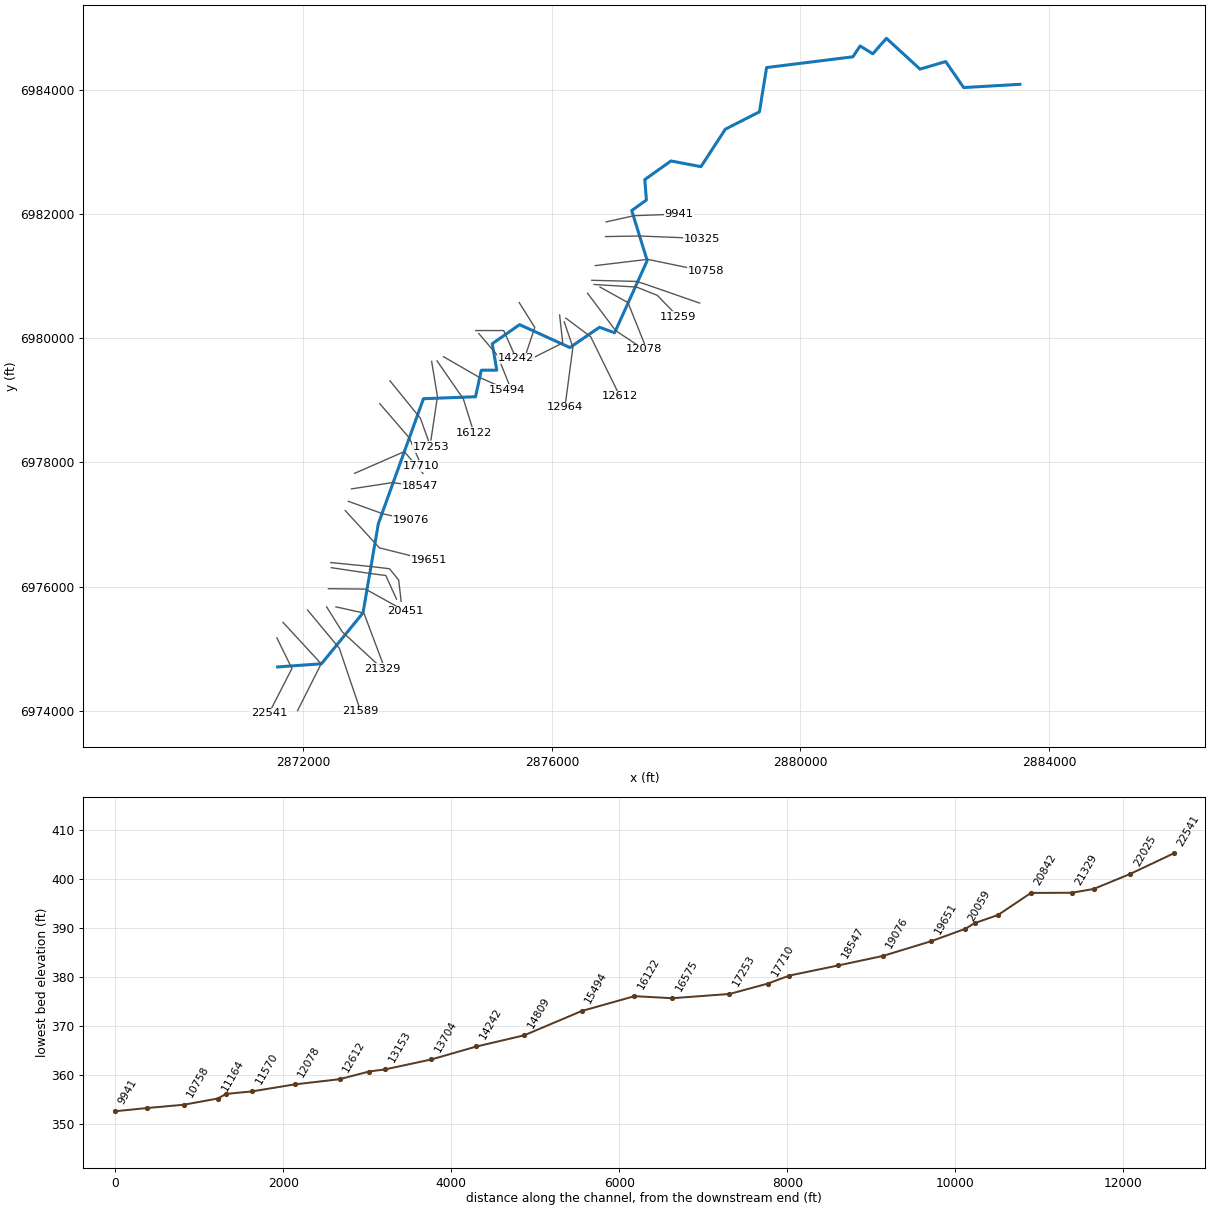
--- ALUM BRANCH.prj (project) ---

Proj Title=ALUM BRANCH Base Level Engineering
Current Plan=p01
Default Exp/Contr=0.3,0.1
English Units
Geom File=g01
Flow File=f01
Plan File=p01
BEGIN DESCRIPTION:
ALUM BRANCH
END DESCRIPTION:

--- ALUM BRANCH.p01 (plan) ---

Plan Title=Multiple Run
Short Identifier=Multiple
Geom File=g01
Flow File=f01
Subcritical Flow
K Sum by GR= 0
Std Step Tol= 0.01
Critical Tol= 0.01
Num of Std Step Trials= 20
Max Error Tol= 0.3
Flow Tol Ratio= 0.001
Split Flow NTrial= 30
Split Flow Tol= 0.02
Split Flow Ratio= 0.02
Log Output Level= 0
Friction Slope Method= 1
Unsteady Friction Slope Method= 2
Unsteady Bridges Friction Slope Method= 1
Parabolic Critical Depth
Global Vel Dist=  1 , 1 , 1
Global Log Level= 0
CheckData=True
Encroach Param= -1, 0, 0, 0
BEGIN DESCRIPTION:
Multiple Run
END DESCRIPTION:

--- ALUM BRANCH.f01 (steady flow) ---

Flow Title=Multiple
Number of Profiles=7
Profile Names=10-year,25-year,50-year,1pct_min,100-year,1pct_plu,500-year
River Rch & RM= ALUM BRANCH,Reach-1,22541
     416     547     651     386     770    1537    1079
River Rch & RM= ALUM BRANCH,Reach-1,21589
     687     929    1128     680    1357    2708    1969
River Rch & RM= ALUM BRANCH,Reach-1,20059
     724     982    1193     720    1437    2867    2088
River Rch & RM= ALUM BRANCH,Reach-1,17710
    1464    2054    2553    1573    3138    6262    4755
River Rch & RM= ALUM BRANCH,Reach-1,9536
    1546    2165    2689    1653    3298    6581    4978
River Rch & RM= ALUM BRANCH,Reach-1,2647
    1682    2364    2941    1812    3616    7215    5480
Boundary for River Rch & Prof#=ALUM BRANCH,Reach-1,1
Up Type=0
Dn Type=3
Dn Slope=0.005
Boundary for River Rch & Prof#=ALUM BRANCH,Reach-1,2
Up Type=0
Dn Type=3
Dn Slope=0.005
Boundary for River Rch & Prof#=ALUM BRANCH,Reach-1,3
Up Type=0
Dn Type=3
Dn Slope=0.005
Boundary for River Rch & Prof#=ALUM BRANCH,Reach-1,4
Up Type=0
Dn Type=3
Dn Slope=0.005
Boundary for River Rch & Prof#=ALUM BRANCH,Reach-1,5
Up Type=0
Dn Type=3
Dn Slope=0.005
Boundary for River Rch & Prof#=ALUM BRANCH,Reach-1,6
Up Type=0
Dn Type=3
Dn Slope=0.005
Boundary for River Rch & Prof#=ALUM BRANCH,Reach-1,7
Up Type=0
Dn Type=3
Dn Slope=0.005

--- ALUM BRANCH.g01 (geometry) ---

Geom Title=Existing Conditions

River Reach=ALUM BRANCH,Reach-1
Reach XY= 30
      2871586.74      6974707.44      2872292.03      6974758.53
      2872960.24      6975578.04      2873207.41      6977014.89
      2873933.22      6979027.27      2874771.70      6979058.68
      2874864.39      6979485.78      2875113.59      6979486.73
      2875040.66      6979913.48      2875481.03      6980219.81
      2876290.19      6979851.04      2876766.78      6980177.90
      2877010.07      6980088.74      2877534.49      6981251.45
      2877285.41      6982057.03      2877521.69      6982227.93
      2877495.53      6982555.56      2877916.51      6982855.90
      2878399.49      6982764.12      2878791.95      6983367.23
      2879340.81      6983647.75      2879455.61      6984360.27
      2880844.57      6984533.24      2880961.09      6984708.22
      2881165.24      6984581.79      2881384.57      6984830.89
      2881924.95      6984335.14      2882338.36      6984456.54
      2882627.83      6984037.99      2883532.81      6984090.58

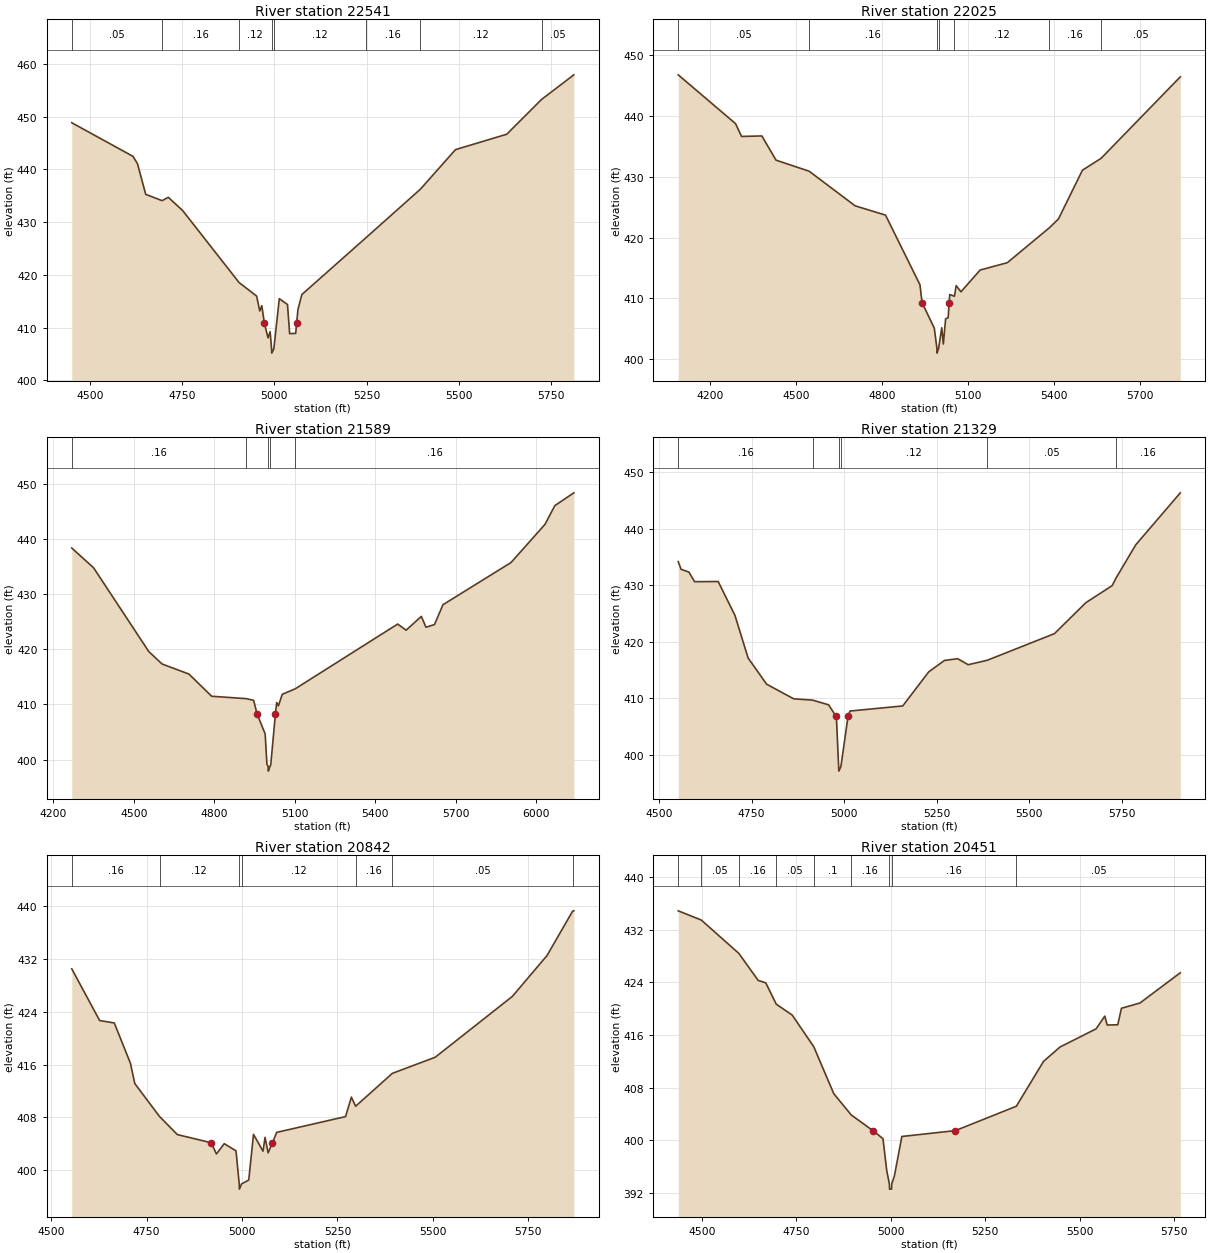
Type RM Length L Ch R = 1,22541,516,516,516
BEGIN DESCRIPTION:
ALUM BRANCH 36.0
END DESCRIPTION:
XS GIS Cut Line= 3
      2871575.02      6975174.97      2871816.16      6974681.87
      2871446.43      6973959.60
#Sta/Elev= 30
  4451.1  448.84  4617.1  442.46  4629.2  441.06  4651.4  435.27  4695.8  434.07
  4712.7  434.70  4751.6  432.19  4904.4  418.55  4952.0  415.98  4960.4  413.17
  4966.0  414.16  4973.0  410.80  4982.9  408.06  4988.5  409.24  4992.5  405.97
  4993.0  405.17  4998.5  405.97  5013.4  415.49  5035.6  414.38  5041.4  408.86
  5057.8  408.92  5060.3  410.80  5063.9  413.42  5074.4  416.27  5247.6  427.01
  5395.8  436.25  5490.7  443.74  5629.6  446.66  5723.9  453.25  5811.4  457.92
#Mann=8,-1,0
  4451.1    0.05       0  4695.8    0.16       0  4904.4    0.12       0
  4992.5    0.07       0  4998.5    0.12       0  5247.6    0.16       0
  5395.8    0.12       0  5723.9    0.05       0
Bank Sta=4973,5060.3
Exp/Cntr=0.3,0.1

Type RM Length L Ch R = 1,22025,436,436,436
BEGIN DESCRIPTION:
Mapping XS e5d85cc6
END DESCRIPTION:
XS GIS Cut Line= 3
      2871672.74      6975425.29      2872287.34      6974758.61
      2871907.11      6974003.37
#Sta/Elev= 30
  4089.1  446.75  4289.2  438.72  4310.1  436.62  4381.0  436.70  4430.4  432.72
  4546.1  430.90  4706.5  425.21  4812.6  423.68  4932.8  412.23  4940.0  409.30
  4982.7  405.11  4991.9  401.79  4992.4  400.99  4997.9  401.79  5008.8  405.17
  5014.4  402.49  5022.3  406.62  5031.1  406.81  5034.7  409.30  5036.7  410.63
  5053.2  410.34  5059.1  412.09  5075.8  411.07  5142.7  414.65  5237.6  415.86
  5384.6  421.61  5416.1  423.05  5499.8  431.07  5565.0  433.02  5841.4  446.42
#Mann=7,-1,0
  4089.1    0.05       0  4546.1    0.16       0  4991.9    0.07       0
  4997.9    0.16       0  5053.2    0.12       0  5384.6    0.16       0
  5565.0    0.05       0
Bank Sta=4940,5034.7
Exp/Cntr=0.3,0.1

Type RM Length L Ch R = 1,21589,260,260,260
BEGIN DESCRIPTION:
Mapping XS dc5c903e
END DESCRIPTION:
XS GIS Cut Line= 3
      2872068.57      6975623.22      2872579.01      6975008.61
      2872922.74      6973993.03
#Sta/Elev= 30
  4268.4  438.37  4349.7  434.79  4555.5  419.59  4604.9  417.34  4705.2  415.51
  4789.8  411.49  4919.4  411.05  4946.1  410.75  4959.5  408.21  4989.1  404.66
  4995.6  399.23  5000.4  398.71  5000.9  397.91  5006.5  398.71  5009.9  399.04
  5027.2  408.21  5032.1  410.34  5038.6  409.76  5052.9  411.84  5101.3  412.84
  5482.9  424.58  5514.5  423.47  5571.1  425.97  5588.4  424.01  5620.1  424.49
  5651.8  428.09  5905.2  435.73  6031.8  442.65  6068.7  446.06  6139.5  448.38
#Mann=5,-1,0
  4268.4    0.16       0  4919.4    0.12       0  5000.4    0.07       0
  5006.5    0.12       0  5101.3    0.16       0
Bank Sta=4959.5,5027.2
Exp/Cntr=0.3,0.1

Type RM Length L Ch R = 1,21329,487,487,487
BEGIN DESCRIPTION:
ALUM BRANCH 35.0
END DESCRIPTION:
XS GIS Cut Line= 3
      2872375.00      6975675.00      2872625.00      6975275.00
      2873275.01      6974674.99
#Sta/Elev= 30
  4552.0  434.20  4559.7  432.84  4580.9  432.35  4596.2  430.65  4659.9  430.68
  4705.3  424.68  4740.7  417.16  4790.8  412.52  4863.9  409.93  4914.9  409.70
  4958.2  408.87  4977.8  406.88  4979.5  406.42  4985.3  397.94  4985.8  397.14
  4991.4  397.94  5010.8  406.88  5016.0  407.77  5158.4  408.67  5228.7  414.70
  5271.2  416.72  5306.9  417.03  5335.3  415.96  5387.1  416.76  5568.3  421.46
  5653.4  426.95  5724.3  429.96  5734.9  431.32  5787.8  437.16  5908.3  446.37
#Mann=6,-1,0
  4552.0    0.16       0  4914.9    0.12       0  4985.3    0.07       0
  4991.4    0.12       0  5387.1    0.05       0  5734.9    0.16       0
Bank Sta=4977.8,5010.8
Exp/Cntr=0.3,0.1

Type RM Length L Ch R = 1,20842,391,391,391
BEGIN DESCRIPTION:
ALUM BRANCH 34.0
END DESCRIPTION:
XS GIS Cut Line= 3
      2872524.97      6975675.01      2872975.00      6975575.00
      2873275.00      6974775.01
#Sta/Elev= 30
  4554.0  430.54  4627.0  422.69  4665.4  422.32  4707.7  416.20  4719.2  413.12
  4783.9  408.13  4830.6  405.38  4919.1  404.14  4933.1  402.44  4953.5  404.00
  4984.3  402.91  4992.7  397.90  4993.2  397.10  4999.0  397.90  5017.7  398.48
  5030.1  405.41  5055.1  402.86  5060.4  404.96  5068.4  402.60  5079.8  404.14
  5090.7  405.71  5271.3  408.11  5286.5  411.06  5297.7  409.68  5393.9  414.67
  5506.3  417.12  5708.3  426.35  5799.1  432.55  5866.4  439.31  5869.4  439.34
#Mann=7,-1,0
  4554.0    0.16       0  4783.9    0.12       0  4992.7    0.07       0
  4999.0    0.12       0  5297.7    0.16       0  5393.9    0.05       0
  5866.4    0.16       0
Bank Sta=4919.1,5079.8
Exp/Cntr=0.3,0.1

Type RM Length L Ch R = 1,20451,278,278,278
BEGIN DESCRIPTION:
Mapping XS 65be04dc
END DESCRIPTION:
XS GIS Cut Line= 3
      2872403.62      6975967.58      2873000.82      6975960.64
      2873639.68      6975606.49
#Sta/Elev= 30
  4437.9  434.89  4499.1  433.48  4598.2  428.42  4649.3  424.32  4669.3  423.95
  4697.2  420.70  4739.3  419.05  4796.3  414.24  4849.3  407.10  4895.3  403.88
  4952.6  401.49  4979.3  400.27  4989.3  395.42  4996.2  393.40  4996.7  392.60
  5002.0  392.60  5002.5  393.40  5009.3  394.54  5029.3  400.60  5170.7  401.49
  5332.1  405.20  5403.9  412.01  5447.4  414.19  5543.0  416.96  5565.9  418.89
  5572.2  417.54  5600.2  417.57  5609.9  420.08  5659.1  420.89  5765.6  425.48
#Mann=9,-1,0
  4437.9    0.16       0  4499.1    0.05       0  4598.2    0.16       0
  4697.2    0.05       0  4796.3     0.1       0  4895.3    0.16       0
  4996.2    0.07       0  5002.5    0.16       0  5332.1    0.05       0
Bank Sta=4952.6,5170.7
Exp/Cntr=0.3,0.1

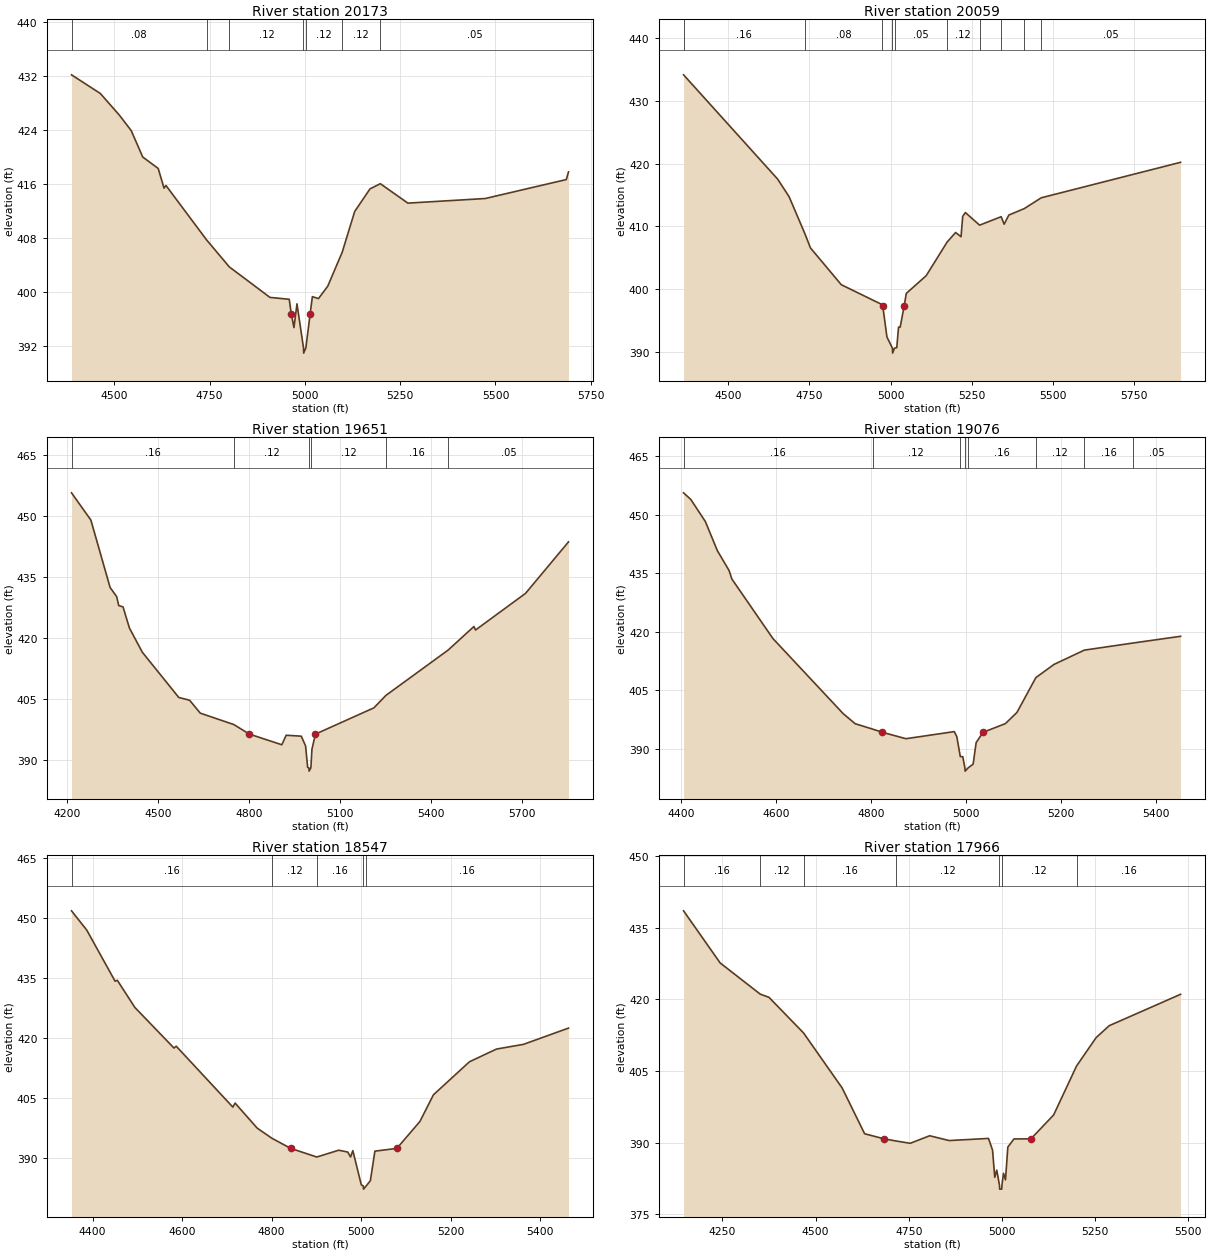
Type RM Length L Ch R = 1,20173,114,114,114
BEGIN DESCRIPTION:
Mapping XS b28b6a3a
END DESCRIPTION:
XS GIS Cut Line= 4
      2872450.13      6976305.95      2873088.15      6976210.46
      2873326.87      6976180.08      2873499.81      6975799.61
#Sta/Elev= 30
  4387.9  432.20  4463.6  429.43  4514.2  426.17  4544.5  423.93  4574.8  420.01
  4615.3  418.32  4630.6  415.40  4635.7  415.79  4742.5  407.71  4801.9  403.72
  4908.5  399.20  4959.1  398.92  4964.2  396.81  4971.4  394.73  4979.3  398.25
  4996.4  391.74  4996.9  390.94  5002.7  391.74  5014.0  396.81  5019.7  399.31
  5035.8  399.03  5060.1  400.87  5097.9  405.89  5130.7  411.94  5171.0  415.30
  5198.0  416.06  5270.2  413.18  5473.0  413.86  5685.7  416.67  5691.6  417.81
#Mann=7,-1,0
  4387.9    0.08       0  4742.5    0.16       0  4801.9    0.12       0
  4996.4    0.07       0  5002.7    0.12       0  5097.9    0.12       0
  5198.0    0.05       0
Bank Sta=4964.2,5014
Exp/Cntr=0.3,0.1

Type RM Length L Ch R = 1,20059,408,408,408
BEGIN DESCRIPTION:
Mapping XS 27ed3bc5
END DESCRIPTION:
XS GIS Cut Line= 5
      2872441.41      6976388.42      2873101.17      6976323.31
      2873387.63      6976288.59      2873535.20      6976106.30
      2873574.27      6975763.37
#Sta/Elev= 30
  4362.2  434.17  4651.9  417.54  4687.4  414.72  4736.8  408.72  4753.0  406.56
  4848.1  400.68  4974.3  397.49  4975.8  397.33  4988.8  392.33  5005.7  390.56
  5006.2  389.76  5012.1  390.56  5019.0  390.63  5024.6  393.91  5029.6  393.91
  5042.0  397.33  5048.4  399.29  5109.6  402.11  5174.2  407.48  5200.3  409.01
  5217.1  408.34  5222.2  411.59  5230.5  412.19  5274.3  410.18  5340.7  411.53
  5349.9  410.33  5364.3  411.79  5411.8  412.82  5464.3  414.55  5893.4  420.21
#Mann=10,-1,0
  4362.2    0.16       0  4736.8    0.08       0  4974.3    0.05       0
  5005.7    0.04       0  5012.1    0.05       0  5174.2    0.12       0
  5274.3    0.16       0  5340.7    0.05       0  5411.8    0.16       0
  5464.3    0.05       0
Bank Sta=4975.8,5042
Exp/Cntr=0.3,0.1

Type RM Length L Ch R = 1,19651,575,575,575
BEGIN DESCRIPTION:
ALUM BRANCH 32.0
END DESCRIPTION:
XS GIS Cut Line= 3
      2872675.01      6977224.99      2873225.00      6976625.00
      2874024.96      6976425.01
#Sta/Elev= 30
  4215.9  455.70  4279.7  449.00  4343.2  432.40  4364.8  430.15  4371.6  427.96
  4385.8  427.63  4406.7  422.46  4449.3  416.48  4569.5  405.35  4605.3  404.66
  4640.4  401.49  4751.0  398.68  4802.3  396.33  4909.3  393.71  4923.5  396.05
  4973.4  395.82  4987.6  393.42  4994.4  388.15  4998.6  388.02  4999.1  387.22
  5005.0  388.02  5008.5  392.59  5020.1  396.33  5212.8  402.79  5252.5  405.86
  5457.8  417.02  5542.6  422.81  5547.8  421.94  5712.7  430.96  5854.4  443.63
#Mann=6,-1,0
  4215.9    0.16       0  4751.0    0.12       0  4998.6    0.07       0
  5005.0    0.12       0  5252.5    0.16       0  5457.8    0.05       0
Bank Sta=4802.3,5020.1
Exp/Cntr=0.3,0.1

Type RM Length L Ch R = 1,19076,529,529,529
BEGIN DESCRIPTION:
ALUM BRANCH 31.0
END DESCRIPTION:
XS GIS Cut Line= 3
      2872724.96      6977375.01      2873275.00      6977175.00
      2873725.05      6977074.99
#Sta/Elev= 30
  4405.2  455.63  4420.5  453.92  4451.1  448.26  4476.4  440.78  4501.0  435.70
  4507.0  433.50  4593.4  418.23  4741.1  398.99  4766.4  396.39  4803.2  395.00
  4823.9  394.18  4873.4  392.54  4975.2  394.36  4980.5  393.05  4986.3  388.99
  4987.8  387.94  4993.0  387.94  4997.5  385.02  4998.0  384.22  5004.0  385.02
  5014.8  386.01  5021.2  391.55  5035.8  394.18  5082.7  396.41  5107.0  399.27
  5146.9  408.22  5185.1  411.60  5248.9  415.27  5350.9  417.08  5451.5  418.82
#Mann=8,-1,0
  4405.2    0.16       0  4803.2    0.12       0  4986.3    0.16       0
  4997.5    0.07       0  5004.0    0.16       0  5146.9    0.12       0
  5248.9    0.16       0  5350.9    0.05       0
Bank Sta=4823.9,5035.8
Exp/Cntr=0.3,0.1

Type RM Length L Ch R = 1,18547,581,581,581
BEGIN DESCRIPTION:
ALUM BRANCH 30.0
END DESCRIPTION:
XS GIS Cut Line= 3
      2872775.01      6977575.00      2873425.00      6977675.00
      2873875.00      6977625.00
#Sta/Elev= 30
  4352.9  451.80  4387.0  446.98  4450.3  434.22  4455.3  434.44  4494.5  427.66
  4581.8  417.53  4586.9  417.98  4713.3  402.78  4718.4  403.78  4767.7  397.53
  4801.1  394.96  4842.6  392.47  4900.9  390.31  4949.8  392.01  4970.1  391.55
  4976.4  390.32  4981.4  391.91  5000.4  383.35  5004.8  383.09  5005.3  382.29
  5011.3  383.09  5020.6  384.39  5030.7  391.77  5079.8  392.47  5131.3  399.19
  5161.5  405.85  5242.0  414.10  5302.3  417.27  5362.7  418.45  5463.3  422.51
#Mann=5,-1,0
  4352.9    0.16       0  4801.1    0.12       0  4900.9    0.16       0
  5004.8    0.07       0  5011.3    0.16       0
Bank Sta=4842.6,5079.8
Exp/Cntr=0.3,0.1

Type RM Length L Ch R = 1,17966,256,256,256
BEGIN DESCRIPTION:
ALUM BRANCH 29.0
END DESCRIPTION:
XS GIS Cut Line= 3
      2872825.03      6977825.01      2873625.00      6978175.00
      2873925.03      6977824.97
#Sta/Elev= 30
  4145.6  438.57  4243.8  427.65  4351.6  421.10  4374.8  420.44  4467.6  412.98
  4571.3  401.44  4631.7  391.84  4683.9  390.77  4715.4  390.33  4754.1  389.84
  4806.3  391.42  4858.6  390.41  4964.2  390.86  4975.1  388.40  4981.0  382.71
  4986.4  384.21  4993.7  381.03  4994.2  380.23  4999.7  380.23  5000.2  381.03
  5004.4  383.56  5009.8  382.18  5016.1  389.04  5032.5  390.75  5078.1  390.77
  5139.0  395.77  5200.6  406.04  5253.1  411.99  5288.2  414.49  5479.8  421.07
#Mann=7,-1,0
  4145.6    0.16       0  4351.6    0.12       0  4467.6    0.16       0
  4715.4    0.12       0  4993.7    0.07       0  5000.2    0.12       0
  5200.6    0.16       0
Bank Sta=4683.9,5078.1
Exp/Cntr=0.3,0.1

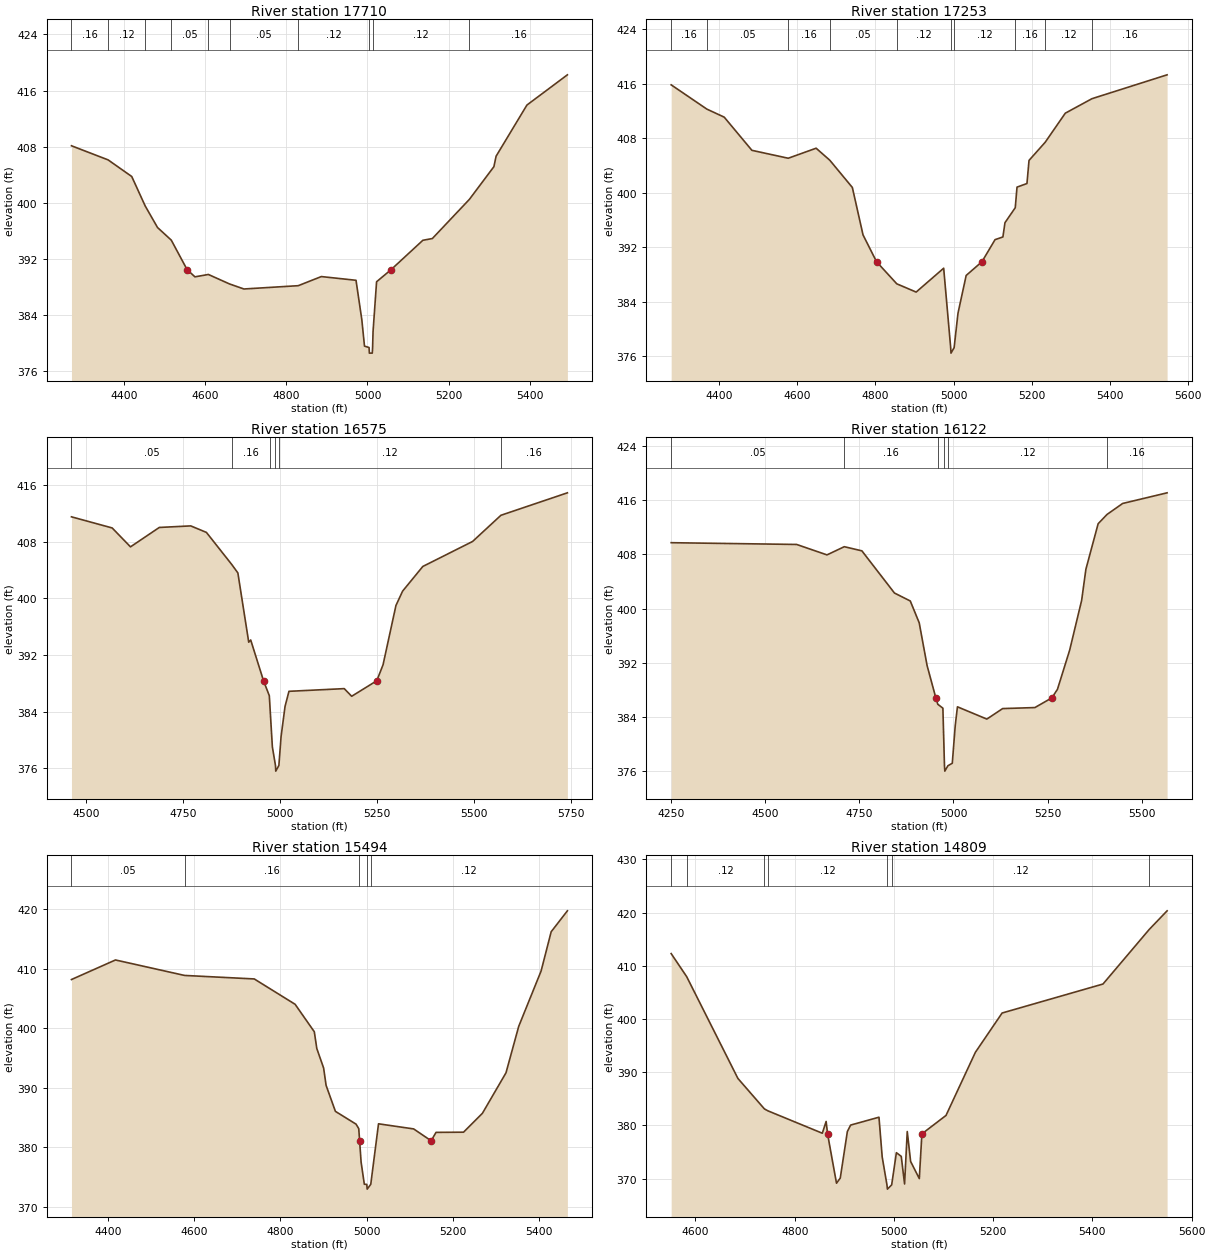
Type RM Length L Ch R = 1,17710,457,457,457
BEGIN DESCRIPTION:
ALUM BRANCH 28.0
END DESCRIPTION:
XS GIS Cut Line= 3
      2873229.22      6978948.21      2873705.84      6978395.68
      2873901.94      6977943.46
#Sta/Elev= 30
  4270.3  408.14  4360.6  406.13  4418.9  403.76  4452.1  399.56  4482.5  396.49
  4516.4  394.69  4555.4  390.49  4574.7  389.46  4607.8  389.80  4659.9  388.45
  4695.4  387.73  4829.3  388.20  4886.3  389.50  4971.8  388.97  4986.1  383.36
  4992.7  379.59  5004.0  379.39  5004.7  378.59  5011.9  378.59  5012.7  379.39
  5013.8  381.67  5022.5  388.76  5058.3  390.49  5136.6  394.67  5160.0  394.92
  5251.4  400.51  5311.7  405.16  5317.2  406.66  5393.1  413.94  5492.9  418.25
#Mann=10,-1,0
  4270.3    0.16       0  4360.6    0.12       0  4452.1    0.16       0
  4516.4    0.05       0  4607.8    0.16       0  4659.9    0.05       0
  4829.3    0.12       0  5004.0    0.07       0  5012.7    0.12       0
  5251.4    0.16       0
Bank Sta=4555.4,5058.3
Exp/Cntr=0.3,0.1

Type RM Length L Ch R = 1,17253,678,678,678
BEGIN DESCRIPTION:
ALUM BRANCH 27.0
END DESCRIPTION:
XS GIS Cut Line= 3
      2873394.47      6979315.25      2873884.28      6978711.85
      2874050.01      6978249.96
#Sta/Elev= 30
  4278.2  415.84  4369.4  412.28  4413.8  411.10  4484.6  406.23  4577.5  405.07
  4648.8  406.54  4683.7  404.78  4741.4  400.78  4768.7  393.82  4803.3  389.88
  4855.0  386.64  4904.5  385.43  4974.9  388.93  4992.8  377.27  4993.6  376.47
  5001.6  377.27  5011.5  382.33  5032.4  387.87  5072.7  389.88  5106.2  393.12
  5126.3  393.52  5131.6  395.61  5157.9  397.81  5162.4  400.83  5187.8  401.36
  5193.1  404.75  5234.5  407.42  5285.8  411.68  5354.1  413.81  5546.1  417.31
#Mann=10,-1,0
  4278.2    0.16       0  4369.4    0.05       0  4577.5    0.16       0
  4683.7    0.05       0  4855.0    0.12       0  4992.8    0.07       0
  5001.6    0.12       0  5157.9    0.16       0  5234.5    0.12       0
  5354.1    0.16       0
Bank Sta=4803.3,5072.7
Exp/Cntr=0.3,0.1

Type RM Length L Ch R = 1,16575,453,453,453
BEGIN DESCRIPTION:
Mapping XS 3a1ea6c0
END DESCRIPTION:
XS GIS Cut Line= 3
      2874064.83      6979628.55      2874158.59      6979062.54
      2874054.42      6978364.59
#Sta/Elev= 30
  4461.5  411.52  4566.5  409.95  4613.8  407.28  4688.1  410.02  4769.2  410.24
  4809.7  409.32  4875.3  404.77  4890.8  403.60  4918.8  393.82  4923.9  394.13
  4957.0  388.37  4971.9  386.26  4974.1  384.25  4979.8  379.03  4987.8  376.41
  4988.6  375.61  4996.6  376.41  5002.3  380.51  5012.5  384.75  5022.6  386.88
  5165.2  387.26  5184.4  386.18  5249.1  388.37  5265.3  390.62  5298.6  399.00
  5315.8  401.03  5367.9  404.51  5496.3  408.04  5569.5  411.74  5740.9  414.91
#Mann=6,-1,0
  4461.5    0.05       0  4875.3    0.16       0  4974.1    0.12       0
  4987.8    0.07       0  4996.6    0.12       0  5569.5    0.16       0
Bank Sta=4957,5249.1
Exp/Cntr=0.3,0.1

Type RM Length L Ch R = 1,16122,628,628,628
BEGIN DESCRIPTION:
ALUM BRANCH 26.0
END DESCRIPTION:
XS GIS Cut Line= 3
      2874152.15      6979635.96      2874575.00      6979025.00
      2874745.44      6978478.59
#Sta/Elev= 30
  4251.3  409.73  4584.1  409.47  4664.6  407.93  4710.5  409.14  4757.1  408.53
  4843.6  402.30  4885.5  401.13  4909.2  397.91  4930.1  391.60  4953.3  386.83
  4958.4  385.89  4972.0  385.31  4976.2  376.82  4977.1  376.02  4985.4  376.82
  4996.9  377.18  5004.8  382.77  5010.6  385.51  5088.6  383.70  5130.5  385.25
  5216.1  385.40  5260.9  386.83  5275.8  388.08  5308.3  393.88  5340.0  401.21
  5351.3  405.81  5383.8  412.53  5407.4  413.90  5448.8  415.52  5566.7  417.09
#Mann=6,-1,0
  4251.3    0.05       0  4710.5    0.16       0  4958.4    0.12       0
  4976.2    0.07       0  4985.4    0.12       0  5407.4    0.16       0
Bank Sta=4953.3,5260.9
Exp/Cntr=0.3,0.1

Type RM Length L Ch R = 1,15494,685,685,685
BEGIN DESCRIPTION:
ALUM BRANCH 25.0
END DESCRIPTION:
XS GIS Cut Line= 3
      2874256.29      6979703.69      2874825.00      6979375.00
      2875275.00      6979175.00
#Sta/Elev= 30
  4315.8  408.22  4417.8  411.51  4577.9  408.91  4739.4  408.32  4834.1  404.06
  4878.6  399.44  4884.4  396.62  4900.2  393.34  4905.9  390.43  4927.5  386.06
  4975.4  383.91  4981.6  383.15  4983.1  381.64  4983.6  381.13  4987.0  377.55
  4994.5  373.81  5000.2  373.79  5001.1  372.99  5009.4  373.79  5027.4  383.97
  5108.8  383.11  5149.3  381.12  5160.7  382.53  5224.4  382.56  5268.1  385.73
  5322.8  392.54  5352.3  400.35  5404.2  409.66  5427.5  416.25  5465.1  419.77
#Mann=5,-1,0
  4315.8    0.05       0  4577.9    0.16       0  4983.1    0.12       0
  5000.2    0.07       0  5009.4    0.12       0
Bank Sta=4983.6,5149.3
Exp/Cntr=0.3,0.1

Type RM Length L Ch R = 1,14809,567,567,567
BEGIN DESCRIPTION:
ALUM BRANCH 24.0
END DESCRIPTION:
XS GIS Cut Line= 3
      2874824.97      6980075.03      2875125.00      6979725.00
      2875324.99      6979225.03
#Sta/Elev= 30
  4551.0  412.30  4582.3  407.96  4685.5  388.83  4738.8  383.11  4746.2  382.73
  4855.6  378.53  4863.3  380.74  4866.2  378.41  4884.2  369.13  4891.8  370.10
  4906.1  378.85  4912.7  380.06  4969.8  381.54  4976.3  374.07  4985.9  368.82
  4986.8  368.02  4995.4  368.82  5004.9  374.87  5014.7  374.18  5021.4  368.99
  5026.8  378.85  5033.6  373.22  5051.1  370.00  5056.3  378.41  5104.9  381.87
  5164.1  393.74  5218.0  401.13  5421.3  406.58  5514.4  416.83  5550.5  420.34
#Mann=7,-1,0
  4551.0    0.16       0  4582.3    0.12       0  4738.8    0.16       0
  4746.2    0.12       0  4985.9    0.07       0  4995.4    0.12       0
  5514.4    0.16       0
Bank Sta=4866.2,5056.3
Exp/Cntr=0.3,0.1

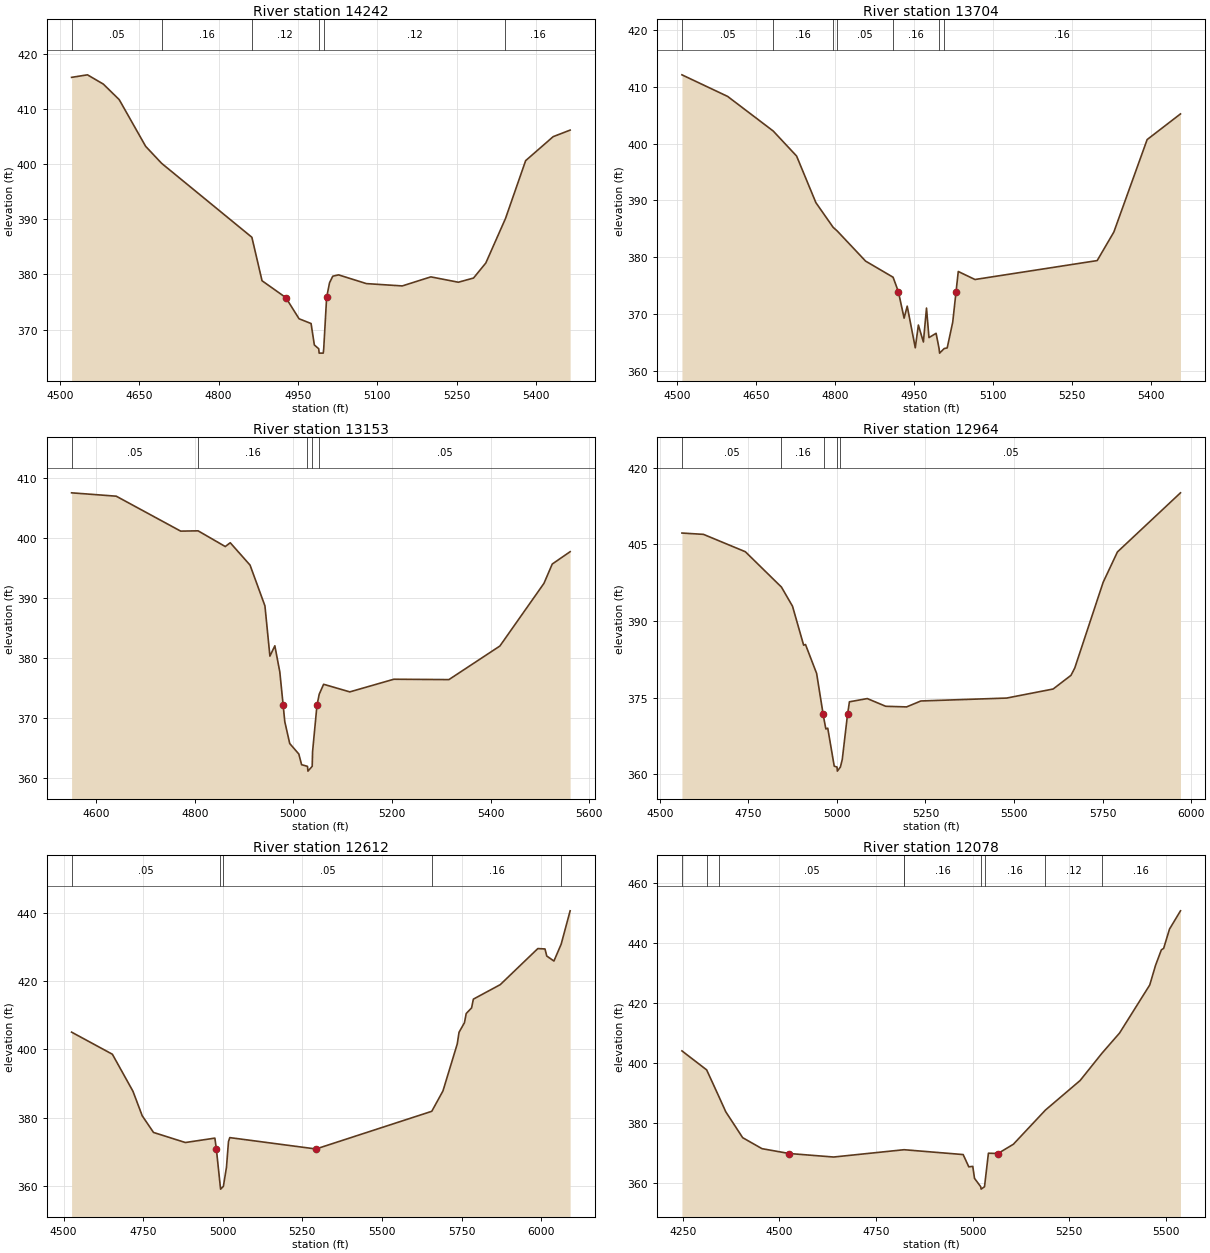
Type RM Length L Ch R = 1,14242,538,538,538
BEGIN DESCRIPTION:
ALUM BRANCH 23.0
END DESCRIPTION:
XS GIS Cut Line= 3
      2874775.04      6980125.00      2875225.00      6980125.00
      2875425.00      6979675.00
#Sta/Elev= 30
  4522.2  415.69  4552.2  416.15  4582.2  414.47  4612.2  411.66  4662.2  403.20
  4692.4  400.12  4863.0  386.73  4882.2  378.86  4927.1  375.81  4952.2  371.97
  4974.9  371.11  4981.1  367.22  4989.3  366.55  4990.2  365.75  4997.9  365.75
  4998.8  366.55  5004.3  375.83  5009.8  378.49  5015.9  379.68  5026.9  379.92
  5079.5  378.34  5147.3  377.92  5201.3  379.56  5253.3  378.59  5282.0  379.35
  5305.2  382.07  5342.4  390.13  5380.5  400.61  5432.5  404.95  5464.6  406.14
#Mann=6,-1,0
  4522.2    0.05       0  4692.4    0.16       0  4863.0    0.12       0
  4989.3    0.07       0  4998.8    0.12       0  5342.4    0.16       0
Bank Sta=4927.1,5004.3
Exp/Cntr=0.3,0.1

Type RM Length L Ch R = 1,13704,551,551,551
BEGIN DESCRIPTION:
ALUM BRANCH 22.0
END DESCRIPTION:
XS GIS Cut Line= 3
      2875474.98      6980575.02      2875725.00      6980175.00
      2875574.99      6979724.97
#Sta/Elev= 30
  4509.9  412.09  4596.6  408.29  4683.1  402.20  4727.5  397.79  4764.1  389.59
  4796.8  385.25  4804.7  384.59  4858.4  379.30  4910.6  376.46  4920.6  373.93
  4931.5  369.26  4937.4  371.37  4952.7  364.04  4958.6  368.04  4968.1  365.06
  4974.0  371.03  4978.7  365.83  4992.2  366.59  4997.9  363.90  4998.9  363.10
  5007.5  363.90  5013.3  364.02  5023.8  368.56  5030.1  373.93  5034.3  377.47
  5066.0  376.06  5297.9  379.39  5329.5  384.41  5392.7  400.69  5456.0  405.21
#Mann=7,-1,0
  4509.9    0.05       0  4683.1    0.16       0  4796.8    0.12       0
  4804.7    0.05       0  4910.6    0.16       0  4997.9    0.07       0
  5007.5    0.16       0
Bank Sta=4920.6,5030.1
Exp/Cntr=0.3,0.1

Type RM Length L Ch R = 1,13153,189,189,189
BEGIN DESCRIPTION:
ALUM BRANCH 21.0
END DESCRIPTION:
XS GIS Cut Line= 3
      2876125.00      6980375.01      2876175.00      6979925.00
      2875674.99      6979675.00
#Sta/Elev= 30
  4549.8  407.50  4640.4  406.94  4771.2  401.11  4806.5  401.16  4861.7  398.54
  4871.8  399.17  4912.0  395.44  4942.2  388.64  4952.3  380.26  4962.3  381.98
  4972.4  377.61  4979.2  372.05  4982.5  369.32  4992.5  365.68  5011.0  363.92
  5016.6  362.14  5028.5  361.87  5029.5  361.07  5038.1  361.87  5038.9  364.35
  5047.8  372.05  5052.4  373.91  5061.3  375.56  5114.4  374.29  5203.8  376.40
  5315.6  376.34  5419.0  381.94  5508.5  392.40  5525.3  395.62  5561.6  397.68
#Mann=5,-1,0
  4549.8    0.05       0  4806.5    0.16       0  5028.5    0.07       0
  5038.1    0.16       0  5052.4    0.05       0
Bank Sta=4979.2,5047.8
Exp/Cntr=0.3,0.1

Type RM Length L Ch R = 1,12964,352,352,352
BEGIN DESCRIPTION:
Mapping XS c8d37e4a
END DESCRIPTION:
XS GIS Cut Line= 3
      2876199.44      6980264.53      2876338.32      6979854.83
      2876210.18      6978888.58
#Sta/Elev= 30
  4562.8  407.24  4623.6  406.98  4741.8  403.58  4843.7  396.66  4874.9  392.92
  4906.3  385.30  4911.6  385.42  4943.0  379.76  4961.4  371.77  4965.1  370.33
  4969.1  368.89  4974.4  369.05  4992.7  361.61  5000.5  361.44  5001.5  360.64
  5010.1  361.44  5015.4  362.94  5030.3  371.77  5035.6  374.21  5086.0  374.84
  5138.1  373.33  5197.0  373.21  5237.3  374.37  5479.4  374.94  5610.6  376.71
  5661.0  379.39  5671.7  380.83  5751.8  397.60  5792.1  403.54  5970.1  415.11
#Mann=5,-1,0
  4562.8    0.05       0  4843.7    0.16       0  4965.1    0.05       0
  5000.5    0.03       0  5010.1    0.05       0
Bank Sta=4961.4,5030.3
Exp/Cntr=0.3,0.1

Type RM Length L Ch R = 1,12612,534,534,534
BEGIN DESCRIPTION:
ALUM BRANCH 20.0
END DESCRIPTION:
XS GIS Cut Line= 3
      2876225.03      6980324.98      2876625.00      6980025.00
      2877094.43      6979068.33
#Sta/Elev= 30
  4525.4  405.02  4653.5  398.55  4718.1  387.72  4747.2  380.54  4782.7  375.66
  4882.7  372.71  4975.4  374.00  4980.0  370.82  4992.4  359.87  4993.4  359.07
  5002.0  359.87  5011.8  365.47  5018.1  372.98  5022.2  374.15  5292.8  370.82
  5656.5  381.85  5691.6  387.81  5736.6  401.60  5742.1  404.98  5759.1  407.78
  5764.6  410.47  5781.5  412.11  5787.1  414.68  5871.5  418.92  5989.5  429.48
  6012.0  429.37  6017.6  427.30  6040.1  425.84  6062.8  430.76  6091.0  440.53
#Mann=5,-1,0
  4525.4    0.05       0  4992.4    0.03       0  5002.0    0.05       0
  5656.5    0.16       0  6062.8    0.05       0
Bank Sta=4980,5292.8
Exp/Cntr=0.3,0.1

Type RM Length L Ch R = 1,12078,508,508,508
BEGIN DESCRIPTION:
ALUM BRANCH 19.0
END DESCRIPTION:
XS GIS Cut Line= 3
      2876575.01      6980724.99      2877025.00      6980125.00
      2877474.99      6979825.01
#Sta/Elev= 30
  4247.7  404.00  4311.7  397.68  4343.0  388.92  4361.2  383.74  4405.0  375.12
  4455.0  371.47  4525.3  369.86  4640.4  368.69  4822.7  371.12  4823.8  371.11
  4975.8  369.51  4990.4  365.43  5000.7  365.58  5005.2  361.60  5021.3  358.81
  5022.3  358.01  5031.1  358.81  5041.2  369.96  5065.9  369.86  5105.8  372.94
  5188.8  384.31  5278.6  394.14  5335.3  403.24  5380.8  409.95  5458.9  425.93
  5473.9  432.46  5488.9  437.60  5494.9  438.11  5510.0  444.51  5538.5  450.60
#Mann=9,-1,0
  4247.7    0.05       0  4311.7     0.1       0  4343.0    0.05       0
  4822.7    0.07       0  4823.8    0.16       0  5021.3    0.07       0
  5031.1    0.16       0  5188.8    0.12       0  5335.3    0.16       0
Bank Sta=4525.3,5065.9
Exp/Cntr=0.3,0.1

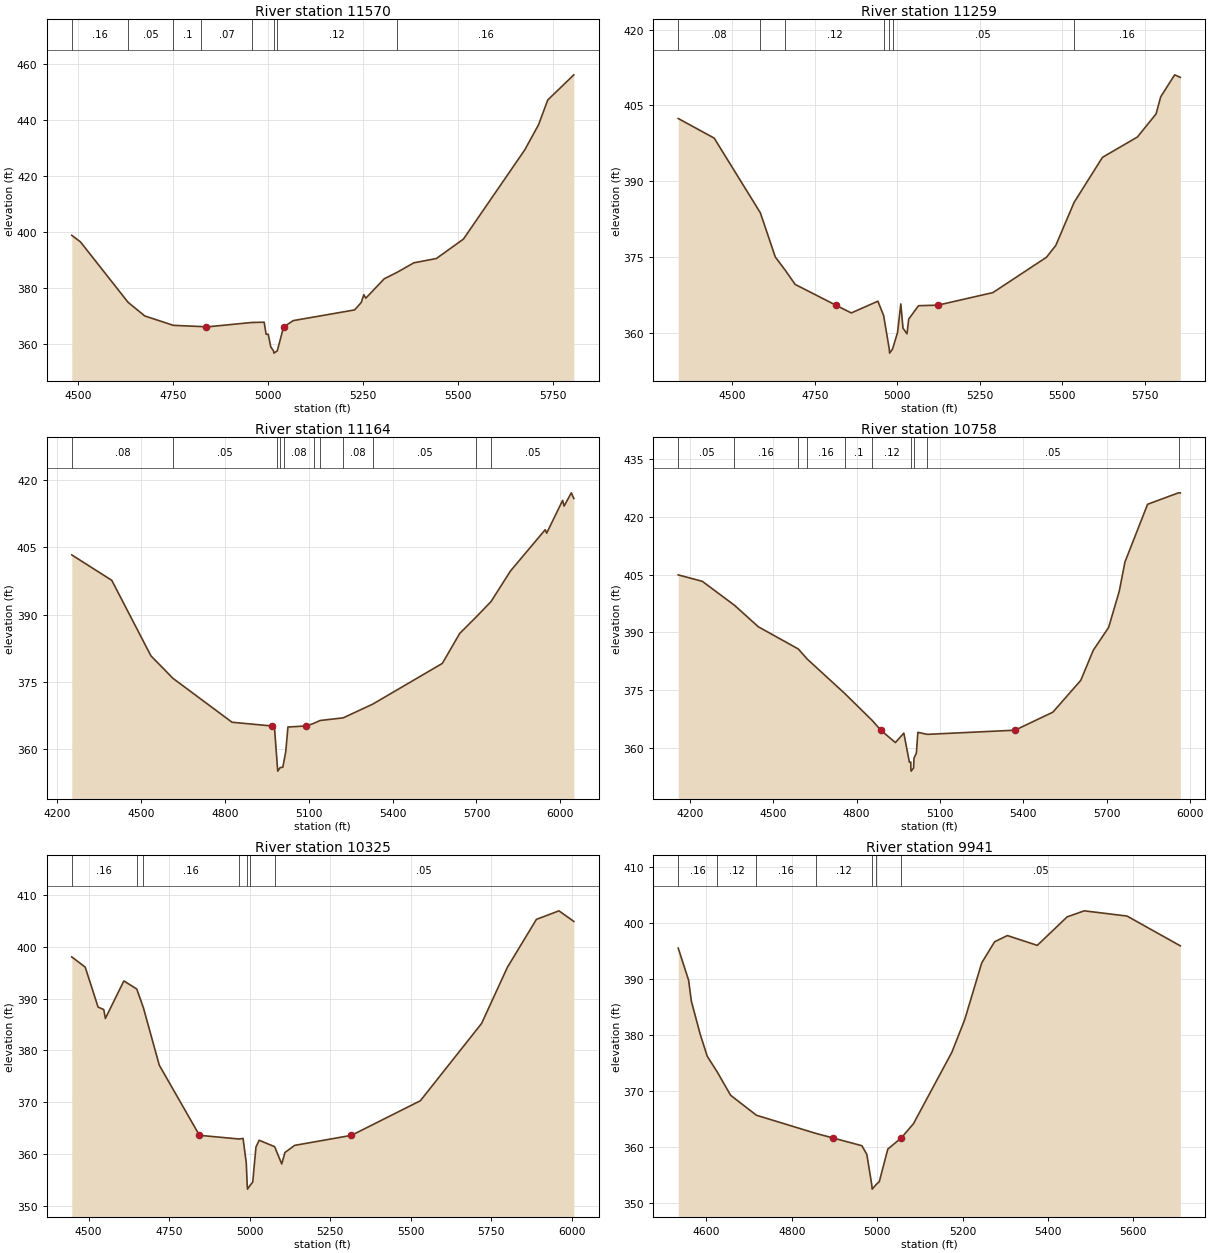
Type RM Length L Ch R = 1,11570,311,311,311
BEGIN DESCRIPTION:
ALUM BRANCH 18.0
END DESCRIPTION:
XS GIS Cut Line= 3
      2876774.97      6980825.01      2877225.00      6980575.00
      2877525.00      6979824.99
#Sta/Elev= 30
  4482.4  398.74  4505.3  396.39  4630.7  374.77  4674.6  369.89  4750.1  366.52
  4824.0  366.09  4836.4  365.94  4956.9  367.55  4989.2  367.64  4994.4  363.34
  4999.9  363.34  5006.6  358.81  5013.9  357.38  5014.8  356.58  5023.7  357.38
  5040.4  365.94  5065.9  368.22  5227.4  372.04  5244.9  374.68  5251.7  377.48
  5257.0  376.25  5305.5  383.18  5339.5  385.50  5383.6  388.90  5442.8  390.43
  5514.2  397.39  5675.7  429.31  5712.1  438.33  5736.3  447.18  5805.0  456.17
#Mann=8,-1,0
  4482.4    0.16       0  4630.7    0.05       0  4750.1     0.1       0
  4824.0    0.07       0  4956.9    0.12       0  5013.9    0.07       0
  5023.7    0.12       0  5339.5    0.16       0
Bank Sta=4836.4,5040.4
Exp/Cntr=0.3,0.1

Type RM Length L Ch R = 1,11259,95,95,95
BEGIN DESCRIPTION:
Mapping XS f80dbb53
END DESCRIPTION:
XS GIS Cut Line= 4
      2876681.05      6980866.64      2877363.32      6980824.97
      2877696.65      6980692.16      2878031.29      6980347.15
#Sta/Elev= 30
  4335.6  402.42  4444.6  398.55  4584.7  383.79  4630.1  375.05  4660.6  372.41
  4690.2  369.64  4813.5  365.54  4860.5  364.00  4941.2  366.32  4958.7  363.48
  4975.8  356.86  4976.8  356.06  4985.6  356.86  5000.8  360.13  5010.8  365.78
  5017.5  360.98  5029.5  359.88  5034.8  362.80  5064.5  365.43  5123.5  365.54
  5290.1  368.02  5452.6  375.00  5480.9  377.34  5536.4  385.84  5622.4  394.74
  5728.4  398.76  5785.0  403.32  5799.1  406.70  5841.5  411.05  5858.6  410.55
#Mann=7,-1,0
  4335.6    0.08       0  4584.7    0.16       0  4660.6    0.12       0
  4958.7    0.05       0  4975.8    0.04       0  4985.6    0.05       0
  5536.4    0.16       0
Bank Sta=4813.5,5123.5
Exp/Cntr=0.3,0.1

Type RM Length L Ch R = 1,11164,406,406,406
BEGIN DESCRIPTION:
Mapping XS 085df377
END DESCRIPTION:
XS GIS Cut Line= 4
      2876641.99      6980934.34      2877363.32      6980916.12
      2877480.51      6980879.66      2878378.93      6980567.16
#Sta/Elev= 30
  4252.8  403.31  4395.9  397.64  4535.9  380.82  4614.6  375.81  4826.0  366.02
  4967.2  365.20  4977.9  364.72  4988.4  355.93  4989.4  355.13  4998.3  355.93
  5007.5  355.99  5013.0  357.81  5018.0  359.47  5025.9  364.96  5092.2  365.20
  5117.7  365.76  5140.8  366.41  5223.5  367.00  5329.2  370.06  5578.0  379.13
  5640.2  385.82  5698.9  389.47  5752.0  392.90  5821.5  399.71  5946.0  408.93
  5951.2  408.16  6008.2  415.46  6013.4  414.18  6039.3  417.14  6048.3  415.86
#Mann=11,-1,0
  4252.8    0.08       0  4614.6    0.05       0  4988.4    0.04       0
  4998.3    0.05       0  5013.0    0.08       0  5117.7    0.12       0
  5140.8    0.05       0  5223.5    0.08       0  5329.2    0.05       0
  5698.9    0.08       0  5752.0    0.05       0
Bank Sta=4967.2,5092.2
Exp/Cntr=0.3,0.1

Type RM Length L Ch R = 1,10758,433,433,433
BEGIN DESCRIPTION:
Mapping XS 95d3a130
END DESCRIPTION:
XS GIS Cut Line= 3
      2876698.76      6981170.81      2877542.49      6981271.50
      2878480.02      6981077.05
#Sta/Elev= 30
  4158.0  404.92  4244.8  403.24  4360.2  397.03  4446.3  391.42  4590.2  385.64
  4621.7  383.06  4756.8  374.10  4856.3  367.04  4887.2  364.51  4939.7  361.29
  4970.0  363.76  4990.1  356.17  4995.1  356.21  4995.2  354.66  4996.2  353.86
  5005.1  354.66  5006.5  357.20  5015.2  358.55  5020.5  363.95  5054.4  363.43
  5370.2  364.51  5506.5  369.20  5606.8  377.47  5651.9  385.30  5707.2  391.25
  5745.6  400.71  5766.0  408.28  5847.4  423.29  5958.7  426.27  5965.2  426.26
#Mann=10,-1,0
  4158.0    0.05       0  4360.2    0.16       0  4590.2    0.12       0
  4621.7    0.16       0  4756.8     0.1       0  4856.3    0.12       0
  4995.2    0.07       0  5005.1    0.12       0  5054.4    0.05       0
  5958.7    0.16       0
Bank Sta=4887.2,5370.2
Exp/Cntr=0.3,0.1

Type RM Length L Ch R = 1,10325,384,384,384
BEGIN DESCRIPTION:
ALUM BRANCH 16.0
END DESCRIPTION:
XS GIS Cut Line= 3
      2876863.32      6981638.34      2877415.65      6981647.35
      2878421.14      6981607.14
#Sta/Elev= 30
  4447.6  398.04  4489.3  396.07  4529.3  388.35  4546.9  387.88  4551.9  386.15
  4609.3  393.40  4649.4  391.84  4669.9  388.24  4719.3  377.13  4844.0  363.58
  4967.3  362.87  4979.4  362.98  4989.4  358.22  4992.2  353.99  4993.2  353.19
  5002.1  353.99  5009.4  354.54  5019.4  361.31  5029.4  362.63  5077.4  361.39
  5099.4  358.05  5109.4  360.26  5139.5  361.64  5316.0  363.58  5529.8  370.26
  5719.9  385.19  5800.0  396.03  5890.1  405.29  5960.1  406.94  6006.3  404.89
#Mann=7,-1,0
  4447.6    0.16       0  4649.4    0.12       0  4669.9    0.16       0
  4967.3    0.12       0  4992.2    0.07       0  5002.1    0.12       0
  5077.4    0.05       0
Bank Sta=4844,5316
Exp/Cntr=0.3,0.1

Type RM Length L Ch R = 1,9941,405,405,405
BEGIN DESCRIPTION:
ALUM BRANCH 15.0
END DESCRIPTION:
XS GIS Cut Line= 3
      2876874.99      6981875.00      2877325.00      6981975.00
      2878039.87      6982000.23
#Sta/Elev= 30
  4533.8  395.50  4558.1  389.78  4564.5  386.06  4585.0  380.22  4601.7  376.23
  4624.7  373.48  4656.7  369.25  4717.1  365.70  4855.7  362.48  4895.3  361.67
  4964.1  360.27  4975.6  358.74  4987.2  353.33  4988.2  352.53  4997.2  353.33
  5004.8  353.85  5024.8  359.67  5055.1  361.58  5056.5  361.67  5084.8  364.18
  5174.9  376.94  5204.9  382.73  5244.9  392.88  5275.0  396.63  5305.0  397.74
  5375.0  395.99  5445.1  401.08  5485.1  402.15  5585.2  401.22  5710.1  395.91
#Mann=7,-1,0
  4533.8    0.16       0  4624.7    0.12       0  4717.1    0.16       0
  4855.7    0.12       0  4987.2    0.07       0  4997.2    0.12       0
  5055.1    0.05       0
Bank Sta=4895.3,5056.5
Exp/Cntr=0.3,0.1