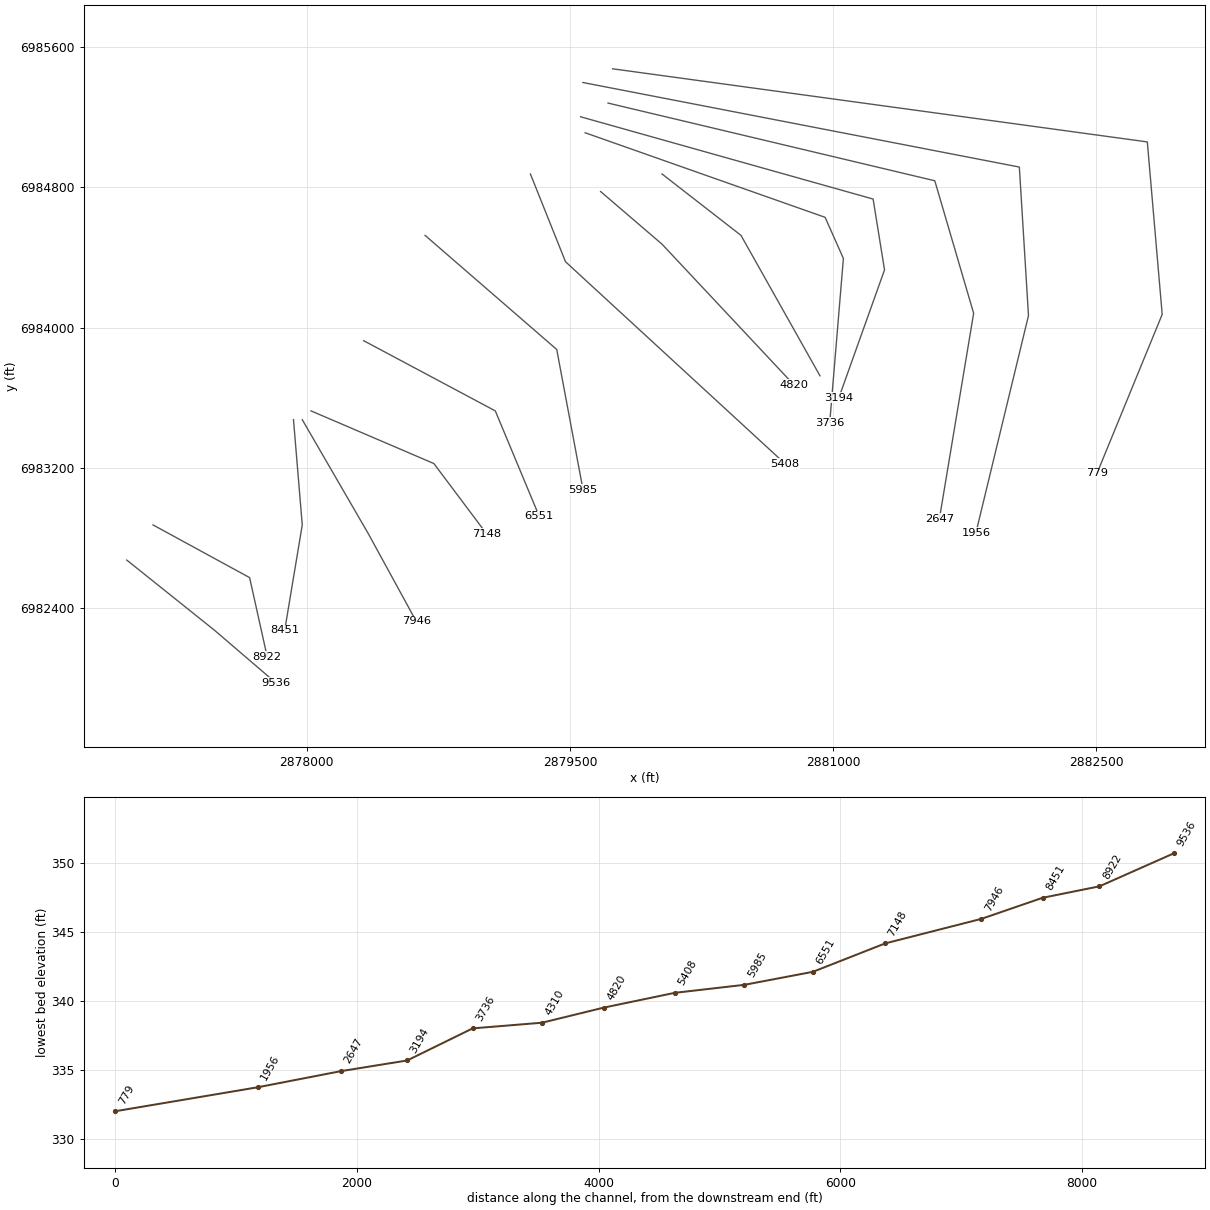
HEC-RAS study ALUM BRANCH.prj: ALUM BRANCH Base Level Engineering

--- ALUM BRANCH.g01 (geometry) --- (continued)

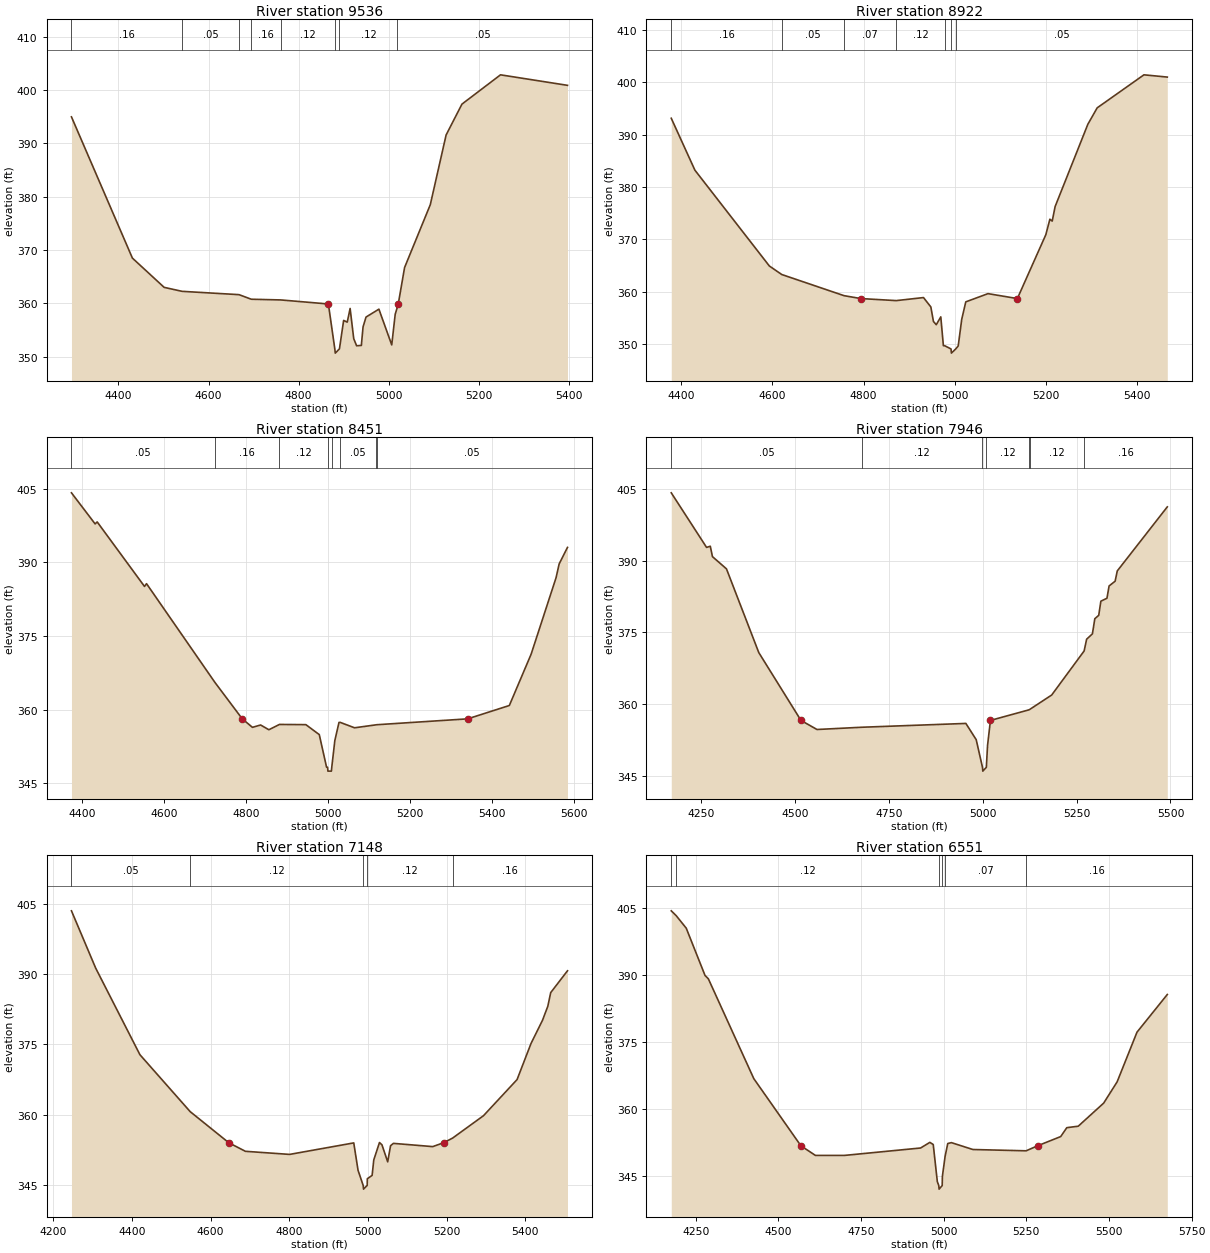
Type RM Length L Ch R = 1,9536,614,614,614
BEGIN DESCRIPTION:
ALUM BRANCH 14.0
END DESCRIPTION:
XS GIS Cut Line= 3
      2876975.01      6982675.00      2877475.00      6982275.00
      2877825.01      6981974.99
#Sta/Elev= 30
  4295.7  394.95  4431.0  368.48  4501.4  363.00  4541.3  362.25  4667.6  361.63
  4695.1  360.77  4760.3  360.64  4866.1  359.88  4880.4  351.47  4881.4  350.67
  4890.7  351.47  4900.0  356.80  4908.0  356.48  4914.4  359.04  4922.4  353.38
  4928.8  352.05  4939.3  352.11  4943.1  355.58  4949.7  357.43  4978.3  358.91
  5006.8  352.21  5014.5  357.96  5019.5  359.35  5021.3  359.88  5035.3  366.71
  5092.4  378.49  5127.5  391.55  5162.7  397.34  5248.3  402.83  5397.0  400.86
#Mann=8,-1,0
  4295.7    0.16       0  4541.3    0.05       0  4667.6    0.07       0
  4695.1    0.16       0  4760.3    0.12       0  4880.4    0.07       0
  4890.7    0.12       0  5019.5    0.05       0
Bank Sta=4866.1,5021.3
Exp/Cntr=0.3,0.1

Type RM Length L Ch R = 1,8922,471,471,471
BEGIN DESCRIPTION:
ALUM BRANCH 13.0
END DESCRIPTION:
XS GIS Cut Line= 3
      2877124.98      6982875.01      2877675.00      6982575.00
      2877775.00      6982125.00
#Sta/Elev= 30
  4378.5  393.10  4430.3  383.20  4593.5  364.92  4620.7  363.29  4757.4  359.25
  4794.3  358.70  4871.7  358.31  4931.5  358.89  4947.6  357.10  4953.3  354.33
  4959.5  353.71  4969.4  355.21  4975.1  349.71  4978.2  349.69  4991.8  349.09
  4992.7  348.29  5002.1  349.09  5007.6  349.66  5015.3  354.74  5024.2  358.07
  5072.9  359.64  5137.3  358.70  5199.7  370.89  5208.6  373.84  5213.7  373.48
  5220.1  376.26  5291.8  391.95  5312.3  395.09  5414.8  401.39  5466.0  400.96
#Mann=7,-1,0
  4378.5    0.16       0  4620.7    0.05       0  4757.4    0.07       0
  4871.7    0.12       0  4978.2    0.05       0  4991.8    0.03       0
  5002.1    0.05       0
Bank Sta=4794.3,5137.3
Exp/Cntr=0.3,0.1

Type RM Length L Ch R = 1,8451,505,505,505
BEGIN DESCRIPTION:
ALUM BRANCH 12.0
END DESCRIPTION:
XS GIS Cut Line= 3
      2877925.00      6983475.04      2877975.00      6982875.00
      2877875.00      6982275.00
#Sta/Elev= 30
  4373.8  404.16  4431.5  397.83  4436.6  398.23  4552.0  385.09  4557.0  385.65
  4724.0  365.52  4790.6  358.11  4815.4  356.38  4835.4  356.86  4855.5  355.89
  4881.3  356.97  4945.8  356.93  4978.5  354.90  4996.2  348.30  4998.7  348.26
  4999.6  347.46  5008.0  347.46  5009.0  348.26  5016.5  353.70  5026.6  357.38
  5029.6  357.39  5064.6  356.29  5117.0  356.89  5118.3  356.91  5340.6  358.11
  5442.3  360.83  5495.5  371.29  5556.3  386.86  5563.9  389.68  5584.2  393.04
#Mann=8,-1,0
  4373.8    0.05       0  4724.0    0.16       0  4881.3    0.12       0
  4998.7    0.07       0  5009.0    0.12       0  5029.6    0.05       0
  5117.0    0.16       0  5118.3    0.05       0
Bank Sta=4790.6,5340.6
Exp/Cntr=0.3,0.1

Type RM Length L Ch R = 1,7946,798,798,798
BEGIN DESCRIPTION:
ALUM BRANCH 11.0
END DESCRIPTION:
XS GIS Cut Line= 3
      2877975.02      6983474.97      2878352.27      6982823.68
      2878624.98      6982325.04
#Sta/Elev= 30
  4170.5  404.17  4264.5  392.75  4274.4  393.00  4280.2  390.82  4317.5  388.26
  4403.6  370.74  4515.9  356.55  4558.6  354.65  4677.5  355.12  4955.1  355.92
  4982.6  352.52  4999.3  346.74  5000.2  345.94  5009.6  346.74  5012.8  351.31
  5020.5  356.55  5123.0  358.76  5124.8  358.83  5183.7  361.87  5270.0  371.08
  5276.7  373.54  5292.1  374.67  5298.5  377.83  5308.9  378.54  5314.6  381.50
  5330.8  382.11  5336.5  384.68  5352.6  385.68  5358.3  387.83  5491.5  401.23
#Mann=7,-1,0
  4170.5    0.05       0  4677.5    0.12       0  4999.3    0.07       0
  5009.6    0.12       0  5123.0    0.16       0  5124.8    0.12       0
  5270.0    0.16       0
Bank Sta=4515.9,5020.5
Exp/Cntr=0.3,0.1

Type RM Length L Ch R = 1,7148,597,597,597
BEGIN DESCRIPTION:
ALUM BRANCH 10.0
END DESCRIPTION:
XS GIS Cut Line= 3
      2878025.01      6983524.99      2878725.00      6983225.00
      2879025.02      6982824.97
#Sta/Elev= 30
  4246.1  403.47  4307.7  391.26  4420.2  372.81  4548.1  360.67  4646.2  354.05
  4688.5  352.22  4800.9  351.56  4964.1  354.01  4975.0  348.18  4988.0  344.96
  4988.9  344.16  4998.3  344.96  4998.6  346.37  5010.8  347.09  5015.0  350.38
  5029.5  354.09  5035.8  353.61  5050.4  349.97  5057.7  353.42  5065.0  353.91
  5165.0  353.22  5192.6  354.05  5215.4  355.03  5294.1  359.81  5379.5  367.51
  5415.0  375.21  5444.1  380.13  5457.7  383.14  5465.0  386.04  5507.7  390.69
#Mann=5,-1,0
  4246.1    0.05       0  4548.1    0.12       0  4988.0    0.07       0
  4998.3    0.12       0  5215.4    0.16       0
Bank Sta=4646.2,5192.6
Exp/Cntr=0.3,0.1

Type RM Length L Ch R = 1,6551,566,566,566
BEGIN DESCRIPTION:
ALUM BRANCH 9.0
END DESCRIPTION:
XS GIS Cut Line= 3
      2878325.04      6983924.98      2879075.00      6983525.00
      2879325.02      6982924.96
#Sta/Elev= 30
  4176.3  404.43  4191.4  403.33  4221.6  400.54  4278.3  389.97  4288.5  389.20
  4425.9  366.85  4568.4  351.81  4612.2  349.66  4700.1  349.66  4930.3  351.32
  4958.3  352.58  4968.5  352.10  4980.9  343.77  4985.3  342.91  4986.2  342.11
  4995.6  342.91  4996.2  344.97  5004.3  349.42  5012.4  352.32  5023.4  352.52
  5088.5  350.98  5249.4  350.69  5284.0  351.81  5354.0  353.88  5372.4  355.87
  5407.0  356.20  5484.0  361.38  5524.6  366.13  5584.7  377.26  5676.3  385.69
#Mann=6,-1,0
  4176.3    0.16       0  4191.4    0.12       0  4985.3    0.07       0
  4995.6    0.12       0  5004.3    0.07       0  5249.4    0.16       0
Bank Sta=4568.4,5284
Exp/Cntr=0.3,0.1

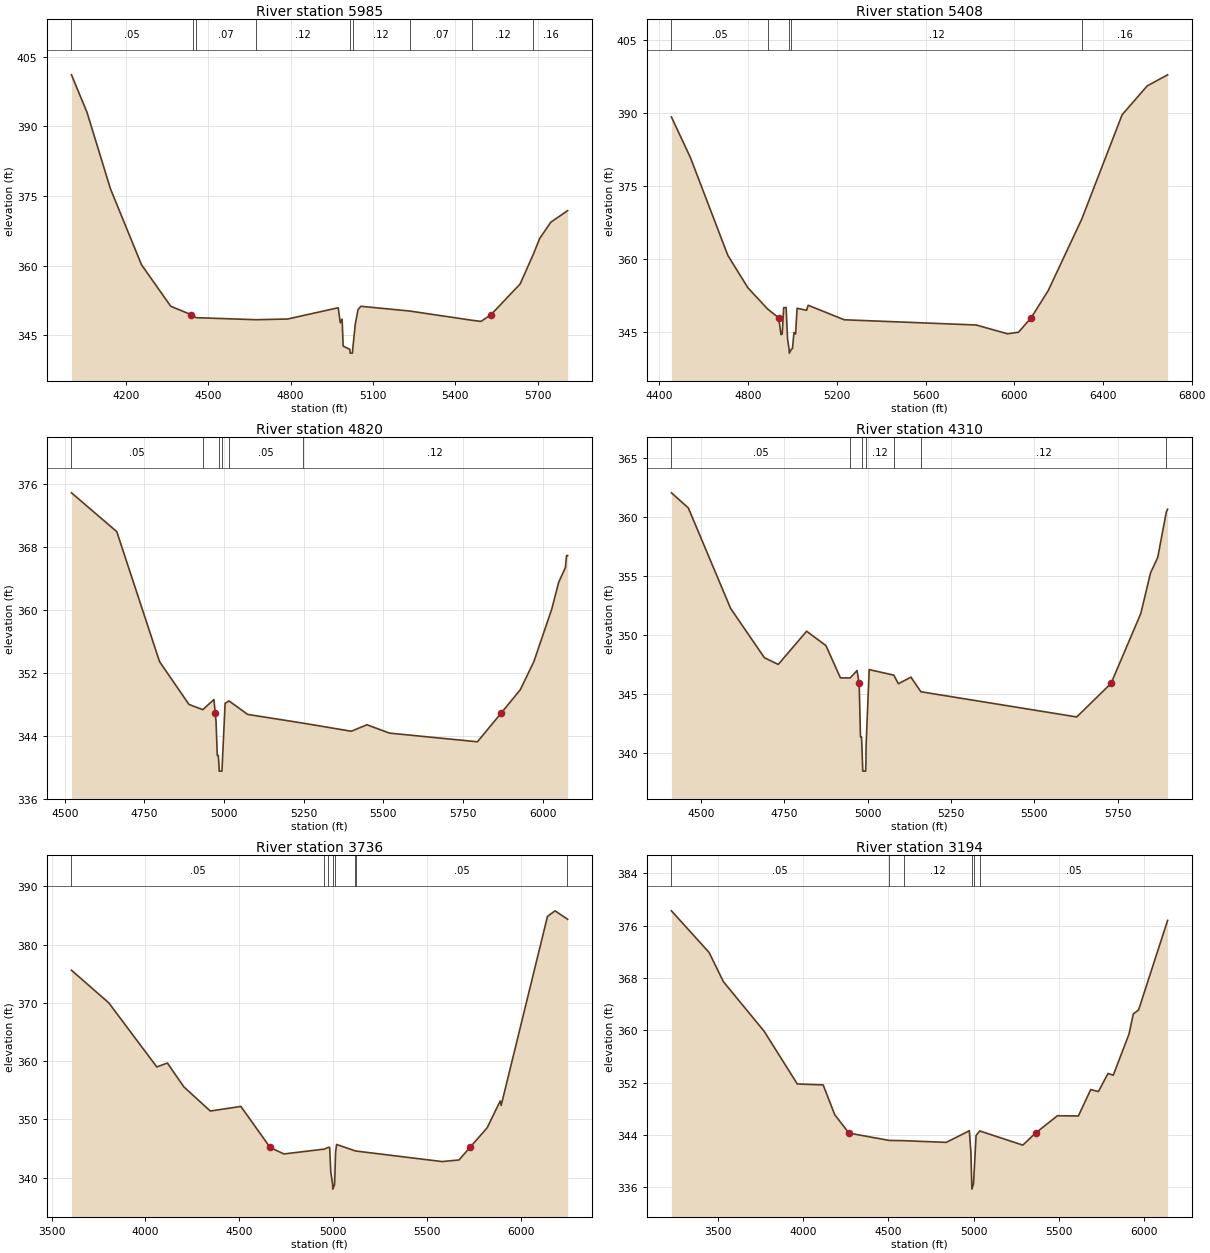
Type RM Length L Ch R = 1,5985,577,577,577
BEGIN DESCRIPTION:
ALUM BRANCH 8.0
END DESCRIPTION:
XS GIS Cut Line= 3
      2878675.00      6984525.00      2879425.00      6983875.00
      2879575.00      6983075.01
#Sta/Elev= 30
  4002.1  401.06  4058.6  393.00  4144.1  376.52  4257.1  360.18  4363.5  351.26
  4438.4  349.43  4443.9  349.15  4456.6  348.80  4674.0  348.36  4788.9  348.51
  4973.2  350.93  4980.8  347.70  4987.4  348.49  4991.3  342.67  5015.7  341.97
  5016.6  341.17  5025.1  341.17  5026.0  341.97  5035.3  347.37  5045.4  350.52
  5055.6  351.25  5233.5  350.23  5459.1  348.25  5493.1  348.00  5529.3  349.43
  5635.5  356.05  5684.0  362.50  5706.8  365.85  5747.5  369.36  5808.5  371.83
#Mann=9,-1,0
  4002.1    0.05       0  4443.9    0.12       0  4456.6    0.07       0
  4674.0    0.12       0  5015.7    0.07       0  5026.0    0.12       0
  5233.5    0.07       0  5459.1    0.12       0  5684.0    0.16       0
Bank Sta=4438.4,5529.3
Exp/Cntr=0.3,0.1

Type RM Length L Ch R = 1,5408,588,588,588
BEGIN DESCRIPTION:
ALUM BRANCH 7.0
END DESCRIPTION:
XS GIS Cut Line= 3
      2879275.01      6984874.98      2879475.00      6984375.00
      2880724.99      6983225.01
#Sta/Elev= 30
  4454.5  389.10  4540.6  380.70  4708.9  360.66  4799.1  354.02  4888.1  349.65
  4937.8  347.86  4948.6  344.38  4953.9  344.50  4960.7  349.93  4971.5  349.96
  4978.2  343.42  4985.1  341.39  4986.0  340.59  4995.5  341.39  5000.1  341.52
  5006.9  344.83  5014.3  344.52  5021.1  349.81  5063.6  349.38  5071.0  350.42
  5233.7  347.44  5828.1  346.37  5969.9  344.56  6019.2  344.88  6076.5  347.86
  6153.6  353.46  6304.3  368.10  6486.5  389.55  6599.4  395.47  6691.5  397.75
#Mann=5,-1,0
  4454.5    0.05       0  4888.1    0.12       0  4985.1    0.07       0
  4995.5    0.12       0  6304.3    0.16       0
Bank Sta=4937.8,6076.5
Exp/Cntr=0.3,0.1

Type RM Length L Ch R = 1,4820,510,510,510
BEGIN DESCRIPTION:
ALUM BRANCH 6.0
END DESCRIPTION:
XS GIS Cut Line= 3
      2879674.98      6984775.02      2880025.00      6984475.00
      2880775.01      6983674.99
#Sta/Elev= 30
  4521.3  374.89  4663.5  369.96  4797.9  353.43  4890.1  348.00  4933.4  347.33
  4968.6  348.62  4972.5  346.93  4975.2  345.78  4979.0  341.52  4982.3  341.52
  4984.2  340.32  4985.1  339.52  4993.7  339.52  4994.6  340.32  5003.6  348.14
  5016.1  348.44  5074.4  346.73  5247.9  345.62  5399.7  344.59  5449.0  345.41
  5519.9  344.35  5795.8  343.25  5870.9  346.93  5930.2  349.86  5972.7  353.42
  6029.3  360.15  6050.8  363.52  6071.8  365.39  6075.5  366.92  6078.9  366.92
#Mann=6,-1,0
  4521.3    0.05       0  4933.4    0.12       0  4984.2    0.07       0
  4994.6    0.12       0  5016.1    0.05       0  5247.9    0.12       0
Bank Sta=4972.5,5870.9
Exp/Cntr=0.3,0.1

Type RM Length L Ch R = 1,4310,574,574,574
BEGIN DESCRIPTION:
ALUM BRANCH 5.0
END DESCRIPTION:
XS GIS Cut Line= 3
      2880024.96      6984875.03      2880475.00      6984525.00
      2880925.00      6983725.01
#Sta/Elev= 30
  4411.7  362.06  4462.4  360.78  4589.1  352.25  4690.5  348.06  4732.1  347.49
  4817.1  350.31  4875.1  349.09  4918.5  346.35  4947.6  346.34  4968.3  346.97
  4974.7  345.88  4978.7  341.32  4981.8  341.32  4984.6  339.23  4985.5  338.43
  4994.1  338.43  4995.0  339.23  4995.5  340.61  5004.8  347.05  5078.6  346.58
  5092.4  345.85  5130.0  346.41  5159.8  345.17  5627.2  343.03  5730.1  345.88
  5819.4  351.82  5848.4  355.25  5870.1  356.57  5895.9  360.44  5899.7  360.67
#Mann=7,-1,0
  4411.7    0.05       0  4947.6    0.12       0  4984.6    0.07       0
  4995.0    0.12       0  5078.6    0.07       0  5159.8    0.12       0
  5895.9    0.05       0
Bank Sta=4974.7,5730.1
Exp/Cntr=0.3,0.1

Type RM Length L Ch R = 1,3736,542,542,542
BEGIN DESCRIPTION:
Mapping XS fd3a126e
END DESCRIPTION:
XS GIS Cut Line= 4
      2879587.07      6985109.76      2880954.28      6984627.98
      2881058.44      6984393.61      2880980.48      6983458.04
#Sta/Elev= 30
  3606.2  375.60  3805.5  369.99  4061.0  359.00  4117.6  359.67  4205.2  355.58
  4346.2  351.43  4509.3  352.22  4665.3  345.17  4738.5  344.06  4954.0  344.89
  4975.0  345.19  4982.4  345.19  4988.6  340.95  4998.4  338.82  4999.3  338.02
  5008.8  338.82  5014.2  344.40  5019.6  345.69  5116.7  344.61  5122.3  344.56
  5581.8  342.75  5672.1  343.03  5730.2  345.17  5822.7  348.58  5891.7  353.16
  5896.8  352.39  6143.8  384.85  6183.9  385.80  6250.1  384.38  6251.1  384.35
#Mann=8,-1,0
  3606.2    0.05       0  4954.0    0.12       0  4975.0    0.07       0
  4998.4    0.07       0  5008.8    0.07       0  5116.7    0.12       0
  5122.3    0.05       0  6250.1    0.16       0
Bank Sta=4665.3,5730.2
Exp/Cntr=0.3,0.1

Type RM Length L Ch R = 1,3194,547,547,547
BEGIN DESCRIPTION:
Mapping XS 37e81ad4
END DESCRIPTION:
XS GIS Cut Line= 4
      2879561.01      6985200.91      2881227.71      6984732.15
      2881292.82      6984328.50      2881032.54      6983599.71
#Sta/Elev= 30
  3225.2  378.26  3446.2  371.90  3530.6  367.42  3769.5  359.85  3964.5  351.78
  4116.3  351.64  4184.4  347.08  4267.8  344.27  4503.6  343.15  4589.1  343.11
  4839.5  342.85  4975.0  344.63  4984.1  341.33  4989.0  336.50  4989.9  335.70
  4999.4  336.50  5014.5  343.91  5035.6  344.60  5289.0  342.43  5363.8  344.27
  5492.0  346.92  5615.2  346.89  5687.7  350.92  5733.0  350.62  5789.3  353.39
  5820.1  353.12  5912.5  359.40  5938.0  362.50  5968.8  363.09  6139.3  376.79
#Mann=6,-1,0
  3225.2    0.05       0  4503.6    0.16       0  4589.1    0.12       0
  4989.0    0.07       0  4999.4    0.12       0  5035.6    0.05       0
Bank Sta=4267.8,5363.8
Exp/Cntr=0.3,0.1

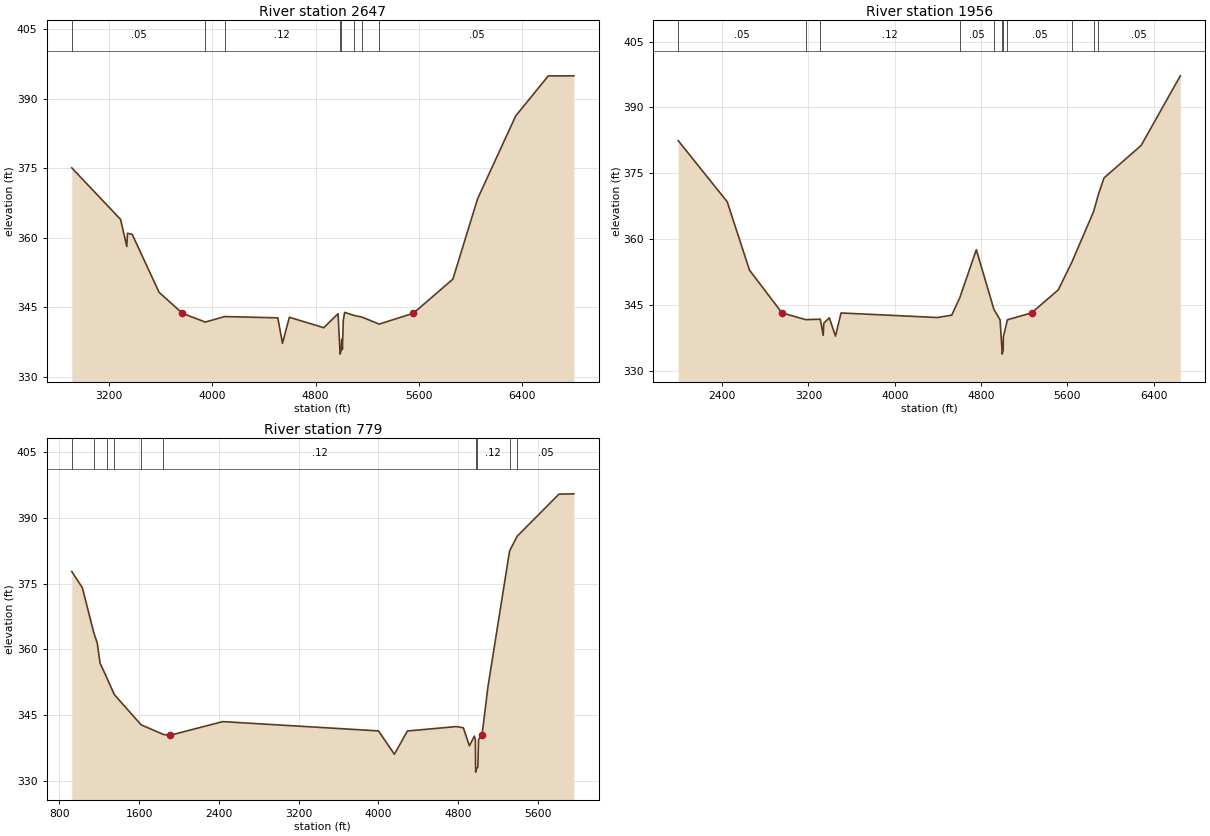
Type RM Length L Ch R = 1,2647,691,691,691
BEGIN DESCRIPTION:
Mapping XS 0c0dba12
END DESCRIPTION:
XS GIS Cut Line= 4
      2879717.27      6985279.03      2881579.28      6984836.31
      2881800.63      6984081.11      2881605.39      6982909.66
#Sta/Elev= 30
  2911.8  375.08  3289.8  363.97  3338.0  358.13  3343.1  360.99  3380.1  360.73
  3587.9  348.26  3768.2  343.74  3945.5  341.84  4096.6  343.03  4507.5  342.75
  4543.8  337.27  4597.0  342.87  4863.7  340.63  4974.3  343.65  4988.6  335.73
  4989.4  334.93  4999.1  335.73  5002.5  338.14  5007.8  335.96  5014.7  342.22
  5025.1  343.93  5098.4  343.27  5160.9  342.90  5292.7  341.40  5557.1  343.74
  5863.5  351.09  6054.8  368.42  6350.2  386.29  6602.3  394.90  6800.3  394.92
#Mann=8,-1,0
  2911.8    0.05       0  3945.5    0.16       0  4096.6    0.12       0
  4988.6    0.07       0  4999.1    0.12       0  5098.4    0.05       0
  5160.9    0.16       0  5292.7    0.05       0
Bank Sta=3768.2,5557.1
Exp/Cntr=0.3,0.1

Type RM Length L Ch R = 1,1956,1177,1177,1177
BEGIN DESCRIPTION:
Mapping XS aff009bf
END DESCRIPTION:
XS GIS Cut Line= 4
      2879574.07      6985396.21      2882061.05      6984914.44
      2882113.13      6984068.08      2881813.65      6982831.09
#Sta/Elev= 30
  1992.6  382.41  2446.4  368.49  2653.4  352.89  2954.5  343.16  3173.4  341.62
  3309.2  341.72  3336.4  338.03  3341.5  340.80  3393.2  342.04  3450.1  337.87
  3501.8  343.14  4397.4  342.10  4528.0  342.64  4603.0  346.66  4755.7  357.56
  4918.4  343.99  4976.1  341.56  4993.9  334.56  4994.7  333.76  5004.5  334.56
  5006.2  337.72  5044.1  341.58  5267.6  343.16  5515.2  348.40  5640.3  354.66
  5842.8  366.25  5885.9  370.04  5938.6  373.89  6283.5  381.32  6646.5  397.18
#Mann=11,-1,0
  1992.6    0.05       0  3173.4    0.16       0  3309.2    0.12       0
  4603.0    0.05       0  4918.4    0.12       0  4993.9    0.07       0
  5004.5    0.12       0  5044.1    0.05       0  5640.3    0.16       0
  5842.8    0.12       0  5885.9    0.05       0
Bank Sta=2954.5,5267.6
Exp/Cntr=0.3,0.1

Type RM Length L Ch R = 1,779,0,0,0
BEGIN DESCRIPTION:
ALUM BRANCH 1.0
END DESCRIPTION:
XS GIS Cut Line= 4
      2879743.33      6985474.34      2882790.21      6985057.67
      2882875.00      6984075.00      2882503.82      6983169.81
#Sta/Elev= 30
   923.4  377.79  1030.1  374.06  1144.2  363.83  1179.6  361.43  1207.7  356.86
  1275.0  353.56  1351.1  349.70  1620.0  342.81  1842.0  340.63  1908.4  340.42
  2439.0  343.55  4002.5  341.43  4161.9  336.11  4292.4  341.41  4784.2  342.42
  4854.5  342.13  4914.7  338.03  4964.9  340.24  4974.9  339.43  4977.1  332.83
  4978.0  332.03  4987.8  332.83  4999.7  333.22  5006.6  339.47  5041.4  340.42
  5101.0  351.47  5318.2  382.46  5394.6  385.83  5813.5  395.41  5963.3  395.49
#Mann=10,-1,0
   923.4    0.16       0  1144.2    0.12       0  1275.0    0.16       0
  1351.1    0.12       0  1620.0    0.05       0  1842.0    0.12       0
  4977.1    0.07       0  4987.8    0.12       0  5318.2    0.16       0
  5394.6    0.05       0
Bank Sta=1908.4,5041.4
Exp/Cntr=0.3,0.1

Chan Stop Cuts=-1