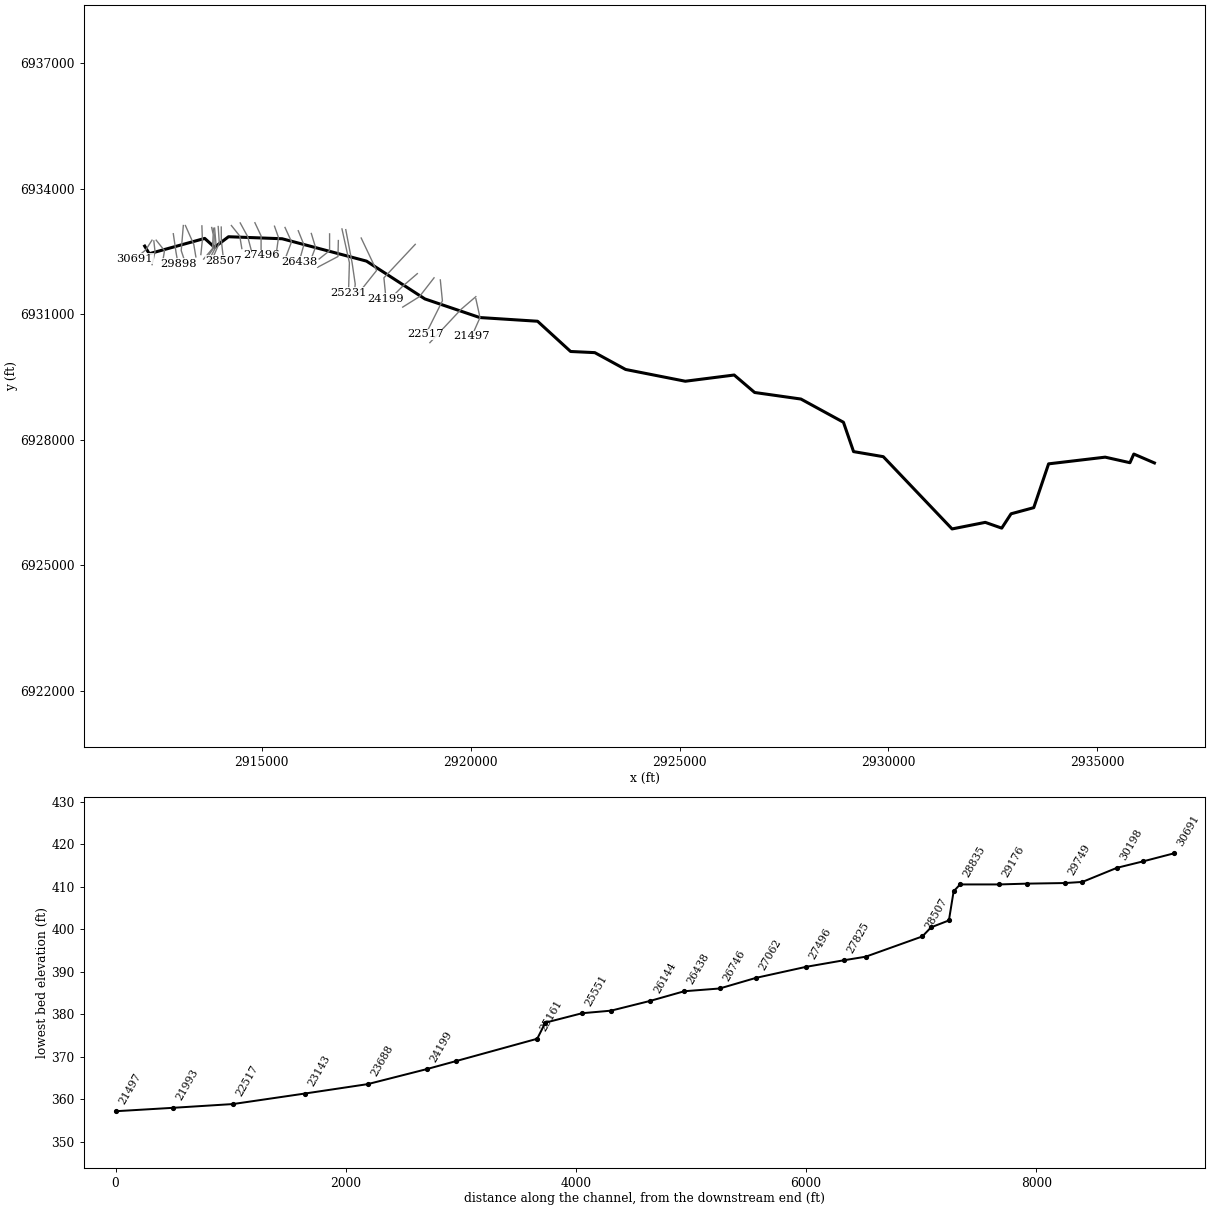
--- BLACK CREEK.prj (project) ---

Proj Title=BLACK CREEK Base Level Engineering
Current Plan=p01
Default Exp/Contr=0.3,0.1
English Units
Geom File=g01
Flow File=f01
Plan File=p01
BEGIN DESCRIPTION:
BLACK CREEK
END DESCRIPTION:

--- BLACK CREEK.p01 (plan) ---

Plan Title=Multiple Run
Short Identifier=Multiple
Geom File=g01
Flow File=f01
Subcritical Flow
K Sum by GR= 0
Std Step Tol= 0.01
Critical Tol= 0.01
Num of Std Step Trials= 20
Max Error Tol= 0.3
Flow Tol Ratio= 0.001
Split Flow NTrial= 30
Split Flow Tol= 0.02
Split Flow Ratio= 0.02
Log Output Level= 0
Friction Slope Method= 1
Unsteady Friction Slope Method= 2
Unsteady Bridges Friction Slope Method= 1
Parabolic Critical Depth
Global Vel Dist=  1 , 1 , 1
Global Log Level= 0
CheckData=True
Encroach Param= -1, 0, 0, 0
BEGIN DESCRIPTION:
Multiple Run
END DESCRIPTION:

--- BLACK CREEK.f01 (steady flow) ---

Flow Title=Multiple
Program Version=5.07
Number of Profiles= 7
Profile Names=10-year,25-year,50-year,1pct_min,100-year,1pct_plu,500-year
River Rch & RM=BLACK CREEK,Reach-1         ,30691
     728     998    1223     746    1489    2971    2208
River Rch & RM=BLACK CREEK,Reach-1         ,24199
    1157    1623    2019    1248    2489    4967    3792
River Rch & RM=BLACK CREEK,Reach-1         ,20935
    1423    2005    2502    1548    3089    6164    4721
River Rch & RM=BLACK CREEK,Reach-1         ,16713
    1528    2159    2700    1673    3339    6662    5121
River Rch & RM=BLACK CREEK,Reach-1         ,15602
    1701    2405    3007    1863    3716    7415    5692
River Rch & RM=BLACK CREEK,Reach-1         ,7130
    1887    2679    3359    2085    4161    8302    6403
River Rch & RM=BLACK CREEK,Reach-1         ,6296
    1961    2782    3487    2164    4317    8613    6635
Boundary for River Rch & Prof#=BLACK CREEK,Reach-1         , 1
Up Type= 0
Dn Type= 3
Dn Slope=0.005
Boundary for River Rch & Prof#=BLACK CREEK,Reach-1         , 2
Up Type= 0
Dn Type= 3
Dn Slope=0.005
Boundary for River Rch & Prof#=BLACK CREEK,Reach-1         , 3
Up Type= 0
Dn Type= 3
Dn Slope=0.005
Boundary for River Rch & Prof#=BLACK CREEK,Reach-1         , 4
Up Type= 0
Dn Type= 3
Dn Slope=0.005
Boundary for River Rch & Prof#=BLACK CREEK,Reach-1         , 5
Up Type= 0
Dn Type= 3
Dn Slope=0.005
Boundary for River Rch & Prof#=BLACK CREEK,Reach-1         , 6
Up Type= 0
Dn Type= 3
Dn Slope=0.005
Boundary for River Rch & Prof#=BLACK CREEK,Reach-1         , 7
Up Type= 0
Dn Type= 3
Dn Slope=0.005
DSS Import GetInterval= 0
DSS Import GetPeak= 0
DSS Import FillOption= 0

--- BLACK CREEK.g01 (geometry) ---

Geom Title=Existing Conditions

River Reach=BLACK CREEK,Reach-1
Reach XY= 30
      2912200.38      6932633.47      2912309.75      6932451.17
      2913637.14      6932816.93      2913870.79      6932604.74
      2914206.38      6932857.04      2915489.79      6932808.79
      2917507.90      6932274.59      2918905.59      6931370.71
      2920218.14      6930925.77      2921602.12      6930837.19
      2922392.52      6930114.60      2922972.38      6930086.83
      2923709.76      6929684.41      2925137.32      6929403.44
      2926307.47      6929551.99      2926797.11      6929134.37
      2927904.39      6928977.82      2928921.97      6928422.84
      2929164.25      6927721.34      2929875.30      6927600.45
      2931521.40      6925873.30      2932316.02      6926030.37
      2932709.93      6925892.47      2932933.24      6926235.33
      2933476.16      6926381.88      2933831.48      6927428.90
      2935185.57      6927588.80      2935778.35      6927456.13
      2935870.52      6927663.29      2936364.11      6927450.35

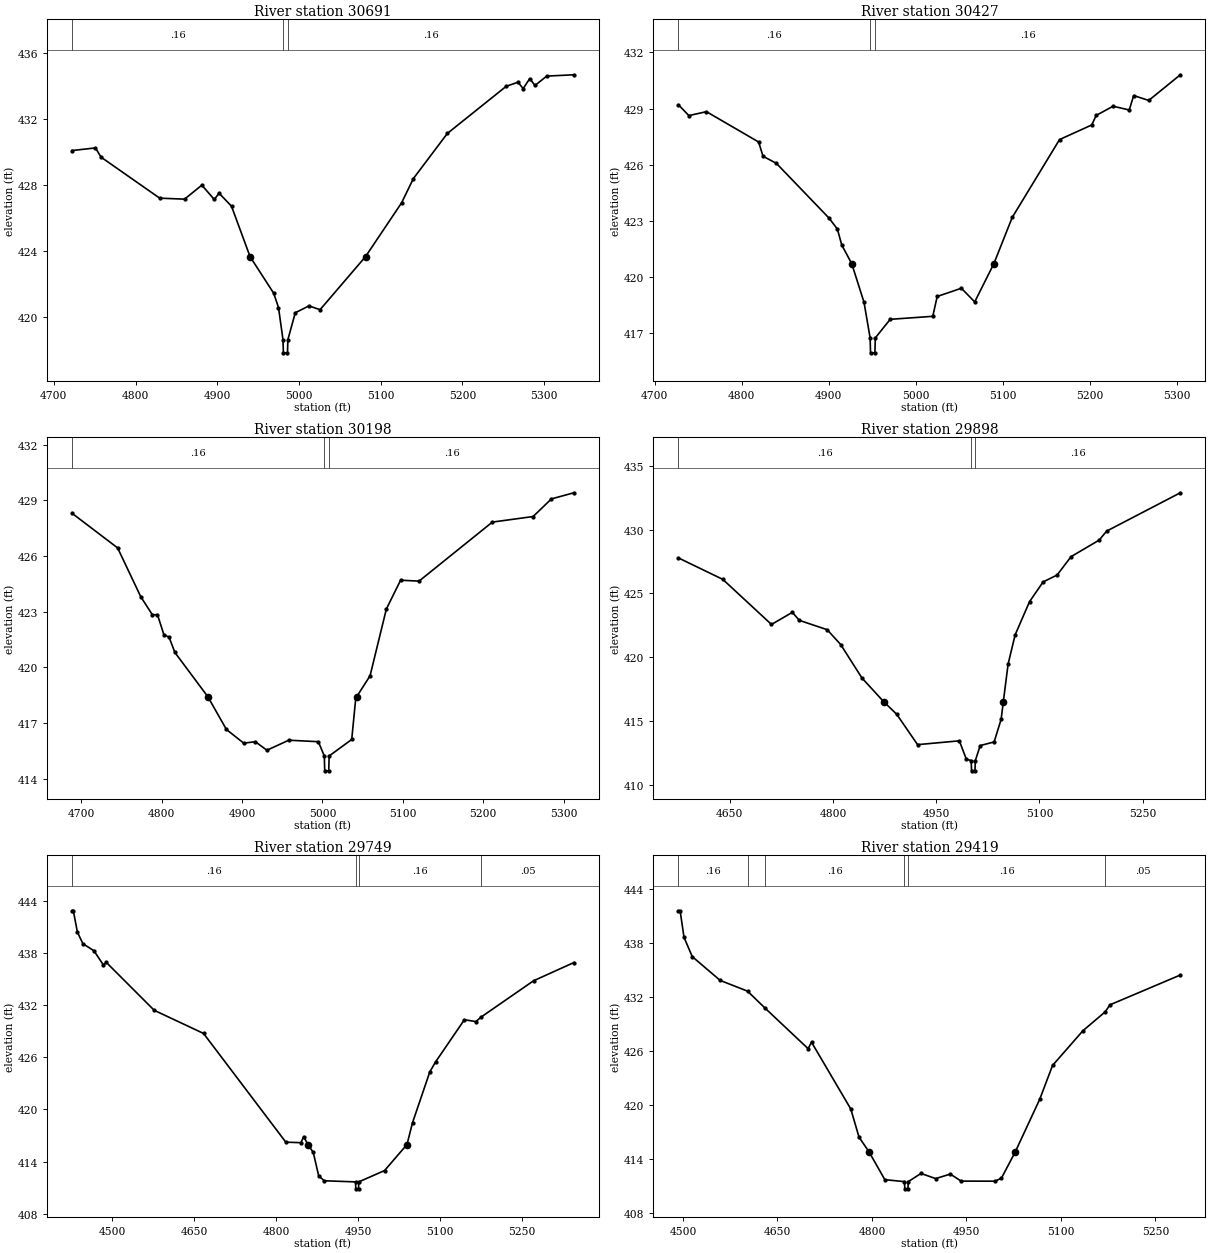
Type RM Length L Ch R = 1,30691,264,264,264
BEGIN DESCRIPTION:
BLACK CREEK 57.0
END DESCRIPTION:
XS GIS Cut Line= 3
      2912375.01      6932775.01      2912225.18      6932541.07
      2911963.19      6932329.91
#Sta/Elev= 30
  4722.2  430.10  4751.0  430.26  4757.8  429.70  4829.6  427.21  4860.0  427.15
  4881.2  428.00  4896.4  427.13  4902.3  427.51  4917.5  426.72  4940.2  423.66
  4969.1  421.44  4975.0  420.57  4980.5  418.62  4981.0  417.82  4986.0  417.82
  4986.5  418.62  4995.5  420.25  5012.2  420.67  5025.9  420.44  5081.5  423.66
  5125.7  426.93  5140.1  428.40  5181.7  431.14  5253.7  434.00  5268.1  434.25
  5274.5  433.86  5282.5  434.47  5288.9  434.05  5303.3  434.62  5336.5  434.70
#Mann=3,-1,0
  4722.2    0.16       0  4980.5    0.07       0  4986.5    0.16       0
Bank Sta=4940.2,5081.5
Exp/Cntr=0.3,0.1

Type RM Length L Ch R = 1,30427,229,229,229
BEGIN DESCRIPTION:
Mapping XS ccc92ba8
END DESCRIPTION:
XS GIS Cut Line= 3
      2912419.31      6932756.95      2912447.95      6932499.14
      2912377.72      6932189.61
#Sta/Elev= 30
  4727.2  429.21  4739.2  428.63  4759.4  428.84  4819.4  427.22  4824.4  426.46
  4839.8  426.08  4900.2  423.16  4909.9  422.57  4914.9  421.72  4926.4  420.72
  4940.5  418.66  4947.5  416.76  4948.0  415.96  4953.0  415.96  4953.5  416.76
  4970.6  417.75  5019.5  417.91  5024.6  418.97  5052.4  419.41  5067.7  418.68
  5089.7  420.72  5110.8  423.19  5165.2  427.35  5202.2  428.13  5207.3  428.64
  5226.7  429.13  5245.3  428.93  5250.4  429.70  5267.7  429.44  5304.0  430.81
#Mann=3,-1,0
  4727.2    0.16       0  4947.5    0.07       0  4953.5    0.16       0
Bank Sta=4926.4,5089.7
Exp/Cntr=0.3,0.1

Type RM Length L Ch R = 1,30198,300,300,300
BEGIN DESCRIPTION:
BLACK CREEK 56.0
END DESCRIPTION:
XS GIS Cut Line= 3
      2912475.01      6932774.98      2912675.00      6932525.00
      2912625.00      6932224.97
#Sta/Elev= 30
  4688.5  428.31  4745.3  426.44  4774.1  423.81  4788.5  422.84  4794.9  422.84
  4802.9  421.76  4809.3  421.63  4816.5  420.81  4857.6  418.42  4880.6  416.66
  4902.2  415.92  4916.6  416.00  4931.0  415.54  4958.2  416.08  4995.0  416.00
  5002.4  415.23  5002.9  414.43  5007.9  414.43  5008.4  415.23  5036.5  416.12
  5041.6  418.38  5042.6  418.42  5059.3  419.55  5079.6  423.15  5097.3  424.70
  5120.2  424.65  5211.4  427.83  5262.1  428.13  5284.9  429.08  5312.8  429.41
#Mann=3,-1,0
  4688.5    0.16       0  5002.4    0.07       0  5008.4    0.16       0
Bank Sta=4857.6,5042.6
Exp/Cntr=0.3,0.1

Type RM Length L Ch R = 1,29898,149,149,149
BEGIN DESCRIPTION:
Mapping XS 8502a456
END DESCRIPTION:
XS GIS Cut Line= 3
      2912885.45      6932928.82      2912950.56      6932480.91
      2912999.79      6932208.84
#Sta/Elev= 30
  4575.6  427.78  4640.1  426.10  4710.8  422.57  4741.1  423.52  4751.3  422.89
  4791.7  422.16  4811.3  421.00  4842.2  418.38  4873.7  416.53  4892.7  415.54
  4923.0  413.16  4983.7  413.46  4993.8  412.03  5000.9  411.91  5001.4  411.11
  5006.4  411.11  5006.9  411.91  5014.0  413.09  5034.2  413.37  5044.4  415.14
  5047.6  416.53  5054.5  419.46  5064.7  421.75  5085.7  424.36  5105.4  425.90
  5125.7  426.44  5146.0  427.88  5186.7  429.17  5197.7  429.88  5304.7  432.88
#Mann=3,-1,0
  4575.6    0.16       0  5000.9    0.07       0  5006.9    0.16       0
Bank Sta=4873.7,5047.6
Exp/Cntr=0.3,0.1

Type RM Length L Ch R = 1,29749,330,330,330
BEGIN DESCRIPTION:
BLACK CREEK 55.0
END DESCRIPTION:
XS GIS Cut Line= 3
      2913125.00      6933124.99      2913075.00      6932525.00
      2913175.00      6932224.99
#Sta/Elev= 30
  4426.5  442.90  4429.0  442.90  4436.5  440.44  4446.6  439.10  4466.6  438.30
  4484.2  436.64  4489.2  436.96  4577.0  431.43  4667.3  428.76  4817.8  416.23
  4845.4  416.17  4850.5  416.86  4858.3  415.96  4868.0  415.04  4878.0  412.34
  4888.1  411.78  4945.3  411.65  4945.8  410.85  4950.8  410.85  4951.3  411.65
  4998.5  412.96  5039.5  415.96  5049.6  418.47  5081.3  424.34  5091.8  425.48
  5144.5  430.34  5165.6  430.13  5174.9  430.64  5271.0  434.83  5344.8  436.93
#Mann=4,-1,0
  4426.5    0.16       0  4945.3    0.07       0  4951.3    0.16       0
  5174.9    0.05       0
Bank Sta=4858.3,5039.5
Exp/Cntr=0.3,0.1

Type RM Length L Ch R = 1,29419,243,243,243
BEGIN DESCRIPTION:
BLACK CREEK 54.0
END DESCRIPTION:
XS GIS Cut Line= 3
      2913175.01      6933124.98      2913375.00      6932675.00
      2913425.01      6932374.96
#Sta/Elev= 30
  4492.8  441.61  4495.5  441.61  4501.7  438.66  4514.7  436.52  4559.1  433.87
  4602.5  432.68  4630.2  430.80  4698.6  426.29  4704.1  427.00  4766.4  419.58
  4779.4  416.46  4795.4  414.81  4820.4  411.73  4851.6  411.51  4852.1  410.71
  4857.1  410.71  4857.6  411.51  4877.8  412.42  4901.1  411.85  4924.4  412.35
  4941.5  411.57  4995.4  411.56  5005.5  411.90  5027.4  414.81  5066.3  420.67
  5086.6  424.42  5134.8  428.28  5170.2  430.38  5177.8  431.16  5289.4  434.47
#Mann=6,-1,0
  4492.8    0.16       0  4602.5     0.1       0  4630.2    0.16       0
  4851.6    0.07       0  4857.6    0.16       0  5170.2    0.05       0
Bank Sta=4795.4,5027.4
Exp/Cntr=0.3,0.1

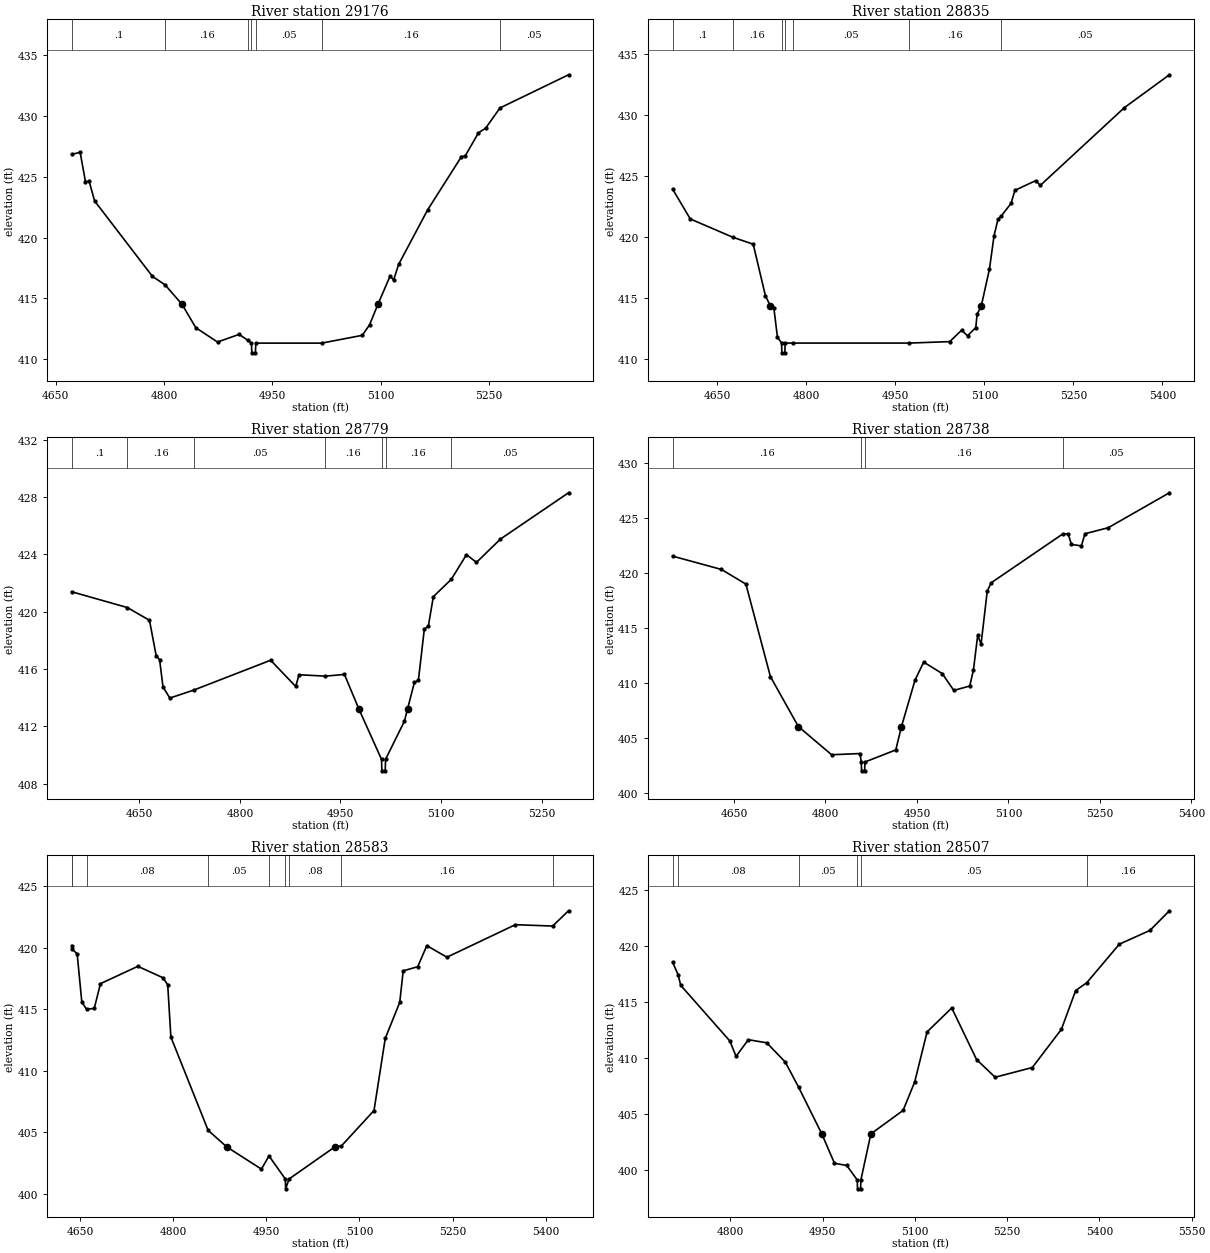
Type RM Length L Ch R = 1,29176,341,341,341
BEGIN DESCRIPTION:
Mapping XS c509b94b
END DESCRIPTION:
XS GIS Cut Line= 3
      2913569.22      6933116.72      2913581.37      6932783.34
      2913544.91      6932430.92
#Sta/Elev= 30
  4672.0  426.85  4683.7  427.02  4691.1  424.60  4696.1  424.65  4703.7  423.02
  4783.8  416.81  4801.4  416.11  4824.9  414.50  4843.8  412.59  4873.9  411.41
  4903.9  412.04  4916.1  411.54  4920.9  411.32  4921.4  410.52  4926.4  410.52
  4926.9  411.32  5018.2  411.32  5074.3  411.96  5084.4  412.82  5095.9  414.50
  5112.8  416.83  5117.8  416.52  5124.6  417.79  5164.8  422.28  5211.7  426.67
  5216.7  426.71  5235.2  428.62  5245.2  429.01  5265.0  430.67  5359.9  433.40
#Mann=7,-1,0
  4672.0     0.1       0  4801.4    0.16       0  4916.1    0.05       0
  4920.9   0.033       0  4926.9    0.05       0  5018.2    0.16       0
  5265.0    0.05       0
Bank Sta=4824.9,5095.9
Exp/Cntr=0.3,0.1

Type RM Length L Ch R = 1,28835,56,56,56
BEGIN DESCRIPTION:
Mapping XS 98e8236f
END DESCRIPTION:
XS GIS Cut Line= 4
      2913803.33      6933077.78      2913839.79      6932911.13
      2913822.90      6932573.33      2913610.65      6932322.62
#Sta/Elev= 30
  4574.4  423.94  4604.2  421.49  4675.9  419.99  4710.3  419.42  4730.8  415.21
  4739.1  414.37  4745.0  414.23  4751.1  411.82  4758.1  411.32  4758.6  410.52
  4763.6  410.52  4764.1  411.32  4777.3  411.32  4973.6  411.32  5041.5  411.44
  5061.5  412.37  5071.5  411.92  5085.4  412.59  5087.6  413.67  5094.7  414.37
  5108.5  417.40  5116.2  420.12  5122.8  421.46  5128.0  421.71  5144.8  422.76
  5151.3  423.83  5186.5  424.63  5194.2  424.24  5335.9  430.61  5411.7  433.30
#Mann=7,-1,0
  4574.4     0.1       0  4675.9    0.16       0  4758.1    0.07       0
  4764.1    0.16       0  4777.3    0.05       0  4973.6    0.16       0
  5128.0    0.05       0
Bank Sta=4739.1,5094.7
Exp/Cntr=0.3,0.1

Type RM Length L Ch R = 1,28779,41,41,41
BEGIN DESCRIPTION:
Mapping XS eeb399cc
END DESCRIPTION:
XS GIS Cut Line= 4
      2913839.78      6933059.61      2913865.83      6932892.90
      2913855.41      6932593.42      2913700.64      6932369.00
#Sta/Elev= 30
  4549.1  421.39  4632.0  420.29  4665.1  419.40  4675.1  416.93  4680.2  416.65
  4685.3  414.74  4695.5  413.97  4731.3  414.53  4845.8  416.61  4883.2  414.78
  4888.2  415.60  4927.3  415.50  4955.9  415.62  4977.2  413.23  5011.2  409.69
  5011.7  408.89  5016.7  408.89  5017.2  409.69  5045.3  412.35  5050.1  413.23
  5060.2  415.06  5066.2  415.21  5075.0  418.77  5081.1  419.01  5088.5  421.05
  5115.3  422.26  5137.9  423.98  5152.8  423.44  5188.6  425.07  5290.1  428.30
#Mann=7,-1,0
  4549.1     0.1       0  4632.0    0.16       0  4731.3    0.05       0
  4927.3    0.16       0  5011.2    0.07       0  5017.2    0.16       0
  5115.3    0.05       0
Bank Sta=4977.2,5050.1
Exp/Cntr=0.3,0.1

Type RM Length L Ch R = 1,28738,155,155,155
BEGIN DESCRIPTION:
Mapping XS 7b50ba5c
END DESCRIPTION:
XS GIS Cut Line= 4
      2913873.64      6933064.77      2913904.89      6932700.19
      2913886.66      6932580.40      2913733.04      6932291.37
#Sta/Elev= 30
  4549.4  421.54  4629.5  420.33  4669.6  419.00  4709.8  410.60  4755.6  406.07
  4810.1  403.51  4856.7  403.62  4858.7  402.85  4859.2  402.05  4864.2  402.05
  4864.7  402.85  4915.3  403.95  4924.6  406.07  4946.8  410.28  4961.0  411.92
  4991.4  410.88  5010.4  409.35  5036.5  409.75  5042.6  411.21  5049.5  414.34
  5055.1  413.57  5065.2  418.35  5071.4  419.11  5189.2  423.56  5197.7  423.56
  5203.3  422.60  5219.6  422.47  5225.3  423.57  5263.6  424.12  5363.8  427.29
#Mann=4,-1,0
  4549.4    0.16       0  4858.7    0.07       0  4864.7    0.16       0
  5189.2    0.05       0
Bank Sta=4755.6,4924.6
Exp/Cntr=0.3,0.1

Type RM Length L Ch R = 1,28583,76,76,76
BEGIN DESCRIPTION:
Mapping XS 7ac9eb9c
END DESCRIPTION:
XS GIS Cut Line= 3
      2913959.58      6933101.24      2913985.62      6932708.00
      2913824.16      6932335.60
#Sta/Elev= 30
  4636.7  420.18  4637.8  419.87  4645.5  419.50  4653.0  415.59  4660.6  415.00
  4673.0  415.07  4683.0  417.08  4743.2  418.49  4783.3  417.57  4791.3  417.00
  4796.4  412.75  4856.4  405.17  4886.3  403.83  4942.2  402.02  4954.4  403.09
  4980.7  401.22  4981.2  400.42  4986.7  401.22  5060.5  403.83  5071.1  403.91
  5123.5  406.78  5141.6  412.64  5164.9  415.56  5170.5  418.12  5193.9  418.46
  5208.5  420.17  5240.9  419.23  5351.1  421.87  5411.1  421.76  5436.7  423.00
#Mann=9,-1,0
  4636.7    0.08       0  4637.8     0.1       0  4660.6    0.08       0
  4856.4    0.05       0  4954.4    0.08       0  4980.7    0.07       0
  4986.7    0.08       0  5071.1    0.16       0  5411.1    0.05       0
Bank Sta=4886.3,5060.5
Exp/Cntr=0.3,0.1

Type RM Length L Ch R = 1,28507,492,492,492
BEGIN DESCRIPTION:
Mapping XS 0506adbe
END DESCRIPTION:
XS GIS Cut Line= 3
      2914032.50      6933088.21      2914035.10      6932760.08
      2914089.78      6932283.55
#Sta/Elev= 30
  4706.0  418.57  4715.1  417.43  4719.2  416.50  4799.2  411.51  4809.2  410.14
  4829.2  411.63  4859.2  411.35  4889.2  409.63  4910.8  407.39  4948.6  403.20
  4969.2  400.57  4989.2  400.37  5006.2  399.08  5006.7  398.28  5011.7  398.28
  5012.2  399.08  5028.4  403.20  5080.8  405.30  5099.7  407.85  5119.8  412.33
  5159.9  414.47  5200.3  409.85  5230.5  408.27  5290.9  409.14  5338.2  412.56
  5361.4  416.03  5379.6  416.74  5432.4  420.18  5482.1  421.41  5513.8  423.17
#Mann=6,-1,0
  4706.0     0.1       0  4715.1    0.08       0  4910.8    0.05       0
  5006.2    0.04       0  5012.2    0.05       0  5379.6    0.16       0
Bank Sta=4948.6,5028.4
Exp/Cntr=0.3,0.1

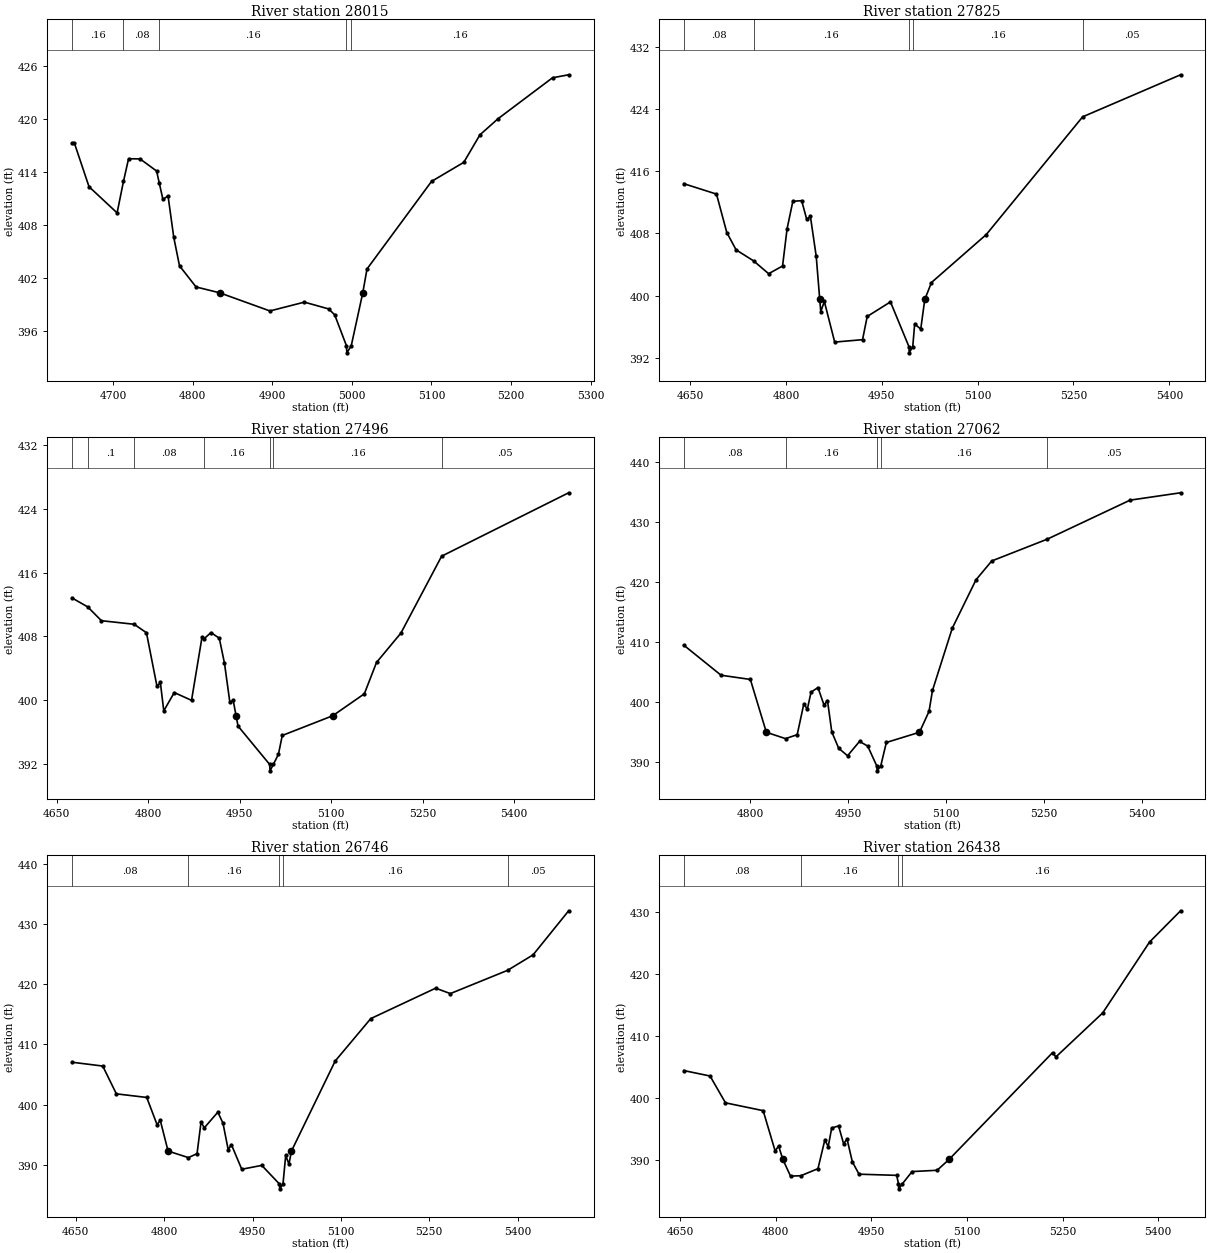
Type RM Length L Ch R = 1,28015,190,190,190
BEGIN DESCRIPTION:
BLACK CREEK 50.0
END DESCRIPTION:
XS GIS Cut Line= 3
      2914274.98      6933125.02      2914475.00      6932875.00
      2914525.00      6932575.02
#Sta/Elev= 30
  4648.1  417.30  4651.3  417.30  4669.7  412.35  4705.0  409.38  4713.0  412.95
  4719.4  415.52  4733.8  415.50  4754.6  414.13  4758.1  412.72  4762.6  410.90
  4769.0  411.31  4776.2  406.60  4783.4  403.38  4804.2  400.98  4833.8  400.32
  4897.0  398.26  4940.3  399.26  4970.8  398.49  4978.4  397.82  4993.2  394.31
  4993.7  393.51  4999.2  394.31  5013.7  400.32  5019.0  403.02  5100.1  412.95
  5140.6  415.11  5160.9  418.23  5183.7  420.06  5252.1  424.70  5272.4  425.04
#Mann=5,-1,0
  4648.1    0.16       0  4713.0    0.08       0  4758.1    0.16       0
  4993.2    0.07       0  4999.2    0.16       0
Bank Sta=4833.8,5013.7
Exp/Cntr=0.3,0.1

Type RM Length L Ch R = 1,27825,329,329,329
BEGIN DESCRIPTION:
Mapping XS 1edcc1ab
END DESCRIPTION:
XS GIS Cut Line= 3
      2914486.48      6933186.97      2914664.44      6932861.43
      2914768.15      6932468.19
#Sta/Elev= 30
  4639.9  414.39  4691.2  413.05  4707.3  408.12  4721.9  405.89  4749.4  404.47
  4772.8  402.83  4794.6  403.82  4801.7  408.61  4810.7  412.12  4824.5  412.21
  4832.5  409.79  4838.2  410.18  4847.3  405.06  4852.8  399.52  4854.4  397.96
  4860.0  399.27  4876.2  394.05  4919.8  394.36  4927.1  397.34  4963.5  399.21
  4992.4  393.47  4992.9  392.67  4998.4  393.47  5001.4  396.38  5010.9  395.72
  5017.2  399.52  5027.7  401.70  5113.5  407.86  5264.3  422.97  5417.6  428.37
#Mann=5,-1,0
  4639.9    0.08       0  4749.4    0.16       0  4992.4    0.07       0
  4998.4    0.16       0  5264.3    0.05       0
Bank Sta=4852.8,5017.2
Exp/Cntr=0.3,0.1

Type RM Length L Ch R = 1,27496,434,434,434
BEGIN DESCRIPTION:
Mapping XS c8ae4449
END DESCRIPTION:
XS GIS Cut Line= 3
      2914838.06      6933191.28      2914985.62      6932878.79
      2914985.62      6932410.06
#Sta/Elev= 30
  4674.8  412.84  4700.9  411.70  4723.3  409.97  4777.0  409.52  4797.1  408.46
  4814.4  401.72  4819.9  402.22  4825.5  398.65  4842.7  400.95  4871.0  399.97
  4888.2  407.91  4891.5  407.70  4902.9  408.48  4916.5  407.77  4925.0  404.63
  4933.8  399.73  4939.3  399.96  4944.0  398.04  4947.2  396.74  4999.1  391.92
  4999.6  391.12  5005.1  391.92  5013.5  393.22  5019.7  395.56  5102.5  398.04
  5154.2  400.79  5174.2  404.73  5214.2  408.42  5280.9  418.07  5489.1  426.03
#Mann=7,-1,0
  4674.8    0.08       0  4700.9     0.1       0  4777.0    0.08       0
  4891.5    0.16       0  4999.1    0.07       0  5005.1    0.16       0
  5280.9    0.05       0
Bank Sta=4944,5102.5
Exp/Cntr=0.3,0.1

Type RM Length L Ch R = 1,27062,316,316,316
BEGIN DESCRIPTION:
Mapping XS f85b0640
END DESCRIPTION:
XS GIS Cut Line= 3
      2915306.79      6933108.86      2915402.29      6932839.73
      2915337.42      6932368.34
#Sta/Elev= 30
  4697.7  409.49  4754.9  404.47  4799.8  403.77  4824.3  394.96  4853.7  393.90
  4871.6  394.56  4881.8  399.72  4887.1  398.79  4892.8  401.64  4903.4  402.42
  4912.7  399.49  4918.0  400.25  4924.6  395.02  4935.2  392.29  4948.8  391.04
  4967.1  393.44  4979.7  392.65  4993.6  389.33  4994.1  388.53  4999.6  389.33
  5008.2  393.26  5059.0  394.96  5073.6  398.44  5078.9  401.93  5109.2  412.30
  5145.6  420.38  5169.7  423.52  5254.9  427.16  5381.7  433.66  5459.1  434.89
#Mann=5,-1,0
  4697.7    0.08       0  4853.7    0.16       0  4993.6    0.07       0
  4999.6    0.16       0  5254.9    0.05       0
Bank Sta=4824.3,5059
Exp/Cntr=0.3,0.1

Type RM Length L Ch R = 1,26746,308,308,308
BEGIN DESCRIPTION:
Mapping XS cecc6e20
END DESCRIPTION:
XS GIS Cut Line= 3
      2915558.52      6933078.48      2915714.79      6932735.56
      2915550.46      6932298.79
#Sta/Elev= 30
  4643.2  407.04  4695.7  406.40  4718.8  401.79  4770.4  401.19  4787.9  396.68
  4793.4  397.38  4806.6  392.30  4841.1  391.21  4855.8  391.87  4862.6  397.13
  4868.1  396.15  4891.1  398.75  4899.8  396.93  4908.7  392.52  4914.1  393.37
  4931.7  389.28  4965.7  389.92  4995.7  386.83  4996.2  386.03  5001.7  386.83
  5006.3  391.58  5011.8  390.13  5016.1  392.30  5090.3  407.23  5150.7  414.27
  5260.9  419.32  5285.8  418.42  5383.0  422.28  5426.3  424.85  5486.7  432.16
#Mann=5,-1,0
  4643.2    0.08       0  4841.1    0.16       0  4995.7    0.07       0
  5001.7    0.16       0  5383.0    0.05       0
Bank Sta=4806.6,5016.1
Exp/Cntr=0.3,0.1

Type RM Length L Ch R = 1,26438,294,294,294
BEGIN DESCRIPTION:
Mapping XS f3acad38
END DESCRIPTION:
XS GIS Cut Line= 3
      2915875.37      6933000.34      2916009.93      6932666.12
      2915897.08      6932262.48
#Sta/Elev= 30
  4655.7  404.43  4697.0  403.55  4721.2  399.23  4780.3  397.97  4799.1  391.48
  4804.5  392.28  4811.2  390.12  4823.2  387.43  4839.4  387.49  4866.3  388.63
  4877.0  393.24  4882.4  392.19  4887.8  395.17  4898.6  395.51  4906.5  392.64
  4911.9  393.40  4920.2  389.73  4930.7  387.74  4989.8  387.55  4992.6  386.18
  4993.1  385.38  4998.6  386.18  5013.9  388.16  5053.2  388.37  5072.0  390.12
  5234.3  407.32  5239.5  406.62  5313.0  413.72  5386.4  425.12  5435.1  430.16
#Mann=4,-1,0
  4655.7    0.08       0  4839.4    0.16       0  4992.6    0.07       0
  4998.6    0.16       0
Bank Sta=4811.2,5072
Exp/Cntr=0.3,0.1

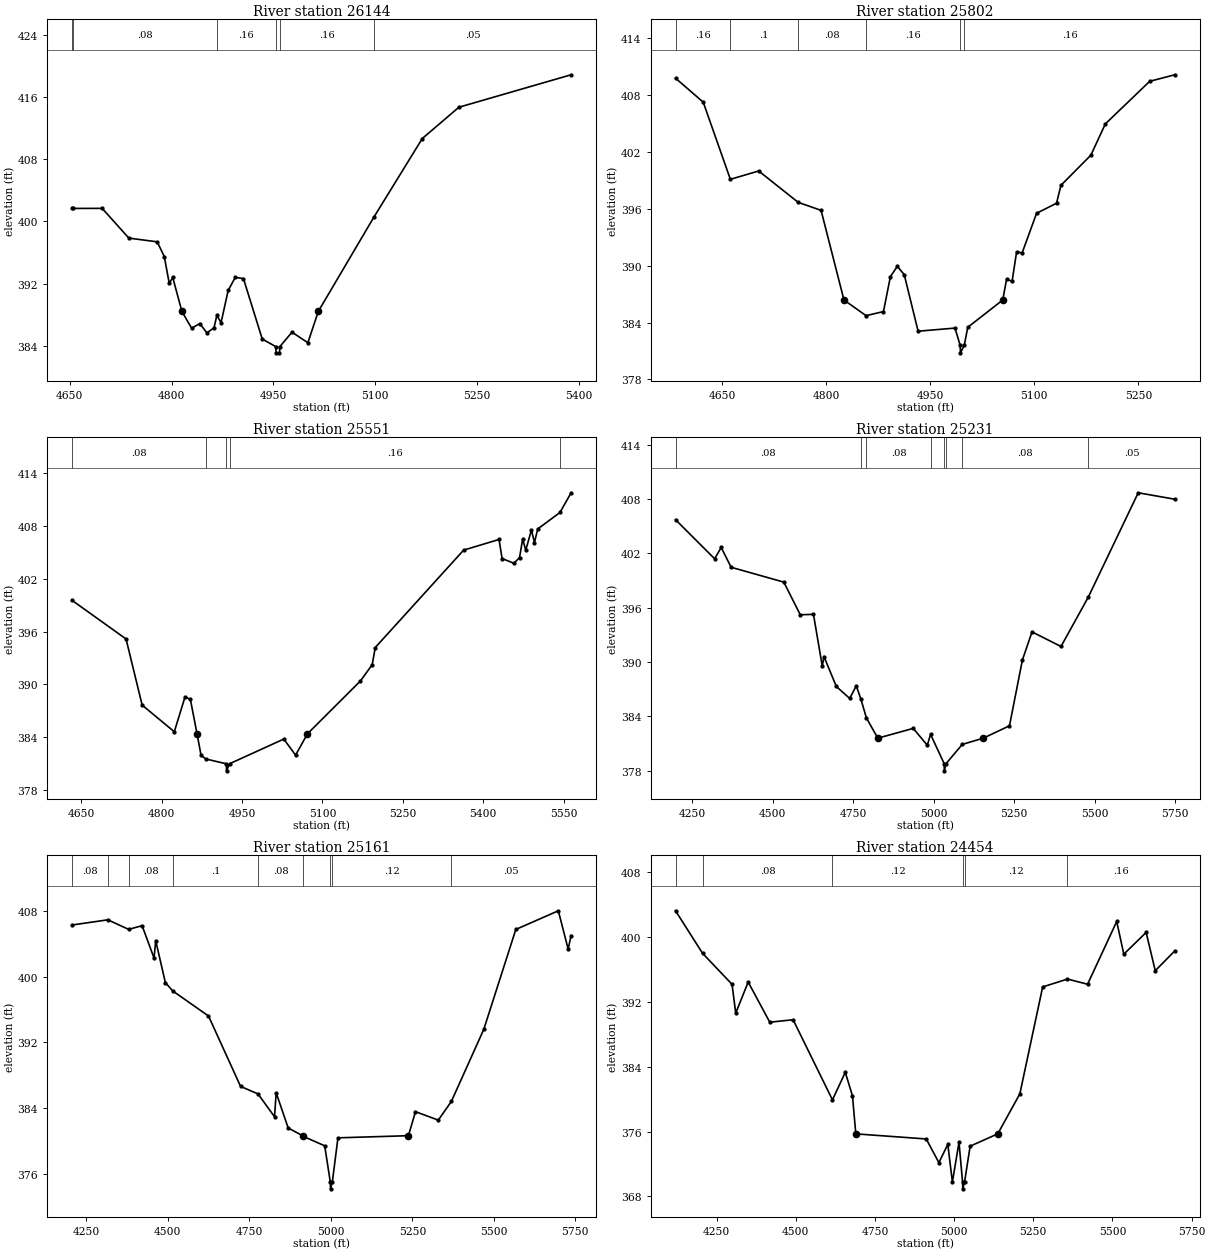
Type RM Length L Ch R = 1,26144,342,342,342
BEGIN DESCRIPTION:
Mapping XS 688a44ba
END DESCRIPTION:
XS GIS Cut Line= 3
      2916187.88      6932935.19      2916287.70      6932605.35
      2916150.09      6932239.81
#Sta/Elev= 30
  4653.2  401.67  4654.9  401.67  4697.7  401.68  4737.0  397.86  4778.8  397.38
  4789.2  395.49  4796.5  392.05  4801.7  392.80  4815.1  388.45  4829.5  386.28
  4841.5  386.88  4851.9  385.69  4862.4  386.32  4866.7  387.95  4872.8  386.99
  4883.3  391.13  4893.7  392.81  4905.8  392.66  4933.5  384.89  4953.4  383.92
  4953.9  383.12  4958.9  383.12  4959.4  383.92  4977.3  385.77  5000.7  384.42
  5016.1  388.45  5097.9  400.55  5169.2  410.65  5223.1  414.67  5388.4  418.84
#Mann=6,-1,0
  4653.2     0.1       0  4654.9    0.08       0  4866.7    0.16       0
  4953.4    0.07       0  4959.4    0.16       0  5097.9    0.05       0
Bank Sta=4815.1,5016.1
Exp/Cntr=0.3,0.1

Type RM Length L Ch R = 1,25802,251,251,251
BEGIN DESCRIPTION:
BLACK CREEK 44.0
END DESCRIPTION:
XS GIS Cut Line= 3
      2916625.00      6932925.01      2916625.00      6932525.00
      2916374.97      6932324.98
#Sta/Elev= 30
  4582.3  409.76  4622.3  407.23  4661.4  399.10  4702.3  399.98  4759.3  396.67
  4792.3  395.83  4825.3  386.38  4857.2  384.73  4882.3  385.16  4892.3  388.84
  4902.3  389.93  4912.3  389.05  4932.3  383.09  4985.5  383.42  4992.9  381.61
  4993.4  380.81  4998.9  381.61  5003.9  383.50  5054.4  386.38  5059.9  388.56
  5067.9  388.36  5074.4  391.45  5082.4  391.35  5103.2  395.52  5132.0  396.58
  5138.4  398.47  5181.6  401.65  5202.4  404.94  5266.4  409.43  5302.5  410.12
#Mann=6,-1,0
  4582.3    0.16       0  4661.4     0.1       0  4759.3    0.08       0
  4857.2    0.16       0  4992.9    0.07       0  4998.9    0.16       0
Bank Sta=4825.3,5054.4
Exp/Cntr=0.3,0.1

Type RM Length L Ch R = 1,25551,320,320,320
BEGIN DESCRIPTION:
Mapping XS 81fff47e
END DESCRIPTION:
XS GIS Cut Line= 3
      2916834.58      6932765.94      2916825.90      6932384.00
      2916339.85      6932127.96
#Sta/Elev= 30
  4632.5  399.54  4733.5  395.15  4763.5  387.66  4823.5  384.64  4843.5  388.59
  4853.5  388.31  4865.9  384.41  4873.5  381.95  4882.5  381.55  4920.5  381.01
  4921.0  380.21  4926.5  381.01  5027.8  383.81  5049.8  381.99  5072.0  384.41
  5170.7  390.39  5192.8  392.24  5198.4  394.18  5363.3  405.22  5429.4  406.43
  5435.1  404.27  5457.1  403.73  5467.7  404.38  5473.5  406.48  5479.2  405.22
  5489.9  407.49  5495.5  406.08  5501.6  407.62  5543.1  409.49  5563.9  411.72
#Mann=5,-1,0
  4632.5    0.08       0  4882.5    0.16       0  4920.5    0.07       0
  4926.5    0.16       0  5543.1    0.05       0
Bank Sta=4865.9,5072
Exp/Cntr=0.3,0.1

Type RM Length L Ch R = 1,25231,70,70,70
BEGIN DESCRIPTION:
Mapping XS 10d0278b
END DESCRIPTION:
XS GIS Cut Line= 3
      2916921.39      6933043.72      2917099.34      6932236.43
      2917077.64      6931511.62
#Sta/Elev= 30
  4197.4  405.73  4319.0  401.41  4339.4  402.66  4370.2  400.47  4534.0  398.83
  4585.2  395.22  4626.2  395.27  4653.6  389.54  4658.8  390.61  4697.3  387.30
  4738.8  385.98  4759.3  387.37  4773.8  385.89  4790.8  383.82  4826.3  381.59
  4936.4  382.67  4980.1  380.81  4990.2  382.01  5032.5  378.78  5033.0  377.98
  5038.5  378.78  5088.8  380.90  5154.2  381.59  5235.6  382.96  5275.6  390.21
  5305.6  393.33  5395.7  391.72  5480.7  397.18  5635.8  408.70  5749.2  407.99
#Mann=8,-1,0
  4197.4    0.08       0  4773.8     0.1       0  4790.8    0.08       0
  4990.2    0.05       0  5032.5    0.04       0  5038.5    0.05       0
  5088.8    0.08       0  5480.7    0.05       0
Bank Sta=4826.3,5154.2
Exp/Cntr=0.3,0.1

Type RM Length L Ch R = 1,25161,707,707,707
BEGIN DESCRIPTION:
Mapping XS ddb1d5bd
END DESCRIPTION:
XS GIS Cut Line= 4
      2917012.53      6933026.37      2917164.44      6932232.09
      2917238.23      6931728.62      2917220.86      6931515.95
#Sta/Elev= 30
  4206.1  406.27  4316.3  406.90  4379.9  405.74  4421.3  406.19  4457.9  402.25
  4463.0  404.37  4492.6  399.27  4515.4  398.25  4624.9  395.21  4723.3  386.65
  4776.7  385.74  4827.4  382.96  4832.5  385.87  4869.3  381.60  4913.5  380.66
  4915.9  380.57  4981.3  379.43  4998.6  375.00  4999.1  374.20  5004.6  375.00
  5021.9  380.40  5238.0  380.66  5259.7  383.58  5329.6  382.55  5369.7  384.82
  5469.3  393.60  5567.4  405.73  5697.8  408.00  5727.9  403.34  5737.0  404.99
#Mann=9,-1,0
  4206.1    0.08       0  4316.3    0.16       0  4379.9    0.08       0
  4515.4     0.1       0  4776.7    0.08       0  4915.9    0.12       0
  4998.6    0.07       0  5004.6    0.12       0  5369.7    0.05       0
Bank Sta=4913.5,5238
Exp/Cntr=0.3,0.1

Type RM Length L Ch R = 1,24454,255,255,255
BEGIN DESCRIPTION:
BLACK CREEK 41.0
END DESCRIPTION:
XS GIS Cut Line= 3
      2917381.44      6932826.74      2917750.00      6932050.00
      2917303.36      6931489.94
#Sta/Elev= 30
  4120.4  403.22  4205.7  397.98  4298.8  394.15  4310.5  390.60  4349.8  394.43
  4418.0  389.48  4491.7  389.78  4615.9  379.90  4656.4  383.30  4679.1  380.39
  4689.6  375.71  4912.0  375.08  4951.9  372.16  4980.1  374.41  4994.6  369.77
  5015.4  374.67  5026.8  369.73  5027.3  368.93  5032.8  369.73  5050.6  374.19
  5137.8  375.71  5207.5  380.64  5279.6  393.83  5358.0  394.80  5421.4  394.16
  5513.4  401.90  5535.8  397.87  5606.3  400.55  5635.1  395.83  5696.5  398.26
#Mann=6,-1,0
  4120.4    0.16       0  4205.7    0.08       0  4615.9    0.12       0
  5026.8    0.07       0  5032.8    0.12       0  5358.0    0.16       0
Bank Sta=4689.6,5137.8
Exp/Cntr=0.3,0.1

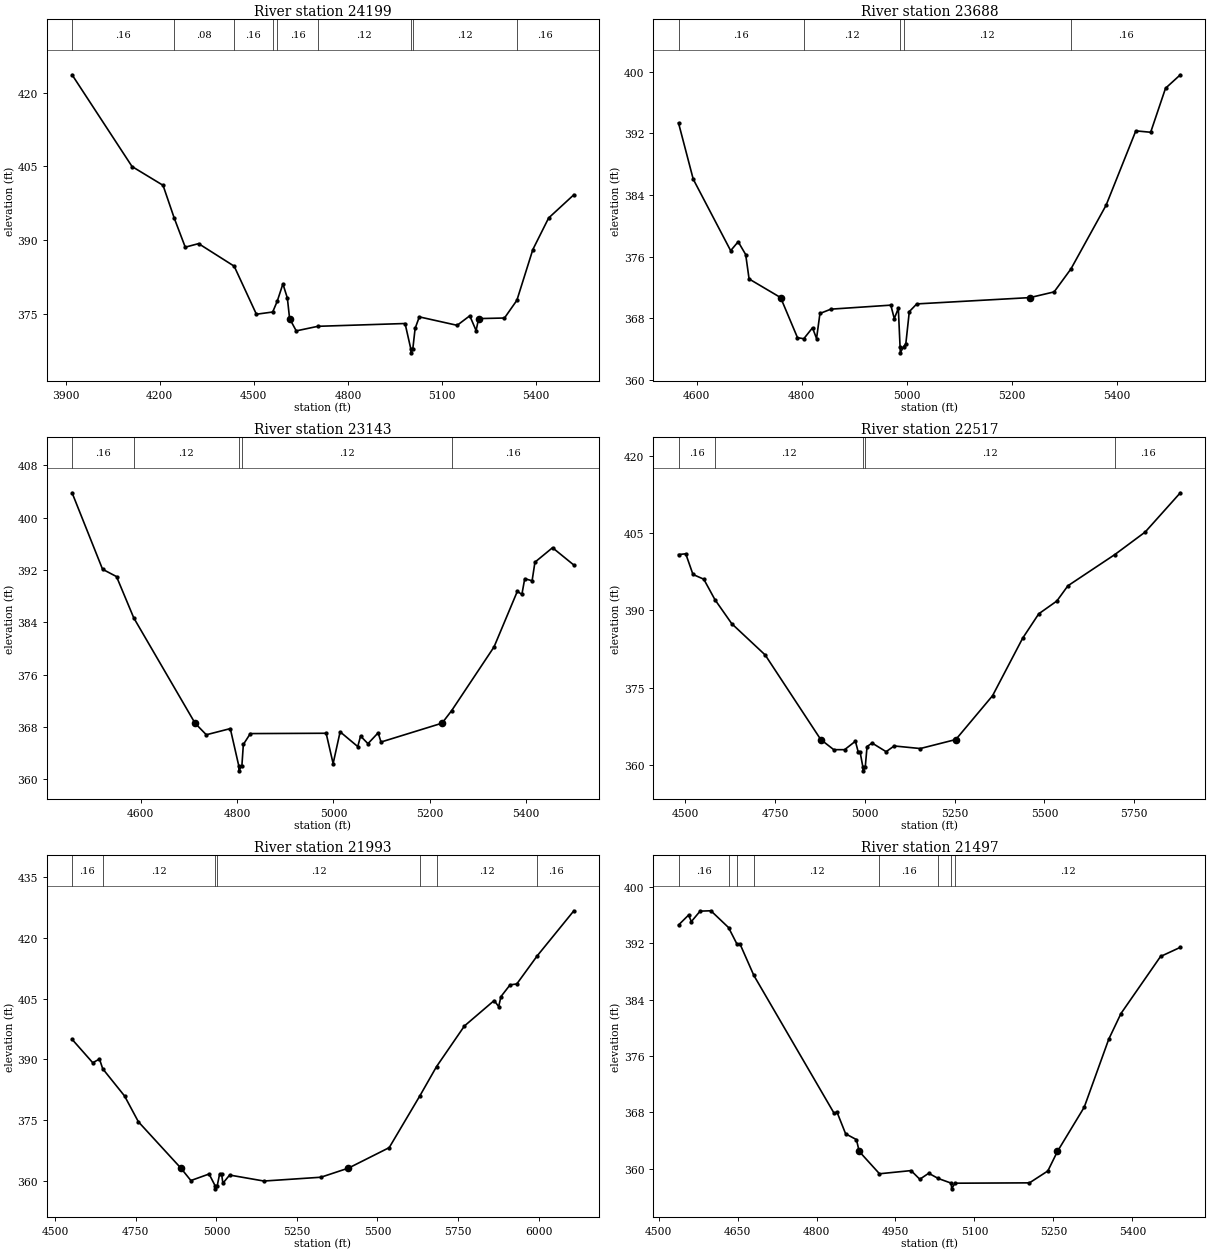
Type RM Length L Ch R = 1,24199,511,511,511
BEGIN DESCRIPTION:
BLACK CREEK 40.0
END DESCRIPTION:
XS GIS Cut Line= 3
      2918675.00      6932675.00      2917925.00      6931875.00
      2917975.00      6931374.98
#Sta/Elev= 30
  3920.7  423.64  4111.9  404.96  4210.6  401.14  4246.2  394.48  4281.4  388.55
  4323.9  389.27  4437.3  384.68  4508.1  374.90  4560.0  375.35  4574.5  377.54
  4592.6  381.07  4606.8  378.19  4613.9  374.01  4635.1  371.51  4704.1  372.44
  4981.9  373.01  5000.2  367.84  5000.7  367.04  5006.6  367.84  5013.9  372.00
  5027.3  374.36  5147.9  372.64  5188.1  374.58  5208.2  371.58  5216.4  374.01
  5298.7  374.13  5338.2  377.73  5389.1  388.07  5439.4  394.49  5519.8  399.22
#Mann=9,-1,0
  3920.7    0.16       0  4246.2    0.08       0  4437.3    0.16       0
  4560.0    0.12       0  4574.5    0.16       0  4704.1    0.12       0
  5000.2    0.07       0  5006.6    0.12       0  5338.2    0.16       0
Bank Sta=4613.9,5216.4
Exp/Cntr=0.3,0.1

Type RM Length L Ch R = 1,23688,545,545,545
BEGIN DESCRIPTION:
BLACK CREEK 39.0
END DESCRIPTION:
XS GIS Cut Line= 3
      2918724.99      6931974.99      2918375.00      6931675.00
      2918025.03      6931325.03
#Sta/Elev= 30
  4565.4  393.35  4593.4  386.06  4664.7  376.78  4679.0  377.94  4693.3  376.28
  4699.8  373.11  4759.9  370.69  4792.0  365.49  4804.0  365.35  4820.6  366.77
  4828.3  365.38  4834.8  368.63  4855.7  369.19  4969.8  369.71  4976.4  367.96
  4984.1  369.30  4987.4  364.32  4987.9  363.52  4994.0  364.32  4998.4  364.70
  5005.0  368.87  5019.2  369.87  5234.9  370.69  5280.9  371.43  5313.0  374.42
  5379.9  382.68  5436.5  392.33  5464.8  392.15  5493.1  397.86  5521.3  399.61
#Mann=5,-1,0
  4565.4    0.16       0  4804.0    0.12       0  4987.4    0.07       0
  4994.0    0.12       0  5313.0    0.16       0
Bank Sta=4759.9,5234.9
Exp/Cntr=0.3,0.1

Type RM Length L Ch R = 1,23143,626,626,626
BEGIN DESCRIPTION:
BLACK CREEK 38.0
END DESCRIPTION:
XS GIS Cut Line= 3
      2919124.99      6931874.98      2918775.00      6931425.00
      2918374.97      6931174.98
#Sta/Elev= 30
  4457.4  403.78  4520.7  392.10  4549.7  390.98  4585.5  384.67  4712.7  368.59
  4736.1  366.82  4785.9  367.76  4803.4  362.11  4803.9  361.31  4810.0  362.11
  4813.0  365.34  4827.5  367.00  4984.9  367.05  4999.4  362.42  5013.9  367.27
  5050.5  365.02  5056.4  366.62  5071.7  365.46  5092.9  367.12  5098.8  365.71
  5225.5  368.59  5245.5  370.51  5333.5  380.24  5381.8  388.72  5391.3  388.26
  5397.2  390.66  5412.5  390.34  5418.4  393.18  5454.9  395.39  5499.2  392.74
#Mann=5,-1,0
  4457.4    0.16       0  4585.5    0.12       0  4803.4    0.07       0
  4810.0    0.12       0  5245.5    0.16       0
Bank Sta=4712.7,5225.5
Exp/Cntr=0.3,0.1

Type RM Length L Ch R = 1,22517,524,524,524
BEGIN DESCRIPTION:
BLACK CREEK 37.0
END DESCRIPTION:
XS GIS Cut Line= 3
      2919275.00      6931824.98      2919325.00      6931325.00
      2918925.00      6930525.00
#Sta/Elev= 30
  4481.5  400.83  4501.6  400.97  4521.7  396.96  4551.8  396.04  4582.9  392.06
  4629.7  387.40  4722.7  381.33  4877.4  364.91  4913.6  362.94  4943.8  362.94
  4973.9  364.58  4981.5  362.54  4986.8  362.54  4994.5  359.63  4995.0  358.83
  5001.4  359.63  5006.3  363.55  5020.3  364.23  5059.4  362.55  5081.8  363.66
  5154.5  363.16  5253.4  364.91  5355.7  373.42  5439.6  384.60  5484.3  389.32
  5534.6  391.80  5565.4  394.76  5696.0  400.82  5780.6  405.20  5878.4  412.82
#Mann=5,-1,0
  4481.5    0.16       0  4582.9    0.12       0  4994.5    0.07       0
  5001.4    0.12       0  5696.0    0.16       0
Bank Sta=4877.4,5253.4
Exp/Cntr=0.3,0.1

Type RM Length L Ch R = 1,21993,496,496,496
BEGIN DESCRIPTION:
BLACK CREEK 36.0
END DESCRIPTION:
XS GIS Cut Line= 3
      2920125.00      6931425.00      2919775.00      6931125.00
      2919024.98      6930324.98
#Sta/Elev= 30
  4552.0  394.92  4616.2  389.13  4637.1  390.04  4647.1  387.64  4715.0  380.90
  4757.8  374.53  4889.7  363.07  4920.8  359.99  4977.3  361.61  4995.8  358.74
  4996.3  357.94  5002.7  358.74  5009.7  361.49  5016.4  361.49  5020.1  359.32
  5041.1  361.35  5147.5  359.87  5324.4  360.81  5410.0  363.07  5536.4  368.13
  5632.1  381.01  5683.3  388.17  5769.9  398.22  5862.2  404.51  5876.3  403.01
  5883.2  405.48  5911.5  408.38  5932.5  408.62  5995.8  415.56  6109.6  426.71
#Mann=7,-1,0
  4552.0    0.16       0  4647.1    0.12       0  4995.8    0.07       0
  5002.7    0.12       0  5632.1    0.16       0  5683.3    0.12       0
  5995.8    0.16       0
Bank Sta=4889.7,5410
Exp/Cntr=0.3,0.1

Type RM Length L Ch R = 1,21497,562,562,562
BEGIN DESCRIPTION:
BLACK CREEK 35.0
END DESCRIPTION:
XS GIS Cut Line= 3
      2920125.00      6931374.99      2920225.00      6930925.00
      2920025.00      6930475.01
#Sta/Elev= 30
  4537.8  394.60  4557.0  396.02  4562.1  395.08  4578.8  396.57  4599.3  396.62
  4632.8  394.24  4649.1  391.85  4654.3  391.95  4680.9  387.44  4833.6  367.84
  4838.7  368.07  4855.3  364.95  4875.8  364.13  4881.1  362.45  4919.6  359.28
  4979.6  359.73  4996.2  358.50  5013.1  359.35  5031.3  358.61  5056.1  357.94
  5056.6  357.14  5063.1  357.94  5204.6  357.99  5239.5  359.68  5257.7  362.45
  5308.6  368.73  5355.1  378.37  5378.4  382.03  5453.6  390.13  5491.2  391.43
#Mann=8,-1,0
  4537.8    0.16       0  4632.8    0.12       0  4649.1    0.16       0
  4680.9    0.12       0  4919.6    0.16       0  5031.3    0.12       0
  5056.1    0.07       0  5063.1    0.12       0
Bank Sta=4881.1,5257.7
Exp/Cntr=0.3,0.1