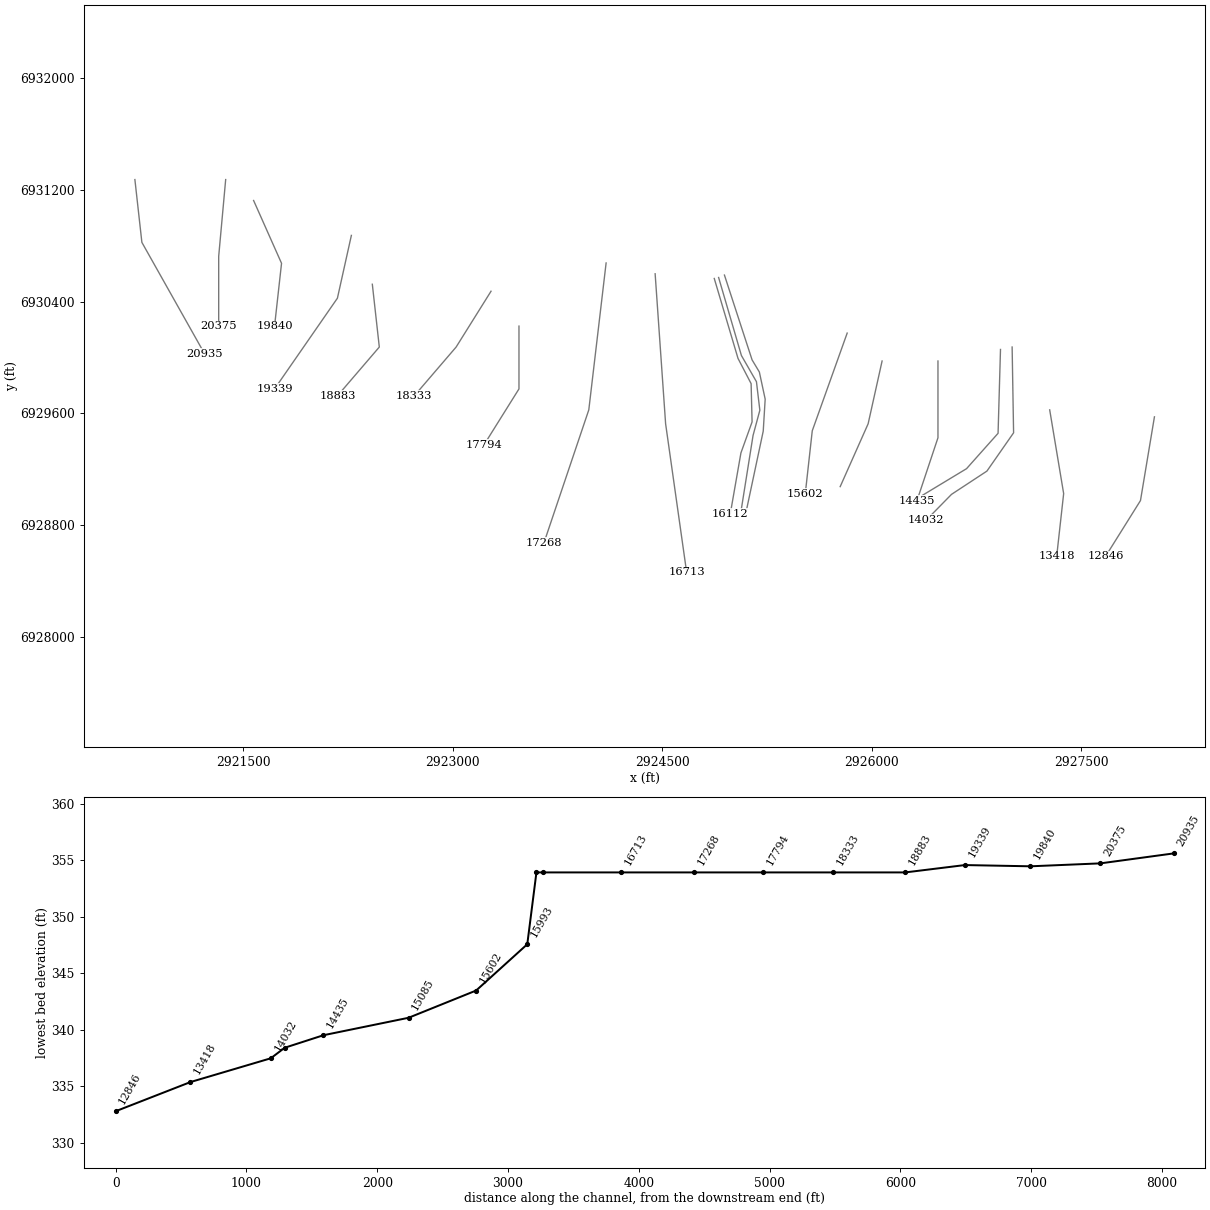
HEC-RAS study BLACK CREEK.prj: BLACK CREEK Base Level Engineering

--- BLACK CREEK.g01 (geometry) --- (continued)

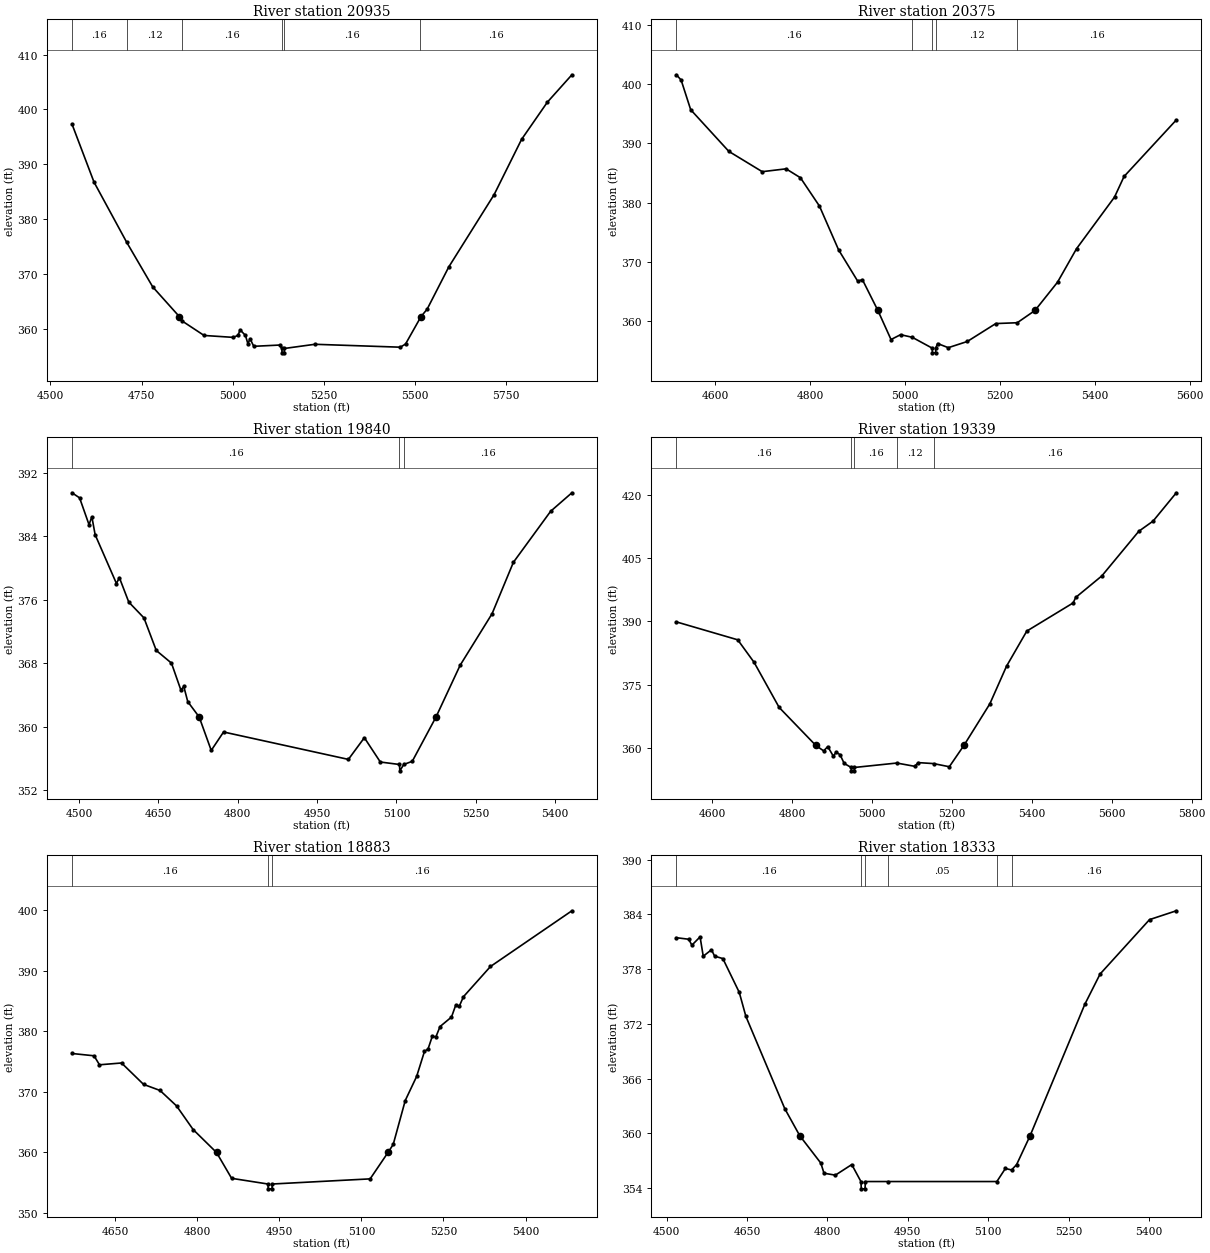
Type RM Length L Ch R = 1,20935,560,560,560
BEGIN DESCRIPTION:
BLACK CREEK 34.0
END DESCRIPTION:
XS GIS Cut Line= 3
      2920725.00      6931275.03      2920775.00      6930825.00
      2921225.01      6930024.98
#Sta/Elev= 30
  4559.3  397.34  4619.7  386.75  4709.4  375.76  4780.7  367.63  4854.0  362.19
  4861.8  361.39  4921.5  358.77  5002.0  358.42  5015.0  358.82  5020.1  359.81
  5035.0  358.77  5041.7  357.24  5047.5  358.18  5057.7  356.79  5128.4  357.02
  5134.7  356.40  5135.2  355.60  5141.4  355.60  5142.0  356.40  5225.3  357.16
  5459.6  356.63  5473.9  357.21  5513.8  361.92  5516.1  362.19  5533.2  363.58
  5592.5  371.28  5716.8  384.47  5792.0  394.54  5862.7  401.33  5930.0  406.33
#Mann=6,-1,0
  4559.3    0.16       0  4709.4    0.12       0  4861.8    0.16       0
  5134.7    0.07       0  5142.0    0.16       0  5513.8    0.16       0
Bank Sta=4854,5516.1
Exp/Cntr=0.3,0.1

Type RM Length L Ch R = 1,20375,535,535,535
BEGIN DESCRIPTION:
BLACK CREEK 33.0
END DESCRIPTION:
XS GIS Cut Line= 3
      2921375.00      6931274.99      2921325.00      6930725.00
      2921325.00      6930224.95
#Sta/Elev= 30
  4518.6  401.55  4528.6  400.66  4548.7  395.67  4629.0  388.65  4699.3  385.23
  4749.5  385.71  4779.7  384.21  4819.8  379.43  4860.0  372.07  4900.2  366.80
  4910.2  367.04  4942.7  361.86  4970.4  356.96  4990.5  357.78  5015.0  357.34
  5056.9  355.52  5057.6  354.72  5064.1  354.72  5064.7  355.52  5068.3  356.29
  5090.9  355.59  5130.9  356.63  5190.9  359.65  5236.1  359.79  5273.5  361.86
  5320.9  366.62  5360.9  372.26  5440.9  380.96  5460.9  384.42  5570.9  393.94
#Mann=5,-1,0
  4518.6    0.16       0  5015.0    0.12       0  5056.9    0.07       0
  5064.7    0.12       0  5236.1    0.16       0
Bank Sta=4942.7,5273.5
Exp/Cntr=0.3,0.1

Type RM Length L Ch R = 1,19840,501,501,501
BEGIN DESCRIPTION:
BLACK CREEK 32.0
END DESCRIPTION:
XS GIS Cut Line= 3
      2921574.99      6931125.02      2921775.00      6930675.00
      2921725.00      6930225.03
#Sta/Elev= 30
  4486.6  389.46  4501.0  388.82  4518.8  385.45  4524.2  386.44  4530.4  384.18
  4570.7  378.04  4576.2  378.78  4594.0  375.70  4622.7  373.71  4646.0  369.61
  4674.7  368.02  4692.5  364.63  4698.0  365.08  4705.5  363.17  4727.1  361.24
  4749.9  357.03  4773.2  359.35  5009.2  355.90  5039.4  358.63  5069.6  355.57
  5105.8  355.26  5106.5  354.46  5113.9  355.26  5130.0  355.66  5174.9  361.24
  5220.5  367.75  5280.9  374.24  5321.2  380.71  5391.6  387.13  5431.8  389.46
#Mann=3,-1,0
  4486.6    0.16       0  5105.8    0.07       0  5113.9    0.16       0
Bank Sta=4727.1,5174.9
Exp/Cntr=0.3,0.1

Type RM Length L Ch R = 1,19339,456,456,456
BEGIN DESCRIPTION:
BLACK CREEK 31.0
END DESCRIPTION:
XS GIS Cut Line= 3
      2922274.99      6930874.95      2922175.00      6930425.00
      2921725.00      6929775.00
#Sta/Elev= 30
  4510.1  389.89  4663.7  385.64  4704.7  380.29  4767.4  369.60  4859.0  360.61
  4878.8  359.30  4889.1  360.33  4903.2  358.00  4909.6  359.00  4919.8  358.41
  4930.1  356.33  4947.7  355.37  4948.4  354.57  4955.2  354.57  4955.9  355.37
  5061.9  356.42  5106.8  355.64  5115.6  356.52  5153.9  356.29  5193.3  355.54
  5230.0  360.61  5294.7  370.44  5336.6  379.39  5387.3  387.71  5503.5  394.40
  5509.6  395.68  5575.1  400.79  5667.7  411.38  5703.5  413.80  5761.6  420.51
#Mann=5,-1,0
  4510.1    0.16       0  4947.7    0.07       0  4955.9    0.16       0
  5061.9    0.12       0  5153.9    0.16       0
Bank Sta=4859,5230
Exp/Cntr=0.3,0.1

Type RM Length L Ch R = 1,18883,550,550,550
BEGIN DESCRIPTION:
BLACK CREEK 30.0
END DESCRIPTION:
XS GIS Cut Line= 3
      2922425.00      6930525.01      2922475.00      6930075.00
      2922174.97      6929724.97
#Sta/Elev= 30
  4571.0  376.32  4611.3  375.94  4621.3  374.45  4661.6  374.75  4701.8  371.21
  4732.0  370.20  4762.2  367.64  4792.4  363.74  4835.2  359.94  4862.8  355.66
  4929.1  354.72  4929.8  353.92  4936.6  353.92  4937.3  354.72  5116.0  355.57
  5148.7  359.94  5158.2  361.27  5180.2  368.54  5201.0  372.52  5215.3  376.66
  5221.9  377.08  5229.6  379.16  5236.2  379.07  5243.8  380.78  5264.7  382.35
  5272.4  384.30  5279.0  384.15  5286.6  385.72  5336.0  390.72  5484.8  399.94
#Mann=3,-1,0
  4571.0    0.16       0  4929.1    0.07       0  4937.3    0.16       0
Bank Sta=4835.2,5148.7
Exp/Cntr=0.3,0.1

Type RM Length L Ch R = 1,18333,539,539,539
BEGIN DESCRIPTION:
BLACK CREEK 29.0
END DESCRIPTION:
XS GIS Cut Line= 3
      2923275.00      6930475.00      2923025.00      6930075.00
      2922724.99      6929724.98
#Sta/Elev= 30
  4518.3  381.44  4541.3  381.27  4547.2  380.62  4562.5  381.53  4568.4  379.41
  4583.8  380.12  4589.6  379.42  4605.0  379.15  4635.6  375.45  4648.0  372.81
  4720.5  362.71  4748.5  359.74  4787.8  356.74  4793.7  355.63  4814.9  355.42
  4845.5  356.58  4862.6  354.72  4863.3  353.92  4870.2  353.92  4871.0  354.72
  4912.9  354.72  5116.2  354.72  5132.1  356.15  5143.6  355.99  5153.0  356.57
  5178.2  359.74  5280.3  374.14  5308.8  377.46  5401.0  383.42  5451.0  384.39
#Mann=6,-1,0
  4518.3    0.16       0  4862.6   0.033       0  4871.0    0.16       0
  4912.9    0.05       0  5116.2    0.12       0  5143.6    0.16       0
Bank Sta=4748.5,5178.2
Exp/Cntr=0.3,0.1

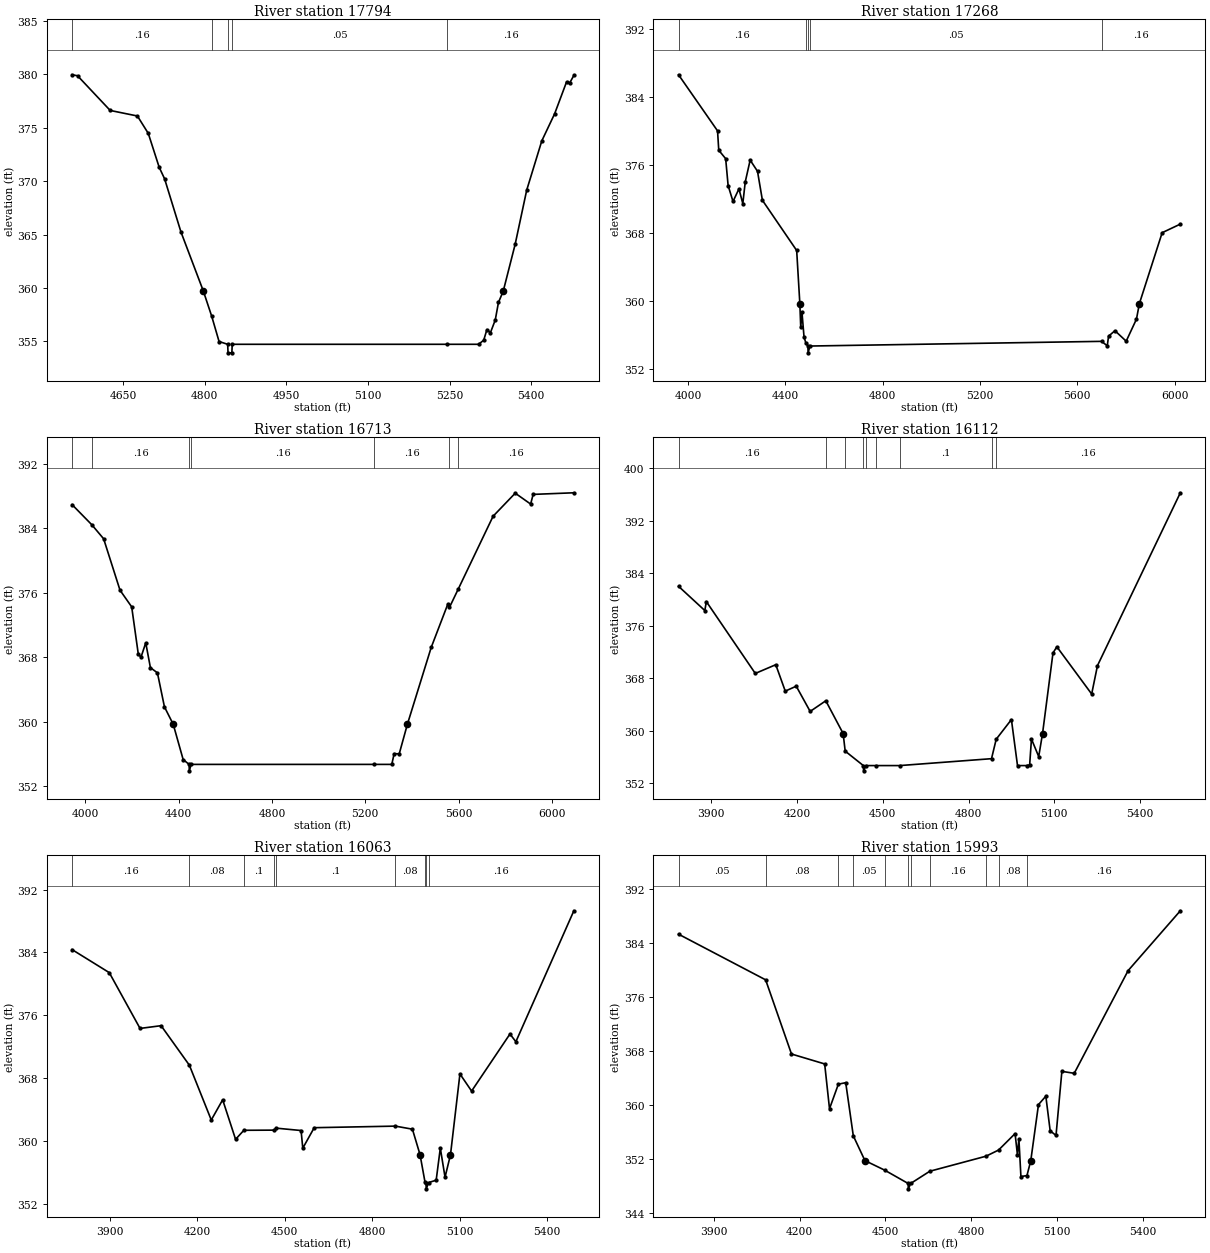
Type RM Length L Ch R = 1,17794,526,526,526
BEGIN DESCRIPTION:
BLACK CREEK 28.0
END DESCRIPTION:
XS GIS Cut Line= 3
      2923475.00      6930225.04      2923475.00      6929775.00
      2923225.02      6929375.04
#Sta/Elev= 30
  4556.6  379.96  4566.6  379.87  4626.6  376.62  4676.6  376.10  4696.6  374.47
  4716.6  371.30  4726.6  370.21  4756.6  365.24  4797.7  359.71  4813.2  357.33
  4826.6  354.98  4842.4  354.72  4843.1  353.92  4850.1  353.92  4850.8  354.72
  5245.7  354.72  5303.2  354.72  5312.7  355.10  5318.6  356.10  5325.0  355.80
  5333.9  356.99  5339.8  358.64  5348.6  359.70  5370.4  364.07  5391.7  369.16
  5419.4  373.77  5443.0  376.31  5464.8  379.28  5470.7  379.20  5478.3  379.90
#Mann=5,-1,0
  4556.6    0.16       0  4813.2    0.05       0  4842.4   0.033       0
  4850.8    0.05       0  5245.7    0.16       0
Bank Sta=4797.7,5348.6
Exp/Cntr=0.3,0.1

Type RM Length L Ch R = 1,17268,555,555,555
BEGIN DESCRIPTION:
BLACK CREEK 27.0
END DESCRIPTION:
XS GIS Cut Line= 3
      2924098.96      6930677.51      2923975.00      6929625.00
      2923654.51      6928674.04
#Sta/Elev= 30
  3960.2  386.60  4120.6  380.01  4125.6  377.73  4154.0  376.74  4164.1  373.58
  4184.2  371.71  4208.6  373.19  4224.5  371.46  4234.6  374.02  4254.7  376.57
  4284.9  375.26  4305.1  371.85  4446.0  365.95  4459.0  359.70  4462.7  356.91
  4467.7  358.70  4476.3  355.76  4483.9  355.08  4492.2  354.72  4492.9  353.92
  4500.6  354.72  5699.4  355.27  5723.1  354.75  5728.4  355.88  5754.6  356.52
  5800.9  355.29  5843.1  357.88  5855.1  359.70  5948.8  368.04  6023.5  369.05
#Mann=5,-1,0
  3960.2    0.16       0  4483.9    0.05       0  4492.2   0.033       0
  4500.6    0.05       0  5699.4    0.16       0
Bank Sta=4459,5855.1
Exp/Cntr=0.3,0.1

Type RM Length L Ch R = 1,16713,601,601,601
BEGIN DESCRIPTION:
BLACK CREEK 26.0
END DESCRIPTION:
XS GIS Cut Line= 3
      2924450.00      6930600.01      2924525.00      6929525.00
      2924675.36      6928462.21
#Sta/Elev= 30
  3943.1  386.96  4028.1  384.45  4078.4  382.72  4148.6  376.34  4198.7  374.27
  4227.1  368.38  4238.8  368.04  4258.9  369.81  4278.9  366.73  4309.0  366.08
  4339.1  361.86  4376.8  359.69  4419.3  355.32  4444.8  354.72  4445.6  353.92
  4453.8  354.72  5236.7  354.72  5313.6  354.72  5323.7  356.05  5345.5  356.03
  5380.4  359.69  5482.5  369.23  5553.5  374.59  5560.9  374.21  5599.5  376.54
  5747.9  385.52  5842.8  388.38  5908.8  387.03  5919.6  388.23  6094.1  388.43
#Mann=7,-1,0
  3943.1    0.05       0  4028.1    0.16       0  4444.8   0.033       0
  4453.8    0.16       0  5236.7    0.16       0  5560.9    0.08       0
  5599.5    0.16       0
Bank Sta=4376.8,5380.4
Exp/Cntr=0.3,0.1

Type RM Length L Ch R = 1,16112,49,49,49
BEGIN DESCRIPTION:
Mapping XS 3f4d4852
END DESCRIPTION:
XS GIS Cut Line= 6
      2924873.28      6930566.37      2925043.41      6929993.50
      2925137.16      6929812.94      2925144.10      6929538.63
      2925064.24      6929316.41      2924987.95      6928879.50
#Sta/Elev= 30
  3785.7  382.00  3877.7  378.31  3882.9  379.68  4054.2  368.74  4125.8  370.07
  4159.0  366.05  4197.4  366.80  4246.1  362.96  4300.8  364.58  4361.4  359.60
  4368.6  356.92  4432.1  354.72  4433.0  353.92  4441.2  354.72  4476.5  354.72
  4559.0  354.72  4880.4  355.77  4896.8  358.73  4950.0  361.72  4971.3  354.72
  5003.1  354.72  5013.8  354.82  5020.1  358.76  5045.5  356.09  5058.9  359.60
  5095.4  371.85  5108.9  372.80  5230.7  365.61  5251.0  369.93  5540.8  396.23
#Mann=9,-1,0
  3785.7    0.16       0  4300.8    0.08       0  4368.6     0.1       0
  4432.1    0.07       0  4441.2     0.1       0  4476.5    0.05       0
  4559.0     0.1       0  4880.4    0.08       0  4896.8    0.16       0
Bank Sta=4361.4,5058.9
Exp/Cntr=0.3,0.1

Type RM Length L Ch R = 1,16063,70,70,70
BEGIN DESCRIPTION:
Mapping XS 785e50f6
END DESCRIPTION:
XS GIS Cut Line= 6
      2924904.51      6930573.39      2925067.71      6930014.33
      2925175.35      6929826.83      2925199.66      6929621.97
      2925151.05      6929441.41      2925067.94      6928918.55
#Sta/Elev= 30
  3770.2  384.36  3897.8  381.43  4003.4  374.33  4075.6  374.68  4172.6  369.65
  4247.7  362.68  4286.8  365.25  4331.1  360.22  4359.5  361.37  4462.6  361.39
  4470.9  361.64  4555.8  361.34  4561.6  359.09  4600.8  361.70  4879.3  361.90
  4937.7  361.51  4963.9  358.26  4980.9  354.77  4984.3  354.72  4985.1  353.92
  4993.4  354.72  5019.2  355.02  5033.4  359.10  5049.6  355.40  5068.3  358.26
  5100.7  368.54  5140.7  366.36  5272.3  373.62  5292.6  372.64  5491.5  389.30
#Mann=9,-1,0
  3770.2    0.16       0  4172.6    0.08       0  4359.5     0.1       0
  4462.6    0.05       0  4470.9     0.1       0  4879.3    0.08       0
  4980.9    0.16       0  4984.3    0.07       0  4993.4    0.16       0
Bank Sta=4963.9,5068.3
Exp/Cntr=0.3,0.1

Type RM Length L Ch R = 1,15993,391,391,391
BEGIN DESCRIPTION:
Mapping XS 4b0f6ef3
END DESCRIPTION:
XS GIS Cut Line= 6
      2924946.17      6930590.75      2925144.10      6929983.08
      2925196.18      6929896.27      2925237.85      6929701.83
      2925223.96      6929472.66      2925102.46      6928899.88
#Sta/Elev= 30
  3776.7  385.33  4081.2  378.56  4171.6  367.56  4287.6  366.09  4304.5  359.45
  4335.5  363.09  4361.2  363.31  4387.7  355.43  4428.3  351.76  4497.4  350.34
  4579.3  348.37  4580.2  347.57  4588.4  348.37  4655.2  350.18  4851.7  352.41
  4895.5  353.32  4953.3  355.76  4961.5  352.62  4966.6  354.99  4973.7  349.39
  4994.8  349.54  5008.2  351.76  5035.1  360.06  5060.8  361.31  5076.0  356.17
  5096.4  355.49  5116.9  364.99  5160.1  364.70  5348.5  379.93  5531.0  388.80
#Mann=11,-1,0
  3776.7    0.05       0  4081.2    0.08       0  4335.5    0.16       0
  4387.7    0.05       0  4497.4     0.1       0  4579.3    0.07       0
  4588.4     0.1       0  4655.2    0.16       0  4851.7     0.1       0
  4895.5    0.08       0  4994.8    0.16       0
Bank Sta=4428.3,5008.2
Exp/Cntr=0.3,0.1

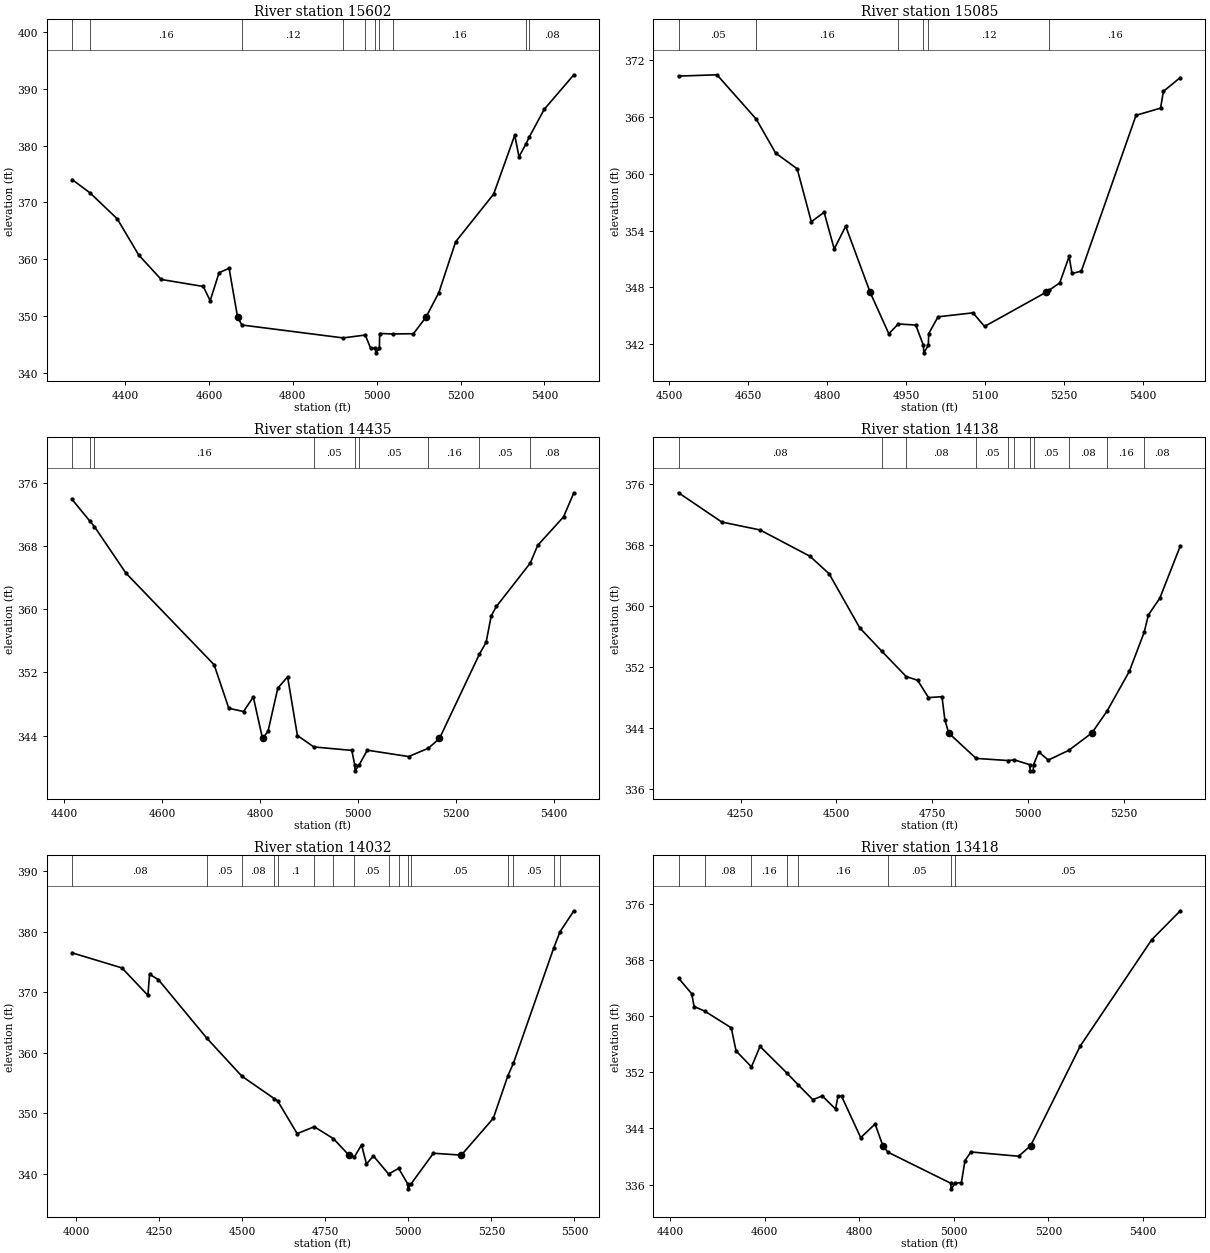
Type RM Length L Ch R = 1,15602,517,517,517
BEGIN DESCRIPTION:
BLACK CREEK 24.0
END DESCRIPTION:
XS GIS Cut Line= 3
      2925825.00      6930174.99      2925575.00      6929475.00
      2925525.00      6929024.96
#Sta/Elev= 30
  4273.9  374.04  4316.8  371.68  4381.7  367.10  4432.6  360.75  4486.3  356.42
  4586.6  355.18  4603.1  352.68  4624.3  357.61  4648.2  358.39  4668.5  349.75
  4678.6  348.39  4920.0  346.11  4972.8  346.62  4985.3  344.33  4997.1  344.28
  4998.0  343.48  5006.5  344.28  5007.1  346.89  5038.1  346.81  5087.6  346.85
  5117.3  349.75  5148.0  354.07  5188.2  363.06  5278.8  371.47  5329.1  381.85
  5339.2  378.06  5356.0  380.33  5363.7  381.54  5399.5  386.43  5470.0  392.51
#Mann=10,-1,0
  4273.9    0.05       0  4316.8    0.16       0  4678.6    0.12       0
  4920.0    0.16       0  4972.8    0.12       0  4997.1    0.07       0
  5006.5    0.12       0  5038.1    0.16       0  5356.0    0.05       0
  5363.7    0.08       0
Bank Sta=4668.5,5117.3
Exp/Cntr=0.3,0.1

Type RM Length L Ch R = 1,15085,650,650,650
BEGIN DESCRIPTION:
BLACK CREEK 23.0
END DESCRIPTION:
XS GIS Cut Line= 3
      2926075.00      6929975.01      2925975.00      6929525.00
      2925775.01      6929075.03
#Sta/Elev= 30
  4517.6  370.33  4590.6  370.47  4665.4  365.77  4702.0  362.20  4743.0  360.53
  4769.9  354.93  4794.2  355.93  4813.4  352.05  4835.2  354.46  4881.7  347.46
  4917.1  343.09  4935.2  344.12  4968.3  344.01  4982.8  341.87  4983.7  341.07
  4992.2  341.87  4993.0  343.11  5010.7  344.88  5077.1  345.30  5099.0  343.86
  5215.5  347.46  5222.3  347.71  5241.9  348.47  5259.7  351.26  5265.2  349.46
  5282.9  349.71  5386.9  366.19  5433.4  366.94  5438.9  368.72  5471.0  370.18
#Mann=6,-1,0
  4517.6    0.05       0  4665.4    0.16       0  4935.2    0.12       0
  4982.8    0.07       0  4992.2    0.12       0  5222.3    0.16       0
Bank Sta=4881.7,5215.5
Exp/Cntr=0.3,0.1

Type RM Length L Ch R = 1,14435,297,297,297
BEGIN DESCRIPTION:
BLACK CREEK 22.0
END DESCRIPTION:
XS GIS Cut Line= 3
      2926475.00      6929975.04      2926475.00      6929425.00
      2926324.99      6928974.98
#Sta/Elev= 30
  4416.0  373.94  4452.7  371.16  4461.7  370.49  4526.0  364.59  4706.0  352.98
  4736.0  347.46  4766.0  347.05  4786.0  348.89  4804.8  343.63  4816.0  344.53
  4836.0  350.01  4856.0  351.45  4876.0  344.01  4909.5  342.56  4987.1  342.12
  4992.9  340.33  4993.8  339.53  5002.5  340.33  5018.7  342.15  5103.1  341.34
  5143.5  342.40  5166.0  343.63  5247.5  354.31  5261.2  355.81  5271.7  359.18
  5282.3  360.37  5351.4  365.87  5366.6  368.12  5419.3  371.72  5440.4  374.78
#Mann=9,-1,0
  4416.0    0.16       0  4452.7    0.05       0  4461.7    0.16       0
  4909.5    0.05       0  4992.9    0.03       0  5002.5    0.05       0
  5143.5    0.16       0  5247.5    0.05       0  5351.4    0.08       0
Bank Sta=4804.8,5166
Exp/Cntr=0.3,0.1

Type RM Length L Ch R = 1,14138,106,106,106
BEGIN DESCRIPTION:
Mapping XS 214afe7c
END DESCRIPTION:
XS GIS Cut Line= 4
      2926922.75      6930057.73      2926905.39      6929457.04
      2926679.69      6929203.56      2926363.75      6929012.61
#Sta/Elev= 30
  4087.8  374.83  4200.6  371.00  4300.6  369.96  4430.7  366.52  4480.7  364.23
  4560.7  357.14  4618.6  354.07  4682.0  350.76  4711.7  350.28  4740.1  348.01
  4775.3  348.13  4782.8  345.11  4792.8  343.37  4864.3  340.05  4947.2  339.77
  4964.4  339.85  5004.6  339.22  5005.5  338.42  5013.3  338.42  5014.2  339.22
  5027.9  340.90  5052.7  339.83  5106.0  341.10  5166.3  343.37  5206.2  346.25
  5264.2  351.45  5302.8  356.54  5314.0  358.84  5343.8  361.03  5397.3  367.87
#Mann=11,-1,0
  4087.8    0.08       0  4618.6    0.16       0  4682.0    0.08       0
  4864.3    0.05       0  4947.2    0.08       0  4964.4    0.05       0
  5004.6    0.03       0  5014.2    0.05       0  5106.0    0.08       0
  5206.2    0.16       0  5302.8    0.08       0
Bank Sta=4792.8,5166.3
Exp/Cntr=0.3,0.1

Type RM Length L Ch R = 1,14032,614,614,614
BEGIN DESCRIPTION:
Mapping XS 9007d665
END DESCRIPTION:
XS GIS Cut Line= 5
      2927006.08      6930075.10      2927016.50      6929460.51
      2926825.52      6929186.20      2926572.05      6929019.54
      2926391.49      6928835.50
#Sta/Elev= 30
  3988.1  376.48  4138.2  373.99  4216.3  369.46  4221.3  372.95  4248.2  372.03
  4394.3  362.34  4499.1  356.10  4597.0  352.38  4606.6  352.03  4665.5  346.61
  4716.8  347.75  4774.3  345.80  4821.2  343.06  4838.0  342.78  4859.2  344.75
  4874.1  341.59  4895.0  342.92  4940.5  339.94  4970.9  340.87  4998.4  338.29
  4999.3  337.49  5008.0  338.29  5075.5  343.37  5159.6  343.06  5255.7  349.14
  5299.9  356.21  5316.3  358.24  5438.0  377.34  5456.6  379.97  5498.2  383.43
#Mann=16,-1,0
  3988.1    0.08       0  4394.3    0.05       0  4499.1    0.08       0
  4597.0    0.16       0  4606.6     0.1       0  4716.8    0.16       0
  4774.3    0.08       0  4838.0    0.05       0  4940.5    0.08       0
  4970.9    0.05       0  4998.4    0.04       0  5008.0    0.05       0
  5299.9    0.08       0  5316.3    0.05       0  5438.0    0.08       0
  5456.6    0.05       0
Bank Sta=4821.2,5159.6
Exp/Cntr=0.3,0.1

Type RM Length L Ch R = 1,13418,572,572,572
BEGIN DESCRIPTION:
BLACK CREEK 20.0
END DESCRIPTION:
XS GIS Cut Line= 3
      2927275.00      6929624.99      2927375.00      6929025.00
      2927325.00      6928575.04
#Sta/Elev= 30
  4417.8  365.45  4445.7  363.22  4450.7  361.40  4473.1  360.75  4529.3  358.36
  4539.4  355.07  4572.0  352.79  4590.1  355.71  4647.2  351.89  4670.8  350.23
  4701.7  348.12  4721.9  348.64  4749.8  346.77  4754.9  348.62  4762.5  348.61
  4803.0  342.69  4833.4  344.64  4849.9  341.53  4860.6  340.62  4993.3  336.19
  4994.3  335.39  5003.1  336.19  5015.9  336.29  5023.5  339.43  5036.1  340.65
  5136.7  340.04  5162.2  341.53  5267.5  355.80  5418.5  370.95  5478.8  375.06
#Mann=8,-1,0
  4417.8    0.12       0  4473.1    0.08       0  4572.0    0.16       0
  4647.2    0.08       0  4670.8    0.16       0  4860.6    0.05       0
  4993.3    0.03       0  5003.1    0.05       0
Bank Sta=4849.9,5162.2
Exp/Cntr=0.3,0.1

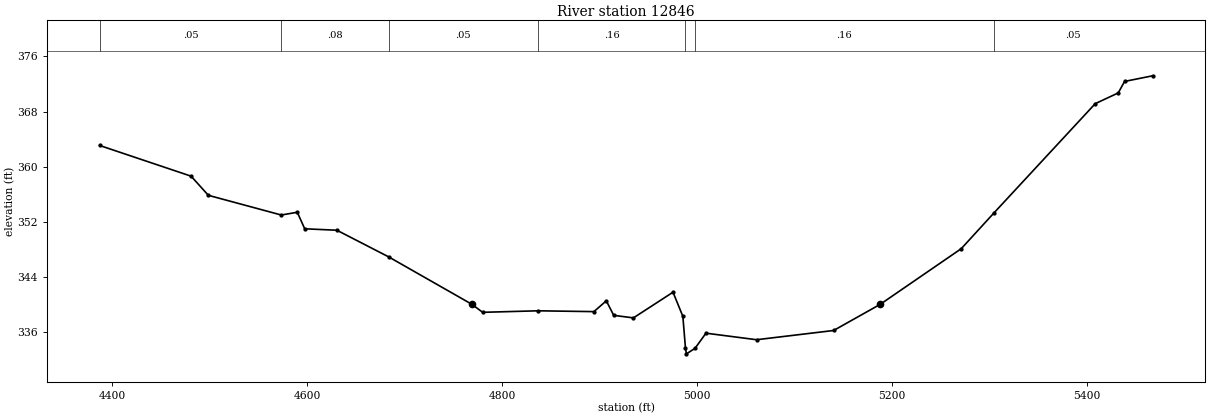
Type RM Length L Ch R = 1,12846,528,528,528
BEGIN DESCRIPTION:
BLACK CREEK 19.0
END DESCRIPTION:
XS GIS Cut Line= 3
      2928025.00      6929574.98      2927925.00      6928975.00
      2927674.98      6928574.96
#Sta/Elev= 30
  4387.4  363.07  4481.2  358.61  4498.9  355.83  4573.7  352.97  4590.1  353.37
  4597.7  350.97  4630.7  350.76  4683.7  346.90  4769.2  340.00  4780.2  338.84
  4837.0  339.06  4894.3  338.94  4907.0  340.51  4914.6  338.40  4934.8  338.03
  4975.4  341.76  4985.5  338.26  4988.2  333.61  4989.2  332.81  4998.0  333.61
  5009.2  335.81  5061.1  334.86  5140.1  336.20  5187.9  340.00  5271.0  348.08
  5304.4  353.25  5408.4  369.14  5432.0  370.70  5438.5  372.37  5467.4  373.19
#Mann=7,-1,0
  4387.4    0.05       0  4573.7    0.08       0  4683.7    0.05       0
  4837.0    0.16       0  4988.2    0.07       0  4998.0    0.16       0
  5304.4    0.05       0
Bank Sta=4769.2,5187.9
Exp/Cntr=0.3,0.1