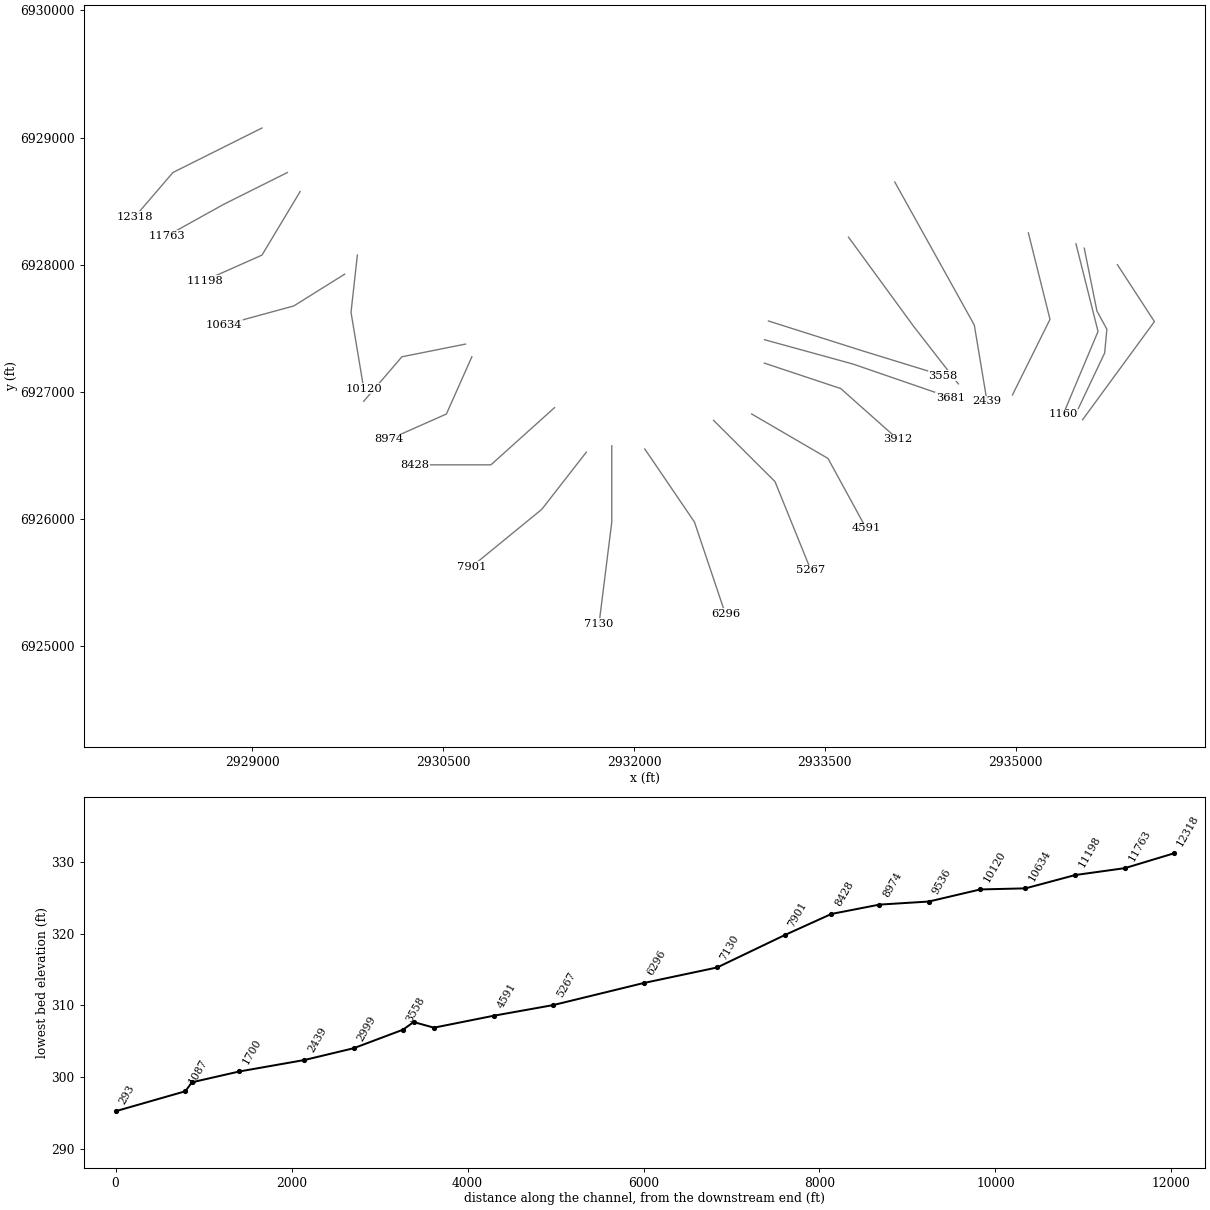
HEC-RAS study BLACK CREEK.prj: BLACK CREEK Base Level Engineering

--- BLACK CREEK.g01 (geometry) --- (continued)

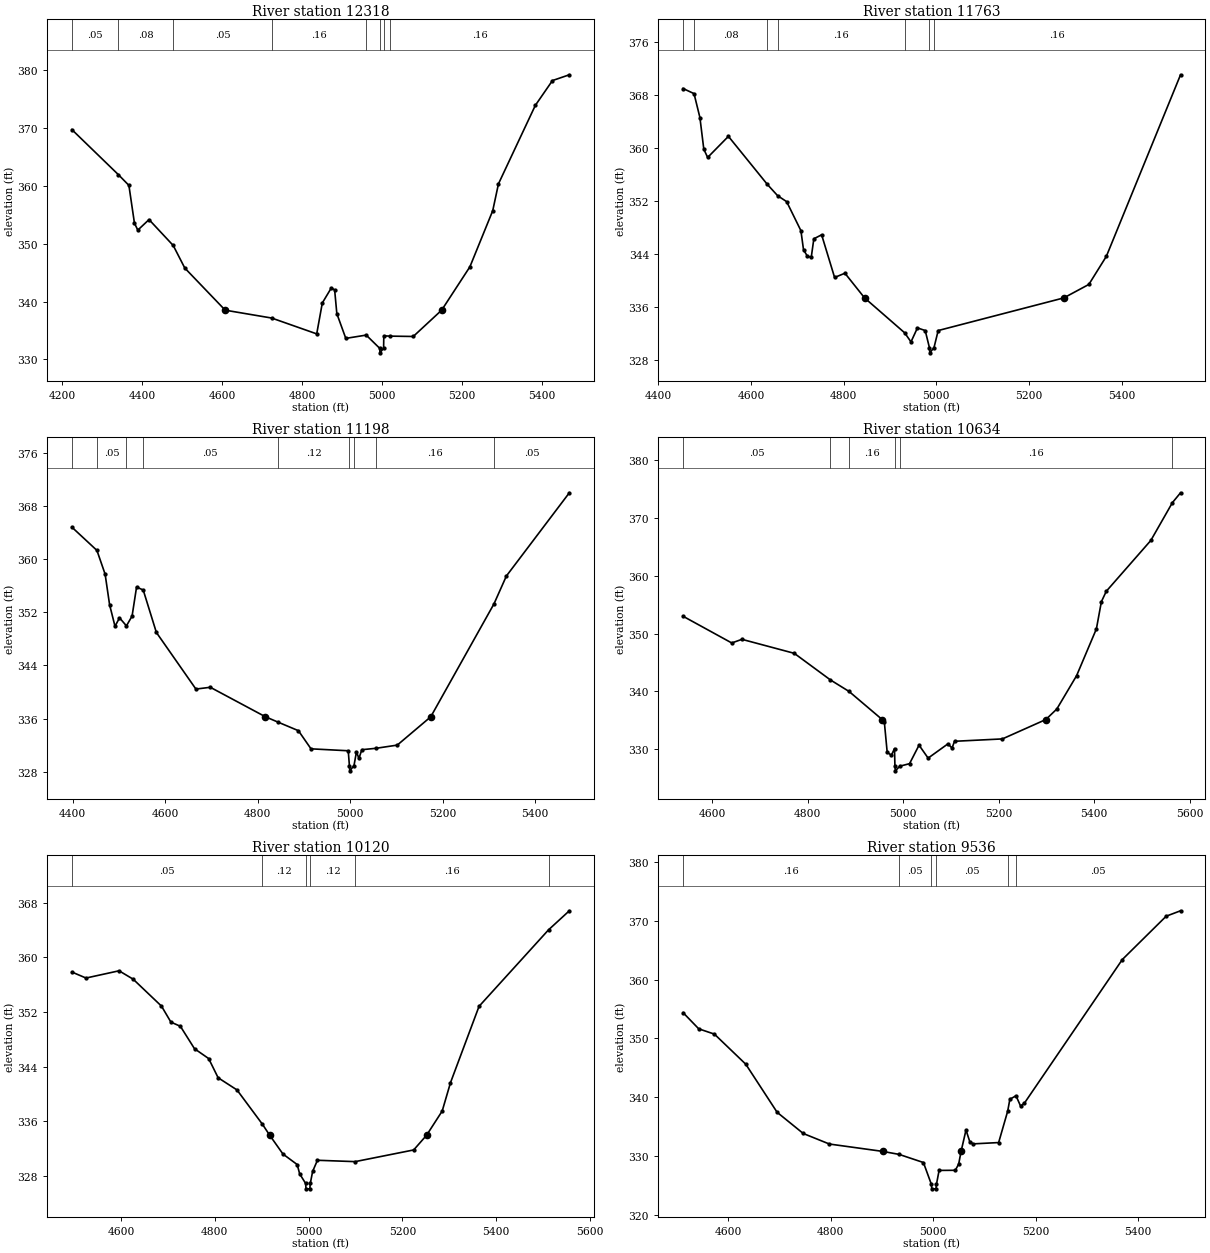
Type RM Length L Ch R = 1,12318,555,555,555
BEGIN DESCRIPTION:
BLACK CREEK 18.0
END DESCRIPTION:
XS GIS Cut Line= 3
      2929075.01      6929075.01      2928375.00      6928725.00
      2928075.01      6928375.01
#Sta/Elev= 30
  4224.0  369.76  4340.2  361.97  4366.6  360.11  4380.5  353.56  4388.9  352.37
  4416.9  354.19  4477.4  349.71  4506.3  345.81  4607.3  338.52  4723.5  337.16
  4836.1  334.42  4850.1  339.77  4872.5  342.36  4880.9  342.03  4886.4  337.92
  4908.8  333.64  4959.8  334.21  4993.3  331.94  4994.3  331.14  5003.3  331.94
  5003.8  334.08  5020.2  334.03  5077.4  333.97  5148.4  338.52  5219.0  346.02
  5276.1  355.73  5290.4  360.37  5382.6  373.95  5425.4  378.24  5467.6  379.24
#Mann=8,-1,0
  4224.0    0.05       0  4340.2    0.08       0  4477.4    0.05       0
  4723.5    0.16       0  4959.8    0.12       0  4993.3    0.07       0
  5003.3    0.12       0  5020.2    0.16       0
Bank Sta=4607.3,5148.4
Exp/Cntr=0.3,0.1

Type RM Length L Ch R = 1,11763,565,565,565
BEGIN DESCRIPTION:
BLACK CREEK 17.0
END DESCRIPTION:
XS GIS Cut Line= 3
      2929275.03      6928725.02      2928775.00      6928475.00
      2928325.03      6928225.02
#Sta/Elev= 30
  4453.5  368.93  4477.2  368.16  4489.9  364.55  4498.3  359.78  4506.6  358.54
  4551.4  361.72  4635.4  354.48  4657.7  352.77  4677.1  351.88  4707.9  347.50
  4713.5  344.63  4721.9  343.65  4730.2  343.49  4735.8  346.28  4752.6  346.88
  4780.6  340.45  4802.9  341.09  4845.3  337.37  4931.8  332.11  4945.5  330.74
  4959.4  332.85  4976.2  332.45  4985.2  329.89  4986.2  329.09  4995.2  329.89
  5004.2  332.45  5275.3  337.37  5329.4  339.40  5367.2  343.64  5527.3  371.00
#Mann=7,-1,0
  4453.5    0.05       0  4477.2    0.08       0  4635.4    0.05       0
  4657.7    0.16       0  4931.8    0.12       0  4985.2    0.07       0
  4995.2    0.16       0
Bank Sta=4845.3,5275.3
Exp/Cntr=0.3,0.1

Type RM Length L Ch R = 1,11198,564,564,564
BEGIN DESCRIPTION:
BLACK CREEK 16.0
END DESCRIPTION:
XS GIS Cut Line= 3
      2929375.00      6928575.01      2929075.00      6928075.00
      2928625.04      6927875.02
#Sta/Elev= 30
  4398.3  364.79  4452.5  361.29  4470.2  357.72  4479.9  353.11  4491.6  349.87
  4501.3  351.15  4516.3  349.94  4528.5  351.41  4538.2  355.78  4552.6  355.33
  4581.0  348.95  4666.5  340.43  4697.6  340.70  4816.9  336.26  4842.9  335.49
  4888.1  334.17  4915.3  331.44  4995.8  331.15  4998.3  328.93  4999.2  328.13
  5008.3  328.93  5013.5  330.97  5019.0  330.01  5025.2  331.31  5055.7  331.52
  5101.8  332.00  5174.2  336.26  5310.9  353.25  5337.7  357.44  5473.8  369.96
#Mann=9,-1,0
  4398.3    0.08       0  4452.5    0.05       0  4516.3    0.16       0
  4552.6    0.05       0  4842.9    0.12       0  4998.3    0.07       0
  5008.3    0.12       0  5055.7    0.16       0  5310.9    0.05       0
Bank Sta=4816.9,5174.2
Exp/Cntr=0.3,0.1

Type RM Length L Ch R = 1,10634,514,514,514
BEGIN DESCRIPTION:
BLACK CREEK 15.0
END DESCRIPTION:
XS GIS Cut Line= 3
      2929725.02      6927925.01      2929325.00      6927675.00
      2928775.01      6927525.00
#Sta/Elev= 30
  4539.1  353.01  4641.1  348.39  4662.4  349.02  4772.0  346.60  4847.7  342.00
  4886.7  340.01  4956.1  335.15  4960.7  334.64  4966.6  329.48  4975.4  328.98
  4981.9  330.14  4982.8  327.08  4983.8  326.28  4992.9  327.08  5013.4  327.52
  5033.3  330.72  5052.3  328.48  5093.7  330.94  5102.4  330.23  5107.6  331.39
  5207.8  331.80  5298.8  335.15  5321.8  336.97  5363.2  342.73  5404.7  350.83
  5415.1  355.52  5425.4  357.33  5518.7  366.12  5563.9  372.66  5580.9  374.36
#Mann=6,-1,0
  4539.1    0.05       0  4847.7    0.12       0  4886.7    0.16       0
  4982.8    0.07       0  4992.9    0.16       0  5563.9    0.05       0
Bank Sta=4956.1,5298.8
Exp/Cntr=0.3,0.1

Type RM Length L Ch R = 1,10120,584,584,584
BEGIN DESCRIPTION:
BLACK CREEK 14.0
END DESCRIPTION:
XS GIS Cut Line= 3
      2929825.01      6928075.05      2929775.00      6927625.00
      2929875.00      6927024.99
#Sta/Elev= 30
  4495.0  357.85  4525.2  356.97  4595.7  358.03  4625.8  356.80  4686.2  352.86
  4706.3  350.52  4726.5  349.91  4756.6  346.63  4786.8  345.19  4807.0  342.38
  4847.2  340.60  4901.6  335.57  4917.0  333.97  4945.3  331.22  4975.7  329.68
  4980.8  328.34  4993.5  326.93  4994.5  326.13  5002.6  326.13  5003.6  326.93
  5008.6  328.69  5018.8  330.31  5099.2  330.11  5224.1  331.82  5251.6  333.97
  5284.9  337.51  5302.6  341.66  5363.5  352.83  5511.7  364.02  5556.1  366.81
#Mann=6,-1,0
  4495.0    0.05       0  4901.6    0.12       0  4993.5    0.07       0
  5003.6    0.12       0  5099.2    0.16       0  5511.7    0.05       0
Bank Sta=4917,5251.6
Exp/Cntr=0.3,0.1

Type RM Length L Ch R = 1,9536,562,562,562
BEGIN DESCRIPTION:
BLACK CREEK 13.0
END DESCRIPTION:
XS GIS Cut Line= 3
      2930675.04      6927375.01      2930175.00      6927275.00
      2929875.01      6926925.01
#Sta/Elev= 30
  4511.9  354.38  4542.5  351.63  4573.1  350.73  4634.3  345.62  4695.5  337.45
  4746.5  333.85  4797.5  332.06  4901.5  330.81  4933.6  330.30  4981.0  328.92
  4996.4  325.25  4997.4  324.45  5005.5  324.45  5006.5  325.25  5011.6  327.58
  5043.2  327.60  5049.8  328.65  5054.5  330.81  5064.1  334.44  5071.8  332.38
  5078.4  332.09  5127.8  332.31  5145.5  337.66  5149.7  339.67  5161.7  340.26
  5170.6  338.51  5178.2  339.02  5369.2  363.40  5454.8  370.76  5482.8  371.68
#Mann=6,-1,0
  4511.9    0.16       0  4933.6    0.05       0  4996.4    0.03       0
  5006.5    0.05       0  5145.5    0.16       0  5161.7    0.05       0
Bank Sta=4901.5,5054.5
Exp/Cntr=0.3,0.1

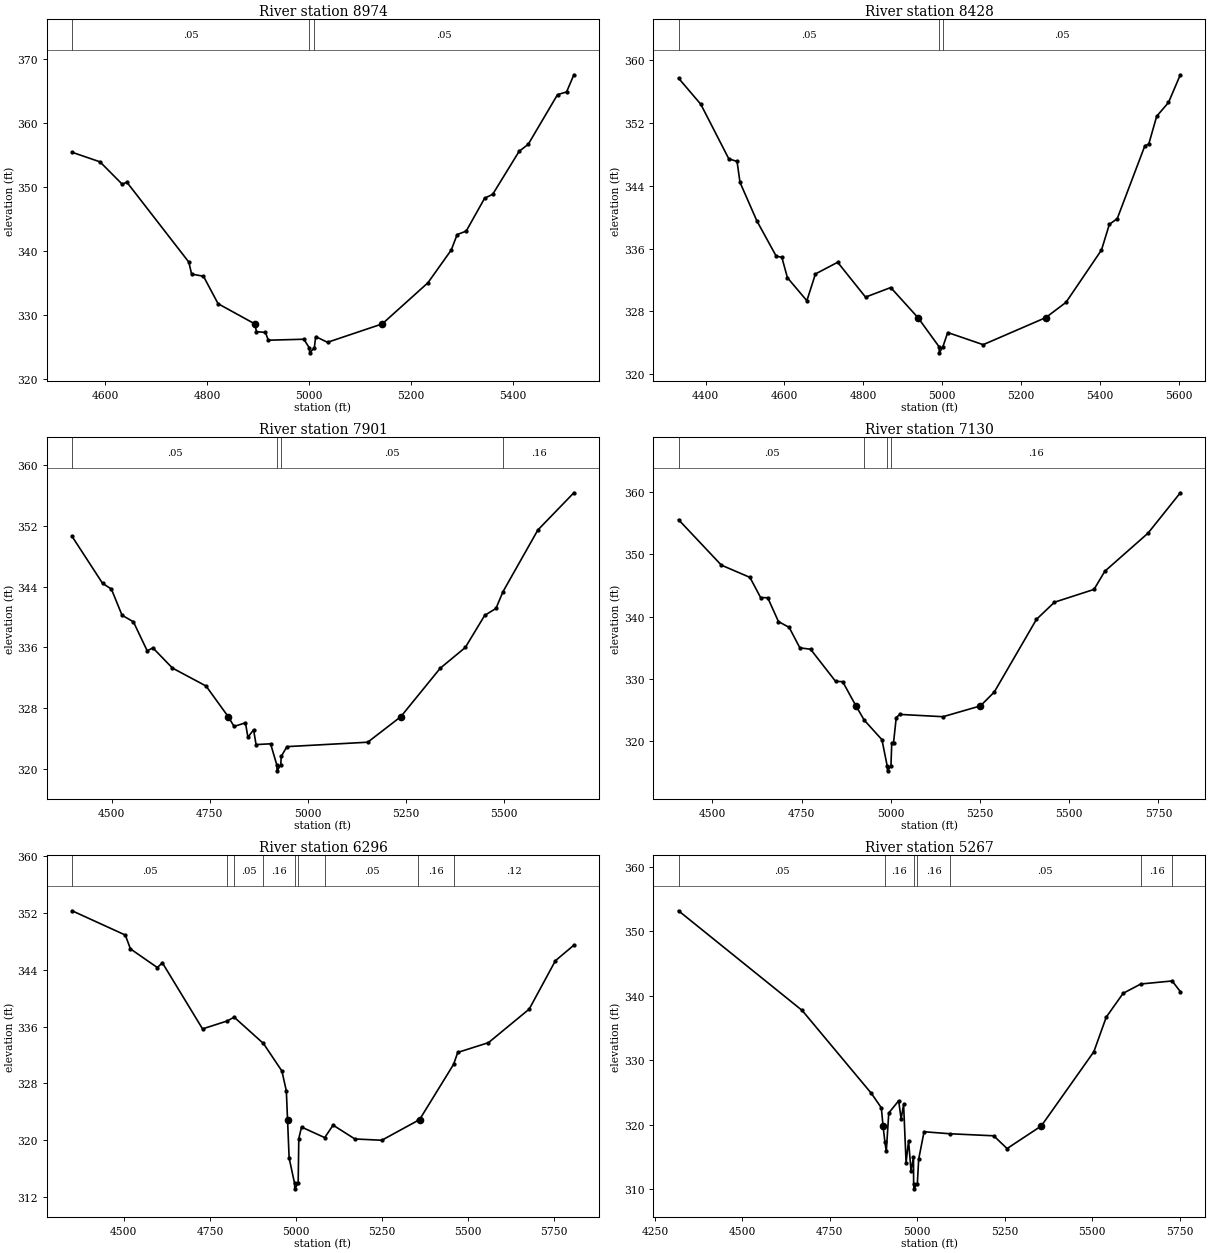
Type RM Length L Ch R = 1,8974,546,546,546
BEGIN DESCRIPTION:
BLACK CREEK 12.0
END DESCRIPTION:
XS GIS Cut Line= 3
      2930725.02      6927275.04      2930525.00      6926825.00
      2930075.03      6926625.01
#Sta/Elev= 30
  4535.2  355.42  4590.0  353.92  4633.7  350.41  4642.6  350.75  4764.4  338.22
  4769.8  336.35  4793.1  336.01  4821.8  331.71  4893.9  328.55  4897.1  327.34
  4914.8  327.21  4920.3  326.00  4990.1  326.15  5000.7  324.82  5001.7  324.02
  5010.8  324.82  5013.3  326.56  5036.6  325.67  5144.0  328.55  5233.6  334.98
  5279.4  340.11  5291.0  342.53  5308.8  343.08  5345.0  348.23  5360.8  348.84
  5412.7  355.57  5430.5  356.66  5488.0  364.44  5505.8  364.86  5520.1  367.55
#Mann=3,-1,0
  4535.2    0.05       0  5000.7    0.03       0  5010.8    0.05       0
Bank Sta=4893.9,5144
Exp/Cntr=0.3,0.1

Type RM Length L Ch R = 1,8428,527,527,527
BEGIN DESCRIPTION:
BLACK CREEK 11.0
END DESCRIPTION:
XS GIS Cut Line= 3
      2931375.02      6926875.02      2930875.00      6926425.00
      2930275.01      6926425.00
#Sta/Elev= 30
  4331.6  357.72  4388.1  354.39  4459.1  347.44  4480.0  347.11  4487.5  344.44
  4530.1  339.55  4579.4  335.03  4593.6  334.90  4607.8  332.29  4657.1  329.36
  4678.8  332.77  4735.2  334.26  4805.9  329.82  4869.8  331.04  4938.8  327.21
  4992.1  323.52  4993.1  322.72  5002.3  323.52  5014.3  325.31  5104.3  323.76
  5263.0  327.21  5314.3  329.15  5404.3  335.82  5424.3  339.09  5444.3  339.82
  5514.3  349.10  5524.3  349.33  5544.3  352.86  5574.3  354.62  5604.3  358.15
#Mann=3,-1,0
  4331.6    0.05       0  4992.1    0.03       0  5002.3    0.05       0
Bank Sta=4938.8,5263
Exp/Cntr=0.3,0.1

Type RM Length L Ch R = 1,7901,771,771,771
BEGIN DESCRIPTION:
BLACK CREEK 10.0
END DESCRIPTION:
XS GIS Cut Line= 3
      2931624.99      6926524.99      2931275.00      6926075.00
      2930725.00      6925625.00
#Sta/Elev= 30
  4398.6  350.59  4476.4  344.43  4499.0  343.67  4526.2  340.23  4555.1  339.38
  4590.4  335.56  4604.9  335.95  4654.7  333.30  4740.6  330.94  4797.2  326.91
  4812.1  325.63  4841.1  326.11  4847.4  324.21  4861.9  325.19  4868.2  323.25
  4905.3  323.35  4921.0  320.60  4922.0  319.80  4931.2  320.60  4932.5  321.70
  4947.0  322.98  5153.2  323.56  5237.6  326.91  5338.3  333.28  5402.2  336.00
  5451.8  340.22  5480.5  341.13  5498.5  343.34  5587.4  351.43  5679.3  356.32
#Mann=4,-1,0
  4398.6    0.05       0  4921.0    0.03       0  4931.2    0.05       0
  5498.5    0.16       0
Bank Sta=4797.2,5237.6
Exp/Cntr=0.3,0.1

Type RM Length L Ch R = 1,7130,834,834,834
BEGIN DESCRIPTION:
BLACK CREEK 9.0
END DESCRIPTION:
XS GIS Cut Line= 3
      2931825.00      6926574.99      2931825.00      6925975.00
      2931725.00      6925175.02
#Sta/Elev= 30
  4405.0  355.51  4525.0  348.23  4605.0  346.27  4635.0  343.04  4655.0  343.00
  4685.0  339.19  4715.0  338.26  4745.0  334.98  4775.0  334.76  4845.0  329.62
  4865.0  329.56  4902.2  325.68  4925.4  323.40  4975.0  320.27  4989.7  316.08
  4990.6  315.28  5000.3  316.08  5002.5  319.78  5007.5  319.78  5015.1  323.82
  5025.1  324.32  5146.1  323.95  5250.9  325.68  5289.7  327.89  5408.1  339.55
  5458.5  342.29  5569.3  344.34  5599.6  347.25  5720.5  353.34  5811.2  359.82
#Mann=4,-1,0
  4405.0    0.05       0  4925.4    0.16       0  4989.7    0.07       0
  5000.3    0.16       0
Bank Sta=4902.2,5250.9
Exp/Cntr=0.3,0.1

Type RM Length L Ch R = 1,6296,1029,1029,1029
BEGIN DESCRIPTION:
double BLACK CREEK 8.0
END DESCRIPTION:
XS GIS Cut Line= 3
      2932084.43      6926549.76      2932475.00      6925975.00
      2932718.08      6925252.08
#Sta/Elev= 30
  4349.6  352.32  4504.2  348.90  4519.1  346.95  4597.2  344.32  4612.0  344.98
  4728.6  335.67  4800.0  336.78  4820.4  337.32  4905.5  333.61  4959.1  329.73
  4972.0  326.93  4975.5  322.88  4980.1  317.47  4995.8  313.92  4996.7  313.12
  5006.4  313.92  5008.2  320.21  5016.1  321.83  5083.5  320.34  5107.8  322.10
  5171.1  320.15  5249.3  319.97  5355.3  322.78  5359.0  322.88  5457.7  330.66
  5469.9  332.35  5559.2  333.73  5677.5  338.46  5753.6  345.28  5807.2  347.47
#Mann=9,-1,0
  4349.6    0.05       0  4800.0    0.16       0  4820.4    0.05       0
  4905.5    0.16       0  4995.8    0.07       0  5006.4    0.16       0
  5083.5    0.05       0  5355.3    0.16       0  5457.7    0.12       0
Bank Sta=4975.5,5359
Exp/Cntr=0.3,0.1

Type RM Length L Ch R = 1,5267,676,676,676
BEGIN DESCRIPTION:
BLACK CREEK 7.0
END DESCRIPTION:
XS GIS Cut Line= 3
      2932625.04      6926774.96      2933108.11      6926293.13
      2933390.43      6925595.92
#Sta/Elev= 30
  4317.7  353.20  4671.2  337.73  4869.2  324.85  4897.5  322.62  4902.3  319.81
  4907.8  317.26  4911.6  315.85  4918.7  321.82  4947.0  323.72  4954.0  320.90
  4961.1  323.14  4968.2  314.13  4975.3  317.54  4982.3  312.83  4989.4  314.99
  4989.8  310.85  4990.7  310.05  5000.4  310.85  5004.2  314.65  5019.6  318.91
  5092.7  318.60  5218.7  318.28  5256.9  316.30  5354.8  319.81  5505.0  331.33
  5540.4  336.69  5588.6  340.39  5639.3  341.84  5728.9  342.31  5752.2  340.65
#Mann=7,-1,0
  4317.7    0.05       0  4907.8    0.16       0  4989.8    0.07       0
  5000.4    0.16       0  5092.7    0.05       0  5639.3    0.16       0
  5728.9    0.12       0
Bank Sta=4902.3,5354.8
Exp/Cntr=0.3,0.1

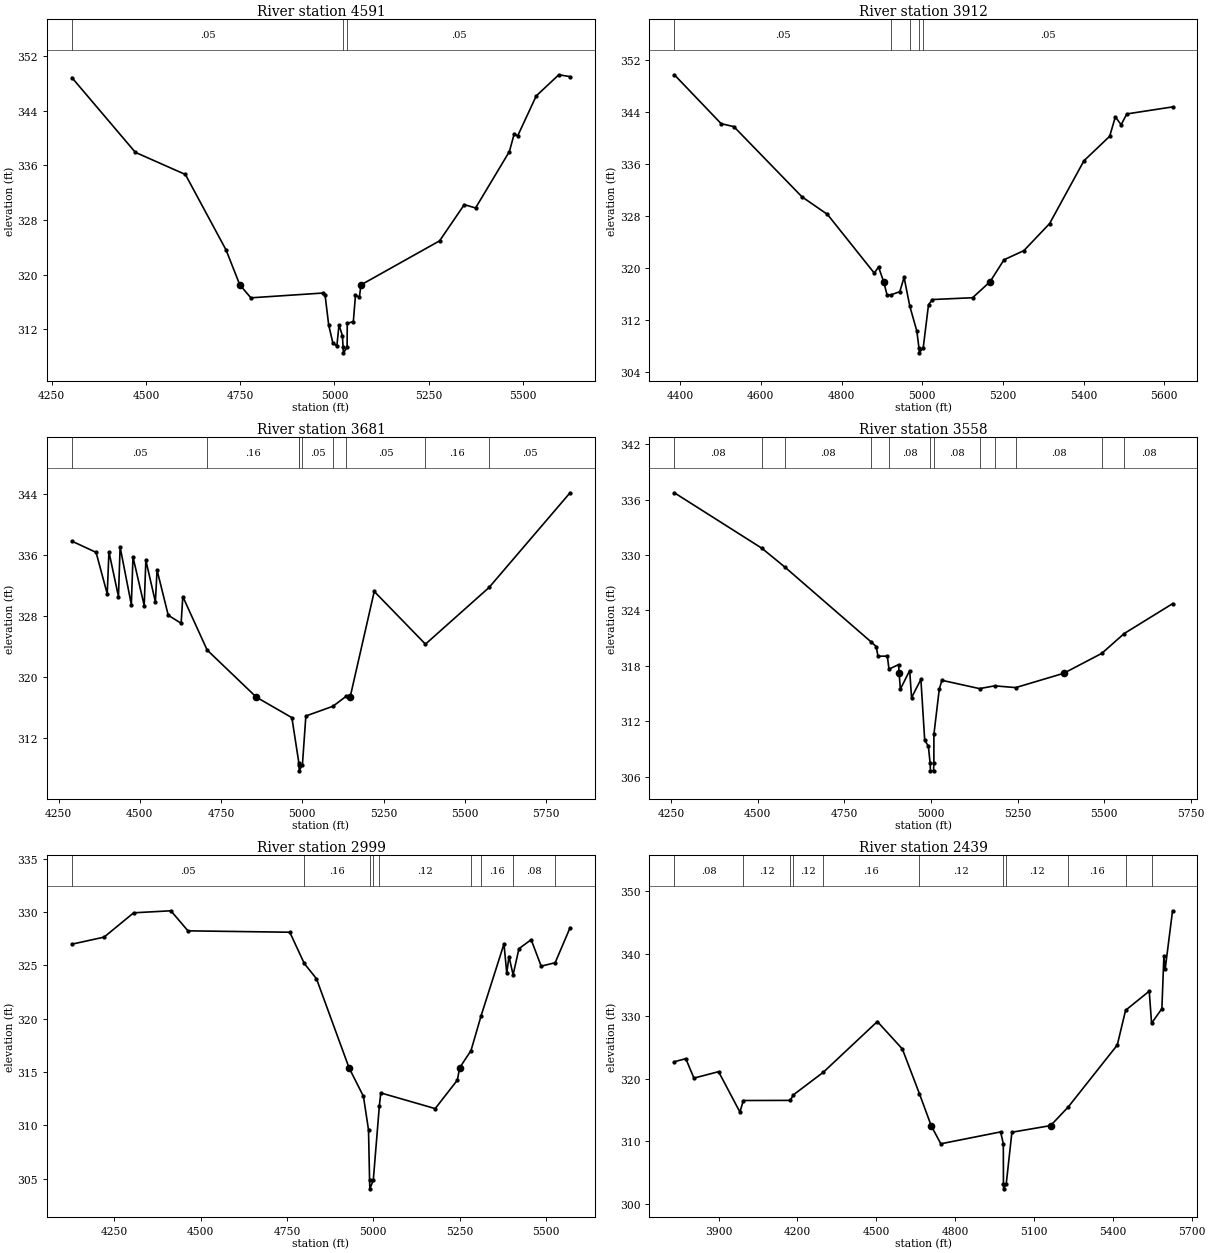
Type RM Length L Ch R = 1,4591,679,679,679
BEGIN DESCRIPTION:
BLACK CREEK 6.0
END DESCRIPTION:
XS GIS Cut Line= 3
      2932924.96      6926825.02      2933525.00      6926475.00
      2933825.02      6925924.97
#Sta/Elev= 30
  4303.7  348.85  4472.0  337.91  4604.7  334.67  4712.7  323.61  4749.1  318.51
  4778.4  316.62  4969.0  317.32  4975.2  317.01  4984.7  312.67  4995.5  310.08
  5006.4  309.55  5012.1  312.66  5021.1  311.09  5023.0  309.37  5023.8  308.57
  5033.6  309.37  5034.0  312.90  5050.1  313.13  5055.8  317.00  5066.2  316.71
  5070.3  318.51  5278.9  324.96  5344.4  330.26  5374.3  329.77  5464.0  338.03
  5476.8  340.62  5485.8  340.30  5535.2  346.17  5595.0  349.26  5624.9  348.99
#Mann=3,-1,0
  4303.7    0.05       0  5023.0    0.03       0  5033.6    0.05       0
Bank Sta=4749.1,5070.3
Exp/Cntr=0.3,0.1

Type RM Length L Ch R = 1,3912,231,231,231
BEGIN DESCRIPTION:
BLACK CREEK 5.0
END DESCRIPTION:
XS GIS Cut Line= 3
      2933025.02      6927224.99      2933625.00      6927025.00
      2934074.99      6926625.01
#Sta/Elev= 30
  4385.8  349.74  4501.7  342.21  4533.3  341.75  4702.0  330.94  4765.2  328.23
  4881.2  319.19  4891.7  320.14  4904.4  317.86  4912.8  315.84  4921.4  315.82
  4944.4  316.33  4955.0  318.54  4969.3  314.07  4986.6  310.27  4991.8  307.71
  4992.6  306.91  5002.5  307.71  5015.6  314.33  5025.3  315.12  5124.8  315.40
  5168.0  317.86  5202.6  321.24  5252.0  322.66  5315.5  326.81  5400.8  336.50
  5464.4  340.26  5478.6  343.26  5492.8  342.04  5507.0  343.71  5620.3  344.79
#Mann=5,-1,0
  4385.8    0.05       0  4921.4    0.16       0  4969.3    0.05       0
  4991.8    0.03       0  5002.5    0.05       0
Bank Sta=4904.4,5168
Exp/Cntr=0.3,0.1

Type RM Length L Ch R = 1,3681,123,123,123
BEGIN DESCRIPTION:
Mapping XS 57815a97
END DESCRIPTION:
XS GIS Cut Line= 3
      2933026.21      6927409.18      2933720.69      6927218.19
      2934488.89      6926953.45
#Sta/Elev= 30
  4290.9  337.84  4365.3  336.37  4399.7  330.91  4404.9  336.44  4434.2  330.57
  4439.3  337.07  4473.8  329.51  4478.9  335.76  4513.4  329.38  4518.5  335.32
  4547.8  329.87  4553.0  334.04  4587.4  328.11  4627.0  327.06  4632.2  330.56
  4707.0  323.55  4858.5  317.36  4967.8  314.67  4989.2  308.74  4989.5  308.49
  4990.4  307.69  5000.2  308.49  5010.8  314.89  5094.3  316.17  5134.6  317.47
  5147.0  317.36  5221.2  331.24  5378.8  324.32  5574.5  331.76  5823.7  344.19
#Mann=9,-1,0
  4290.9    0.05       0  4707.0    0.16       0  4989.2    0.05       0
  4989.5    0.04       0  5000.2    0.05       0  5094.3    0.08       0
  5134.6    0.05       0  5378.8    0.16       0  5574.5    0.05       0
Bank Sta=4858.5,5147
Exp/Cntr=0.3,0.1

Type RM Length L Ch R = 1,3558,559,559,559
BEGIN DESCRIPTION:
Mapping XS 355a3861
END DESCRIPTION:
XS GIS Cut Line= 3
      2933056.67      6927556.72      2933794.48      6927322.36
      2934428.13      6927127.06
#Sta/Elev= 30
  4259.6  336.75  4512.4  330.73  4577.4  328.73  4826.3  320.62  4841.8  320.09
  4847.0  319.04  4874.0  319.05  4878.7  317.64  4906.3  318.13  4908.1  317.19
  4911.5  315.47  4938.5  317.49  4943.8  314.55  4970.8  316.53  4981.8  309.93
  4992.3  309.30  4997.5  307.42  4998.3  306.62  5007.3  306.62  5008.2  307.42
  5008.3  310.56  5023.8  315.47  5031.4  316.43  5140.0  315.53  5183.7  315.83
  5244.3  315.64  5382.8  317.19  5492.7  319.35  5557.4  321.50  5696.8  324.73
#Mann=12,-1,0
  4259.6    0.08       0  4512.4    0.05       0  4577.4    0.08       0
  4826.3    0.05       0  4878.7    0.08       0  4997.5    0.07       0
  5008.2    0.08       0  5140.0    0.05       0  5183.7    0.16       0
  5244.3    0.08       0  5492.7    0.16       0  5557.4    0.08       0
Bank Sta=4908.1,5382.8
Exp/Cntr=0.3,0.1

Type RM Length L Ch R = 1,2999,560,560,560
BEGIN DESCRIPTION:
BLACK CREEK 4.0
END DESCRIPTION:
XS GIS Cut Line= 3
      2933685.99      6928216.44      2934200.33      6927511.67
      2934549.70      6927061.92
#Sta/Elev= 30
  4127.5  326.98  4220.6  327.64  4306.4  329.92  4414.0  330.11  4463.5  328.23
  4758.2  328.10  4800.2  325.17  4835.5  323.74  4929.8  315.39  4971.4  312.72
  4986.1  309.58  4989.2  304.85  4990.0  304.05  4999.9  304.85  5017.4  311.79
  5021.6  313.04  5179.1  311.57  5243.3  314.24  5249.8  315.39  5282.8  317.01
  5311.9  320.26  5378.2  327.00  5386.3  324.27  5392.7  325.82  5404.6  324.11
  5421.6  326.56  5456.9  327.40  5485.9  324.92  5526.3  325.24  5569.5  328.52
#Mann=9,-1,0
  4127.5    0.05       0  4800.2    0.16       0  4989.2    0.07       0
  4999.9    0.16       0  5017.4    0.12       0  5282.8    0.05       0
  5311.9    0.16       0  5404.6    0.08       0  5526.3    0.05       0
Bank Sta=4929.8,5249.8
Exp/Cntr=0.3,0.1

Type RM Length L Ch R = 1,2439,739,739,739
BEGIN DESCRIPTION:
BLACK CREEK 3.0
END DESCRIPTION:
XS GIS Cut Line= 3
      2934049.98      6928650.04      2934675.00      6927525.00
      2934775.00      6926924.97
#Sta/Elev= 30
  3732.0  322.73  3775.5  323.22  3806.4  320.11  3900.2  321.14  3981.4  314.68
  3994.4  316.53  4173.0  316.55  4184.7  317.43  4298.7  321.05  4504.2  329.15
  4599.2  324.78  4664.1  317.64  4708.9  312.52  4745.6  309.61  4973.2  311.51
  4983.5  309.61  4983.9  303.21  4984.7  302.41  4994.6  303.21  5016.1  311.46
  5163.4  312.52  5230.5  315.50  5416.9  325.39  5448.6  330.95  5538.6  334.01
  5547.5  328.88  5586.7  331.21  5594.3  339.58  5599.4  337.59  5627.3  346.86
#Mann=11,-1,0
  3732.0    0.08       0  3994.4    0.12       0  4173.0    0.16       0
  4184.7    0.12       0  4298.7    0.16       0  4664.1    0.12       0
  4983.9    0.07       0  4994.6    0.12       0  5230.5    0.16       0
  5448.6    0.08       0  5547.5    0.05       0
Bank Sta=4708.9,5163.4
Exp/Cntr=0.3,0.1

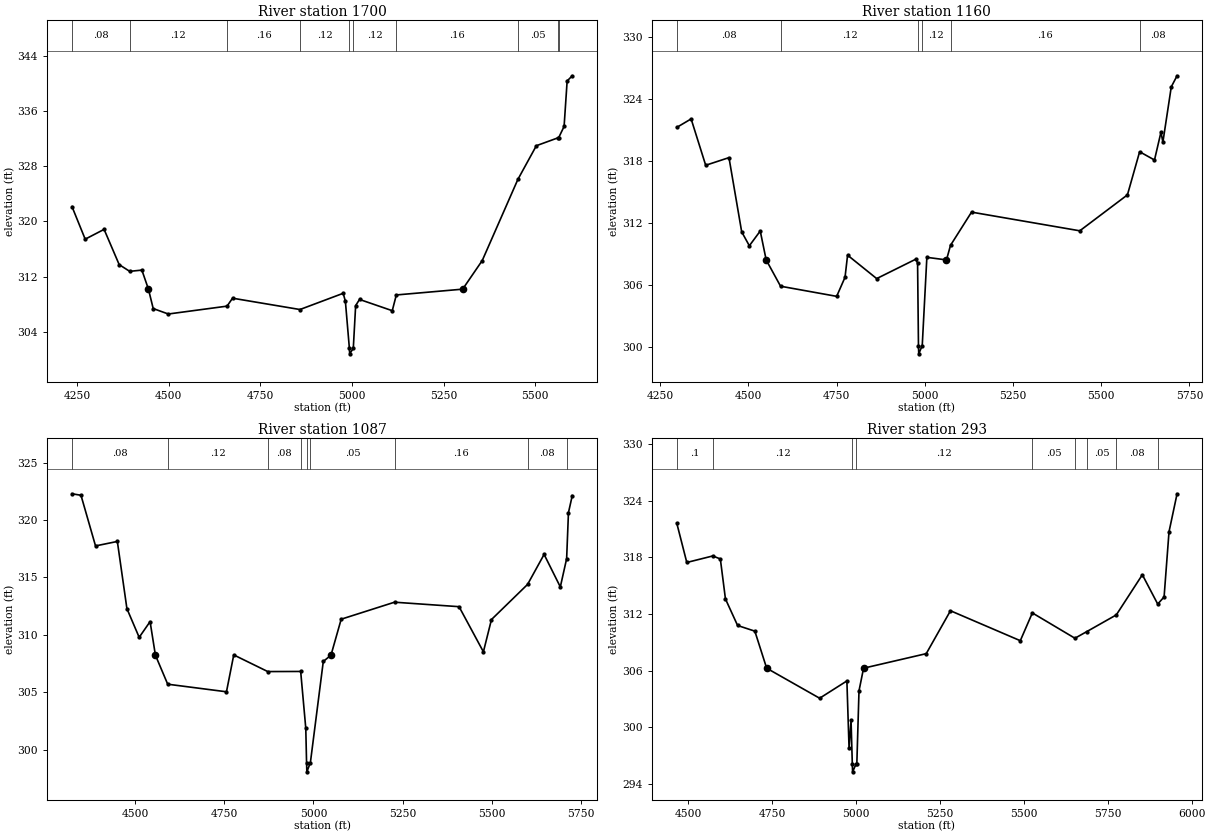
Type RM Length L Ch R = 1,1700,540,540,540
BEGIN DESCRIPTION:
BLACK CREEK 2.0
END DESCRIPTION:
XS GIS Cut Line= 3
      2935100.01      6928249.97      2935270.17      6927569.76
      2934975.02      6926975.04
#Sta/Elev= 30
  4235.7  322.15  4271.7  317.43  4323.3  318.85  4364.5  313.74  4393.2  312.77
  4426.4  312.95  4444.3  310.19  4457.3  307.38  4498.5  306.59  4658.8  307.73
  4673.8  308.88  4857.7  307.24  4975.7  309.59  4981.7  308.43  4992.6  301.62
  4993.4  300.82  5003.3  301.62  5009.7  307.81  5020.3  308.70  5109.6  307.07
  5120.7  309.35  5301.7  310.19  5355.2  314.34  5452.3  326.08  5502.8  330.97
  5562.8  332.13  5563.4  332.10  5578.5  333.76  5586.8  340.35  5600.8  341.10
#Mann=10,-1,0
  4235.7    0.08       0  4393.2    0.12       0  4658.8    0.16       0
  4857.7    0.12       0  4992.6    0.07       0  5003.3    0.12       0
  5120.7    0.16       0  5452.3    0.05       0  5562.8    0.08       0
  5563.4    0.05       0
Bank Sta=4444.3,5301.7
Exp/Cntr=0.3,0.1

Type RM Length L Ch R = 1,1160,73,73,73
BEGIN DESCRIPTION:
Mapping XS 445313af
END DESCRIPTION:
XS GIS Cut Line= 3
      2935474.16      6928164.39      2935647.78      6927474.27
      2935374.32      6926823.19
#Sta/Elev= 30
  4297.2  321.25  4337.8  322.07  4379.1  317.58  4445.1  318.32  4481.1  311.13
  4502.8  309.78  4533.7  311.21  4550.5  308.41  4591.3  305.86  4750.3  304.88
  4774.0  306.73  4781.2  308.87  4863.7  306.60  4974.5  308.48  4979.6  308.10
  4982.1  300.11  4982.9  299.31  4992.8  300.11  5005.9  308.66  5061.5  308.41
  5072.9  309.82  5132.5  313.04  5439.3  311.23  5574.3  314.71  5608.9  318.89
  5651.0  318.09  5669.4  320.79  5674.8  319.82  5698.6  325.18  5715.0  326.25
#Mann=6,-1,0
  4297.2    0.08       0  4591.3    0.12       0  4982.1    0.07       0
  4992.8    0.12       0  5072.9    0.16       0  5608.9    0.08       0
Bank Sta=4550.5,5061.5
Exp/Cntr=0.3,0.1

Type RM Length L Ch R = 1,1087,794,794,794
BEGIN DESCRIPTION:
Mapping XS 84756307
END DESCRIPTION:
XS GIS Cut Line= 5
      2935539.27      6928129.67      2935639.10      6927634.86
      2935717.22      6927491.63      2935699.86      6927305.00
      2935465.47      6926810.18
#Sta/Elev= 30
  4323.1  322.28  4348.3  322.15  4389.1  317.74  4450.3  318.13  4477.1  312.28
  4511.5  309.78  4542.1  311.15  4557.0  308.23  4591.5  305.70  4756.3  305.04
  4776.7  308.25  4872.1  306.80  4964.4  306.81  4978.7  301.86  4980.9  298.87
  4981.7  298.07  4991.6  298.87  5027.8  307.68  5049.4  308.23  5078.0  311.36
  5227.5  312.84  5408.5  312.45  5476.8  308.52  5499.4  311.33  5600.7  314.39
  5647.0  317.00  5692.5  314.17  5710.2  316.63  5715.3  320.64  5726.0  322.12
#Mann=9,-1,0
  4323.1    0.08       0  4591.5    0.12       0  4872.1    0.08       0
  4964.4    0.05       0  4980.9    0.04       0  4991.6    0.05       0
  5227.5    0.16       0  5600.7    0.08       0  5710.2    0.16       0
Bank Sta=4557,5049.4
Exp/Cntr=0.3,0.1

Type RM Length L Ch R = 1,293,0,0,0
BEGIN DESCRIPTION:
BLACK CREEK 1.0
END DESCRIPTION:
XS GIS Cut Line= 3
      2935799.99      6928000.02      2936091.13      6927552.01
      2935526.33      6926779.94
#Sta/Elev= 30
  4465.7  321.60  4495.5  317.45  4573.0  318.14  4595.5  317.82  4610.7  313.59
  4646.9  310.78  4698.3  310.18  4733.5  306.26  4891.4  303.08  4972.6  304.91
  4979.1  297.78  4985.0  300.74  4988.8  296.09  4989.6  295.29  4999.6  296.09
  5002.2  296.09  5008.7  303.86  5022.3  306.26  5209.1  307.80  5281.3  312.34
  5489.4  309.17  5525.3  312.11  5652.2  309.43  5687.9  310.14  5775.5  311.90
  5853.1  316.15  5898.9  313.05  5917.9  313.80  5932.6  320.70  5956.6  324.72
#Mann=9,-1,0
  4465.7     0.1       0  4573.0    0.12       0  4988.8    0.07       0
  4999.6    0.12       0  5525.3    0.05       0  5652.2    0.12       0
  5687.9    0.05       0  5775.5    0.08       0  5898.9    0.16       0
Bank Sta=4733.5,5022.3
Exp/Cntr=0.3,0.1

Chan Stop Cuts=-1