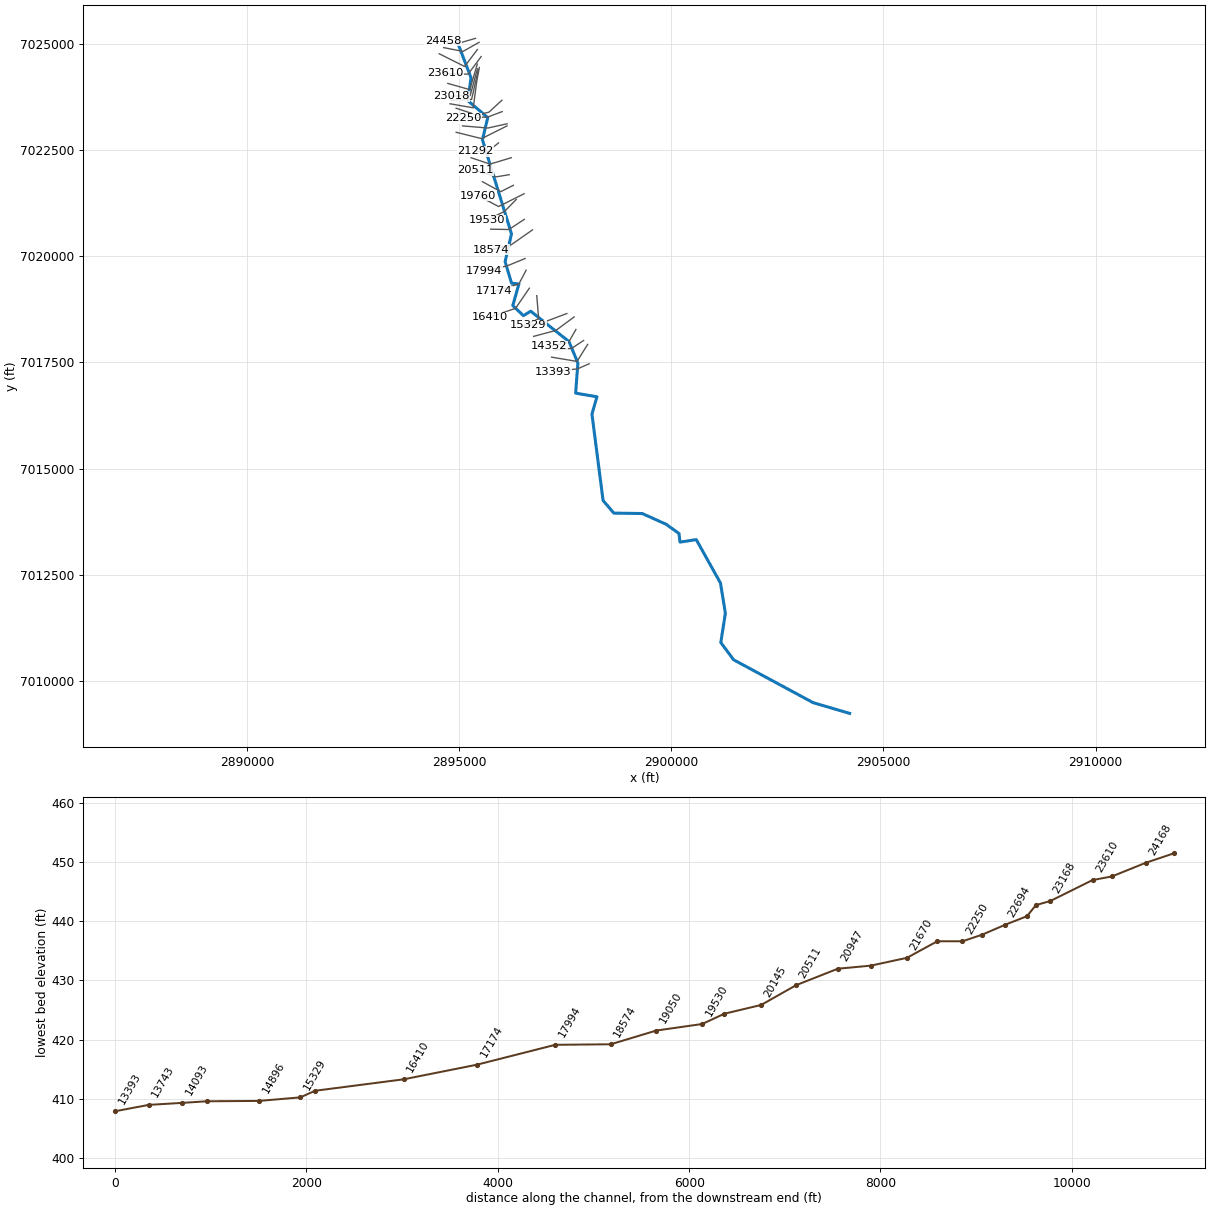
--- BRUSHY CREEK.prj (project) ---

Proj Title=BRUSHY CREEK Base Level Engineering
Current Plan=p01
Default Exp/Contr=0.3,0.1
English Units
Geom File=g01
Flow File=f01
Plan File=p01
BEGIN DESCRIPTION:
BRUSHY CREEK
END DESCRIPTION:

--- BRUSHY CREEK.p01 (plan) ---

Plan Title=Multiple Run
Short Identifier=Multiple
Geom File=g01
Flow File=f01
Subcritical Flow
K Sum by GR= 0
Std Step Tol= 0.01
Critical Tol= 0.01
Num of Std Step Trials= 20
Max Error Tol= 0.3
Flow Tol Ratio= 0.001
Split Flow NTrial= 30
Split Flow Tol= 0.02
Split Flow Ratio= 0.02
Log Output Level= 0
Friction Slope Method= 1
Unsteady Friction Slope Method= 2
Unsteady Bridges Friction Slope Method= 1
Parabolic Critical Depth
Global Vel Dist=  1 , 1 , 1
Global Log Level= 0
CheckData=True
Encroach Param= -1, 0, 0, 0
BEGIN DESCRIPTION:
Multiple Run
END DESCRIPTION:

--- BRUSHY CREEK.f01 (steady flow) ---

Flow Title=Multiple
Program Version=5.07
Number of Profiles= 7
Profile Names=10-year,25-year,50-year,1pct_min,100-year,1pct_plu,500-year
River Rch & RM=BRUSHY CREEK,Reach-1         ,24458
     333     433     512     302     603    1202     835
River Rch & RM=BRUSHY CREEK,Reach-1         ,22454
     589     792     959     578    1153    2300    1666
River Rch & RM=BRUSHY CREEK,Reach-1         ,19530
     880    1210    1485     905    1806    3603    2676
River Rch & RM=BRUSHY CREEK,Reach-1         ,15329
     944    1299    1596     973    1942    3875    2882
River Rch & RM=BRUSHY CREEK,Reach-1         ,12217
    1228    1711    2117    1300    2594    5175    3901
River Rch & RM=BRUSHY CREEK,Reach-1         ,8358
    1445    2022    2510    1544    3081    6147    4654
River Rch & RM=BRUSHY CREEK,Reach-1         ,2805
    1742    2452    3055    1885    3761    7503    5714
Boundary for River Rch & Prof#=BRUSHY CREEK,Reach-1         , 1
Up Type= 0
Dn Type= 3
Dn Slope=0.005
Boundary for River Rch & Prof#=BRUSHY CREEK,Reach-1         , 2
Up Type= 0
Dn Type= 3
Dn Slope=0.005
Boundary for River Rch & Prof#=BRUSHY CREEK,Reach-1         , 3
Up Type= 0
Dn Type= 3
Dn Slope=0.005
Boundary for River Rch & Prof#=BRUSHY CREEK,Reach-1         , 4
Up Type= 0
Dn Type= 3
Dn Slope=0.005
Boundary for River Rch & Prof#=BRUSHY CREEK,Reach-1         , 5
Up Type= 0
Dn Type= 3
Dn Slope=0.005
Boundary for River Rch & Prof#=BRUSHY CREEK,Reach-1         , 6
Up Type= 0
Dn Type= 3
Dn Slope=0.005
Boundary for River Rch & Prof#=BRUSHY CREEK,Reach-1         , 7
Up Type= 0
Dn Type= 3
Dn Slope=0.005
DSS Import GetInterval= 0
DSS Import GetPeak= 0
DSS Import FillOption= 0

--- BRUSHY CREEK.g01 (geometry) ---

Geom Title=Existing Conditions

River Reach=BRUSHY CREEK,Reach-1
Reach XY= 30
      2894944.72      7025075.40      2895274.44      7024210.84
      2895201.66      7023668.07      2895669.54      7023270.42
      2895544.54      7022748.54      2896229.30      7020530.51
      2896079.83      7019875.55      2896230.89      7019367.65
      2896404.53      7019350.27      2896260.20      7018841.44
      2896509.89      7018603.33      2896682.74      7018707.77
      2897585.87      7017990.69      2897795.01      7017486.41
      2897741.41      7016777.89      2898244.35      7016690.58
      2898126.18      7016284.48      2898388.95      7014246.91
      2898642.86      7013949.60      2899310.42      7013940.48
      2899873.33      7013688.09      2900179.32      7013468.91
      2900201.02      7013267.09      2900586.30      7013324.99
      2901157.48      7012300.85      2901272.07      7011589.05
      2901164.43      7010899.81      2901466.51      7010493.56
      2903341.51      7009483.15      2904201.91      7009230.64

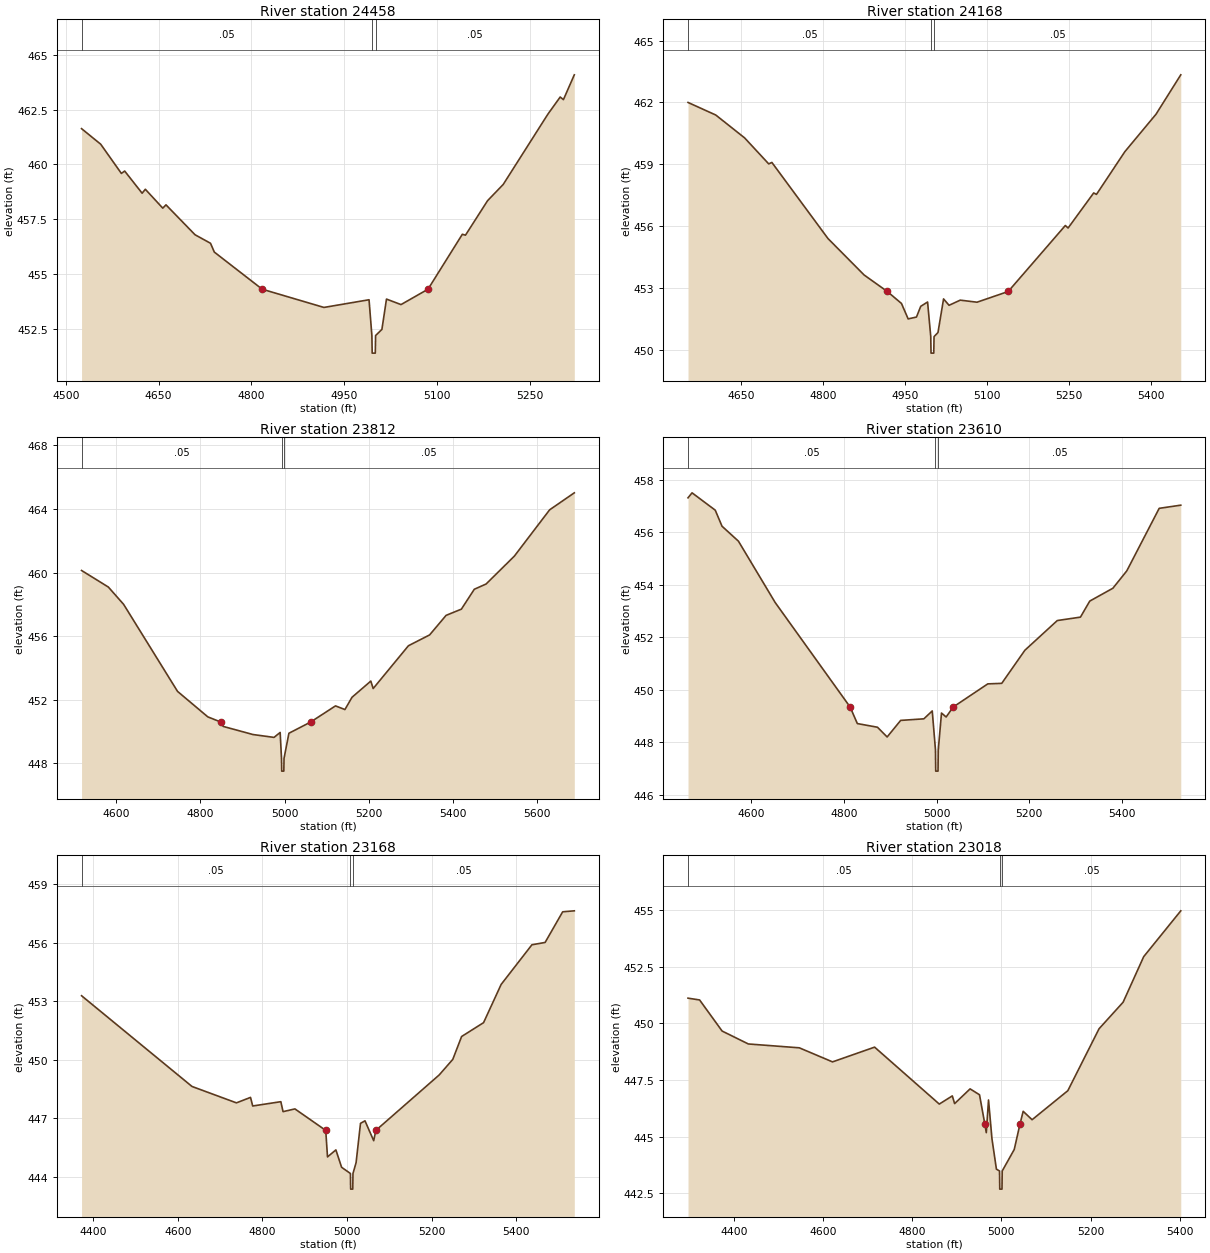
Type RM Length L Ch R = 1,24458,290,290,290
BEGIN DESCRIPTION:
BRUSHY CREEK 41.0
END DESCRIPTION:
XS GIS Cut Line= 3
      2895380.98      7025138.38      2894925.54      7025004.90
      2894613.64      7025084.54
#Sta/Elev= 30
  4525.4  461.63  4556.4  460.92  4589.8  459.59  4595.1  459.70  4623.3  458.69
  4628.5  458.87  4656.7  458.01  4661.9  458.16  4708.8  456.80  4733.9  456.41
  4740.0  456.01  4817.4  454.32  4917.2  453.49  4990.1  453.84  4994.7  452.21
  4995.2  451.41  5000.2  451.41  5000.7  452.21  5010.9  452.49  5018.3  453.87
  5041.8  453.62  5085.4  454.32  5140.9  456.82  5146.0  456.78  5181.7  458.35
  5207.0  459.09  5279.2  462.29  5299.1  463.07  5304.3  462.95  5321.9  464.08
#Mann=3,-1,0
  4525.4    0.05       0  4994.7    0.03       0  5000.7    0.05       0
Bank Sta=4817.4,5085.4
Exp/Cntr=0.3,0.1

Type RM Length L Ch R = 1,24168,356,356,356
BEGIN DESCRIPTION:
Mapping XS b6483f39
END DESCRIPTION:
XS GIS Cut Line= 3
      2895464.99      7025044.45      2895087.38      7024830.90
      2894629.56      7024919.35
#Sta/Elev= 30
  4553.7  462.00  4604.4  461.39  4657.1  460.28  4701.1  459.02  4706.9  459.09
  4809.3  455.40  4875.4  453.63  4917.7  452.83  4943.6  452.25  4955.8  451.50
  4971.0  451.59  4978.8  452.11  4991.3  452.32  4997.1  450.64  4997.6  449.84
  5002.6  449.84  5003.1  450.64  5010.3  450.84  5020.5  452.47  5030.5  452.16
  5051.0  452.41  5081.6  452.31  5138.6  452.83  5242.9  456.03  5248.0  455.91
  5294.7  457.61  5299.8  457.54  5351.6  459.61  5408.6  461.43  5453.8  463.34
#Mann=3,-1,0
  4553.7    0.05       0  4997.1    0.03       0  5003.1    0.05       0
Bank Sta=4917.7,5138.6
Exp/Cntr=0.3,0.1

Type RM Length L Ch R = 1,23812,202,202,202
BEGIN DESCRIPTION:
BRUSHY CREEK 40.0
END DESCRIPTION:
XS GIS Cut Line= 3
      2895425.01      7024875.01      2895125.00      7024475.00
      2894525.03      7024774.99
#Sta/Elev= 30
  4517.5  460.13  4581.1  459.09  4617.5  458.00  4745.6  452.53  4817.5  450.93
  4848.7  450.60  4854.0  450.33  4924.8  449.82  4974.8  449.64  4989.4  449.95
  4992.6  448.32  4993.1  447.52  4998.1  447.52  4998.6  448.32  5010.2  449.90
  5061.5  450.60  5120.9  451.62  5143.3  451.39  5160.1  452.16  5204.8  453.18
  5210.4  452.71  5294.2  455.40  5344.5  456.08  5383.7  457.31  5420.0  457.70
  5450.7  458.95  5478.7  459.28  5545.8  461.03  5629.6  463.94  5688.3  465.01
#Mann=3,-1,0
  4517.5    0.05       0  4992.6    0.03       0  4998.6    0.05       0
Bank Sta=4848.7,5061.5
Exp/Cntr=0.3,0.1

Type RM Length L Ch R = 1,23610,442,442,442
BEGIN DESCRIPTION:
Mapping XS 7ddb3437
END DESCRIPTION:
XS GIS Cut Line= 3
      2895514.13      7024708.44      2895205.96      7024293.92
      2894658.46      7024311.24
#Sta/Elev= 30
  4462.9  457.31  4471.6  457.50  4521.7  456.84  4536.3  456.23  4571.8  455.66
  4651.0  453.33  4813.0  449.35  4828.6  448.72  4872.1  448.58  4893.0  448.21
  4922.2  448.84  4972.3  448.90  4990.4  449.20  4997.4  447.71  4997.9  446.91
  5002.9  446.91  5003.4  447.71  5010.4  449.12  5020.4  448.97  5035.7  449.35
  5110.4  450.23  5140.5  450.25  5190.5  451.51  5260.5  452.64  5310.5  452.77
  5330.6  453.38  5380.6  453.87  5410.6  454.53  5480.6  456.91  5527.2  457.03
#Mann=3,-1,0
  4462.9    0.05       0  4997.4    0.03       0  5003.4    0.05       0
Bank Sta=4813,5035.7
Exp/Cntr=0.3,0.1

Type RM Length L Ch R = 1,23168,150,150,150
BEGIN DESCRIPTION:
BRUSHY CREEK 39.0
END DESCRIPTION:
XS GIS Cut Line= 3
      2895423.66      7024531.56      2895245.72      7023929.82
      2894728.54      7024075.45
#Sta/Elev= 30
  4372.5  453.28  4633.6  448.63  4738.6  447.79  4771.9  448.07  4777.1  447.63
  4843.6  447.85  4848.8  447.34  4876.9  447.48  4949.7  446.38  4953.9  445.02
  4973.7  445.38  4987.2  444.49  5008.1  444.17  5008.6  443.37  5013.6  443.37
  5014.1  444.17  5021.5  444.73  5031.9  446.74  5042.5  446.87  5063.1  445.85
  5068.2  446.38  5217.9  449.22  5250.1  450.02  5270.9  451.19  5322.8  451.90
  5364.4  453.86  5437.1  455.89  5468.3  456.01  5509.8  457.58  5537.3  457.63
#Mann=3,-1,0
  4372.5    0.05       0  5008.1    0.03       0  5014.1    0.05       0
Bank Sta=4949.7,5068.2
Exp/Cntr=0.3,0.1

Type RM Length L Ch R = 1,23018,93,93,93
BEGIN DESCRIPTION:
double BRUSHY CREEK 38.0
END DESCRIPTION:
XS GIS Cut Line= 3
      2895425.84      7024418.72      2895255.66      7023790.67
      2894801.91      7023775.70
#Sta/Elev= 30
  4297.5  451.11  4323.5  451.03  4373.9  449.66  4432.7  449.09  4547.0  448.92
  4621.5  448.30  4715.8  448.95  4860.8  446.44  4890.0  446.80  4895.2  446.46
  4929.9  447.11  4951.0  446.85  4963.0  445.55  4966.2  445.18  4971.2  446.62
  4978.9  444.91  4988.9  443.57  4995.9  443.49  4996.4  442.69  5001.4  442.69
  5001.9  443.49  5028.9  444.44  5041.6  445.55  5048.9  446.12  5068.9  445.75
  5149.0  447.03  5219.0  449.76  5272.9  450.93  5319.1  452.94  5402.2  454.96
#Mann=3,-1,0
  4297.5    0.05       0  4995.9    0.03       0  5001.9    0.05       0
Bank Sta=4963,5041.6
Exp/Cntr=0.3,0.1

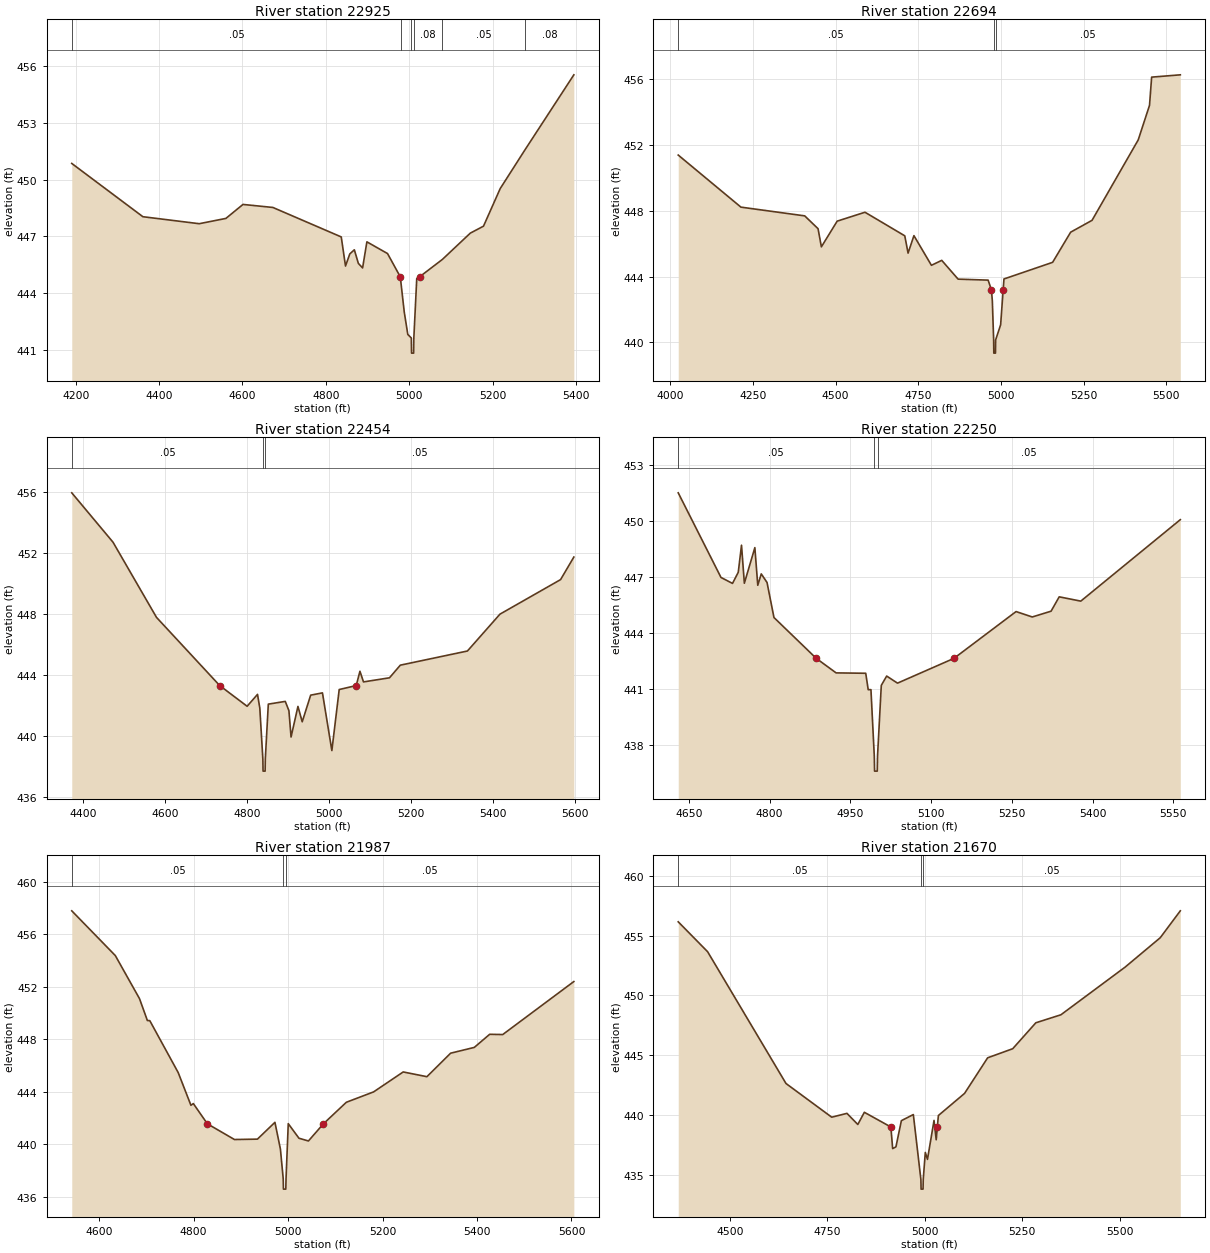
Type RM Length L Ch R = 1,22925,231,231,231
BEGIN DESCRIPTION:
double BRUSHY CREEK 37.0
END DESCRIPTION:
XS GIS Cut Line= 4
      2895447.54      7024405.68      2895289.06      7023699.91
      2895202.97      7023696.47      2894808.54      7023679.40
#Sta/Elev= 30
  4190.5  450.86  4361.1  448.04  4496.2  447.67  4560.2  447.95  4601.2  448.69
  4672.9  448.53  4836.9  446.97  4847.1  445.43  4857.4  446.07  4868.3  446.29
  4877.9  445.57  4888.1  445.33  4898.4  446.71  4947.9  446.09  4978.5  444.86
  4980.5  444.47  4988.0  443.00  4996.5  441.81  5005.0  441.62  5005.5  440.82
  5010.5  440.82  5011.0  441.62  5018.0  444.77  5024.9  444.86  5079.5  445.78
  5146.4  447.17  5178.1  447.54  5218.2  449.53  5277.6  451.58  5394.8  455.55
#Mann=6,-1,0
  4190.5    0.05       0  4980.5    0.08       0  5005.0    0.07       0
  5011.0    0.08       0  5079.5    0.05       0  5277.6    0.08       0
Bank Sta=4978.5,5024.9
Exp/Cntr=0.3,0.1

Type RM Length L Ch R = 1,22694,240,240,240
BEGIN DESCRIPTION:
Mapping XS 5907f1ec
END DESCRIPTION:
XS GIS Cut Line= 4
      2895471.42      7024451.29      2895408.48      7024117.10
      2895328.19      7023500.78      2894779.62      7023596.18
#Sta/Elev= 30
  4024.1  451.37  4213.7  448.21  4406.6  447.68  4447.0  446.90  4457.0  445.80
  4504.8  447.36  4588.9  447.90  4709.2  446.47  4719.2  445.42  4736.9  446.48
  4789.8  444.68  4821.0  444.98  4870.5  443.84  4961.3  443.78  4971.2  443.19
  4974.0  442.53  4978.0  440.15  4978.5  439.35  4983.5  439.35  4984.0  440.15
  4999.1  441.07  5006.8  443.19  5009.2  443.85  5156.3  444.86  5210.9  446.69
  5275.6  447.41  5415.2  452.29  5449.4  454.39  5455.8  456.10  5542.5  456.24
#Mann=3,-1,0
  4024.1    0.05       0  4978.0    0.03       0  4984.0    0.05       0
Bank Sta=4971.2,5006.8
Exp/Cntr=0.3,0.1

Type RM Length L Ch R = 1,22454,204,204,204
BEGIN DESCRIPTION:
double BRUSHY CREEK 36.0
END DESCRIPTION:
XS GIS Cut Line= 4
      2896002.41      7023679.35      2895700.00      7023400.00
      2895417.45      7023327.79      2894924.24      7023491.85
#Sta/Elev= 30
  4373.2  455.96  4473.6  452.72  4579.6  447.78  4733.6  443.30  4800.4  441.94
  4825.7  442.72  4831.3  441.82  4838.7  438.48  4839.2  437.68  4844.2  437.68
  4844.7  438.48  4852.0  442.08  4893.3  442.26  4902.2  441.65  4907.4  439.92
  4924.2  441.93  4934.6  440.92  4955.2  442.67  4983.9  442.82  5006.8  439.03
  5024.7  443.04  5066.2  443.30  5075.2  444.24  5083.9  443.54  5147.2  443.81
  5173.6  444.64  5337.1  445.57  5416.3  447.99  5564.0  450.26  5596.3  451.74
#Mann=3,-1,0
  4373.2    0.05       0  4838.7    0.03       0  4844.7    0.05       0
Bank Sta=4733.6,5066.2
Exp/Cntr=0.3,0.1

Type RM Length L Ch R = 1,22250,263,263,263
BEGIN DESCRIPTION:
Mapping XS d9207e65
END DESCRIPTION:
XS GIS Cut Line= 3
      2896009.27      7023411.78      2895678.51      7023286.76
      2895100.42      7023258.12
#Sta/Elev= 30
  4630.5  451.51  4709.9  446.97  4731.3  446.65  4742.0  447.25  4748.0  448.70
  4753.3  446.66  4772.8  448.57  4778.2  446.55  4784.7  447.16  4795.4  446.70
  4808.3  444.82  4886.8  442.63  4923.7  441.85  4978.7  441.83  4983.3  440.95
  4988.4  440.95  4994.6  437.38  4995.1  436.58  5000.1  436.58  5000.6  437.38
  5007.6  441.18  5017.6  441.68  5037.7  441.30  5142.6  442.63  5257.9  445.14
  5288.0  444.85  5322.9  445.16  5338.0  445.93  5378.1  445.70  5562.9  450.07
#Mann=3,-1,0
  4630.5    0.05       0  4994.6    0.03       0  5000.6    0.05       0
Bank Sta=4886.8,5142.6
Exp/Cntr=0.3,0.1

Type RM Length L Ch R = 1,21987,317,317,317
BEGIN DESCRIPTION:
BRUSHY CREEK 35.0
END DESCRIPTION:
XS GIS Cut Line= 3
      2896125.00      7023125.00      2895675.00      7023025.00
      2895074.96      7023075.00
#Sta/Elev= 30
  4542.0  457.79  4634.2  454.38  4685.4  451.10  4702.1  449.43  4707.2  449.42
  4767.4  445.46  4794.3  442.97  4799.4  443.10  4829.1  441.56  4886.5  440.36
  4935.1  440.39  4972.2  441.67  4983.8  439.63  4989.7  437.38  4990.2  436.58
  4995.2  436.58  4995.7  437.38  5000.4  441.57  5023.0  440.46  5043.1  440.25
  5074.9  441.56  5123.4  443.20  5181.1  443.99  5243.8  445.51  5294.0  445.15
  5344.2  446.94  5394.3  447.38  5426.9  448.38  5454.5  448.36  5605.1  452.40
#Mann=3,-1,0
  4542.0    0.05       0  4989.7    0.03       0  4995.7    0.05       0
Bank Sta=4829.1,5074.9
Exp/Cntr=0.3,0.1

Type RM Length L Ch R = 1,21670,378,378,378
BEGIN DESCRIPTION:
BRUSHY CREEK 34.0
END DESCRIPTION:
XS GIS Cut Line= 3
      2896124.96      7023074.98      2895525.00      7022775.00
      2894925.04      7022924.99
#Sta/Elev= 30
  4366.9  456.16  4442.3  453.66  4643.6  442.63  4761.0  439.81  4800.1  440.13
  4828.0  439.20  4844.8  440.22  4912.9  438.99  4917.5  437.18  4925.9  437.33
  4939.9  439.52  4970.6  440.03  4990.0  434.59  4990.5  433.79  4995.5  433.79
  4996.0  434.59  5001.3  436.86  5006.9  436.28  5023.7  439.54  5029.3  437.92
  5032.2  438.98  5034.9  439.95  5102.1  441.80  5161.4  444.78  5225.8  445.54
  5285.1  447.71  5349.5  448.38  5514.4  452.37  5604.6  454.83  5656.1  457.08
#Mann=3,-1,0
  4366.9    0.05       0  4990.0    0.03       0  4996.0    0.05       0
Bank Sta=4912.9,5032.2
Exp/Cntr=0.3,0.1

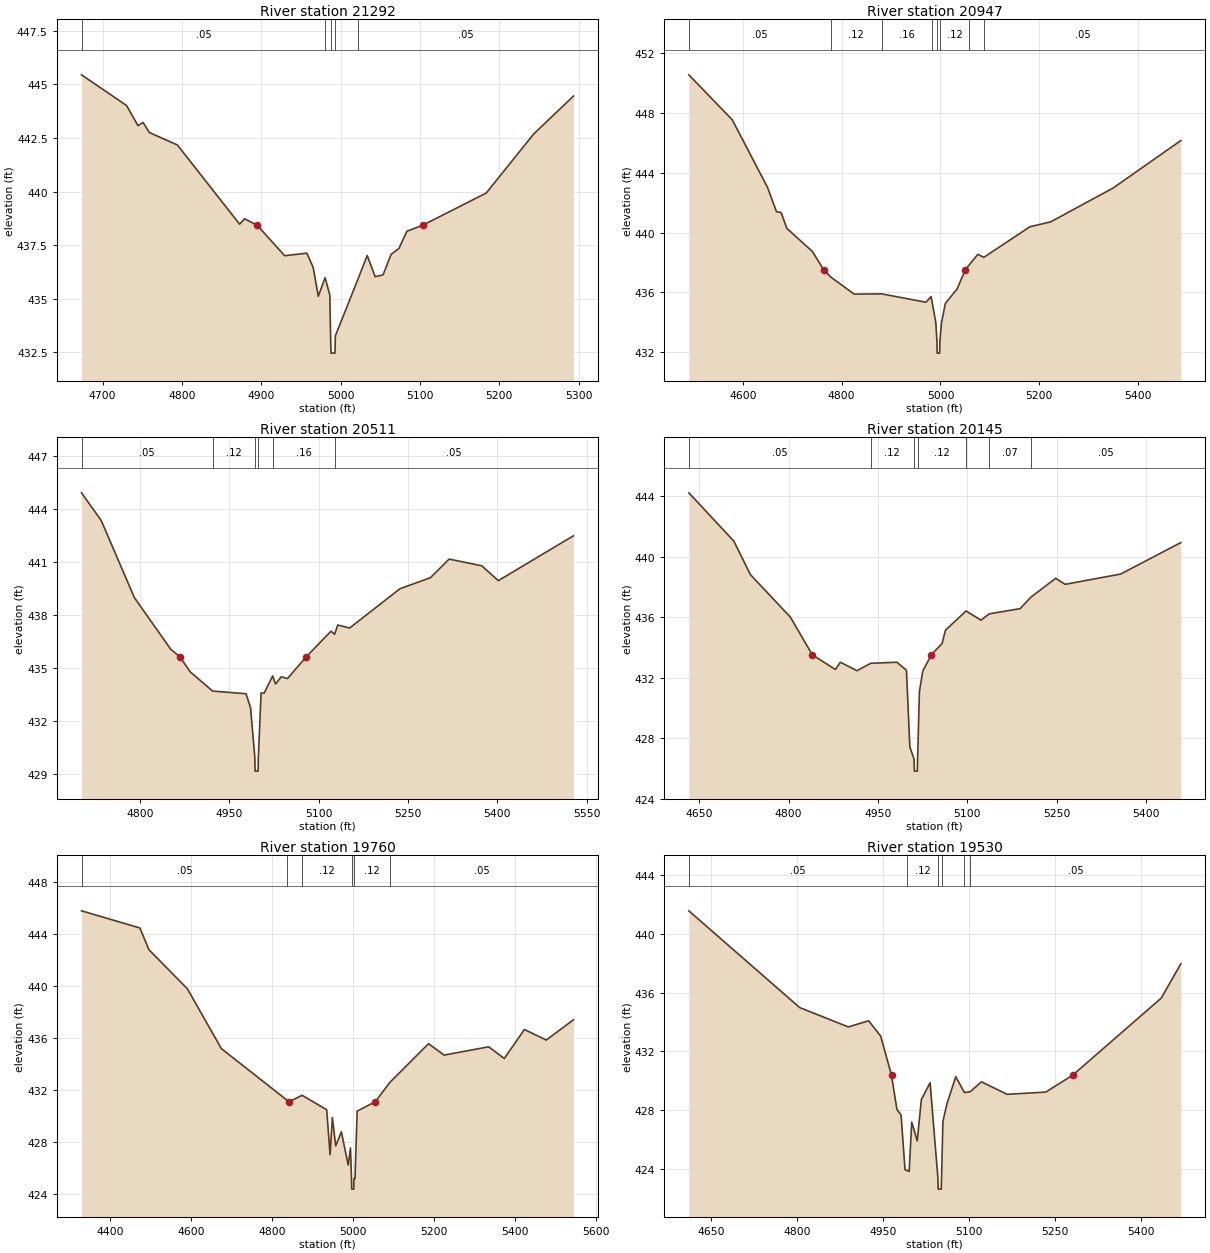
Type RM Length L Ch R = 1,21292,345,345,345
BEGIN DESCRIPTION:
BRUSHY CREEK 33.0
END DESCRIPTION:
XS GIS Cut Line= 3
      2895925.00      7022675.00      2895675.00      7022475.00
      2895374.96      7022475.00
#Sta/Elev= 30
  4673.4  445.44  4730.2  444.01  4744.6  443.07  4751.0  443.22  4759.0  442.75
  4794.3  442.17  4872.7  438.48  4879.1  438.73  4894.9  438.43  4929.5  437.01
  4957.5  437.13  4965.5  436.46  4971.9  435.12  4980.5  435.99  4986.4  435.18
  4987.4  433.27  4987.9  432.47  4992.9  432.47  4993.4  433.27  5021.5  435.88
  5033.6  437.02  5043.6  436.03  5053.6  436.12  5063.6  437.07  5073.6  437.35
  5083.6  438.15  5103.5  438.43  5183.6  439.93  5243.6  442.69  5293.6  444.45
#Mann=5,-1,0
  4673.4    0.05       0  4980.5    0.12       0  4987.4    0.07       0
  4993.4    0.12       0  5021.5    0.05       0
Bank Sta=4894.9,5103.5
Exp/Cntr=0.3,0.1

Type RM Length L Ch R = 1,20947,436,436,436
BEGIN DESCRIPTION:
BRUSHY CREEK 32.0
END DESCRIPTION:
XS GIS Cut Line= 3
      2896224.96      7022324.99      2895725.00      7022175.00
      2895275.01      7022325.00
#Sta/Elev= 30
  4490.5  450.54  4578.3  447.54  4649.7  443.03  4667.9  441.40  4677.5  441.34
  4688.8  440.29  4741.0  438.73  4763.7  437.50  4778.0  437.03  4825.4  435.89
  4880.7  435.91  4970.7  435.35  4981.1  435.73  4983.4  435.31  4990.7  433.98
  4992.9  432.75  4993.4  431.95  4998.4  431.95  4998.9  432.75  5002.0  433.96
  5009.9  435.27  5033.6  436.23  5050.2  437.50  5058.4  437.85  5075.7  438.55
  5087.9  438.35  5181.1  440.39  5223.3  440.72  5349.8  442.98  5486.8  446.15
#Mann=8,-1,0
  4490.5    0.05       0  4778.0    0.12       0  4880.7    0.16       0
  4983.4    0.12       0  4992.9    0.07       0  4998.9    0.12       0
  5058.4    0.16       0  5087.9    0.05       0
Bank Sta=4763.7,5050.2
Exp/Cntr=0.3,0.1

Type RM Length L Ch R = 1,20511,366,366,366
BEGIN DESCRIPTION:
BRUSHY CREEK 31.0
END DESCRIPTION:
XS GIS Cut Line= 3
      2896175.04      7021925.01      2895875.00      7021875.00
      2895375.00      7022025.00
#Sta/Elev= 30
  4701.7  444.92  4734.7  443.36  4790.5  438.99  4851.3  436.08  4866.9  435.64
  4884.2  434.79  4922.0  433.70  4978.0  433.55  4985.6  432.75  4992.7  429.97
  4993.2  429.17  4998.2  429.17  4998.7  429.97  5003.3  433.59  5008.5  433.59
  5022.7  434.56  5027.6  434.10  5037.2  434.51  5047.6  434.41  5079.1  435.64
  5120.7  437.09  5126.8  436.91  5132.0  437.44  5152.0  437.27  5236.4  439.49
  5287.8  440.12  5319.1  441.17  5373.9  440.79  5401.7  439.95  5527.9  442.49
#Mann=6,-1,0
  4701.7    0.05       0  4922.0    0.12       0  4992.7    0.07       0
  4998.7    0.12       0  5022.7    0.16       0  5126.8    0.05       0
Bank Sta=4866.9,5079.1
Exp/Cntr=0.3,0.1

Type RM Length L Ch R = 1,20145,385,385,385
BEGIN DESCRIPTION:
BRUSHY CREEK 30.0
END DESCRIPTION:
XS GIS Cut Line= 3
      2896274.99      7021675.00      2895975.00      7021525.00
      2895544.52      7021760.11
#Sta/Elev= 30
  4632.7  444.23  4708.2  441.04  4736.1  438.82  4803.2  436.01  4840.0  433.52
  4878.7  432.55  4887.0  433.03  4915.0  432.47  4938.0  432.96  4981.9  433.03
  4998.0  432.50  5003.7  427.44  5010.7  426.63  5011.2  425.83  5016.2  425.83
  5016.7  426.63  5019.8  431.10  5025.5  432.46  5039.8  433.52  5057.8  434.27
  5063.5  435.15  5098.1  436.42  5123.2  435.81  5136.9  436.23  5188.7  436.57
  5206.9  437.33  5248.5  438.58  5264.4  438.18  5357.6  438.86  5458.6  440.94
#Mann=7,-1,0
  4632.7    0.05       0  4938.0    0.12       0  5010.7    0.07       0
  5016.7    0.12       0  5098.1    0.05       0  5136.9    0.07       0
  5206.9    0.05       0
Bank Sta=4840,5039.8
Exp/Cntr=0.3,0.1

Type RM Length L Ch R = 1,19760,230,230,230
BEGIN DESCRIPTION:
BRUSHY CREEK 29.0
END DESCRIPTION:
XS GIS Cut Line= 3
      2896526.07      7021475.86      2895925.00      7021175.00
      2895445.61      7021427.96
#Sta/Elev= 30
  4329.4  445.76  4473.5  444.44  4495.8  442.77  4590.8  439.76  4674.6  435.16
  4837.5  431.17  4842.4  431.08  4873.8  431.57  4934.5  430.46  4942.9  427.00
  4948.5  429.85  4956.8  427.68  4970.8  428.76  4987.6  426.20  4993.2  427.52
  4995.8  425.15  4996.3  424.35  5001.3  424.35  5001.8  425.15  5004.4  425.15
  5009.7  430.35  5054.7  431.08  5090.1  432.55  5185.9  435.54  5224.3  434.66
  5334.4  435.30  5372.8  434.40  5422.5  436.63  5476.5  435.82  5543.6  437.38
#Mann=6,-1,0
  4329.4    0.05       0  4837.5    0.07       0  4873.8    0.12       0
  4995.8    0.07       0  5001.8    0.12       0  5090.1    0.05       0
Bank Sta=4842.4,5054.7
Exp/Cntr=0.3,0.1

Type RM Length L Ch R = 1,19530,480,480,480
BEGIN DESCRIPTION:
BRUSHY CREEK 28.0
END DESCRIPTION:
XS GIS Cut Line= 3
      2896341.78      7021341.60      2896069.92      7021063.50
      2895649.56      7020854.85
#Sta/Elev= 30
  4611.1  441.58  4804.4  434.99  4889.2  433.67  4924.7  434.09  4945.8  433.04
  4964.6  430.38  4974.1  428.04  4981.3  427.67  4988.2  423.94  4991.6  423.89
  4995.4  423.83  4999.9  427.19  5009.5  425.91  5016.7  428.72  5031.9  429.87
  5045.5  423.42  5046.0  422.62  5051.4  422.62  5051.9  423.42  5054.3  427.24
  5061.3  428.43  5076.7  430.28  5091.9  429.20  5102.0  429.26  5121.5  429.93
  5166.3  429.08  5233.6  429.23  5280.6  430.38  5435.3  435.64  5469.3  437.97
#Mann=6,-1,0
  4611.1    0.05       0  4991.6    0.12       0  5045.5    0.07       0
  5051.9    0.12       0  5091.9    0.16       0  5102.0    0.05       0
Bank Sta=4964.6,5280.6
Exp/Cntr=0.3,0.1

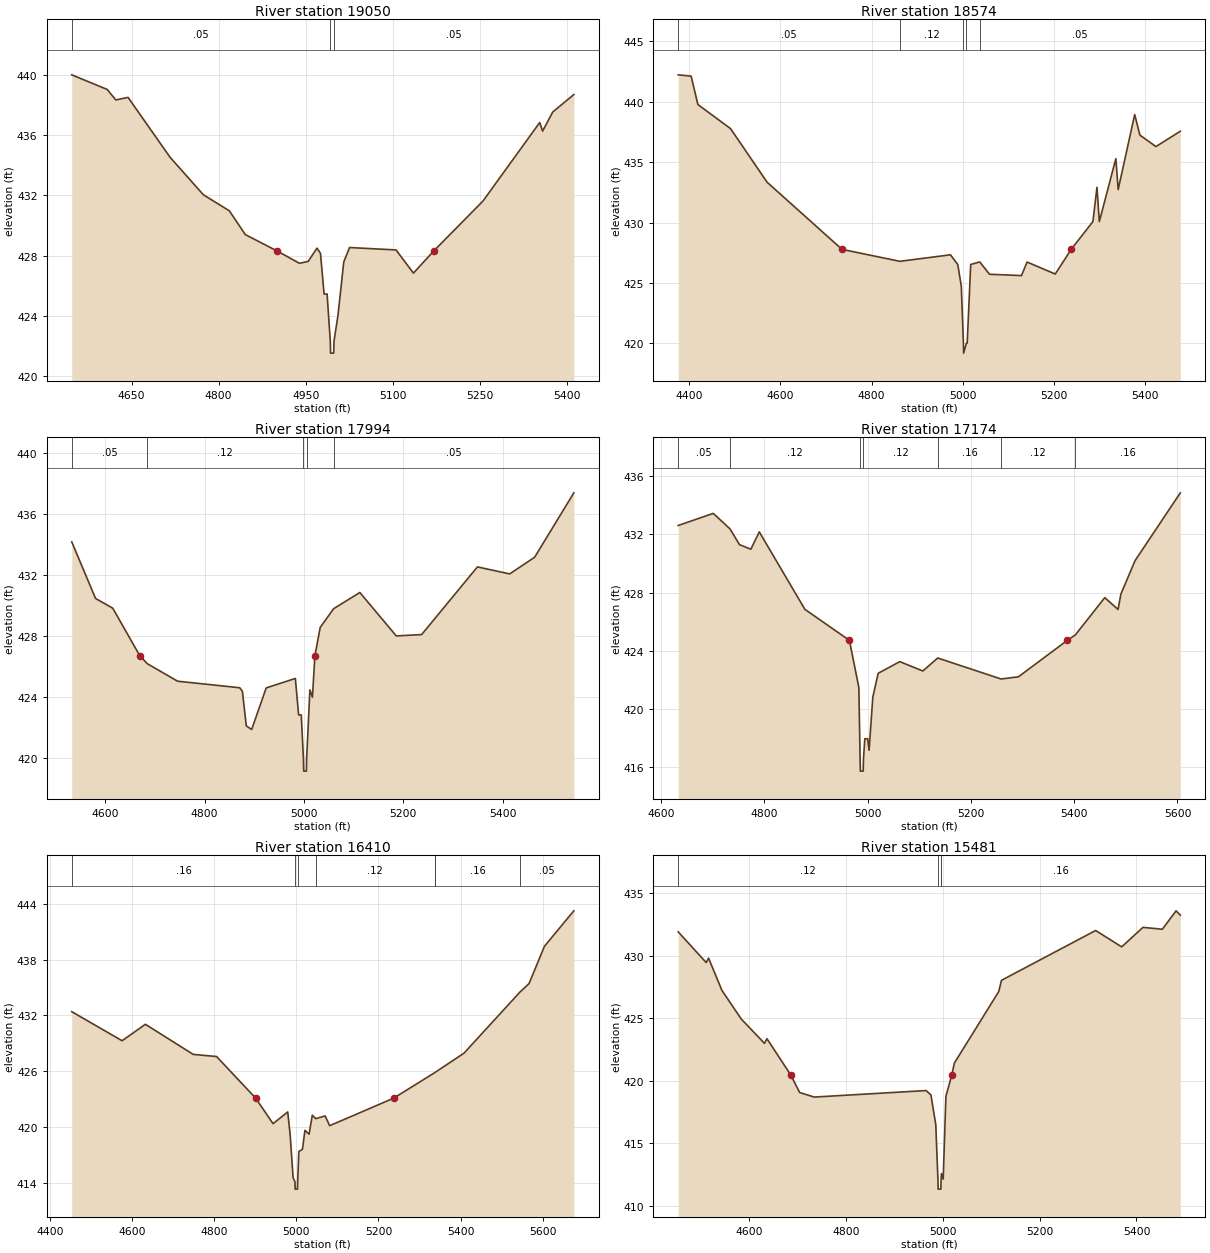
Type RM Length L Ch R = 1,19050,476,476,476
BEGIN DESCRIPTION:
Mapping XS 3ddd1f76
END DESCRIPTION:
XS GIS Cut Line= 3
      2896531.81      7020872.79      2896167.27      7020633.23
      2895738.75      7020641.03
#Sta/Elev= 30
  4547.0  440.02  4607.9  439.05  4622.9  438.35  4644.0  438.52  4716.3  434.54
  4773.6  432.05  4818.4  430.98  4845.9  429.40  4900.7  428.31  4939.3  427.49
  4954.3  427.62  4969.4  428.50  4975.4  428.15  4981.6  425.45  4986.8  425.45
  4992.3  422.32  4992.8  421.52  4998.2  421.52  4998.7  422.32  5005.5  424.02
  5015.5  427.58  5025.5  428.54  5105.5  428.38  5135.5  426.84  5170.5  428.31
  5255.5  431.64  5353.0  436.85  5358.0  436.28  5375.5  437.55  5411.8  438.71
#Mann=3,-1,0
  4547.0    0.05       0  4992.3    0.03       0  4998.7    0.05       0
Bank Sta=4900.7,5170.5
Exp/Cntr=0.3,0.1

Type RM Length L Ch R = 1,18574,580,580,580
BEGIN DESCRIPTION:
BRUSHY CREEK 27.0
END DESCRIPTION:
XS GIS Cut Line= 3
      2896724.96      7020624.97      2896225.00      7020275.00
      2895749.01      7020156.92
#Sta/Elev= 30
  4376.2  442.24  4404.5  442.13  4419.3  439.78  4490.8  437.79  4571.0  433.35
  4735.2  427.79  4862.1  426.80  4973.0  427.34  4989.1  426.53  4996.8  424.73
  5001.4  420.00  5001.9  419.20  5007.8  420.00  5009.7  420.03  5017.4  426.54
  5037.3  426.75  5058.6  425.73  5128.7  425.62  5141.0  426.74  5202.8  425.75
  5237.7  427.79  5285.3  430.09  5294.2  432.93  5299.4  430.09  5335.6  435.30
  5340.7  432.74  5376.9  438.95  5388.3  437.25  5423.5  436.30  5476.9  437.57
#Mann=5,-1,0
  4376.2    0.05       0  4862.1    0.12       0  5001.4    0.07       0
  5007.8    0.12       0  5037.3    0.05       0
Bank Sta=4735.2,5237.7
Exp/Cntr=0.3,0.1

Type RM Length L Ch R = 1,17994,820,820,820
BEGIN DESCRIPTION:
BRUSHY CREEK 26.0
END DESCRIPTION:
XS GIS Cut Line= 3
      2896549.99      7019950.00      2896125.00      7019775.00
      2895584.77      7019663.61
#Sta/Elev= 30
  4532.4  434.15  4580.3  430.44  4615.0  429.80  4669.3  426.69  4684.5  426.16
  4745.6  425.01  4870.7  424.58  4876.1  424.34  4883.9  422.08  4894.7  421.84
  4924.0  424.57  4982.7  425.19  4989.3  422.80  4994.6  422.80  4999.0  419.91
  4999.5  419.11  5004.9  419.11  5005.4  419.91  5012.0  424.44  5017.1  423.96
  5022.1  426.69  5032.8  428.54  5059.9  429.77  5112.6  430.83  5186.0  427.98
  5237.1  428.07  5349.4  432.51  5414.3  432.05  5464.6  433.14  5543.6  437.37
#Mann=5,-1,0
  4532.4    0.05       0  4684.5    0.12       0  4999.0    0.07       0
  5005.4    0.12       0  5059.9    0.05       0
Bank Sta=4669.3,5022.1
Exp/Cntr=0.3,0.1

Type RM Length L Ch R = 1,17174,764,764,764
BEGIN DESCRIPTION:
BRUSHY CREEK 25.0
END DESCRIPTION:
XS GIS Cut Line= 3
      2896575.02      7019675.04      2896404.53      7019350.27
      2895824.95      7019174.99
#Sta/Elev= 30
  4633.2  432.60  4701.0  433.43  4733.4  432.37  4751.7  431.29  4773.8  430.97
  4790.2  432.16  4878.4  426.85  4964.7  424.72  4983.0  421.48  4985.4  416.55
  4985.9  415.75  4991.4  415.75  4991.9  416.55  4994.5  417.97  5000.0  417.97
  5002.8  417.18  5010.0  420.82  5020.4  422.46  5062.2  423.26  5106.9  422.62
  5135.7  423.51  5258.4  422.07  5292.0  422.22  5386.7  424.72  5402.4  425.10
  5459.2  427.65  5484.9  426.84  5490.5  427.90  5517.9  430.19  5605.5  434.84
#Mann=7,-1,0
  4633.2    0.05       0  4733.4    0.12       0  4985.4    0.07       0
  4991.9    0.12       0  5135.7    0.16       0  5258.4    0.12       0
  5402.4    0.16       0
Bank Sta=4964.7,5386.7
Exp/Cntr=0.3,0.1

Type RM Length L Ch R = 1,16410,929,929,929
BEGIN DESCRIPTION:
BRUSHY CREEK 24.0
END DESCRIPTION:
XS GIS Cut Line= 3
      2896650.01      7019250.01      2896325.00      7018775.00
      2895711.57      7018567.27
#Sta/Elev= 30
  4452.8  432.40  4575.4  429.27  4632.2  431.04  4748.7  427.80  4805.6  427.57
  4900.8  423.09  4943.1  420.34  4979.0  421.60  4985.0  419.08  4992.0  414.51
  4996.6  414.09  4997.1  413.29  5002.7  413.29  5003.2  414.09  5006.0  417.34
  5014.8  417.58  5020.9  419.62  5031.0  419.21  5038.8  421.25  5047.2  420.88
  5070.2  421.17  5081.1  420.12  5237.2  423.09  5337.3  425.84  5338.6  425.88
  5408.4  427.93  5544.9  434.52  5566.8  435.42  5604.5  439.45  5676.0  443.26
#Mann=7,-1,0
  4452.8    0.16       0  4996.6    0.07       0  5003.2    0.16       0
  5047.2    0.12       0  5337.3    0.05       0  5338.6    0.16       0
  5544.9    0.05       0
Bank Sta=4900.8,5237.2
Exp/Cntr=0.3,0.1

Type RM Length L Ch R = 1,15481,152,152,152
BEGIN DESCRIPTION:
BRUSHY CREEK 23.0
END DESCRIPTION:
XS GIS Cut Line= 3
      2896825.00      7019074.96      2896870.33      7018530.64
      2896425.01      7018325.01
#Sta/Elev= 30
  4453.8  431.89  4511.5  429.44  4516.5  429.79  4544.1  427.21  4584.2  424.92
  4631.9  422.99  4637.0  423.36  4685.9  420.48  4704.6  419.06  4734.7  418.70
  4965.5  419.22  4975.6  418.87  4985.6  416.50  4990.0  412.15  4990.5  411.35
  4996.1  411.35  4996.6  412.15  4997.3  412.59  5000.9  412.15  5006.5  418.76
  5018.8  420.48  5023.9  421.41  5115.7  427.13  5121.2  428.02  5315.7  432.00
  5369.4  430.69  5413.4  432.25  5453.4  432.10  5481.8  433.57  5490.5  433.22
#Mann=4,-1,0
  4453.8    0.12       0  4990.0    0.07       0  4996.6    0.12       0
  4997.3    0.16       0
Bank Sta=4685.9,5018.8
Exp/Cntr=0.3,0.1

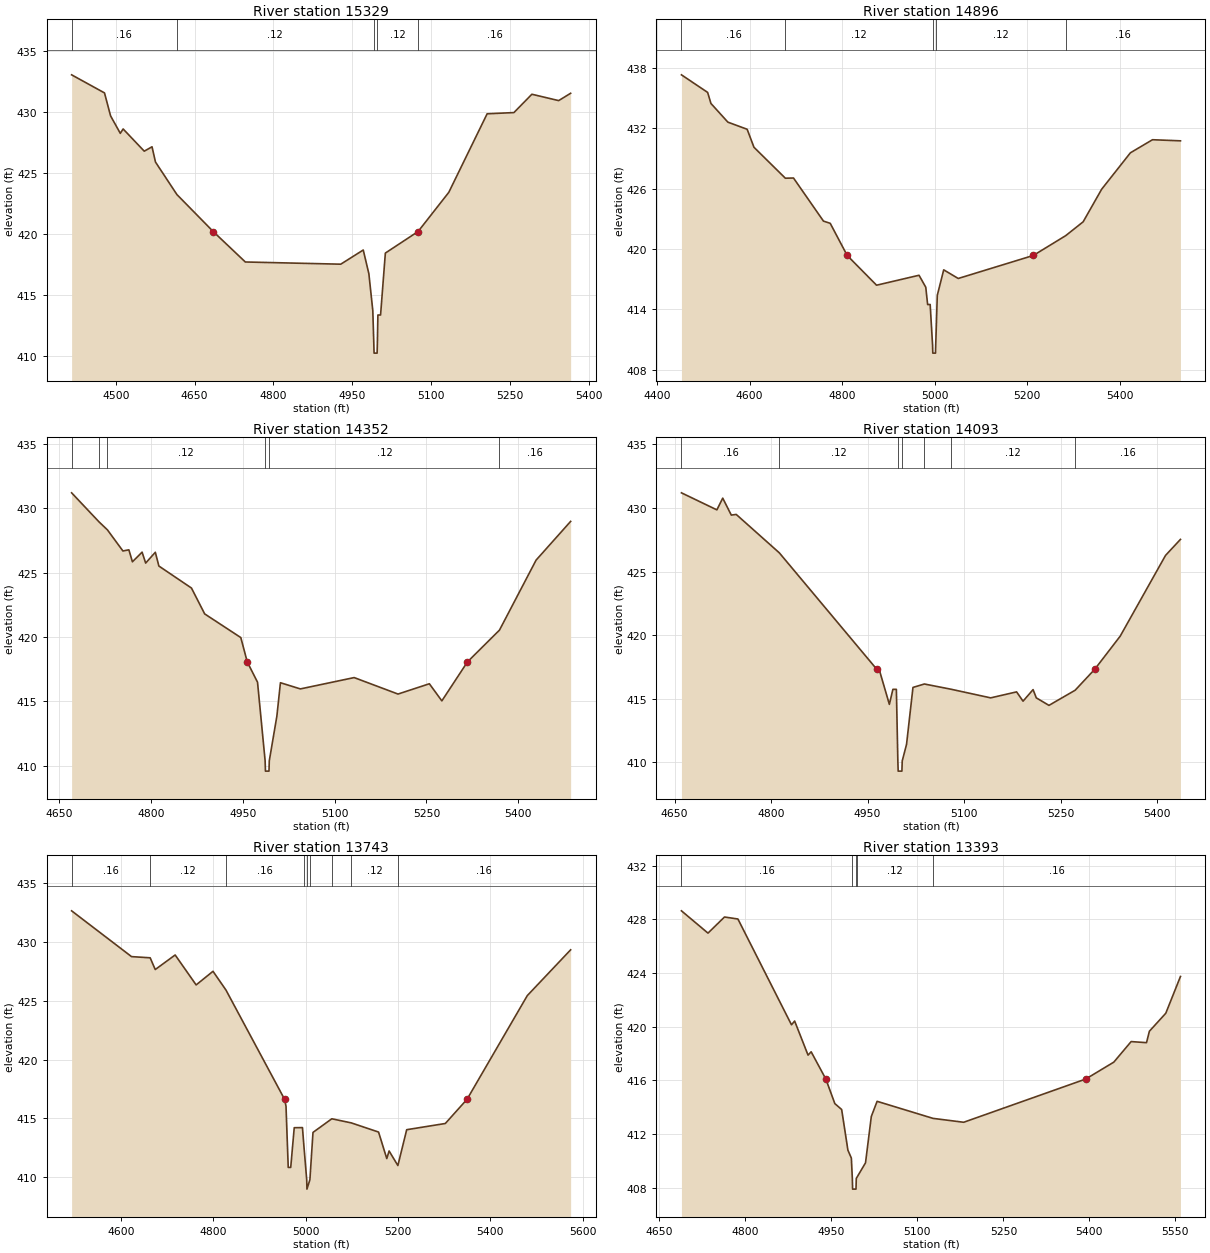
Type RM Length L Ch R = 1,15329,433,433,433
BEGIN DESCRIPTION:
BRUSHY CREEK 22.0
END DESCRIPTION:
XS GIS Cut Line= 3
      2897534.37      7018653.70      2896987.87      7018446.94
      2896629.06      7018375.25
#Sta/Elev= 30
  4415.7  433.02  4478.3  431.54  4489.9  429.66  4508.4  428.23  4513.8  428.59
  4554.0  426.77  4568.8  427.13  4575.4  425.88  4616.2  423.22  4685.4  420.19
  4746.5  417.70  4928.2  417.52  4971.0  418.68  4981.7  416.74  4989.2  413.72
  4991.1  411.04  4991.6  410.24  4997.4  410.24  4997.9  411.04  4998.9  413.36
  5004.0  413.36  5013.1  418.43  5075.3  420.19  5075.9  420.22  5133.9  423.40
  5206.9  429.83  5257.9  429.93  5292.1  431.43  5343.1  430.91  5365.9  431.51
#Mann=5,-1,0
  4415.7    0.16       0  4616.2    0.12       0  4991.1    0.07       0
  4997.9    0.12       0  5075.9    0.16       0
Bank Sta=4685.4,5075.3
Exp/Cntr=0.3,0.1

Type RM Length L Ch R = 1,14896,544,544,544
BEGIN DESCRIPTION:
Mapping XS 3889528f
END DESCRIPTION:
XS GIS Cut Line= 3
      2897706.31      7018573.01      2897276.58      7018255.27
      2896750.49      7018114.64
#Sta/Elev= 30
  4452.6  437.34  4509.2  435.59  4516.4  434.49  4553.0  432.63  4594.7  431.92
  4609.4  430.13  4677.3  427.05  4694.9  427.07  4759.7  422.78  4774.3  422.56
  4811.0  419.36  4874.5  416.40  4966.3  417.39  4980.9  416.20  4984.9  414.48
  4990.4  414.48  4995.6  410.44  4996.1  409.64  5001.9  409.64  5002.4  410.44
  5005.8  415.39  5019.7  417.93  5051.1  417.07  5213.4  419.36  5283.4  421.33
  5321.2  422.71  5361.3  425.96  5423.4  429.58  5471.1  430.88  5531.6  430.77
#Mann=5,-1,0
  4452.6    0.16       0  4677.3    0.12       0  4995.6    0.07       0
  5002.4    0.12       0  5283.4    0.16       0
Bank Sta=4811,5213.4
Exp/Cntr=0.3,0.1

Type RM Length L Ch R = 1,14352,259,259,259
BEGIN DESCRIPTION:
BRUSHY CREEK 21.0
END DESCRIPTION:
XS GIS Cut Line= 3
      2897748.46      7018277.74      2897575.00      7017975.00
      2897119.39      7017877.20
#Sta/Elev= 30
  4670.6  431.21  4715.4  428.95  4729.1  428.33  4754.4  426.69  4764.1  426.78
  4769.9  425.85  4785.7  426.60  4791.5  425.75  4807.3  426.59  4813.1  425.52
  4866.3  423.81  4887.9  421.80  4946.9  419.96  4957.4  418.07  4974.2  416.49
  4986.6  410.38  4987.1  409.58  4992.9  409.58  4993.4  410.38  5005.8  413.86
  5011.6  416.45  5044.2  415.97  5132.0  416.85  5203.6  415.57  5254.8  416.37
  5275.2  415.04  5317.0  418.07  5369.3  420.54  5429.1  425.98  5485.5  428.99
#Mann=6,-1,0
  4670.6     0.1       0  4715.4    0.16       0  4729.1    0.12       0
  4986.6    0.07       0  4993.4    0.12       0  5369.3    0.16       0
Bank Sta=4957.4,5317
Exp/Cntr=0.3,0.1

Type RM Length L Ch R = 1,14093,350,350,350
BEGIN DESCRIPTION:
Mapping XS 90202396
END DESCRIPTION:
XS GIS Cut Line= 3
      2897929.74      7018017.81      2897650.69      7017834.16
      2897211.90      7017784.08
#Sta/Elev= 30
  4660.7  431.19  4715.8  429.85  4724.9  430.77  4738.2  429.44  4745.9  429.49
  4812.9  426.47  4964.3  417.32  4968.8  417.18  4983.9  414.56  4989.4  415.74
  4994.8  415.74  4997.1  410.11  4997.6  409.31  5003.4  409.31  5003.9  410.11
  5010.6  411.41  5020.6  415.89  5038.3  416.16  5079.6  415.75  5141.4  415.07
  5181.7  415.54  5191.7  414.81  5207.3  415.72  5212.3  415.07  5232.0  414.48
  5272.7  415.67  5303.2  417.32  5342.7  419.92  5413.2  426.27  5436.4  427.53
#Mann=7,-1,0
  4660.7    0.16       0  4812.9    0.12       0  4997.1    0.07       0
  5003.9    0.12       0  5038.3    0.16       0  5079.6    0.12       0
  5272.7    0.16       0
Bank Sta=4964.3,5303.2
Exp/Cntr=0.3,0.1

Type RM Length L Ch R = 1,13743,350,350,350
BEGIN DESCRIPTION:
BRUSHY CREEK 20.0
END DESCRIPTION:
XS GIS Cut Line= 3
      2898025.01      7017925.01      2897775.00      7017525.00
      2897174.99      7017625.00
#Sta/Elev= 30
  4493.7  432.67  4623.4  428.77  4663.7  428.67  4674.7  427.67  4717.8  428.91
  4763.2  426.36  4799.7  427.52  4827.8  425.92  4954.6  416.62  4957.7  416.03
  4962.5  410.82  4967.9  410.82  4975.5  414.20  4993.3  414.21  4996.3  412.70
  5002.5  409.77  5003.0  408.97  5009.4  409.77  5016.1  413.80  5056.8  414.96
  5099.0  414.61  5158.0  413.83  5175.8  411.57  5180.8  412.22  5199.8  410.98
  5218.9  414.03  5302.5  414.56  5349.5  416.62  5479.9  425.45  5573.7  429.35
#Mann=9,-1,0
  4493.7    0.16       0  4663.7    0.12       0  4827.8    0.16       0
  4996.3    0.12       0  5002.5    0.07       0  5009.4    0.12       0
  5056.8    0.16       0  5099.0    0.12       0  5199.8    0.16       0
Bank Sta=4954.6,5349.5
Exp/Cntr=0.3,0.1

Type RM Length L Ch R = 1,13393,343,343,343
BEGIN DESCRIPTION:
Mapping XS e7284789
END DESCRIPTION:
XS GIS Cut Line= 3
      2898060.86      7017469.25      2897789.01      7017350.02
      2897219.55      7017283.31
#Sta/Elev= 30
  4688.6  428.63  4734.9  426.97  4763.7  428.17  4787.1  428.02  4880.5  420.14
  4886.0  420.42  4909.4  417.88  4914.8  418.13  4940.4  416.10  4956.1  414.27
  4968.0  413.83  4978.9  410.80  4984.9  410.21  4986.6  408.70  4987.1  407.90
  4993.0  407.90  4993.5  408.70  4995.5  408.84  5009.6  409.86  5019.7  413.31
  5029.8  414.44  5127.3  413.17  5180.8  412.88  5393.6  416.10  5442.6  417.36
  5472.8  418.89  5499.6  418.81  5504.6  419.66  5533.2  421.00  5558.8  423.74
#Mann=5,-1,0
  4688.6    0.16       0  4986.6    0.07       0  4993.5    0.16       0
  4995.5    0.12       0  5127.3    0.16       0
Bank Sta=4940.4,5393.6
Exp/Cntr=0.3,0.1