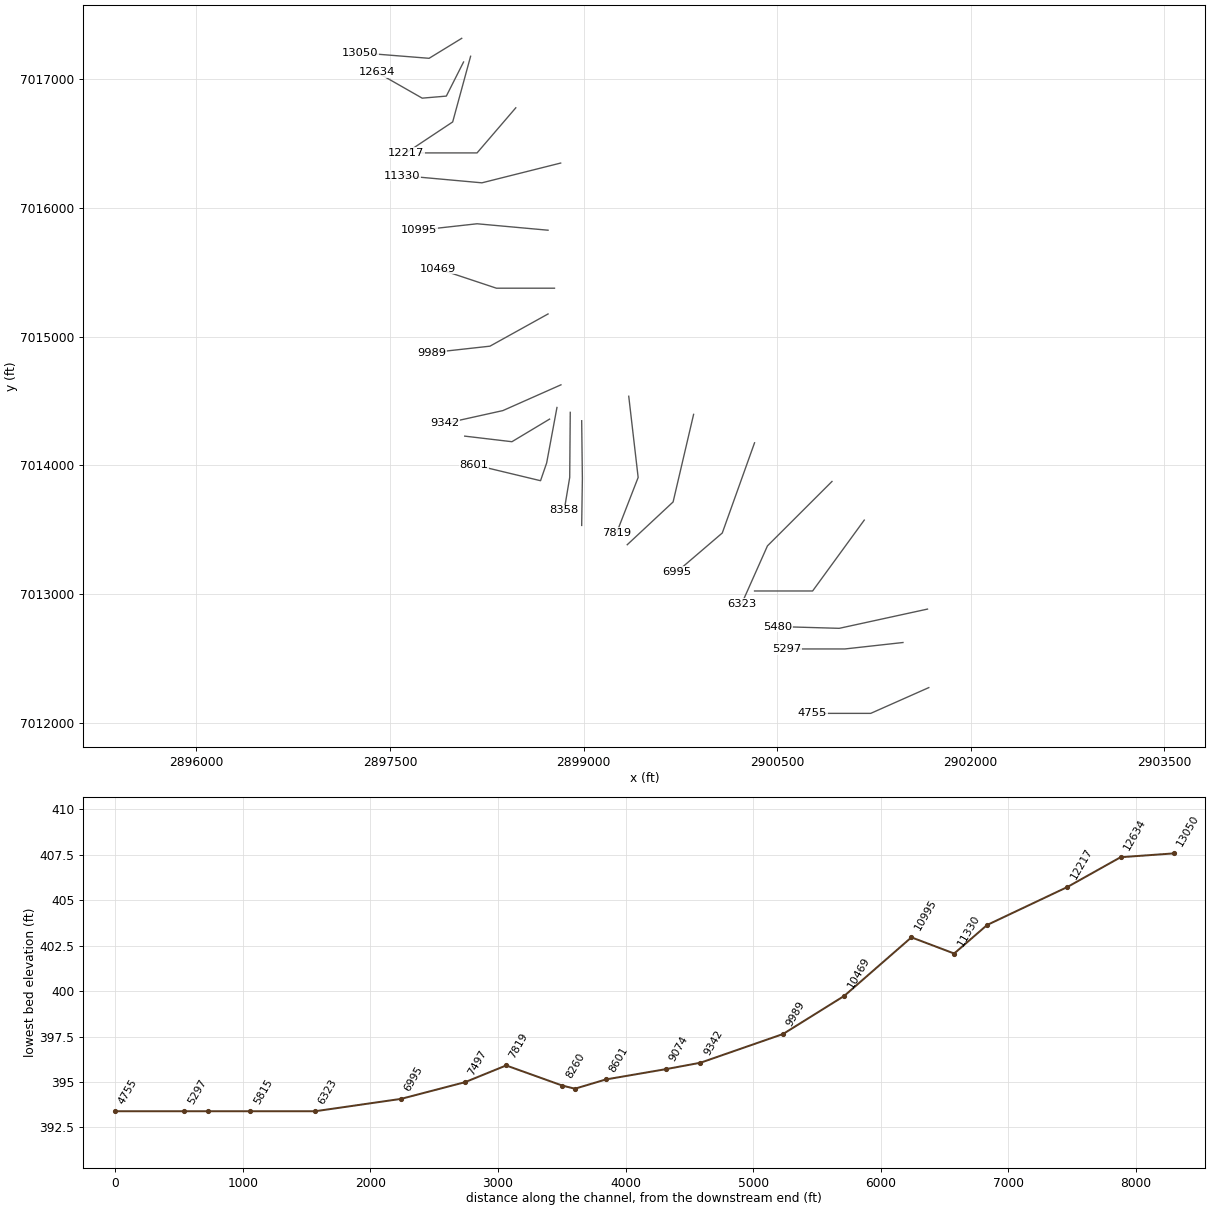
HEC-RAS study BRUSHY CREEK.prj: BRUSHY CREEK Base Level Engineering

--- BRUSHY CREEK.g01 (geometry) --- (continued)

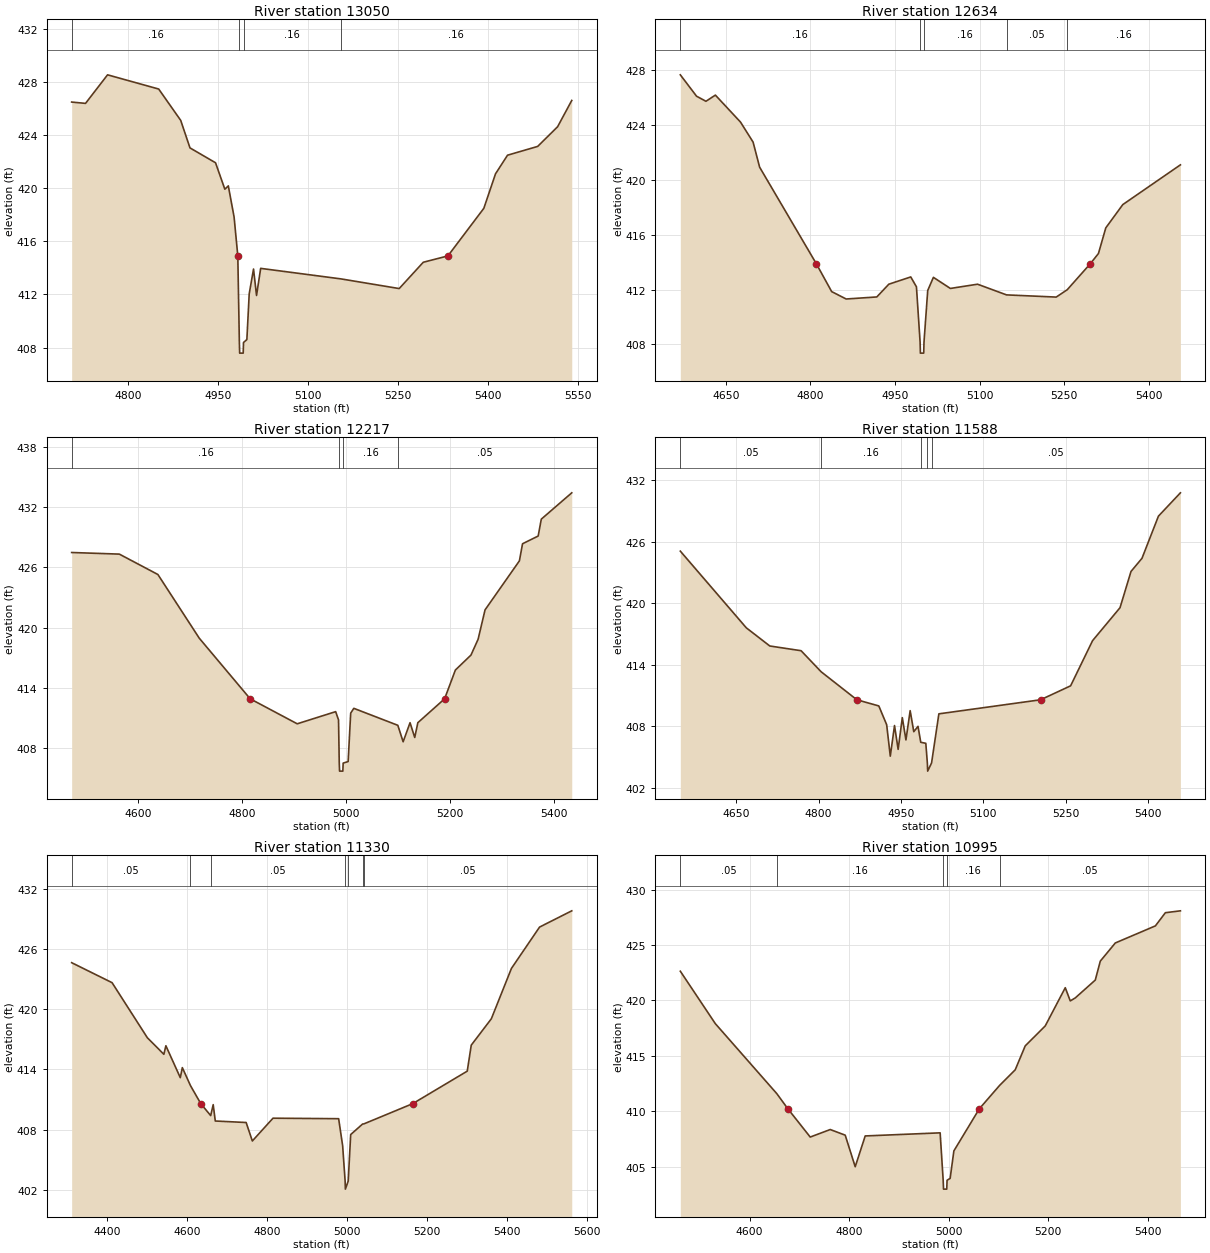
Type RM Length L Ch R = 1,13050,416,416,416
BEGIN DESCRIPTION:
Mapping XS 76652df8
END DESCRIPTION:
XS GIS Cut Line= 3
      2898056.12      7017314.25      2897803.32      7017159.23
      2897268.37      7017202.03
#Sta/Elev= 30
  4706.4  426.48  4729.5  426.38  4766.2  428.53  4851.4  427.46  4888.1  425.10
  4903.5  423.03  4946.1  421.91  4961.6  419.92  4967.4  420.17  4977.0  417.83
  4983.2  414.90  4985.8  408.38  4986.3  407.58  4992.2  407.58  4992.7  408.38
  4998.3  408.60  5002.2  412.04  5009.4  413.91  5014.4  411.92  5021.3  413.96
  5154.8  413.17  5252.1  412.44  5292.2  414.42  5333.3  414.90  5393.1  418.48
  5412.6  421.08  5432.6  422.48  5482.8  423.14  5516.0  424.62  5539.6  426.60
#Mann=4,-1,0
  4706.4    0.16       0  4985.8    0.07       0  4992.7    0.16       0
  5154.8    0.16       0
Bank Sta=4983.2,5333.3
Exp/Cntr=0.3,0.1

Type RM Length L Ch R = 1,12634,417,417,417
BEGIN DESCRIPTION:
BRUSHY CREEK 19.0
END DESCRIPTION:
XS GIS Cut Line= 4
      2898070.45      7017130.65      2897936.88      7016865.89
      2897750.00      7016850.00      2897400.01      7017049.99
#Sta/Elev= 30
  4569.1  427.68  4597.9  426.12  4614.6  425.75  4631.3  426.20  4675.9  424.23
  4698.2  422.77  4709.8  420.94  4810.3  413.90  4837.6  411.86  4863.3  411.32
  4917.7  411.47  4939.0  412.40  4977.9  412.93  4988.0  412.21  4994.5  408.17
  4995.0  407.37  5000.9  407.37  5001.4  408.17  5008.0  411.94  5018.1  412.90
  5048.2  412.09  5096.4  412.40  5147.8  411.62  5236.0  411.46  5255.6  412.00
  5296.6  413.90  5310.9  414.64  5323.9  416.51  5354.1  418.21  5456.3  421.11
#Mann=5,-1,0
  4569.1    0.16       0  4994.5    0.07       0  5001.4    0.16       0
  5147.8    0.05       0  5255.6    0.16       0
Bank Sta=4810.3,5296.6
Exp/Cntr=0.3,0.1

Type RM Length L Ch R = 1,12217,629,629,629
BEGIN DESCRIPTION:
BRUSHY CREEK 18.0
END DESCRIPTION:
XS GIS Cut Line= 3
      2898125.01      7017175.05      2897986.17      7016665.42
      2897624.98      7016424.99
#Sta/Elev= 30
  4471.8  427.49  4563.5  427.33  4637.7  425.30  4717.3  418.96  4815.2  412.93
  4905.7  410.44  4979.7  411.65  4985.2  410.83  4986.6  406.53  4987.2  405.73
  4993.5  405.73  4994.1  406.53  5003.7  406.68  5008.6  411.50  5014.6  411.98
  5099.3  410.29  5109.5  408.65  5122.8  410.55  5131.8  409.08  5137.8  410.55
  5189.3  412.93  5210.0  415.79  5240.0  417.28  5253.7  418.85  5267.1  421.78
  5333.2  426.66  5339.2  428.36  5369.3  429.13  5375.3  430.81  5433.9  433.43
#Mann=4,-1,0
  4471.8    0.16       0  4986.6    0.07       0  4994.1    0.16       0
  5099.3    0.05       0
Bank Sta=4815.2,5189.3
Exp/Cntr=0.3,0.1

Type RM Length L Ch R = 1,11588,258,258,258
BEGIN DESCRIPTION:
BRUSHY CREEK 17.0
END DESCRIPTION:
XS GIS Cut Line= 3
      2898474.99      7016774.99      2898175.00      7016425.00
      2897724.96      7016425.00
#Sta/Elev= 30
  4548.0  425.07  4668.2  417.60  4711.0  415.83  4768.0  415.37  4804.5  413.32
  4869.6  410.59  4909.6  409.99  4923.9  408.16  4930.5  405.10  4938.2  408.08
  4944.8  405.76  4952.4  408.85  4959.0  406.68  4966.7  409.53  4973.3  407.48
  4981.0  408.00  4986.0  406.45  4995.2  406.35  4998.0  404.44  4998.6  403.64
  5005.7  404.44  5019.0  409.22  5204.3  410.59  5259.0  411.95  5299.0  416.35
  5349.0  419.56  5369.0  423.09  5389.0  424.37  5419.0  428.48  5459.0  430.75
#Mann=5,-1,0
  4548.0    0.05       0  4804.5    0.16       0  4986.0    0.05       0
  4998.0    0.03       0  5005.7    0.05       0
Bank Sta=4869.6,5204.3
Exp/Cntr=0.3,0.1

Type RM Length L Ch R = 1,11330,335,335,335
BEGIN DESCRIPTION:
Mapping XS 76e4505c
END DESCRIPTION:
XS GIS Cut Line= 3
      2898822.80      7016346.29      2898212.63      7016192.81
      2897594.96      7016248.96
#Sta/Elev= 30
  4311.6  424.64  4412.5  422.65  4500.7  417.16  4541.9  415.51  4547.0  416.36
  4583.0  413.18  4588.1  414.18  4608.4  412.39  4634.2  410.59  4658.9  409.40
  4665.2  410.49  4670.4  408.86  4747.5  408.71  4763.0  406.87  4814.6  409.14
  4978.6  409.09  4988.6  406.40  4994.8  402.87  4995.4  402.07  5002.5  402.87
  5008.7  407.51  5038.5  408.56  5041.5  408.57  5163.7  410.59  5299.9  413.83
  5309.9  416.42  5360.1  419.05  5410.3  424.07  5480.6  428.19  5561.0  429.81
#Mann=7,-1,0
  4311.6    0.05       0  4608.4    0.16       0  4658.9    0.05       0
  4994.8    0.03       0  5002.5    0.05       0  5038.5    0.16       0
  5041.5    0.05       0
Bank Sta=4634.2,5163.7
Exp/Cntr=0.3,0.1

Type RM Length L Ch R = 1,10995,526,526,526
BEGIN DESCRIPTION:
BRUSHY CREEK 16.0
END DESCRIPTION:
XS GIS Cut Line= 3
      2898725.04      7015825.00      2898175.00      7015875.00
      2897724.98      7015825.00
#Sta/Elev= 30
  4460.8  422.63  4531.1  417.90  4654.7  411.58  4676.8  410.22  4721.9  407.66
  4762.1  408.34  4792.2  407.83  4812.3  404.98  4832.4  407.76  4983.0  408.04
  4989.1  403.76  4989.8  402.96  4996.3  402.96  4996.9  403.76  5003.1  403.93
  5010.6  406.41  5061.9  410.22  5102.5  412.32  5133.9  413.73  5154.0  415.89
  5194.2  417.69  5234.5  421.14  5244.5  419.95  5254.6  420.22  5294.8  421.83
  5304.9  423.54  5335.1  425.18  5415.6  426.72  5435.7  427.91  5465.9  428.08
#Mann=5,-1,0
  4460.8    0.05       0  4654.7    0.16       0  4989.1    0.07       0
  4996.9    0.16       0  5102.5    0.05       0
Bank Sta=4676.8,5061.9
Exp/Cntr=0.3,0.1

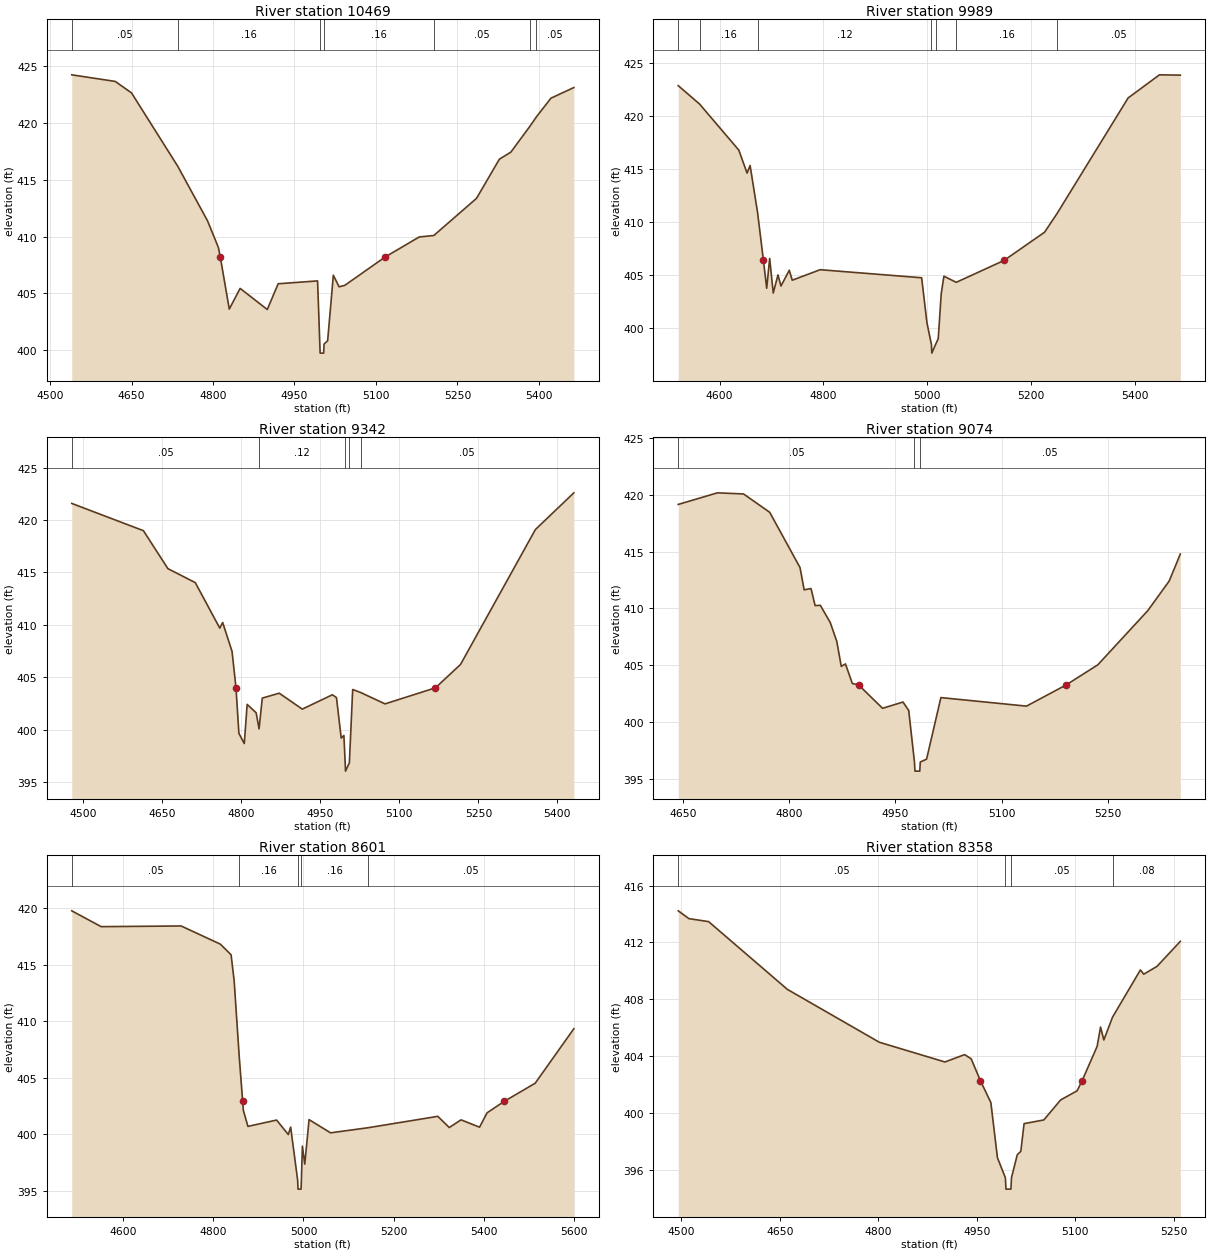
Type RM Length L Ch R = 1,10469,480,480,480
BEGIN DESCRIPTION:
BRUSHY CREEK 15.0
END DESCRIPTION:
XS GIS Cut Line= 3
      2898775.01      7015375.00      2898325.00      7015375.00
      2897874.96      7015525.01
#Sta/Elev= 30
  4540.0  424.25  4620.0  423.67  4650.0  422.66  4735.1  416.20  4790.0  411.39
  4810.0  409.04  4813.5  408.20  4830.0  403.62  4850.0  405.44  4900.0  403.58
  4920.0  405.85  4992.6  406.10  4996.7  400.54  4997.3  399.74  5003.8  399.74
  5004.5  400.54  5011.1  400.83  5021.6  406.60  5032.2  405.58  5042.7  405.71
  5116.8  408.20  5179.7  409.97  5206.6  410.10  5285.2  413.37  5327.3  416.82
  5348.4  417.44  5383.7  419.73  5395.5  420.55  5422.2  422.19  5464.4  423.13
#Mann=7,-1,0
  4540.0    0.05       0  4735.1    0.16       0  4996.7    0.07       0
  5004.5    0.16       0  5206.6    0.05       0  5383.7    0.16       0
  5395.5    0.05       0
Bank Sta=4813.5,5116.8
Exp/Cntr=0.3,0.1

Type RM Length L Ch R = 1,9989,647,647,647
BEGIN DESCRIPTION:
BRUSHY CREEK 14.0
END DESCRIPTION:
XS GIS Cut Line= 3
      2898725.04      7015175.02      2898275.00      7014925.00
      2897825.00      7014875.00
#Sta/Elev= 30
  4520.2  422.84  4561.3  421.11  4636.9  416.77  4652.9  414.60  4658.7  415.32
  4673.1  410.89  4684.4  406.37  4690.7  403.75  4696.4  406.57  4703.3  403.30
  4712.4  405.01  4718.2  403.96  4734.2  405.45  4739.9  404.51  4793.7  405.50
  4989.3  404.74  4999.6  400.48  5008.2  398.44  5008.9  397.64  5016.0  398.44
  5021.3  399.00  5027.0  403.22  5032.2  404.89  5056.0  404.31  5148.0  406.37
  5226.2  409.03  5250.9  410.84  5387.2  421.68  5447.6  423.86  5487.8  423.83
#Mann=7,-1,0
  4520.2    0.05       0  4561.3    0.16       0  4673.1    0.12       0
  5008.2    0.07       0  5016.0    0.12       0  5056.0    0.16       0
  5250.9    0.05       0
Bank Sta=4684.4,5148
Exp/Cntr=0.3,0.1

Type RM Length L Ch R = 1,9342,268,268,268
BEGIN DESCRIPTION:
BRUSHY CREEK 13.0
END DESCRIPTION:
XS GIS Cut Line= 3
      2898825.03      7014625.01      2898375.00      7014425.00
      2897924.96      7014324.99
#Sta/Elev= 30
  4477.8  421.58  4613.9  418.98  4660.4  415.36  4712.4  414.03  4758.9  409.69
  4764.4  410.23  4782.2  407.47  4789.7  404.00  4795.2  399.66  4805.4  398.69
  4810.9  402.42  4828.0  401.62  4833.5  400.09  4839.6  403.02  4871.8  403.49
  4915.6  401.97  4972.8  403.34  4980.5  403.07  4989.5  399.21  4994.6  399.46
  4997.0  396.86  4997.7  396.06  5005.0  396.86  5011.3  403.84  5026.2  403.56
  5072.7  402.47  5168.5  404.00  5216.1  406.23  5358.3  419.09  5431.3  422.59
#Mann=5,-1,0
  4477.8    0.05       0  4833.5    0.12       0  4997.0    0.07       0
  5005.0    0.12       0  5026.2    0.05       0
Bank Sta=4789.7,5168.5
Exp/Cntr=0.3,0.1

Type RM Length L Ch R = 1,9074,473,473,473
BEGIN DESCRIPTION:
Mapping XS 26423505
END DESCRIPTION:
XS GIS Cut Line= 3
      2898736.82      7014358.84      2898445.15      7014183.49
      2898079.42      7014226.82
#Sta/Elev= 30
  4643.7  419.14  4699.0  420.16  4735.9  420.06  4772.8  418.45  4815.6  413.59
  4821.4  411.64  4831.1  411.75  4836.9  410.25  4844.2  410.28  4858.3  408.76
  4867.5  407.10  4873.8  404.91  4879.7  405.13  4889.4  403.41  4898.3  403.28
  4932.1  401.23  4960.9  401.78  4969.0  401.04  4977.1  396.51  4977.8  395.71
  4984.6  395.71  4985.3  396.51  4994.2  396.76  5014.4  402.17  5135.2  401.42
  5191.1  403.28  5235.9  405.05  5306.4  409.81  5336.6  412.41  5352.3  414.78
#Mann=3,-1,0
  4643.7    0.05       0  4977.1    0.03       0  4985.3    0.05       0
Bank Sta=4898.3,5191.1
Exp/Cntr=0.3,0.1

Type RM Length L Ch R = 1,8601,243,243,243
BEGIN DESCRIPTION:
BRUSHY CREEK 12.0
END DESCRIPTION:
XS GIS Cut Line= 4
      2898794.10      7014449.08      2898714.24      7014018.56
      2898666.87      7013880.80      2898151.70      7014004.69
#Sta/Elev= 30
  4486.2  419.76  4551.4  418.36  4728.7  418.42  4815.8  416.81  4839.5  415.87
  4846.3  413.58  4857.6  406.85  4865.2  402.91  4866.7  402.11  4876.8  400.69
  4940.4  401.25  4966.4  399.97  4971.6  400.63  4987.1  395.94  4987.9  395.14
  4994.7  395.14  4995.4  395.94  4997.6  398.94  5002.9  397.35  5012.4  401.29
  5060.1  400.12  5143.1  400.57  5297.9  401.58  5323.3  400.59  5349.4  401.27
  5390.5  400.62  5407.2  401.89  5445.5  402.91  5513.9  404.51  5599.6  409.33
#Mann=5,-1,0
  4486.2    0.05       0  4857.6    0.16       0  4987.1    0.07       0
  4995.4    0.16       0  5143.1    0.05       0
Bank Sta=4865.2,5445.5
Exp/Cntr=0.3,0.1

Type RM Length L Ch R = 1,8358,98,98,98
BEGIN DESCRIPTION:
BRUSHY CREEK 11.0
END DESCRIPTION:
XS GIS Cut Line= 3
      2898897.11      7014411.31      2898892.88      7013906.63
      2898850.00      7013649.99
#Sta/Elev= 30
  4495.3  414.22  4511.6  413.67  4541.6  413.46  4661.6  408.69  4801.6  404.97
  4901.6  403.58  4931.6  404.10  4941.6  403.80  4955.7  402.26  4971.6  400.72
  4981.6  396.84  4993.7  395.43  4994.6  394.63  5002.1  394.63  5003.0  395.43
  5011.8  397.05  5017.2  397.29  5022.2  399.24  5052.3  399.50  5077.9  400.91
  5103.0  401.55  5110.6  402.26  5133.5  404.68  5138.7  406.04  5143.7  405.13
  5157.0  406.74  5199.4  410.06  5204.5  409.76  5224.7  410.31  5260.2  412.07
#Mann=4,-1,0
  4495.3    0.05       0  4993.7    0.03       0  5003.0    0.05       0
  5157.0    0.08       0
Bank Sta=4955.7,5110.6
Exp/Cntr=0.3,0.1

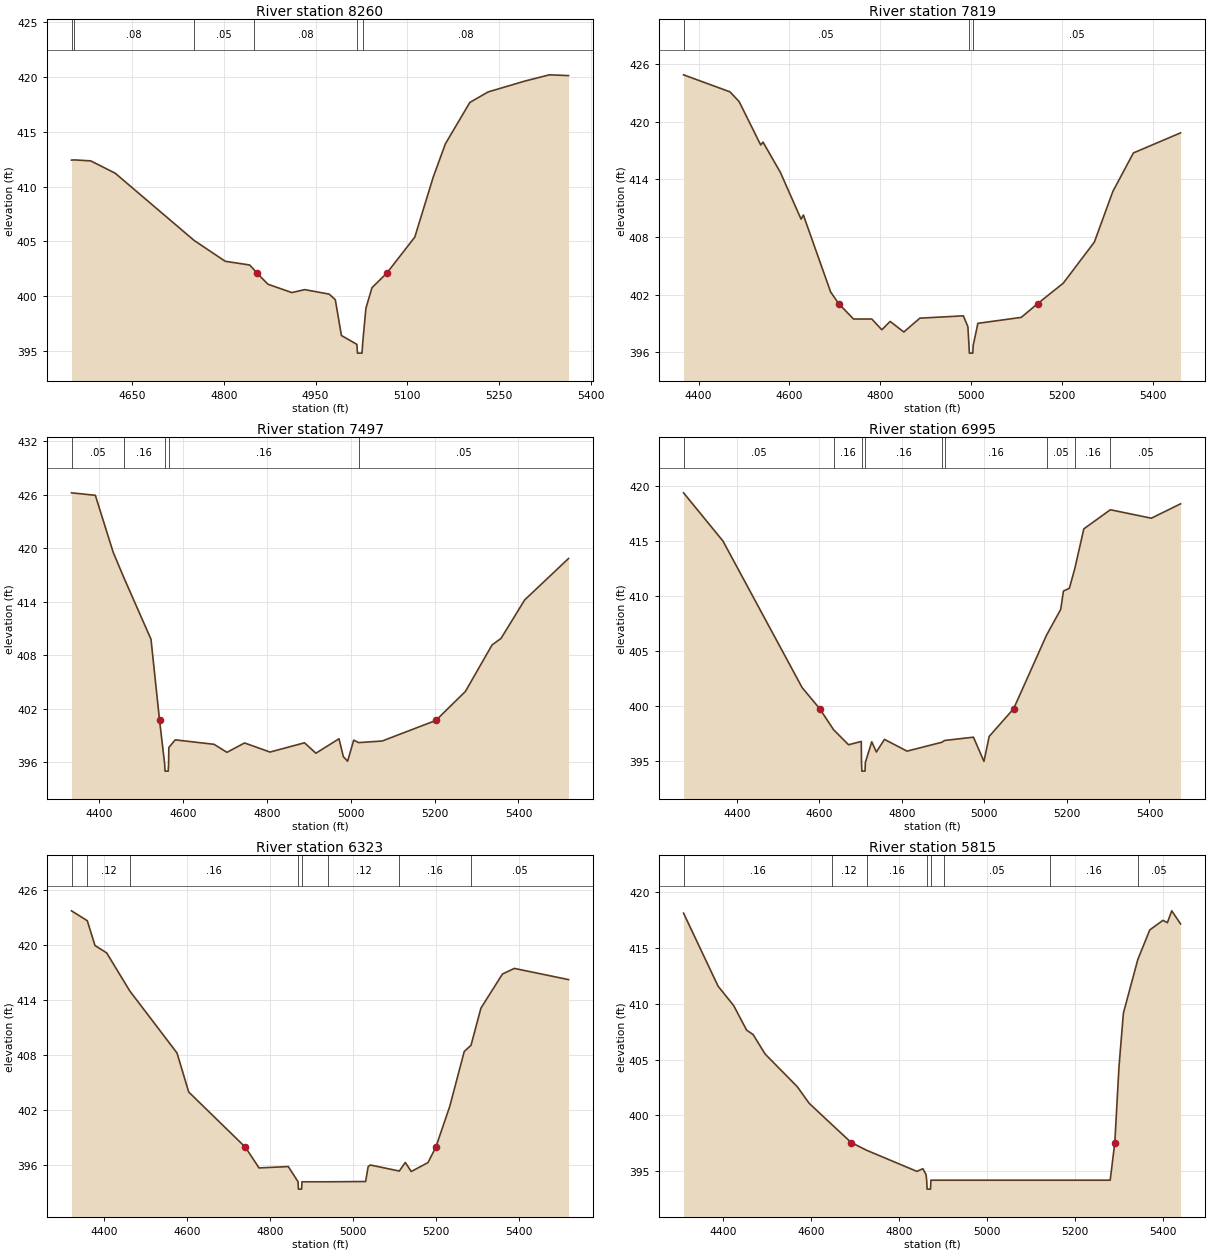
Type RM Length L Ch R = 1,8260,441,441,441
BEGIN DESCRIPTION:
BRUSHY CREEK 10.0
END DESCRIPTION:
XS GIS Cut Line= 3
      2898985.65      7014346.25      2898991.01      7013897.28
      2898985.65      7013533.72
#Sta/Elev= 30
  4551.0  412.43  4555.6  412.45  4582.3  412.36  4622.3  411.24  4751.3  405.10
  4802.3  403.19  4842.3  402.85  4849.1  402.44  4854.2  402.10  4872.3  401.09
  4911.3  400.33  4932.3  400.60  4972.3  400.19  4982.3  399.68  4992.3  396.41
  5017.6  395.60  5018.5  394.80  5026.0  394.80  5026.9  395.60  5032.3  398.89
  5042.3  400.78  5066.4  402.10  5112.3  405.40  5142.3  410.86  5162.3  413.92
  5202.3  417.70  5232.3  418.66  5292.3  419.65  5332.3  420.22  5363.6  420.15
#Mann=6,-1,0
  4551.0    0.05       0  4555.6    0.08       0  4751.3    0.05       0
  4849.1    0.08       0  5017.6    0.07       0  5026.9    0.08       0
Bank Sta=4854.2,5066.4
Exp/Cntr=0.3,0.1

Type RM Length L Ch R = 1,7819,322,322,322
BEGIN DESCRIPTION:
Mapping XS 09399f53
END DESCRIPTION:
XS GIS Cut Line= 3
      2899350.23      7014536.38      2899423.15      7013906.14
      2899257.18      7013478.25
#Sta/Elev= 30
  4367.0  424.87  4469.1  423.10  4489.2  422.09  4536.7  417.57  4541.8  417.87
  4579.8  414.74  4625.5  409.85  4630.6  410.28  4690.5  402.28  4708.3  401.06
  4740.9  399.46  4781.1  399.46  4803.2  398.34  4821.4  399.21  4851.6  398.11
  4886.9  399.55  4982.5  399.79  4992.5  398.67  4994.9  396.71  4995.8  395.91
  5003.3  395.91  5004.2  396.71  5014.5  399.01  5109.9  399.63  5146.0  401.06
  5202.4  403.19  5270.8  407.47  5311.4  412.73  5356.6  416.74  5460.4  418.83
#Mann=3,-1,0
  4367.0    0.05       0  4994.9    0.03       0  5004.2    0.05       0
Bank Sta=4708.3,5146
Exp/Cntr=0.3,0.1

Type RM Length L Ch R = 1,7497,502,502,502
BEGIN DESCRIPTION:
Mapping XS 3d340b77
END DESCRIPTION:
XS GIS Cut Line= 3
      2899852.83      7014395.68      2899693.99      7013716.03
      2899338.62      7013384.01
#Sta/Elev= 30
  4334.9  426.22  4391.7  425.94  4434.2  419.55  4459.3  416.74  4524.3  409.79
  4544.7  400.68  4556.9  395.79  4557.7  394.99  4565.3  394.99  4566.2  395.79
  4566.8  397.64  4582.1  398.50  4674.5  398.00  4705.3  397.10  4747.2  398.15
  4808.0  397.13  4890.1  398.17  4917.2  397.00  4972.3  398.62  4982.6  396.62
  4992.8  396.10  5007.3  398.47  5019.1  398.19  5075.2  398.37  5203.1  400.68
  5273.5  403.93  5337.0  409.15  5358.5  409.89  5414.7  414.20  5519.2  418.85
#Mann=5,-1,0
  4334.9    0.05       0  4459.3    0.16       0  4556.9    0.07       0
  4566.2    0.16       0  5019.1    0.05       0
Bank Sta=4544.7,5203.1
Exp/Cntr=0.3,0.1

Type RM Length L Ch R = 1,6995,672,672,672
BEGIN DESCRIPTION:
BRUSHY CREEK 9.0
END DESCRIPTION:
XS GIS Cut Line= 3
      2900324.99      7014174.97      2900075.00      7013475.00
      2899724.96      7013174.97
#Sta/Elev= 30
  4271.0  419.40  4366.5  415.01  4558.2  401.68  4600.9  399.75  4634.5  397.84
  4670.8  396.47  4701.6  396.77  4702.2  394.87  4703.1  394.07  4710.7  394.07
  4711.6  394.87  4727.0  396.74  4738.2  395.81  4757.8  396.96  4812.5  395.89
  4897.2  396.70  4903.5  396.86  4973.4  397.16  4998.9  394.96  5011.6  397.23
  5070.8  399.75  5150.7  406.46  5184.9  408.79  5191.5  410.46  5205.8  410.71
  5218.8  412.47  5240.9  416.12  5305.2  417.86  5404.5  417.09  5475.3  418.40
#Mann=9,-1,0
  4271.0    0.05       0  4634.5    0.16       0  4702.2    0.07       0
  4711.6    0.16       0  4897.2    0.12       0  4903.5    0.16       0
  5150.7    0.05       0  5218.8    0.16       0  5305.2    0.05       0
Bank Sta=4600.9,5070.8
Exp/Cntr=0.3,0.1

Type RM Length L Ch R = 1,6323,508,508,508
BEGIN DESCRIPTION:
BRUSHY CREEK 8.0
END DESCRIPTION:
XS GIS Cut Line= 3
      2900925.02      7013875.02      2900425.00      7013375.00
      2900224.99      7012924.98
#Sta/Elev= 30
  4320.6  423.74  4358.7  422.66  4377.2  419.96  4405.5  419.15  4461.3  415.00
  4575.2  408.24  4603.5  403.98  4740.3  397.96  4773.2  395.70  4843.9  395.85
  4867.4  394.19  4868.3  393.39  4876.0  393.39  4876.9  394.19  4939.4  394.19
  5030.5  394.22  5036.6  395.85  5042.1  396.02  5111.8  395.36  5126.2  396.30
  5140.6  395.31  5180.9  396.28  5199.9  397.96  5233.6  402.42  5268.5  408.40
  5284.9  409.08  5308.8  413.13  5360.8  416.85  5389.5  417.46  5520.2  416.24
#Mann=8,-1,0
  4320.6    0.16       0  4358.7    0.12       0  4461.3    0.16       0
  4867.4    0.07       0  4876.9    0.16       0  4939.4    0.12       0
  5111.8    0.16       0  5284.9    0.05       0
Bank Sta=4740.3,5199.9
Exp/Cntr=0.3,0.1

Type RM Length L Ch R = 1,5815,335,335,335
BEGIN DESCRIPTION:
BRUSHY CREEK 7.0
END DESCRIPTION:
XS GIS Cut Line= 3
      2901175.02      7013575.02      2900775.00      7013025.00
      2900325.00      7013025.00
#Sta/Elev= 30
  4310.1  418.11  4388.6  411.57  4424.1  409.83  4453.5  407.63  4468.2  407.24
  4495.6  405.49  4568.6  402.57  4595.7  401.08  4646.9  399.19  4691.5  397.56
  4726.4  396.87  4840.7  394.98  4854.2  395.22  4861.5  394.70  4862.9  394.19
  4863.8  393.39  4871.6  393.39  4872.5  394.19  4901.6  394.19  5142.6  394.19
  5280.2  394.19  5290.7  397.56  5300.2  404.36  5310.2  409.15  5343.0  413.96
  5370.2  416.61  5400.2  417.47  5410.2  417.26  5420.2  418.32  5440.2  417.15
#Mann=8,-1,0
  4310.1    0.16       0  4646.9    0.12       0  4726.4    0.16       0
  4862.9   0.033       0  4872.5    0.16       0  4901.6    0.05       0
  5142.6    0.16       0  5343.0    0.05       0
Bank Sta=4691.5,5290.7
Exp/Cntr=0.3,0.1

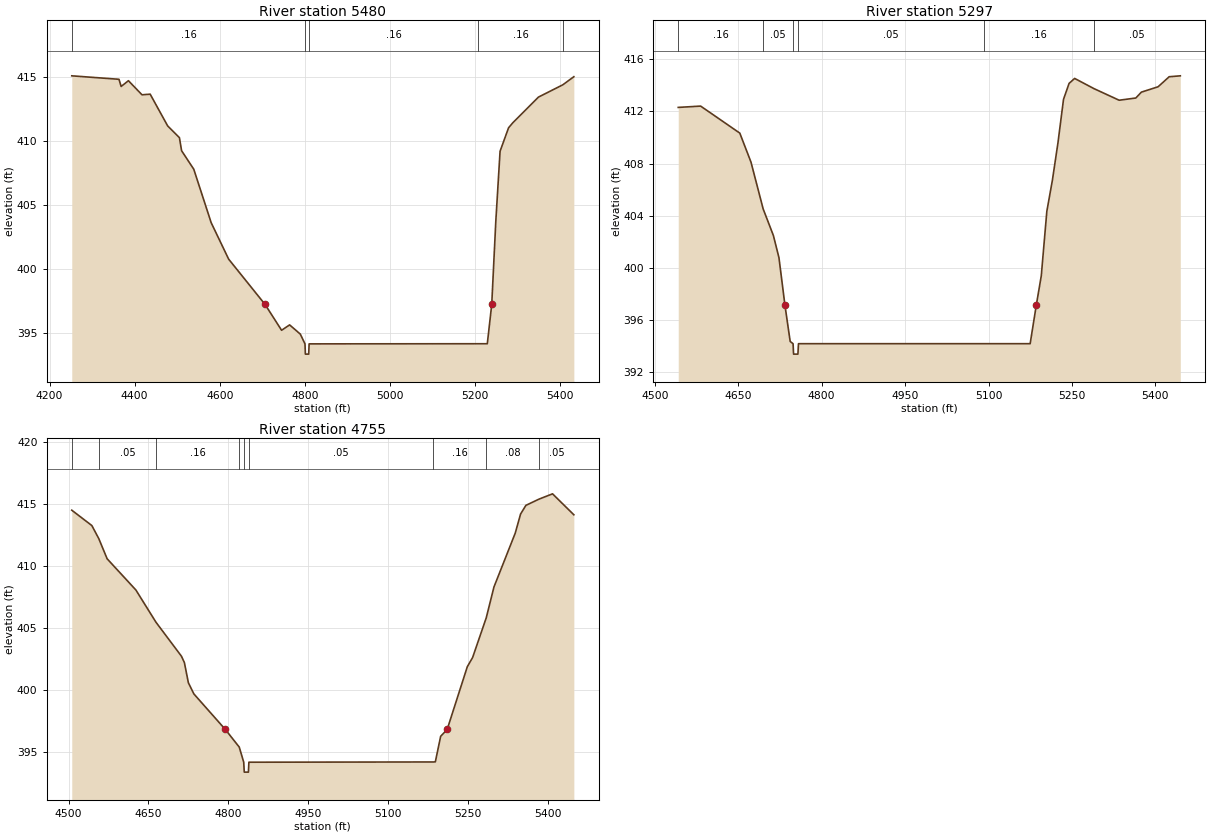
Type RM Length L Ch R = 1,5480,183,183,183
BEGIN DESCRIPTION:
Mapping XS ce6274a0
END DESCRIPTION:
XS GIS Cut Line= 3
      2901665.00      7012884.38      2900980.97      7012735.07
      2900501.81      7012748.96
#Sta/Elev= 30
  4252.2  415.09  4363.1  414.82  4368.2  414.26  4385.3  414.71  4417.2  413.61
  4436.4  413.66  4477.4  411.19  4505.1  410.27  4510.2  409.25  4538.8  407.81
  4579.7  403.64  4620.7  400.80  4706.4  397.26  4745.1  395.25  4764.0  395.67
  4789.1  394.95  4800.1  394.19  4801.0  393.39  4808.8  393.39  4809.8  394.19
  5207.5  394.20  5228.4  394.20  5238.8  397.26  5248.4  403.76  5258.4  409.21
  5278.4  411.04  5288.4  411.43  5348.5  413.43  5405.8  414.39  5431.7  415.02
#Mann=5,-1,0
  4252.2    0.16       0  4800.1   0.033       0  4809.8    0.16       0
  5207.5    0.16       0  5405.8    0.05       0
Bank Sta=4706.4,5238.8
Exp/Cntr=0.3,0.1

Type RM Length L Ch R = 1,5297,542,542,542
BEGIN DESCRIPTION:
BRUSHY CREEK 6.0
END DESCRIPTION:
XS GIS Cut Line= 3
      2901475.02      7012625.00      2901025.00      7012575.00
      2900574.99      7012575.00
#Sta/Elev= 30
  4542.1  412.30  4582.4  412.40  4652.8  410.33  4672.9  408.11  4694.8  404.52
  4713.2  402.48  4723.2  400.79  4734.0  397.13  4743.4  394.36  4748.6  394.19
  4749.5  393.39  4757.3  393.39  4758.3  394.19  5092.0  394.19  5174.9  394.19
  5185.9  397.13  5194.9  399.39  5204.9  404.34  5214.9  406.72  5224.9  409.59
  5234.9  412.92  5244.9  414.14  5254.9  414.52  5290.1  413.73  5334.9  412.85
  5364.9  413.02  5374.9  413.47  5404.9  413.88  5424.9  414.65  5444.9  414.72
#Mann=6,-1,0
  4542.1    0.16       0  4694.8    0.05       0  4748.6   0.033       0
  4758.3    0.05       0  5092.0    0.16       0  5290.1    0.05       0
Bank Sta=4734,5185.9
Exp/Cntr=0.3,0.1

Type RM Length L Ch R = 1,4755,357,357,357
BEGIN DESCRIPTION:
BRUSHY CREEK 5.0
END DESCRIPTION:
XS GIS Cut Line= 3
      2901675.04      7012275.02      2901225.00      7012075.00
      2900774.98      7012075.00
#Sta/Elev= 30
  4506.0  414.52  4543.7  413.28  4556.8  412.22  4572.4  410.60  4626.4  408.08
  4664.1  405.48  4711.9  402.74  4717.4  402.23  4724.9  400.60  4735.2  399.70
  4794.3  396.83  4820.4  395.41  4828.8  394.19  4829.8  393.39  4837.6  393.39
  4838.5  394.19  5185.0  394.21  5188.5  394.22  5198.5  396.28  5210.7  396.83
  5248.5  401.89  5258.5  402.64  5284.0  405.83  5298.5  408.32  5338.5  412.67
  5348.5  414.21  5358.5  414.91  5383.0  415.41  5408.5  415.84  5448.5  414.15
#Mann=9,-1,0
  4506.0    0.16       0  4556.8    0.05       0  4664.1    0.16       0
  4820.4    0.05       0  4828.8   0.033       0  4838.5    0.05       0
  5185.0    0.16       0  5284.0    0.08       0  5383.0    0.05       0
Bank Sta=4794.3,5210.7
Exp/Cntr=0.3,0.1