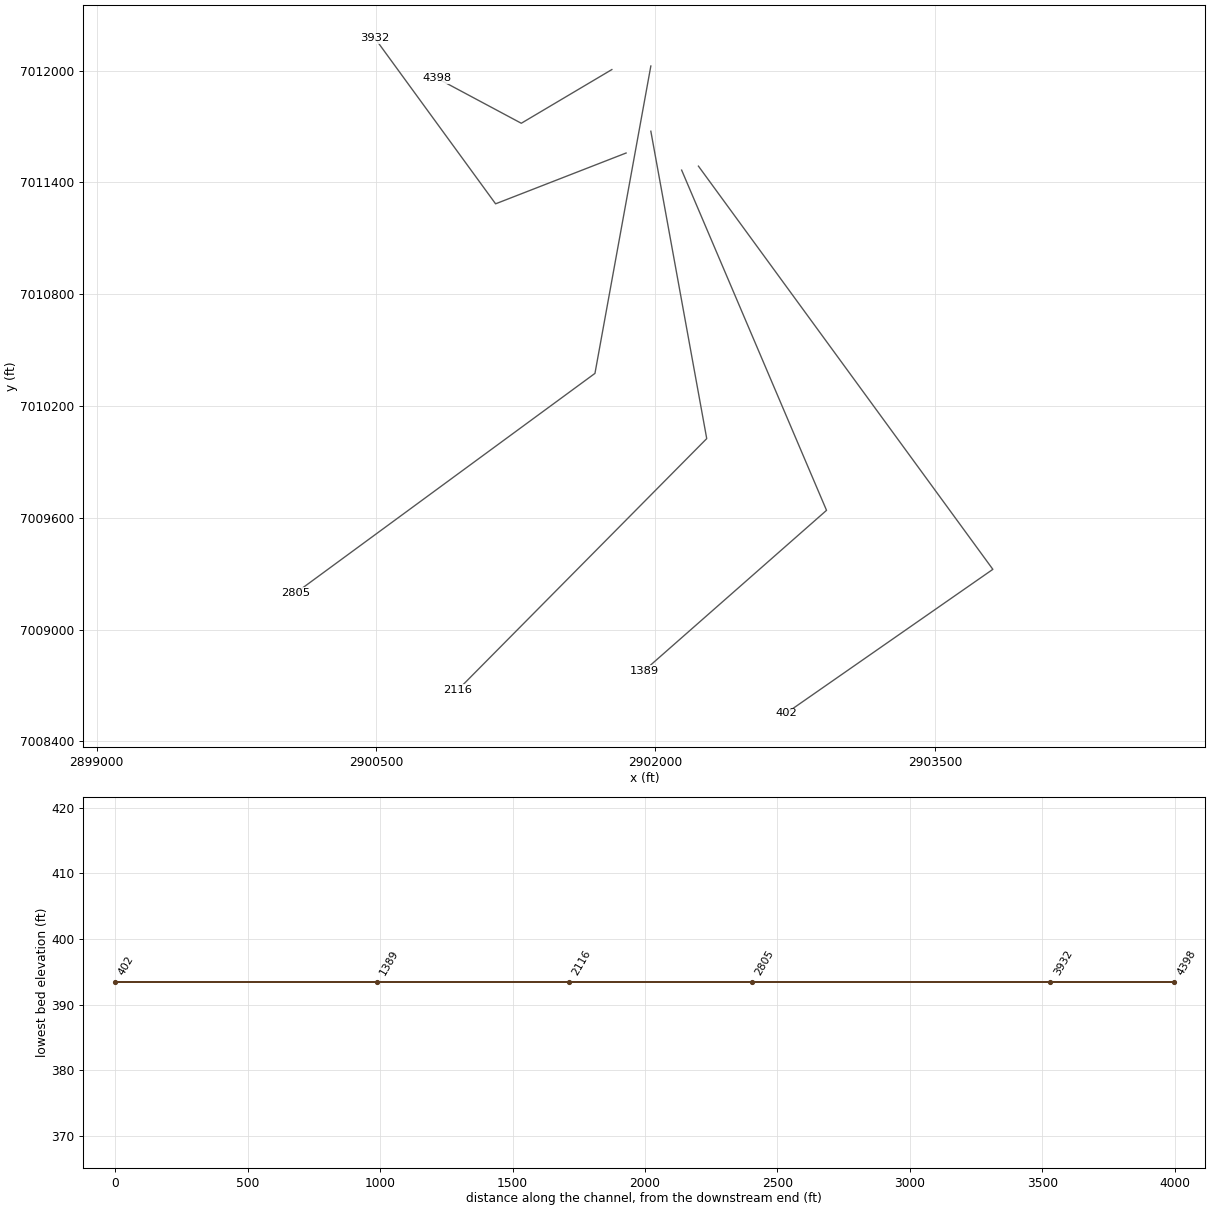
HEC-RAS study BRUSHY CREEK.prj: BRUSHY CREEK Base Level Engineering

--- BRUSHY CREEK.g01 (geometry) --- (continued)

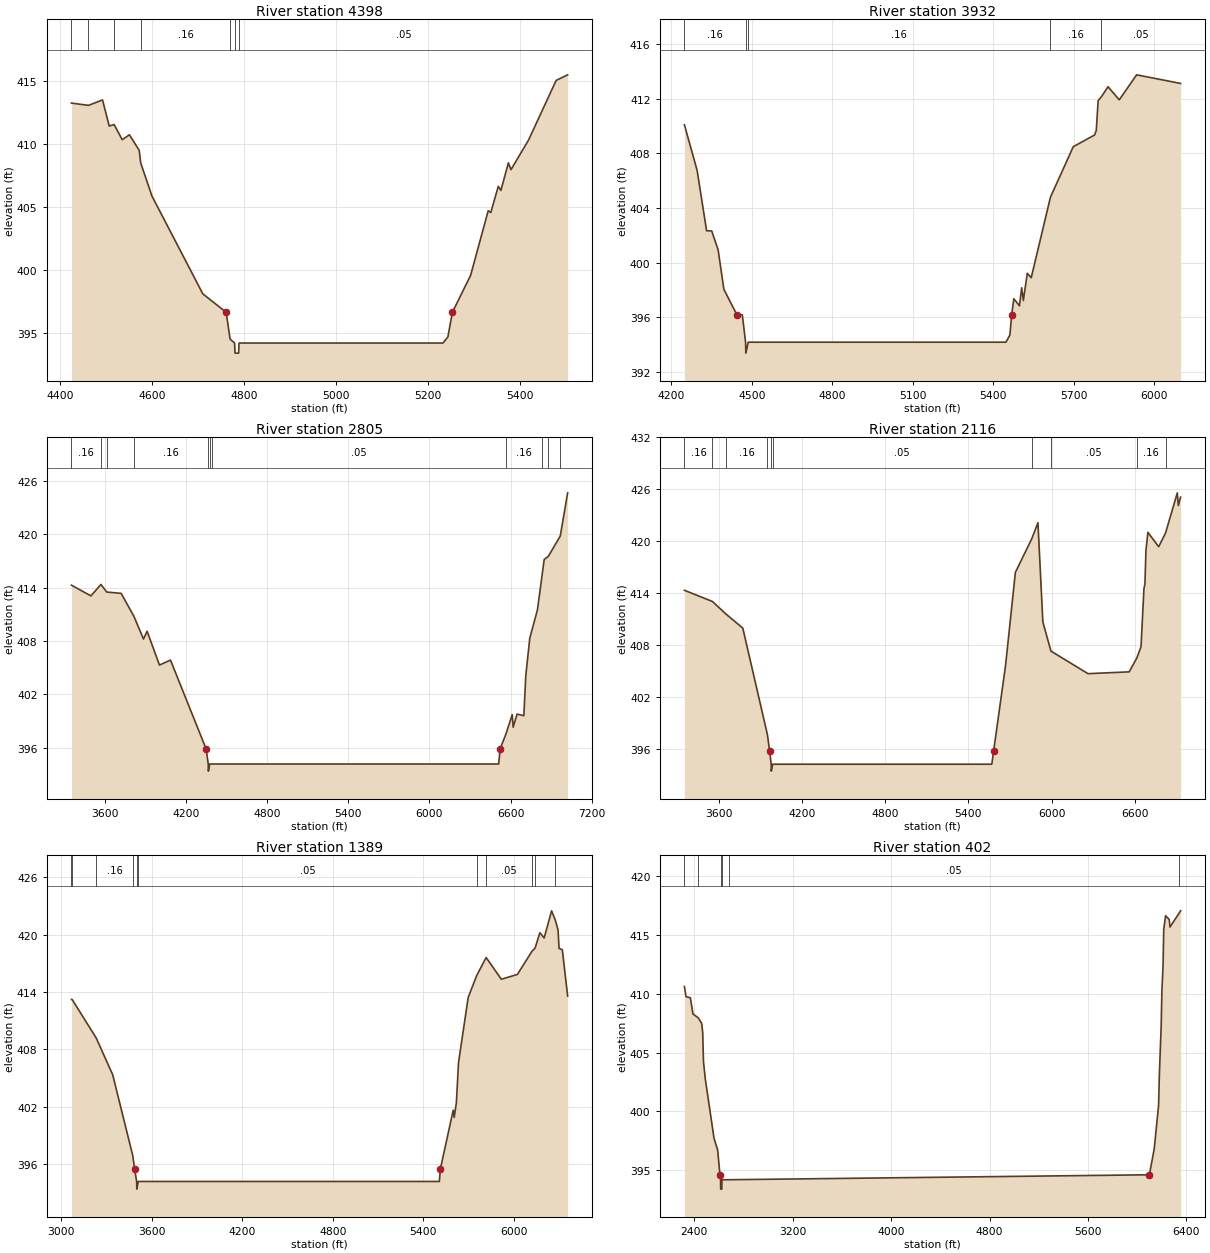
Type RM Length L Ch R = 1,4398,466,466,466
BEGIN DESCRIPTION:
Mapping XS 0f2e9a46
END DESCRIPTION:
XS GIS Cut Line= 3
      2901765.72      7012005.92      2901279.58      7011717.71
      2900825.40      7011960.40
#Sta/Elev= 30
  4424.0  413.21  4461.0  413.03  4491.6  413.46  4506.2  411.39  4516.8  411.51
  4534.5  410.31  4550.1  410.70  4571.5  409.46  4574.6  408.48  4599.2  405.84
  4709.9  398.09  4760.7  396.63  4769.3  394.50  4779.1  394.19  4780.1  393.39
  4787.9  393.39  4788.8  394.19  5232.8  394.19  5243.4  394.68  5253.3  396.63
  5292.9  399.56  5331.2  404.68  5336.8  404.53  5353.1  406.61  5358.8  406.29
  5375.1  408.47  5380.7  407.93  5419.0  410.28  5479.1  415.01  5504.1  415.45
#Mann=7,-1,0
  4424.0    0.16       0  4461.0    0.05       0  4516.8    0.08       0
  4574.6    0.16       0  4769.3    0.05       0  4779.1   0.033       0
  4788.8    0.05       0
Bank Sta=4760.7,5253.3
Exp/Cntr=0.3,0.1

Type RM Length L Ch R = 1,3932,1127,1127,1127
BEGIN DESCRIPTION:
BRUSHY CREEK 4.0
END DESCRIPTION:
XS GIS Cut Line= 3
      2901842.09      7011557.99      2901141.61      7011285.28
      2900494.20      7012173.59
#Sta/Elev= 30
  4248.3  410.09  4295.7  406.76  4331.0  402.34  4350.1  402.33  4374.0  400.95
  4395.4  398.06  4443.9  396.20  4464.2  396.19  4476.4  394.19  4477.4  393.39
  4486.2  394.19  5447.7  394.19  5462.4  394.72  5469.1  396.20  5477.1  397.37
  5498.0  396.85  5506.4  398.17  5512.6  397.24  5527.3  399.23  5542.0  398.91
  5613.7  404.80  5698.8  408.49  5778.4  409.35  5784.6  409.68  5791.6  411.86
  5803.8  412.15  5828.6  412.88  5870.3  411.92  5935.2  413.75  6099.2  413.12
#Mann=5,-1,0
  4248.3    0.16       0  4476.4   0.033       0  4486.2    0.16       0
  5613.7    0.16       0  5803.8    0.05       0
Bank Sta=4443.9,5469.1
Exp/Cntr=0.3,0.1

Type RM Length L Ch R = 1,2805,689,689,689
BEGIN DESCRIPTION:
BRUSHY CREEK 3.0
END DESCRIPTION:
XS GIS Cut Line= 3
      2901975.00      7012025.02      2901675.00      7010375.00
      2900070.12      7009197.46
#Sta/Elev= 30
  3354.3  414.27  3497.9  413.07  3572.2  414.35  3615.0  413.50  3721.5  413.35
  3814.7  410.81  3886.7  408.22  3913.3  409.10  4004.8  405.30  4086.1  405.86
  4349.9  395.87  4365.4  394.19  4366.3  393.39  4376.0  394.19  4393.8  394.19
  6512.0  394.19  6522.5  395.87  6565.4  397.55  6612.3  399.74  6619.0  398.32
  6647.8  399.79  6698.0  399.62  6712.7  404.15  6742.0  408.32  6798.3  411.48
  6828.6  414.88  6848.5  417.16  6879.3  417.51  6967.3  419.79  7021.9  424.64
#Mann=11,-1,0
  3354.3    0.16       0  3572.2    0.12       0  3615.0    0.05       0
  3814.7    0.16       0  4365.4   0.033       0  4376.0    0.16       0
  4393.8    0.05       0  6565.4    0.16       0  6828.6    0.05       0
  6879.3    0.08       0  6967.3    0.05       0
Bank Sta=4349.9,6522.5
Exp/Cntr=0.3,0.1

Type RM Length L Ch R = 1,2116,727,727,727
BEGIN DESCRIPTION:
BRUSHY CREEK 2.0
END DESCRIPTION:
XS GIS Cut Line= 3
      2901975.00      7011675.00      2902275.00      7010025.00
      2900939.97      7008676.67
#Sta/Elev= 30
  3354.3  414.30  3555.6  413.01  3654.6  411.54  3774.8  409.93  3951.7  397.64
  3968.3  395.73  3979.2  394.19  3980.0  393.39  3989.8  394.19  5568.7  394.19
  5582.0  395.73  5667.7  405.60  5738.5  416.37  5857.2  420.28  5901.1  422.12
  5936.4  410.64  5994.8  407.27  6261.7  404.66  6558.7  404.87  6613.0  406.46
  6643.6  407.77  6664.8  414.49  6671.9  415.05  6678.9  418.85  6693.0  421.00
  6770.9  419.34  6820.0  420.91  6905.2  425.57  6912.3  424.11  6928.8  425.07
#Mann=10,-1,0
  3354.3    0.16       0  3555.6    0.05       0  3654.6    0.16       0
  3951.7    0.05       0  3979.2   0.033       0  3989.8    0.05       0
  5857.2    0.08       0  5994.8    0.05       0  6613.0    0.16       0
  6820.0    0.05       0
Bank Sta=3968.3,5582
Exp/Cntr=0.3,0.1

Type RM Length L Ch R = 1,1389,987,987,987
BEGIN DESCRIPTION:
Mapping XS 74dc344c
END DESCRIPTION:
XS GIS Cut Line= 3
      2902140.33      7011466.24      2902918.09      7009639.89
      2901940.13      7008779.84
#Sta/Elev= 30
  3068.7  413.22  3073.4  413.21  3232.8  409.18  3341.8  405.35  3475.1  396.87
  3486.9  395.49  3500.6  394.19  3501.5  393.39  3511.3  394.19  5505.9  394.19
  5512.7  395.49  5598.0  401.65  5604.6  400.89  5618.9  402.45  5633.1  406.62
  5697.1  413.42  5752.7  415.69  5816.0  417.60  5916.8  415.33  6023.0  415.83
  6120.4  418.27  6140.5  418.59  6172.0  420.19  6200.5  419.65  6249.8  422.48
  6273.7  421.54  6292.5  420.49  6299.1  418.55  6320.9  418.41  6356.1  413.57
#Mann=11,-1,0
  3068.7    0.16       0  3073.4    0.08       0  3232.8    0.16       0
  3475.1    0.05       0  3500.6   0.033       0  3511.3    0.05       0
  5752.7    0.08       0  5816.0    0.05       0  6120.4    0.08       0
  6140.5    0.05       0  6273.7    0.16       0
Bank Sta=3486.9,5512.7
Exp/Cntr=0.3,0.1

Type RM Length L Ch R = 1,402,0,0,0
BEGIN DESCRIPTION:
BRUSHY CREEK 1.0
END DESCRIPTION:
XS GIS Cut Line= 3
      2902230.48      7011487.59      2903810.92      7009323.19
      2902700.00      7008550.00
#Sta/Elev= 30
  2320.0  410.63  2332.8  409.77  2368.3  409.67  2389.2  408.30  2433.0  407.96
  2460.2  407.49  2468.7  406.70  2474.9  404.24  2489.6  402.77  2560.6  397.72
  2590.0  396.73  2608.8  394.61  2614.0  394.19  2614.8  393.39  2623.8  393.39
  2624.7  394.19  2684.1  394.19  6099.7  394.61  6138.8  396.80  6174.6  400.52
  6180.7  403.09  6195.5  407.24  6201.6  410.33  6210.4  412.25  6216.5  415.49
  6231.3  416.65  6261.0  416.33  6267.1  415.69  6343.0  416.90  6353.5  417.07
#Mann=6,-1,0
  2320.0    0.08       0  2433.0    0.16       0  2614.0   0.033       0
  2624.7    0.16       0  2684.1    0.05       0  6343.0    0.08       0
Bank Sta=2608.8,6099.7
Exp/Cntr=0.3,0.1

Chan Stop Cuts=-1