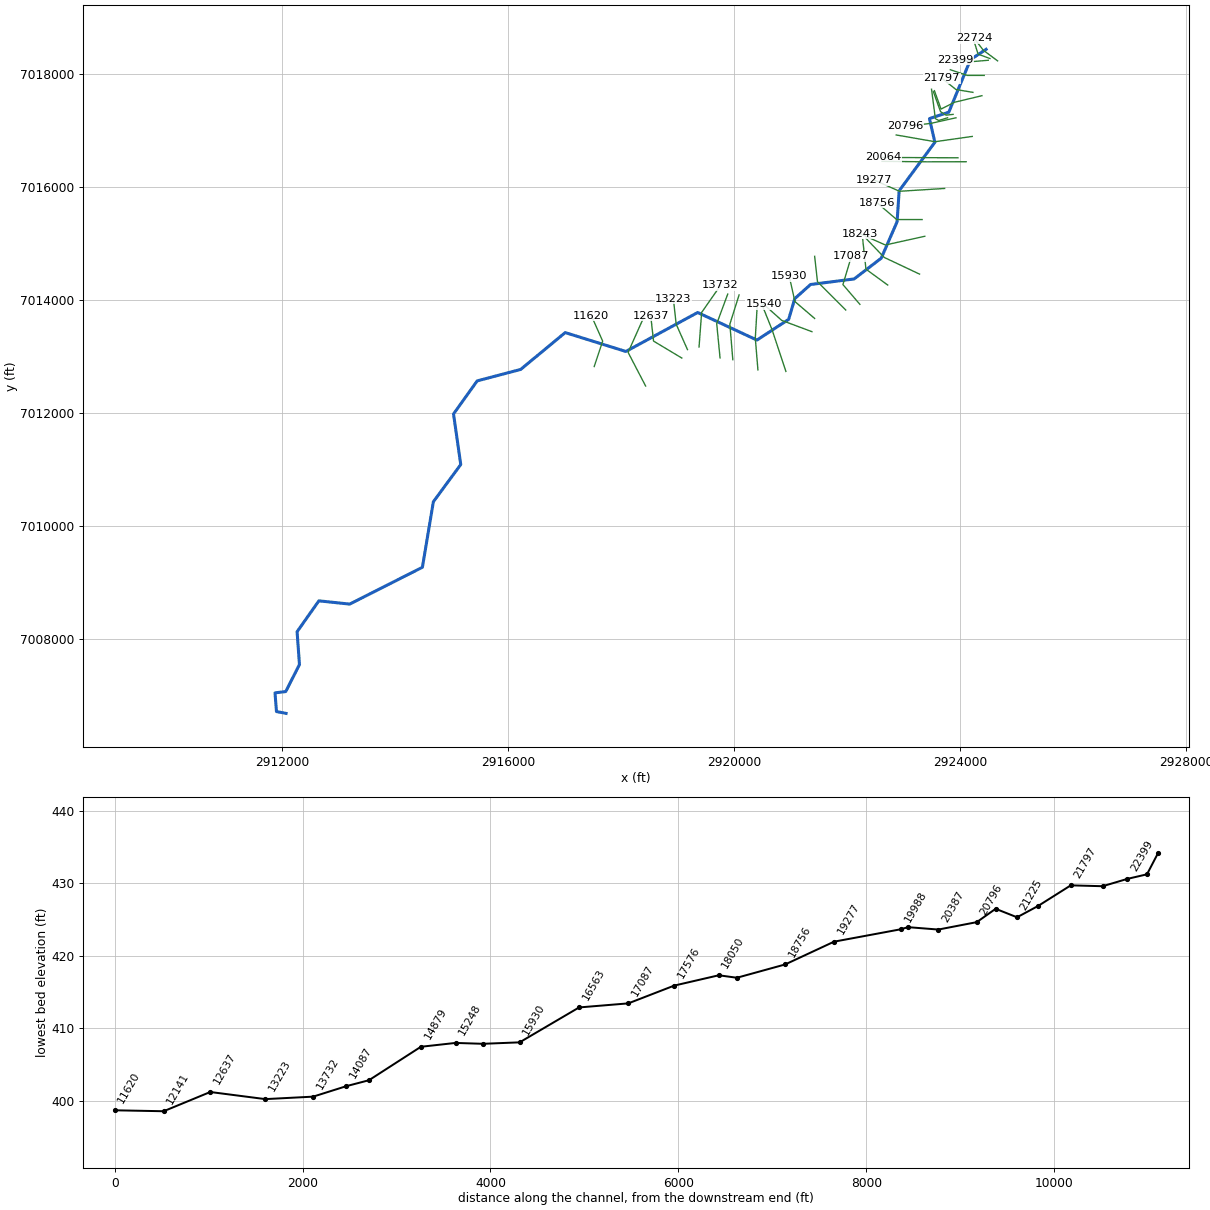
--- CARTER CREEK.prj (project) ---

Proj Title=CARTER CREEK Base Level Engineering
Current Plan=p01
Default Exp/Contr=0.3,0.1
English Units
Geom File=g01
Flow File=f01
Plan File=p01
BEGIN DESCRIPTION:
CARTER CREEK
END DESCRIPTION:

--- CARTER CREEK.p01 (plan) ---

Plan Title=Multiple Run
Short Identifier=Multiple
Geom File=g01
Flow File=f01
Subcritical Flow
K Sum by GR= 0
Std Step Tol= 0.01
Critical Tol= 0.01
Num of Std Step Trials= 20
Max Error Tol= 0.3
Flow Tol Ratio= 0.001
Split Flow NTrial= 30
Split Flow Tol= 0.02
Split Flow Ratio= 0.02
Log Output Level= 0
Friction Slope Method= 1
Unsteady Friction Slope Method= 2
Unsteady Bridges Friction Slope Method= 1
Parabolic Critical Depth
Global Vel Dist=  1 , 1 , 1
Global Log Level= 0
CheckData=True
Encroach Param= -1, 0, 0, 0
BEGIN DESCRIPTION:
Multiple Run
END DESCRIPTION:

--- CARTER CREEK.f01 (steady flow) ---

Flow Title=Multiple
Number of Profiles=7
Profile Names=10-year,25-year,50-year,1pct_min,100-year,1pct_plu,500-year
River Rch & RM= CARTER CREEK,Reach-1,22724
     399     523     622     368     734    1465    1025
River Rch & RM= CARTER CREEK,Reach-1,21225
     557     745     899     539    1075    2146    1542
River Rch & RM= CARTER CREEK,Reach-1,20796
     898    1229    1503     912    1820    3631    2674
River Rch & RM= CARTER CREEK,Reach-1,13223
    1211    1672    2057    1253    2501    4990    3708
River Rch & RM= CARTER CREEK,Reach-1,2562
    1623    2272    2819    1731    3455    6893    5204
Boundary for River Rch & Prof#=CARTER CREEK,Reach-1,1
Up Type=0
Dn Type=3
Dn Slope=0.005
Boundary for River Rch & Prof#=CARTER CREEK,Reach-1,2
Up Type=0
Dn Type=3
Dn Slope=0.005
Boundary for River Rch & Prof#=CARTER CREEK,Reach-1,3
Up Type=0
Dn Type=3
Dn Slope=0.005
Boundary for River Rch & Prof#=CARTER CREEK,Reach-1,4
Up Type=0
Dn Type=3
Dn Slope=0.005
Boundary for River Rch & Prof#=CARTER CREEK,Reach-1,5
Up Type=0
Dn Type=3
Dn Slope=0.005
Boundary for River Rch & Prof#=CARTER CREEK,Reach-1,6
Up Type=0
Dn Type=3
Dn Slope=0.005
Boundary for River Rch & Prof#=CARTER CREEK,Reach-1,7
Up Type=0
Dn Type=3
Dn Slope=0.005

--- CARTER CREEK.g01 (geometry) ---

Geom Title=Existing Conditions

River Reach=CARTER CREEK,Reach-1
Reach XY= 30
      2924457.65      7018436.61      2924181.07      7018253.33
      2923797.95      7017324.13      2923455.59      7017210.71
      2923551.36      7016792.30      2922919.63      7015933.64
      2922883.39      7015386.61      2922602.46      7014741.35
      2922123.38      7014374.32      2921352.77      7014276.12
      2921073.63      7014026.91      2920964.83      7013659.49
      2920404.27      7013292.92      2919355.59      7013780.71
      2918084.92      7013091.47      2917012.50      7013425.32
      2916224.50      7012773.73      2915455.28      7012570.98
      2915036.58      7011985.95      2915164.53      7011091.38
      2914680.14      7010433.55      2914486.31      7009273.79
      2913199.81      7008622.58      2912654.79      7008680.21
      2912269.28      7008133.64      2912311.46      7007552.79
      2912068.68      7007075.66      2911878.57      7007052.23
      2911904.61      7006721.50      2912074.25      7006689.42

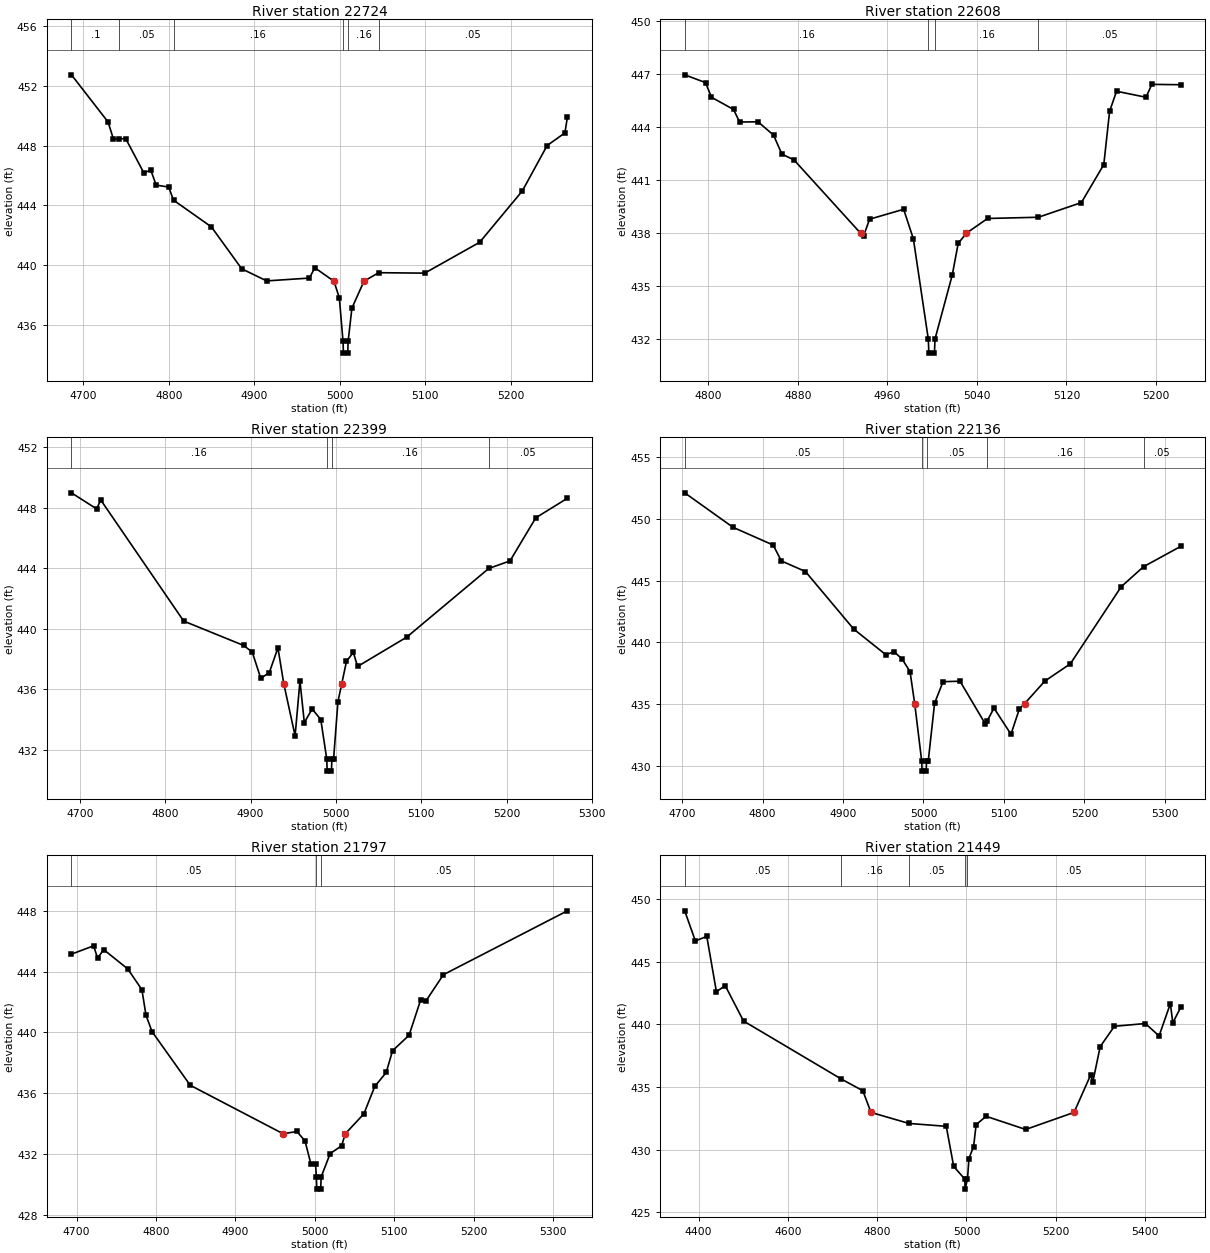
Type RM Length L Ch R = 1,22724,116,116,116
BEGIN DESCRIPTION:
CARTER CREEK 39.0
END DESCRIPTION:
XS GIS Cut Line= 3
      2924660.97      7018231.90      2924409.42      7018419.51
      2924246.93      7018630.61
#Sta/Elev= 30
  4686.2  452.74  4729.0  449.58  4735.3  448.44  4742.2  448.47  4749.9  448.44
  4770.7  446.19  4779.1  446.34  4785.3  445.35  4799.9  445.22  4805.6  444.34
  4849.9  442.55  4885.4  439.74  4914.6  438.93  4964.6  439.12  4970.9  439.81
  4993.3  438.91  4999.6  437.79  5003.9  434.89  5004.4  434.09  5009.4  434.09
  5009.9  434.89  5014.3  437.10  5028.4  438.91  5045.6  439.48  5099.5  439.45
  5163.8  441.52  5213.7  444.96  5242.7  448.00  5263.5  448.85  5266.4  449.90
#Mann=6,-1,0
  4686.2     0.1       0  4742.2    0.05       0  4805.6    0.16       0
  5003.9    0.07       0  5009.9    0.16       0  5045.6    0.05       0
Bank Sta=4993.3,5028.4
Exp/Cntr=0.3,0.1

Type RM Length L Ch R = 1,22608,209,209,209
BEGIN DESCRIPTION:
Mapping XS 252a04be
END DESCRIPTION:
XS GIS Cut Line= 3
      2924526.41      7018273.15      2924315.90      7018351.28
      2924250.80      7018559.59
#Sta/Elev= 30
  4779.1  446.96  4797.7  446.52  4803.0  445.69  4822.7  445.00  4828.1  444.29
  4844.6  444.30  4858.4  443.55  4865.9  442.47  4876.6  442.15  4936.1  438.00
  4938.9  437.86  4944.2  438.79  4974.6  439.35  4983.3  437.67  4996.6  432.01
  4997.1  431.21  5002.1  431.21  5002.6  432.01  5018.0  435.63  5023.3  437.42
  5030.7  438.00  5049.5  438.83  5094.9  438.90  5133.3  439.73  5153.3  441.88
  5158.5  444.90  5164.7  446.03  5191.0  445.69  5196.2  446.42  5221.9  446.40
#Mann=4,-1,0
  4779.1    0.16       0  4996.6    0.07       0  5002.6    0.16       0
  5094.9    0.05       0
Bank Sta=4936.1,5030.7
Exp/Cntr=0.3,0.1

Type RM Length L Ch R = 1,22399,263,263,263
BEGIN DESCRIPTION:
Mapping XS 22dfc5e1
END DESCRIPTION:
XS GIS Cut Line= 3
      2924496.01      7018242.77      2924190.03      7018216.73
      2923918.30      7018251.23
#Sta/Elev= 30
  4690.2  448.98  4719.6  447.92  4724.6  448.50  4821.7  440.50  4891.9  438.89
  4902.0  438.45  4912.0  436.71  4922.0  437.10  4932.1  438.73  4938.9  436.37
  4952.2  432.91  4957.9  436.54  4963.0  433.79  4972.2  434.69  4982.3  433.99
  4989.3  431.38  4989.8  430.58  4994.8  430.58  4995.3  431.38  4997.3  431.38
  5002.4  435.18  5006.9  436.37  5012.4  437.84  5020.4  438.43  5025.4  437.50
  5083.0  439.44  5179.1  443.98  5204.0  444.48  5234.2  447.33  5271.2  448.62
#Mann=4,-1,0
  4690.2    0.16       0  4989.3    0.07       0  4995.3    0.16       0
  5179.1    0.05       0
Bank Sta=4938.9,5006.9
Exp/Cntr=0.3,0.1

Type RM Length L Ch R = 1,22136,339,339,339
BEGIN DESCRIPTION:
CARTER CREEK 38.0
END DESCRIPTION:
XS GIS Cut Line= 3
      2924424.96      7017975.00      2924125.00      7017975.00
      2923824.99      7018075.00
#Sta/Elev= 30
  4703.3  452.10  4763.3  449.31  4813.3  447.87  4823.3  446.59  4853.3  445.73
  4913.3  441.07  4953.3  438.99  4963.3  439.24  4973.3  438.66  4983.3  437.62
  4989.1  435.03  4997.8  430.37  4998.3  429.57  5003.3  429.57  5003.8  430.37
  5005.9  430.37  5013.8  435.07  5024.3  436.81  5045.4  436.85  5077.0  433.37
  5079.1  433.63  5087.6  434.67  5108.7  432.56  5119.2  434.61  5125.6  435.03
  5150.8  436.86  5182.5  438.26  5245.7  444.50  5273.4  446.12  5319.5  447.76
#Mann=5,-1,0
  4703.3    0.05       0  4997.8    0.03       0  5003.8    0.05       0
  5079.1    0.16       0  5273.4    0.05       0
Bank Sta=4989.1,5125.6
Exp/Cntr=0.3,0.1

Type RM Length L Ch R = 1,21797,348,348,348
BEGIN DESCRIPTION:
CARTER CREEK 37.0
END DESCRIPTION:
XS GIS Cut Line= 3
      2924224.98      7017675.00      2923925.00      7017725.00
      2923674.98      7017925.02
#Sta/Elev= 30
  4693.5  445.14  4721.4  445.69  4726.4  444.87  4734.0  445.44  4764.4  444.17
  4782.2  442.80  4787.3  441.13  4794.9  440.05  4843.0  436.52  4960.0  433.33
  4977.3  433.48  4987.5  432.86  4995.1  431.31  5000.8  431.31  5001.8  430.49
  5002.3  429.69  5007.3  429.69  5007.8  430.49  5019.2  432.03  5033.6  432.54
  5038.2  433.33  5061.6  434.64  5075.3  436.44  5089.7  437.36  5097.7  438.79
  5118.5  439.81  5132.9  442.10  5139.3  442.03  5161.7  443.79  5317.8  447.99
#Mann=3,-1,0
  4693.5    0.05       0  5001.8    0.03       0  5007.8    0.05       0
Bank Sta=4960,5038.2
Exp/Cntr=0.3,0.1

Type RM Length L Ch R = 1,21449,224,224,224
BEGIN DESCRIPTION:
CARTER CREEK 36.0
END DESCRIPTION:
XS GIS Cut Line= 4
      2924383.16      7017615.60      2923900.00      7017500.00
      2923660.51      7017379.06      2923543.31      7017704.61
#Sta/Elev= 30
  4368.7  449.05  4392.6  446.65  4418.2  447.01  4439.8  442.59  4459.4  443.09
  4500.5  440.26  4719.2  435.64  4767.8  434.70  4786.1  432.97  4871.0  432.09
  4954.7  431.86  4971.4  428.66  4996.3  427.65  4996.8  426.85  5002.3  427.65
  5005.5  429.29  5016.0  430.25  5021.6  431.99  5043.9  432.66  5132.7  431.61
  5241.0  432.97  5277.9  435.93  5283.3  435.43  5299.5  438.21  5331.4  439.84
  5400.8  440.06  5431.5  439.07  5456.9  441.65  5462.2  440.11  5479.8  441.34
#Mann=5,-1,0
  4368.7    0.05       0  4719.2    0.16       0  4871.0    0.05       0
  4996.3    0.03       0  5002.3    0.05       0
Bank Sta=4786.1,5241
Exp/Cntr=0.3,0.1

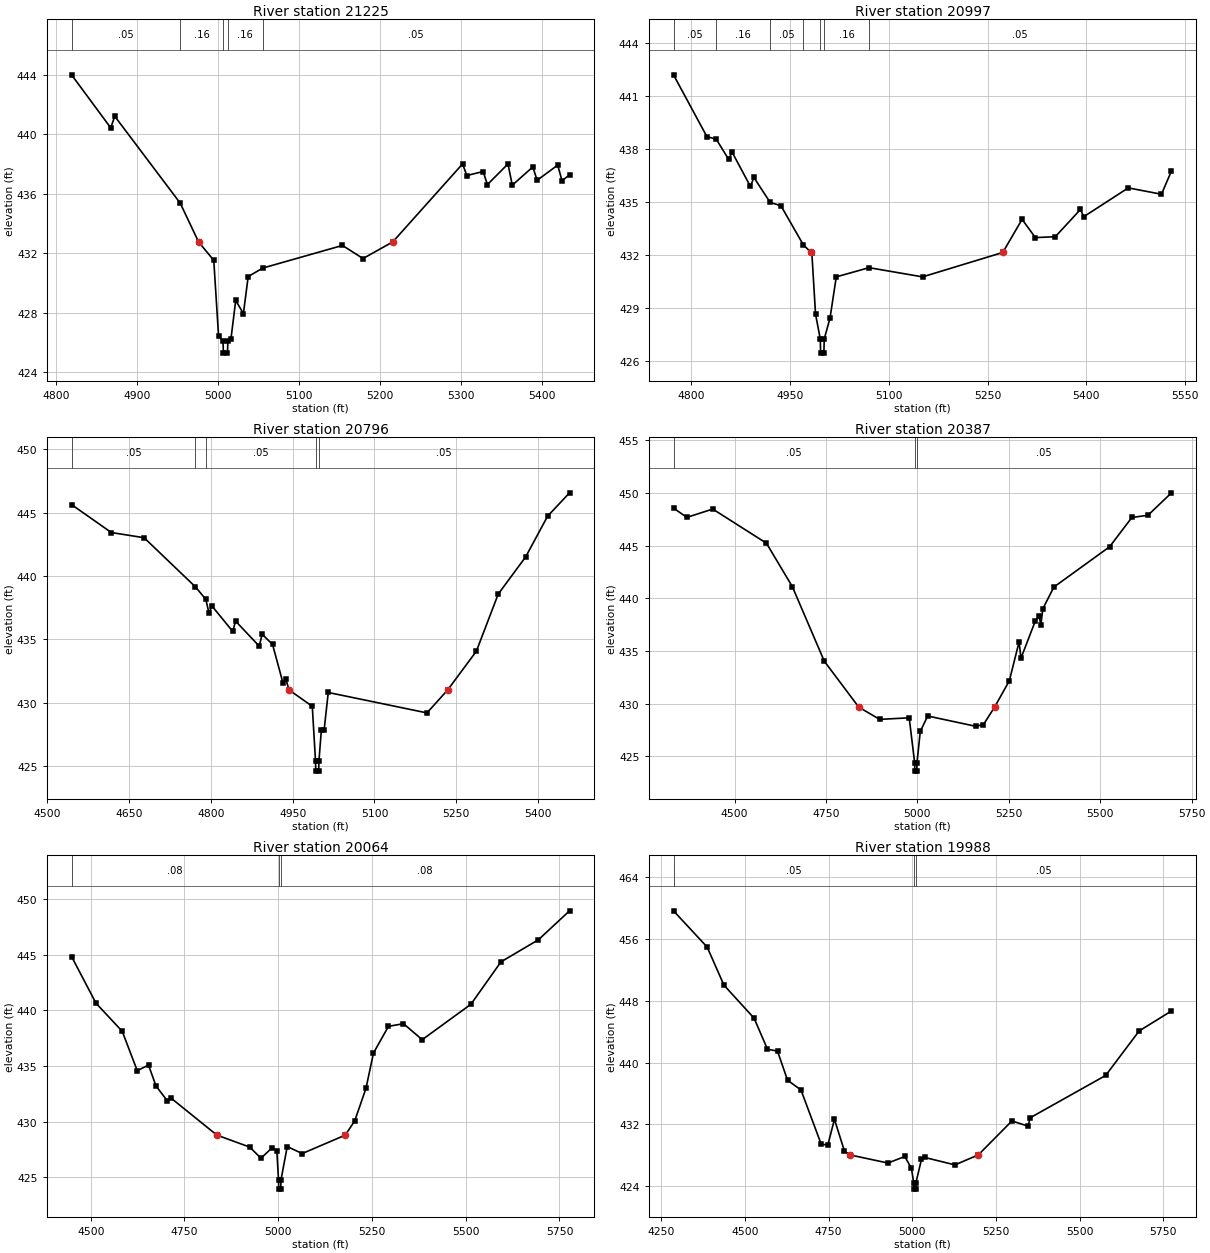
Type RM Length L Ch R = 1,21225,228,228,228
BEGIN DESCRIPTION:
Mapping XS 7d2c47b4
END DESCRIPTION:
XS GIS Cut Line= 4
      2923874.47      7017285.73      2923749.48      7017271.85
      2923652.25      7017332.61      2923525.53      7017685.00
#Sta/Elev= 30
  4819.6  444.00  4867.9  440.44  4873.0  441.21  4953.8  435.37  4976.4  432.77
  4995.2  431.53  5001.1  426.45  5006.6  426.09  5007.1  425.29  5012.1  425.29
  5012.6  426.09  5016.4  426.24  5022.3  428.83  5031.8  427.95  5037.7  430.44
  5055.8  431.01  5154.1  432.53  5179.5  431.65  5216.3  432.77  5302.4  438.01
  5307.7  437.23  5327.8  437.50  5333.1  436.62  5358.5  438.01  5363.8  436.58
  5389.2  437.81  5394.5  436.91  5419.9  437.93  5425.2  436.88  5434.5  437.27
#Mann=5,-1,0
  4819.6    0.05       0  4953.8    0.16       0  5006.6    0.07       0
  5012.6    0.16       0  5055.8    0.05       0
Bank Sta=4976.4,5216.3
Exp/Cntr=0.3,0.1

Type RM Length L Ch R = 1,20997,201,201,201
BEGIN DESCRIPTION:
Mapping XS 9b360f26
END DESCRIPTION:
XS GIS Cut Line= 4
      2923777.28      7017224.98      2923621.00      7017178.10
      2923560.24      7017209.35      2923492.54      7017730.07
#Sta/Elev= 30
  4772.8  442.19  4823.5  438.70  4837.8  438.55  4856.6  437.41  4861.8  437.82
  4889.7  435.88  4894.9  436.39  4919.6  434.98  4936.0  434.79  4969.9  432.59
  4981.8  432.15  4983.0  432.11  4988.6  428.66  4995.8  427.26  4996.3  426.46
  5001.3  426.46  5001.8  427.26  5010.6  428.44  5020.1  430.77  5069.9  431.29
  5151.2  430.77  5273.1  432.15  5302.4  434.02  5322.6  432.99  5352.9  433.04
  5391.1  434.58  5396.1  434.17  5463.8  435.80  5514.2  435.44  5529.4  436.76
#Mann=7,-1,0
  4772.8    0.05       0  4837.8    0.16       0  4919.6    0.05       0
  4969.9    0.16       0  4995.8    0.07       0  5001.8    0.16       0
  5069.9    0.05       0
Bank Sta=4981.8,5273.1
Exp/Cntr=0.3,0.1

Type RM Length L Ch R = 1,20796,409,409,409
BEGIN DESCRIPTION:
CARTER CREEK 35.0
END DESCRIPTION:
XS GIS Cut Line= 3
      2923924.98      7017225.00      2923475.00      7017125.00
      2923025.02      7017075.00
#Sta/Elev= 30
  4544.2  445.63  4617.2  443.43  4677.3  443.02  4771.4  439.15  4790.6  438.16
  4796.4  437.06  4801.6  437.65  4840.0  435.63  4845.1  436.45  4888.6  434.47
  4893.8  435.41  4913.0  434.61  4932.2  431.55  4937.3  431.87  4943.3  431.02
  4985.9  429.73  4991.8  425.42  4992.3  424.62  4997.6  424.62  4998.1  425.42
  5002.6  427.90  5007.7  427.90  5015.2  430.82  5196.3  429.21  5234.3  431.02
  5286.9  434.07  5327.1  438.58  5377.4  441.51  5417.7  444.72  5457.9  446.56
#Mann=5,-1,0
  4544.2    0.05       0  4771.4    0.16       0  4790.6    0.05       0
  4991.8    0.03       0  4998.1    0.05       0
Bank Sta=4943.3,5234.3
Exp/Cntr=0.3,0.1

Type RM Length L Ch R = 1,20387,323,323,323
BEGIN DESCRIPTION:
Mapping XS 00a3e561
END DESCRIPTION:
XS GIS Cut Line= 3
      2924213.05      7016895.57      2923554.19      7016801.82
      2922868.32      7016921.33
#Sta/Elev= 30
  4333.1  448.56  4369.6  447.68  4440.4  448.47  4587.2  445.23  4658.0  441.11
  4745.3  434.04  4839.5  429.68  4896.8  428.51  4977.6  428.66  4992.5  424.40
  4993.0  423.60  4998.4  423.60  4998.9  424.40  5007.9  427.37  5028.2  428.83
  5158.9  427.86  5180.5  428.01  5211.2  429.68  5251.5  432.18  5278.1  435.87
  5283.2  434.31  5322.6  437.86  5332.6  438.31  5337.7  437.49  5342.9  439.00
  5373.3  441.07  5525.6  444.89  5586.5  447.67  5630.5  447.88  5694.8  450.01
#Mann=3,-1,0
  4333.1    0.05       0  4992.5    0.03       0  4998.9    0.05       0
Bank Sta=4839.5,5211.2
Exp/Cntr=0.3,0.1

Type RM Length L Ch R = 1,20064,76,76,76
BEGIN DESCRIPTION:
Mapping XS 4d578e9d
END DESCRIPTION:
XS GIS Cut Line= 3
      2923960.22      7016517.54      2923415.51      7016519.71
      2922632.13      7016524.05
#Sta/Elev= 30
  4448.8  444.85  4514.0  440.65  4584.0  438.12  4624.0  434.58  4654.0  435.09
  4674.0  433.21  4704.0  431.88  4714.0  432.12  4836.3  428.79  4924.0  427.71
  4954.0  426.71  4984.0  427.66  4996.3  427.36  5000.8  424.73  5001.3  423.93
  5006.7  423.93  5007.2  424.73  5024.0  427.76  5064.0  427.13  5178.9  428.79
  5204.0  430.07  5234.0  432.99  5254.0  436.17  5294.0  438.57  5334.0  438.81
  5384.0  437.37  5514.0  440.56  5594.0  444.37  5694.0  446.36  5776.9  448.96
#Mann=3,-1,0
  4448.8    0.08       0  5000.8    0.07       0  5007.2    0.08       0
Bank Sta=4836.3,5178.9
Exp/Cntr=0.3,0.1

Type RM Length L Ch R = 1,19988,711,711,711
BEGIN DESCRIPTION:
Mapping XS a21e5459
END DESCRIPTION:
XS GIS Cut Line= 3
      2924105.63      7016448.09      2923419.85      7016445.92
      2922618.48      7016454.58
#Sta/Elev= 30
  4287.1  459.60  4387.7  454.91  4437.7  450.00  4527.7  445.73  4567.7  441.72
  4597.7  441.47  4627.7  437.71  4667.7  436.46  4727.7  429.50  4747.7  429.28
  4767.7  432.67  4797.7  428.54  4813.3  428.07  4927.7  427.01  4977.8  427.86
  4997.7  426.32  5004.5  424.44  5005.0  423.64  5010.4  423.64  5010.9  424.44
  5027.7  427.49  5037.7  427.73  5127.7  426.77  5197.6  428.07  5297.8  432.45
  5346.5  431.77  5351.5  432.84  5577.8  438.33  5677.8  444.08  5774.3  446.66
#Mann=3,-1,0
  4287.1    0.05       0  5004.5    0.03       0  5010.9    0.05       0
Bank Sta=4813.3,5197.6
Exp/Cntr=0.3,0.1

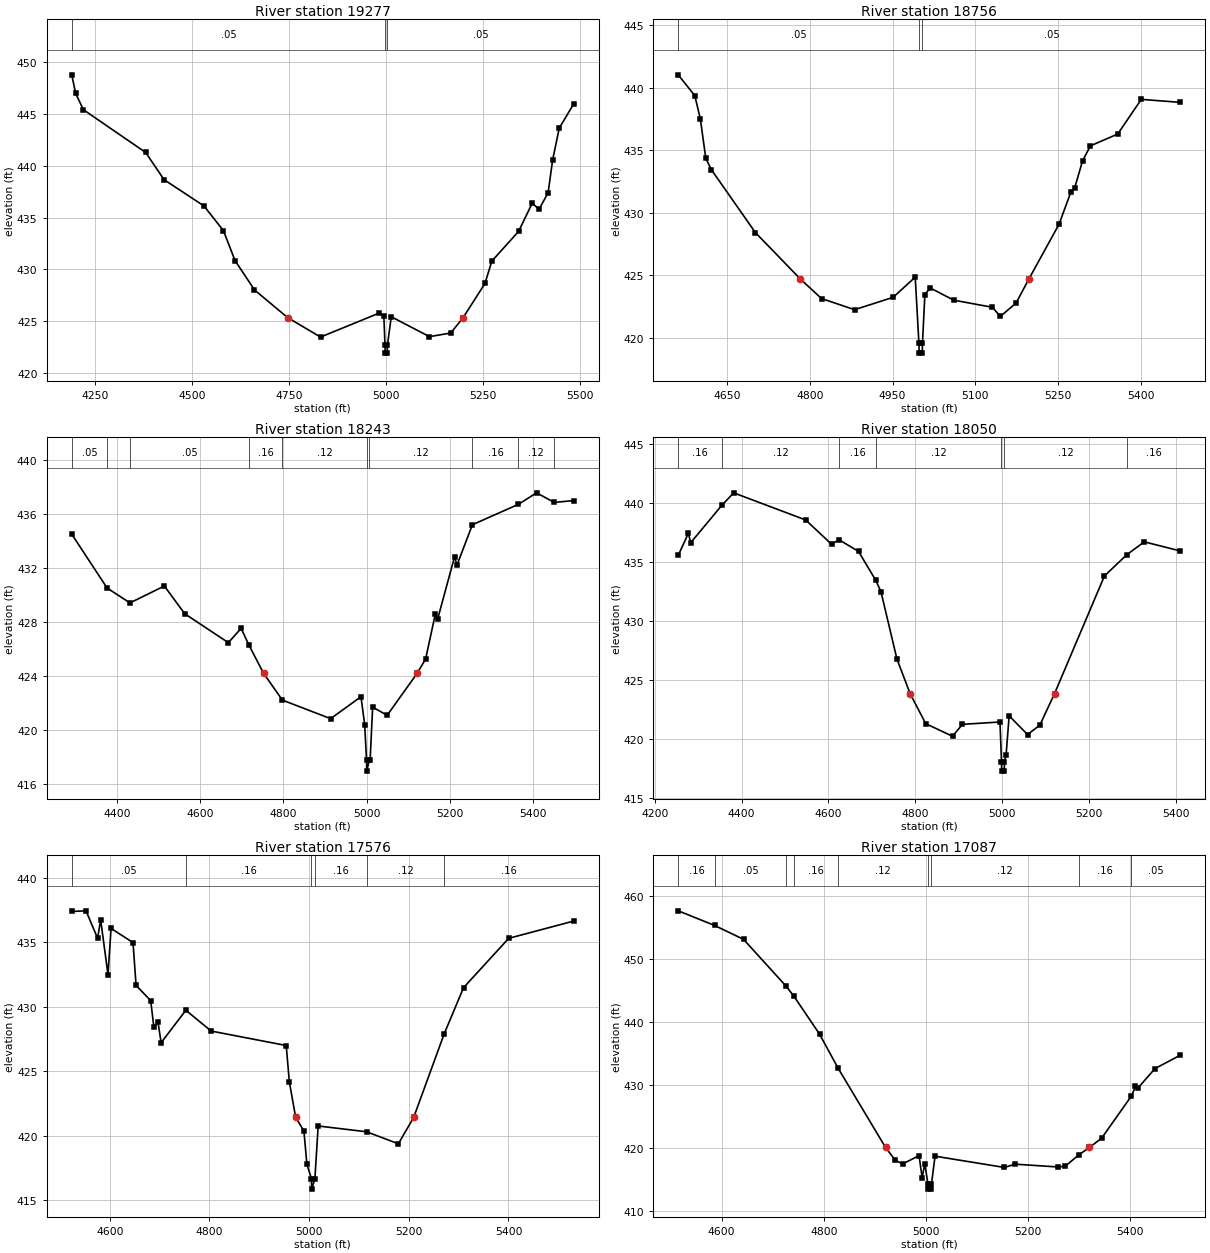
Type RM Length L Ch R = 1,19277,521,521,521
BEGIN DESCRIPTION:
CARTER CREEK 32.0
END DESCRIPTION:
XS GIS Cut Line= 3
      2923725.00      7015975.00      2922925.00      7015925.00
      2922475.00      7016125.00
#Sta/Elev= 30
  4190.2  448.78  4200.2  446.98  4220.3  445.41  4380.6  441.29  4428.2  438.66
  4530.9  436.13  4581.0  433.75  4611.0  430.86  4661.1  428.03  4746.4  425.36
  4831.4  423.48  4981.7  425.78  4994.5  425.53  4997.5  422.73  4998.0  421.93
  5003.4  421.93  5003.9  422.73  5013.6  425.44  5112.1  423.52  5166.9  423.87
  5199.0  425.36  5255.1  428.65  5272.9  430.81  5341.9  433.68  5376.8  436.39
  5394.6  435.82  5417.9  437.40  5429.5  440.56  5446.6  443.64  5484.2  446.00
#Mann=3,-1,0
  4190.2    0.05       0  4997.5    0.03       0  5003.9    0.05       0
Bank Sta=4746.4,5199
Exp/Cntr=0.3,0.1

Type RM Length L Ch R = 1,18756,513,513,513
BEGIN DESCRIPTION:
CARTER CREEK 31.0
END DESCRIPTION:
XS GIS Cut Line= 3
      2923324.97      7015425.00      2922875.00      7015425.00
      2922524.96      7015725.03
#Sta/Elev= 30
  4561.2  441.02  4591.2  439.36  4601.2  437.53  4611.2  434.35  4621.2  433.45
  4701.2  428.42  4783.0  424.70  4821.2  423.15  4881.2  422.26  4951.2  423.25
  4991.2  424.86  4997.9  419.59  4998.4  418.79  5003.9  418.79  5004.4  419.59
  5008.7  423.47  5018.3  424.00  5061.1  423.02  5131.4  422.45  5145.6  421.72
  5174.2  422.79  5197.3  424.70  5252.1  429.08  5274.0  431.70  5280.6  432.00
  5294.9  434.16  5309.2  435.35  5358.6  436.29  5401.4  439.06  5472.2  438.82
#Mann=3,-1,0
  4561.2    0.05       0  4997.9    0.03       0  5004.4    0.05       0
Bank Sta=4783,5197.3
Exp/Cntr=0.3,0.1

Type RM Length L Ch R = 1,18243,193,193,193
BEGIN DESCRIPTION:
CARTER CREEK 30.0
END DESCRIPTION:
XS GIS Cut Line= 3
      2923372.54      7015129.08      2922675.00      7014975.00
      2922224.99      7015175.00
#Sta/Elev= 30
  4291.4  434.48  4376.3  430.50  4431.3  429.40  4514.0  430.65  4562.8  428.60
  4667.8  426.46  4698.5  427.52  4717.0  426.29  4752.7  424.18  4797.8  422.21
  4913.6  420.84  4986.5  422.46  4995.5  420.39  4999.9  417.76  5000.4  416.96
  5006.5  417.76  5008.5  417.76  5014.6  421.69  5049.5  421.09  5121.3  424.18
  5141.9  425.25  5165.1  428.55  5170.6  428.18  5211.6  432.82  5217.1  432.18
  5254.3  435.18  5365.0  436.69  5408.6  437.54  5451.1  436.83  5498.2  436.97
#Mann=10,-1,0
  4291.4    0.05       0  4376.3    0.16       0  4431.3    0.05       0
  4717.0    0.16       0  4797.8    0.12       0  4999.9    0.07       0
  5006.5    0.12       0  5254.3    0.16       0  5365.0    0.12       0
  5451.1    0.05       0
Bank Sta=4752.7,5121.3
Exp/Cntr=0.3,0.1

Type RM Length L Ch R = 1,18050,474,474,474
BEGIN DESCRIPTION:
Mapping XS 0f35c06a
END DESCRIPTION:
XS GIS Cut Line= 3
      2923280.49      7014459.83      2922655.53      7014754.95
      2922333.47      7015090.86
#Sta/Elev= 30
  4253.9  435.56  4277.1  437.43  4282.7  436.64  4354.0  439.79  4381.6  440.86
  4547.5  438.56  4607.0  436.51  4624.6  436.88  4669.2  435.90  4708.9  433.45
  4720.8  432.50  4757.6  426.80  4788.0  423.86  4824.0  421.32  4885.7  420.25
  4908.5  421.26  4995.0  421.46  4998.5  418.10  4999.0  417.30  5004.8  417.30
  5005.3  418.10  5009.1  418.67  5016.1  421.98  5058.5  420.40  5086.8  421.19
  5120.7  423.86  5235.6  433.82  5287.4  435.63  5327.4  436.71  5410.4  435.94
#Mann=7,-1,0
  4253.9    0.16       0  4354.0    0.12       0  4624.6    0.16       0
  4708.9    0.12       0  4998.5    0.07       0  5005.3    0.12       0
  5287.4    0.16       0
Bank Sta=4788,5120.7
Exp/Cntr=0.3,0.1

Type RM Length L Ch R = 1,17576,489,489,489
BEGIN DESCRIPTION:
CARTER CREEK 29.0
END DESCRIPTION:
XS GIS Cut Line= 3
      2922717.39      7014266.23      2922332.71      7014546.92
      2922275.00      7015074.97
#Sta/Elev= 30
  4523.8  437.38  4552.4  437.43  4575.6  435.31  4581.8  436.73  4596.5  432.48
  4602.6  436.07  4646.7  434.97  4652.8  431.66  4682.2  430.47  4688.4  428.45
  4696.9  428.79  4703.1  427.22  4752.7  429.73  4803.5  428.12  4954.1  427.00
  4960.3  424.21  4973.0  421.44  4989.6  420.38  4995.5  417.83  5004.7  416.68
  5005.2  415.88  5011.6  416.68  5018.2  420.77  5115.4  420.32  5179.1  419.39
  5209.9  421.44  5271.1  427.91  5309.9  431.48  5400.5  435.30  5531.2  436.64
#Mann=6,-1,0
  4523.8    0.05       0  4752.7    0.16       0  5004.7    0.07       0
  5011.6    0.16       0  5115.4    0.12       0  5271.1    0.16       0
Bank Sta=4973,5209.9
Exp/Cntr=0.3,0.1

Type RM Length L Ch R = 1,17087,524,524,524
BEGIN DESCRIPTION:
CARTER CREEK 28.0
END DESCRIPTION:
XS GIS Cut Line= 3
      2922225.02      7013924.97      2921925.00      7014275.00
      2922074.99      7014774.97
#Sta/Elev= 30
  4515.1  457.71  4586.3  455.38  4643.0  453.17  4726.2  445.73  4741.7  444.11
  4791.7  438.10  4828.3  432.64  4921.0  420.06  4940.4  417.99  4954.7  417.45
  4986.6  418.76  4992.6  415.26  4997.9  417.47  5004.0  414.23  5004.5  413.43
  5010.4  413.43  5010.9  414.23  5017.9  418.67  5153.6  416.88  5174.5  417.40
  5258.0  416.96  5272.8  417.07  5299.6  418.90  5320.2  420.06  5344.1  421.54
  5402.5  428.26  5410.3  429.77  5415.5  429.55  5448.5  432.61  5498.1  434.74
#Mann=9,-1,0
  4515.1    0.16       0  4586.3    0.05       0  4726.2    0.12       0
  4741.7    0.16       0  4828.3    0.12       0  5004.0    0.07       0
  5010.9    0.12       0  5299.6    0.16       0  5402.5    0.05       0
Bank Sta=4921,5320.2
Exp/Cntr=0.3,0.1

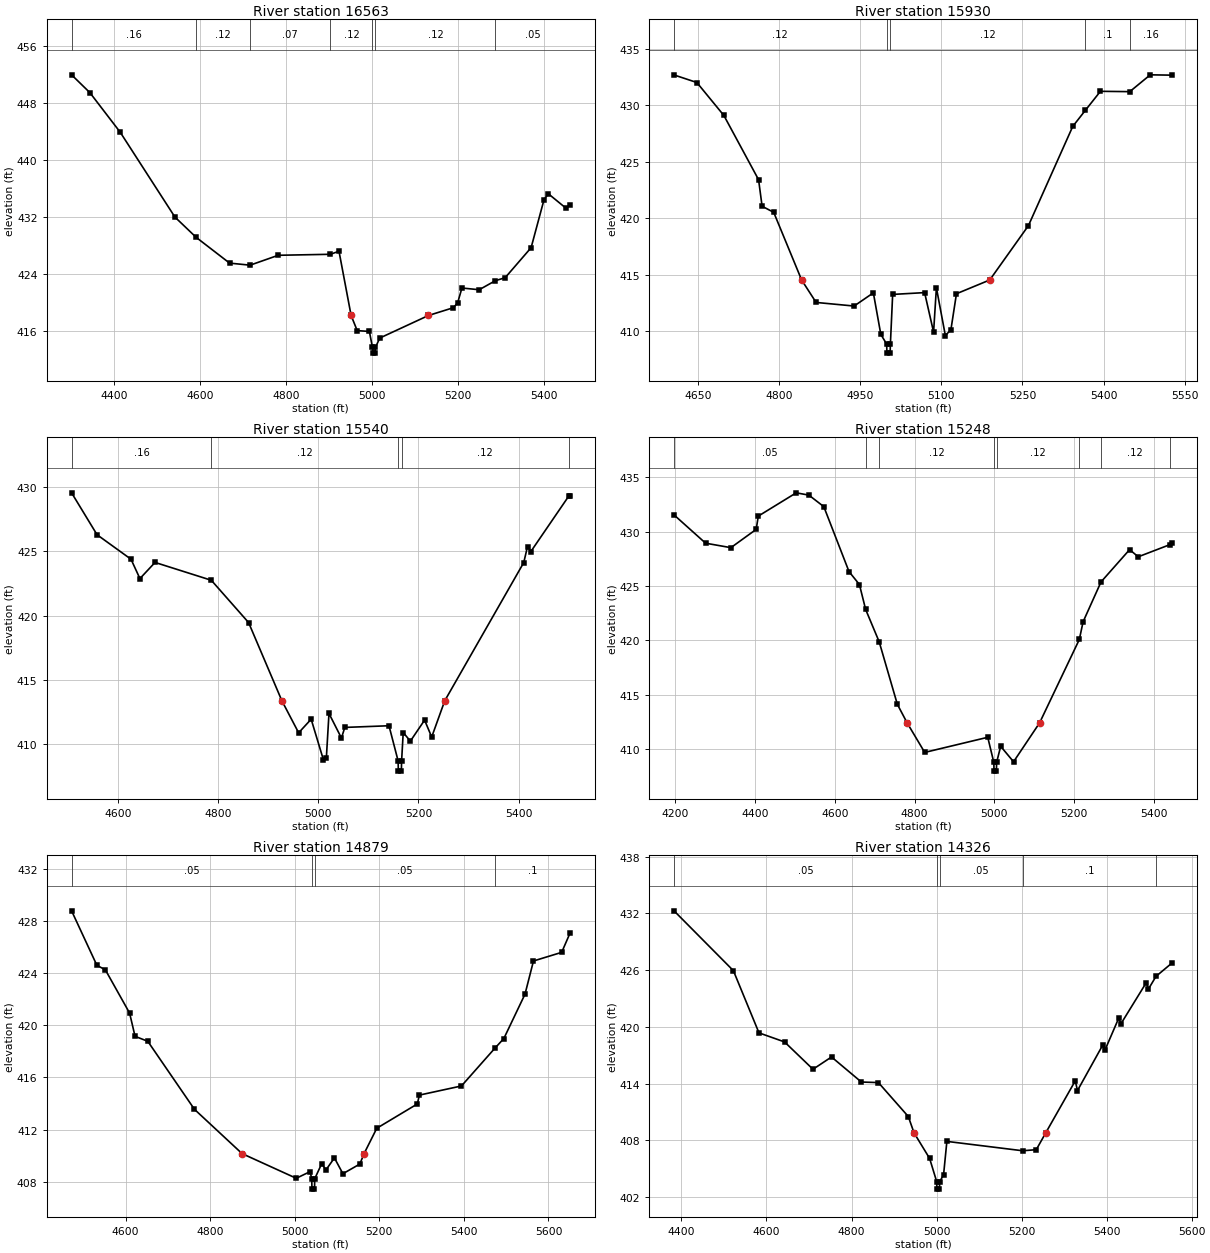
Type RM Length L Ch R = 1,16563,633,633,633
BEGIN DESCRIPTION:
CARTER CREEK 27.0
END DESCRIPTION:
XS GIS Cut Line= 3
      2921975.03      7013824.97      2921475.00      7014325.00
      2921425.00      7014774.99
#Sta/Elev= 30
  4301.1  451.98  4343.6  449.48  4414.3  443.91  4541.6  431.99  4591.0  429.14
  4668.8  425.52  4716.5  425.23  4782.0  426.62  4903.4  426.76  4923.4  427.19
  4951.6  418.16  4965.8  416.03  4994.1  415.92  5001.3  413.67  5001.8  412.87
  5007.7  412.87  5008.2  413.67  5018.3  414.99  5131.6  418.16  5189.4  419.25
  5199.4  419.92  5209.5  422.02  5249.7  421.78  5287.3  423.05  5310.1  423.47
  5370.5  427.69  5400.6  434.45  5410.7  435.26  5451.0  433.27  5461.0  433.68
#Mann=7,-1,0
  4301.1    0.16       0  4591.0    0.12       0  4716.5    0.07       0
  4903.4    0.12       0  5001.3    0.07       0  5008.2    0.12       0
  5287.3    0.05       0
Bank Sta=4951.6,5131.6
Exp/Cntr=0.3,0.1

Type RM Length L Ch R = 1,15930,390,390,390
BEGIN DESCRIPTION:
CARTER CREEK 26.0
END DESCRIPTION:
XS GIS Cut Line= 3
      2921424.97      7013675.03      2921075.00      7013975.00
      2920975.00      7014424.99
#Sta/Elev= 30
  4605.6  432.70  4647.8  432.03  4697.8  429.11  4762.0  423.42  4768.5  421.07
  4790.0  420.53  4841.6  414.54  4868.4  412.55  4938.7  412.23  4974.3  413.40
  4988.1  409.72  4998.9  408.86  4999.4  408.06  5005.3  408.06  5005.8  408.86
  5010.0  413.26  5069.1  413.42  5085.7  409.92  5090.9  413.85  5107.5  409.61
  5117.8  410.15  5128.0  413.32  5189.6  414.54  5261.2  419.36  5343.1  428.14
  5366.5  429.57  5394.3  431.25  5448.6  431.22  5486.5  432.71  5527.5  432.68
#Mann=5,-1,0
  4605.6    0.12       0  4998.9    0.07       0  5005.8    0.12       0
  5366.5     0.1       0  5448.6    0.16       0
Bank Sta=4841.6,5189.6
Exp/Cntr=0.3,0.1

Type RM Length L Ch R = 1,15540,292,292,292
BEGIN DESCRIPTION:
CARTER CREEK 25.0
END DESCRIPTION:
XS GIS Cut Line= 3
      2921376.19      7013441.60      2920842.38      7013641.23
      2920524.97      7013925.03
#Sta/Elev= 30
  4507.1  429.57  4558.0  426.30  4625.8  424.39  4643.6  422.88  4673.8  424.14
  4786.2  422.75  4860.7  419.45  4927.2  413.35  4960.7  410.85  4985.7  411.91
  5010.2  408.74  5016.0  408.85  5021.3  412.36  5046.2  410.44  5052.9  411.27
  5141.2  411.40  5159.4  408.66  5159.9  407.86  5165.9  407.86  5166.4  408.66
  5169.6  410.87  5183.9  410.20  5212.3  411.84  5226.5  410.52  5252.6  413.35
  5410.4  424.13  5417.9  425.38  5424.6  424.99  5500.6  429.33  5502.8  429.33
#Mann=5,-1,0
  4507.1    0.16       0  4786.2    0.12       0  5159.4    0.07       0
  5166.4    0.12       0  5500.6     0.1       0
Bank Sta=4927.2,5252.6
Exp/Cntr=0.3,0.1

Type RM Length L Ch R = 1,15248,369,369,369
BEGIN DESCRIPTION:
Mapping XS d70c4f1c
END DESCRIPTION:
XS GIS Cut Line= 3
      2920916.15      7012738.49      2920673.11      7013471.96
      2920495.17      7013914.64
#Sta/Elev= 30
  4196.7  431.53  4275.9  428.93  4339.3  428.52  4402.7  430.20  4408.0  431.42
  4503.1  433.56  4534.8  433.35  4572.3  432.29  4635.5  426.32  4661.6  425.13
  4677.1  422.85  4711.2  419.86  4756.7  414.12  4781.3  412.41  4825.3  409.70
  4983.4  411.09  4998.6  408.78  4999.1  407.98  5005.1  407.98  5005.6  408.78
  5015.8  410.26  5048.1  408.84  5113.3  412.41  5213.0  420.08  5222.5  421.71
  5267.4  425.37  5339.1  428.34  5360.7  427.68  5439.6  428.79  5446.5  428.94
#Mann=8,-1,0
  4196.7    0.05       0  4677.1    0.16       0  4711.2    0.12       0
  4998.6    0.07       0  5005.6    0.12       0  5213.0    0.07       0
  5267.4    0.12       0  5439.6     0.1       0
Bank Sta=4781.3,5113.3
Exp/Cntr=0.3,0.1

Type RM Length L Ch R = 1,14879,553,553,553
BEGIN DESCRIPTION:
CARTER CREEK 24.0
END DESCRIPTION:
XS GIS Cut Line= 3
      2920421.54      7012765.40      2920375.00      7013325.00
      2920411.06      7013941.22
#Sta/Elev= 30
  4472.2  428.76  4532.0  424.59  4552.1  424.24  4609.4  420.93  4622.3  419.15
  4652.4  418.77  4762.8  413.56  4875.4  410.17  5003.6  408.28  5036.2  408.79
  5040.2  408.25  5040.7  407.45  5046.7  407.45  5047.3  408.25  5063.8  409.40
  5073.8  408.92  5093.8  409.84  5113.9  408.63  5153.9  409.37  5164.0  410.17
  5194.0  412.11  5289.8  413.97  5294.8  414.65  5394.3  415.35  5473.9  418.26
  5494.5  418.98  5544.6  422.38  5564.6  424.92  5631.3  425.58  5651.0  427.05
#Mann=4,-1,0
  4472.2    0.05       0  5040.2    0.03       0  5047.3    0.05       0
  5473.9     0.1       0
Bank Sta=4875.4,5164
Exp/Cntr=0.3,0.1

Type RM Length L Ch R = 1,14326,239,239,239
BEGIN DESCRIPTION:
CARTER CREEK 23.0
END DESCRIPTION:
XS GIS Cut Line= 3
      2919977.10      7012945.91      2919925.00      7013575.00
      2920087.92      7014090.83
#Sta/Elev= 30
  4382.6  432.28  4522.2  425.95  4582.4  419.37  4642.6  418.41  4709.4  415.52
  4753.0  416.82  4823.2  414.17  4863.3  414.11  4933.6  410.52  4947.0  408.80
  4983.7  406.09  5000.3  403.64  5000.8  402.84  5006.9  402.84  5007.4  403.64
  5016.5  404.34  5024.3  407.89  5202.3  406.90  5234.5  407.01  5256.9  408.80
  5326.2  414.29  5331.5  413.27  5390.9  418.08  5396.2  417.56  5428.5  420.93
  5433.7  420.33  5493.1  424.67  5498.4  424.01  5516.2  425.35  5554.8  426.80
#Mann=5,-1,0
  4382.6    0.05       0  5000.3    0.03       0  5007.4    0.05       0
  5202.3     0.1       0  5516.2    0.05       0
Bank Sta=4947,5256.9
Exp/Cntr=0.3,0.1

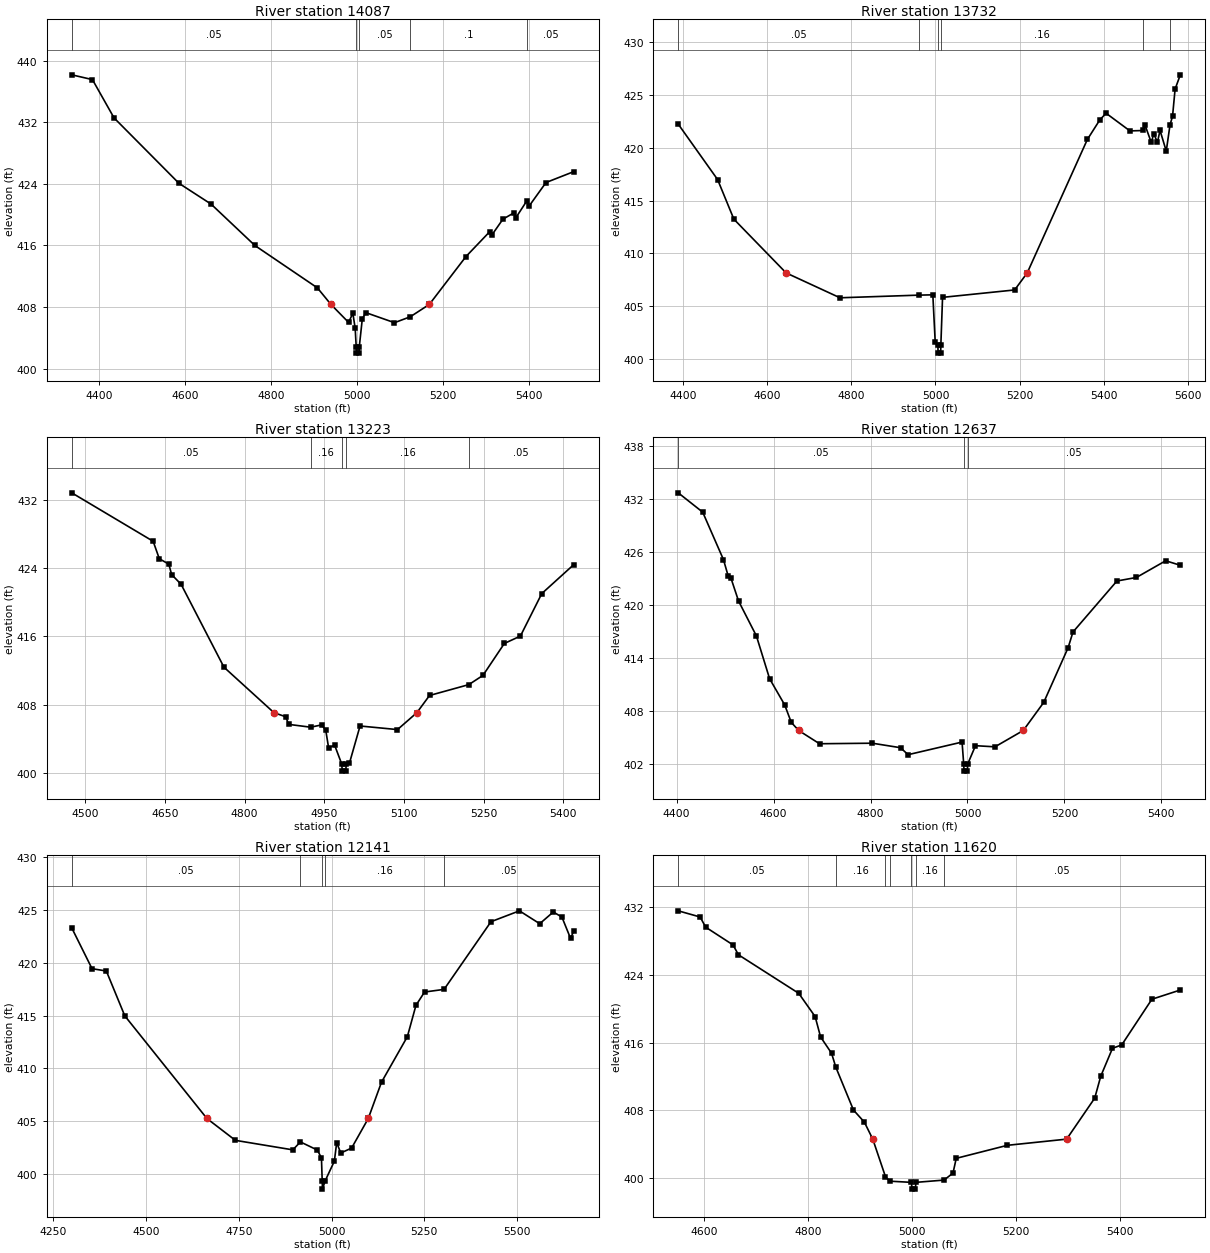
Type RM Length L Ch R = 1,14087,355,355,355
BEGIN DESCRIPTION:
Mapping XS 3dc0392d
END DESCRIPTION:
XS GIS Cut Line= 3
      2919751.40      7012977.22      2919692.38      7013581.34
      2919886.83      7014105.65
#Sta/Elev= 30
  4337.2  438.15  4385.2  437.53  4435.4  432.56  4586.2  424.07  4660.8  421.37
  4762.5  416.00  4907.7  410.50  4939.2  408.35  4980.1  406.02  4990.1  407.20
  4995.5  405.25  4997.9  402.83  4998.4  402.03  5004.5  402.03  5005.0  402.83
  5012.1  406.51  5020.5  407.28  5086.8  405.98  5123.5  406.75  5167.7  408.35
  5252.9  414.57  5308.3  417.81  5313.6  417.41  5338.7  419.42  5363.7  420.22
  5369.1  419.63  5394.5  421.82  5399.4  421.11  5438.7  424.17  5503.4  425.59
#Mann=5,-1,0
  4337.2    0.05       0  4997.9    0.03       0  5005.0    0.05       0
  5123.5     0.1       0  5394.5    0.05       0
Bank Sta=4939.2,5167.7
Exp/Cntr=0.3,0.1

Type RM Length L Ch R = 1,13732,509,509,509
BEGIN DESCRIPTION:
CARTER CREEK 22.0
END DESCRIPTION:
XS GIS Cut Line= 3
      2919379.88      7013171.64      2919425.46      7013781.14
      2919758.35      7014258.41
#Sta/Elev= 30
  4388.8  422.22  4482.4  416.98  4521.0  413.24  4645.2  408.16  4773.2  405.81
  4960.4  406.06  4993.8  406.09  4999.4  401.66  5005.8  401.38  5006.3  400.58
  5012.4  400.58  5012.9  401.38  5016.9  405.85  5188.2  406.55  5218.1  408.16
  5361.0  420.77  5390.6  422.62  5405.5  423.25  5462.2  421.58  5494.4  421.62
  5497.9  422.15  5512.8  420.50  5518.9  421.29  5527.6  420.51  5533.7  421.63
  5548.5  419.67  5557.5  422.17  5563.4  422.95  5569.5  425.53  5581.9  426.88
#Mann=6,-1,0
  4388.8    0.05       0  4960.4    0.16       0  5005.8    0.07       0
  5012.9    0.16       0  5494.4    0.05       0  5557.5    0.16       0
Bank Sta=4645.2,5218.1
Exp/Cntr=0.3,0.1

Type RM Length L Ch R = 1,13223,586,586,586
BEGIN DESCRIPTION:
CARTER CREEK 21.0
END DESCRIPTION:
XS GIS Cut Line= 3
      2919174.99      7013125.03      2918975.00      7013575.00
      2918925.00      7014025.02
#Sta/Elev= 30
  4474.7  432.80  4627.9  427.13  4639.5  425.09  4657.3  424.46  4662.8  423.23
  4680.5  422.10  4761.2  412.40  4855.3  407.08  4877.5  406.60  4883.0  405.71
  4924.4  405.38  4945.2  405.65  4952.8  405.04  4958.2  402.98  4969.6  403.27
  4983.1  401.04  4983.8  400.24  4990.6  400.24  4991.3  401.04  4997.3  401.14
  5017.4  405.52  5087.9  405.10  5124.4  407.08  5148.2  409.09  5222.1  410.36
  5248.8  411.44  5289.1  415.18  5319.3  416.04  5359.5  421.01  5419.9  424.41
#Mann=5,-1,0
  4474.7    0.05       0  4924.4    0.16       0  4983.1    0.07       0
  4991.3    0.16       0  5222.1    0.05       0
Bank Sta=4855.3,5124.4
Exp/Cntr=0.3,0.1

Type RM Length L Ch R = 1,12637,496,496,496
BEGIN DESCRIPTION:
CARTER CREEK 20.0
END DESCRIPTION:
XS GIS Cut Line= 3
      2919074.99      7012975.01      2918575.00      7013275.00
      2918524.99      7013725.05
#Sta/Elev= 30
  4403.3  432.72  4453.8  430.53  4496.6  425.16  4506.3  423.32  4512.1  423.06
  4527.7  420.48  4564.6  416.52  4591.8  411.68  4622.9  408.72  4636.5  406.74
  4651.8  405.82  4694.8  404.32  4803.7  404.38  4862.0  403.87  4877.5  403.08
  4988.9  404.51  4992.3  402.02  4993.0  401.22  4999.8  401.22  5000.5  402.02
  5016.6  404.10  5056.8  403.97  5115.2  405.82  5157.4  409.00  5207.7  415.19
  5217.8  416.97  5308.4  422.74  5348.6  423.14  5409.0  425.03  5439.2  424.52
#Mann=3,-1,0
  4403.3    0.05       0  4992.3    0.03       0  5000.5    0.05       0
Bank Sta=4651.8,5115.2
Exp/Cntr=0.3,0.1

Type RM Length L Ch R = 1,12141,521,521,521
BEGIN DESCRIPTION:
CARTER CREEK 19.0
END DESCRIPTION:
XS GIS Cut Line= 3
      2918434.55      7012480.27      2918125.00      7013075.00
      2918403.30      7013698.98
#Sta/Elev= 30
  4299.4  423.31  4354.0  419.45  4392.6  419.23  4442.4  414.98  4663.8  405.26
  4740.6  403.19  4895.3  402.29  4915.9  403.04  4961.6  402.27  4972.6  401.52
  4974.6  399.37  4975.3  398.57  4982.8  399.37  5007.4  401.22  5013.7  402.98
  5024.6  401.99  5053.9  402.46  5098.8  405.26  5134.5  408.70  5204.2  413.01
  5227.4  415.98  5250.6  417.24  5303.2  417.49  5429.7  423.90  5506.4  424.93
  5561.1  423.71  5597.7  424.82  5620.9  424.34  5644.1  422.33  5653.1  423.02
#Mann=5,-1,0
  4299.4    0.05       0  4915.9    0.16       0  4974.6    0.07       0
  4982.8    0.16       0  5303.2    0.05       0
Bank Sta=4663.8,5098.8
Exp/Cntr=0.3,0.1

Type RM Length L Ch R = 1,11620,576,576,576
BEGIN DESCRIPTION:
CARTER CREEK 18.0
END DESCRIPTION:
XS GIS Cut Line= 3
      2917524.98      7012824.95      2917675.00      7013275.00
      2917475.01      7013724.97
#Sta/Elev= 30
  4550.0  431.60  4592.2  430.87  4602.8  429.67  4655.5  427.57  4666.0  426.40
  4782.0  421.85  4813.6  419.10  4824.1  416.69  4845.2  414.77  4853.3  413.14
  4887.4  408.05  4908.4  406.62  4924.6  404.61  4949.1  400.16  4957.3  399.64
  4999.1  399.50  4999.9  398.70  5006.8  398.70  5007.5  399.50  5061.9  399.77
  5079.1  400.60  5085.3  402.34  5183.8  403.88  5297.9  404.61  5352.0  409.46
  5363.6  412.05  5386.2  415.35  5404.0  415.75  5462.1  421.15  5516.8  422.24
#Mann=7,-1,0
  4550.0    0.05       0  4853.3    0.16       0  4949.1    0.05       0
  4957.3    0.16       0  4999.1    0.07       0  5007.5    0.16       0
  5061.9    0.05       0
Bank Sta=4924.6,5297.9
Exp/Cntr=0.3,0.1