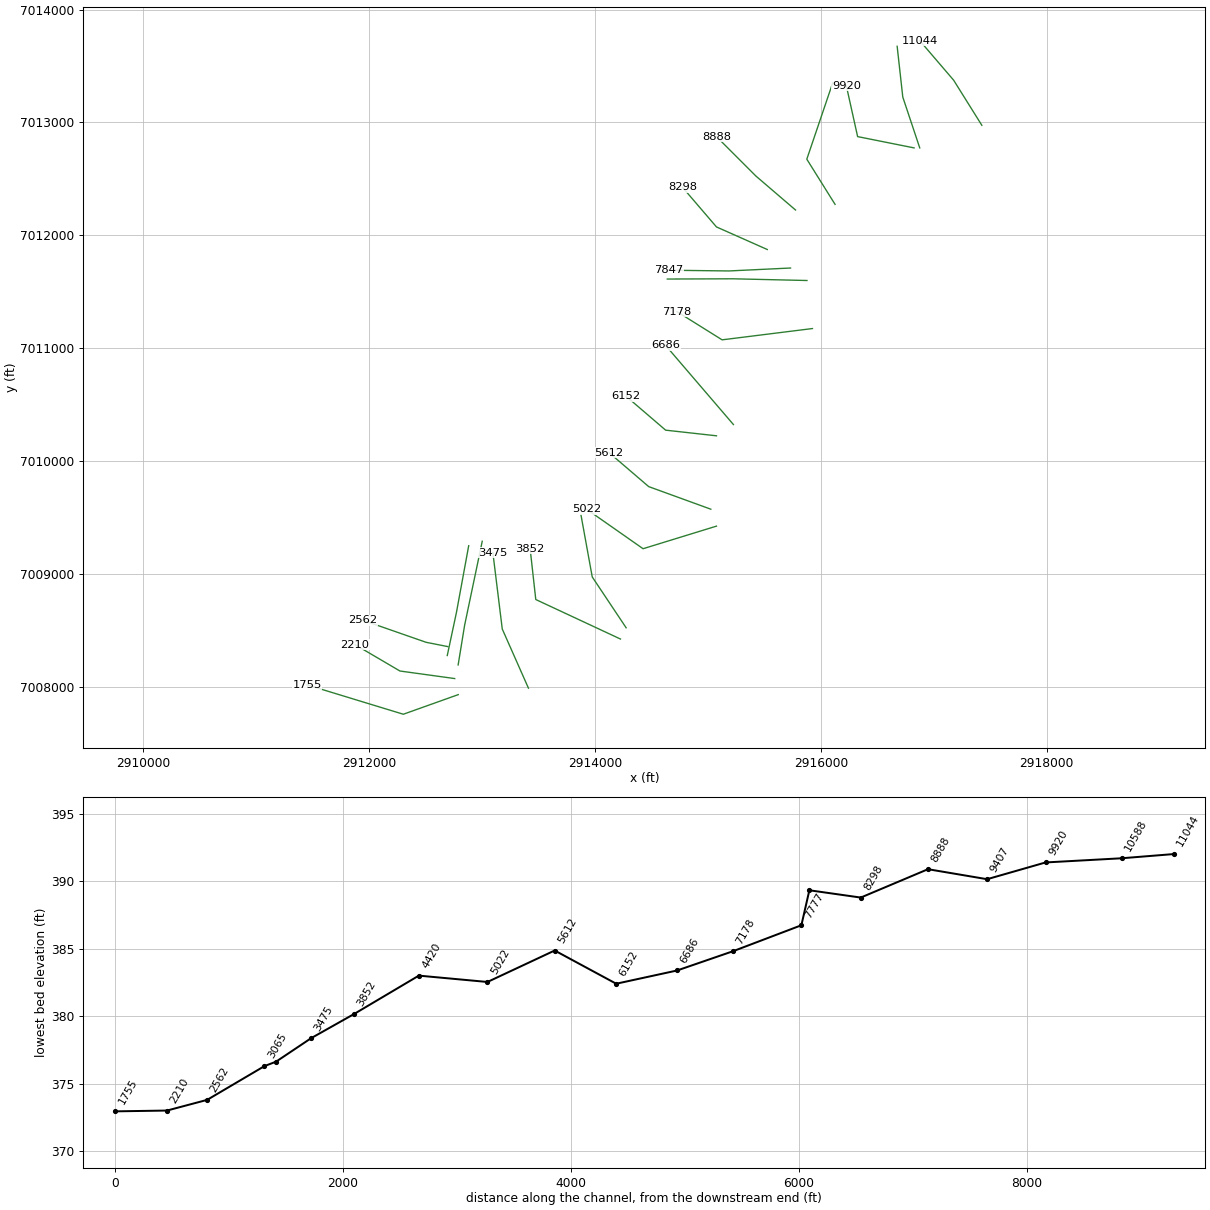
HEC-RAS study CARTER CREEK.prj: CARTER CREEK Base Level Engineering

--- CARTER CREEK.g01 (geometry) --- (continued)

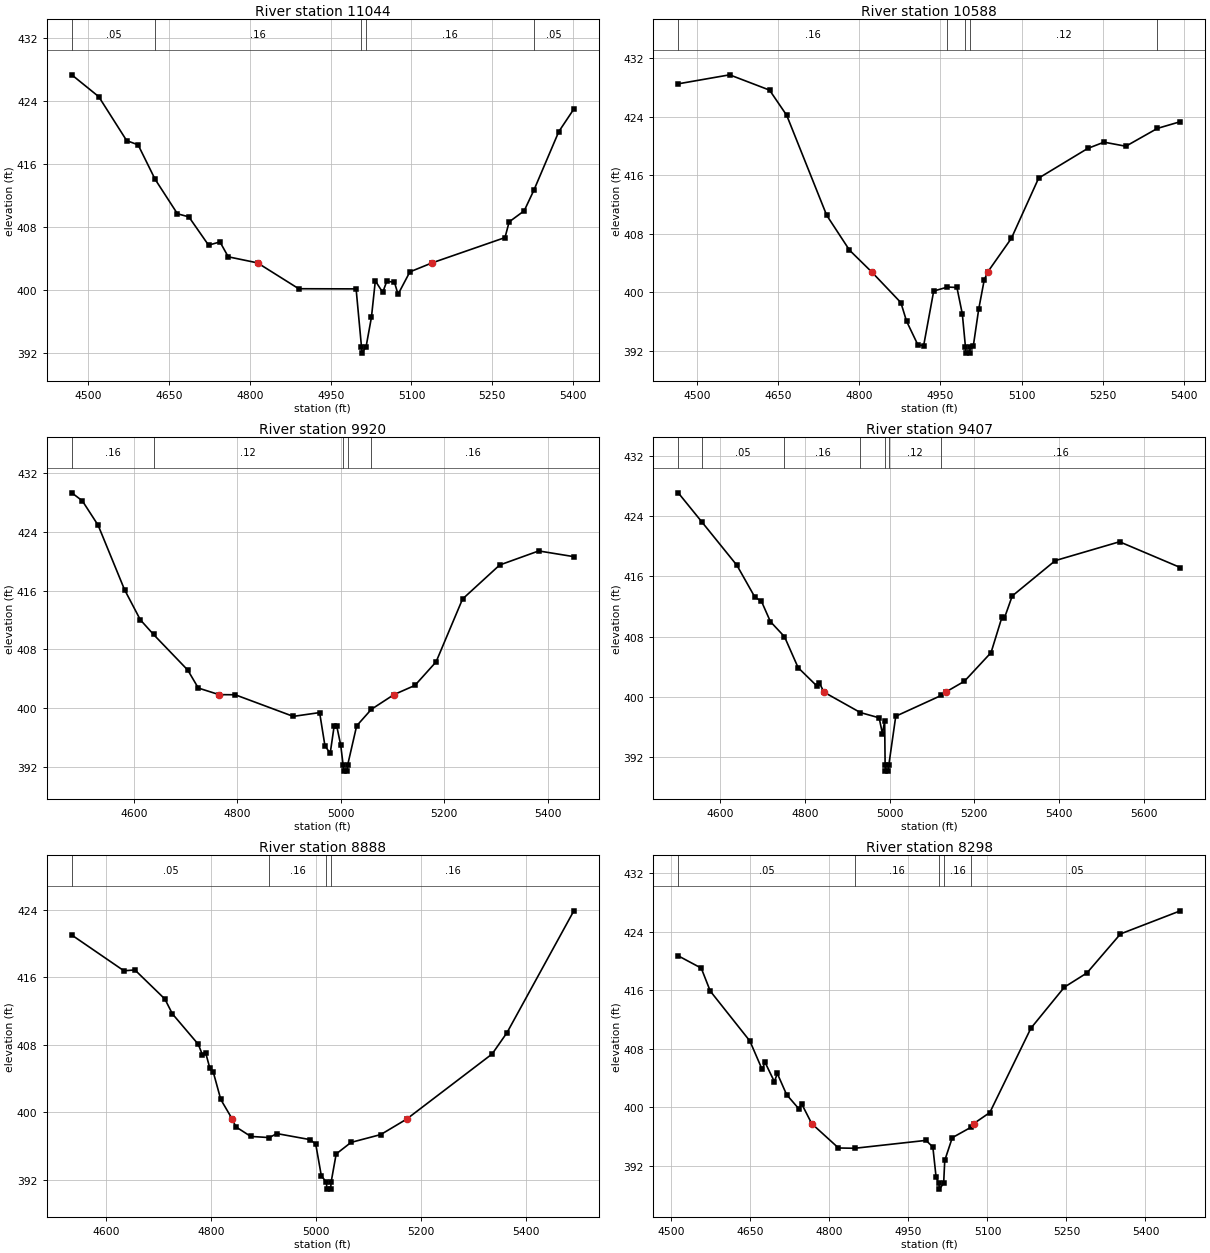
Type RM Length L Ch R = 1,11044,456,456,456
BEGIN DESCRIPTION:
CARTER CREEK 17.0
END DESCRIPTION:
XS GIS Cut Line= 3
      2917424.99      7012975.02      2917175.00      7013375.00
      2916874.97      7013725.04
#Sta/Elev= 30
  4469.0  427.31  4519.1  424.54  4571.0  418.96  4592.2  418.43  4623.7  414.07
  4665.3  409.68  4686.5  409.29  4723.1  405.70  4744.3  406.11  4759.7  404.22
  4814.1  403.45  4890.6  400.17  4997.2  400.15  5007.2  392.80  5008.0  392.00
  5015.7  392.80  5025.7  396.55  5032.9  401.17  5046.6  399.71  5054.3  401.13
  5068.5  400.98  5075.1  399.46  5097.1  402.31  5138.3  403.45  5273.8  406.66
  5281.5  408.65  5309.5  410.06  5327.5  412.68  5373.7  420.10  5401.7  422.97
#Mann=5,-1,0
  4469.0    0.05       0  4623.7    0.16       0  5007.2    0.07       0
  5015.7    0.16       0  5327.5    0.05       0
Bank Sta=4814.1,5138.3
Exp/Cntr=0.3,0.1

Type RM Length L Ch R = 1,10588,668,668,668
BEGIN DESCRIPTION:
CARTER CREEK 16.0
END DESCRIPTION:
XS GIS Cut Line= 3
      2916875.00      7012775.01      2916725.00      7013225.00
      2916675.00      7013675.00
#Sta/Elev= 30
  4465.9  428.53  4560.8  429.76  4634.5  427.67  4666.2  424.22  4740.0  410.55
  4782.1  405.78  4823.6  402.76  4877.0  398.60  4887.5  396.06  4908.6  392.79
  4919.1  392.73  4937.6  400.18  4963.1  400.73  4980.5  400.67  4990.5  397.04
  4996.3  392.49  4997.0  391.69  5004.1  391.69  5004.9  392.49  5010.7  392.64
  5020.7  397.69  5030.8  401.65  5037.1  402.76  5081.1  407.40  5131.4  415.63
  5222.0  419.69  5252.1  420.55  5292.4  419.99  5350.6  422.43  5393.0  423.35
#Mann=5,-1,0
  4465.9    0.16       0  4963.1    0.12       0  4996.3    0.07       0
  5004.9    0.12       0  5350.6    0.05       0
Bank Sta=4823.6,5037.1
Exp/Cntr=0.3,0.1

Type RM Length L Ch R = 1,9920,513,513,513
BEGIN DESCRIPTION:
CARTER CREEK 15.0
END DESCRIPTION:
XS GIS Cut Line= 3
      2916824.99      7012775.00      2916325.00      7012875.00
      2916224.99      7013325.03
#Sta/Elev= 30
  4480.0  429.36  4500.4  428.27  4531.0  424.93  4582.0  416.15  4612.6  412.03
  4638.1  410.03  4704.3  405.17  4724.7  402.72  4764.8  401.82  4796.1  401.80
  4908.3  398.85  4959.3  399.37  4969.5  394.87  4979.7  393.79  4987.3  397.49
  4992.5  397.49  5000.1  394.93  5004.8  392.18  5005.6  391.38  5012.7  391.38
  5013.4  392.18  5030.9  397.56  5059.4  399.82  5103.0  401.82  5143.6  403.08
  5184.5  406.29  5235.7  414.87  5307.5  419.51  5383.0  421.43  5450.9  420.65
#Mann=5,-1,0
  4480.0    0.16       0  4638.1    0.12       0  5004.8    0.07       0
  5013.4    0.12       0  5059.4    0.16       0
Bank Sta=4764.8,5103
Exp/Cntr=0.3,0.1

Type RM Length L Ch R = 1,9407,519,519,519
BEGIN DESCRIPTION:
CARTER CREEK 14.0
END DESCRIPTION:
XS GIS Cut Line= 3
      2916125.02      7012274.96      2915875.00      7012675.00
      2916104.40      7013350.89
#Sta/Elev= 30
  4500.9  427.10  4556.6  423.24  4639.5  417.47  4682.0  413.23  4697.3  412.71
  4718.5  410.00  4751.8  407.99  4784.0  403.88  4828.2  401.45  4834.1  401.86
  4845.0  400.63  4930.9  397.92  4975.3  397.22  4983.1  395.10  4988.3  396.85
  4989.4  390.94  4990.2  390.14  4997.3  390.14  4998.1  390.94  5014.5  397.43
  5121.8  400.19  5132.2  400.63  5176.7  402.08  5239.5  405.88  5265.6  410.65
  5270.9  410.44  5289.5  413.40  5391.2  418.10  5542.9  420.60  5686.4  417.18
#Mann=7,-1,0
  4500.9    0.16       0  4556.6    0.05       0  4751.8    0.16       0
  4930.9    0.12       0  4989.4    0.07       0  4998.1    0.12       0
  5121.8    0.16       0
Bank Sta=4845,5132.2
Exp/Cntr=0.3,0.1

Type RM Length L Ch R = 1,8888,590,590,590
BEGIN DESCRIPTION:
CARTER CREEK 13.0
END DESCRIPTION:
XS GIS Cut Line= 3
      2915775.00      7012225.00      2915425.00      7012525.00
      2915075.03      7012874.97
#Sta/Elev= 30
  4534.4  421.01  4633.7  416.77  4654.6  416.87  4711.7  413.42  4725.9  411.67
  4775.3  408.05  4783.0  406.83  4789.6  406.98  4797.3  405.21  4803.8  404.76
  4818.1  401.51  4840.0  399.18  4846.7  398.27  4875.2  397.13  4910.7  396.99
  4924.6  397.47  4988.2  396.75  4998.9  396.21  5009.5  392.47  5019.3  391.68
  5020.1  390.88  5027.3  390.88  5028.1  391.68  5037.8  395.05  5066.1  396.42
  5122.7  397.35  5171.9  399.18  5334.8  406.91  5363.1  409.44  5490.3  423.88
#Mann=4,-1,0
  4534.4    0.05       0  4910.7    0.16       0  5019.3    0.07       0
  5028.1    0.16       0
Bank Sta=4840,5171.9
Exp/Cntr=0.3,0.1

Type RM Length L Ch R = 1,8298,451,451,451
BEGIN DESCRIPTION:
CARTER CREEK 12.0
END DESCRIPTION:
XS GIS Cut Line= 3
      2915524.98      7011875.01      2915075.00      7012075.00
      2914775.00      7012425.00
#Sta/Elev= 30
  4512.8  420.70  4556.5  419.02  4573.6  415.88  4648.9  409.04  4672.1  405.16
  4677.6  406.13  4695.4  403.48  4700.9  404.61  4718.6  401.71  4741.9  399.76
  4747.4  400.42  4766.3  397.74  4817.1  394.41  4848.0  394.37  4983.3  395.45
  4996.3  394.54  5002.5  390.38  5007.9  389.58  5008.7  388.78  5016.8  389.58
  5018.9  392.71  5033.2  395.82  5069.4  397.27  5073.8  397.74  5104.5  399.26
  5182.5  410.80  5246.1  416.42  5288.9  418.36  5352.6  423.70  5466.2  426.86
#Mann=5,-1,0
  4512.8    0.05       0  4848.0    0.16       0  5007.9    0.07       0
  5016.8    0.16       0  5069.4    0.05       0
Bank Sta=4766.3,5073.8
Exp/Cntr=0.3,0.1

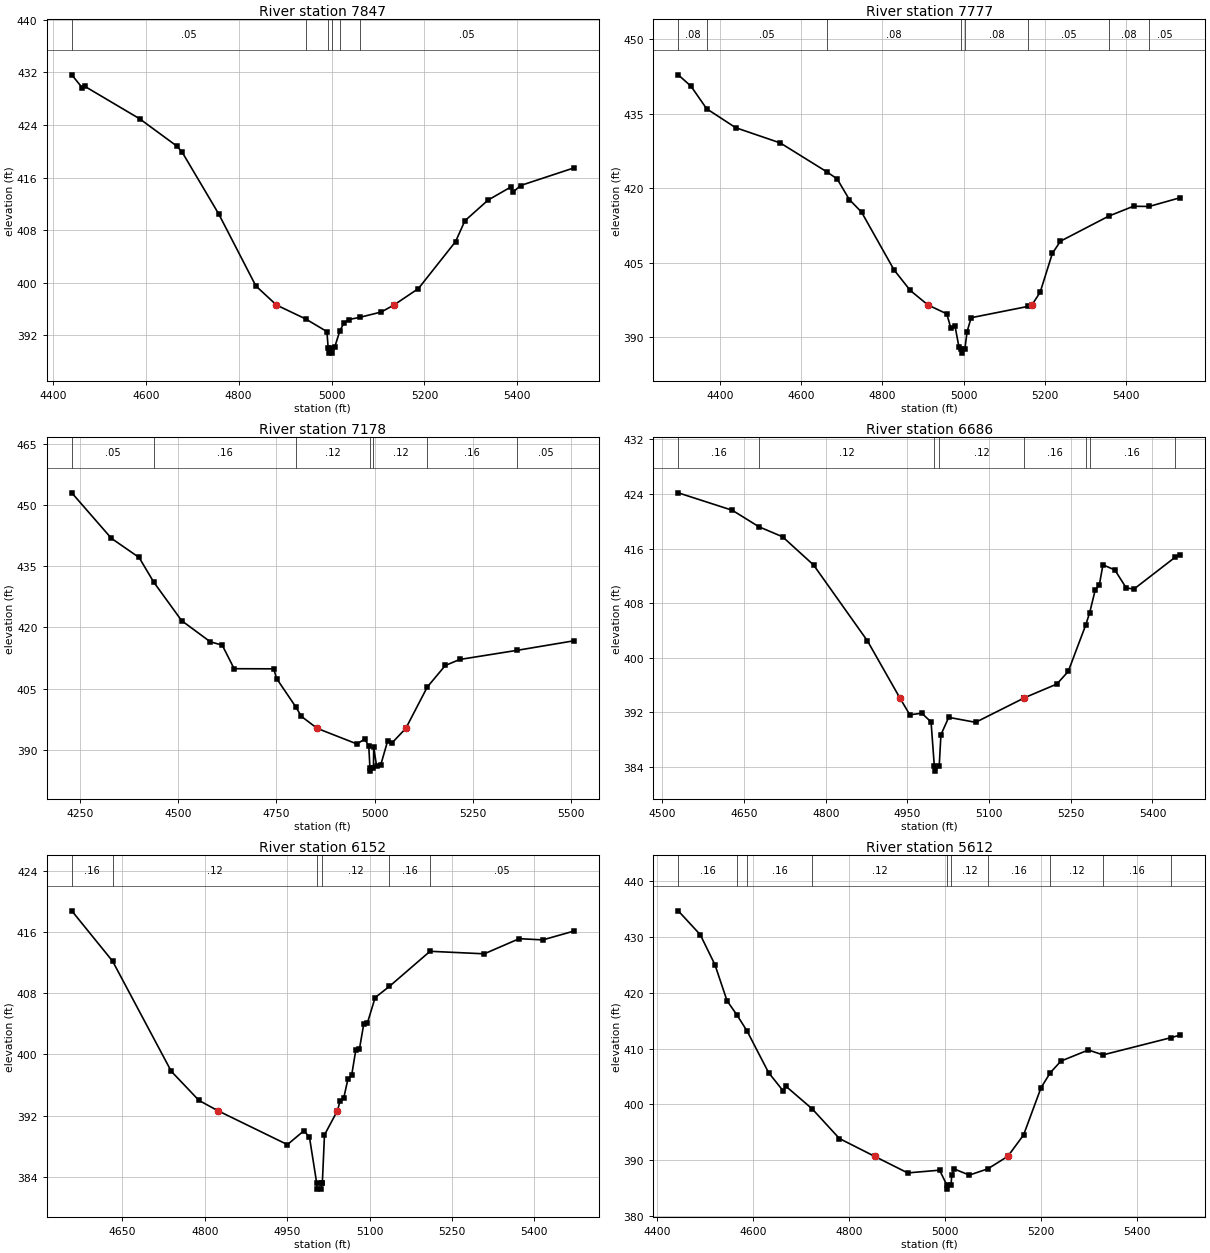
Type RM Length L Ch R = 1,7847,70,70,70
BEGIN DESCRIPTION:
Mapping XS f576bc4a
END DESCRIPTION:
XS GIS Cut Line= 3
      2915731.01      7011711.15      2915184.12      7011685.10
      2914650.27      7011691.61
#Sta/Elev= 30
  4440.5  431.61  4463.1  429.64  4468.1  429.88  4586.7  424.93  4666.8  420.78
  4678.3  419.85  4756.9  410.48  4837.0  399.53  4881.4  396.63  4944.4  394.51
  4990.1  392.59  4992.7  390.12  4993.5  389.32  5000.8  389.32  5001.6  390.12
  5007.1  390.29  5017.9  392.71  5027.1  393.94  5037.1  394.42  5061.6  394.77
  5107.1  395.57  5134.4  396.63  5187.1  399.13  5267.1  406.26  5287.2  409.43
  5337.2  412.58  5385.9  414.55  5390.9  413.78  5407.2  414.79  5521.9  417.46
#Mann=6,-1,0
  4440.5    0.05       0  4944.4    0.08       0  4992.7    0.07       0
  5001.6    0.08       0  5017.9    0.16       0  5061.6    0.05       0
Bank Sta=4881.4,5134.4
Exp/Cntr=0.3,0.1

Type RM Length L Ch R = 1,7777,599,599,599
BEGIN DESCRIPTION:
Mapping XS fb1bc556
END DESCRIPTION:
XS GIS Cut Line= 3
      2915876.44      7011600.47      2915221.02      7011615.66
      2914639.72      7011613.49
#Sta/Elev= 30
  4297.1  442.85  4328.5  440.56  4367.1  436.01  4438.6  432.19  4548.6  429.11
  4664.4  423.22  4688.6  421.86  4718.7  417.69  4748.7  415.16  4828.7  403.52
  4868.7  399.37  4912.1  396.45  4958.7  394.65  4968.7  391.76  4978.7  392.30
  4988.7  387.95  4994.3  387.53  4995.1  386.73  5003.2  387.53  5008.7  391.06
  5018.7  393.87  5159.9  396.17  5168.5  396.46  5188.7  399.00  5218.7  406.83
  5238.7  409.30  5357.9  414.37  5418.7  416.35  5457.0  416.30  5534.0  418.08
#Mann=8,-1,0
  4297.1    0.08       0  4367.1    0.05       0  4664.4    0.08       0
  4994.3    0.07       0  5003.2    0.08       0  5159.9    0.05       0
  5357.9    0.08       0  5457.0    0.05       0
Bank Sta=4912.1,5168.5
Exp/Cntr=0.3,0.1

Type RM Length L Ch R = 1,7178,492,492,492
BEGIN DESCRIPTION:
CARTER CREEK 10.0
END DESCRIPTION:
XS GIS Cut Line= 3
      2915925.02      7011175.00      2915125.00      7011075.00
      2914725.04      7011324.98
#Sta/Elev= 30
  4229.4  452.96  4330.2  441.82  4400.7  437.13  4438.1  431.08  4509.1  421.65
  4582.1  416.47  4612.4  415.66  4642.6  409.89  4743.4  409.86  4750.9  407.46
  4799.5  400.55  4813.9  398.21  4854.1  395.28  4955.0  391.47  4975.2  392.65
  4985.3  390.97  4988.3  385.61  4989.2  384.81  4997.3  385.61  4997.9  390.60
  5005.4  385.97  5015.5  386.24  5033.1  392.10  5043.3  391.60  5079.6  395.28
  5134.4  405.42  5180.1  410.68  5216.7  412.15  5363.5  414.40  5507.3  416.72
#Mann=7,-1,0
  4229.4    0.05       0  4438.1    0.16       0  4799.5    0.12       0
  4988.3    0.07       0  4997.3    0.12       0  5134.4    0.16       0
  5363.5    0.05       0
Bank Sta=4854.1,5079.6
Exp/Cntr=0.3,0.1

Type RM Length L Ch R = 1,6686,534,534,534
BEGIN DESCRIPTION:
CARTER CREEK 9.0
END DESCRIPTION:
XS GIS Cut Line= 3
      2915225.03      7010324.97      2914925.00      7010675.00
      2914625.00      7011025.00
#Sta/Elev= 30
  4529.1  424.16  4628.5  421.60  4677.2  419.19  4720.7  417.72  4777.7  413.58
  4876.5  402.47  4936.4  394.06  4954.4  391.63  4976.4  391.87  4993.4  390.58
  4999.3  384.18  5000.1  383.38  5008.4  384.18  5011.5  388.71  5025.8  391.26
  5075.2  390.53  5163.3  394.06  5164.2  394.11  5224.4  396.14  5245.3  397.99
  5277.3  404.77  5284.7  406.61  5294.7  409.88  5302.4  410.66  5309.0  413.61
  5330.9  412.86  5351.8  410.22  5366.0  410.06  5441.1  414.69  5451.1  415.10
#Mann=8,-1,0
  4529.1    0.16       0  4677.2    0.12       0  4999.3    0.07       0
  5008.4    0.12       0  5164.2    0.16       0  5277.3    0.12       0
  5284.7    0.16       0  5441.1    0.05       0
Bank Sta=4936.4,5163.3
Exp/Cntr=0.3,0.1

Type RM Length L Ch R = 1,6152,540,540,540
BEGIN DESCRIPTION:
CARTER CREEK 8.0
END DESCRIPTION:
XS GIS Cut Line= 3
      2915074.96      7010225.00      2914625.00      7010275.00
      2914275.01      7010574.99
#Sta/Elev= 30
  4558.1  418.78  4632.4  412.20  4739.2  397.80  4789.5  394.00  4823.7  392.66
  4950.5  388.22  4980.6  390.03  4990.7  389.18  5003.8  383.20  5004.6  382.40
  5012.0  382.40  5012.9  383.20  5014.1  383.20  5018.0  389.49  5041.6  392.66
  5046.5  393.97  5053.1  394.33  5060.8  396.83  5067.4  397.26  5075.0  400.59
  5081.6  400.70  5089.3  403.93  5095.9  404.07  5110.2  407.44  5136.1  408.90
  5210.1  413.49  5308.8  413.16  5372.5  415.14  5415.3  414.98  5471.8  416.13
#Mann=6,-1,0
  4558.1    0.16       0  4632.4    0.12       0  5003.8    0.07       0
  5012.9    0.12       0  5136.1    0.16       0  5210.1    0.05       0
Bank Sta=4823.7,5041.6
Exp/Cntr=0.3,0.1

Type RM Length L Ch R = 1,5612,590,590,590
BEGIN DESCRIPTION:
CARTER CREEK 7.0
END DESCRIPTION:
XS GIS Cut Line= 3
      2915024.96      7009575.01      2914475.00      7009775.00
      2914124.98      7010075.02
#Sta/Elev= 30
  4443.4  434.64  4489.2  430.38  4519.8  425.02  4545.1  418.55  4566.3  415.94
  4587.2  413.08  4631.6  405.71  4662.2  402.41  4667.5  403.28  4722.6  399.21
  4779.2  393.91  4852.5  390.73  4921.5  387.76  4988.0  388.25  5002.7  385.66
  5003.6  384.86  5011.9  385.66  5013.3  387.30  5018.6  388.46  5050.0  387.37
  5088.5  388.49  5130.2  390.73  5163.0  394.55  5199.3  402.98  5218.7  405.69
  5241.0  407.77  5298.0  409.75  5328.5  408.87  5470.1  411.95  5489.6  412.42
#Mann=10,-1,0
  4443.4    0.16       0  4566.3    0.12       0  4587.2    0.16       0
  4722.6    0.12       0  5002.7    0.07       0  5011.9    0.12       0
  5088.5    0.16       0  5218.7    0.12       0  5328.5    0.16       0
  5470.1    0.05       0
Bank Sta=4852.5,5130.2
Exp/Cntr=0.3,0.1

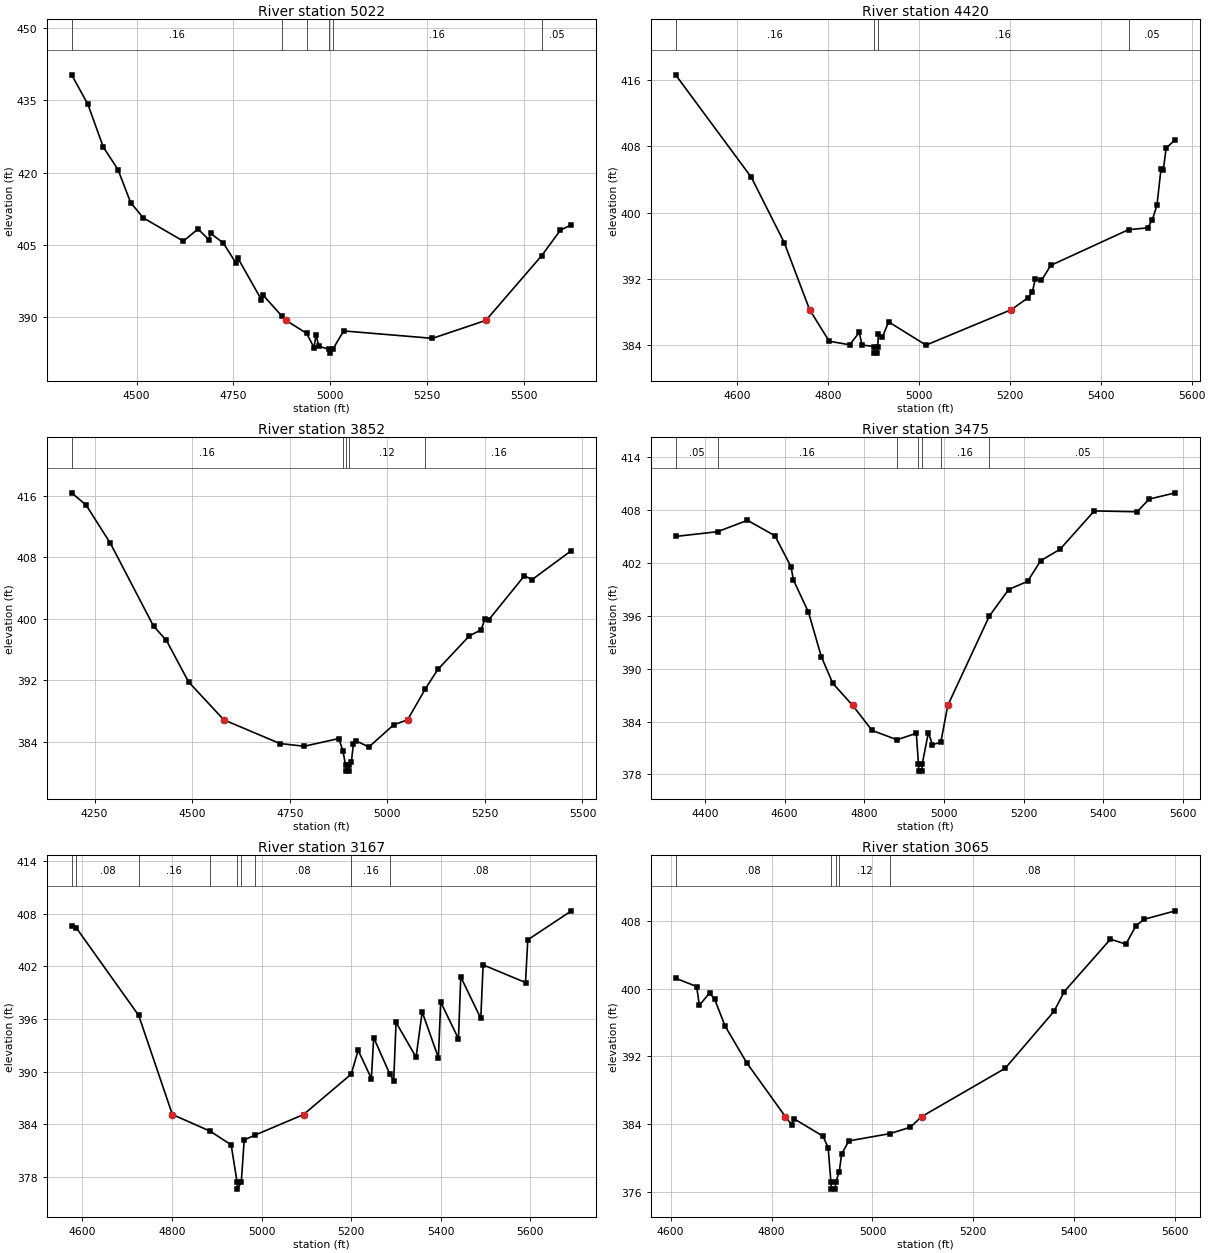
Type RM Length L Ch R = 1,5022,602,602,602
BEGIN DESCRIPTION:
CARTER CREEK 6.0
END DESCRIPTION:
XS GIS Cut Line= 3
      2915074.96      7009424.99      2914425.00      7009225.00
      2913924.96      7009575.03
#Sta/Elev= 30
  4332.4  440.31  4374.2  434.20  4414.1  425.31  4452.0  420.64  4484.7  413.78
  4517.4  410.61  4620.7  405.78  4658.7  408.30  4686.1  406.12  4691.4  407.38
  4724.0  405.39  4756.7  401.21  4762.0  402.20  4822.1  393.65  4827.4  394.51
  4874.7  390.26  4885.8  389.33  4939.1  386.63  4958.2  383.66  4963.4  386.36
  4970.6  383.94  4997.4  383.33  4998.2  382.53  5006.6  383.33  5034.7  387.14
  5264.0  385.60  5401.8  389.33  5545.6  402.73  5594.4  408.07  5622.8  409.17
#Mann=6,-1,0
  4332.4    0.16       0  4874.7    0.12       0  4939.1    0.16       0
  4997.4    0.07       0  5006.6    0.16       0  5545.6    0.05       0
Bank Sta=4885.8,5401.8
Exp/Cntr=0.3,0.1

Type RM Length L Ch R = 1,4420,568,568,568
BEGIN DESCRIPTION:
CARTER CREEK 5.0
END DESCRIPTION:
XS GIS Cut Line= 3
      2914275.00      7008525.00      2913975.00      7008975.00
      2913875.01      7009524.96
#Sta/Elev= 30
  4464.5  416.66  4631.3  404.25  4703.4  396.38  4759.4  388.25  4802.5  384.44
  4847.6  384.01  4868.6  385.51  4874.6  383.99  4900.0  383.80  4900.9  383.00
  4908.4  383.00  4909.3  383.80  4910.7  385.33  4919.7  384.96  4933.2  386.78
  5015.5  383.97  5203.0  388.25  5239.1  389.66  5249.3  390.34  5255.6  391.91
  5269.6  391.79  5289.9  393.61  5461.1  397.93  5503.4  398.15  5513.5  399.13
  5523.7  400.88  5532.6  405.29  5537.7  405.17  5544.0  407.81  5564.3  408.82
#Mann=4,-1,0
  4464.5    0.16       0  4900.0    0.07       0  4909.3    0.16       0
  5461.1    0.05       0
Bank Sta=4759.4,5203
Exp/Cntr=0.3,0.1

Type RM Length L Ch R = 1,3852,377,377,377
BEGIN DESCRIPTION:
CARTER CREEK 4.0
END DESCRIPTION:
XS GIS Cut Line= 3
      2914225.01      7008424.99      2913475.00      7008775.00
      2913425.00      7009224.97
#Sta/Elev= 30
  4191.3  416.40  4228.4  414.80  4290.6  409.82  4401.0  399.05  4434.1  397.18
  4490.8  391.78  4581.1  386.84  4724.9  383.75  4787.2  383.40  4875.5  384.40
  4886.2  382.82  4892.9  380.96  4893.8  380.16  4901.4  380.16  4902.2  380.96
  4907.8  381.33  4913.3  383.75  4919.6  384.11  4952.7  383.30  5016.2  386.19
  5051.9  386.84  5097.6  390.89  5129.6  393.41  5210.1  397.77  5240.3  398.56
  5250.4  400.03  5260.4  399.90  5351.0  405.59  5371.1  405.11  5471.7  408.88
#Mann=5,-1,0
  4191.3    0.16       0  4886.2    0.12       0  4892.9    0.07       0
  4902.2    0.12       0  5097.6    0.16       0
Bank Sta=4581.1,5051.9
Exp/Cntr=0.3,0.1

Type RM Length L Ch R = 1,3475,308,308,308
BEGIN DESCRIPTION:
Mapping XS cfbaf946
END DESCRIPTION:
XS GIS Cut Line= 3
      2913410.00      7007990.17      2913178.22      7008513.63
      2913094.93      7009190.35
#Sta/Elev= 30
  4326.7  405.00  4431.9  405.54  4507.0  406.83  4575.9  405.08  4616.3  401.56
  4622.4  400.05  4660.1  396.41  4692.3  391.37  4721.1  388.34  4771.2  385.82
  4819.7  382.99  4882.3  381.93  4930.8  382.66  4936.2  379.17  4937.1  378.37
  4944.7  378.37  4945.6  379.17  4961.0  382.74  4971.3  381.37  4992.3  381.65
  5009.7  385.82  5113.9  395.95  5162.5  398.98  5210.0  399.90  5243.1  402.26
  5291.2  403.53  5377.5  407.90  5484.9  407.80  5515.2  409.24  5581.0  409.95
#Mann=7,-1,0
  4326.7    0.05       0  4431.9    0.16       0  4882.3    0.12       0
  4936.2    0.07       0  4945.6    0.12       0  4992.3    0.16       0
  5113.9    0.05       0
Bank Sta=4771.2,5009.7
Exp/Cntr=0.3,0.1

Type RM Length L Ch R = 1,3167,102,102,102
BEGIN DESCRIPTION:
Mapping XS d70170c3
END DESCRIPTION:
XS GIS Cut Line= 3
      2912787.59      7008195.89      2912844.89      7008547.49
      2913000.90      7009291.16
#Sta/Elev= 30
  4575.9  406.59  4586.0  406.42  4725.6  396.42  4800.8  385.13  4884.5  383.25
  4932.1  381.68  4945.3  377.43  4946.2  376.63  4954.7  377.43  4961.2  382.23
  4984.6  382.77  5093.8  385.13  5200.1  389.73  5215.7  392.45  5245.2  389.23
  5250.4  393.89  5286.0  389.78  5295.1  388.99  5300.3  395.63  5345.0  391.66
  5358.7  396.82  5394.9  391.61  5400.0  397.95  5439.7  393.75  5444.8  400.81
  5489.6  396.08  5494.7  402.18  5589.4  400.17  5594.5  405.04  5692.0  408.34
#Mann=9,-1,0
  4575.9    0.05       0  4586.0    0.08       0  4725.6    0.16       0
  4884.5    0.05       0  4945.3    0.07       0  4954.7    0.05       0
  4984.6    0.08       0  5200.1    0.16       0  5286.0    0.08       0
Bank Sta=4800.8,5093.8
Exp/Cntr=0.3,0.1

Type RM Length L Ch R = 1,3065,503,503,503
BEGIN DESCRIPTION:
CARTER CREEK 3.0
END DESCRIPTION:
XS GIS Cut Line= 3
      2912691.24      7008279.26      2912772.51      7008660.90
      2912881.05      7009251.61
#Sta/Elev= 30
  4609.8  401.23  4651.6  400.25  4656.8  398.02  4677.0  399.48  4687.2  398.75
  4707.7  395.60  4750.8  391.23  4827.4  384.87  4839.7  383.92  4844.8  384.61
  4901.9  382.56  4912.2  381.21  4917.7  377.10  4918.6  376.30  4926.2  376.30
  4927.1  377.10  4934.2  378.33  4938.8  380.42  4953.1  382.00  5034.5  382.86
  5075.3  383.62  5097.5  384.87  5263.1  390.58  5360.0  397.32  5380.4  399.66
  5471.9  405.85  5502.4  405.26  5522.7  407.46  5538.7  408.20  5600.6  409.20
#Mann=5,-1,0
  4609.8    0.08       0  4917.7    0.07       0  4927.1    0.08       0
  4934.2    0.12       0  5034.5    0.08       0
Bank Sta=4827.4,5097.5
Exp/Cntr=0.3,0.1

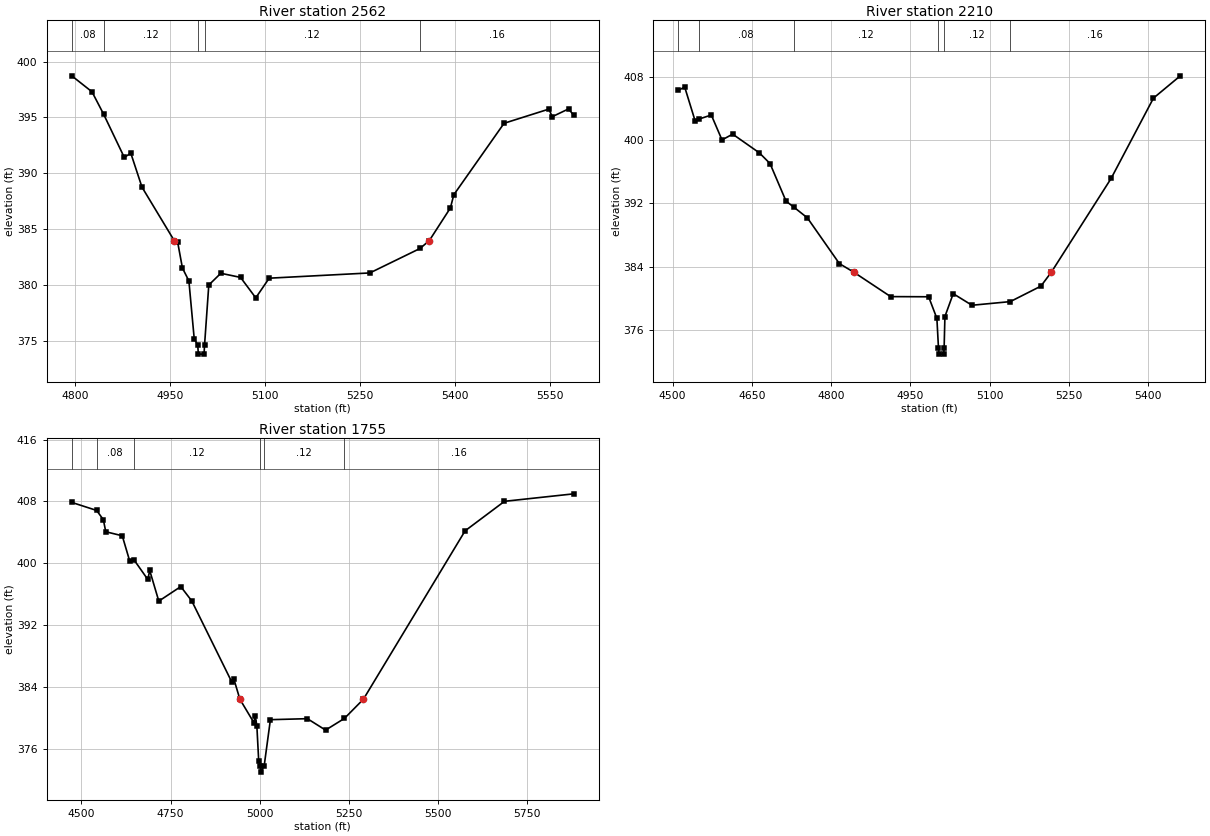
Type RM Length L Ch R = 1,2562,352,352,352
BEGIN DESCRIPTION:
Mapping XS f13dd043
END DESCRIPTION:
XS GIS Cut Line= 3
      2912696.31      7008357.98      2912503.62      7008396.17
      2911941.09      7008592.36
#Sta/Elev= 30
  4795.3  398.72  4827.2  397.29  4845.6  395.28  4878.2  391.41  4888.4  391.80
  4906.1  388.75  4956.9  383.97  4962.4  383.82  4969.9  381.51  4980.1  380.35
  4988.5  375.18  4994.1  374.60  4995.0  373.80  5004.0  373.80  5004.8  374.60
  5011.5  379.99  5030.5  381.04  5061.6  380.67  5085.6  378.84  5106.8  380.60
  5265.6  381.07  5344.8  383.26  5359.5  383.97  5392.7  386.89  5398.1  388.07
  5477.4  394.47  5548.1  395.74  5553.4  395.06  5579.2  395.76  5587.5  395.17
#Mann=5,-1,0
  4795.3    0.08       0  4845.6    0.12       0  4994.1    0.07       0
  5004.8    0.12       0  5344.8    0.16       0
Bank Sta=4956.9,5359.5
Exp/Cntr=0.3,0.1

Type RM Length L Ch R = 1,2210,455,455,455
BEGIN DESCRIPTION:
CARTER CREEK 2.0
END DESCRIPTION:
XS GIS Cut Line= 3
      2912757.05      7008074.99      2912272.23      7008141.81
      2911875.02      7008374.99
#Sta/Elev= 30
  4510.6  406.25  4522.8  406.68  4542.6  402.40  4549.3  402.63  4573.2  403.15
  4593.4  400.01  4613.6  400.74  4664.1  398.38  4684.3  397.03  4714.6  392.29
  4729.1  391.55  4754.9  390.19  4815.5  384.42  4842.3  383.36  4912.5  380.26
  4984.4  380.24  5000.0  377.51  5003.0  373.81  5003.9  373.01  5012.9  373.01
  5013.7  373.81  5015.2  377.75  5030.9  380.63  5066.4  379.17  5138.9  379.63
  5196.8  381.58  5216.8  383.36  5329.7  395.16  5409.8  405.28  5460.6  408.09
#Mann=6,-1,0
  4510.6    0.16       0  4549.3    0.08       0  4729.1    0.12       0
  5003.0    0.07       0  5013.7    0.12       0  5138.9    0.16       0
Bank Sta=4842.3,5216.8
Exp/Cntr=0.3,0.1

Type RM Length L Ch R = 1,1755,699,699,699
BEGIN DESCRIPTION:
Mapping XS 7450d00e
END DESCRIPTION:
XS GIS Cut Line= 3
      2912788.35      7007932.63      2912302.23      7007759.01
      2911449.00      7008019.15
#Sta/Elev= 30
  4472.8  407.87  4542.5  406.83  4561.3  405.64  4568.2  404.07  4614.4  403.55
  4635.6  400.23  4646.8  400.47  4686.1  397.89  4691.4  399.06  4716.9  395.09
  4778.5  396.97  4809.3  395.12  4921.8  384.60  4927.1  385.05  4944.3  382.39
  4983.4  379.37  4987.5  380.21  4991.9  378.95  4997.1  374.41  5001.7  373.75
  5002.5  372.95  5012.4  373.75  5029.9  379.74  5133.6  379.87  5184.7  378.39
  5237.7  379.91  5290.8  382.39  5576.0  404.19  5686.5  408.01  5881.0  408.98
#Mann=6,-1,0
  4472.8    0.16       0  4542.5    0.08       0  4646.8    0.12       0
  5001.7    0.07       0  5012.4    0.12       0  5237.7    0.16       0
Bank Sta=4944.3,5290.8
Exp/Cntr=0.3,0.1