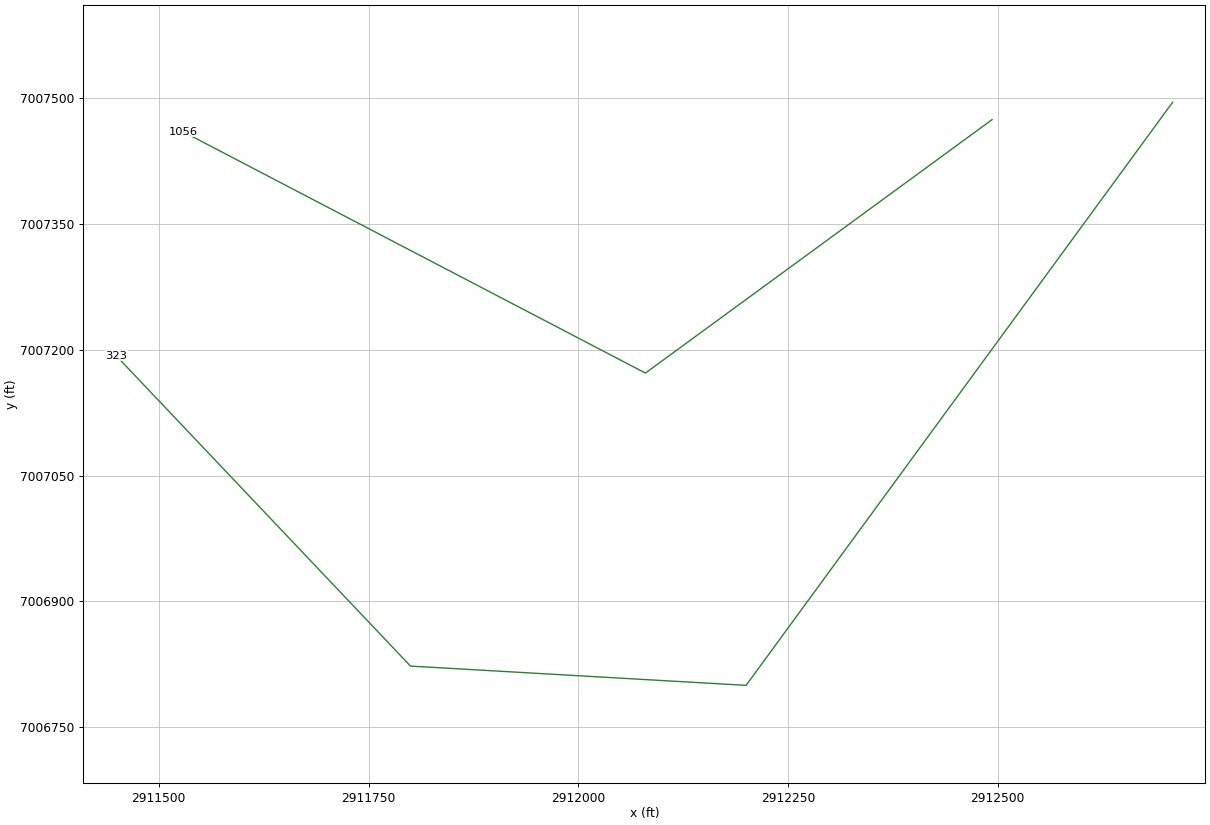
HEC-RAS study CARTER CREEK.prj: CARTER CREEK Base Level Engineering

--- CARTER CREEK.g01 (geometry) --- (continued)

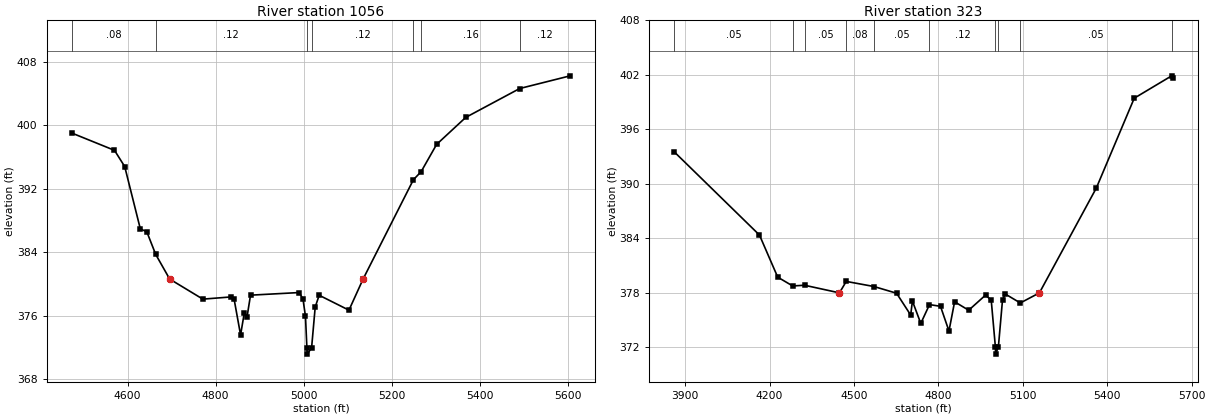
Type RM Length L Ch R = 1,1056,733,733,733
BEGIN DESCRIPTION:
Mapping XS 9a5a6998
END DESCRIPTION:
XS GIS Cut Line= 3
      2912493.20      7007474.29      2912080.01      7007172.21
      2911529.36      7007459.65
#Sta/Elev= 30
  4472.7  399.03  4570.2  396.84  4593.4  394.80  4628.9  386.94  4643.6  386.58
  4663.8  383.73  4695.6  380.62  4771.0  378.09  4835.8  378.37  4842.1  378.06
  4856.7  373.58  4865.2  376.36  4871.4  375.85  4879.3  378.59  4990.2  378.92
  4998.6  378.07  5004.2  375.91  5007.4  371.96  5008.2  371.16  5018.1  371.96
  5026.3  377.09  5035.3  378.58  5103.0  376.70  5135.1  380.62  5249.5  393.14
  5267.0  394.15  5302.2  397.59  5368.4  400.99  5491.0  404.63  5605.7  406.23
#Mann=7,-1,0
  4472.7    0.08       0  4663.8    0.12       0  5007.4    0.07       0
  5018.1    0.12       0  5249.5    0.05       0  5267.0    0.16       0
  5491.0    0.12       0
Bank Sta=4695.6,5135.1
Exp/Cntr=0.3,0.1

Type RM Length L Ch R = 1,323,0,0,0
BEGIN DESCRIPTION:
CARTER CREEK 1.0
END DESCRIPTION:
XS GIS Cut Line= 4
      2912708.45      7007495.09      2912200.00      7006800.00
      2911800.00      7006822.96      2911449.17      7007192.90
#Sta/Elev= 30
  3861.2  393.52  4164.2  384.36  4229.0  379.73  4282.3  378.76  4324.3  378.84
  4448.4  378.00  4472.5  379.26  4570.9  378.70  4651.4  377.96  4701.5  375.56
  4707.7  377.10  4737.4  374.64  4768.4  376.71  4807.5  376.52  4837.6  373.80
  4857.6  377.02  4907.7  376.09  4967.8  377.76  4987.8  377.18  5002.5  372.06
  5003.3  371.26  5013.2  372.06  5027.9  377.24  5037.9  377.87  5091.1  376.89
  5159.0  378.00  5361.3  389.54  5496.0  399.42  5629.0  401.88  5632.9  401.69
#Mann=10,-1,0
  3861.2    0.05       0  4282.3    0.08       0  4324.3    0.05       0
  4472.5    0.08       0  4570.9    0.05       0  4768.4    0.12       0
  5002.5    0.07       0  5013.2    0.12       0  5091.1    0.05       0
  5629.0    0.12       0
Bank Sta=4448.4,5159
Exp/Cntr=0.3,0.1

Chan Stop Cuts=-1