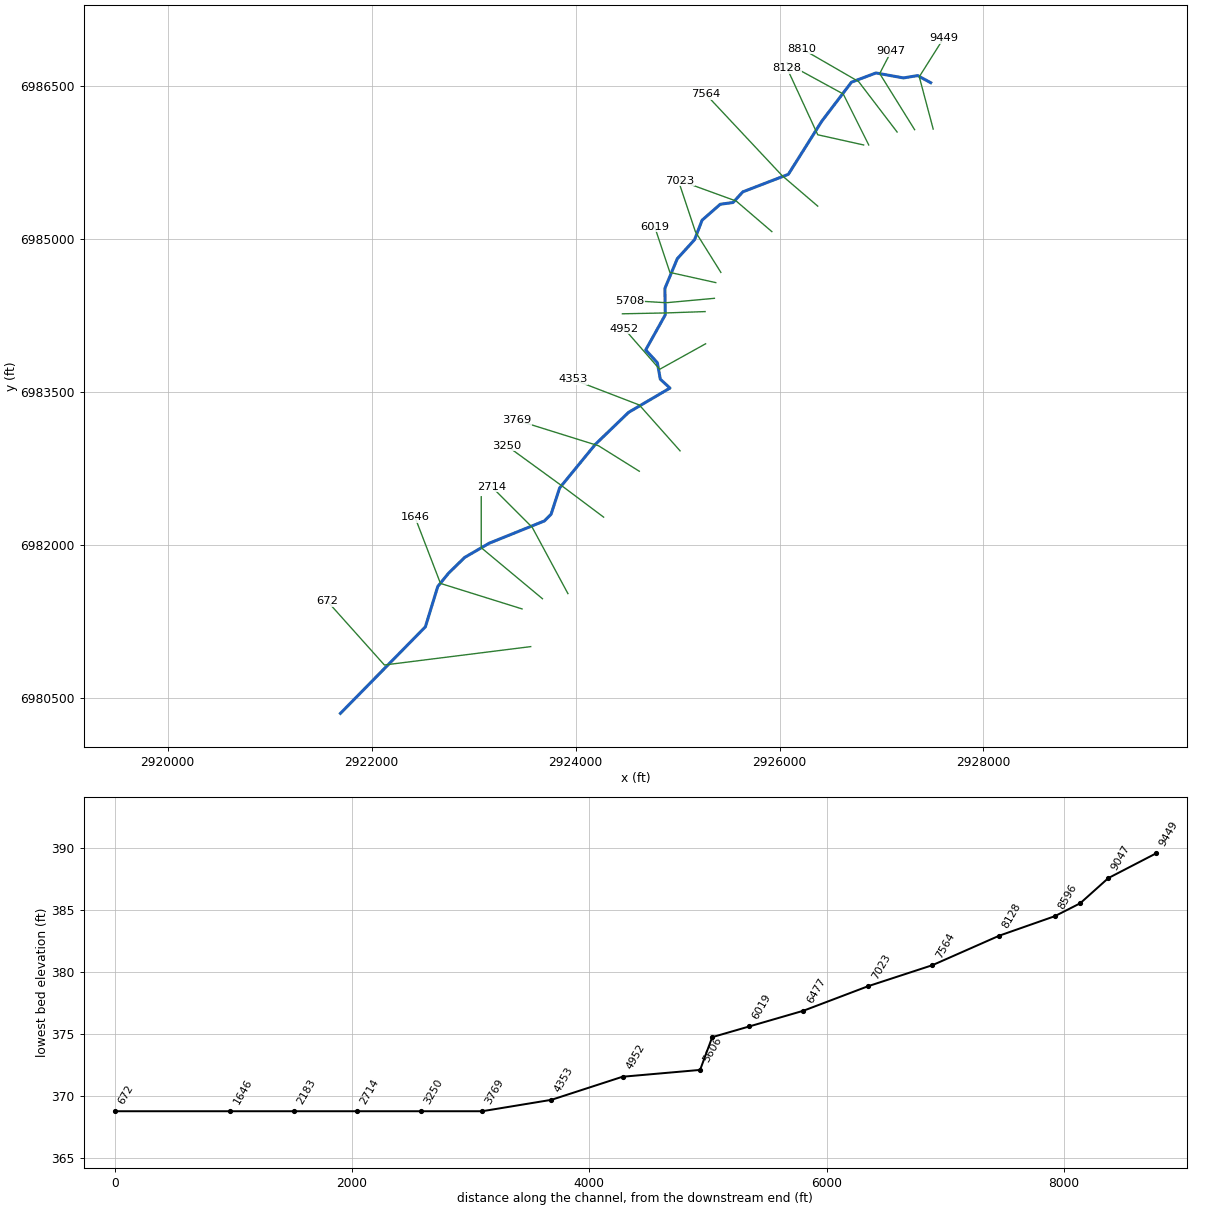
--- CHINQUANPIA BRANCH.prj (project) ---

Proj Title=CHINQUANPIA BRANCH Base Level Engineering
Current Plan=p01
Default Exp/Contr=0.3,0.1
English Units
Geom File=g01
Flow File=f01
Plan File=p01
BEGIN DESCRIPTION:
CHINQUANPIA BRANCH
END DESCRIPTION:

--- CHINQUANPIA BRANCH.p01 (plan) ---

Plan Title=Multiple Run
Short Identifier=Multiple
Geom File=g01
Flow File=f01
Subcritical Flow
K Sum by GR= 0
Std Step Tol= 0.01
Critical Tol= 0.01
Num of Std Step Trials= 20
Max Error Tol= 0.3
Flow Tol Ratio= 0.001
Split Flow NTrial= 30
Split Flow Tol= 0.02
Split Flow Ratio= 0.02
Log Output Level= 0
Friction Slope Method= 1
Unsteady Friction Slope Method= 2
Unsteady Bridges Friction Slope Method= 1
Parabolic Critical Depth
Global Vel Dist=  1 , 1 , 1
Global Log Level= 0
CheckData=True
Encroach Param= -1, 0, 0, 0
BEGIN DESCRIPTION:
Multiple Run
END DESCRIPTION:

--- CHINQUANPIA BRANCH.f01 (steady flow) ---

Flow Title=Multiple
Number of Profiles=7
Profile Names=10-year,25-year,50-year,1pct_min,100-year,1pct_plu,500-year
River Rch & RM= CHINQUANPIA BRAN,Reach-1,9449
     505     675     813     488     974    1944    1398
River Rch & RM= CHINQUANPIA BRAN,Reach-1,8810
     892    1229    1511     923    1841    3673    2738
River Rch & RM= CHINQUANPIA BRAN,Reach-1,3769
    1086    1504    1855    1136    2266    4521    3386
Boundary for River Rch & Prof#=CHINQUANPIA BRAN,Reach-1,1
Up Type=0
Dn Type=3
Dn Slope=0.005
Boundary for River Rch & Prof#=CHINQUANPIA BRAN,Reach-1,2
Up Type=0
Dn Type=3
Dn Slope=0.005
Boundary for River Rch & Prof#=CHINQUANPIA BRAN,Reach-1,3
Up Type=0
Dn Type=3
Dn Slope=0.005
Boundary for River Rch & Prof#=CHINQUANPIA BRAN,Reach-1,4
Up Type=0
Dn Type=3
Dn Slope=0.005
Boundary for River Rch & Prof#=CHINQUANPIA BRAN,Reach-1,5
Up Type=0
Dn Type=3
Dn Slope=0.005
Boundary for River Rch & Prof#=CHINQUANPIA BRAN,Reach-1,6
Up Type=0
Dn Type=3
Dn Slope=0.005
Boundary for River Rch & Prof#=CHINQUANPIA BRAN,Reach-1,7
Up Type=0
Dn Type=3
Dn Slope=0.005

--- CHINQUANPIA BRANCH.g01 (geometry) ---

Geom Title=Existing Conditions

River Reach=CHINQUANPIA BRAN,Reach-1
Reach XY= 30
      2927482.43      6986535.65      2927354.59      6986605.39
      2927215.94      6986582.37      2926945.38      6986631.08
      2926705.59      6986540.71      2926413.72      6986156.84
      2926086.64      6985636.97      2925639.93      6985464.89
      2925544.44      6985360.73      2925418.57      6985343.36
      2925240.62      6985187.11      2925166.84      6984996.14
      2924997.57      6984809.51      2924876.04      6984518.71
      2924879.46      6984258.53      2924687.62      6983914.51
      2924802.13      6983789.36      2924830.90      6983627.93
      2924925.59      6983540.71      2924519.57      6983302.47
      2924193.35      6982988.20      2923843.16      6982560.59
      2923759.83      6982303.65      2923693.86      6982237.68
      2923152.19      6982018.93      2922912.61      6981880.04
      2922752.88      6981723.79      2922648.72      6981595.31
      2922527.19      6981199.48      2921693.86      6980350.52

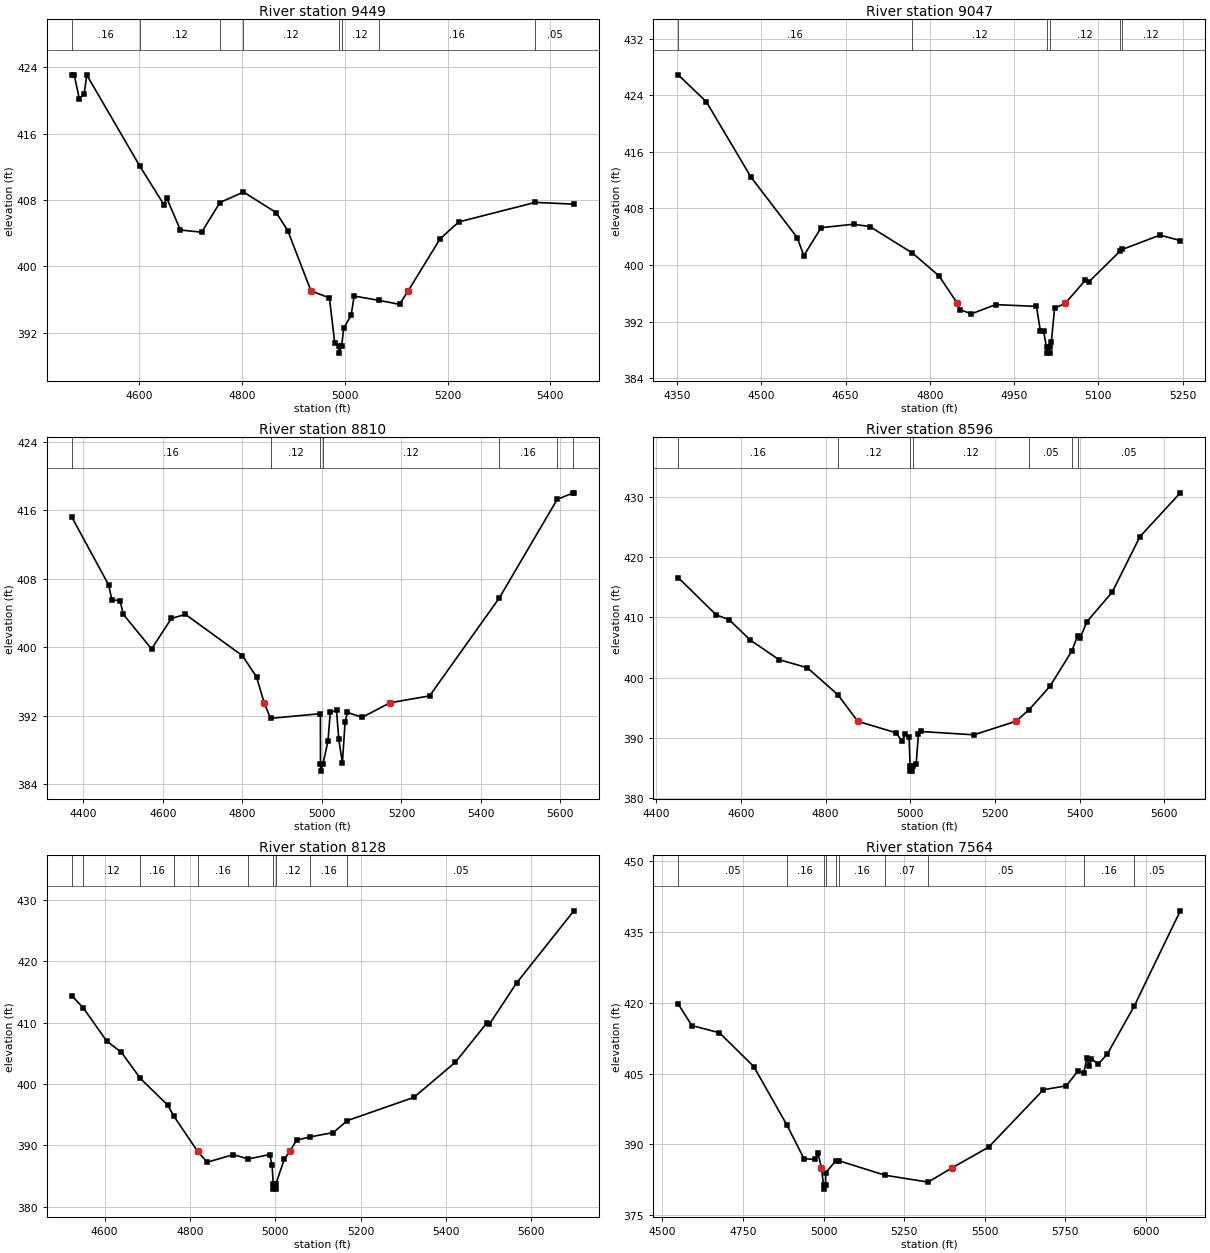
Type RM Length L Ch R = 1,9449,402,402,402
BEGIN DESCRIPTION:
CHINQUANPIA BRANCH 17.0
END DESCRIPTION:
XS GIS Cut Line= 3
      2927507.29      6986080.81      2927370.62      6986593.72
      2927608.39      6986970.70
#Sta/Elev= 30
  4469.2  423.08  4474.0  423.08  4483.9  420.17  4493.3  420.80  4498.5  423.05
  4601.4  412.09  4648.6  407.41  4653.8  408.23  4680.5  404.37  4721.9  404.11
  4757.3  407.68  4803.2  408.95  4866.8  406.47  4889.3  404.30  4934.4  397.04
  4970.3  396.19  4980.6  390.80  4988.0  390.33  4988.5  389.53  4994.0  390.33
  4998.1  392.53  5012.5  394.10  5018.4  396.41  5066.0  395.90  5106.7  395.41
  5123.6  397.04  5185.5  403.31  5222.0  405.35  5370.7  407.70  5445.7  407.49
#Mann=8,-1,0
  4469.2    0.16       0  4601.4    0.12       0  4757.3    0.16       0
  4803.2    0.12       0  4988.0    0.07       0  4994.0    0.12       0
  5066.0    0.16       0  5370.7    0.05       0
Bank Sta=4934.4,5123.6
Exp/Cntr=0.3,0.1

Type RM Length L Ch R = 1,9047,237,237,237
BEGIN DESCRIPTION:
CHINQUANPIA BRANCH 16.0
END DESCRIPTION:
XS GIS Cut Line= 3
      2927324.98      6986075.03      2926982.57      6986625.41
      2927095.81      6986843.80
#Sta/Elev= 30
  4351.8  426.90  4401.9  423.08  4481.3  412.44  4563.7  403.88  4575.5  401.32
  4606.2  405.28  4664.0  405.77  4693.3  405.43  4768.8  401.70  4816.3  398.46
  4848.9  394.58  4852.9  393.70  4874.1  393.10  4917.1  394.40  4989.8  394.15
  4996.8  390.66  5002.6  390.66  5007.7  388.34  5008.2  387.54  5013.2  387.54
  5013.7  388.34  5016.3  389.10  5022.1  393.89  5041.0  394.58  5077.0  397.86
  5082.7  397.59  5138.1  401.92  5142.4  402.20  5209.8  404.23  5246.0  403.46
#Mann=6,-1,0
  4351.8    0.16       0  4768.8    0.12       0  5007.7    0.07       0
  5013.7    0.12       0  5138.1    0.16       0  5142.4    0.12       0
Bank Sta=4848.9,5041
Exp/Cntr=0.3,0.1

Type RM Length L Ch R = 1,8810,214,214,214
BEGIN DESCRIPTION:
Mapping XS d97f47d1
END DESCRIPTION:
XS GIS Cut Line= 3
      2927153.10      6986052.19      2926775.52      6986546.96
      2926220.84      6986867.26
#Sta/Elev= 30
  4370.9  415.23  4463.6  407.29  4471.8  405.56  4492.7  405.42  4500.2  403.87
  4571.6  399.80  4621.5  403.37  4656.8  403.84  4800.2  399.01  4835.6  396.53
  4854.8  393.51  4870.8  391.68  4996.3  392.23  4996.5  386.31  4997.0  385.51
  5002.5  386.31  5015.3  389.02  5021.1  392.37  5036.8  392.62  5042.6  389.21
  5051.6  386.46  5058.4  391.26  5064.2  392.37  5101.5  391.81  5171.8  393.51
  5271.0  394.31  5446.4  405.77  5591.8  417.28  5632.4  418.06  5633.8  418.06
#Mann=7,-1,0
  4370.9    0.16       0  4870.8    0.12       0  4996.5    0.07       0
  5002.5    0.12       0  5446.4    0.16       0  5591.8    0.05       0
  5632.4    0.16       0
Bank Sta=4854.8,5171.8
Exp/Cntr=0.3,0.1

Type RM Length L Ch R = 1,8596,468,468,468
BEGIN DESCRIPTION:
CHINQUANPIA BRANCH 15.0
END DESCRIPTION:
XS GIS Cut Line= 3
      2926874.99      6985925.01      2926625.00      6986425.00
      2926075.00      6986725.00
#Sta/Elev= 30
  4452.2  416.60  4541.6  410.43  4572.4  409.60  4622.7  406.22  4689.8  402.99
  4756.9  401.64  4828.9  397.17  4876.0  392.75  4966.5  390.83  4980.5  389.46
  4988.8  390.59  4997.2  390.09  4999.8  385.27  5000.3  384.47  5005.3  384.47
  5005.8  385.27  5014.1  385.69  5019.3  390.65  5025.0  391.05  5150.3  390.50
  5249.7  392.75  5281.0  394.70  5329.7  398.53  5381.6  404.42  5395.2  406.95
  5400.9  406.51  5417.0  409.28  5476.8  414.18  5542.3  423.40  5637.7  430.68
#Mann=7,-1,0
  4452.2    0.16       0  4828.9    0.12       0  4999.8    0.07       0
  5005.8    0.12       0  5281.0    0.05       0  5381.6    0.16       0
  5395.2    0.05       0
Bank Sta=4876,5249.7
Exp/Cntr=0.3,0.1

Type RM Length L Ch R = 1,8128,564,564,564
BEGIN DESCRIPTION:
CHINQUANPIA BRANCH 14.0
END DESCRIPTION:
XS GIS Cut Line= 3
      2926824.95      6985925.01      2926375.00      6986025.00
      2926075.01      6986674.98
#Sta/Elev= 30
  4523.0  414.38  4549.9  412.39  4604.9  406.99  4639.5  405.15  4683.9  400.90
  4748.3  396.54  4761.7  394.83  4818.1  389.03  4818.8  388.97  4840.5  387.28
  4902.0  388.52  4936.5  387.80  4986.7  388.53  4992.6  386.82  4995.1  383.70
  4995.6  382.90  5000.7  382.90  5001.2  383.70  5021.1  387.78  5033.8  389.03
  5050.0  390.87  5081.8  391.40  5135.8  392.10  5168.9  394.05  5324.9  397.83
  5422.2  403.55  5496.5  409.98  5502.0  409.75  5565.4  416.42  5699.8  428.18
#Mann=10,-1,0
  4523.0    0.16       0  4549.9    0.12       0  4683.9    0.16       0
  4761.7    0.12       0  4818.8    0.16       0  4936.5    0.12       0
  4995.1    0.07       0  5001.2    0.12       0  5081.8    0.16       0
  5168.9    0.05       0
Bank Sta=4818.1,5033.8
Exp/Cntr=0.3,0.1

Type RM Length L Ch R = 1,7564,541,541,541
BEGIN DESCRIPTION:
CHINQUANPIA BRANCH 13.0
END DESCRIPTION:
XS GIS Cut Line= 3
      2926374.98      6985325.01      2926025.00      6985625.00
      2925275.03      6986424.97
#Sta/Elev= 30
  4549.2  419.73  4591.4  415.17  4677.0  413.65  4783.5  406.49  4886.8  394.04
  4939.4  386.96  4974.5  386.82  4982.2  388.26  4993.6  385.04  4999.9  381.32
  5000.4  380.52  5006.2  381.32  5006.9  384.03  5038.3  386.52  5046.8  386.55
  5190.9  383.46  5324.3  382.01  5399.0  385.04  5512.5  389.44  5682.0  401.58
  5752.9  402.40  5788.5  405.49  5807.4  405.13  5816.8  408.32  5823.7  406.67
  5831.0  408.18  5852.0  406.96  5880.3  409.15  5964.0  419.33  6106.7  439.48
#Mann=10,-1,0
  4549.2    0.05       0  4886.8    0.16       0  4999.9    0.07       0
  5006.2    0.16       0  5038.3    0.12       0  5046.8    0.16       0
  5190.9    0.07       0  5324.3    0.05       0  5807.4    0.16       0
  5964.0    0.05       0
Bank Sta=4993.6,5399
Exp/Cntr=0.3,0.1

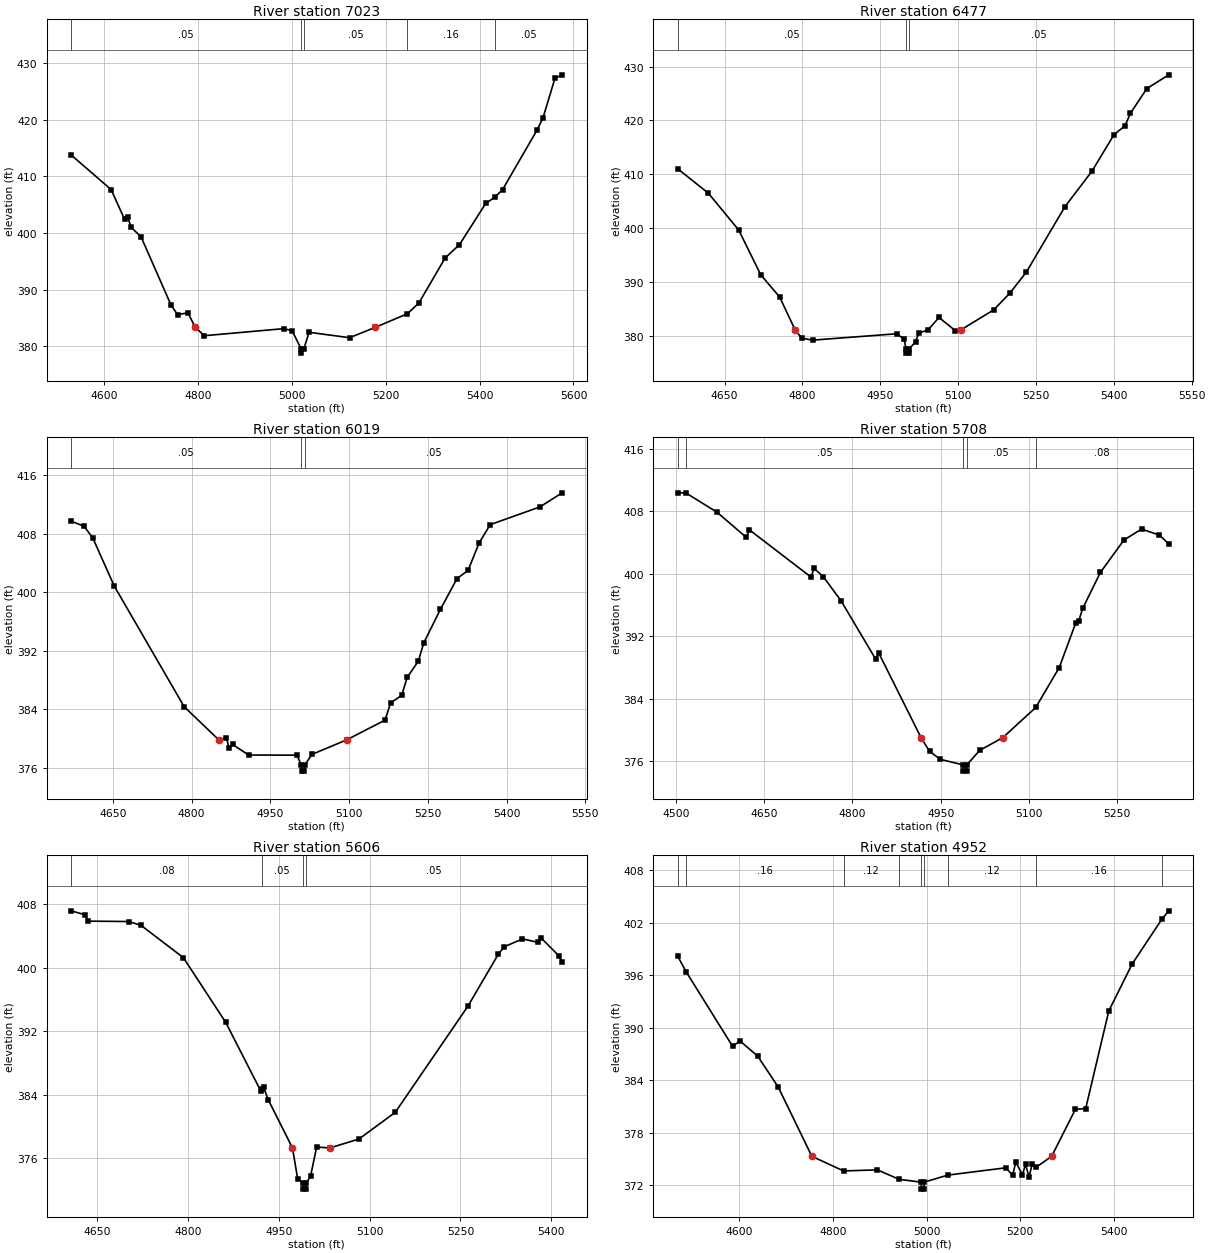
Type RM Length L Ch R = 1,7023,546,546,546
BEGIN DESCRIPTION:
CHINQUANPIA BRANCH 12.0
END DESCRIPTION:
XS GIS Cut Line= 3
      2925924.99      6985075.01      2925575.00      6985375.00
      2925025.00      6985575.00
#Sta/Elev= 30
  4529.7  413.75  4614.8  407.65  4643.3  402.43  4649.9  402.83  4657.6  400.98
  4678.4  399.35  4742.1  387.36  4756.3  385.61  4778.3  385.93  4794.2  383.38
  4813.4  381.90  4983.5  383.15  5000.6  382.76  5019.4  379.63  5019.9  378.83
  5025.7  379.63  5036.6  382.50  5123.0  381.55  5177.9  383.38  5246.1  385.77
  5270.6  387.66  5326.5  395.59  5357.1  397.95  5413.0  405.21  5432.7  406.33
  5448.9  407.64  5522.7  418.18  5535.3  420.35  5560.6  427.26  5575.9  427.88
#Mann=5,-1,0
  4529.7    0.05       0  5019.4    0.03       0  5025.7    0.05       0
  5246.1    0.16       0  5432.7    0.05       0
Bank Sta=4794.2,5177.9
Exp/Cntr=0.3,0.1

Type RM Length L Ch R = 1,6477,458,458,458
BEGIN DESCRIPTION:
CHINQUANPIA BRANCH 11.0
END DESCRIPTION:
XS GIS Cut Line= 3
      2925424.99      6984675.02      2925175.00      6985075.00
      2925025.00      6985524.99
#Sta/Elev= 30
  4559.8  411.03  4618.7  406.51  4677.1  399.69  4719.6  391.38  4756.1  387.25
  4785.8  381.17  4798.6  379.62  4819.8  379.26  4981.4  380.44  4996.1  379.43
  4999.4  377.65  4999.9  376.85  5005.2  376.85  5005.7  377.65  5017.9  378.93
  5023.8  380.53  5042.0  381.17  5063.1  383.46  5094.7  381.01  5105.4  381.17
  5168.5  384.87  5200.1  388.02  5231.7  391.92  5305.5  403.97  5358.2  410.64
  5400.4  417.39  5421.5  419.00  5432.0  421.34  5463.7  425.93  5505.8  428.47
#Mann=3,-1,0
  4559.8    0.05       0  4999.4    0.03       0  5005.7    0.05       0
Bank Sta=4785.8,5105.4
Exp/Cntr=0.3,0.1

Type RM Length L Ch R = 1,6019,311,311,311
BEGIN DESCRIPTION:
CHINQUANPIA BRANCH 10.0
END DESCRIPTION:
XS GIS Cut Line= 3
      2925374.95      6984575.01      2924925.00      6984675.00
      2924774.99      6985125.03
#Sta/Elev= 30
  4570.5  409.71  4594.8  409.03  4611.4  407.46  4652.4  400.87  4785.6  384.39
  4851.5  379.86  4866.2  380.13  4871.4  378.71  4877.8  379.23  4908.5  377.78
  5000.7  377.76  5009.0  376.38  5009.5  375.58  5014.9  375.58  5015.4  376.38
  5028.9  377.86  5095.6  379.86  5168.5  382.55  5179.0  384.91  5200.1  385.92
  5210.6  388.38  5231.7  390.59  5242.2  393.10  5273.9  397.67  5305.5  401.88
  5326.6  402.99  5347.7  406.76  5368.7  409.24  5463.6  411.67  5505.8  413.59
#Mann=3,-1,0
  4570.5    0.05       0  5009.0    0.03       0  5015.4    0.05       0
Bank Sta=4851.5,5095.6
Exp/Cntr=0.3,0.1

Type RM Length L Ch R = 1,5708,102,102,102
BEGIN DESCRIPTION:
Mapping XS e50287ea
END DESCRIPTION:
XS GIS Cut Line= 3
      2925361.47      6984421.09      2924888.36      6984377.69
      2924529.01      6984399.34
#Sta/Elev= 30
  4502.9  410.38  4516.3  410.39  4569.7  407.90  4619.6  404.67  4624.6  405.65
  4729.5  399.59  4734.6  400.71  4750.4  399.64  4780.5  396.56  4839.5  389.07
  4844.5  389.89  4916.7  379.01  4931.2  377.25  4949.5  376.23  4988.2  375.52
  4988.7  374.72  4994.1  374.72  4994.6  375.52  5016.4  377.38  5055.7  379.01
  5111.8  382.88  5151.7  387.99  5179.7  393.69  5184.7  393.94  5191.7  395.58
  5221.8  400.19  5261.9  404.35  5291.9  405.74  5322.0  404.98  5338.0  403.85
#Mann=5,-1,0
  4502.9    0.08       0  4516.3    0.05       0  4988.2    0.04       0
  4994.6    0.05       0  5111.8    0.08       0
Bank Sta=4916.7,5055.7
Exp/Cntr=0.3,0.1

Type RM Length L Ch R = 1,5606,654,654,654
BEGIN DESCRIPTION:
Mapping XS e6a9466b
END DESCRIPTION:
XS GIS Cut Line= 3
      2925270.27      6984290.88      2924892.70      6984277.86
      2924459.38      6984269.20
#Sta/Elev= 30
  4606.9  407.18  4629.8  406.68  4634.8  405.88  4702.2  405.83  4722.2  405.35
  4792.3  401.27  4862.3  393.10  4920.0  384.48  4922.1  384.66  4925.0  384.90
  4932.4  383.36  4972.5  377.28  4981.0  373.42  4989.2  372.88  4989.7  372.08
  4995.1  372.08  4995.6  372.88  5002.4  373.71  5012.4  377.38  5034.5  377.28
  5082.4  378.40  5142.4  381.77  5262.5  395.16  5312.5  401.69  5322.5  402.65
  5352.5  403.63  5377.7  403.22  5382.7  403.81  5412.5  401.52  5418.1  400.75
#Mann=4,-1,0
  4606.9    0.08       0  4922.1    0.05       0  4989.2    0.03       0
  4995.6    0.05       0
Bank Sta=4972.5,5034.5
Exp/Cntr=0.3,0.1

Type RM Length L Ch R = 1,4952,599,599,599
BEGIN DESCRIPTION:
CHINQUANPIA BRANCH 8.0
END DESCRIPTION:
XS GIS Cut Line= 3
      2925275.00      6983975.00      2924825.00      6983725.00
      2924474.99      6984125.01
#Sta/Elev= 30
  4469.9  398.13  4487.5  396.39  4586.6  387.86  4602.6  388.46  4640.3  386.72
  4683.8  383.21  4755.6  375.28  4823.1  373.61  4895.4  373.73  4941.5  372.65
  4988.6  372.33  4989.1  371.53  4994.5  371.53  4995.0  372.33  5045.1  373.13
  5169.3  373.97  5183.5  373.11  5190.2  374.61  5204.4  373.18  5211.0  374.35
  5218.6  372.90  5225.3  374.45  5233.3  374.02  5266.7  375.28  5317.3  380.65
  5339.2  380.74  5388.5  391.90  5437.9  397.23  5501.3  402.36  5516.2  403.34
#Mann=9,-1,0
  4469.9    0.08       0  4487.5    0.16       0  4823.1    0.12       0
  4941.5    0.16       0  4988.6    0.07       0  4995.0    0.16       0
  5045.1    0.12       0  5233.3    0.16       0  5501.3    0.05       0
Bank Sta=4755.6,5266.7
Exp/Cntr=0.3,0.1

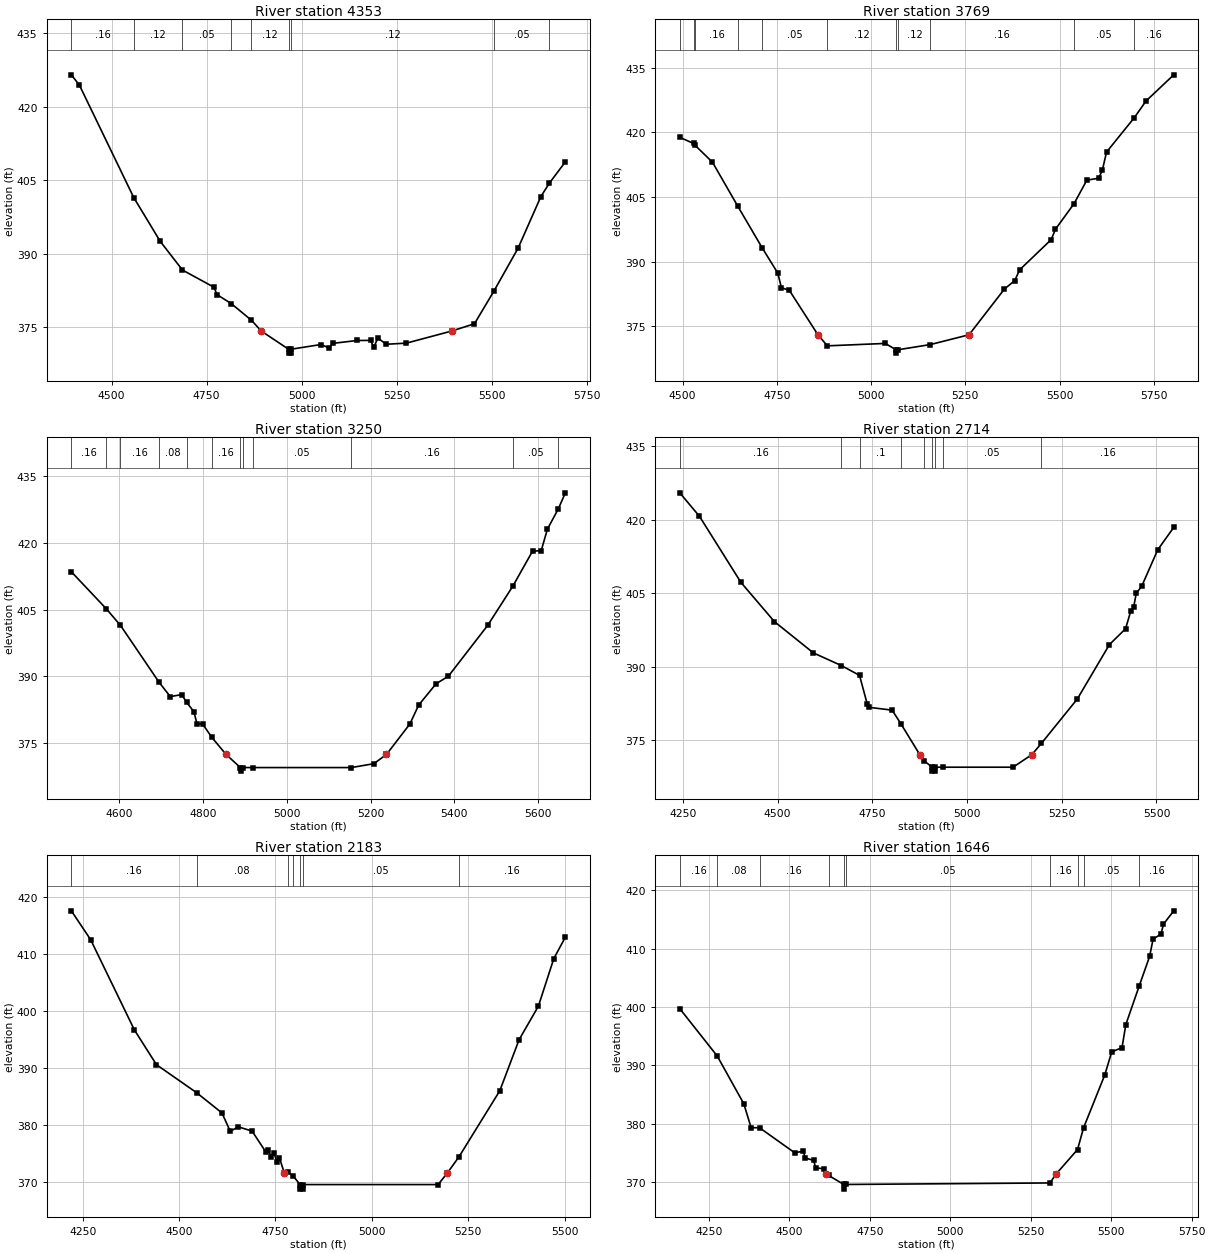
Type RM Length L Ch R = 1,4353,584,584,584
BEGIN DESCRIPTION:
CHINQUANPIA BRANCH 7.0
END DESCRIPTION:
XS GIS Cut Line= 3
      2925025.02      6982924.98      2924625.00      6983375.00
      2923975.02      6983624.99
#Sta/Elev= 30
  4394.3  426.52  4415.6  424.39  4558.2  401.46  4628.0  392.49  4686.4  386.64
  4769.4  383.12  4776.9  381.63  4814.7  379.78  4867.6  376.39  4893.4  374.19
  4965.1  370.47  4965.6  369.67  4971.2  369.67  4971.7  370.47  5050.0  371.42
  5071.4  370.76  5082.1  371.67  5145.3  372.25  5180.7  372.27  5189.3  370.87
  5200.0  372.78  5221.4  371.48  5275.0  371.71  5394.3  374.19  5453.9  375.67
  5505.5  382.41  5568.5  391.11  5628.5  401.66  5650.7  404.39  5692.8  408.74
#Mann=9,-1,0
  4394.3    0.16       0  4558.2    0.12       0  4686.4    0.05       0
  4814.7    0.16       0  4867.6    0.12       0  4965.1    0.07       0
  4971.7    0.12       0  5505.5    0.05       0  5650.7    0.16       0
Bank Sta=4893.4,5394.3
Exp/Cntr=0.3,0.1

Type RM Length L Ch R = 1,3769,519,519,519
BEGIN DESCRIPTION:
CHINQUANPIA BRANCH 6.0
END DESCRIPTION:
XS GIS Cut Line= 3
      2924625.00      6982725.00      2924225.00      6982975.00
      2923424.95      6983225.01
#Sta/Elev= 30
  4492.7  418.82  4529.4  417.39  4533.0  416.99  4579.4  413.05  4647.0  402.77
  4711.0  393.21  4752.7  387.31  4762.2  383.93  4783.4  383.30  4859.1  373.01
  4884.0  370.44  5037.7  371.00  5065.7  369.55  5066.2  368.75  5072.7  369.55
  5157.3  370.74  5259.8  373.01  5353.6  383.62  5380.9  385.57  5394.0  388.08
  5477.8  395.10  5488.8  397.49  5538.4  403.45  5572.1  408.88  5603.5  409.33
  5613.4  411.25  5624.4  415.40  5698.1  423.39  5729.2  427.26  5802.6  433.32
#Mann=11,-1,0
  4492.7    0.16       0  4529.4    0.12       0  4533.0    0.16       0
  4647.0    0.12       0  4711.0    0.05       0  4884.0    0.12       0
  5065.7    0.07       0  5072.7    0.12       0  5157.3    0.16       0
  5538.4    0.05       0  5698.1    0.16       0
Bank Sta=4859.1,5259.8
Exp/Cntr=0.3,0.1

Type RM Length L Ch R = 1,3250,536,536,536
BEGIN DESCRIPTION:
CHINQUANPIA BRANCH 5.0
END DESCRIPTION:
XS GIS Cut Line= 3
      2924274.99      6982275.01      2923875.00      6982575.00
      2923324.96      6982975.03
#Sta/Elev= 30
  4485.1  413.46  4568.6  405.15  4602.4  401.44  4694.5  388.70  4721.5  385.46
  4748.6  385.92  4760.6  384.17  4777.8  382.07  4785.1  379.41  4798.6  379.34
  4820.5  376.33  4854.7  372.49  4888.8  369.55  4889.3  368.75  4895.9  369.55
  4918.8  369.55  5154.0  369.55  5207.7  370.42  5237.9  372.49  5293.8  379.33
  5314.7  383.55  5356.4  388.35  5385.8  390.04  5479.7  401.45  5539.4  410.19
  5586.7  418.07  5607.6  418.21  5622.3  423.03  5648.3  427.56  5665.2  431.17
#Mann=12,-1,0
  4485.1    0.16       0  4568.6    0.12       0  4602.4    0.16       0
  4694.5    0.08       0  4760.6    0.05       0  4820.5    0.16       0
  4888.8   0.033       0  4895.9    0.16       0  4918.8    0.05       0
  5154.0    0.16       0  5539.4    0.05       0  5648.3    0.16       0
Bank Sta=4854.7,5237.9
Exp/Cntr=0.3,0.1

Type RM Length L Ch R = 1,2714,531,531,531
BEGIN DESCRIPTION:
CHINQUANPIA BRANCH 4.0
END DESCRIPTION:
XS GIS Cut Line= 3
      2923925.01      6981524.98      2923575.00      6982175.00
      2923175.04      6982574.96
#Sta/Elev= 30
  4241.8  425.44  4293.7  420.67  4403.3  407.19  4491.7  399.20  4594.7  392.82
  4668.2  390.26  4716.3  388.26  4736.7  382.39  4742.4  381.74  4802.4  381.17
  4826.1  378.32  4875.5  372.09  4886.4  370.86  4908.3  369.55  4908.8  368.75
  4915.0  368.75  4915.6  369.55  4935.8  369.55  5121.5  369.55  5170.9  372.09
  5196.1  374.38  5291.2  383.45  5376.0  394.54  5418.5  397.75  5432.6  401.46
  5439.7  402.09  5446.8  405.01  5460.9  406.37  5503.3  413.82  5545.7  418.41
#Mann=9,-1,0
  4241.8    0.16       0  4668.2    0.05       0  4716.3     0.1       0
  4826.1    0.16       0  4886.4     0.1       0  4908.3   0.033       0
  4915.6     0.1       0  4935.8    0.05       0  5196.1    0.16       0
Bank Sta=4875.5,5170.9
Exp/Cntr=0.3,0.1

Type RM Length L Ch R = 1,2183,537,537,537
BEGIN DESCRIPTION:
CHINQUANPIA BRANCH 3.0
END DESCRIPTION:
XS GIS Cut Line= 3
      2923675.01      6981474.99      2923075.00      6981975.00
      2923075.00      6982474.96
#Sta/Elev= 30
  4220.7  417.55  4270.8  412.48  4384.1  396.67  4441.4  390.57  4545.3  385.67
  4611.2  382.11  4632.7  378.89  4653.5  379.67  4689.3  378.93  4725.1  375.25
  4731.6  375.54  4739.4  374.37  4746.0  375.17  4753.8  373.46  4760.3  374.24
  4772.8  371.59  4782.0  371.72  4795.3  371.09  4813.9  369.55  4814.4  368.75
  4820.6  368.75  4821.2  369.55  5171.7  369.55  5195.8  371.59  5225.5  374.38
  5331.7  386.00  5381.7  394.95  5431.7  400.82  5471.7  409.17  5501.7  412.93
#Mann=7,-1,0
  4220.7    0.16       0  4545.3    0.08       0  4782.0    0.16       0
  4795.3    0.05       0  4813.9   0.033       0  4821.2    0.05       0
  5225.5    0.16       0
Bank Sta=4772.8,5195.8
Exp/Cntr=0.3,0.1

Type RM Length L Ch R = 1,1646,974,974,974
BEGIN DESCRIPTION:
CHINQUANPIA BRANCH 2.0
END DESCRIPTION:
XS GIS Cut Line= 3
      2923474.97      6981375.01      2922675.00      6981625.00
      2922425.01      6982274.97
#Sta/Elev= 30
  4159.9  399.72  4276.3  391.59  4358.9  383.39  4381.5  379.30  4408.0  379.27
  4516.6  375.00  4543.8  375.25  4549.1  374.10  4576.3  373.67  4581.6  372.42
  4608.8  372.22  4613.2  371.26  4622.5  371.09  4669.5  369.55  4670.1  368.75
  4676.9  369.55  5310.1  369.81  5327.6  371.26  5395.5  375.54  5414.1  379.25
  5480.2  388.35  5501.6  392.29  5533.7  393.03  5545.5  396.98  5587.5  403.68
  5619.4  408.67  5630.2  411.65  5654.8  412.51  5662.3  414.20  5694.4  416.50
#Mann=10,-1,0
  4159.9    0.16       0  4276.3    0.08       0  4408.0    0.16       0
  4622.5    0.05       0  4669.5   0.033       0  4676.9    0.05       0
  5310.1    0.16       0  5395.5    0.08       0  5414.1    0.05       0
  5587.5    0.16       0
Bank Sta=4613.2,5327.6
Exp/Cntr=0.3,0.1

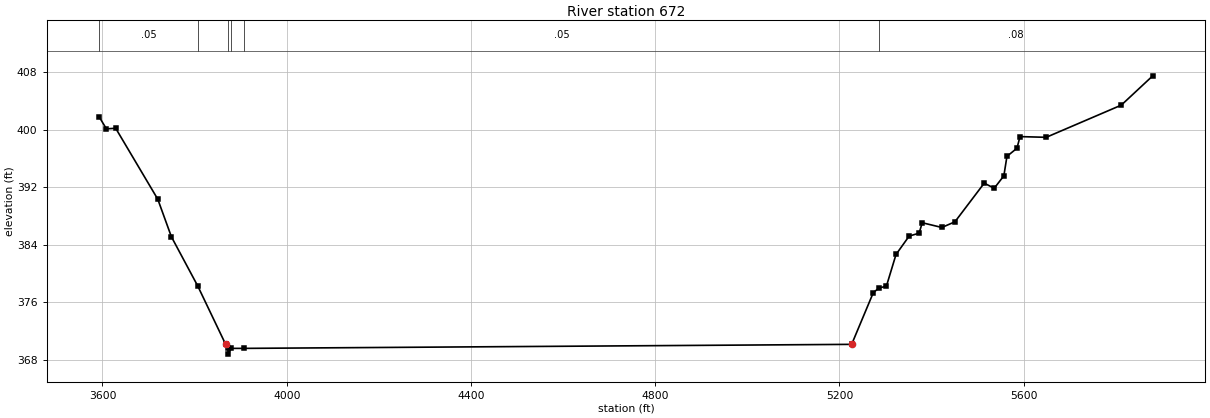
Type RM Length L Ch R = 1,672,0,0,0
BEGIN DESCRIPTION:
CHINQUANPIA BRANCH 1.0
END DESCRIPTION:
XS GIS Cut Line= 3
      2923560.20      6981005.29      2922125.00      6980825.00
      2921564.75      6981451.18
#Sta/Elev= 30
  3593.3  401.74  3608.6  400.11  3628.8  400.19  3720.2  390.31  3749.7  385.09
  3807.1  378.21  3867.5  370.11  3872.3  369.55  3872.9  368.75  3879.8  369.55
  3906.6  369.55  5226.4  370.11  5273.4  377.31  5285.8  377.96  5301.8  378.20
  5322.7  382.62  5351.2  385.18  5372.9  385.59  5379.6  387.04  5422.2  386.38
  5450.6  387.17  5514.2  392.55  5535.9  391.84  5556.8  393.57  5563.5  396.28
  5585.2  397.41  5591.9  399.03  5648.7  398.93  5811.7  403.41  5880.0  407.49
#Mann=6,-1,0
  3593.3    0.05       0  3807.1    0.16       0  3872.3   0.033       0
  3879.8    0.16       0  3906.6    0.05       0  5285.8    0.08       0
Bank Sta=3867.5,5226.4
Exp/Cntr=0.3,0.1

Chan Stop Cuts=-1