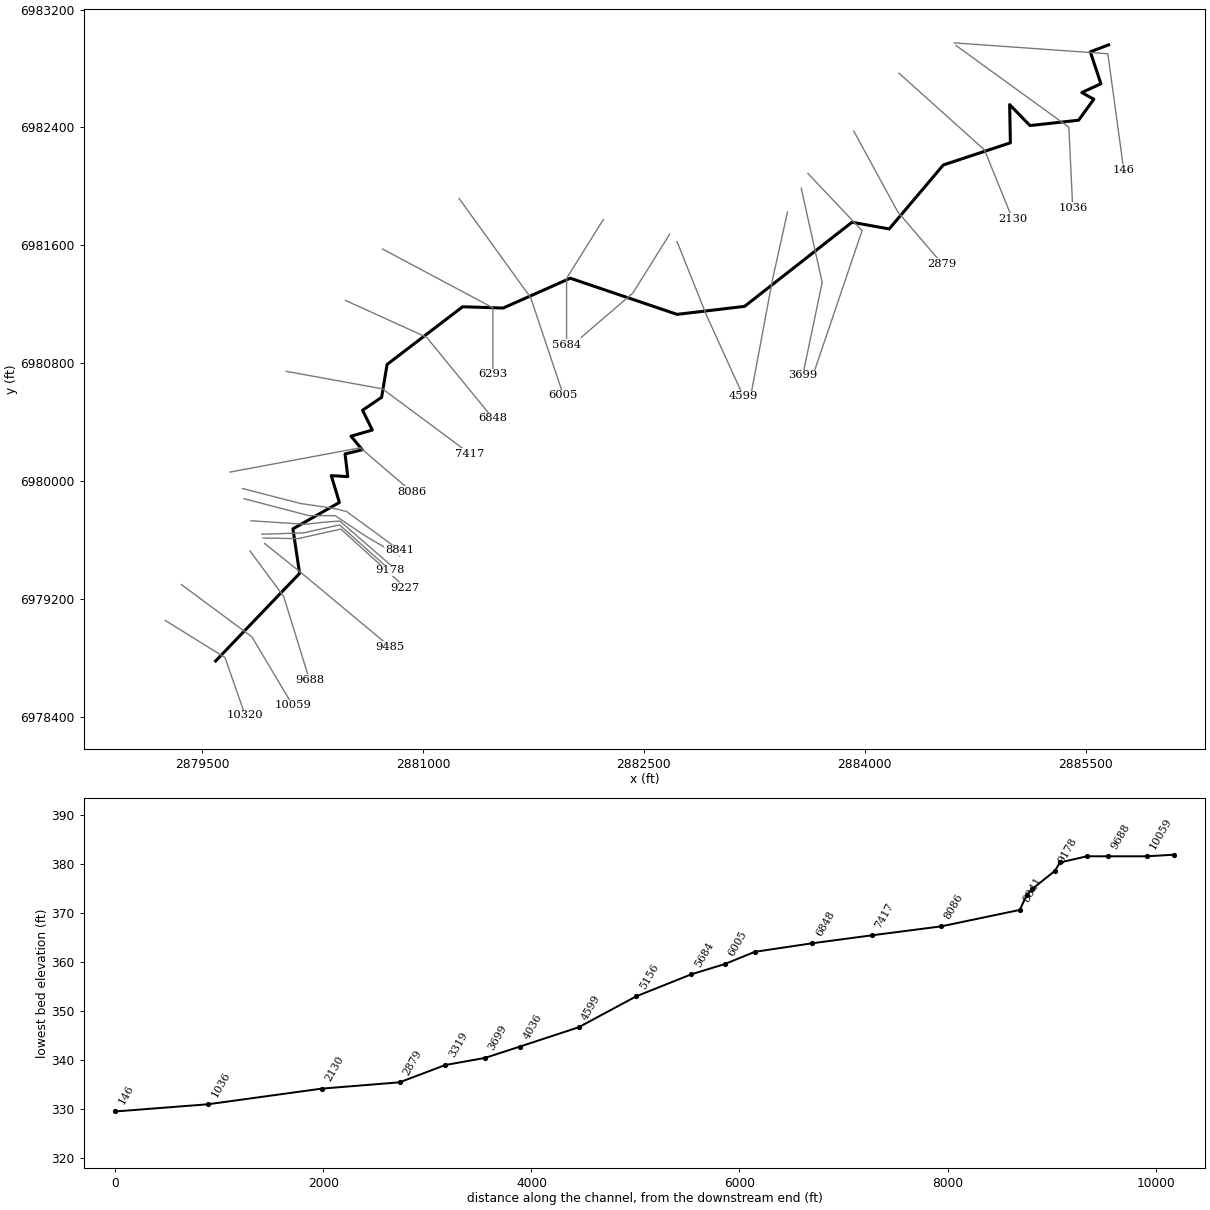
--- CLARK BRANCH.prj (project) ---

Proj Title=CLARK BRANCH Base Level Engineering
Current Plan=p01
Default Exp/Contr=0.3,0.1
English Units
Geom File=g01
Flow File=f01
Plan File=p01
BEGIN DESCRIPTION:
CLARK BRANCH
END DESCRIPTION:

--- CLARK BRANCH.p01 (plan) ---

Plan Title=Multiple Run
Short Identifier=Multiple
Geom File=g01
Flow File=f01
Subcritical Flow
K Sum by GR= 0
Std Step Tol= 0.01
Critical Tol= 0.01
Num of Std Step Trials= 20
Max Error Tol= 0.3
Flow Tol Ratio= 0.001
Split Flow NTrial= 30
Split Flow Tol= 0.02
Split Flow Ratio= 0.02
Log Output Level= 0
Friction Slope Method= 1
Unsteady Friction Slope Method= 2
Unsteady Bridges Friction Slope Method= 1
Parabolic Critical Depth
Global Vel Dist=  1 , 1 , 1
Global Log Level= 0
CheckData=True
Encroach Param= -1, 0, 0, 0
BEGIN DESCRIPTION:
Multiple Run
END DESCRIPTION:

--- CLARK BRANCH.f01 (steady flow) ---

Flow Title=Multiple
Number of Profiles=7
Profile Names=10-year,25-year,50-year,1pct_min,100-year,1pct_plu,500-year
River Rch & RM= CLARK BRANCH,Reach-1,10320
     574     773     935     563    1123    2241    1623
River Rch & RM= CLARK BRANCH,Reach-1,10059
     784    1072    1311     796    1588    3169    2337
River Rch & RM= CLARK BRANCH,Reach-1,2879
    1296    1814    2252    1386    2766    5518    4183
Boundary for River Rch & Prof#=CLARK BRANCH,Reach-1,1
Up Type=0
Dn Type=3
Dn Slope=0.005
Boundary for River Rch & Prof#=CLARK BRANCH,Reach-1,2
Up Type=0
Dn Type=3
Dn Slope=0.005
Boundary for River Rch & Prof#=CLARK BRANCH,Reach-1,3
Up Type=0
Dn Type=3
Dn Slope=0.005
Boundary for River Rch & Prof#=CLARK BRANCH,Reach-1,4
Up Type=0
Dn Type=3
Dn Slope=0.005
Boundary for River Rch & Prof#=CLARK BRANCH,Reach-1,5
Up Type=0
Dn Type=3
Dn Slope=0.005
Boundary for River Rch & Prof#=CLARK BRANCH,Reach-1,6
Up Type=0
Dn Type=3
Dn Slope=0.005
Boundary for River Rch & Prof#=CLARK BRANCH,Reach-1,7
Up Type=0
Dn Type=3
Dn Slope=0.005

--- CLARK BRANCH.g01 (geometry) ---

Geom Title=Existing Conditions

River Reach=CLARK BRANCH,Reach-1
Reach XY= 30
      2879592.02      6978777.15      2880162.29      6979372.08
      2880117.25      6979674.54      2880432.43      6979853.77
      2880377.42      6980036.01      2880489.26      6980029.08
      2880471.02      6980183.13      2880588.18      6980211.36
      2880511.43      6980303.52      2880656.21      6980345.52
      2880589.91      6980479.75      2880719.26      6980567.67
      2880756.30      6980790.53      2881269.24      6981182.46
      2881544.55      6981173.66      2882000.37      6981376.16
      2882725.59      6981130.71      2883183.67      6981185.07
      2883912.94      6981756.28      2884165.59      6981710.71
      2884533.15      6982145.07      2884988.51      6982295.51
      2884983.30      6982554.94      2885121.24      6982412.51
      2885451.64      6982448.95      2885554.77      6982591.38
      2885473.23      6982636.71      2885602.91      6982696.57
      2885531.19      6982913.42      2885655.59      6982960.71

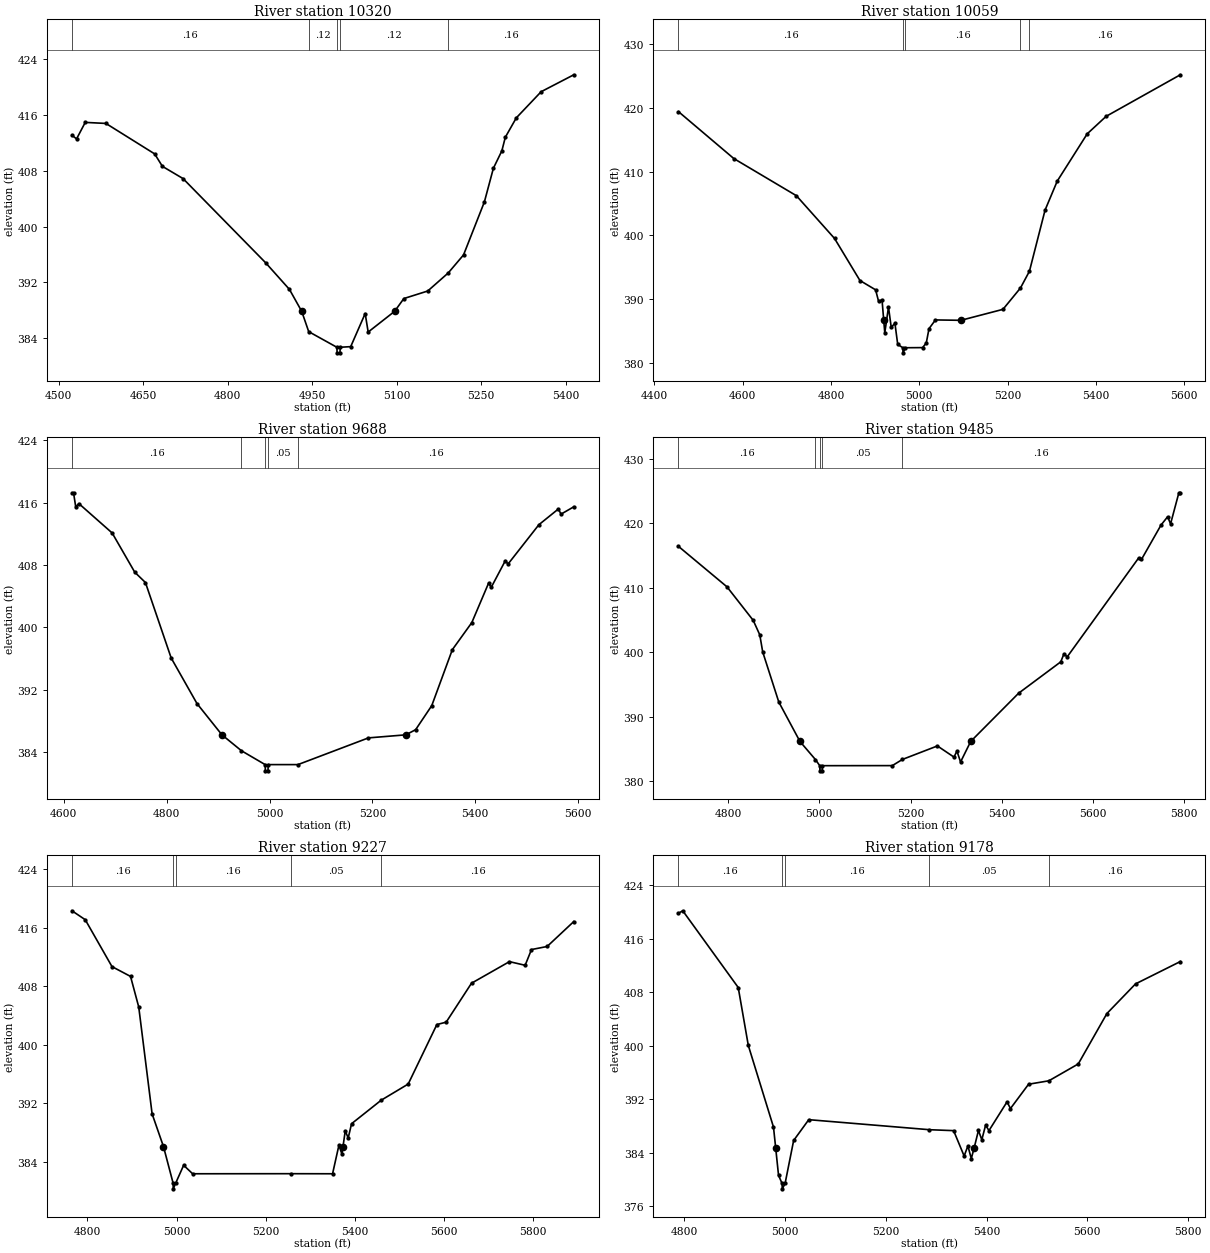
Type RM Length L Ch R = 1,10320,261,261,261
BEGIN DESCRIPTION:
CLARK BRANCH 15.0
END DESCRIPTION:
XS GIS Cut Line= 3
      2879250.15      6979052.58      2879655.29      6978801.56
      2879792.64      6978410.27
#Sta/Elev= 30
  4523.4  413.12  4531.6  412.59  4547.0  414.96  4583.7  414.81  4670.3  410.44
  4684.1  408.65  4720.7  406.90  4867.2  394.84  4909.7  391.00  4931.5  387.85
  4943.9  384.94  4993.9  382.70  4994.4  381.90  4999.4  381.90  4999.9  382.70
  5018.5  382.79  5044.2  387.54  5049.5  384.88  5096.4  387.85  5112.9  389.69
  5155.3  390.77  5191.7  393.36  5218.9  395.95  5255.9  403.55  5271.9  408.38
  5286.9  410.87  5293.1  412.83  5312.6  415.61  5356.7  419.36  5414.7  421.79
#Mann=5,-1,0
  4523.4    0.16       0  4943.9    0.12       0  4993.9    0.07       0
  4999.9    0.12       0  5191.7    0.16       0
Bank Sta=4931.5,5096.4
Exp/Cntr=0.3,0.1

Type RM Length L Ch R = 1,10059,371,371,371
BEGIN DESCRIPTION:
Mapping XS af9981ae
END DESCRIPTION:
XS GIS Cut Line= 3
      2879360.77      6979295.67      2879838.22      6978941.92
      2880115.98      6978475.37
#Sta/Elev= 30
  4454.4  419.40  4579.7  412.05  4721.6  406.22  4808.1  399.51  4865.6  392.92
  4901.1  391.46  4907.7  389.69  4915.7  389.85  4919.5  386.68  4921.9  384.72
  4930.3  388.75  4936.5  385.59  4944.9  386.21  4951.2  382.90  4962.8  382.38
  4963.3  381.58  4968.8  382.38  5007.5  382.40  5015.9  383.12  5022.1  385.37
  5036.7  386.74  5094.4  386.68  5189.7  388.40  5229.4  391.75  5249.7  394.38
  5285.1  403.96  5312.7  408.51  5380.6  415.92  5423.4  418.66  5591.6  425.18
#Mann=5,-1,0
  4454.4    0.16       0  4962.8    0.07       0  4968.8    0.16       0
  5229.4    0.12       0  5249.7    0.16       0
Bank Sta=4919.5,5094.4
Exp/Cntr=0.3,0.1

Type RM Length L Ch R = 1,9688,203,203,203
BEGIN DESCRIPTION:
CLARK BRANCH 14.0
END DESCRIPTION:
XS GIS Cut Line= 3
      2879825.01      6979524.98      2880053.90      6979216.41
      2880228.84      6978651.16
#Sta/Elev= 30
  4615.8  417.27  4618.9  417.27  4623.1  415.48  4629.3  415.88  4694.0  412.11
  4737.9  407.08  4758.7  405.75  4808.8  396.06  4858.9  390.22  4907.5  386.20
  4945.4  384.16  4991.5  382.38  4992.0  381.58  4997.0  381.58  4997.5  382.38
  5055.3  382.38  5192.4  385.81  5265.0  386.20  5284.1  386.86  5315.5  389.95
  5355.5  397.13  5393.4  400.61  5426.0  405.67  5431.2  405.14  5458.6  408.56
  5463.8  408.12  5523.8  413.17  5561.7  415.19  5566.9  414.53  5591.7  415.47
#Mann=5,-1,0
  4615.8    0.16       0  4945.4    0.05       0  4991.5   0.035       0
  4997.5    0.05       0  5055.3    0.16       0
Bank Sta=4907.5,5265
Exp/Cntr=0.3,0.1

Type RM Length L Ch R = 1,9485,258,258,258
BEGIN DESCRIPTION:
CLARK BRANCH 13.0
END DESCRIPTION:
XS GIS Cut Line= 3
      2879925.03      6979574.97      2880175.00      6979375.00
      2880774.97      6978875.02
#Sta/Elev= 30
  4690.9  416.38  4797.3  410.11  4854.9  404.91  4869.3  402.66  4875.7  400.02
  4911.0  392.25  4957.4  386.14  4991.5  383.32  5000.8  382.38  5001.3  381.58
  5006.3  381.58  5006.8  382.38  5160.1  382.39  5182.3  383.35  5259.0  385.44
  5295.4  383.71  5301.9  384.65  5309.8  382.95  5332.1  386.14  5437.3  393.62
  5529.7  398.48  5536.3  399.66  5544.1  399.28  5700.3  414.56  5706.8  414.36
  5749.7  419.69  5764.1  420.97  5770.6  419.87  5788.8  424.69  5792.0  424.69
#Mann=5,-1,0
  4690.9    0.16       0  4991.5    0.05       0  5000.8   0.033       0
  5006.8    0.05       0  5182.3    0.16       0
Bank Sta=4957.4,5332.1
Exp/Cntr=0.3,0.1

Type RM Length L Ch R = 1,9227,49,49,49
BEGIN DESCRIPTION:
Mapping XS 20d26829
END DESCRIPTION:
XS GIS Cut Line= 4
      2879915.20      6979612.35      2880151.73      6979608.01
      2880442.53      6979673.11      2880880.47      6979276.37
#Sta/Elev= 30
  4765.5  418.32  4795.3  417.10  4855.3  410.69  4896.9  409.35  4915.3  405.17
  4945.3  390.56  4970.8  386.09  4992.3  381.12  4992.8  380.32  4998.3  381.12
  5016.0  383.54  5036.2  382.38  5256.5  382.39  5350.0  382.38  5364.2  386.27
  5371.0  385.07  5373.4  386.09  5378.4  388.23  5385.1  387.28  5392.6  389.22
  5459.0  392.43  5519.6  394.64  5583.9  402.77  5604.8  403.10  5661.6  408.42
  5746.7  411.37  5781.9  410.87  5796.1  413.02  5831.2  413.44  5891.0  416.85
#Mann=5,-1,0
  4765.5    0.16       0  4992.3    0.07       0  4998.3    0.16       0
  5256.5    0.05       0  5459.0    0.16       0
Bank Sta=4970.8,5373.4
Exp/Cntr=0.3,0.1

Type RM Length L Ch R = 1,9178,221,221,221
BEGIN DESCRIPTION:
Mapping XS b3abb69b
END DESCRIPTION:
XS GIS Cut Line= 4
      2879906.49      6979638.39      2880188.63      6979647.07
      2880433.85      6979701.32      2880778.94      6979393.14
#Sta/Elev= 30
  4788.6  419.80  4797.1  420.17  4907.2  408.70  4927.2  400.04  4977.2  387.83
  4981.5  384.75  4987.2  380.63  4994.2  379.40  4994.7  378.60  5000.2  379.40
  5017.2  385.83  5047.2  388.94  5286.7  387.44  5334.7  387.30  5355.6  383.51
  5363.1  385.01  5369.8  383.12  5375.6  384.75  5384.0  387.33  5390.7  385.94
  5398.2  388.12  5404.9  387.31  5440.8  391.61  5447.5  390.60  5483.5  394.24
  5523.7  394.75  5582.1  397.27  5639.0  404.81  5695.8  409.24  5784.7  412.58
#Mann=5,-1,0
  4788.6    0.16       0  4994.2    0.07       0  5000.2    0.16       0
  5286.7    0.05       0  5523.7    0.16       0
Bank Sta=4981.5,5375.6
Exp/Cntr=0.3,0.1

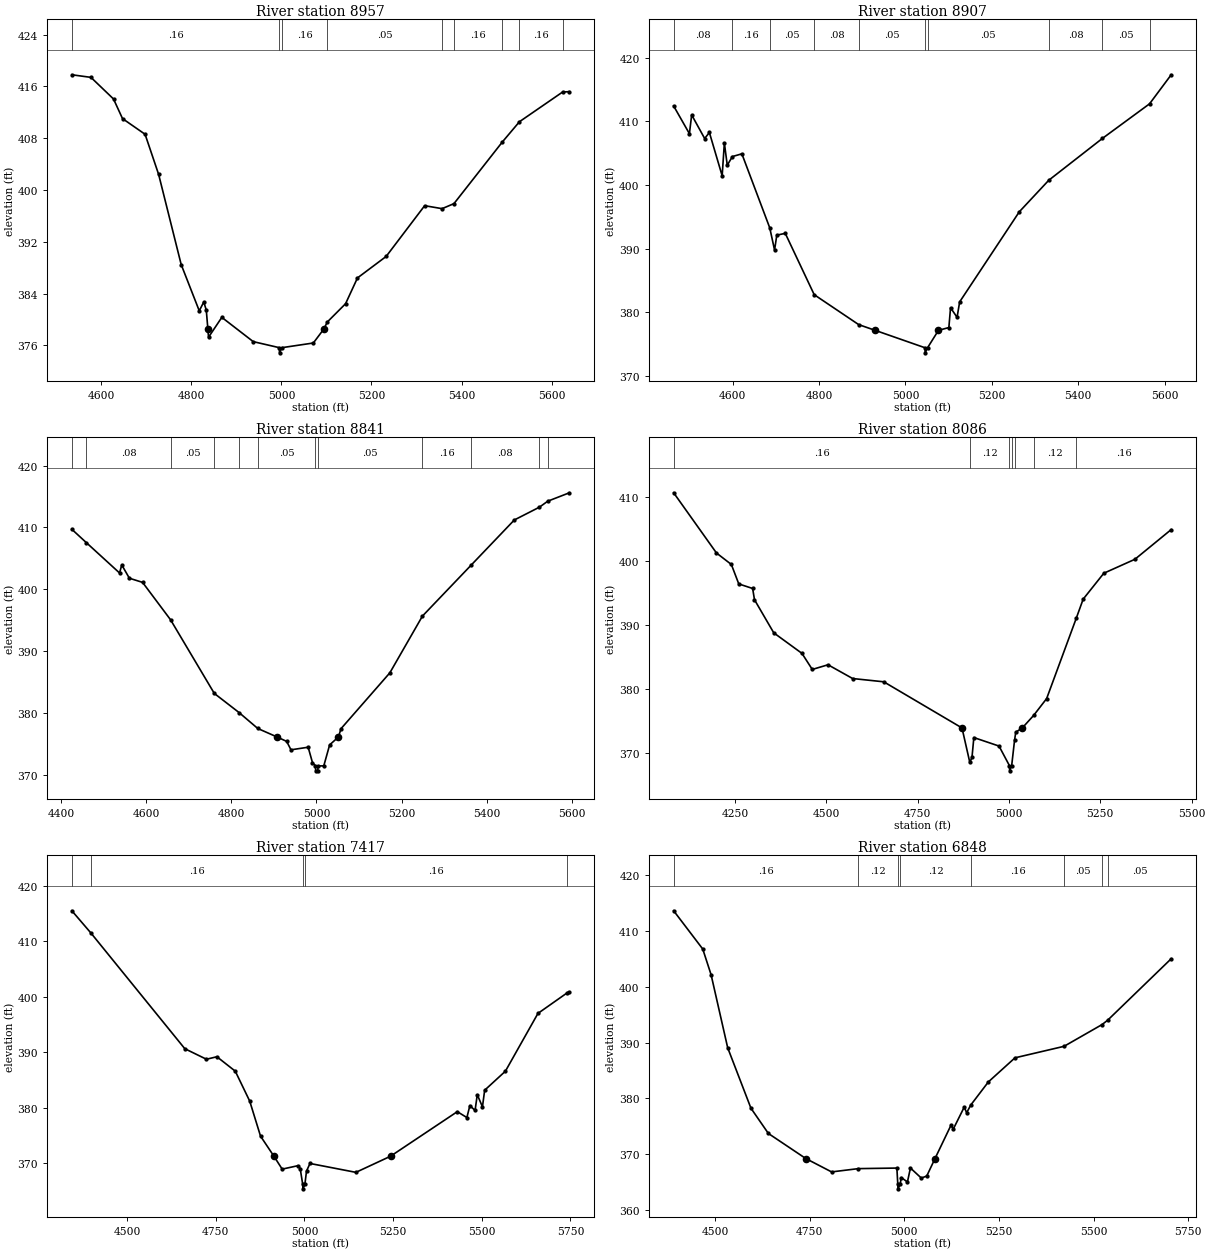
Type RM Length L Ch R = 1,8957,50,50,50
BEGIN DESCRIPTION:
Mapping XS dfdff487
END DESCRIPTION:
XS GIS Cut Line= 5
      2879832.71      6979729.54      2880197.31      6979705.66
      2880364.41      6979723.03      2880436.02      6979727.37
      2880813.41      6979399.87
#Sta/Elev= 30
  4534.7  417.79  4577.1  417.39  4627.2  414.05  4647.2  411.02  4697.3  408.60
  4727.4  402.40  4777.5  388.47  4817.6  381.33  4827.6  382.69  4833.2  381.45
  4836.8  378.45  4838.2  377.25  4867.7  380.32  4937.5  376.57  4995.3  375.64
  4995.8  374.84  5001.3  375.64  5070.9  376.36  5093.5  378.45  5102.3  379.63
  5142.5  382.43  5168.9  386.41  5232.6  389.73  5318.1  397.57  5356.8  397.11
  5383.2  397.89  5490.6  407.41  5528.6  410.54  5624.5  415.13  5639.5  415.18
#Mann=9,-1,0
  4534.7    0.16       0  4995.3    0.07       0  5001.3    0.16       0
  5102.3    0.05       0  5356.8    0.08       0  5383.2    0.16       0
  5490.6    0.05       0  5528.6    0.16       0  5624.5    0.05       0
Bank Sta=4836.8,5093.5
Exp/Cntr=0.3,0.1

Type RM Length L Ch R = 1,8907,66,66,66
BEGIN DESCRIPTION:
Mapping XS 2b20a1d6
END DESCRIPTION:
XS GIS Cut Line= 5
      2879784.94      6979879.29      2880225.52      6979764.26
      2880403.47      6979764.26      2880613.97      6979623.20
      2880842.81      6979489.35
#Sta/Elev= 30
  4463.5  412.39  4500.0  408.04  4505.2  410.99  4535.3  407.28  4546.2  408.23
  4575.8  401.43  4580.9  406.58  4587.6  403.09  4599.5  404.45  4621.4  404.88
  4686.0  393.25  4697.1  389.77  4702.3  392.11  4721.9  392.39  4788.9  382.76
  4891.9  378.06  4930.1  377.16  5045.3  374.43  5045.8  373.63  5051.3  374.43
  5076.5  377.16  5100.6  377.60  5104.5  380.71  5119.6  379.21  5125.6  381.63
  5263.6  395.77  5331.9  400.73  5455.9  407.29  5565.2  412.73  5615.3  417.29
#Mann=10,-1,0
  4463.5    0.08       0  4599.5    0.16       0  4686.0    0.05       0
  4788.9    0.08       0  4891.9    0.05       0  5045.3    0.04       0
  5051.3    0.05       0  5331.9    0.08       0  5455.9    0.05       0
  5565.2    0.08       0
Bank Sta=4930.1,5076.5
Exp/Cntr=0.3,0.1

Type RM Length L Ch R = 1,8841,755,755,755
BEGIN DESCRIPTION:
Mapping XS 01620a51
END DESCRIPTION:
XS GIS Cut Line= 5
      2879774.09      6979948.73      2880169.09      6979846.72
      2880392.62      6979814.17      2880481.59      6979792.47
      2880839.62      6979529.92
#Sta/Elev= 30
  4425.1  409.68  4459.1  407.53  4537.2  402.62  4542.4  403.92  4560.3  401.77
  4591.3  401.10  4657.0  395.06  4759.9  383.14  4818.0  380.05  4862.1  377.47
  4907.3  376.10  4930.0  375.38  4940.1  374.02  4980.5  374.44  4990.6  371.96
  4997.7  371.42  4998.2  370.62  5003.2  370.62  5003.7  371.42  5017.2  371.42
  5031.0  374.82  5051.7  376.10  5057.6  377.43  5172.5  386.47  5249.1  395.65
  5363.6  403.89  5465.0  411.19  5524.0  413.26  5543.6  414.23  5594.5  415.59
#Mann=12,-1,0
  4425.1    0.16       0  4459.1    0.08       0  4657.0    0.05       0
  4759.9    0.16       0  4818.0    0.08       0  4862.1    0.05       0
  4997.7    0.04       0  5003.7    0.05       0  5249.1    0.16       0
  5363.6    0.08       0  5524.0    0.05       0  5543.6    0.08       0
Bank Sta=4907.3,5051.7
Exp/Cntr=0.3,0.1

Type RM Length L Ch R = 1,8086,669,669,669
BEGIN DESCRIPTION:
CLARK BRANCH 11.0
END DESCRIPTION:
XS GIS Cut Line= 3
      2879689.80      6980059.98      2880575.00      6980225.00
      2880924.98      6979925.02
#Sta/Elev= 30
  4082.6  410.70  4199.8  401.29  4240.5  399.50  4260.8  396.46  4298.7  395.75
  4303.8  393.99  4356.5  388.82  4433.7  385.61  4461.9  383.10  4505.0  383.83
  4572.4  381.68  4657.5  381.17  4871.6  373.96  4892.9  368.59  4898.9  369.35
  4904.0  372.46  4972.9  371.13  5001.5  368.06  5002.0  367.26  5007.5  368.06
  5015.4  372.04  5018.7  373.30  5036.5  373.96  5067.5  375.91  5103.2  378.55
  5184.2  391.09  5203.1  394.08  5259.6  398.13  5344.7  400.31  5444.0  404.95
#Mann=7,-1,0
  4082.6    0.16       0  4892.9    0.12       0  5001.5    0.07       0
  5007.5    0.12       0  5015.4    0.16       0  5067.5    0.12       0
  5184.2    0.16       0
Bank Sta=4871.6,5036.5
Exp/Cntr=0.3,0.1

Type RM Length L Ch R = 1,7417,569,569,569
BEGIN DESCRIPTION:
CLARK BRANCH 10.0
END DESCRIPTION:
XS GIS Cut Line= 3
      2880071.74      6980744.00      2880725.00      6980625.00
      2881318.22      6980185.00
#Sta/Elev= 30
  4344.5  415.50  4397.8  411.53  4662.9  390.66  4723.9  388.76  4753.4  389.21
  4805.2  386.61  4845.9  381.22  4876.4  374.91  4914.2  371.29  4937.4  368.97
  4981.9  369.59  4988.2  369.07  4995.3  366.22  4995.8  365.42  5001.4  366.22
  5006.0  368.61  5015.8  369.99  5145.2  368.39  5242.8  371.29  5431.1  379.32
  5458.1  378.26  5466.5  380.41  5481.2  379.54  5487.4  382.38  5502.0  380.19
  5508.2  383.18  5566.7  386.61  5658.5  397.02  5741.3  400.74  5747.1  400.85
#Mann=5,-1,0
  4344.5    0.05       0  4397.8    0.16       0  4995.3    0.07       0
  5001.4    0.16       0  5741.3    0.05       0
Bank Sta=4914.2,5242.8
Exp/Cntr=0.3,0.1

Type RM Length L Ch R = 1,6848,555,555,555
BEGIN DESCRIPTION:
CLARK BRANCH 9.0
END DESCRIPTION:
XS GIS Cut Line= 3
      2880475.00      6981225.00      2881025.00      6980975.00
      2881475.01      6980424.99
#Sta/Elev= 30
  4390.3  413.60  4467.2  406.75  4489.2  402.16  4533.1  389.07  4594.6  378.24
  4640.7  373.72  4739.4  369.24  4807.7  366.84  4878.5  367.43  4980.2  367.53
  4982.6  364.61  4983.1  363.81  4988.8  364.61  4991.7  365.84  5008.1  365.04
  5016.0  367.54  5044.7  365.74  5059.1  366.10  5081.0  369.24  5122.9  375.16
  5129.4  374.53  5158.1  378.44  5164.6  377.44  5175.6  378.83  5222.0  382.96
  5292.3  387.27  5422.0  389.33  5522.3  393.22  5537.3  394.01  5705.1  405.01
#Mann=8,-1,0
  4390.3    0.16       0  4878.5    0.12       0  4982.6    0.07       0
  4988.8    0.12       0  5175.6    0.16       0  5422.0    0.05       0
  5522.3    0.16       0  5537.3    0.05       0
Bank Sta=4739.4,5081
Exp/Cntr=0.3,0.1

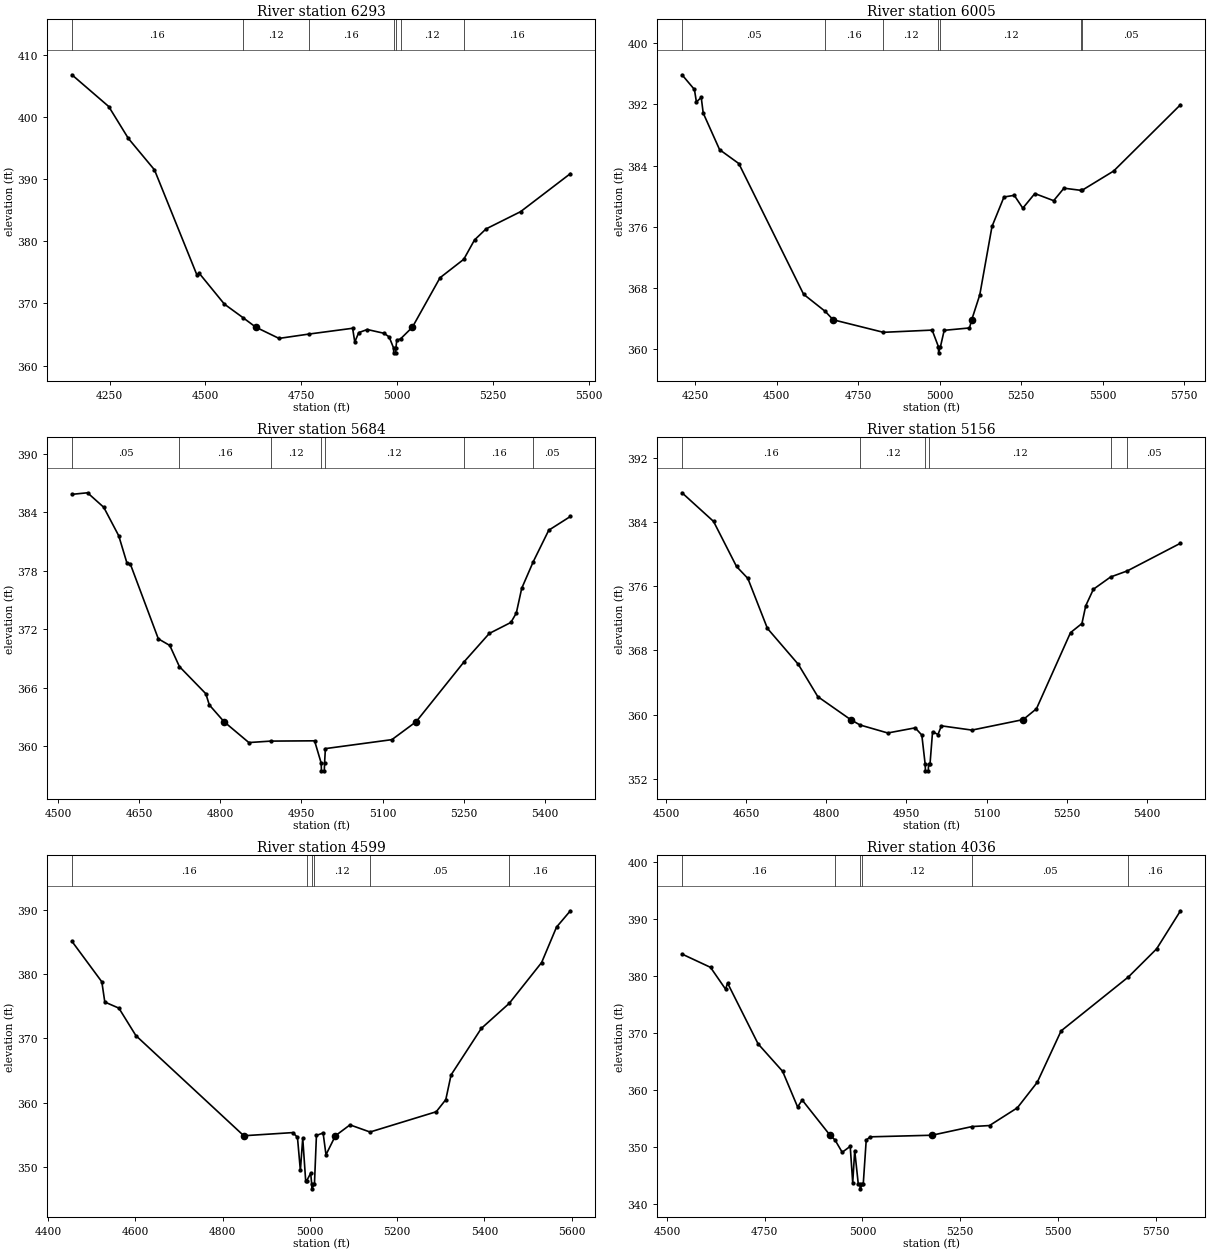
Type RM Length L Ch R = 1,6293,288,288,288
BEGIN DESCRIPTION:
CLARK BRANCH 8.0
END DESCRIPTION:
XS GIS Cut Line= 3
      2880724.99      6981575.01      2881475.00      6981175.00
      2881475.00      6980725.01
#Sta/Elev= 30
  4151.9  406.75  4247.9  401.65  4299.2  396.51  4367.2  391.47  4478.1  374.54
  4483.8  374.85  4549.6  369.88  4598.0  367.71  4631.4  366.18  4692.0  364.37
  4770.2  365.07  4884.0  366.00  4889.6  363.79  4899.9  365.30  4922.2  365.80
  4966.1  365.19  4979.2  364.61  4990.7  362.85  4991.2  362.05  4996.4  362.05
  4996.9  362.85  4999.1  364.08  5008.9  364.29  5039.9  366.18  5111.9  374.12
  5173.9  377.09  5201.9  380.20  5231.9  381.97  5321.9  384.74  5451.9  390.86
#Mann=7,-1,0
  4151.9    0.16       0  4598.0    0.12       0  4770.2    0.16       0
  4990.7    0.07       0  4996.9    0.16       0  5008.9    0.12       0
  5173.9    0.16       0
Bank Sta=4631.4,5039.9
Exp/Cntr=0.3,0.1

Type RM Length L Ch R = 1,6005,321,321,321
BEGIN DESCRIPTION:
Mapping XS c5c90afe
END DESCRIPTION:
XS GIS Cut Line= 3
      2881245.35      6981917.60      2881731.45      6981244.00
      2881953.67      6980580.82
#Sta/Elev= 30
  4209.0  395.86  4247.1  393.94  4253.2  392.31  4268.0  392.90  4274.1  390.86
  4324.4  386.08  4383.3  384.27  4582.2  367.20  4649.0  364.95  4672.8  363.87
  4827.2  362.23  4976.8  362.52  4996.1  360.35  4996.6  359.55  5002.3  360.35
  5013.8  362.49  5091.4  362.80  5098.3  363.87  5123.0  367.12  5160.5  376.05
  5197.3  379.90  5228.8  380.12  5255.1  378.44  5292.0  380.35  5349.8  379.42
  5381.4  381.05  5435.2  380.76  5436.0  380.75  5533.9  383.29  5739.1  391.95
#Mann=7,-1,0
  4209.0    0.05       0  4649.0    0.16       0  4827.2    0.12       0
  4996.1    0.07       0  5002.3    0.12       0  5435.2    0.16       0
  5436.0    0.05       0
Bank Sta=4672.8,5098.3
Exp/Cntr=0.3,0.1

Type RM Length L Ch R = 1,5684,528,528,528
BEGIN DESCRIPTION:
CLARK BRANCH 7.0
END DESCRIPTION:
XS GIS Cut Line= 3
      2882224.98      6981774.97      2881975.00      6981375.00
      2881975.00      6980924.97
#Sta/Elev= 30
  4525.6  385.82  4554.5  385.98  4584.5  384.49  4612.2  381.57  4627.6  378.73
  4633.5  378.69  4685.4  371.00  4706.6  370.32  4724.3  368.16  4773.2  365.37
  4779.7  364.22  4806.9  362.50  4852.8  360.36  4893.2  360.51  4974.3  360.54
  4986.5  358.26  4987.0  357.46  4992.3  357.46  4992.8  358.26  4994.3  359.74
  5117.3  360.66  5162.1  362.50  5250.4  368.62  5297.3  371.55  5337.3  372.68
  5347.3  373.64  5357.3  376.18  5378.8  378.93  5407.3  382.14  5447.3  383.55
#Mann=7,-1,0
  4525.6    0.05       0  4724.3    0.16       0  4893.2    0.12       0
  4986.5    0.07       0  4992.8    0.12       0  5250.4    0.16       0
  5378.8    0.05       0
Bank Sta=4806.9,5162.1
Exp/Cntr=0.3,0.1

Type RM Length L Ch R = 1,5156,557,557,557
BEGIN DESCRIPTION:
CLARK BRANCH 6.0
END DESCRIPTION:
XS GIS Cut Line= 3
      2882675.01      6981675.02      2882425.00      6981275.00
      2882075.00      6980975.00
#Sta/Elev= 30
  4530.0  387.65  4589.0  384.08  4632.0  378.46  4653.2  376.97  4689.8  370.74
  4747.6  366.26  4784.1  362.23  4845.4  359.37  4863.0  358.70  4915.0  357.70
  4966.3  358.34  4978.7  357.44  4985.0  353.78  4985.5  352.98  4990.8  352.98
  4991.3  353.78  4994.1  353.88  4998.8  357.86  5008.9  357.51  5015.4  358.59
  5072.5  358.06  5168.4  359.37  5193.2  360.72  5256.9  370.21  5278.3  371.35
  5285.4  373.56  5299.7  375.62  5331.9  377.15  5363.2  377.91  5462.7  381.36
#Mann=6,-1,0
  4530.0    0.16       0  4863.0    0.12       0  4985.0    0.07       0
  4991.3    0.12       0  5331.9    0.16       0  5363.2    0.05       0
Bank Sta=4845.4,5168.4
Exp/Cntr=0.3,0.1

Type RM Length L Ch R = 1,4599,563,563,563
BEGIN DESCRIPTION:
CLARK BRANCH 5.0
END DESCRIPTION:
XS GIS Cut Line= 3
      2882725.01      6981624.98      2882925.00      6981125.00
      2883174.98      6980575.04
#Sta/Elev= 30
  4454.6  385.09  4523.2  378.79  4530.0  375.65  4562.3  374.70  4601.3  370.43
  4848.6  354.87  4960.8  355.36  4971.6  354.63  4978.3  349.47  4983.7  354.50
  4990.4  347.90  4993.0  347.90  5001.9  349.05  5004.2  347.42  5004.7  346.62
  5010.6  347.42  5015.1  354.92  5030.4  355.30  5037.0  351.92  5058.6  354.87
  5092.0  356.56  5138.0  355.45  5289.7  358.60  5311.6  360.48  5323.7  364.32
  5392.9  371.54  5457.1  375.45  5531.3  381.79  5565.4  387.29  5597.2  389.83
#Mann=6,-1,0
  4454.6    0.16       0  4993.0    0.12       0  5004.2    0.07       0
  5010.6    0.12       0  5138.0    0.05       0  5457.1    0.16       0
Bank Sta=4848.6,5058.6
Exp/Cntr=0.3,0.1

Type RM Length L Ch R = 1,4036,337,337,337
BEGIN DESCRIPTION:
CLARK BRANCH 4.0
END DESCRIPTION:
XS GIS Cut Line= 3
      2883474.99      6981824.96      2883375.00      6981375.00
      2883225.00      6980574.97
#Sta/Elev= 30
  4538.5  383.86  4611.4  381.53  4649.9  377.70  4655.0  378.77  4733.1  368.11
  4795.8  363.30  4834.2  357.04  4845.8  358.27  4917.1  352.09  4929.7  351.27
  4948.2  349.10  4968.7  350.14  4975.1  343.76  4980.2  349.40  4989.2  343.61
  4993.6  343.49  4994.1  342.69  5000.1  343.49  5002.0  343.49  5009.6  351.23
  5019.8  351.81  5177.8  352.09  5280.4  353.61  5325.0  353.79  5396.2  356.90
  5447.1  361.38  5508.1  370.39  5680.4  379.86  5752.3  384.77  5813.4  391.45
#Mann=6,-1,0
  4538.5    0.16       0  4929.7    0.12       0  4993.6    0.07       0
  5000.1    0.12       0  5280.4    0.05       0  5680.4    0.16       0
Bank Sta=4917.1,5177.8
Exp/Cntr=0.3,0.1

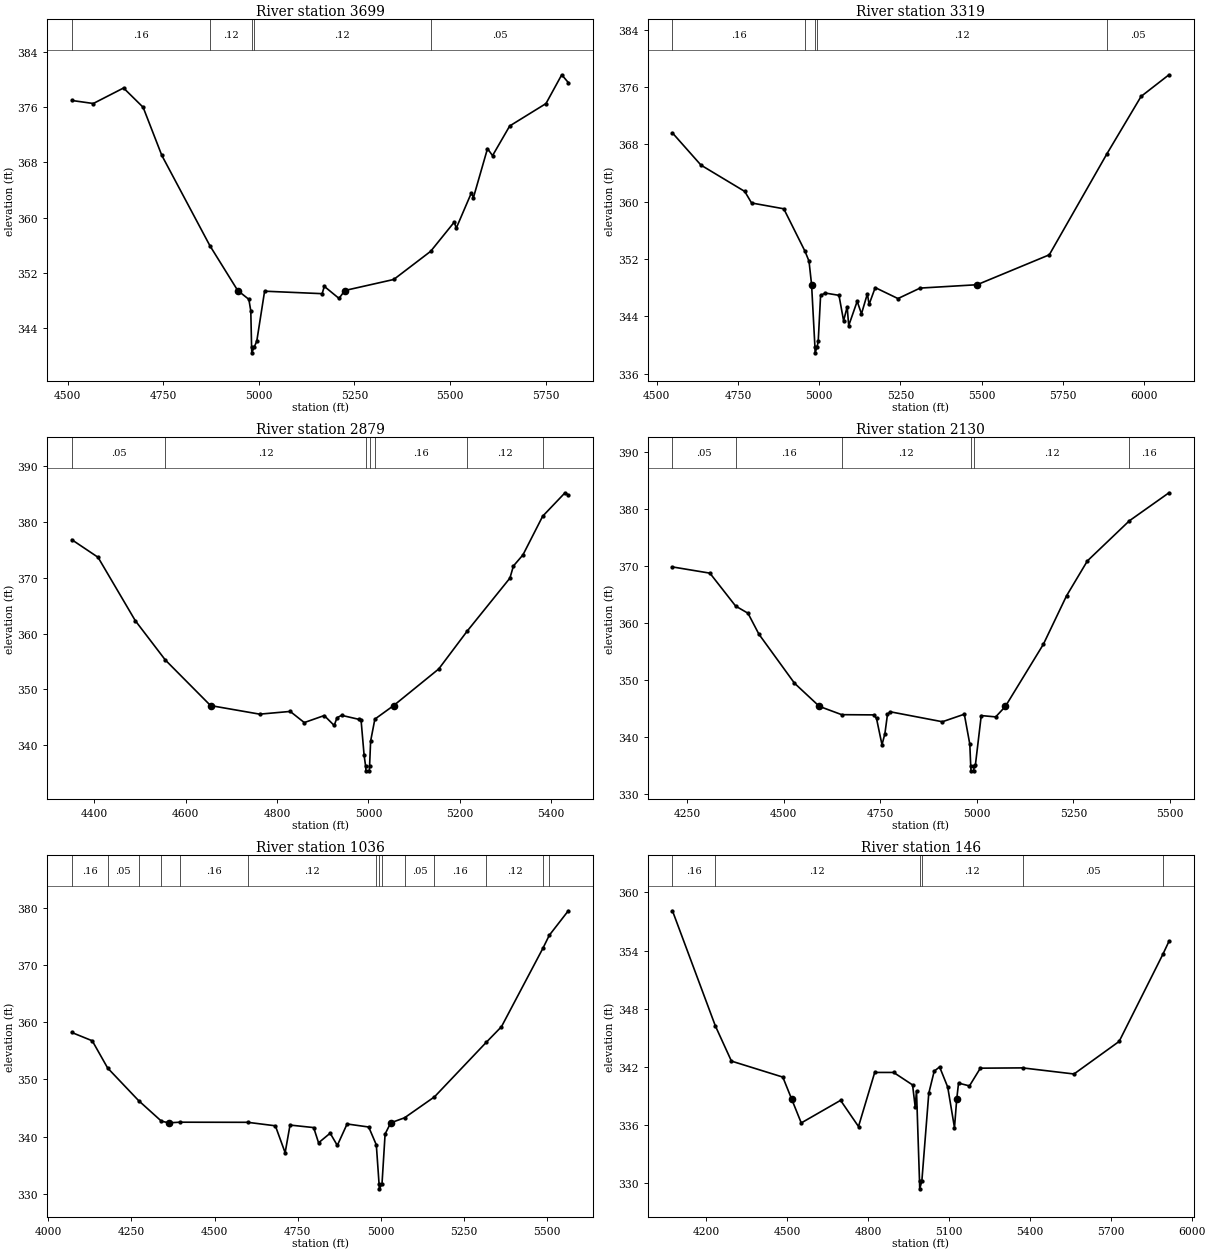
Type RM Length L Ch R = 1,3699,380,380,380
BEGIN DESCRIPTION:
Mapping XS f88b2df4
END DESCRIPTION:
XS GIS Cut Line= 3
      2883568.25      6981987.07      2883710.62      6981348.17
      2883579.07      6980718.12
#Sta/Elev= 30
  4511.0  377.00  4567.2  376.56  4646.3  378.81  4697.5  376.01  4746.3  369.03
  4872.0  355.92  4944.8  349.41  4973.9  348.13  4979.0  346.45  4981.1  341.16
  4981.6  340.36  4987.6  341.16  4994.6  342.04  5015.1  349.31  5165.6  348.95
  5171.2  350.01  5209.7  348.26  5224.9  349.41  5352.7  351.01  5449.3  355.10
  5511.0  359.34  5516.2  358.46  5555.9  363.60  5561.1  362.90  5597.9  370.01
  5611.1  368.99  5656.0  373.30  5750.8  376.55  5792.0  380.73  5809.2  379.60
#Mann=5,-1,0
  4511.0    0.16       0  4872.0    0.12       0  4981.1    0.07       0
  4987.6    0.12       0  5449.3    0.05       0
Bank Sta=4944.8,5224.9
Exp/Cntr=0.3,0.1

Type RM Length L Ch R = 1,3319,440,440,440
BEGIN DESCRIPTION:
CLARK BRANCH 3.0
END DESCRIPTION:
XS GIS Cut Line= 3
      2883613.41      6982087.73      2883981.45      6981698.87
      2883662.37      6980758.97
#Sta/Elev= 30
  4548.2  369.59  4636.0  365.10  4770.7  361.43  4791.7  359.82  4890.8  359.01
  4956.3  353.07  4968.5  351.70  4976.4  348.42  4986.7  339.72  4987.2  338.92
  4993.2  339.72  4996.8  340.54  5004.1  346.92  5018.3  347.26  5060.7  346.94
  5074.9  343.39  5085.9  345.34  5090.6  342.71  5116.7  346.11  5129.9  344.36
  5148.1  347.16  5153.3  345.67  5172.2  348.02  5242.2  346.49  5310.3  347.95
  5485.8  348.42  5707.9  352.59  5885.7  366.71  5990.4  374.68  6076.2  377.70
#Mann=5,-1,0
  4548.2    0.16       0  4956.3    0.12       0  4986.7    0.07       0
  4993.2    0.12       0  5885.7    0.05       0
Bank Sta=4976.4,5485.8
Exp/Cntr=0.3,0.1

Type RM Length L Ch R = 1,2879,749,749,749
BEGIN DESCRIPTION:
CLARK BRANCH 2.0
END DESCRIPTION:
XS GIS Cut Line= 3
      2883925.01      6982374.98      2884225.00      6981825.00
      2884525.03      6981474.97
#Sta/Elev= 30
  4350.4  376.85  4407.8  373.70  4489.4  362.33  4555.2  355.27  4654.3  347.09
  4761.9  345.55  4828.8  346.04  4859.6  344.04  4903.3  345.30  4925.1  343.52
  4931.3  344.91  4941.3  345.34  4980.2  344.60  4984.0  344.46  4990.6  338.21
  4994.0  336.18  4994.7  335.38  5001.8  335.38  5002.6  336.18  5004.9  340.71
  5014.2  344.66  5055.3  347.09  5154.1  353.66  5216.3  360.44  5310.0  369.96
  5317.7  372.14  5338.5  374.12  5381.8  381.07  5430.7  385.27  5437.9  384.87
#Mann=7,-1,0
  4350.4    0.05       0  4555.2    0.12       0  4994.0    0.07       0
  5002.6    0.12       0  5014.2    0.16       0  5216.3    0.12       0
  5381.8    0.16       0
Bank Sta=4654.3,5055.3
Exp/Cntr=0.3,0.1

Type RM Length L Ch R = 1,2130,1094,1094,1094
BEGIN DESCRIPTION:
Mapping XS 5e6e4ced
END DESCRIPTION:
XS GIS Cut Line= 3
      2884231.89      6982768.27      2884812.59      6982247.47
      2885002.44      6981779.33
#Sta/Elev= 30
  4212.2  369.81  4309.1  368.72  4375.8  362.95  4407.7  361.70  4436.1  358.02
  4528.1  349.44  4592.5  345.38  4650.3  343.93  4733.7  343.89  4740.4  343.26
  4754.6  338.66  4762.1  340.60  4768.8  343.99  4776.3  344.43  4910.9  342.69
  4967.7  344.01  4981.9  338.76  4984.3  334.89  4985.0  334.09  4992.1  334.09
  4992.9  334.89  4996.3  335.07  5011.5  343.77  5048.9  343.54  5074.0  345.38
  5172.3  356.26  5232.3  364.75  5286.3  370.87  5394.9  377.89  5497.4  382.80
#Mann=6,-1,0
  4212.2    0.05       0  4375.8    0.16       0  4650.3    0.12       0
  4984.3    0.07       0  4992.9    0.12       0  5394.9    0.16       0
Bank Sta=4592.5,5074
Exp/Cntr=0.3,0.1

Type RM Length L Ch R = 1,1036,890,890,890
BEGIN DESCRIPTION:
Mapping XS 0170bccd
END DESCRIPTION:
XS GIS Cut Line= 3
      2884619.84      6982955.83      2885385.51      6982401.12
      2885411.55      6981854.22
#Sta/Elev= 30
  4070.6  358.20  4132.1  356.75  4178.4  351.99  4271.5  346.30  4340.0  342.71
  4362.2  342.42  4395.9  342.53  4599.6  342.51  4682.7  341.90  4712.1  337.20
  4726.8  342.03  4797.9  341.59  4812.6  338.93  4847.5  340.61  4869.0  338.47
  4898.4  342.22  4963.4  341.69  4986.3  338.57  4994.6  331.69  4995.4  330.89
  5003.3  331.69  5012.7  340.47  5029.6  342.42  5071.2  343.30  5161.2  346.96
  5317.0  356.49  5362.6  359.21  5487.3  372.92  5506.4  375.18  5563.6  379.46
#Mann=14,-1,0
  4070.6    0.16       0  4178.4    0.05       0  4271.5    0.16       0
  4340.0    0.05       0  4395.9    0.16       0  4599.6    0.12       0
  4986.3    0.16       0  4994.6    0.07       0  5003.3    0.16       0
  5071.2    0.05       0  5161.2    0.16       0  5317.0    0.12       0
  5487.3    0.16       0  5506.4     0.1       0
Bank Sta=4362.2,5029.6
Exp/Cntr=0.3,0.1

Type RM Length L Ch R = 1,146,0,0,0
BEGIN DESCRIPTION:
CLARK BRANCH 1.0
END DESCRIPTION:
XS GIS Cut Line= 3
      2884606.84      6982974.03      2885650.00      6982900.00
      2885757.90      6982112.04
#Sta/Elev= 30
  4074.7  358.11  4233.8  346.23  4293.4  342.60  4483.9  340.95  4516.3  338.71
  4552.3  336.22  4698.1  338.55  4764.6  335.85  4824.7  341.43  4894.9  341.43
  4965.1  340.14  4974.7  337.89  4979.7  339.53  4990.8  330.22  4991.6  329.42
  4999.5  330.22  5025.2  339.28  5045.3  341.56  5065.3  342.00  5095.4  339.92
  5120.5  335.73  5128.9  338.71  5135.6  340.33  5176.0  340.04  5216.4  341.87
  5373.0  341.90  5563.7  341.27  5731.1  344.63  5893.4  353.63  5915.8  354.96
#Mann=6,-1,0
  4074.7    0.16       0  4233.8    0.12       0  4990.8    0.07       0
  4999.5    0.12       0  5373.0    0.05       0  5893.4    0.16       0
Bank Sta=4516.3,5128.9
Exp/Cntr=0.3,0.1

Chan Stop Cuts=-1