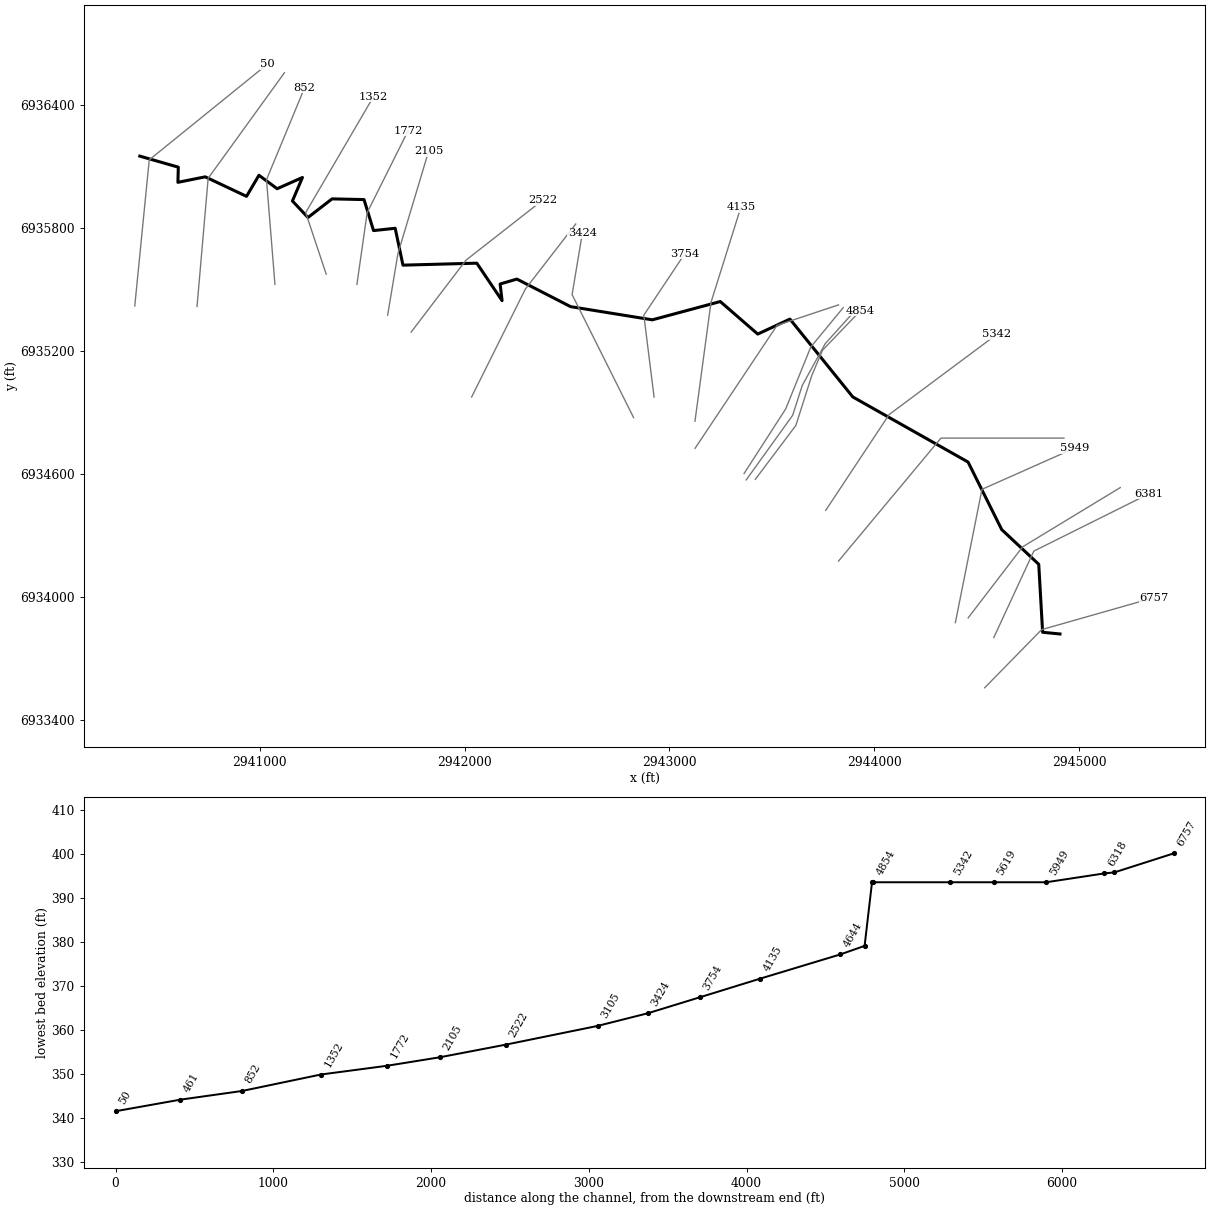
--- COWAN BRANCH.prj (project) ---

Proj Title=COWAN BRANCH Base Level Engineering
Current Plan=p01
Default Exp/Contr=0.3,0.1
English Units
Geom File=g01
Flow File=f01
Plan File=p01
BEGIN DESCRIPTION:
COWAN BRANCH
END DESCRIPTION:

--- COWAN BRANCH.p01 (plan) ---

Plan Title=Multiple Run
Short Identifier=Multiple
Geom File=g01
Flow File=f01
Subcritical Flow
K Sum by GR= 0
Std Step Tol= 0.01
Critical Tol= 0.01
Num of Std Step Trials= 20
Max Error Tol= 0.3
Flow Tol Ratio= 0.001
Split Flow NTrial= 30
Split Flow Tol= 0.02
Split Flow Ratio= 0.02
Log Output Level= 0
Friction Slope Method= 1
Unsteady Friction Slope Method= 2
Unsteady Bridges Friction Slope Method= 1
Parabolic Critical Depth
Global Vel Dist=  1 , 1 , 1
Global Log Level= 0
CheckData=True
Encroach Param= -1, 0, 0, 0
BEGIN DESCRIPTION:
Multiple Run
END DESCRIPTION:

--- COWAN BRANCH.f01 (steady flow) ---

Flow Title=Multiple
Number of Profiles=7
Profile Names=10-year,25-year,50-year,1pct_min,100-year,1pct_plu,500-year
River Rch & RM= COWAN BRANCH,Reach-1,6757
     469     629     760     459     915    1826    1325
River Rch & RM= COWAN BRANCH,Reach-1,4854
     673     922    1129     689    1375    2743    2038
Boundary for River Rch & Prof#=COWAN BRANCH,Reach-1,1
Up Type=0
Dn Type=3
Dn Slope=0.005
Boundary for River Rch & Prof#=COWAN BRANCH,Reach-1,2
Up Type=0
Dn Type=3
Dn Slope=0.005
Boundary for River Rch & Prof#=COWAN BRANCH,Reach-1,3
Up Type=0
Dn Type=3
Dn Slope=0.005
Boundary for River Rch & Prof#=COWAN BRANCH,Reach-1,4
Up Type=0
Dn Type=3
Dn Slope=0.005
Boundary for River Rch & Prof#=COWAN BRANCH,Reach-1,5
Up Type=0
Dn Type=3
Dn Slope=0.005
Boundary for River Rch & Prof#=COWAN BRANCH,Reach-1,6
Up Type=0
Dn Type=3
Dn Slope=0.005
Boundary for River Rch & Prof#=COWAN BRANCH,Reach-1,7
Up Type=0
Dn Type=3
Dn Slope=0.005

--- COWAN BRANCH.g01 (geometry) ---

Geom Title=Existing Conditions

River Reach=COWAN BRANCH,Reach-1
Reach XY= 30
      2944905.71      6933819.21      2944820.96      6933827.61
      2944802.00      6934159.29      2944621.37      6934328.53
      2944457.18      6934658.07      2943894.68      6934975.77
      2943587.90      6935355.62      2943430.83      6935282.48
      2943247.99      6935441.23      2942916.34      6935352.00
      2942517.57      6935416.34      2942255.58      6935550.83
      2942173.82      6935526.79      2942183.22      6935445.66
      2942059.97      6935628.43      2941699.66      6935618.77
      2941661.75      6935798.69      2941556.05      6935787.43
      2941509.66      6935938.75      2941353.64      6935942.14
      2941236.07      6935851.28      2941160.28      6935931.91
      2941209.22      6936046.50      2941085.72      6935991.69
      2940996.91      6936057.33      2940936.32      6935954.43
      2940734.72      6936049.66      2940601.54      6936022.88
      2940603.45      6936096.80      2940415.59      6936150.71

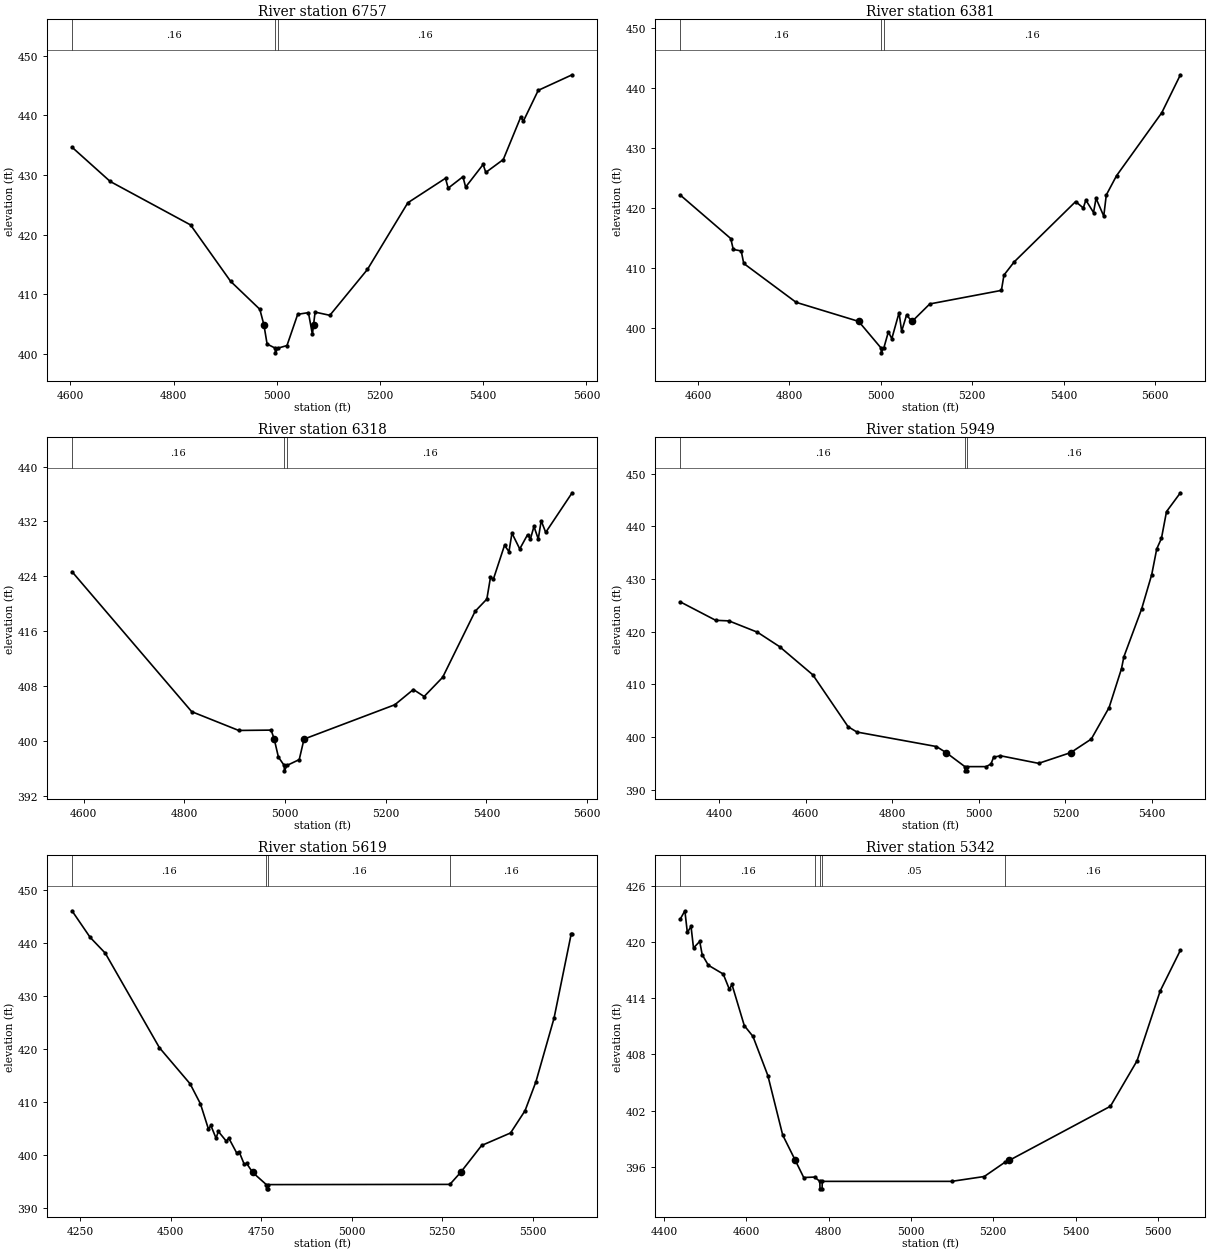
Type RM Length L Ch R = 1,6757,376,376,376
BEGIN DESCRIPTION:
COWAN BRANCH 16.0
END DESCRIPTION:
XS GIS Cut Line= 3
      2944538.36      6933556.88      2944816.07      6933840.44
      2945366.53      6933997.02
#Sta/Elev= 30
  4603.1  434.65  4677.2  428.90  4832.8  421.62  4910.5  412.16  4967.1  407.47
  4975.0  404.87  4981.2  401.64  4996.7  400.97  4997.2  400.17  5002.7  400.97
  5019.7  401.39  5040.5  406.63  5061.3  406.91  5069.0  403.26  5071.2  404.87
  5074.2  407.00  5102.8  406.46  5175.6  414.15  5253.9  425.33  5326.9  429.44
  5332.1  427.78  5360.7  429.70  5365.9  427.96  5399.8  431.75  5405.0  430.42
  5438.9  432.58  5472.7  439.70  5477.9  439.03  5506.6  444.18  5572.3  446.79
#Mann=3,-1,0
  4603.1    0.16       0  4996.7    0.07       0  5002.7    0.16       0
Bank Sta=4975,5071.2
Exp/Cntr=0.3,0.1

Type RM Length L Ch R = 1,6381,63,63,63
BEGIN DESCRIPTION:
Mapping XS cbf5263a
END DESCRIPTION:
XS GIS Cut Line= 3
      2944582.66      6933801.70      2944777.97      6934223.58
      2945341.53      6934504.06
#Sta/Elev= 30
  4561.4  422.16  4671.9  414.91  4677.4  413.10  4694.8  412.84  4700.3  410.76
  4814.9  404.28  4951.8  401.10  5000.8  396.66  5001.3  395.86  5006.8  396.66
  5016.8  399.36  5024.3  398.22  5040.2  402.56  5045.8  399.45  5056.5  402.14
  5068.7  401.10  5107.4  404.01  5264.1  406.27  5269.7  408.82  5292.1  411.02
  5426.5  421.07  5443.3  420.01  5448.9  421.32  5465.7  419.25  5471.2  421.61
  5488.1  418.65  5493.6  422.17  5516.0  425.38  5615.0  435.88  5655.8  442.21
#Mann=3,-1,0
  4561.4    0.16       0  5000.8    0.07       0  5006.8    0.16       0
Bank Sta=4951.8,5068.7
Exp/Cntr=0.3,0.1

Type RM Length L Ch R = 1,6318,369,369,369
BEGIN DESCRIPTION:
Mapping XS fd999253
END DESCRIPTION:
XS GIS Cut Line= 3
      2944457.66      6933898.06      2944723.28      6934244.41
      2945199.88      6934533.50
#Sta/Elev= 30
  4576.6  424.68  4814.5  404.26  4907.9  401.52  4972.3  401.57  4978.5  400.26
  4986.8  397.63  4998.2  396.43  4998.7  395.63  5004.2  396.43  5028.2  397.27
  5037.7  400.26  5218.2  405.27  5255.0  407.49  5276.4  406.47  5313.2  409.27
  5377.7  418.89  5401.0  420.68  5408.2  423.84  5414.0  423.58  5436.1  428.51
  5445.0  427.60  5450.9  430.29  5466.4  427.99  5481.8  430.05  5487.7  429.46
  5494.6  431.27  5503.2  429.44  5509.0  432.10  5518.0  430.40  5570.5  436.18
#Mann=3,-1,0
  4576.6    0.16       0  4998.2    0.07       0  5004.2    0.16       0
Bank Sta=4978.5,5037.7
Exp/Cntr=0.3,0.1

Type RM Length L Ch R = 1,5949,330,330,330
BEGIN DESCRIPTION:
COWAN BRANCH 15.0
END DESCRIPTION:
XS GIS Cut Line= 3
      2944395.17      6933874.67      2944525.00      6934525.00
      2944974.99      6934725.00
#Sta/Elev= 30
  4310.3  425.67  4392.2  422.17  4422.8  422.06  4488.7  419.91  4539.7  417.18
  4616.6  411.83  4698.1  401.99  4718.5  400.98  4902.1  398.23  4924.6  397.08
  4967.9  394.42  4968.4  393.62  4973.4  393.62  4973.9  394.42  5017.2  394.42
  5028.2  394.93  5034.3  396.20  5050.1  396.48  5138.3  395.04  5212.5  397.08
  5260.0  399.65  5301.1  405.62  5329.8  413.00  5335.3  415.26  5376.3  424.32
  5399.6  430.83  5411.2  435.71  5422.1  437.72  5433.8  442.79  5465.9  446.36
#Mann=3,-1,0
  4310.3    0.16       0  4967.9    0.07       0  4973.9    0.16       0
Bank Sta=4924.6,5212.5
Exp/Cntr=0.3,0.1

Type RM Length L Ch R = 1,5619,277,277,277
BEGIN DESCRIPTION:
COWAN BRANCH 14.0
END DESCRIPTION:
XS GIS Cut Line= 3
      2943824.99      6934174.99      2944325.00      6934775.00
      2944924.96      6934775.00
#Sta/Elev= 30
  4227.9  446.16  4278.0  441.14  4319.7  438.16  4469.4  420.28  4554.0  413.47
  4582.6  409.68  4604.8  404.89  4611.3  405.60  4625.6  403.20  4632.1  404.46
  4654.2  402.61  4660.7  403.22  4682.9  400.37  4689.4  400.62  4703.7  398.23
  4710.2  398.42  4726.8  396.72  4764.5  394.42  4765.0  393.62  4770.0  393.62
  4770.5  394.42  5271.3  394.46  5300.9  396.72  5358.9  401.81  5438.9  404.18
  5478.9  408.39  5508.9  413.85  5558.9  425.86  5606.4  441.81  5608.9  441.81
#Mann=4,-1,0
  4227.9    0.16       0  4764.5   0.033       0  4770.5    0.16       0
  5271.3    0.16       0
Bank Sta=4726.8,5300.9
Exp/Cntr=0.3,0.1

Type RM Length L Ch R = 1,5342,488,488,488
BEGIN DESCRIPTION:
COWAN BRANCH 13.0
END DESCRIPTION:
XS GIS Cut Line= 3
      2943762.60      6934422.53      2944072.09      6934889.95
      2944597.23      6935280.93
#Sta/Elev= 30
  4439.4  422.49  4450.6  423.38  4456.6  421.06  4465.6  421.70  4471.6  419.40
  4486.7  420.10  4492.7  418.68  4507.7  417.55  4543.8  416.61  4558.9  414.96
  4564.9  415.51  4595.0  411.09  4616.0  409.94  4652.2  405.75  4688.3  399.38
  4719.0  396.66  4739.4  394.83  4765.9  394.88  4778.5  394.42  4779.0  393.62
  4784.0  393.62  4784.5  394.42  5098.8  394.42  5178.1  394.94  5228.1  396.46
  5238.5  396.66  5484.7  402.46  5549.3  407.32  5605.6  414.80  5654.7  419.16
#Mann=5,-1,0
  4439.4    0.16       0  4765.9    0.05       0  4778.5   0.033       0
  4784.5    0.05       0  5228.1    0.16       0
Bank Sta=4719,5238.5
Exp/Cntr=0.3,0.1

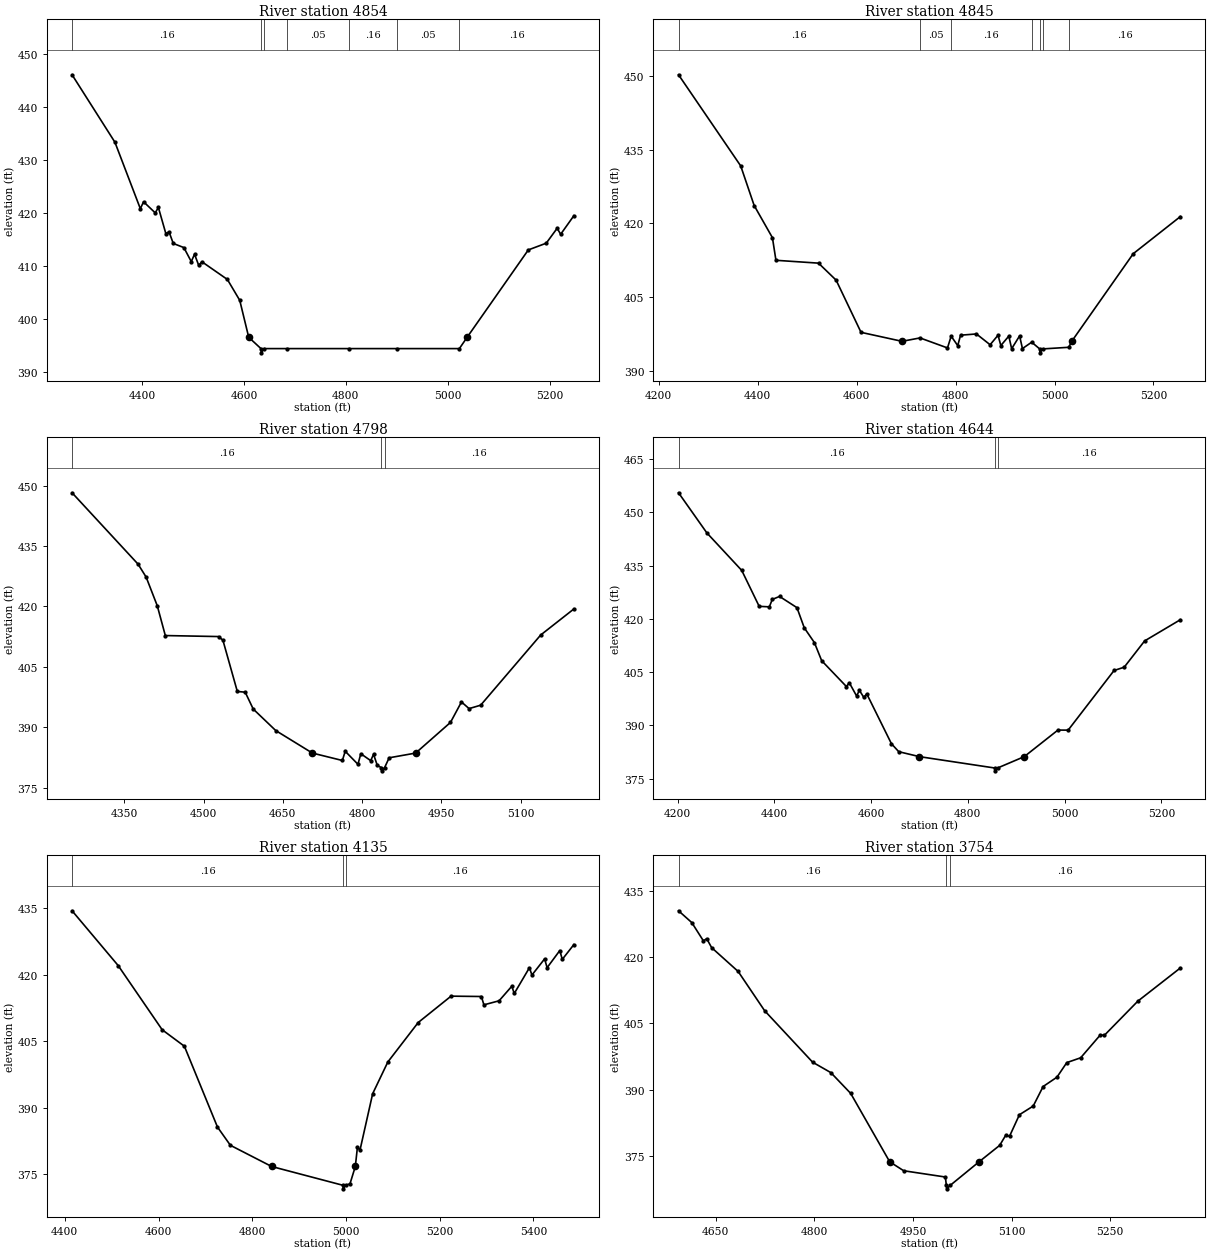
Type RM Length L Ch R = 1,4854,9,9,9
BEGIN DESCRIPTION:
Mapping XS 6a1c158f
END DESCRIPTION:
XS GIS Cut Line= 5
      2943418.87      6934573.60      2943616.77      6934836.60
      2943694.90      6935081.39      2943746.98      6935203.79
      2943930.92      6935395.50
#Sta/Elev= 30
  4262.8  446.06  4346.9  433.34  4396.8  420.80  4403.1  422.11  4426.0  420.02
  4432.2  421.04  4446.8  416.12  4453.1  416.44  4461.4  414.25  4482.2  413.47
  4496.8  410.82  4503.1  412.22  4511.4  410.11  4517.6  410.80  4567.6  407.46
  4591.9  403.52  4609.5  396.55  4633.5  394.42  4634.0  393.62  4639.5  394.42
  4683.7  394.42  4806.4  394.42  4900.9  394.42  5022.9  394.42  5038.1  396.55
  5158.2  413.03  5193.4  414.30  5214.8  417.11  5221.7  415.98  5247.6  419.48
#Mann=7,-1,0
  4262.8    0.16       0  4633.5   0.035       0  4639.5    0.16       0
  4683.7    0.05       0  4806.4    0.16       0  4900.9    0.05       0
  5022.9    0.16       0
Bank Sta=4609.5,5038.1
Exp/Cntr=0.3,0.1

Type RM Length L Ch R = 1,4845,47,47,47
BEGIN DESCRIPTION:
Mapping XS 50486fd4
END DESCRIPTION:
XS GIS Cut Line= 5
      2943374.56      6934570.94      2943601.15      6934886.08
      2943648.02      6935031.91      2943759.91      6935235.46
      2943920.71      6935413.90
#Sta/Elev= 30
  4240.4  450.32  4366.0  431.74  4393.2  423.66  4430.1  417.10  4437.2  412.49
  4523.2  411.91  4558.8  408.44  4609.1  397.80  4691.9  395.97  4728.3  396.66
  4783.8  394.62  4791.2  397.02  4804.5  395.09  4810.2  397.22  4842.3  397.47
  4869.9  395.27  4885.9  397.21  4891.6  395.11  4907.7  397.03  4913.4  394.46
  4929.5  397.08  4935.2  394.49  4953.9  395.79  4970.1  394.42  4970.6  393.62
  4976.1  394.42  5028.8  394.75  5034.8  395.97  5159.1  413.84  5254.2  421.40
#Mann=7,-1,0
  4240.4    0.16       0  4728.3    0.05       0  4791.2    0.16       0
  4953.9    0.05       0  4970.1   0.035       0  4976.1    0.05       0
  5028.8    0.16       0
Bank Sta=4691.9,5034.8
Exp/Cntr=0.3,0.1

Type RM Length L Ch R = 1,4798,154,154,154
BEGIN DESCRIPTION:
Mapping XS 9ac466e3
END DESCRIPTION:
XS GIS Cut Line= 4
      2943364.16      6934602.22      2943567.29      6934917.33
      2943689.69      6935219.41      2943847.66      6935411.05
#Sta/Elev= 30
  4251.3  448.21  4376.2  430.48  4391.4  427.28  4412.5  420.14  4427.7  412.76
  4528.3  412.51  4536.6  411.62  4563.9  398.88  4578.8  398.70  4594.0  394.51
  4636.6  389.17  4705.9  383.58  4762.6  381.74  4768.0  384.03  4792.1  380.79
  4797.5  383.42  4816.2  381.70  4821.6  383.28  4828.7  380.50  4836.5  379.97
  4837.0  379.17  4842.5  379.97  4851.1  382.41  4901.2  383.58  4967.1  391.19
  4987.9  396.27  5002.3  394.62  5024.2  395.47  5137.8  412.90  5200.5  419.36
#Mann=3,-1,0
  4251.3    0.16       0  4836.5    0.07       0  4842.5    0.16       0
Bank Sta=4705.9,4901.2
Exp/Cntr=0.3,0.1

Type RM Length L Ch R = 1,4644,509,509,509
BEGIN DESCRIPTION:
COWAN BRANCH 11.0
END DESCRIPTION:
XS GIS Cut Line= 3
      2943125.03      6934725.04      2943525.00      6935325.00
      2943825.01      6935425.00
#Sta/Elev= 30
  4201.9  455.46  4260.4  444.18  4332.6  433.61  4368.6  423.51  4389.6  423.37
  4395.7  425.45  4410.7  426.30  4446.7  423.14  4461.8  417.47  4482.8  413.30
  4497.8  408.22  4548.9  400.95  4554.9  402.01  4569.9  398.31  4575.9  399.86
  4584.9  397.89  4591.0  398.89  4642.0  384.86  4657.1  382.62  4700.0  381.22
  4855.4  378.03  4855.9  377.23  4861.4  378.03  4916.5  381.22  4986.2  388.70
  5007.3  388.68  5102.2  405.46  5123.2  406.39  5165.4  413.78  5239.2  419.74
#Mann=3,-1,0
  4201.9    0.16       0  4855.4    0.07       0  4861.4    0.16       0
Bank Sta=4700,4916.5
Exp/Cntr=0.3,0.1

Type RM Length L Ch R = 1,4135,381,381,381
BEGIN DESCRIPTION:
COWAN BRANCH 10.0
END DESCRIPTION:
XS GIS Cut Line= 3
      2943124.59      6934857.48      2943202.59      6935436.75
      2943348.27      6935900.83
#Sta/Elev= 30
  4415.5  434.45  4513.9  422.09  4607.8  407.61  4655.2  403.89  4725.8  385.66
  4753.4  381.54  4841.5  376.76  4993.6  372.52  4994.1  371.72  4999.6  372.52
  5008.6  372.85  5020.0  376.76  5024.6  381.22  5029.8  380.38  5057.0  393.18
  5089.4  400.34  5154.2  409.24  5224.3  415.19  5289.1  415.11  5294.4  413.23
  5326.8  414.14  5354.0  417.43  5359.2  415.79  5391.6  421.61  5396.9  419.95
  5424.0  423.60  5429.3  421.61  5456.4  425.48  5461.7  423.49  5486.4  426.82
#Mann=3,-1,0
  4415.5    0.16       0  4993.6    0.07       0  4999.6    0.16       0
Bank Sta=4841.5,5020
Exp/Cntr=0.3,0.1

Type RM Length L Ch R = 1,3754,330,330,330
BEGIN DESCRIPTION:
COWAN BRANCH 9.0
END DESCRIPTION:
XS GIS Cut Line= 3
      2942925.00      6934974.98      2942875.00      6935375.00
      2943075.01      6935675.01
#Sta/Elev= 30
  4593.2  430.54  4613.4  427.86  4631.0  423.73  4636.1  424.21  4643.6  422.18
  4683.9  416.79  4724.2  407.89  4797.3  396.21  4825.0  393.85  4855.2  389.14
  4914.6  373.63  4935.9  371.60  4999.3  370.18  5000.8  368.30  5001.3  367.50
  5006.8  368.30  5050.6  373.63  5082.0  377.36  5091.0  379.61  5097.0  379.43
  5112.0  384.30  5133.0  386.27  5148.1  390.70  5169.1  392.81  5184.1  396.12
  5205.2  397.21  5235.2  402.40  5241.2  402.29  5292.3  410.06  5356.9  417.57
#Mann=3,-1,0
  4593.2    0.16       0  5000.8    0.07       0  5006.8    0.16       0
Bank Sta=4914.6,5050.6
Exp/Cntr=0.3,0.1

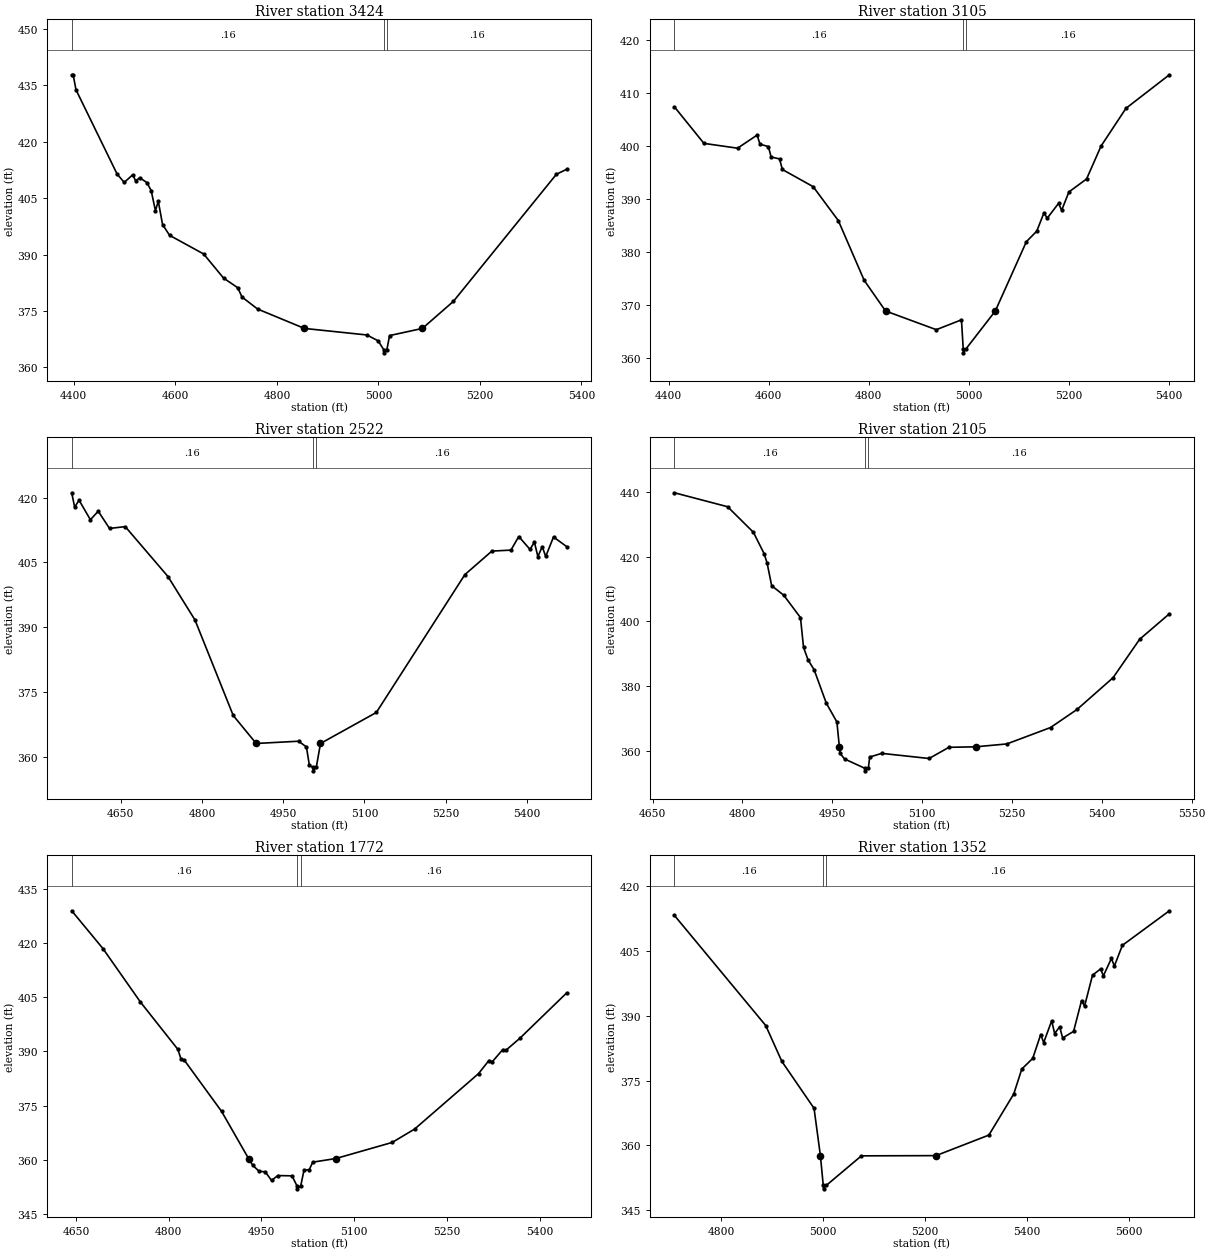
Type RM Length L Ch R = 1,3424,319,319,319
BEGIN DESCRIPTION:
COWAN BRANCH 8.0
END DESCRIPTION:
XS GIS Cut Line= 3
      2942824.99      6934875.01      2942525.00      6935475.00
      2942574.99      6935774.96
#Sta/Elev= 30
  4395.9  437.80  4398.7  437.80  4404.3  433.81  4485.3  411.40  4499.3  409.18
  4516.1  411.22  4521.7  409.63  4530.0  410.41  4544.0  409.13  4552.4  407.01
  4560.8  401.65  4566.4  404.21  4574.8  397.98  4588.7  395.11  4655.8  390.15
  4695.0  383.74  4722.9  381.18  4731.3  378.71  4762.0  375.52  4854.3  370.36
  4977.3  368.62  4999.6  367.05  5010.6  364.67  5011.1  363.87  5016.6  364.67
  5022.0  368.46  5086.6  370.36  5147.8  377.57  5350.6  411.35  5370.8  412.67
#Mann=3,-1,0
  4395.9    0.16       0  5010.6    0.07       0  5016.6    0.16       0
Bank Sta=4854.3,5086.6
Exp/Cntr=0.3,0.1

Type RM Length L Ch R = 1,3105,583,583,583
BEGIN DESCRIPTION:
COWAN BRANCH 7.0
END DESCRIPTION:
XS GIS Cut Line= 3
      2942034.66      6934975.26      2942296.84      6935502.13
      2942542.48      6935819.47
#Sta/Elev= 30
  4411.5  407.42  4470.5  400.53  4537.7  399.62  4576.9  402.10  4582.5  400.38
  4599.3  399.93  4604.9  397.96  4621.7  397.60  4627.3  395.60  4688.9  392.36
  4739.2  385.96  4791.0  374.67  4833.7  368.89  4935.2  365.36  4985.5  367.22
  4989.0  361.79  4989.5  360.99  4995.0  361.79  5053.2  368.89  5115.3  381.97
  5136.1  383.96  5150.6  387.44  5156.9  386.39  5179.6  389.20  5185.9  387.91
  5200.4  391.36  5235.7  393.81  5264.7  400.03  5314.5  407.15  5401.3  413.48
#Mann=3,-1,0
  4411.5    0.16       0  4989.0    0.07       0  4995.0    0.16       0
Bank Sta=4833.7,5053.2
Exp/Cntr=0.3,0.1

Type RM Length L Ch R = 1,2522,417,417,417
BEGIN DESCRIPTION:
COWAN BRANCH 6.0
END DESCRIPTION:
XS GIS Cut Line= 3
      2941739.50      6935292.09      2942006.64      6935642.59
      2942379.72      6935934.49
#Sta/Elev= 30
  4559.3  421.14  4564.7  417.81  4572.9  419.41  4593.8  414.90  4608.3  416.87
  4629.1  412.88  4658.2  413.30  4737.1  401.74  4787.0  391.68  4857.7  369.55
  4900.1  363.07  4978.4  363.59  4992.9  362.27  4998.4  357.99  5005.1  357.53
  5005.6  356.73  5011.1  357.53  5018.9  363.07  5122.1  370.25  5285.7  402.19
  5335.5  407.63  5370.8  407.86  5385.2  411.01  5406.0  408.02  5414.1  409.73
  5420.5  406.35  5428.6  408.66  5435.0  406.38  5449.4  410.90  5473.7  408.68
#Mann=3,-1,0
  4559.3    0.16       0  5005.1    0.07       0  5011.1    0.16       0
Bank Sta=4900.1,5018.9
Exp/Cntr=0.3,0.1

Type RM Length L Ch R = 1,2105,333,333,333
BEGIN DESCRIPTION:
COWAN BRANCH 5.0
END DESCRIPTION:
XS GIS Cut Line= 3
      2941624.99      6935374.96      2941675.00      6935675.00
      2941825.00      6936175.00
#Sta/Elev= 30
  4686.6  439.67  4775.4  435.36  4818.4  427.48  4836.2  420.92  4841.2  418.06
  4848.9  411.00  4869.1  408.05  4897.0  401.15  4902.1  391.95  4909.7  388.08
  4919.8  385.06  4940.1  374.75  4957.8  368.95  4961.9  361.28  4962.9  359.33
  4970.5  357.54  5004.3  354.67  5004.8  353.87  5010.3  354.67  5012.5  358.12
  5032.5  359.26  5111.7  357.68  5144.8  361.13  5189.2  361.28  5241.4  362.17
  5314.4  367.23  5358.8  372.83  5418.8  382.61  5463.2  394.47  5512.8  402.32
#Mann=3,-1,0
  4686.6    0.16       0  5004.3    0.07       0  5010.3    0.16       0
Bank Sta=4961.9,5189.2
Exp/Cntr=0.3,0.1

Type RM Length L Ch R = 1,1772,420,420,420
BEGIN DESCRIPTION:
COWAN BRANCH 4.0
END DESCRIPTION:
XS GIS Cut Line= 3
      2941475.00      6935525.00      2941525.00      6935875.00
      2941725.01      6936275.03
#Sta/Elev= 30
  4643.1  428.89  4693.6  418.43  4754.2  403.65  4814.8  390.55  4819.9  387.87
  4824.9  387.63  4885.5  373.40  4929.2  360.34  4936.0  358.47  4946.1  356.82
  4956.3  356.65  4966.4  354.26  4976.5  355.62  4999.5  355.55  5007.6  352.75
  5008.1  351.95  5013.6  352.75  5019.0  357.17  5027.4  357.24  5033.0  359.33
  5070.5  360.34  5161.6  364.79  5197.9  368.49  5301.3  383.83  5318.1  387.46
  5323.7  387.14  5340.5  390.48  5346.0  390.35  5368.4  393.65  5443.9  406.16
#Mann=3,-1,0
  4643.1    0.16       0  5007.6    0.07       0  5013.6    0.16       0
Bank Sta=4929.2,5070.5
Exp/Cntr=0.3,0.1

Type RM Length L Ch R = 1,1352,500,500,500
BEGIN DESCRIPTION:
COWAN BRANCH 3.0
END DESCRIPTION:
XS GIS Cut Line= 3
      2941325.01      6935574.96      2941225.00      6935875.00
      2941555.82      6936440.93
#Sta/Elev= 30
  4707.9  413.18  4887.1  387.73  4918.8  379.43  4982.0  368.58  4994.5  357.64
  5000.1  350.76  5000.6  349.96  5006.1  350.76  5075.0  357.59  5221.5  357.64
  5325.3  362.39  5374.2  371.91  5389.9  377.66  5411.4  380.13  5427.1  385.65
  5432.9  383.78  5448.6  388.81  5454.4  385.88  5464.3  387.44  5470.1  384.85
  5491.6  386.37  5507.3  393.50  5513.1  392.19  5528.8  399.37  5544.5  400.80
  5550.2  399.24  5565.9  403.24  5571.7  401.48  5587.4  406.27  5679.7  414.26
#Mann=3,-1,0
  4707.9    0.16       0  5000.1    0.07       0  5006.1    0.16       0
Bank Sta=4994.5,5221.5
Exp/Cntr=0.3,0.1

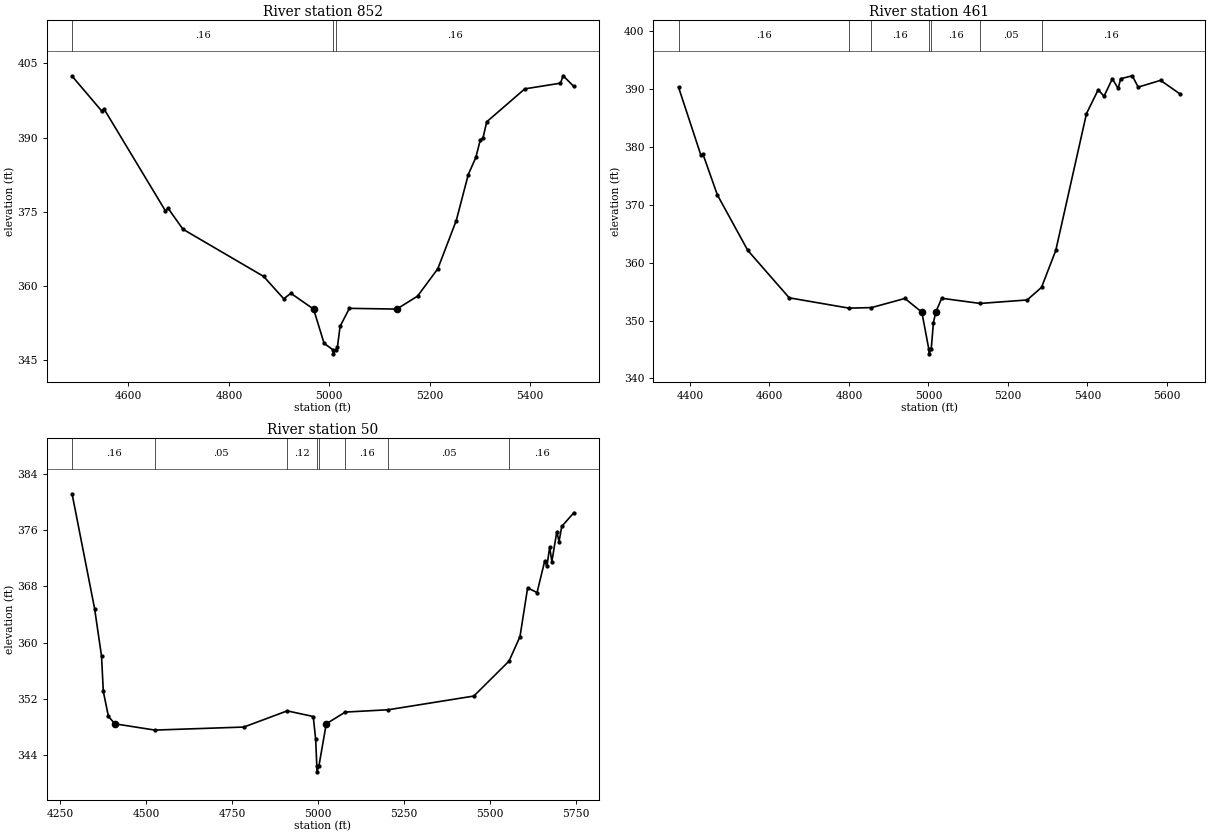
Type RM Length L Ch R = 1,852,391,391,391
BEGIN DESCRIPTION:
COWAN BRANCH 2.0
END DESCRIPTION:
XS GIS Cut Line= 3
      2941075.00      6935524.97      2941033.75      6936035.50
      2941220.00      6936485.27
#Sta/Elev= 30
  4487.8  402.44  4546.5  395.42  4551.5  395.78  4673.8  375.14  4678.8  375.71
  4708.6  371.44  4869.1  361.90  4909.2  357.37  4923.4  358.47  4968.6  355.28
  4989.5  348.36  5007.3  347.02  5007.8  346.22  5013.3  347.02  5016.0  347.52
  5021.4  351.79  5039.9  355.43  5134.2  355.28  5175.6  357.90  5215.9  363.44
  5252.7  373.21  5276.6  382.51  5291.7  385.99  5300.5  389.53  5305.9  389.92
  5313.3  393.19  5389.1  399.86  5460.1  401.01  5465.5  402.51  5486.8  400.35
#Mann=3,-1,0
  4487.8    0.16       0  5007.3    0.07       0  5013.3    0.16       0
Bank Sta=4968.6,5134.2
Exp/Cntr=0.3,0.1

Type RM Length L Ch R = 1,461,411,411,411
BEGIN DESCRIPTION:
Mapping XS 9ce6250f
END DESCRIPTION:
XS GIS Cut Line= 3
      2940694.82      6935417.52      2940749.08      6936042.56
      2941121.15      6936557.40
#Sta/Elev= 30
  4371.2  390.33  4427.5  378.56  4432.5  378.79  4469.0  371.70  4545.5  362.12
  4649.7  353.93  4799.8  352.15  4856.7  352.24  4940.8  353.82  4983.4  351.45
  5001.0  345.05  5001.5  344.25  5007.0  345.05  5012.5  349.60  5018.3  351.45
  5033.4  353.85  5130.0  352.96  5248.4  353.56  5284.5  355.73  5320.4  362.12
  5397.7  385.77  5427.1  389.87  5441.8  388.77  5462.7  391.77  5477.4  390.11
  5483.6  391.79  5513.0  392.30  5527.7  390.34  5584.1  391.51  5633.8  389.12
#Mann=7,-1,0
  4371.2    0.16       0  4799.8    0.05       0  4856.7    0.16       0
  5001.0    0.07       0  5007.0    0.16       0  5130.0    0.05       0
  5284.5    0.16       0
Bank Sta=4983.4,5018.3
Exp/Cntr=0.3,0.1

Type RM Length L Ch R = 1,50,0,0,0
BEGIN DESCRIPTION:
COWAN BRANCH 1.0
END DESCRIPTION:
XS GIS Cut Line= 3
      2940391.01      6935419.76      2940461.65      6936132.57
      2941039.51      6936600.40
#Sta/Elev= 30
  4283.7  381.17  4349.3  364.82  4369.4  358.08  4374.6  353.05  4389.5  349.51
  4408.2  348.45  4524.4  347.56  4783.4  347.99  4909.6  350.29  4985.3  349.49
  4992.4  346.26  4995.7  342.42  4996.2  341.62  5001.7  342.42  5023.2  348.45
  5078.4  350.12  5203.5  350.45  5452.5  352.40  5554.9  357.37  5586.8  360.86
  5609.0  367.79  5636.4  367.12  5658.7  371.61  5665.2  370.84  5673.1  373.59
  5679.5  371.53  5693.9  375.78  5700.4  374.37  5708.3  376.53  5743.5  378.48
#Mann=8,-1,0
  4283.7    0.16       0  4524.4    0.05       0  4909.6    0.12       0
  4995.7    0.07       0  5001.7    0.12       0  5078.4    0.16       0
  5203.5    0.05       0  5554.9    0.16       0
Bank Sta=4408.2,5023.2
Exp/Cntr=0.3,0.1

Chan Stop Cuts=-1