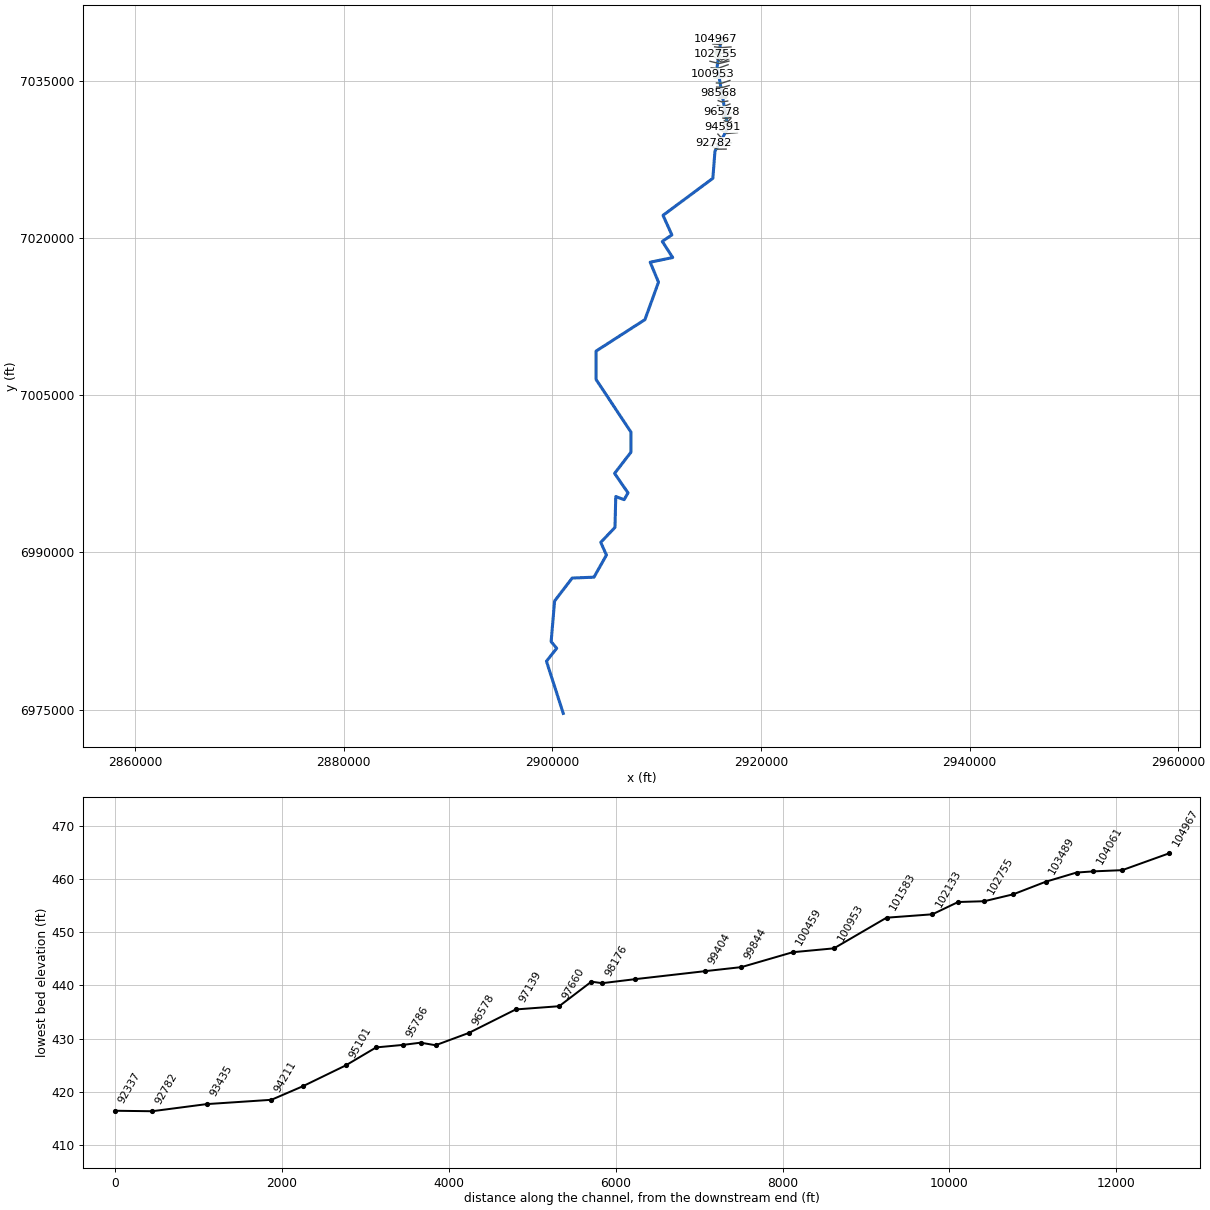
--- DRY CREEK.prj (project) ---

Proj Title=DRY CREEK Base Level Engineering
Current Plan=p01
Default Exp/Contr=0.3,0.1
English Units
Geom File=g01
Flow File=f01
Plan File=p01
BEGIN DESCRIPTION:
DRY CREEK
END DESCRIPTION:

--- DRY CREEK.p01 (plan) ---

Plan Title=Multiple Run
Short Identifier=Multiple
Geom File=g01
Flow File=f01
Subcritical Flow
K Sum by GR= 0
Std Step Tol= 0.01
Critical Tol= 0.01
Num of Std Step Trials= 20
Max Error Tol= 0.3
Flow Tol Ratio= 0.001
Split Flow NTrial= 30
Split Flow Tol= 0.02
Split Flow Ratio= 0.02
Log Output Level= 0
Friction Slope Method= 1
Unsteady Friction Slope Method= 2
Unsteady Bridges Friction Slope Method= 1
Parabolic Critical Depth
Global Vel Dist=  1 , 1 , 1
Global Log Level= 0
CheckData=True
Encroach Param= -1, 0, 0, 0
BEGIN DESCRIPTION:
Multiple Run
END DESCRIPTION:

--- DRY CREEK.f01 (steady flow) ---

Flow Title=Multiple
Program Version=5.07
Number of Profiles= 7
Profile Names=10-year,25-year,50-year,1pct_min,100-year,1pct_plu,500-year
River Rch & RM=DRY CREEK,Reach-1         ,104967
     624     845    1026     620    1237    2468    1801
River Rch & RM=DRY CREEK,Reach-1         ,102133
     830    1135    1389     843    1683    3358    2477
River Rch & RM=DRY CREEK,Reach-1         ,94211
    1712    2406    2994    1845    3681    7345    5579
River Rch & RM=DRY CREEK,Reach-1         ,87285
    2159    3053    3816    2358    4706    9389    7178
River Rch & RM=DRY CREEK,Reach-1         ,82260
    2232    3153    3937    2430    4849    9675    7380
River Rch & RM=DRY CREEK,Reach-1         ,76090
    2642    3742    4681    2893    5773   11518    8805
River Rch & RM=DRY CREEK,Reach-1         ,70420
    2596    3663    4571    2817    5621   11215    8525
River Rch & RM=DRY CREEK,Reach-1         ,64660
    3611    5145    6462    4006    7993   15947   12262
River Rch & RM=DRY CREEK,Reach-1         ,61418
    4193    5979    7513    4658    9295   18545   14260
River Rch & RM=DRY CREEK,Reach-1         ,60702
    4602    6622    8375    5226   10428   20806   16208
River Rch & RM=DRY CREEK,Reach-1         ,53884
    4710    6776    8567    5345   10665   21279   16566
River Rch & RM=DRY CREEK,Reach-1         ,45796
    6019    8711   11061    6926   13819   27573   21620
River Rch & RM=DRY CREEK,Reach-1         ,39261
    6139    8861   11230    7018   14003   27939   21817
River Rch & RM=DRY CREEK,Reach-1         ,33246
    7221   10406   13174    8220   16401   32725   25468
Boundary for River Rch & Prof#=DRY CREEK,Reach-1         , 1
Up Type= 0
Dn Type= 3
Dn Slope=0.00118
Boundary for River Rch & Prof#=DRY CREEK,Reach-1         , 2
Up Type= 0
Dn Type= 3
Dn Slope=0.00118
Boundary for River Rch & Prof#=DRY CREEK,Reach-1         , 3
Up Type= 0
Dn Type= 3
Dn Slope=0.00118
Boundary for River Rch & Prof#=DRY CREEK,Reach-1         , 4
Up Type= 0
Dn Type= 3
Dn Slope=0.00118
Boundary for River Rch & Prof#=DRY CREEK,Reach-1         , 5
Up Type= 0
Dn Type= 3
Dn Slope=0.00118
Boundary for River Rch & Prof#=DRY CREEK,Reach-1         , 6
Up Type= 0
Dn Type= 3
Dn Slope=0.00118
Boundary for River Rch & Prof#=DRY CREEK,Reach-1         , 7
Up Type= 0
Dn Type= 3
Dn Slope=0.00118
DSS Import GetInterval= 0
DSS Import GetPeak= 0
DSS Import FillOption= 0

--- DRY CREEK.g01 (geometry) ---

Geom Title=Existing Conditions

River Reach=DRY CREEK,Reach-1
Reach XY= 30
      2916204.59      7039100.81      2915807.29      7036439.79
      2916843.34      7030530.56      2915597.45      7028334.64
      2915392.18      7025732.23      2910618.02      7022195.91
      2911465.67      7020324.17      2910547.70      7019706.33
      2911543.15      7018165.32      2909387.48      7017719.13
      2910183.10      7015814.84      2908884.49      7012236.28
      2904201.91      7009230.64      2904201.91      7006520.13
      2907543.85      7001495.14      2907542.24      6999572.00
      2905975.40      6997549.69      2907261.07      6995691.89
      2906890.64      6995042.83      2906088.78      6995339.11
      2906013.12      6992390.59      2904650.01      6990963.59
      2905195.00      6989751.30      2904000.41      6987638.29
      2901912.65      6987555.13      2900225.74      6985361.97
      2899895.59      6981480.71      2900429.62      6980845.36
      2899446.51      6979611.02      2901055.59      6974630.71

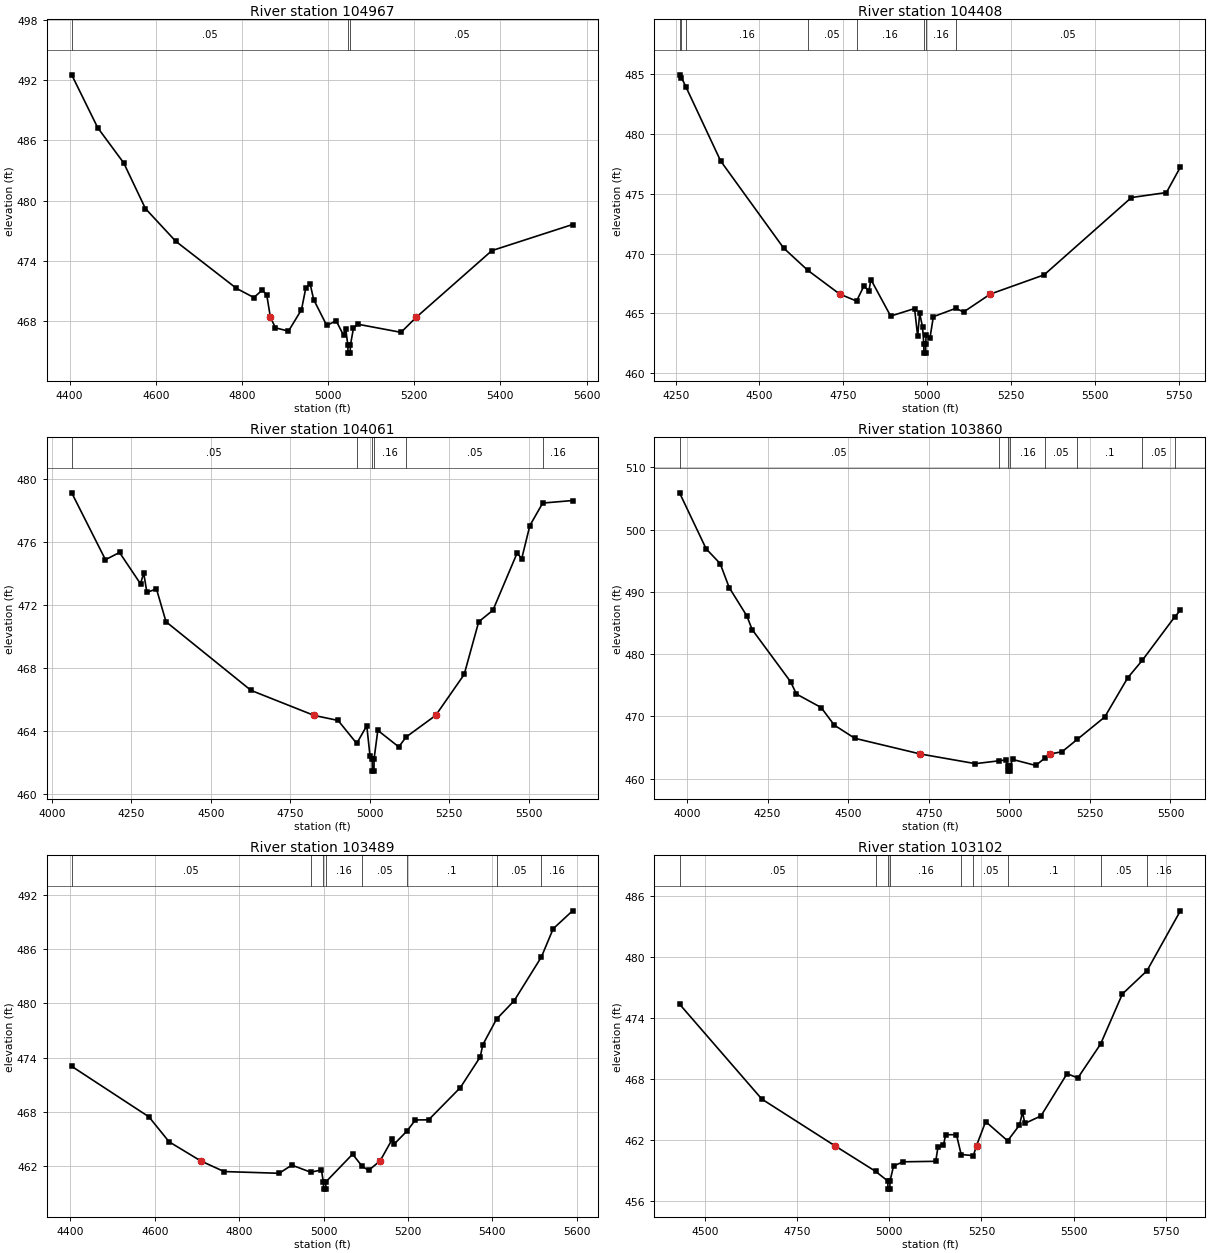
Type RM Length L Ch R = 1,104967,559,559,559
BEGIN DESCRIPTION:
DRY CREEK 100.0
END DESCRIPTION:
XS GIS Cut Line= 3
      2916774.97      7039075.00      2916183.62      7039006.54
      2915618.50      7039058.42
#Sta/Elev= 30
  4404.7  492.54  4465.1  487.27  4525.5  483.76  4575.8  479.22  4646.3  475.96
  4787.2  471.27  4827.5  470.36  4847.6  471.11  4857.7  470.57  4866.0  468.39
  4877.8  467.34  4908.0  467.01  4938.2  469.15  4948.3  471.33  4958.3  471.70
  4966.6  470.14  4996.8  467.58  5018.7  468.04  5035.8  466.60  5040.8  467.26
  5045.8  465.62  5046.3  464.82  5051.3  464.82  5051.8  465.62  5058.9  467.31
  5068.9  467.70  5169.3  466.89  5204.6  468.39  5380.2  475.03  5567.5  477.63
#Mann=3,-1,0
  4404.7    0.05       0  5045.8    0.03       0  5051.8    0.05       0
Bank Sta=4866,5204.6
Exp/Cntr=0.3,0.1

Type RM Length L Ch R = 1,104408,347,347,347
BEGIN DESCRIPTION:
DRY CREEK 99.0
END DESCRIPTION:
XS GIS Cut Line= 3
      2916774.98      7038924.99      2916153.34      7038526.50
      2915399.18      7038561.99
#Sta/Elev= 30
  4261.6  484.96  4267.4  484.72  4280.2  483.98  4384.2  477.75  4571.8  470.47
  4643.6  468.61  4739.2  466.61  4789.4  466.03  4811.1  467.27  4826.3  466.89
  4832.2  467.83  4891.1  464.77  4962.4  465.40  4971.7  463.08  4977.6  465.01
  4986.2  463.85  4989.8  462.47  4990.3  461.67  4995.3  461.67  4995.8  462.47
  4996.8  463.19  5008.4  462.95  5018.4  464.72  5085.5  465.42  5108.5  465.11
  5188.2  466.61  5348.7  468.22  5609.0  474.69  5713.4  475.11  5755.0  477.24
#Mann=8,-1,0
  4261.6    0.08       0  4267.4    0.05       0  4280.2    0.16       0
  4643.6    0.05       0  4789.4    0.16       0  4989.8    0.07       0
  4995.8    0.16       0  5085.5    0.05       0
Bank Sta=4739.2,5188.2
Exp/Cntr=0.3,0.1

Type RM Length L Ch R = 1,104061,201,201,201
BEGIN DESCRIPTION:
Mapping XS 3731758c
END DESCRIPTION:
XS GIS Cut Line= 3
      2917130.94      7038280.78      2916217.77      7038214.80
      2915561.56      7038287.72
#Sta/Elev= 30
  4062.3  479.12  4168.5  474.87  4212.7  475.33  4278.8  473.34  4288.8  474.03
  4298.9  472.79  4328.9  473.02  4359.0  470.93  4626.4  466.57  4824.8  464.98
  4900.4  464.66  4959.0  463.20  4990.7  464.32  5000.8  462.41  5007.8  462.24
  5008.3  461.44  5013.3  461.44  5013.8  462.24  5025.4  464.03  5091.3  462.98
  5114.6  463.61  5207.5  464.98  5297.1  467.58  5342.9  470.93  5387.6  471.66
  5463.6  475.29  5478.2  474.94  5503.8  477.04  5544.2  478.47  5638.1  478.63
#Mann=6,-1,0
  4062.3    0.05       0  4959.0    0.16       0  5007.8    0.07       0
  5013.8    0.16       0  5114.6    0.05       0  5544.2    0.16       0
Bank Sta=4824.8,5207.5
Exp/Cntr=0.3,0.1

Type RM Length L Ch R = 1,103860,371,371,371
BEGIN DESCRIPTION:
DRY CREEK 98.0
END DESCRIPTION:
XS GIS Cut Line= 3
      2917174.97      7037725.01      2916175.00      7038025.00
      2915675.00      7037925.00
#Sta/Elev= 30
  3976.8  505.89  4059.4  496.90  4102.9  494.53  4130.8  490.69  4185.6  486.13
  4202.1  483.94  4321.3  475.57  4339.6  473.59  4416.1  471.43  4457.0  468.60
  4520.5  466.49  4724.0  463.97  4894.6  462.42  4966.9  462.87  4989.5  463.02
  4996.0  462.02  4996.5  461.22  5001.5  461.22  5002.0  462.02  5010.4  463.09
  5082.0  462.13  5110.6  463.33  5125.7  463.97  5163.6  464.33  5211.1  466.33
  5296.1  469.91  5367.5  476.21  5412.2  478.98  5512.7  485.95  5530.7  487.04
#Mann=8,-1,0
  3976.8    0.05       0  4966.9    0.16       0  4996.0    0.07       0
  5002.0    0.16       0  5110.6    0.05       0  5211.1     0.1       0
  5412.2    0.05       0  5512.7    0.16       0
Bank Sta=4724,5125.7
Exp/Cntr=0.3,0.1

Type RM Length L Ch R = 1,103489,387,387,387
BEGIN DESCRIPTION:
DRY CREEK 97.0
END DESCRIPTION:
XS GIS Cut Line= 3
      2916774.96      7037625.00      2916175.00      7037675.00
      2915624.97      7037875.01
#Sta/Elev= 30
  4402.9  473.04  4586.0  467.46  4633.7  464.71  4708.6  462.60  4764.1  461.42
  4894.6  461.23  4924.7  462.13  4969.5  461.35  4994.9  461.60  4999.4  460.28
  4999.9  459.48  5004.9  459.48  5005.4  460.28  5068.8  463.34  5091.1  462.02
  5106.7  461.55  5134.1  462.60  5162.6  464.98  5167.9  464.48  5197.4  465.88
  5217.7  467.12  5249.0  467.13  5324.2  470.69  5371.4  474.08  5377.4  475.42
  5410.0  478.25  5451.8  480.28  5516.3  485.11  5544.3  488.23  5590.2  490.21
#Mann=8,-1,0
  4402.9    0.05       0  4969.5    0.16       0  4999.4    0.07       0
  5005.4    0.16       0  5091.1    0.05       0  5197.4     0.1       0
  5410.0    0.05       0  5516.3    0.16       0
Bank Sta=4708.6,5134.1
Exp/Cntr=0.3,0.1

Type RM Length L Ch R = 1,103102,347,347,347
BEGIN DESCRIPTION:
DRY CREEK 96.0
END DESCRIPTION:
XS GIS Cut Line= 3
      2916825.04      7037425.01      2916225.00      7037325.00
      2915625.01      7037774.99
#Sta/Elev= 30
  4431.1  475.35  4654.2  466.00  4851.5  461.42  4962.8  458.88  4995.9  457.93
  4996.4  457.13  5001.4  457.13  5001.9  457.93  5011.5  459.40  5036.9  459.82
  5125.9  459.87  5132.1  461.30  5146.7  461.45  5153.0  462.49  5182.1  462.49
  5194.9  460.54  5228.0  460.43  5236.6  461.42  5261.3  463.78  5320.9  461.89
  5353.0  463.43  5361.3  464.72  5367.5  463.60  5411.3  464.34  5482.1  468.50
  5511.3  468.08  5572.9  471.41  5632.1  476.35  5698.9  478.64  5789.4  484.54
#Mann=9,-1,0
  4431.1    0.05       0  4962.8    0.16       0  4995.9    0.07       0
  5001.9    0.16       0  5194.9     0.1       0  5228.0    0.05       0
  5320.9     0.1       0  5572.9    0.05       0  5698.9    0.16       0
Bank Sta=4851.5,5236.6
Exp/Cntr=0.3,0.1

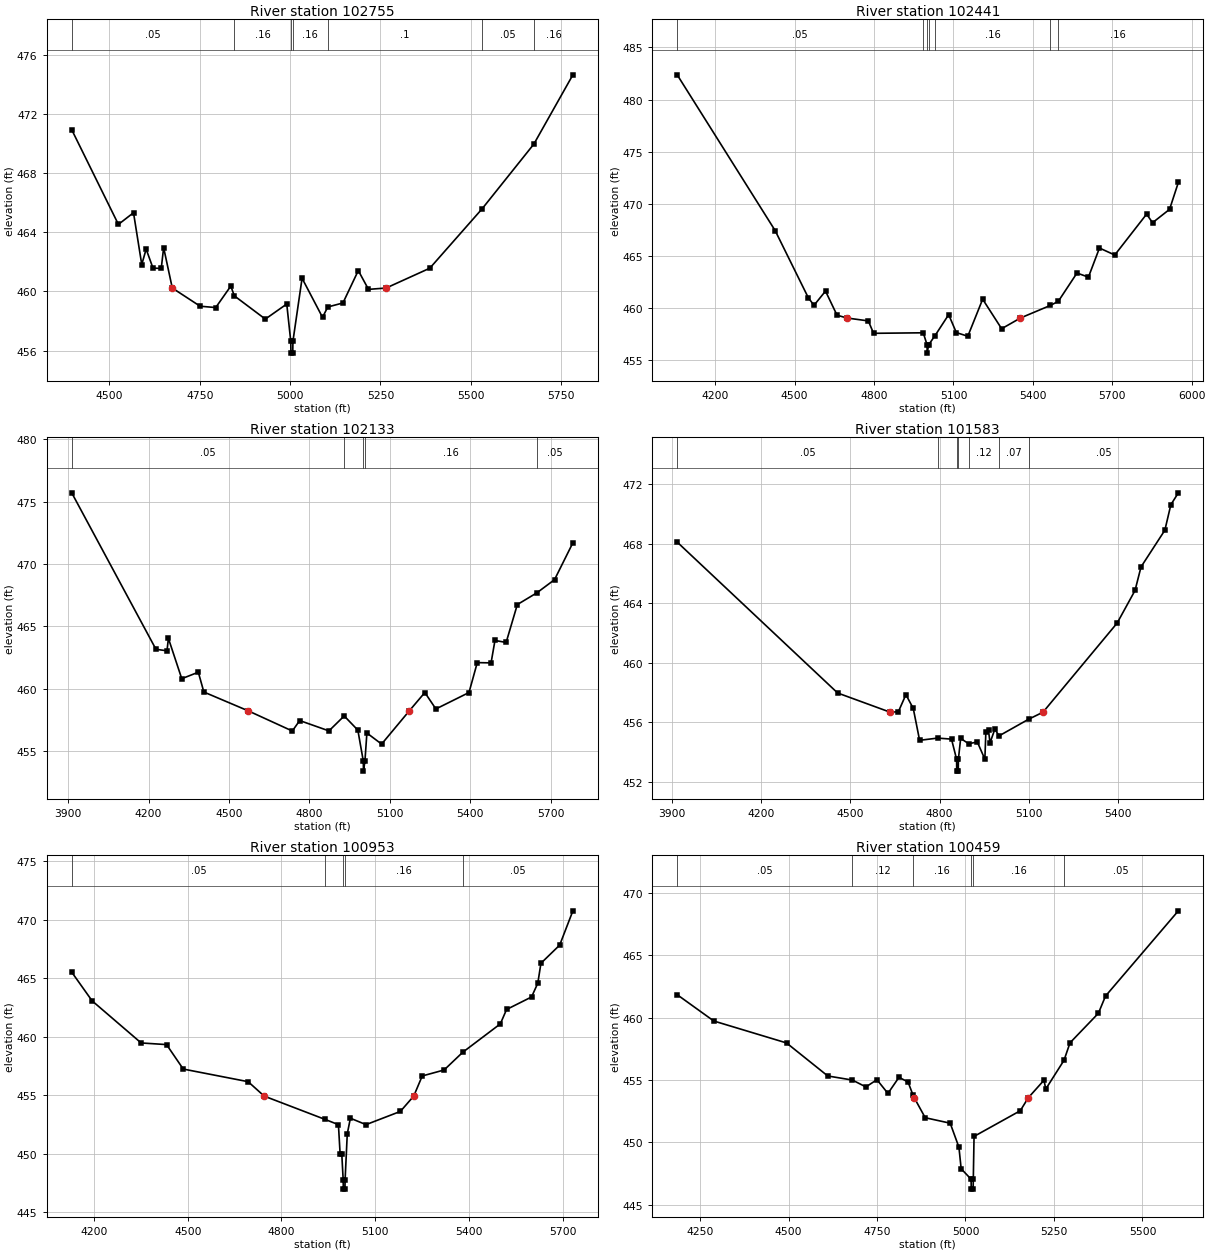
Type RM Length L Ch R = 1,102755,314,314,314
BEGIN DESCRIPTION:
DRY CREEK 95.0
END DESCRIPTION:
XS GIS Cut Line= 3
      2916724.98      7037224.99      2916225.00      7037025.00
      2915625.02      7037624.98
#Sta/Elev= 30
  4395.7  470.93  4524.9  464.53  4566.7  465.32  4589.5  461.82  4601.7  462.86
  4620.5  461.58  4643.4  461.55  4650.1  462.96  4674.0  460.23  4751.1  459.00
  4794.2  458.91  4835.9  460.36  4845.8  459.70  4931.5  458.13  4990.8  459.15
  5001.9  456.63  5002.4  455.83  5007.4  455.83  5007.9  456.63  5033.2  460.89
  5089.8  458.25  5104.4  458.95  5146.3  459.22  5188.8  461.41  5217.0  460.14
  5265.8  460.23  5386.7  461.57  5531.3  465.58  5674.7  469.96  5782.7  474.64
#Mann=7,-1,0
  4395.7    0.05       0  4845.8    0.16       0  5001.9    0.07       0
  5007.9    0.16       0  5104.4     0.1       0  5531.3    0.05       0
  5674.7    0.16       0
Bank Sta=4674,5265.8
Exp/Cntr=0.3,0.1

Type RM Length L Ch R = 1,102441,308,308,308
BEGIN DESCRIPTION:
Mapping XS 661b9ed2
END DESCRIPTION:
XS GIS Cut Line= 4
      2916992.07      7037180.08      2916394.85      7036850.22
      2916151.80      7036850.22      2915388.98      7037446.61
#Sta/Elev= 30
  4056.2  482.37  4426.4  467.43  4551.3  461.01  4573.0  460.26  4616.6  461.63
  4660.1  459.32  4697.1  459.05  4778.3  458.77  4798.3  457.58  4985.9  457.63
  5000.3  456.48  5000.8  455.68  5006.3  456.48  5030.7  457.37  5082.0  459.37
  5110.9  457.65  5154.3  457.30  5210.4  460.85  5282.1  458.02  5353.3  459.05
  5466.7  460.26  5496.3  460.65  5566.7  463.36  5610.1  462.97  5651.7  465.76
  5709.5  465.09  5829.8  469.01  5852.4  468.19  5916.6  469.47  5949.8  472.05
#Mann=7,-1,0
  4056.2    0.05       0  4985.9    0.12       0  5000.3    0.07       0
  5006.3    0.12       0  5030.7    0.16       0  5466.7    0.05       0
  5496.3    0.16       0
Bank Sta=4697.1,5353.3
Exp/Cntr=0.3,0.1

Type RM Length L Ch R = 1,102133,550,550,550
BEGIN DESCRIPTION:
Mapping XS 0f5a5f57
END DESCRIPTION:
XS GIS Cut Line= 3
      2916933.04      7036926.61      2916002.49      7036693.97
      2915118.53      7036908.90
#Sta/Elev= 30
  3913.4  475.71  4227.5  463.15  4268.7  463.03  4273.9  464.03  4323.7  460.79
  4385.5  461.31  4406.1  459.72  4572.6  458.20  4736.0  456.59  4763.5  457.43
  4872.6  456.60  4929.5  457.80  4980.4  456.66  5000.8  454.17  5001.3  453.37
  5006.8  454.17  5014.1  456.43  5069.0  455.54  5171.9  458.20  5230.2  459.68
  5271.4  458.36  5394.9  459.68  5425.7  462.08  5477.2  462.06  5491.7  463.86
  5533.4  463.70  5575.1  466.74  5648.5  467.69  5713.9  468.74  5782.3  471.70
#Mann=5,-1,0
  3913.4    0.05       0  4929.5    0.16       0  5000.8    0.07       0
  5006.8    0.16       0  5648.5    0.05       0
Bank Sta=4572.6,5171.9
Exp/Cntr=0.3,0.1

Type RM Length L Ch R = 1,101583,630,630,630
BEGIN DESCRIPTION:
DRY CREEK 94.0
END DESCRIPTION:
XS GIS Cut Line= 3
      2916852.84      7036581.12      2915873.77      7036229.00
      2915229.81      7036286.62
#Sta/Elev= 30
  3916.7  468.12  4456.8  457.98  4633.6  456.69  4661.2  456.72  4686.6  457.87
  4711.4  456.94  4732.7  454.80  4793.5  454.95  4840.1  454.88  4857.2  453.53
  4857.7  452.73  4862.8  452.73  4863.3  453.53  4870.9  454.93  4897.9  454.57
  4927.0  454.69  4952.4  453.53  4955.7  455.33  4964.7  455.46  4969.7  454.63
  4986.0  455.55  5000.2  455.10  5099.9  456.22  5148.1  456.69  5397.7  462.68
  5457.9  464.87  5478.0  466.45  5558.3  468.92  5578.4  470.63  5603.7  471.43
#Mann=7,-1,0
  3916.7    0.05       0  4793.5    0.16       0  4857.2    0.07       0
  4863.3    0.16       0  4897.9    0.12       0  5000.2    0.07       0
  5099.9    0.05       0
Bank Sta=4633.6,5148.1
Exp/Cntr=0.3,0.1

Type RM Length L Ch R = 1,100953,494,494,494
BEGIN DESCRIPTION:
DRY CREEK 93.0
END DESCRIPTION:
XS GIS Cut Line= 3
      2916843.09      7036116.53      2916075.00      7035725.00
      2915332.73      7035727.65
#Sta/Elev= 30
  4128.5  465.51  4193.7  463.06  4350.8  459.46  4432.1  459.32  4485.5  457.23
  4693.3  456.15  4744.6  454.92  4940.2  452.92  4982.3  452.48  4987.8  449.94
  4993.1  449.94  4997.5  447.77  4998.0  446.97  5003.2  446.97  5003.7  447.77
  5010.6  451.69  5020.6  453.03  5070.6  452.48  5180.6  453.61  5223.4  454.92
  5250.6  456.64  5320.6  457.15  5380.1  458.66  5500.6  461.09  5520.6  462.32
  5600.6  463.39  5620.6  464.57  5630.6  466.27  5690.6  467.82  5732.9  470.75
#Mann=5,-1,0
  4128.5    0.05       0  4940.2    0.16       0  4997.5    0.07       0
  5003.7    0.16       0  5380.1    0.05       0
Bank Sta=4744.6,5223.4
Exp/Cntr=0.3,0.1

Type RM Length L Ch R = 1,100459,615,615,615
BEGIN DESCRIPTION:
DRY CREEK 92.0
END DESCRIPTION:
XS GIS Cut Line= 3
      2916876.66      7035554.40      2916075.00      7035275.00
      2915509.84      7035319.98
#Sta/Elev= 30
  4185.5  461.84  4288.9  459.73  4494.4  457.97  4610.9  455.32  4680.5  454.99
  4718.7  454.44  4749.8  455.02  4780.9  453.92  4812.1  455.21  4837.7  454.84
  4851.4  453.81  4855.3  453.57  4886.2  451.97  4956.8  451.53  4981.5  449.60
  4987.8  447.87  5015.8  447.04  5016.3  446.24  5021.6  446.24  5022.1  447.04
  5024.2  450.47  5154.8  452.53  5177.4  453.57  5221.8  454.98  5226.8  454.27
  5278.4  456.58  5295.3  457.98  5375.5  460.35  5395.6  461.73  5601.4  468.57
#Mann=6,-1,0
  4185.5    0.05       0  4680.5    0.12       0  4851.4    0.16       0
  5015.8    0.07       0  5022.1    0.16       0  5278.4    0.05       0
Bank Sta=4855.3,5177.4
Exp/Cntr=0.3,0.1

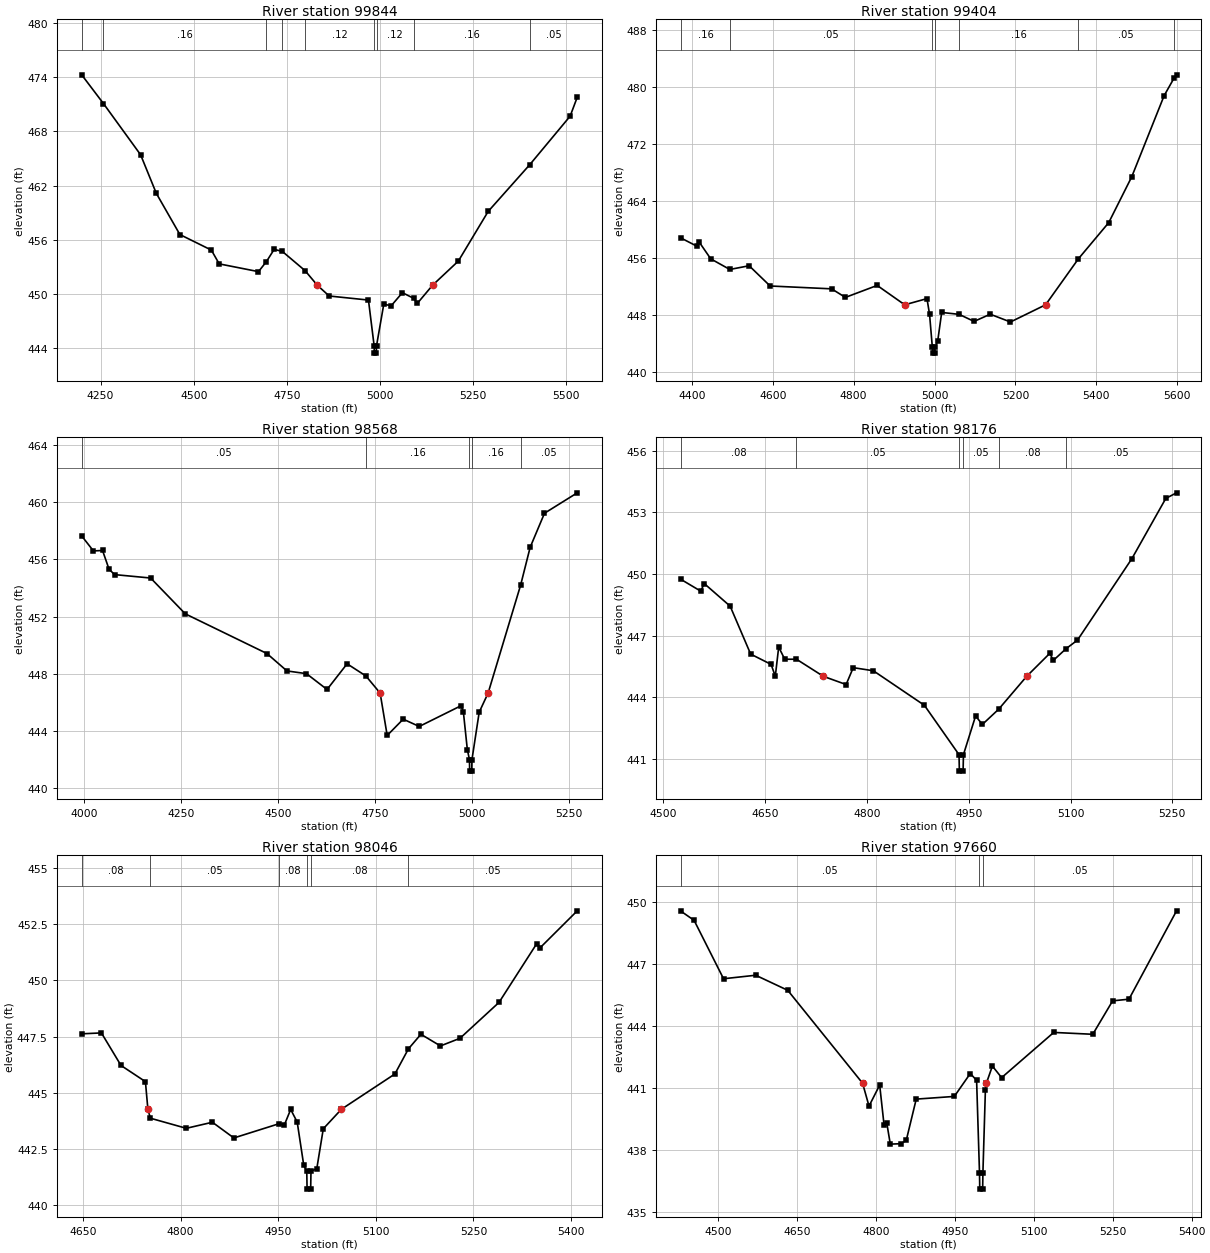
Type RM Length L Ch R = 1,99844,440,440,440
BEGIN DESCRIPTION:
DRY CREEK 91.0
END DESCRIPTION:
XS GIS Cut Line= 3
      2917025.02      7035075.01      2916275.00      7034825.00
      2915735.95      7034838.24
#Sta/Elev= 30
  4199.4  474.28  4257.9  471.09  4357.5  465.42  4399.7  461.14  4462.9  456.58
  4547.3  454.86  4568.4  453.33  4673.8  452.47  4695.2  453.59  4715.9  454.94
  4737.8  454.71  4798.8  452.58  4831.5  450.97  4863.5  449.77  4968.9  449.32
  4984.2  444.24  4984.7  443.44  4990.0  443.44  4990.5  444.24  5010.0  448.86
  5030.0  448.69  5060.0  450.14  5090.3  449.51  5100.0  448.95  5141.1  450.97
  5210.1  453.64  5290.1  459.14  5401.9  464.33  5510.1  469.70  5529.2  471.80
#Mann=9,-1,0
  4199.4    0.05       0  4257.9    0.16       0  4695.2    0.12       0
  4737.8    0.16       0  4798.8    0.12       0  4984.2    0.07       0
  4990.5    0.12       0  5090.3    0.16       0  5401.9    0.05       0
Bank Sta=4831.5,5141.1
Exp/Cntr=0.3,0.1

Type RM Length L Ch R = 1,99404,836,836,836
BEGIN DESCRIPTION:
Mapping XS 2bb60b80
END DESCRIPTION:
XS GIS Cut Line= 3
      2916957.37      7034590.85      2916371.41      7034426.78
      2915754.28      7034445.01
#Sta/Elev= 30
  4372.8  458.82  4412.3  457.67  4417.5  458.28  4446.4  455.90  4493.6  454.41
  4541.4  454.93  4593.3  452.09  4745.4  451.69  4779.5  450.49  4858.1  452.17
  4926.3  449.45  4981.3  450.32  4987.7  448.11  4994.6  443.47  4995.1  442.67
  5000.4  442.67  5000.9  443.47  5007.7  444.31  5017.7  448.38  5060.9  448.11
  5097.8  447.12  5137.8  448.13  5187.8  447.04  5274.7  449.45  5356.1  455.92
  5430.9  460.98  5487.9  467.42  5568.0  478.80  5592.1  481.22  5598.7  481.72
#Mann=7,-1,0
  4372.8    0.16       0  4493.6    0.05       0  4994.6    0.03       0
  5000.9    0.05       0  5060.9    0.16       0  5356.1    0.05       0
  5592.1    0.16       0
Bank Sta=4926.3,5274.7
Exp/Cntr=0.3,0.1

Type RM Length L Ch R = 1,98568,392,392,392
BEGIN DESCRIPTION:
DRY CREEK 90.0
END DESCRIPTION:
XS GIS Cut Line= 3
      2917137.01      7034088.24      2916163.33      7033832.51
      2915894.84      7033872.10
#Sta/Elev= 30
  3993.3  457.65  4023.5  456.60  4047.1  456.63  4063.8  455.32  4078.1  454.94
  4171.1  454.70  4260.5  452.19  4471.0  449.41  4522.7  448.19  4573.0  448.00
  4626.1  446.89  4677.8  448.69  4726.2  447.84  4763.0  446.64  4781.2  443.67
  4822.5  444.81  4863.9  444.30  4971.5  445.75  4977.6  445.34  4987.9  442.68
  4993.4  441.97  4993.9  441.17  4999.3  441.17  4999.8  441.97  5018.5  445.30
  5041.5  446.64  5125.3  454.20  5149.9  456.85  5186.9  459.24  5271.4  460.67
#Mann=5,-1,0
  3993.3    0.05       0  4726.2    0.16       0  4993.4    0.07       0
  4999.8    0.16       0  5125.3    0.05       0
Bank Sta=4763,5041.5
Exp/Cntr=0.3,0.1

Type RM Length L Ch R = 1,98176,130,130,130
BEGIN DESCRIPTION:
Mapping XS 5b21c902
END DESCRIPTION:
XS GIS Cut Line= 3
      2916757.14      7033502.84      2916342.18      7033464.65
      2916029.26      7033477.46
#Sta/Elev= 30
  4526.3  449.74  4555.4  449.17  4560.5  449.54  4598.7  448.44  4628.9  446.11
  4659.0  445.61  4665.2  445.03  4670.2  446.45  4679.1  445.86  4696.4  445.86
  4735.9  445.03  4769.5  444.63  4780.0  445.45  4809.6  445.30  4884.8  443.62
  4935.8  441.22  4936.3  440.42  4941.8  440.42  4942.3  441.22  4960.2  443.10
  4970.2  442.69  4994.2  443.43  5035.5  445.03  5069.6  446.15  5074.6  445.80
  5093.4  446.37  5110.3  446.79  5190.4  450.75  5240.4  453.68  5256.2  453.95
#Mann=6,-1,0
  4526.3    0.08       0  4696.4    0.05       0  4935.8    0.07       0
  4942.3    0.05       0  4994.2    0.08       0  5093.4    0.05       0
Bank Sta=4735.9,5035.5
Exp/Cntr=0.3,0.1

Type RM Length L Ch R = 1,98046,386,386,386
BEGIN DESCRIPTION:
DRY CREEK 88.0
END DESCRIPTION:
XS GIS Cut Line= 3
      2916695.19      7033397.63      2916344.31      7033370.86
      2915934.81      7033369.85
#Sta/Elev= 30
  4648.1  447.62  4678.4  447.66  4708.5  446.21  4746.0  445.49  4749.8  444.26
  4753.6  443.86  4808.8  443.41  4848.9  443.68  4881.9  442.98  4951.9  443.62
  4959.2  443.54  4969.2  444.25  4979.2  443.69  4989.3  441.76  4993.9  441.50
  4994.4  440.70  4999.9  440.70  5000.4  441.50  5009.3  441.61  5019.3  443.39
  5047.2  444.26  5129.3  445.83  5150.1  446.95  5169.3  447.60  5199.3  447.08
  5229.3  447.42  5289.3  449.02  5347.3  451.64  5352.3  451.45  5409.5  453.10
#Mann=6,-1,0
  4648.1    0.08       0  4753.6    0.05       0  4951.9    0.08       0
  4993.9    0.07       0  5000.4    0.08       0  5150.1    0.05       0
Bank Sta=4749.8,5047.2
Exp/Cntr=0.3,0.1

Type RM Length L Ch R = 1,97660,521,521,521
BEGIN DESCRIPTION:
Mapping XS cbbbda7a
END DESCRIPTION:
XS GIS Cut Line= 3
      2916817.70      7033113.55      2916266.52      7033022.41
      2915904.79      7033150.21
#Sta/Elev= 30
  4429.0  449.55  4453.9  449.11  4509.9  446.28  4571.0  446.45  4632.0  445.72
  4774.3  441.22  4786.5  440.11  4806.8  441.13  4815.2  439.18  4820.3  439.29
  4827.0  438.27  4847.3  438.29  4857.4  438.46  4876.3  440.45  4948.7  440.58
  4979.1  441.69  4991.1  441.36  4996.6  436.89  4997.1  436.09  5002.6  436.09
  5003.1  436.89  5007.8  440.88  5009.7  441.22  5021.1  442.05  5038.7  441.49
  5137.8  443.68  5212.0  443.59  5249.8  445.21  5280.8  445.29  5371.3  449.57
#Mann=3,-1,0
  4429.0    0.05       0  4996.6    0.03       0  5003.1    0.05       0
Bank Sta=4774.3,5009.7
Exp/Cntr=0.3,0.1

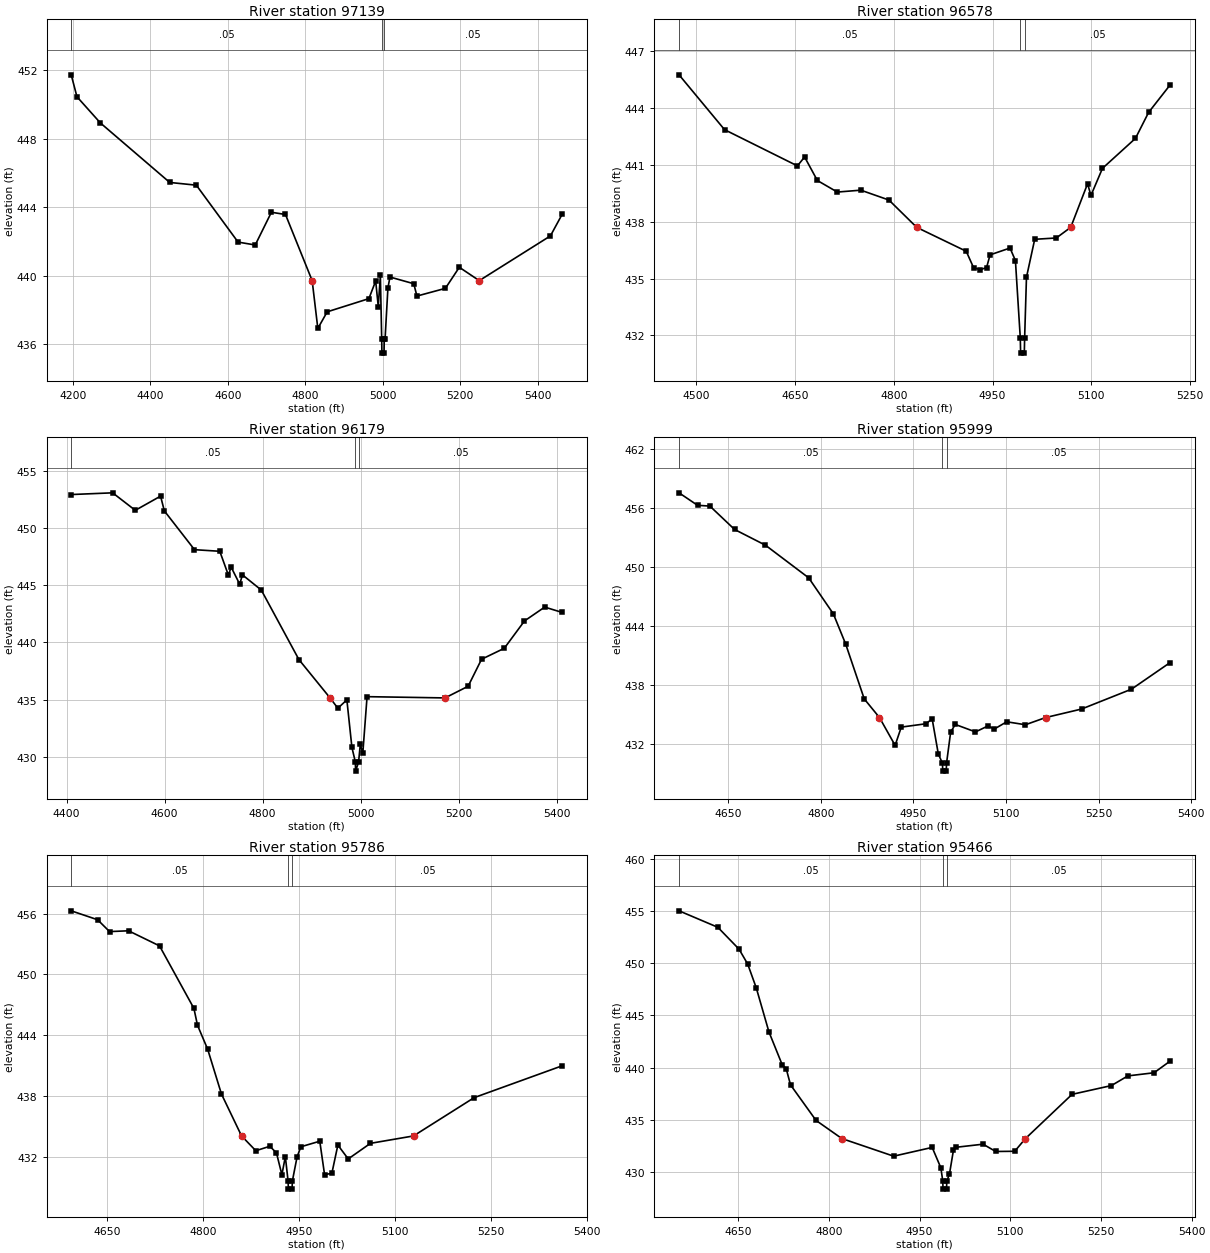
Type RM Length L Ch R = 1,97139,561,561,561
BEGIN DESCRIPTION:
DRY CREEK 87.0
END DESCRIPTION:
XS GIS Cut Line= 3
      2917024.97      7032824.99      2916275.00      7032525.00
      2915841.63      7032680.60
#Sta/Elev= 30
  4195.5  451.72  4210.3  450.44  4270.9  448.91  4449.9  445.44  4518.6  445.28
  4626.3  441.96  4670.7  441.79  4712.4  443.70  4748.8  443.57  4817.7  439.71
  4832.3  436.92  4856.5  437.89  4964.2  438.66  4981.7  439.69  4988.4  438.20
  4993.8  440.01  4997.3  436.28  4997.8  435.48  5003.3  435.48  5003.8  436.28
  5005.9  436.28  5013.3  439.28  5018.6  439.92  5080.1  439.53  5088.2  438.81
  5161.7  439.26  5197.7  440.49  5249.2  439.71  5432.9  442.32  5463.7  443.60
#Mann=3,-1,0
  4195.5    0.05       0  4997.3    0.03       0  5003.8    0.05       0
Bank Sta=4817.7,5249.2
Exp/Cntr=0.3,0.1

Type RM Length L Ch R = 1,96578,399,399,399
BEGIN DESCRIPTION:
DRY CREEK 86.0
END DESCRIPTION:
XS GIS Cut Line= 3
      2916933.74      7032264.53      2916425.00      7032075.00
      2916222.39      7032087.66
#Sta/Elev= 30
  4473.8  445.74  4542.9  442.85  4653.6  440.94  4664.5  441.41  4683.9  440.17
  4714.2  439.56  4749.9  439.66  4792.6  439.14  4834.8  437.70  4910.0  436.44
  4921.2  435.57  4931.3  435.47  4940.9  435.58  4946.2  436.25  4976.5  436.61
  4984.7  435.95  4992.1  431.87  4992.6  431.07  4998.2  431.07  4998.7  431.87
  5001.5  435.07  5014.0  437.07  5046.8  437.14  5068.7  437.70  5094.3  440.00
  5099.4  439.38  5116.9  440.81  5167.0  442.39  5187.0  443.76  5219.7  445.21
#Mann=3,-1,0
  4473.8    0.05       0  4992.1    0.03       0  4998.7    0.05       0
Bank Sta=4834.8,5068.7
Exp/Cntr=0.3,0.1

Type RM Length L Ch R = 1,96179,180,180,180
BEGIN DESCRIPTION:
Mapping XS ba043351
END DESCRIPTION:
XS GIS Cut Line= 3
      2917208.00      7032014.51      2916711.50      7031788.84
      2916268.52      7031899.58
#Sta/Elev= 30
  4409.5  452.93  4494.0  453.08  4540.2  451.55  4591.8  452.79  4599.5  451.50
  4661.0  448.11  4712.6  447.97  4730.2  445.88  4735.7  446.59  4753.3  445.09
  4758.8  445.91  4797.3  444.58  4874.1  438.50  4937.6  435.15  4953.5  434.25
  4971.9  434.98  4982.2  430.82  4989.2  429.55  4989.7  428.75  4995.8  429.55
  4999.3  431.08  5004.4  430.31  5013.1  435.26  5172.2  435.15  5219.3  436.17
  5246.7  438.53  5293.1  439.49  5334.3  441.88  5375.5  443.09  5411.5  442.62
#Mann=3,-1,0
  4409.5    0.05       0  4989.2    0.03       0  4995.8    0.05       0
Bank Sta=4937.6,5172.2
Exp/Cntr=0.3,0.1

Type RM Length L Ch R = 1,95999,213,213,213
BEGIN DESCRIPTION:
DRY CREEK 85.0
END DESCRIPTION:
XS GIS Cut Line= 3
      2917125.00      7031625.00      2916675.00      7031625.00
      2916333.03      7031674.25
#Sta/Elev= 30
  4570.5  457.55  4600.5  456.28  4620.5  456.20  4660.5  453.82  4710.5  452.22
  4780.5  448.90  4820.5  445.23  4840.5  442.15  4870.5  436.58  4895.2  434.68
  4920.5  431.85  4930.5  433.71  4970.5  434.05  4980.5  434.55  4990.5  430.97
  4997.2  430.03  4997.7  429.23  5003.3  429.23  5003.8  430.03  5010.5  433.21
  5018.0  433.98  5050.7  433.22  5071.0  433.83  5081.1  433.51  5101.3  434.25
  5131.6  433.95  5164.2  434.68  5222.6  435.55  5303.4  437.57  5366.0  440.28
#Mann=3,-1,0
  4570.5    0.05       0  4997.2    0.03       0  5003.8    0.05       0
Bank Sta=4895.2,5164.2
Exp/Cntr=0.3,0.1

Type RM Length L Ch R = 1,95786,320,320,320
BEGIN DESCRIPTION:
Mapping XS 550a9288
END DESCRIPTION:
XS GIS Cut Line= 3
      2917093.41      7031563.13      2916718.45      7031413.84
      2916360.80      7031486.75
#Sta/Elev= 30
  4593.5  456.28  4634.8  455.40  4653.5  454.23  4683.2  454.31  4731.7  452.82
  4785.5  446.65  4791.1  444.99  4807.1  442.61  4828.6  438.20  4860.1  434.06
  4882.4  432.60  4904.3  433.04  4914.7  432.39  4923.2  430.23  4928.6  432.02
  4932.9  429.61  4933.4  428.81  4939.1  428.81  4939.6  429.61  4947.0  432.00
  4952.9  432.99  4982.5  433.54  4990.0  430.24  5001.4  430.37  5010.8  433.16
  5027.0  431.79  5061.8  433.33  5129.2  434.06  5224.1  437.84  5362.1  440.99
#Mann=3,-1,0
  4593.5    0.05       0  4932.9    0.03       0  4939.6    0.05       0
Bank Sta=4860.1,5129.2
Exp/Cntr=0.3,0.1

Type RM Length L Ch R = 1,95466,365,365,365
BEGIN DESCRIPTION:
DRY CREEK 84.0
END DESCRIPTION:
XS GIS Cut Line= 3
      2917124.99      7031474.99      2916825.00      7031125.00
      2916489.62      7031229.70
#Sta/Elev= 30
  4552.1  455.03  4616.3  453.45  4651.4  451.35  4665.7  449.92  4679.9  447.63
  4700.8  443.42  4722.8  440.26  4729.3  439.90  4736.5  438.34  4778.7  434.93
  4821.4  433.19  4907.1  431.50  4970.8  432.34  4985.1  430.39  4988.3  429.14
  4988.8  428.34  4994.5  428.34  4995.0  429.14  4999.3  429.75  5005.9  432.05
  5009.8  432.35  5055.0  432.65  5075.9  431.95  5107.3  431.97  5125.1  433.19
  5202.2  437.43  5267.2  438.27  5294.5  439.20  5337.8  439.50  5364.4  440.62
#Mann=3,-1,0
  4552.1    0.05       0  4988.3    0.03       0  4995.0    0.05       0
Bank Sta=4821.4,5125.1
Exp/Cntr=0.3,0.1

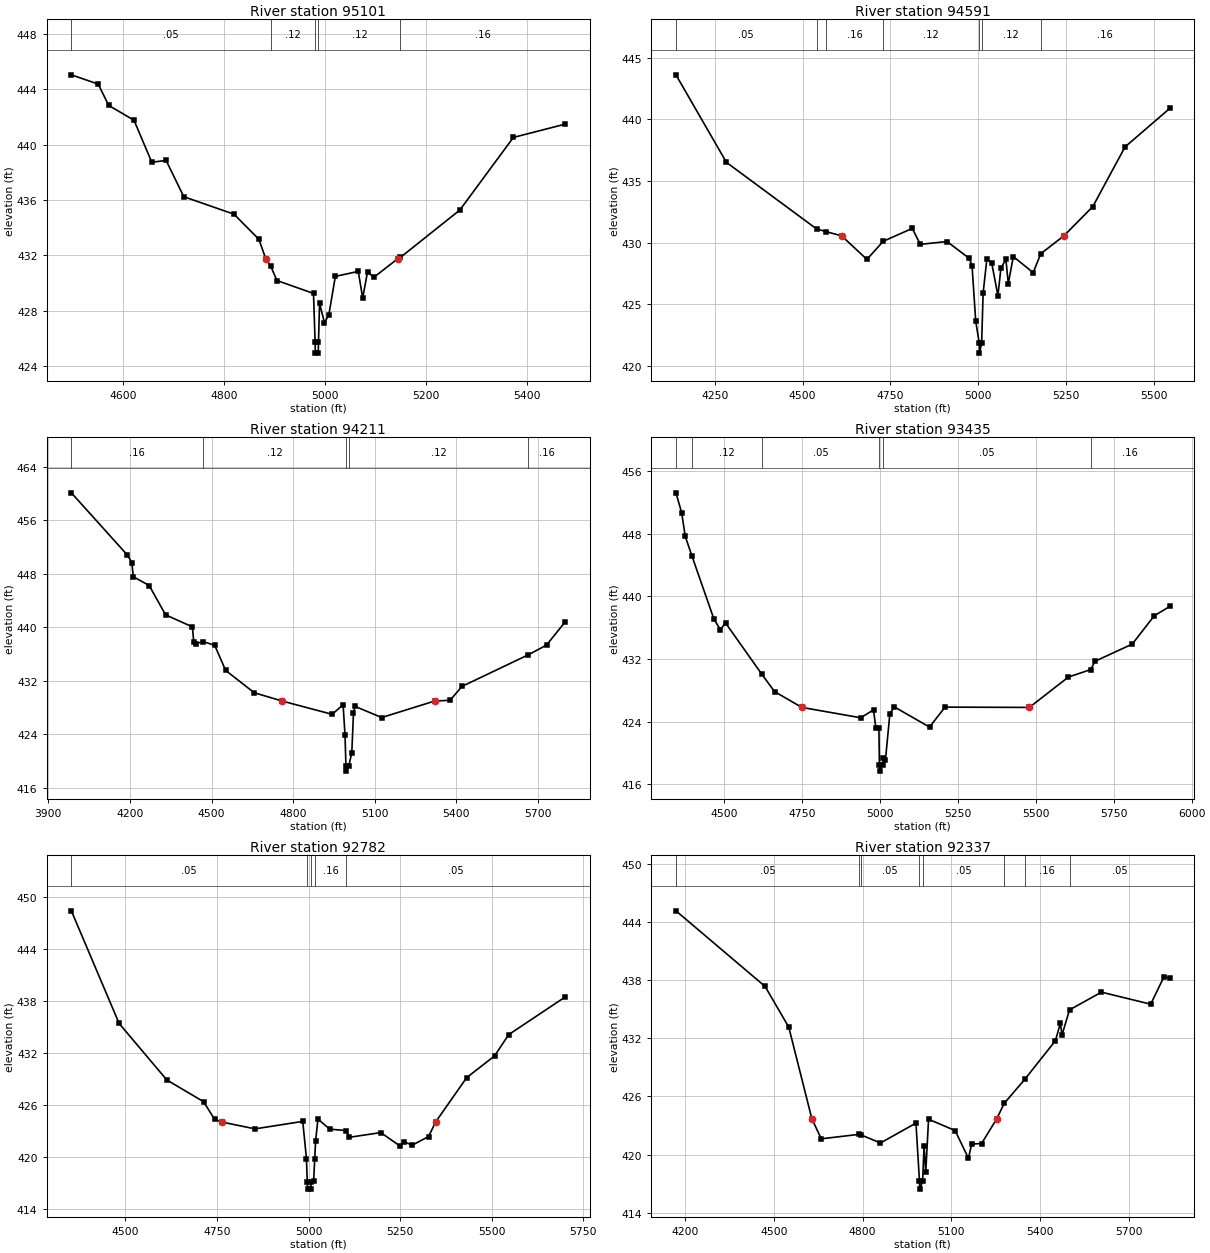
Type RM Length L Ch R = 1,95101,510,510,510
BEGIN DESCRIPTION:
Mapping XS 8f9c045e
END DESCRIPTION:
XS GIS Cut Line= 3
      2917155.93      7031129.09      2916839.98      7030774.95
      2916374.67      7030969.40
#Sta/Elev= 30
  4497.6  445.04  4550.8  444.37  4571.7  442.83  4621.8  441.76  4657.0  438.73
  4685.4  438.86  4720.5  436.24  4820.0  434.98  4869.3  433.17  4882.9  431.77
  4892.5  431.25  4905.1  430.19  4977.6  429.26  4980.8  425.75  4981.3  424.95
  4987.0  424.95  4987.5  425.75  4989.6  428.55  4999.3  427.15  5008.0  427.71
  5020.9  430.49  5066.4  430.85  5075.1  428.93  5084.8  430.83  5096.8  430.41
  5144.8  431.77  5149.9  431.86  5267.7  435.28  5373.8  440.52  5476.5  441.48
#Mann=5,-1,0
  4497.6    0.05       0  4892.5    0.12       0  4980.8    0.07       0
  4987.5    0.12       0  5149.9    0.16       0
Bank Sta=4882.9,5144.8
Exp/Cntr=0.3,0.1

Type RM Length L Ch R = 1,94591,380,380,380
BEGIN DESCRIPTION:
DRY CREEK 83.0
END DESCRIPTION:
XS GIS Cut Line= 4
      2917200.00      7031000.01      2916909.13      7030361.03
      2916692.12      7030289.41      2916349.25      7030619.31
#Sta/Elev= 30
  4139.4  443.60  4283.2  436.51  4539.8  431.12  4565.8  430.91  4611.2  430.56
  4683.3  428.65  4729.8  430.12  4812.4  431.16  4835.5  429.87  4911.4  430.10
  4974.9  428.73  4982.7  428.14  4993.2  423.64  5003.3  421.86  5003.8  421.06
  5010.0  421.86  5014.3  425.94  5024.8  428.65  5038.4  428.40  5056.4  425.72
  5064.9  427.94  5079.1  428.65  5086.0  426.69  5100.2  428.88  5156.8  427.58
  5178.4  429.11  5244.3  430.56  5326.6  432.93  5418.4  437.76  5545.8  440.88
#Mann=7,-1,0
  4139.4    0.05       0  4539.8    0.12       0  4565.8    0.16       0
  4729.8    0.12       0  5003.3    0.07       0  5010.0    0.12       0
  5178.4    0.16       0
Bank Sta=4611.2,5244.3
Exp/Cntr=0.3,0.1

Type RM Length L Ch R = 1,94211,776,776,776
BEGIN DESCRIPTION:
DRY CREEK 82.0
END DESCRIPTION:
XS GIS Cut Line= 3
      2917750.00      7030100.00      2916738.86      7030009.36
      2916034.66      7030389.40
#Sta/Elev= 30
  3984.8  460.14  4190.6  450.83  4207.3  449.71  4212.3  447.59  4270.9  446.27
  4331.2  441.88  4429.7  440.08  4434.7  437.85  4441.6  437.56  4469.6  437.88
  4511.9  437.31  4552.1  433.56  4657.2  430.22  4759.8  428.98  4943.6  426.99
  4983.8  428.43  4990.8  423.89  4994.2  419.29  4995.0  418.49  5004.7  419.29
  5015.7  421.22  5021.9  427.12  5027.6  428.18  5125.7  426.51  5320.3  428.98
  5377.0  429.09  5420.8  431.17  5664.7  435.90  5731.6  437.35  5800.2  440.83
#Mann=5,-1,0
  3984.8    0.16       0  4469.6    0.12       0  4994.2    0.07       0
  5004.7    0.12       0  5664.7    0.16       0
Bank Sta=4759.8,5320.3
Exp/Cntr=0.3,0.1

Type RM Length L Ch R = 1,93435,653,653,653
BEGIN DESCRIPTION:
DRY CREEK 81.0
END DESCRIPTION:
XS GIS Cut Line= 3
      2917154.09      7029135.20      2916525.00      7029275.00
      2915874.58      7029954.69
#Sta/Elev= 30
  4344.5  453.24  4362.8  450.71  4374.3  447.69  4395.4  445.22  4466.5  437.10
  4487.0  435.77  4503.6  436.62  4620.0  430.07  4661.1  427.84  4748.7  425.82
  4937.7  424.50  4978.7  425.51  4986.4  423.16  4996.0  423.17  4997.7  418.48
  4998.5  417.68  5008.2  418.48  5010.2  419.39  5017.1  419.13  5031.2  425.02
  5045.4  425.89  5158.6  423.31  5208.3  425.86  5479.0  425.82  5604.3  429.70
  5676.3  430.66  5689.2  431.71  5809.3  433.91  5880.1  437.54  5929.7  438.72
#Mann=6,-1,0
  4344.5    0.16       0  4395.4    0.12       0  4620.0    0.05       0
  4997.7    0.03       0  5008.2    0.05       0  5676.3    0.16       0
Bank Sta=4748.7,5479
Exp/Cntr=0.3,0.1

Type RM Length L Ch R = 1,92782,445,445,445
BEGIN DESCRIPTION:
DRY CREEK 80.0
END DESCRIPTION:
XS GIS Cut Line= 3
      2916724.98      7028825.00      2916075.00      7028875.00
      2915425.02      7029124.99
#Sta/Elev= 30
  4352.2  448.39  4482.6  435.42  4612.9  428.91  4713.2  426.41  4743.3  424.38
  4762.5  424.07  4853.7  423.28  4984.0  424.14  4994.1  419.85  4996.3  417.14
  4997.2  416.34  5006.0  416.34  5006.9  417.14  5013.7  417.28  5016.7  419.85
  5019.1  421.91  5025.5  424.40  5057.7  423.25  5102.5  423.08  5111.2  422.31
  5197.0  422.85  5250.5  421.28  5261.2  421.79  5282.7  421.40  5327.7  422.40
  5346.7  424.07  5431.6  429.18  5507.7  431.68  5546.2  434.13  5700.5  438.47
#Mann=5,-1,0
  4352.2    0.05       0  4996.3    0.03       0  5006.9    0.05       0
  5016.7    0.16       0  5102.5    0.05       0
Bank Sta=4762.5,5346.7
Exp/Cntr=0.3,0.1

Type RM Length L Ch R = 1,92337,690,690,690
BEGIN DESCRIPTION:
DRY CREEK 79.0
END DESCRIPTION:
XS GIS Cut Line= 3
      2916666.41      7028523.14      2915835.75      7028515.51
      2915089.18      7028897.68
#Sta/Elev= 30
  4169.3  445.14  4470.7  437.34  4550.7  433.14  4628.9  423.67  4660.7  421.62
  4788.1  422.08  4793.7  422.04  4860.7  421.19  4980.7  423.24  4992.6  417.23
  4993.5  416.43  5003.2  417.23  5008.2  420.91  5013.8  418.17  5023.3  423.64
  5113.2  422.47  5158.0  419.62  5169.3  421.09  5202.4  421.13  5253.5  423.67
  5279.3  425.29  5348.2  427.74  5452.3  431.75  5468.9  433.54  5474.5  432.34
  5499.8  434.92  5607.7  436.75  5774.2  435.51  5818.6  438.30  5838.7  438.21
#Mann=8,-1,0
  4169.3    0.05       0  4788.1    0.16       0  4793.7    0.05       0
  4992.6    0.07       0  5003.2    0.05       0  5279.3    0.05       0
  5348.2    0.16       0  5499.8    0.05       0
Bank Sta=4628.9,5253.5
Exp/Cntr=0.3,0.1