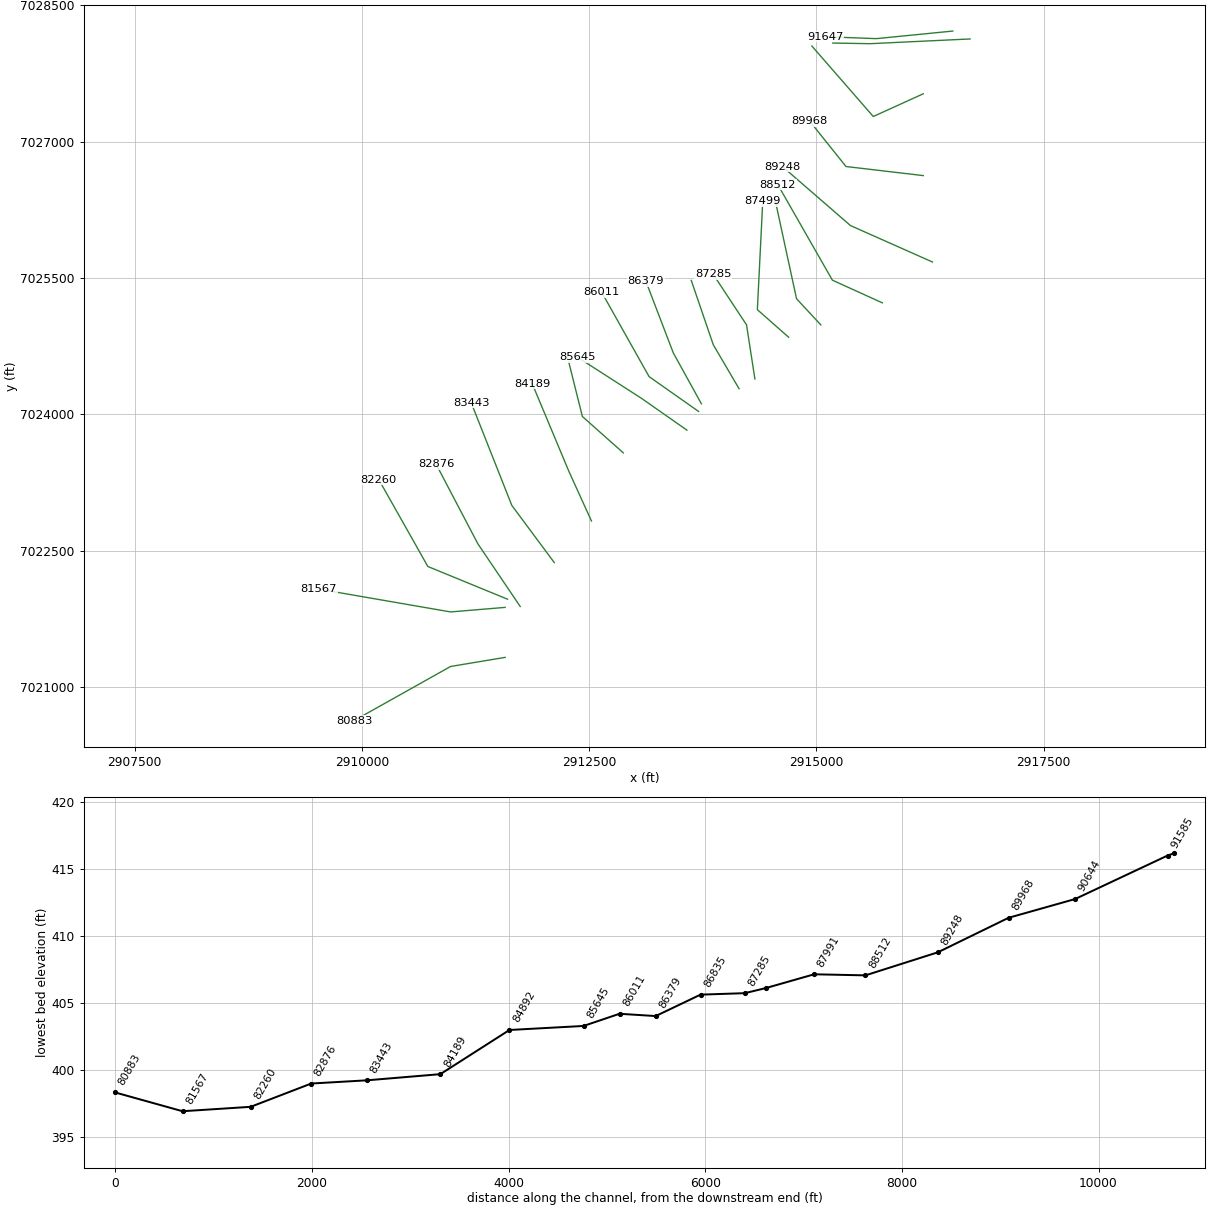
HEC-RAS study DRY CREEK.prj: DRY CREEK Base Level Engineering

--- DRY CREEK.g01 (geometry) --- (continued)

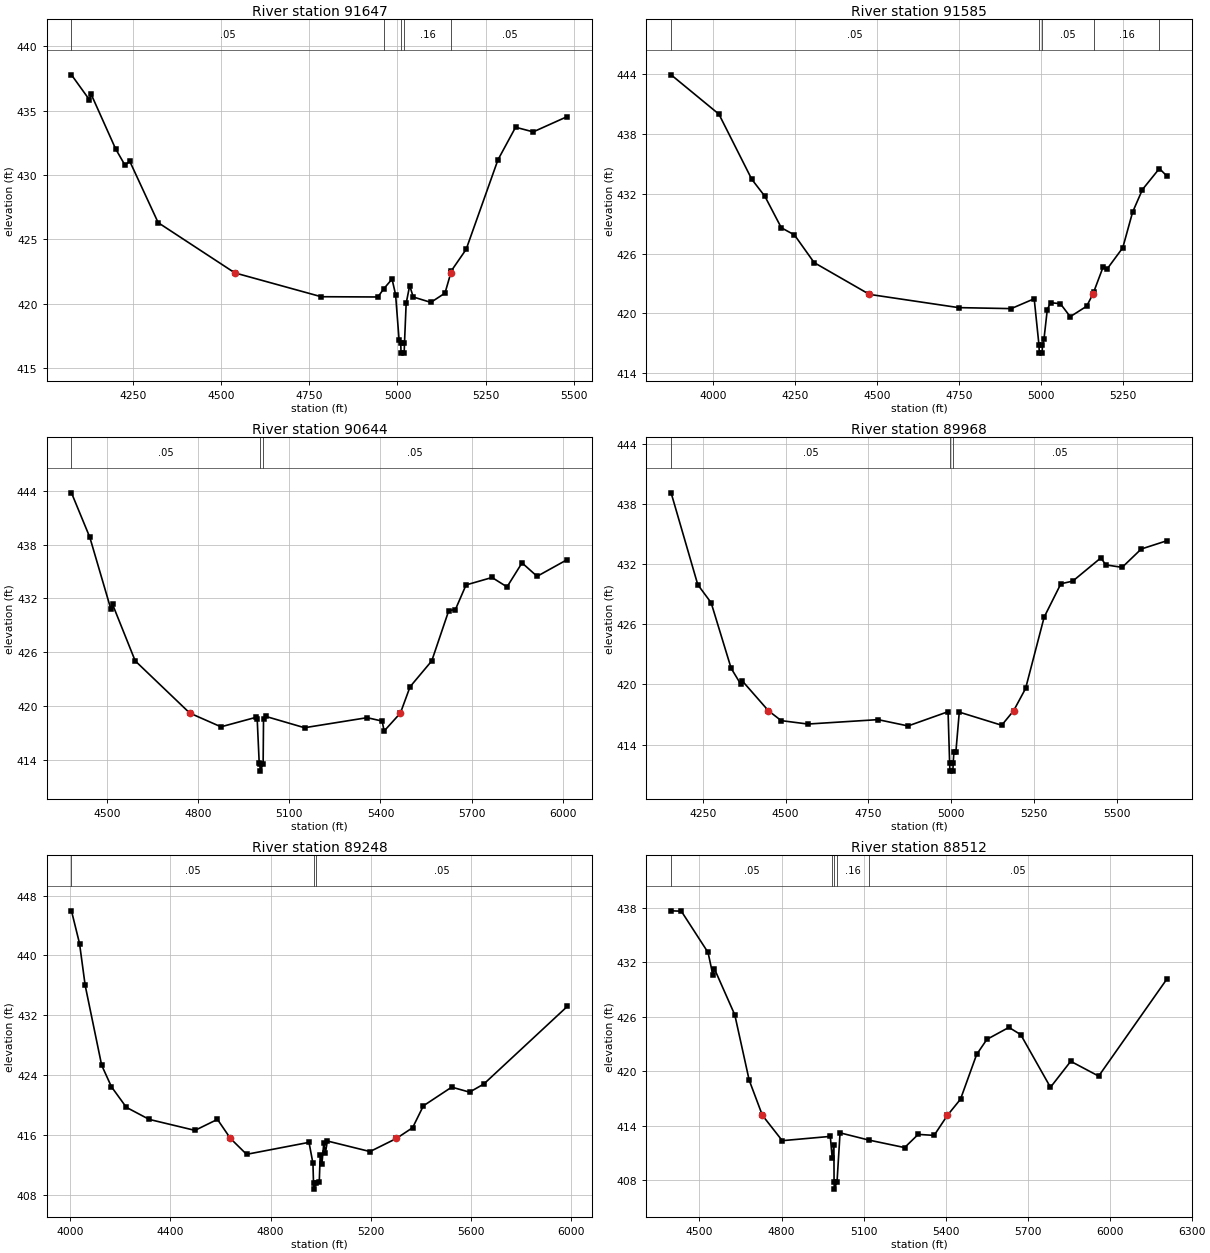
Type RM Length L Ch R = 1,91647,62,62,62
BEGIN DESCRIPTION:
Mapping XS 7e80301d
END DESCRIPTION:
XS GIS Cut Line= 3
      2916499.61      7028215.08      2915659.33      7028131.75
      2915098.41      7028152.52
#Sta/Elev= 30
  4075.9  437.77  4126.6  435.84  4131.6  436.27  4201.1  432.02  4227.5  430.76
  4241.3  431.05  4321.7  426.29  4539.1  422.39  4784.0  420.54  4944.6  420.52
  4961.6  421.17  4984.7  421.91  4994.7  420.71  5004.7  417.17  5009.4  416.96
  5010.2  416.16  5019.1  416.16  5020.0  416.96  5024.7  420.02  5034.7  421.41
  5044.7  420.52  5094.7  420.10  5134.8  420.82  5151.3  422.39  5153.0  422.56
  5194.8  424.22  5284.9  431.17  5334.9  433.70  5384.9  433.34  5481.6  434.53
#Mann=5,-1,0
  4075.9    0.05       0  4961.6    0.16       0  5009.4    0.07       0
  5020.0    0.16       0  5153.0    0.05       0
Bank Sta=4539.1,5151.3
Exp/Cntr=0.3,0.1

Type RM Length L Ch R = 1,91585,941,941,941
BEGIN DESCRIPTION:
Mapping XS 84658ac2
END DESCRIPTION:
XS GIS Cut Line= 3
      2916690.59      7028128.28      2915589.89      7028076.19
      2915180.18      7028083.14
#Sta/Elev= 30
  3873.2  443.95  4019.0  440.00  4119.1  433.46  4159.1  431.75  4209.2  428.59
  4249.2  427.87  4309.3  425.09  4477.8  421.90  4749.8  420.57  4910.0  420.47
  4980.1  421.46  4994.7  416.80  4995.6  416.00  5004.5  416.00  5005.3  416.80
  5010.0  417.43  5020.0  420.36  5030.0  421.07  5060.0  420.96  5090.0  419.66
  5140.0  420.71  5158.6  421.90  5161.0  422.09  5190.1  424.64  5202.4  424.45
  5250.1  426.58  5280.1  430.16  5310.1  432.43  5361.8  434.54  5384.9  433.77
#Mann=5,-1,0
  3873.2    0.05       0  4994.7    0.03       0  5005.3    0.05       0
  5161.0    0.16       0  5361.8    0.05       0
Bank Sta=4477.8,5158.6
Exp/Cntr=0.3,0.1

Type RM Length L Ch R = 1,90644,676,676,676
BEGIN DESCRIPTION:
DRY CREEK 77.0
END DESCRIPTION:
XS GIS Cut Line= 3
      2916174.98      7027524.99      2915625.00      7027275.00
      2914949.98      7028050.02
#Sta/Elev= 30
  4383.0  443.78  4443.4  438.82  4512.6  430.82  4518.1  431.36  4592.8  425.04
  4772.4  419.22  4875.1  417.69  4990.4  418.75  4994.3  418.51  5000.9  413.63
  5003.1  413.55  5004.0  412.75  5013.8  413.55  5015.1  418.61  5022.7  418.85
  5150.0  417.59  5356.0  418.71  5405.4  418.33  5412.0  417.22  5465.5  419.22
  5497.4  422.16  5568.7  425.04  5624.7  430.65  5646.5  430.76  5681.6  433.51
  5767.1  434.34  5816.4  433.29  5865.8  435.97  5915.4  434.47  6014.9  436.34
#Mann=3,-1,0
  4383.0    0.05       0  5003.1    0.03       0  5013.8    0.05       0
Bank Sta=4772.4,5465.5
Exp/Cntr=0.3,0.1

Type RM Length L Ch R = 1,89968,720,720,720
BEGIN DESCRIPTION:
DRY CREEK 76.0
END DESCRIPTION:
XS GIS Cut Line= 3
      2916175.00      7026625.00      2915325.00      7026725.00
      2914924.98      7027225.02
#Sta/Elev= 30
  4154.8  439.13  4235.3  429.96  4275.6  428.16  4336.0  421.61  4365.0  420.03
  4370.0  420.34  4448.4  417.38  4487.1  416.39  4567.6  416.05  4779.1  416.49
  4869.7  415.86  4990.5  417.28  4995.2  412.15  4996.1  411.35  5005.1  411.35
  5005.9  412.15  5008.1  413.21  5013.9  413.21  5024.3  417.24  5152.3  415.93
  5188.3  417.38  5224.4  419.60  5280.4  426.72  5330.8  430.05  5366.8  430.32
  5451.7  432.64  5466.1  431.94  5515.7  431.69  5573.3  433.52  5651.0  434.35
#Mann=3,-1,0
  4154.8    0.05       0  4995.2    0.03       0  5005.9    0.05       0
Bank Sta=4448.4,5188.3
Exp/Cntr=0.3,0.1

Type RM Length L Ch R = 1,89248,736,736,736
BEGIN DESCRIPTION:
DRY CREEK 75.0
END DESCRIPTION:
XS GIS Cut Line= 3
      2916275.02      7025674.99      2915375.00      7026075.00
      2914624.99      7026725.01
#Sta/Elev= 30
  4006.0  445.96  4038.2  441.59  4060.7  435.99  4126.4  425.33  4165.4  422.45
  4224.9  419.70  4315.9  418.09  4498.5  416.62  4588.1  418.09  4640.1  415.54
  4704.3  413.42  4953.3  415.02  4969.0  412.21  4971.2  409.57  4972.0  408.77
  4981.9  409.57  4994.2  409.75  4998.0  413.36  5004.7  412.11  5012.3  414.98
  5018.9  413.65  5026.5  415.20  5196.5  413.79  5301.7  415.54  5366.5  416.98
  5409.3  419.90  5522.3  422.40  5593.5  421.73  5650.5  422.82  5983.4  433.19
#Mann=3,-1,0
  4006.0    0.05       0  4971.2    0.03       0  4981.9    0.05       0
Bank Sta=4640.1,5301.7
Exp/Cntr=0.3,0.1

Type RM Length L Ch R = 1,88512,521,521,521
BEGIN DESCRIPTION:
DRY CREEK 74.0
END DESCRIPTION:
XS GIS Cut Line= 3
      2915725.02      7025224.99      2915175.00      7025475.00
      2914575.01      7026524.99
#Sta/Elev= 30
  4396.2  437.66  4433.6  437.62  4531.3  433.08  4548.9  430.61  4554.4  431.30
  4629.1  426.22  4681.8  419.03  4730.0  415.17  4802.7  412.38  4978.4  412.85
  4985.5  410.44  4991.6  411.86  4992.2  407.85  4993.1  407.05  5003.0  407.85
  5014.1  413.24  5118.8  412.45  5250.2  411.62  5299.8  413.07  5358.1  412.96
  5406.8  415.17  5454.6  416.94  5513.6  421.86  5551.1  423.52  5631.7  424.84
  5674.9  424.04  5783.6  418.25  5857.7  421.11  5959.9  419.48  6209.7  430.17
#Mann=5,-1,0
  4396.2    0.05       0  4985.5    0.16       0  4992.2    0.07       0
  5003.0    0.16       0  5118.8    0.05       0
Bank Sta=4730,5406.8
Exp/Cntr=0.3,0.1

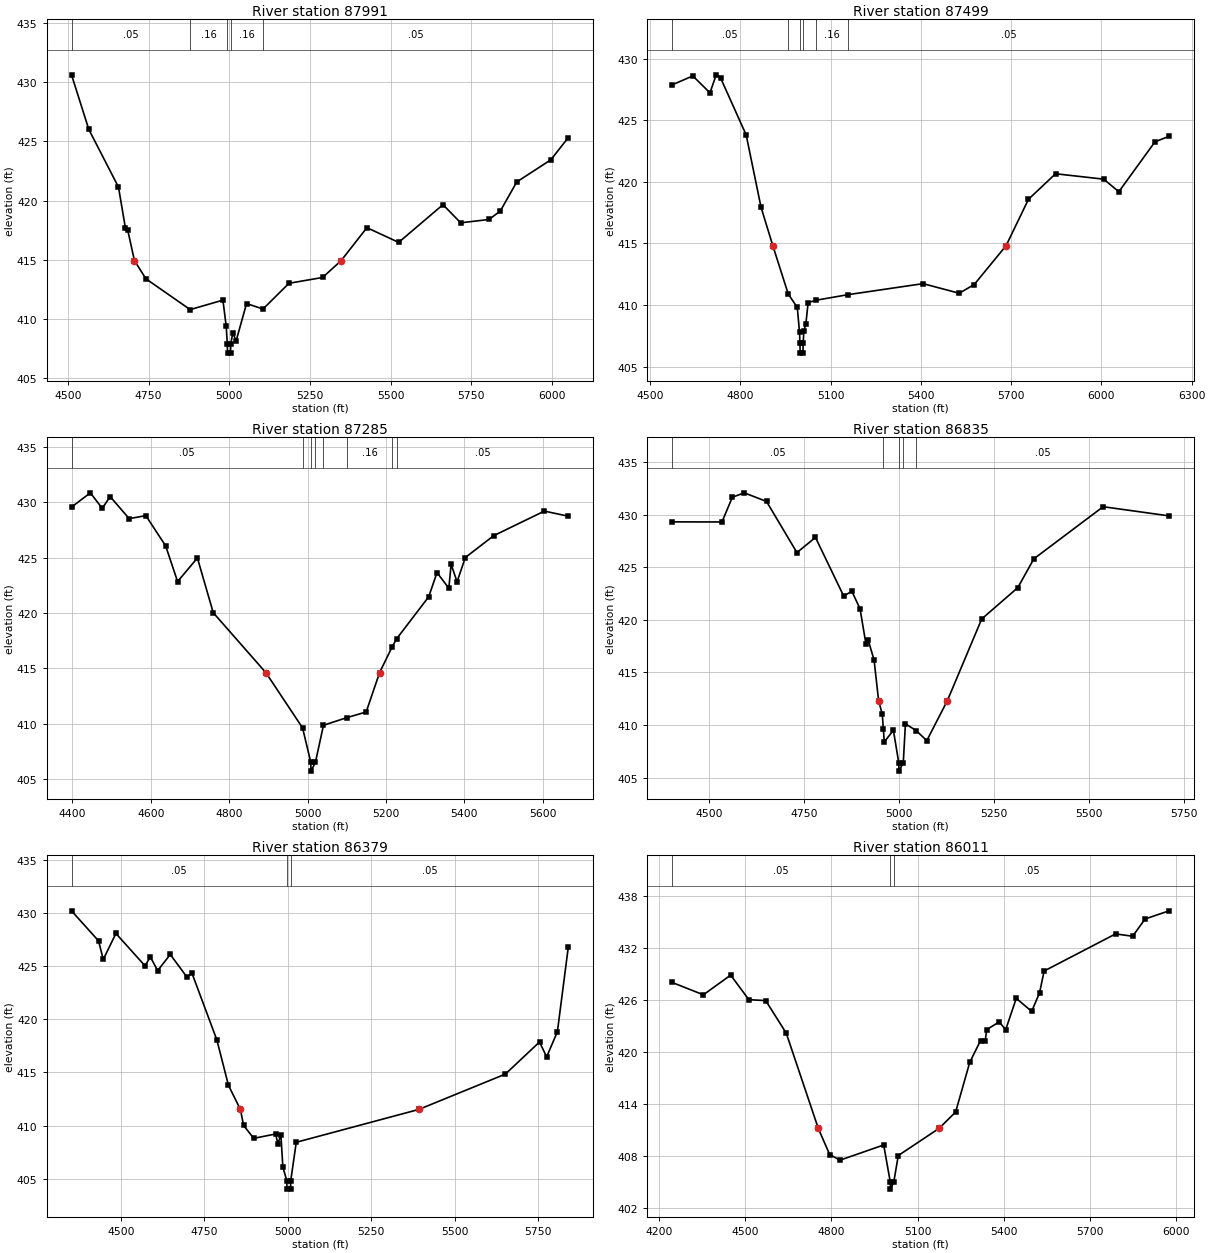
Type RM Length L Ch R = 1,87991,492,492,492
BEGIN DESCRIPTION:
Mapping XS 520a09b7
END DESCRIPTION:
XS GIS Cut Line= 3
      2915048.22      7024982.44      2914780.86      7025270.64
      2914538.03      7026391.11
#Sta/Elev= 30
  4510.9  430.60  4564.6  425.99  4656.5  421.13  4678.0  417.67  4684.8  417.55
  4705.9  414.93  4741.5  413.40  4878.6  410.80  4980.1  411.60  4990.3  409.40
  4993.6  407.93  4994.4  407.13  5003.6  407.13  5004.4  407.93  5010.8  408.84
  5021.0  408.16  5053.3  411.31  5104.4  410.85  5184.8  413.02  5289.0  413.51
  5346.4  414.93  5426.3  417.71  5524.7  416.47  5662.0  419.65  5716.8  418.12
  5804.5  418.40  5839.6  419.11  5890.8  421.57  5996.1  423.43  6050.5  425.31
#Mann=5,-1,0
  4510.9    0.05       0  4878.6    0.16       0  4993.6    0.07       0
  5004.4    0.16       0  5104.4    0.05       0
Bank Sta=4705.9,5346.4
Exp/Cntr=0.3,0.1

Type RM Length L Ch R = 1,87499,214,214,214
BEGIN DESCRIPTION:
DRY CREEK 73.0
END DESCRIPTION:
XS GIS Cut Line= 3
      2914694.07      7024847.01      2914350.00      7025150.00
      2914409.24      7026341.77
#Sta/Elev= 30
  4573.1  427.88  4641.6  428.60  4698.6  427.23  4719.4  428.69  4733.7  428.45
  4819.0  423.81  4868.4  417.94  4907.6  414.82  4958.8  410.90  4988.9  409.81
  4996.4  407.79  4997.7  406.90  4998.5  406.10  5007.7  406.10  5008.5  406.90
  5010.7  407.88  5017.3  408.45  5024.9  410.19  5050.2  410.39  5158.7  410.85
  5407.0  411.74  5527.2  410.96  5577.2  411.67  5683.0  414.82  5757.5  418.59
  5847.6  420.66  6007.8  420.22  6057.8  419.20  6178.0  423.25  6224.8  423.70
#Mann=6,-1,0
  4573.1    0.05       0  4958.8    0.12       0  4997.7    0.07       0
  5008.5    0.12       0  5050.2    0.16       0  5158.7    0.05       0
Bank Sta=4907.6,5683
Exp/Cntr=0.3,0.1

Type RM Length L Ch R = 1,87285,450,450,450
BEGIN DESCRIPTION:
DRY CREEK 72.0
END DESCRIPTION:
XS GIS Cut Line= 3
      2914322.97      7024387.51      2914230.86      7024982.83
      2913864.66      7025538.51
#Sta/Elev= 30
  4397.6  429.55  4445.7  430.84  4476.0  429.44  4496.2  430.50  4544.8  428.51
  4587.3  428.78  4637.9  426.05  4668.3  422.83  4718.9  424.96  4759.3  420.02
  4893.6  414.61  4987.3  409.62  5008.2  406.52  5008.8  405.72  5020.1  406.52
  5040.6  409.86  5100.5  410.55  5149.6  411.06  5183.8  414.61  5215.9  416.94
  5227.2  417.66  5309.2  421.46  5330.3  423.64  5360.5  422.23  5366.4  424.39
  5381.5  422.81  5402.6  425.00  5474.9  426.97  5604.3  429.19  5665.5  428.73
#Mann=8,-1,0
  4397.6    0.05       0  4987.3    0.16       0  5008.2    0.07       0
  5020.1    0.16       0  5040.6    0.12       0  5100.5    0.16       0
  5215.9    0.12       0  5227.2    0.05       0
Bank Sta=4893.6,5183.8
Exp/Cntr=0.3,0.1

Type RM Length L Ch R = 1,86835,456,456,456
BEGIN DESCRIPTION:
Mapping XS 0df58b32
END DESCRIPTION:
XS GIS Cut Line= 3
      2914148.47      7024280.77      2913864.64      7024765.11
      2913623.03      7025471.77
#Sta/Elev= 30
  4403.1  429.30  4534.1  429.29  4561.4  431.64  4592.8  432.06  4651.4  431.24
  4731.5  426.38  4780.3  427.82  4854.6  422.25  4876.1  422.70  4897.6  421.05
  4913.3  417.68  4919.1  418.07  4934.7  416.16  4946.5  412.31  4956.2  411.02
  4959.1  409.58  4961.5  408.39  4985.5  409.49  4999.6  406.41  5000.1  405.61
  5011.5  406.41  5017.2  410.11  5045.6  409.46  5073.4  408.51  5127.6  412.31
  5218.0  420.07  5313.1  423.05  5355.4  425.79  5537.8  430.74  5711.3  429.87
#Mann=5,-1,0
  4403.1    0.05       0  4959.1    0.16       0  4999.6    0.07       0
  5011.5    0.16       0  5045.6    0.05       0
Bank Sta=4946.5,5127.6
Exp/Cntr=0.3,0.1

Type RM Length L Ch R = 1,86379,368,368,368
BEGIN DESCRIPTION:
DRY CREEK 71.0
END DESCRIPTION:
XS GIS Cut Line= 3
      2913734.42      7024114.09      2913425.00      7024675.00
      2913122.46      7025465.60
#Sta/Elev= 30
  4352.7  430.21  4433.7  427.38  4447.7  425.63  4485.6  428.08  4572.7  425.03
  4588.7  425.87  4610.5  424.58  4648.3  426.10  4697.6  424.00  4713.6  424.31
  4787.7  418.06  4822.5  413.78  4858.3  411.51  4867.7  410.01  4898.2  408.79
  4963.5  409.20  4970.4  408.30  4979.5  409.09  4985.3  406.09  4997.0  404.81
  4997.6  404.01  5008.4  404.01  5008.9  404.81  5025.4  408.42  5392.1  411.51
  5651.3  414.84  5753.5  417.86  5774.9  416.46  5807.0  418.83  5839.8  426.83
#Mann=3,-1,0
  4352.7    0.05       0  4997.0    0.03       0  5008.9    0.05       0
Bank Sta=4858.3,5392.1
Exp/Cntr=0.3,0.1

Type RM Length L Ch R = 1,86011,366,366,366
BEGIN DESCRIPTION:
Mapping XS b76aa8d4
END DESCRIPTION:
XS GIS Cut Line= 3
      2913703.17      7024030.74      2913158.91      7024413.54
      2912638.06      7025340.65
#Sta/Elev= 30
  4246.4  428.00  4354.9  426.58  4449.8  428.85  4513.1  426.02  4571.8  425.91
  4643.2  422.16  4754.6  411.19  4794.3  408.16  4830.5  407.52  4982.3  409.27
  5005.3  404.98  5005.8  404.18  5017.3  404.98  5033.0  408.05  5175.3  411.19
  5232.6  413.07  5281.7  418.79  5319.3  421.31  5335.2  421.23  5341.0  422.57
  5384.3  423.46  5406.7  422.55  5443.6  426.17  5497.2  424.67  5524.6  426.81
  5540.5  429.32  5789.2  433.60  5848.5  433.33  5891.9  435.32  5975.2  436.26
#Mann=3,-1,0
  4246.4    0.05       0  5005.3    0.03       0  5017.3    0.05       0
Bank Sta=4754.6,5175.3
Exp/Cntr=0.3,0.1

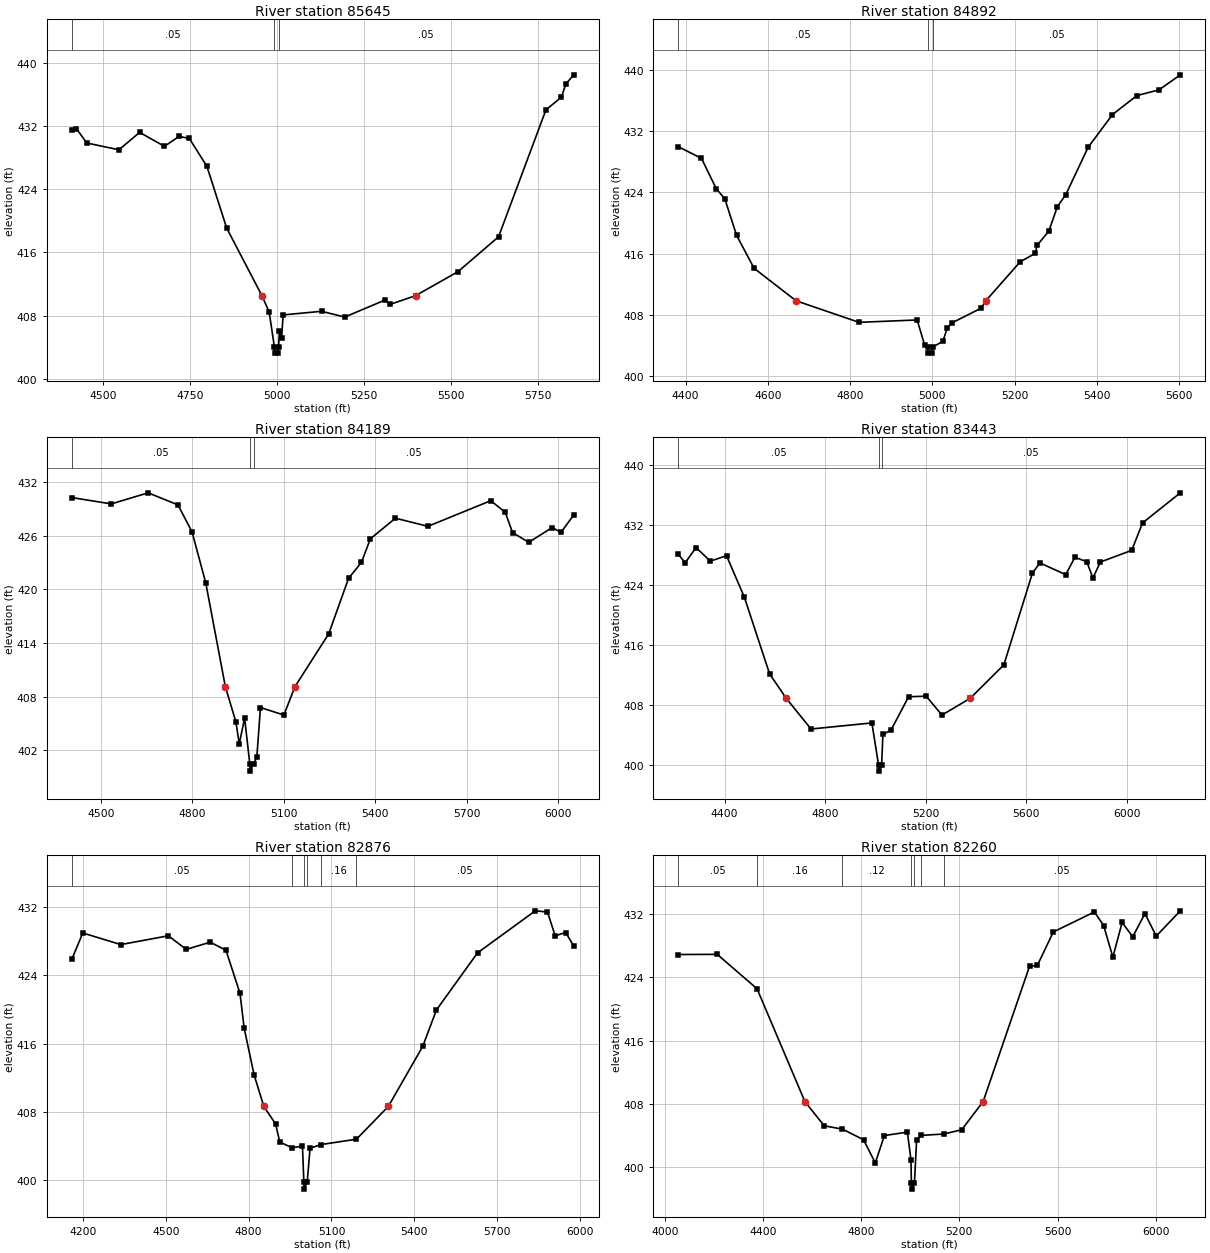
Type RM Length L Ch R = 1,85645,753,753,753
BEGIN DESCRIPTION:
DRY CREEK 70.0
END DESCRIPTION:
XS GIS Cut Line= 3
      2913574.99      7023825.01      2913075.00      7024175.00
      2912374.98      7024625.01
#Sta/Elev= 30
  4409.7  431.51  4423.2  431.65  4452.8  429.84  4545.3  428.98  4604.6  431.18
  4676.0  429.42  4717.9  430.67  4747.5  430.42  4798.1  426.87  4854.8  419.08
  4956.0  410.54  4976.9  408.46  4991.8  404.07  4992.3  403.27  5003.3  403.27
  5003.8  404.07  5006.5  406.12  5012.6  405.20  5017.0  408.10  5127.3  408.56
  5194.0  407.83  5309.0  409.97  5324.1  409.43  5397.8  410.54  5519.3  413.57
  5635.9  417.98  5771.9  434.02  5816.5  435.64  5829.4  437.33  5852.2  438.46
#Mann=3,-1,0
  4409.7    0.05       0  4991.8    0.03       0  5003.8    0.05       0
Bank Sta=4956,5397.8
Exp/Cntr=0.3,0.1

Type RM Length L Ch R = 1,84892,703,703,703
BEGIN DESCRIPTION:
DRY CREEK 69.0
END DESCRIPTION:
XS GIS Cut Line= 3
      2912875.03      7023574.97      2912425.00      7023975.00
      2912275.00      7024575.01
#Sta/Elev= 30
  4382.2  429.99  4438.7  428.46  4474.6  424.49  4495.6  423.14  4524.0  418.39
  4566.6  414.07  4668.7  409.82  4821.7  407.00  4963.0  407.31  4981.0  404.07
  4988.6  403.77  4989.1  402.97  5000.1  402.97  5000.6  403.77  5025.6  404.51
  5035.9  406.23  5048.7  406.96  5118.3  408.84  5129.9  409.82  5213.7  414.93
  5249.8  416.01  5254.9  417.09  5283.3  418.95  5303.9  422.14  5324.5  423.72
  5378.6  429.90  5437.9  434.19  5497.1  436.67  5551.3  437.43  5602.8  439.39
#Mann=3,-1,0
  4382.2    0.05       0  4988.6    0.03       0  5000.6    0.05       0
Bank Sta=4668.7,5129.9
Exp/Cntr=0.3,0.1

Type RM Length L Ch R = 1,84189,746,746,746
BEGIN DESCRIPTION:
DRY CREEK 68.0
END DESCRIPTION:
XS GIS Cut Line= 3
      2912524.99      7022825.02      2912275.00      7023375.00
      2911872.90      7024336.47
#Sta/Elev= 30
  4404.6  430.29  4534.2  429.58  4655.0  430.82  4752.8  429.47  4798.9  426.45
  4844.0  420.73  4908.2  409.12  4942.8  405.17  4953.8  402.73  4971.4  405.60
  4988.4  400.47  4988.9  399.67  5000.5  400.47  5011.4  401.22  5023.3  406.79
  5100.2  405.95  5136.3  409.12  5247.2  415.04  5312.2  421.25  5354.4  423.03
  5383.6  425.67  5465.9  427.98  5572.4  427.07  5778.5  429.94  5826.1  428.63
  5849.9  426.37  5902.9  425.28  5979.8  426.93  6009.0  426.40  6050.9  428.36
#Mann=3,-1,0
  4404.6    0.05       0  4988.4    0.03       0  5000.5    0.05       0
Bank Sta=4908.2,5136.3
Exp/Cntr=0.3,0.1

Type RM Length L Ch R = 1,83443,567,567,567
BEGIN DESCRIPTION:
DRY CREEK 67.0
END DESCRIPTION:
XS GIS Cut Line= 3
      2912115.95      7022367.74      2911648.62      7022997.35
      2911202.76      7024124.68
#Sta/Elev= 30
  4215.9  428.12  4243.1  426.95  4287.0  428.99  4343.3  427.18  4408.0  427.90
  4478.9  422.37  4579.1  412.17  4645.5  408.90  4743.9  404.82  4985.9  405.63
  5012.5  400.01  5013.0  399.21  5024.6  400.01  5029.7  404.09  5062.0  404.68
  5132.0  409.12  5201.8  409.19  5264.5  406.68  5376.6  408.90  5510.6  413.36
  5624.1  425.57  5653.8  426.94  5756.6  425.39  5793.3  427.70  5840.4  427.10
  5864.7  424.94  5894.5  427.06  6019.1  428.62  6062.1  432.27  6212.3  436.28
#Mann=3,-1,0
  4215.9    0.05       0  5012.5    0.03       0  5024.6    0.05       0
Bank Sta=4645.5,5376.6
Exp/Cntr=0.3,0.1

Type RM Length L Ch R = 1,82876,616,616,616
BEGIN DESCRIPTION:
DRY CREEK 66.0
END DESCRIPTION:
XS GIS Cut Line= 3
      2911740.95      7021885.10      2911275.00      7022575.00
      2910817.31      7023447.65
#Sta/Elev= 30
  4159.8  425.84  4199.6  428.94  4337.4  427.58  4509.6  428.61  4574.2  427.02
  4661.1  427.86  4718.1  426.92  4769.0  421.86  4784.0  417.80  4820.0  412.33
  4855.4  408.64  4897.9  406.59  4912.9  404.48  4957.7  403.81  4995.1  404.00
  5000.1  399.77  5000.6  398.97  5012.2  399.77  5022.6  403.76  5063.5  404.19
  5190.6  404.81  5305.8  408.64  5430.4  415.66  5480.1  419.93  5628.9  426.61
  5838.1  431.53  5882.3  431.39  5910.0  428.61  5948.4  428.99  5977.7  427.38
#Mann=6,-1,0
  4159.8    0.05       0  4957.7    0.12       0  5000.1    0.07       0
  5012.2    0.12       0  5063.5    0.16       0  5190.6    0.05       0
Bank Sta=4855.4,5305.8
Exp/Cntr=0.3,0.1

Type RM Length L Ch R = 1,82260,693,693,693
BEGIN DESCRIPTION:
DRY CREEK 65.0
END DESCRIPTION:
XS GIS Cut Line= 3
      2911602.03      7021964.99      2910725.00      7022325.00
      2910185.67      7023280.45
#Sta/Elev= 30
  4054.9  426.87  4213.8  426.89  4376.0  422.54  4570.9  408.29  4649.5  405.23
  4723.9  404.81  4809.6  403.47  4857.6  400.55  4894.8  404.00  4988.3  404.43
  5002.9  400.93  5004.7  398.03  5005.2  397.23  5017.1  398.03  5025.9  403.43
  5044.9  404.02  5136.2  404.19  5209.6  404.73  5296.9  408.29  5486.0  425.39
  5517.8  425.49  5582.8  429.72  5750.3  432.25  5787.8  430.53  5825.4  426.54
  5863.0  430.92  5906.3  429.12  5956.0  432.04  6002.0  429.20  6100.1  432.39
#Mann=7,-1,0
  4054.9    0.05       0  4376.0    0.16       0  4723.9    0.12       0
  5004.7    0.07       0  5017.1    0.12       0  5044.9    0.16       0
  5136.2    0.05       0
Bank Sta=4570.9,5296.9
Exp/Cntr=0.3,0.1

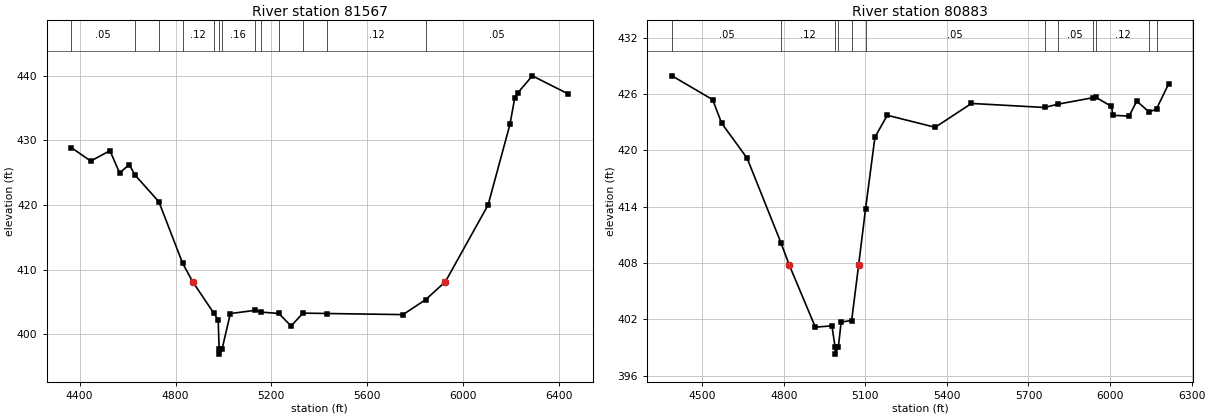
Type RM Length L Ch R = 1,81567,684,684,684
BEGIN DESCRIPTION:
DRY CREEK 64.0
END DESCRIPTION:
XS GIS Cut Line= 3
      2911575.04      7021875.00      2910975.00      7021825.00
      2909525.71      7022076.08
#Sta/Elev= 30
  4365.9  428.86  4446.2  426.79  4526.5  428.40  4566.6  424.95  4606.8  426.24
  4631.4  424.61  4730.6  420.50  4829.8  410.96  4871.4  408.13  4958.7  403.30
  4978.2  402.19  4982.1  397.70  4982.6  396.90  4994.5  397.70  5028.9  403.18
  5130.2  403.67  5155.8  403.41  5231.1  403.20  5282.6  401.25  5332.0  403.25
  5433.0  403.19  5749.5  403.02  5844.4  405.34  5926.7  408.13  6104.7  419.99
  6196.0  432.48  6216.3  436.63  6229.5  437.39  6289.3  439.99  6438.9  437.19
#Mann=13,-1,0
  4365.9    0.05       0  4631.4    0.12       0  4730.6    0.16       0
  4829.8    0.12       0  4958.7    0.16       0  4982.1    0.07       0
  4994.5    0.16       0  5130.2    0.05       0  5155.8    0.16       0
  5231.1    0.12       0  5332.0    0.16       0  5433.0    0.12       0
  5844.4    0.05       0
Bank Sta=4871.4,5926.7
Exp/Cntr=0.3,0.1

Type RM Length L Ch R = 1,80883,671,671,671
BEGIN DESCRIPTION:
DRY CREEK 63.0
END DESCRIPTION:
XS GIS Cut Line= 3
      2911574.97      7021324.99      2910975.00      7021225.00
      2909912.68      7020629.07
#Sta/Elev= 30
  4389.1  427.93  4538.6  425.39  4571.6  422.89  4665.3  419.16  4789.8  410.15
  4820.2  407.79  4916.2  401.17  4977.1  401.31  4988.6  399.10  4989.1  398.30
  5001.0  399.10  5011.1  401.72  5049.7  401.88  5075.4  407.79  5100.8  413.77
  5135.4  421.41  5180.8  423.73  5356.8  422.45  5490.4  424.99  5759.2  424.56
  5807.6  424.91  5935.4  425.59  5946.5  425.65  6004.9  424.69  6010.6  423.73
  6069.9  423.64  6098.1  425.24  6144.0  424.07  6170.7  424.41  6215.4  427.07
#Mann=12,-1,0
  4389.1    0.05       0  4789.8    0.12       0  4988.6    0.07       0
  5001.0    0.12       0  5049.7    0.16       0  5100.8    0.05       0
  5759.2    0.16       0  5807.6    0.05       0  5935.4    0.16       0
  5946.5    0.12       0  6144.0    0.16       0  6170.7    0.12       0
Bank Sta=4820.2,5075.4
Exp/Cntr=0.3,0.1