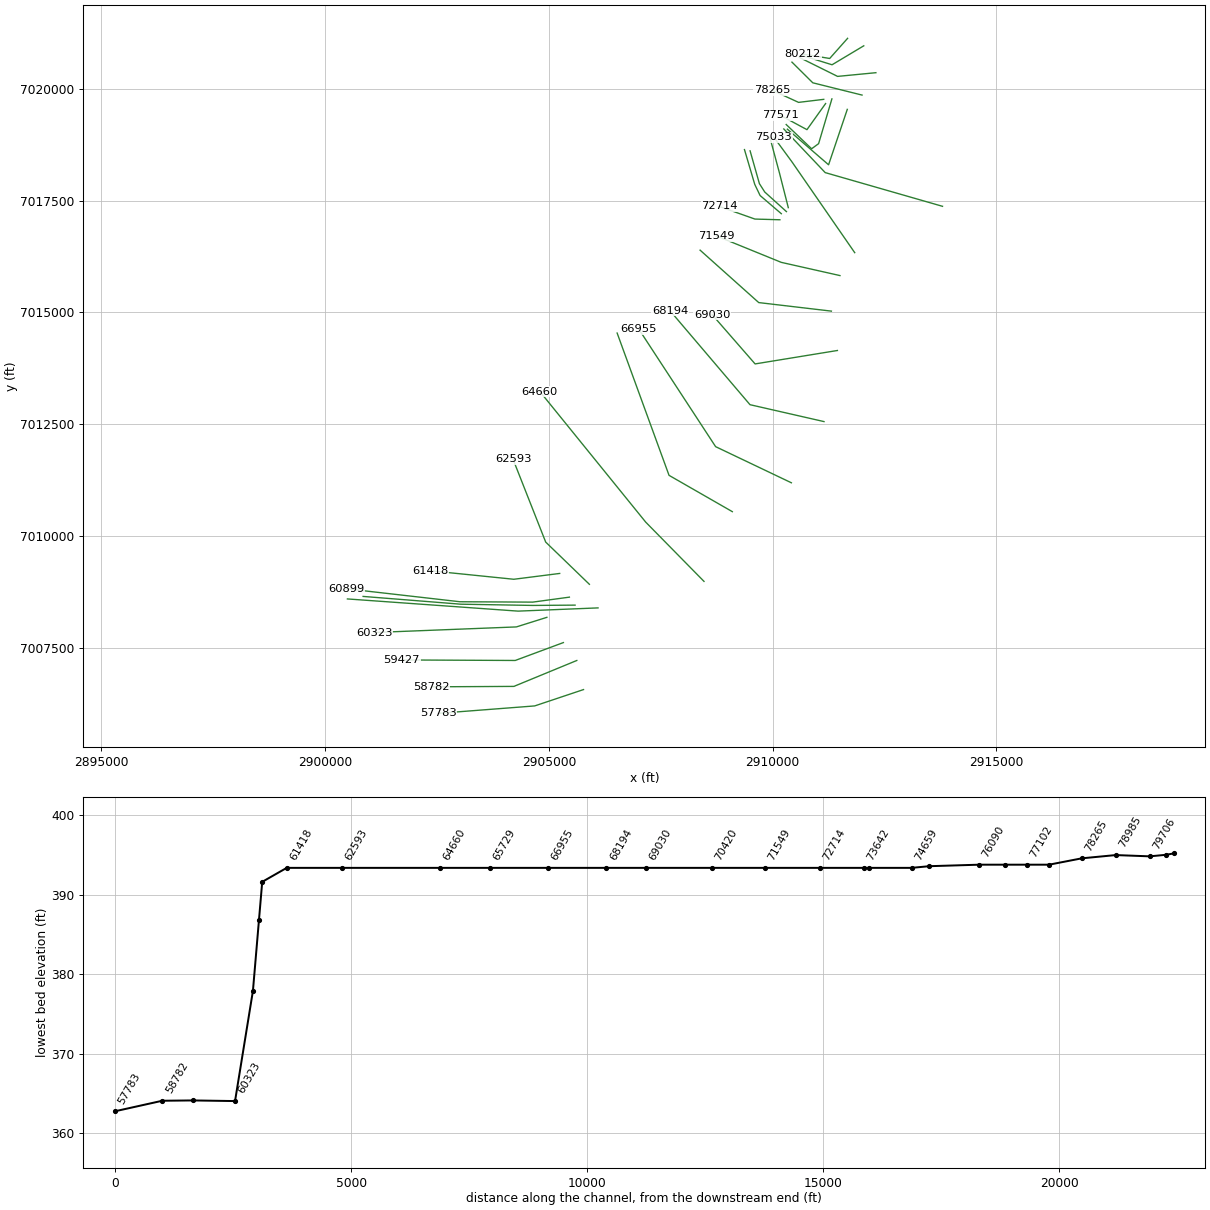
HEC-RAS study DRY CREEK.prj: DRY CREEK Base Level Engineering

--- DRY CREEK.g01 (geometry) --- (continued)

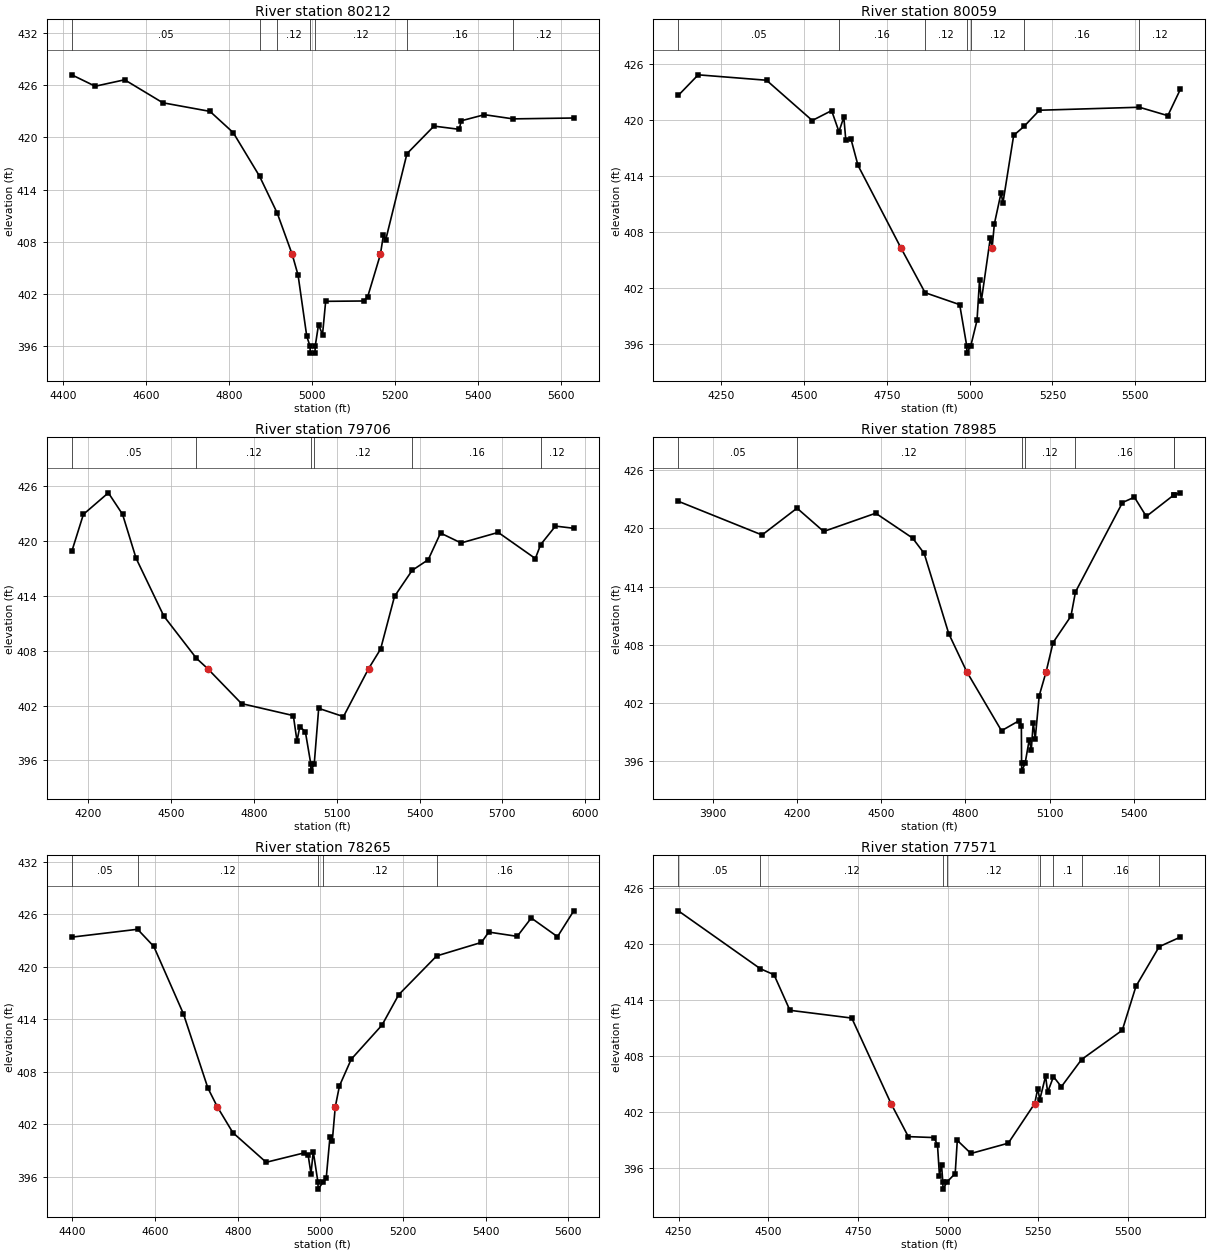
Type RM Length L Ch R = 1,80212,153,153,153
BEGIN DESCRIPTION:
DRY CREEK 62.0
END DESCRIPTION:
XS GIS Cut Line= 3
      2911675.02      7021125.02      2911275.00      7020675.00
      2910674.98      7020775.00
#Sta/Elev= 30
  4421.2  427.18  4477.7  425.87  4548.7  426.61  4640.7  423.97  4754.5  422.98
  4810.5  420.54  4873.9  415.54  4916.5  411.31  4952.8  406.54  4966.9  404.16
  4987.8  397.15  4995.7  396.01  4996.2  395.21  5007.7  395.21  5008.2  396.01
  5016.2  398.49  5025.8  397.33  5033.4  401.16  5124.7  401.20  5134.8  401.70
  5165.3  406.54  5172.8  408.81  5177.9  408.17  5229.4  418.12  5294.5  421.29
  5355.3  420.92  5360.4  421.90  5416.2  422.60  5485.2  422.12  5631.6  422.22
#Mann=7,-1,0
  4421.2    0.05       0  4873.9    0.16       0  4916.5    0.12       0
  4995.7    0.07       0  5008.2    0.12       0  5229.4    0.16       0
  5485.2    0.12       0
Bank Sta=4952.8,5165.3
Exp/Cntr=0.3,0.1

Type RM Length L Ch R = 1,80059,353,353,353
BEGIN DESCRIPTION:
Mapping XS 107e1154
END DESCRIPTION:
XS GIS Cut Line= 3
      2912036.13      7020958.06      2911327.75      7020534.42
      2910668.97      7020738.99
#Sta/Elev= 30
  4120.8  422.63  4180.8  424.83  4387.0  424.25  4525.1  419.94  4583.5  421.00
  4605.6  418.75  4620.4  420.30  4626.3  417.84  4641.8  417.97  4663.2  415.13
  4792.6  406.31  4865.6  401.51  4970.1  400.23  4991.2  395.84  4991.7  395.04
  5003.7  395.84  5022.4  398.55  5030.0  402.90  5035.3  400.60  5062.6  407.38
  5068.0  406.31  5074.7  408.87  5095.2  412.23  5100.4  411.07  5133.0  418.35
  5164.4  419.31  5210.8  421.04  5512.4  421.36  5598.3  420.46  5636.0  423.27
#Mann=7,-1,0
  4120.8    0.05       0  4605.6    0.16       0  4865.6    0.12       0
  4991.2    0.07       0  5003.7    0.12       0  5164.4    0.16       0
  5512.4    0.12       0
Bank Sta=4792.6,5068
Exp/Cntr=0.3,0.1

Type RM Length L Ch R = 1,79706,721,721,721
BEGIN DESCRIPTION:
DRY CREEK 61.0
END DESCRIPTION:
XS GIS Cut Line= 3
      2912306.87      7020357.33      2911451.35      7020274.69
      2910592.75      7020700.53
#Sta/Elev= 30
  4140.5  418.81  4182.6  422.86  4273.0  425.21  4324.5  422.86  4373.4  418.07
  4473.9  411.76  4591.7  407.16  4632.4  406.03  4755.2  402.21  4942.9  400.90
  4956.1  398.12  4966.2  399.68  4986.3  399.16  5006.1  395.64  5006.6  394.84
  5018.6  395.64  5034.7  401.69  5124.4  400.79  5215.5  406.03  5258.9  408.16
  5309.3  413.91  5373.2  416.75  5431.3  417.91  5475.9  420.82  5550.3  419.74
  5684.8  420.89  5819.3  418.04  5838.5  419.56  5892.1  421.58  5958.4  421.34
#Mann=6,-1,0
  4140.5    0.05       0  4591.7    0.12       0  5006.1    0.07       0
  5018.6    0.12       0  5373.2    0.16       0  5838.5    0.12       0
Bank Sta=4632.4,5215.5
Exp/Cntr=0.3,0.1

Type RM Length L Ch R = 1,78985,720,720,720
BEGIN DESCRIPTION:
Mapping XS 8c38d699
END DESCRIPTION:
XS GIS Cut Line= 3
      2911997.93      7019857.33      2910897.19      7020131.64
      2910431.88      7020593.48
#Sta/Elev= 30
  3776.1  422.79  4074.7  419.32  4199.4  422.08  4294.4  419.68  4479.9  421.56
  4611.5  419.00  4652.8  417.42  4740.5  409.15  4804.9  405.22  4928.5  399.16
  4992.2  400.21  4999.3  399.65  5000.1  395.80  5000.6  395.00  5012.6  395.80
  5027.5  398.25  5034.6  397.16  5041.7  399.98  5048.8  398.35  5062.9  402.76
  5087.5  405.22  5112.4  408.24  5176.1  410.96  5192.2  413.45  5359.9  422.66
  5402.3  423.21  5444.8  421.23  5542.6  423.43  5542.9  423.43  5566.1  423.66
#Mann=7,-1,0
  3776.1    0.05       0  4199.4    0.12       0  5000.1    0.07       0
  5012.6    0.12       0  5192.2    0.16       0  5542.6    0.12       0
  5542.9    0.16       0
Bank Sta=4804.9,5087.5
Exp/Cntr=0.3,0.1

Type RM Length L Ch R = 1,78265,694,694,694
BEGIN DESCRIPTION:
Mapping XS ef96c7c4
END DESCRIPTION:
XS GIS Cut Line= 3
      2911141.94      7019761.85      2910579.48      7019694.14
      2909990.93      7019964.98
#Sta/Elev= 30
  4398.5  423.41  4557.7  424.31  4596.9  422.35  4668.7  414.63  4727.8  406.15
  4750.9  403.98  4788.2  401.05  4868.8  397.66  4959.5  398.72  4970.2  398.52
  4977.2  396.36  4982.7  398.89  4994.0  395.39  4994.5  394.59  5006.5  395.39
  5014.0  395.81  5023.2  400.60  5028.7  400.06  5035.9  403.98  5046.1  406.40
  5074.6  409.45  5149.0  413.35  5189.5  416.83  5281.2  421.26  5389.7  422.81
  5407.2  423.99  5476.1  423.50  5510.1  425.60  5573.5  423.46  5612.9  426.42
#Mann=5,-1,0
  4398.5    0.05       0  4557.7    0.12       0  4994.0    0.07       0
  5006.5    0.12       0  5281.2    0.16       0
Bank Sta=4750.9,5035.9
Exp/Cntr=0.3,0.1

Type RM Length L Ch R = 1,77571,469,469,469
BEGIN DESCRIPTION:
Mapping XS eb881422
END DESCRIPTION:
XS GIS Cut Line= 3
      2911183.63      7019668.07      2910766.98      7019084.77
      2910168.98      7019407.17
#Sta/Elev= 30
  4249.5  423.53  4477.7  417.34  4515.7  416.70  4559.9  412.90  4731.9  412.07
  4841.0  402.94  4889.2  399.40  4960.5  399.30  4970.3  398.53  4975.8  395.23
  4981.5  396.40  4985.1  394.59  4985.6  393.79  4997.6  394.59  5019.6  395.46
  5025.4  399.00  5063.4  397.60  5167.2  398.70  5240.8  402.94  5249.1  404.53
  5254.9  403.36  5271.0  405.86  5276.7  404.15  5292.9  405.81  5314.8  404.73
  5371.0  407.64  5484.3  410.77  5522.4  415.47  5587.0  419.70  5645.7  420.72
#Mann=8,-1,0
  4249.5    0.05       0  4477.7    0.12       0  4985.1    0.07       0
  4997.6    0.12       0  5254.9    0.16       0  5292.9     0.1       0
  5371.0    0.16       0  5587.0     0.1       0
Bank Sta=4841,5240.8
Exp/Cntr=0.3,0.1

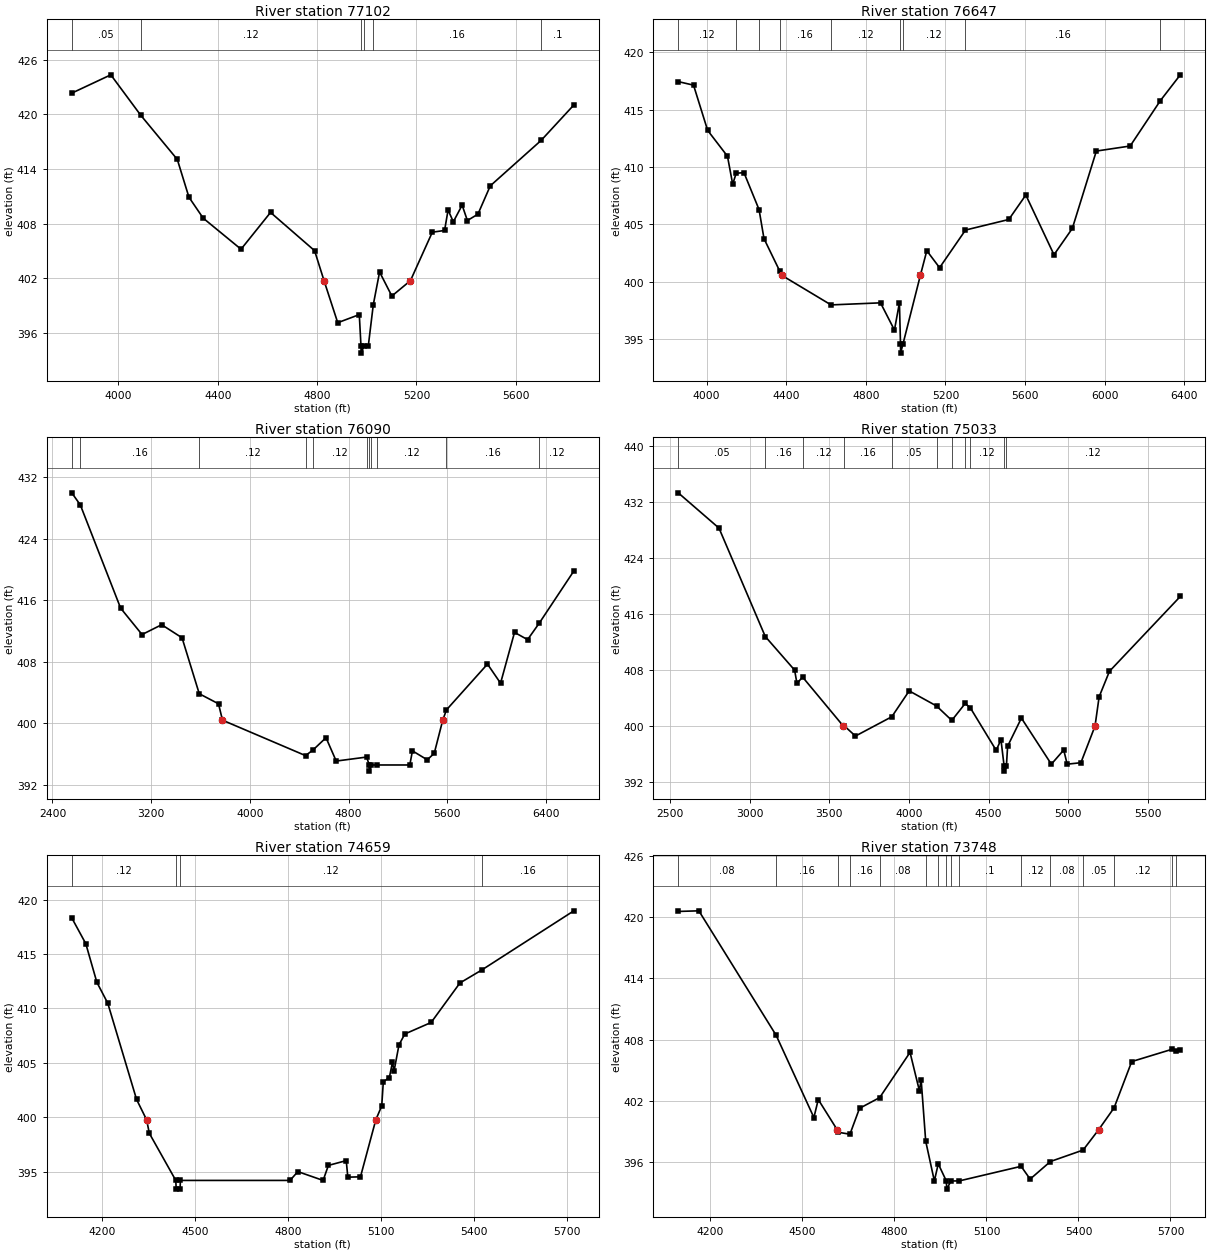
Type RM Length L Ch R = 1,77102,455,455,455
BEGIN DESCRIPTION:
Mapping XS 0e2cedb8
END DESCRIPTION:
XS GIS Cut Line= 4
      2911324.28      7019772.28      2911027.40      7018772.27
      2910871.15      7018657.68      2910303.43      7019199.37
#Sta/Elev= 30
  3812.4  422.34  3969.6  424.35  4089.6  419.93  4237.3  415.06  4284.2  410.91
  4341.6  408.61  4493.9  405.20  4612.8  409.24  4790.1  405.04  4828.1  401.75
  4883.3  397.13  4970.1  398.02  4976.9  394.59  4977.4  393.79  4989.5  394.59
  5006.4  394.59  5026.5  399.11  5051.8  402.70  5101.2  400.06  5176.1  401.75
  5264.1  407.07  5313.5  407.26  5327.6  409.51  5348.7  408.21  5384.2  410.04
  5405.3  408.35  5447.8  409.05  5497.5  412.16  5702.3  417.15  5834.0  421.04
#Mann=6,-1,0
  3812.4    0.05       0  4089.6    0.12       0  4976.9    0.07       0
  4989.5    0.12       0  5026.5    0.16       0  5702.3     0.1       0
Bank Sta=4828.1,5176.1
Exp/Cntr=0.3,0.1

Type RM Length L Ch R = 1,76647,557,557,557
BEGIN DESCRIPTION:
DRY CREEK 60.0
END DESCRIPTION:
XS GIS Cut Line= 3
      2911668.01      7019537.85      2911250.00      7018300.00
      2910329.74      7019094.96
#Sta/Elev= 30
  3857.3  417.44  3934.2  417.13  4005.1  413.19  4104.7  410.94  4130.9  408.50
  4148.4  409.46  4187.5  409.51  4263.4  406.29  4288.2  403.76  4366.6  400.96
  4376.3  400.58  4625.1  397.99  4873.6  398.17  4943.6  395.80  4968.6  398.18
  4974.0  394.59  4974.5  393.79  4986.6  394.59  5074.1  400.58  5106.2  402.71
  5170.4  401.23  5300.6  404.51  5518.1  405.43  5603.7  407.56  5745.2  402.36
  5837.3  404.65  5958.0  411.39  6128.0  411.83  6280.0  415.79  6379.9  418.03
#Mann=9,-1,0
  3857.3    0.12       0  4148.4    0.16       0  4263.4    0.12       0
  4366.6    0.16       0  4625.1    0.12       0  4974.0    0.07       0
  4986.6    0.12       0  5300.6    0.16       0  6280.0    0.12       0
Bank Sta=4376.3,5074.1
Exp/Cntr=0.3,0.1

Type RM Length L Ch R = 1,76090,1057,1057,1057
BEGIN DESCRIPTION:
DRY CREEK 59.0
END DESCRIPTION:
XS GIS Cut Line= 3
      2913795.59      7017372.10      2911175.00      7018125.00
      2910249.98      7019100.02
#Sta/Elev= 30
  2556.3  430.00  2625.8  428.42  2952.3  415.00  3126.0  411.56  3285.2  412.84
  3450.3  411.14  3589.9  403.86  3746.0  402.55  3778.1  400.42  4451.5  395.81
  4512.8  396.55  4617.6  398.14  4700.2  395.10  4946.9  395.62  4968.1  394.59
  4969.3  393.79  4983.0  394.59  5032.7  394.59  5296.9  394.59  5318.3  396.43
  5438.4  395.26  5495.1  396.11  5564.0  400.42  5594.1  401.76  5926.7  407.72
  6032.7  405.23  6145.9  411.84  6251.9  410.90  6347.9  413.08  6626.9  419.83
#Mann=11,-1,0
  2556.3    0.12       0  2625.8    0.16       0  3589.9    0.12       0
  4451.5    0.16       0  4512.8    0.12       0  4946.9    0.16       0
  4968.1    0.07       0  4983.0    0.16       0  5032.7    0.12       0
  5594.1    0.16       0  6347.9    0.12       0
Bank Sta=3778.1,5564
Exp/Cntr=0.3,0.1

Type RM Length L Ch R = 1,75033,374,374,374
BEGIN DESCRIPTION:
DRY CREEK 58.0
END DESCRIPTION:
XS GIS Cut Line= 3
      2911833.77      7016337.15      2910425.00      7018375.00
      2910026.23      7018917.77
#Sta/Elev= 30
  2552.0  433.27  2807.8  428.24  3098.2  412.79  3282.3  408.00  3297.1  406.10
  3332.4  407.01  3588.1  400.02  3595.0  400.03  3664.1  398.60  3892.2  401.35
  4001.4  405.04  4172.9  402.89  4268.8  400.83  4353.1  403.25  4385.9  402.59
  4547.5  396.56  4577.2  398.09  4596.8  394.40  4598.1  393.60  4611.7  394.40
  4619.1  397.15  4705.6  401.16  4893.5  394.59  4971.3  396.61  4992.9  394.59
  5079.0  394.80  5167.6  400.02  5193.4  404.19  5258.2  407.83  5702.9  418.50
#Mann=11,-1,0
  2552.0    0.05       0  3098.2    0.16       0  3332.4    0.12       0
  3595.0    0.16       0  3892.2    0.05       0  4172.9    0.16       0
  4268.8    0.12       0  4353.1    0.16       0  4385.9    0.12       0
  4596.8    0.07       0  4611.7    0.12       0
Bank Sta=3588.1,5167.6
Exp/Cntr=0.3,0.1

Type RM Length L Ch R = 1,74659,911,911,911
BEGIN DESCRIPTION:
Mapping XS 27439cc1
END DESCRIPTION:
XS GIS Cut Line= 3
      2910350.25      7017342.38      2910152.33      7018118.43
      2909938.80      7018910.05
#Sta/Elev= 30
  4101.2  418.32  4146.5  415.95  4182.2  412.40  4217.4  410.48  4310.3  401.64
  4342.8  399.76  4351.6  398.52  4437.0  394.19  4438.3  393.39  4450.7  393.39
  4452.0  394.19  4805.7  394.19  4831.0  395.00  4912.6  394.19  4929.6  395.57
  4987.2  396.01  4992.4  394.49  5033.2  394.52  5082.7  399.76  5101.8  401.04
  5106.9  403.25  5126.4  403.65  5136.5  405.04  5141.7  404.26  5157.5  406.65
  5176.4  407.65  5261.4  408.71  5354.3  412.34  5424.1  413.52  5722.0  418.97
#Mann=4,-1,0
  4101.2    0.12       0  4437.0    0.07       0  4452.0    0.12       0
  5424.1    0.16       0
Bank Sta=4342.8,5082.7
Exp/Cntr=0.3,0.1

Type RM Length L Ch R = 1,73748,106,106,106
BEGIN DESCRIPTION:
Mapping XS 5f539b57
END DESCRIPTION:
XS GIS Cut Line= 4
      2910308.58      7017253.84      2909824.21      7017691.34
      2909704.41      7017878.84      2909496.54      7018611.62
#Sta/Elev= 30
  4095.1  420.54  4162.3  420.60  4414.3  408.43  4537.4  400.39  4551.6  402.15
  4613.4  399.19  4614.4  398.96  4654.9  398.76  4686.1  401.29  4751.9  402.34
  4850.8  406.76  4881.2  403.03  4887.1  404.07  4901.9  398.08  4930.1  394.19
  4942.8  395.86  4969.1  394.19  4970.5  393.39  4984.3  394.19  5010.9  394.19
  5213.0  395.62  5242.4  394.37  5308.5  396.09  5415.1  397.21  5465.5  399.19
  5516.1  401.34  5573.6  405.86  5703.6  407.05  5718.2  406.94  5732.0  406.98
#Mann=16,-1,0
  4095.1    0.08       0  4414.3    0.16       0  4614.4    0.08       0
  4654.9    0.16       0  4751.9    0.08       0  4901.9    0.05       0
  4942.8    0.08       0  4969.1    0.07       0  4984.3    0.08       0
  5010.9     0.1       0  5213.0    0.12       0  5308.5    0.08       0
  5415.1    0.05       0  5516.1    0.12       0  5703.6    0.08       0
  5718.2    0.05       0
Bank Sta=4613.4,5465.5
Exp/Cntr=0.3,0.1

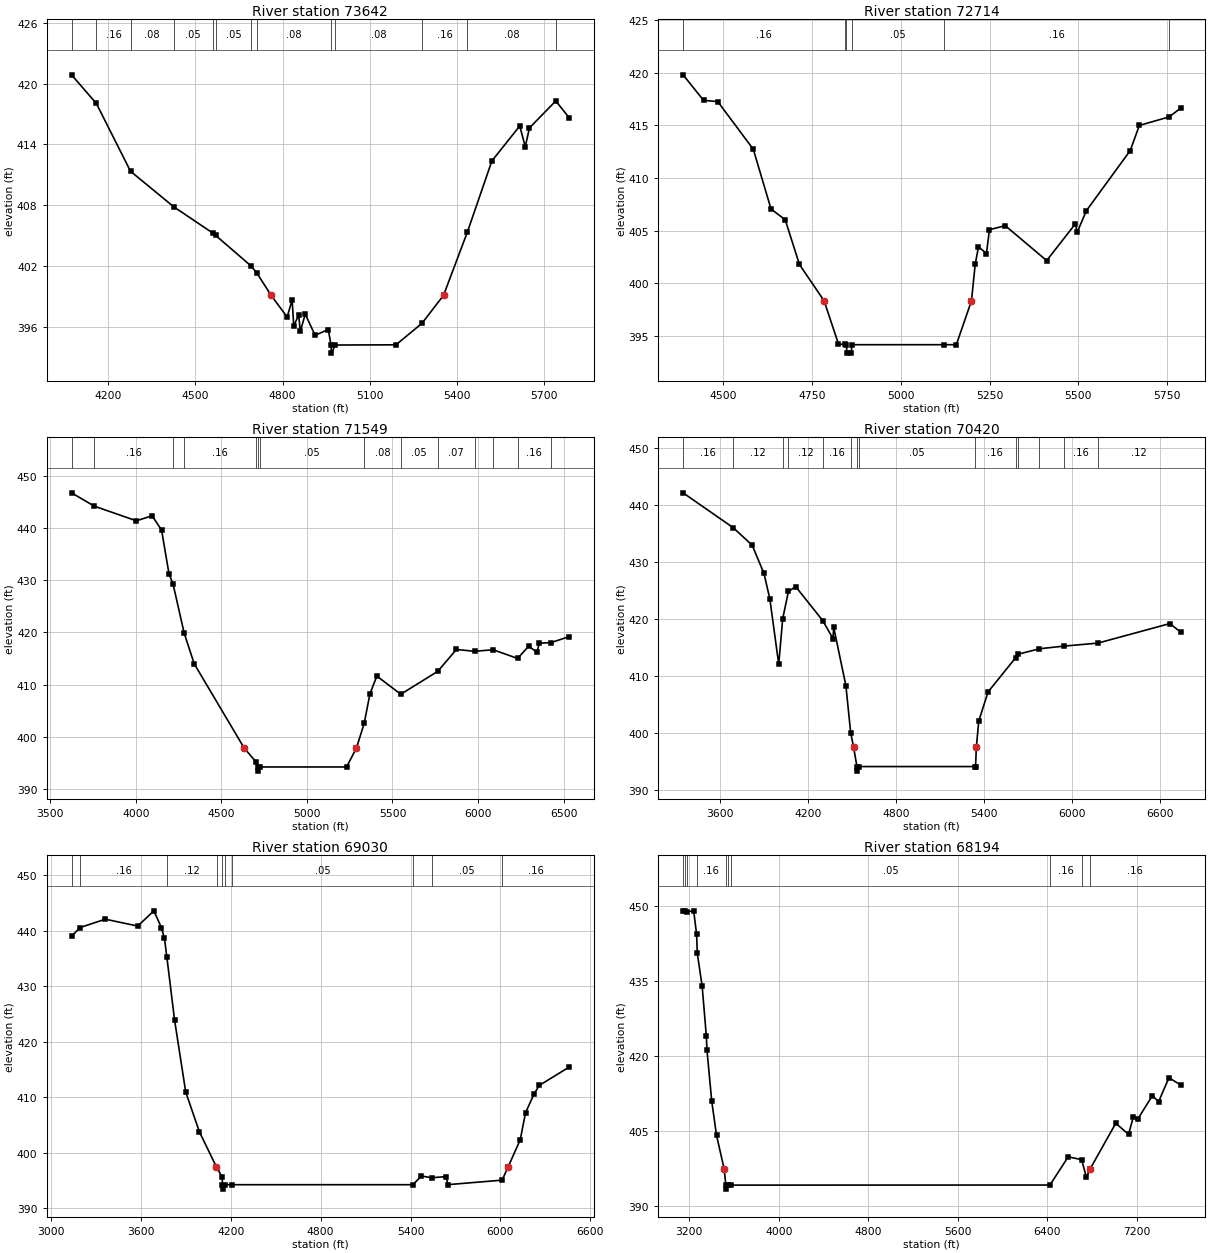
Type RM Length L Ch R = 1,73642,928,928,928
BEGIN DESCRIPTION:
Mapping XS 80398683
END DESCRIPTION:
XS GIS Cut Line= 4
      2910194.00      7017206.96      2909720.04      7017613.22
      2909600.25      7017863.22      2909371.09      7018639.22
#Sta/Elev= 30
  4074.2  420.86  4159.6  418.03  4277.0  411.34  4425.8  407.83  4558.9  405.26
  4569.8  405.01  4692.0  401.98  4711.4  401.29  4760.4  399.10  4815.6  396.95
  4832.7  398.65  4838.2  396.09  4855.3  397.13  4860.9  395.54  4877.8  397.24
  4911.7  395.15  4957.1  395.72  4966.3  394.19  4967.7  393.39  4981.5  394.19
  5189.8  394.21  5279.4  396.34  5353.4  399.10  5435.4  405.35  5519.7  412.37
  5615.4  415.81  5634.4  413.76  5648.7  415.62  5739.3  418.28  5784.8  416.64
#Mann=13,-1,0
  4074.2    0.08       0  4159.6    0.16       0  4277.0    0.08       0
  4425.8    0.05       0  4558.9    0.16       0  4569.8    0.05       0
  4692.0    0.16       0  4711.4    0.08       0  4966.3    0.07       0
  4981.5    0.08       0  5279.4    0.16       0  5435.4    0.08       0
  5739.3    0.16       0
Bank Sta=4760.4,5353.4
Exp/Cntr=0.3,0.1

Type RM Length L Ch R = 1,72714,1165,1165,1165
BEGIN DESCRIPTION:
Mapping XS 8b9a433c
END DESCRIPTION:
XS GIS Cut Line= 3
      2910162.79      7017071.55      2909605.46      7017087.18
      2908809.25      7017368.19
#Sta/Elev= 30
  4386.2  419.79  4444.0  417.37  4484.0  417.25  4584.1  412.73  4634.1  407.06
  4674.1  406.04  4714.1  401.80  4783.6  398.36  4824.2  394.25  4841.5  394.22
  4846.5  394.19  4847.9  393.39  4860.4  393.39  4861.8  394.19  5121.9  394.19
  5156.3  394.19  5199.0  398.36  5209.4  401.80  5218.7  403.48  5241.2  402.84
  5249.6  405.10  5294.2  405.48  5410.8  402.17  5491.7  405.65  5497.0  404.86
  5522.7  406.90  5646.4  412.61  5672.0  414.99  5756.1  415.80  5788.1  416.62
#Mann=6,-1,0
  4386.2    0.16       0  4841.5    0.05       0  4846.5   0.033       0
  4861.8    0.05       0  5121.9    0.16       0  5756.1    0.05       0
Bank Sta=4783.6,5199
Exp/Cntr=0.3,0.1

Type RM Length L Ch R = 1,71549,1129,1129,1129
BEGIN DESCRIPTION:
Mapping XS 6146a0be
END DESCRIPTION:
XS GIS Cut Line= 3
      2911504.73      7015824.60      2910194.00      7016119.73
      2908744.32      7016710.02
#Sta/Elev= 30
  3623.5  446.81  3756.6  444.25  4002.5  441.44  4094.7  442.41  4150.0  439.65
  4193.3  431.28  4217.1  429.29  4282.3  419.85  4340.8  413.99  4632.8  397.83
  4700.4  395.22  4712.4  394.19  4713.8  393.39  4727.7  394.19  5231.7  394.19
  5289.2  397.83  5334.7  402.56  5368.2  408.23  5408.7  411.63  5548.7  408.15
  5764.6  412.54  5873.8  416.74  5980.5  416.39  6088.4  416.69  6231.5  415.02
  6296.5  417.37  6344.6  416.21  6358.8  417.95  6426.3  418.05  6532.3  419.20
#Mann=14,-1,0
  3623.5    0.05       0  3756.6    0.16       0  4217.1    0.12       0
  4282.3    0.16       0  4700.4    0.05       0  4712.4   0.033       0
  4727.7    0.05       0  5334.7    0.08       0  5548.7    0.05       0
  5764.6    0.07       0  5980.5    0.05       0  6088.4    0.12       0
  6231.5    0.16       0  6426.3    0.12       0
Bank Sta=4632.8,5289.2
Exp/Cntr=0.3,0.1

Type RM Length L Ch R = 1,70420,1390,1390,1390
BEGIN DESCRIPTION:
Mapping XS 6bc5b110
END DESCRIPTION:
XS GIS Cut Line= 3
      2911312.90      7015030.32      2909689.66      7015221.29
      2908379.47      7016392.65
#Sta/Elev= 30
  3347.7  442.15  3690.7  436.02  3818.8  432.98  3899.4  428.03  3939.3  423.58
  4000.1  412.11  4027.2  420.12  4066.2  424.87  4115.5  425.72  4299.9  419.77
  4369.8  416.61  4374.8  418.58  4457.9  408.37  4490.7  400.11  4510.7  397.55
  4533.3  394.19  4534.7  393.39  4548.7  394.19  5335.8  394.19  5342.1  394.19
  5347.2  397.55  5363.8  402.16  5427.3  407.27  5614.7  413.24  5633.7  413.88
  5777.7  414.83  5943.3  415.29  6176.2  415.82  6666.2  419.24  6739.6  417.77
#Mann=14,-1,0
  3347.7    0.16       0  3690.7    0.12       0  4027.2    0.16       0
  4066.2    0.12       0  4299.9    0.16       0  4490.7    0.05       0
  4533.3   0.033       0  4548.7    0.05       0  5335.8    0.16       0
  5614.7    0.12       0  5633.7    0.16       0  5777.7    0.12       0
  5943.3    0.16       0  6176.2    0.12       0
Bank Sta=4510.7,5347.2
Exp/Cntr=0.3,0.1

Type RM Length L Ch R = 1,69030,836,836,836
BEGIN DESCRIPTION:
DRY CREEK 53.0
END DESCRIPTION:
XS GIS Cut Line= 3
      2911447.42      7014150.97      2909608.45      7013850.86
      2908650.02      7014949.98
#Sta/Elev= 30
  3136.7  439.04  3194.4  440.61  3362.1  442.11  3578.6  440.87  3686.3  443.62
  3737.0  440.58  3757.2  438.63  3773.0  435.29  3824.4  423.95  3899.1  410.91
  3990.3  403.74  4103.5  397.42  4106.8  397.23  4142.3  395.57  4144.6  394.19
  4146.1  393.39  4160.2  394.19  4208.7  394.19  5415.7  394.19  5472.9  395.76
  5541.0  395.44  5636.2  395.65  5650.4  394.20  6011.5  395.01  6052.0  397.42
  6132.7  402.31  6167.8  407.16  6224.8  410.57  6259.9  412.11  6458.3  415.40
#Mann=10,-1,0
  3136.7    0.05       0  3194.4    0.16       0  3773.0    0.12       0
  4106.8    0.16       0  4144.6   0.033       0  4160.2    0.16       0
  4208.7    0.05       0  5415.7    0.16       0  5541.0    0.05       0
  6011.5    0.16       0
Bank Sta=4103.5,6052
Exp/Cntr=0.3,0.1

Type RM Length L Ch R = 1,68194,1239,1239,1239
BEGIN DESCRIPTION:
Mapping XS 7e2dfe8f
END DESCRIPTION:
XS GIS Cut Line= 3
      2911147.95      7012562.45      2909494.35      7012940.04
      2907710.47      7015036.42
#Sta/Elev= 30
  3144.4  448.86  3163.6  448.98  3177.5  448.84  3239.7  448.93  3265.7  444.26
  3271.9  440.46  3314.9  433.99  3352.6  423.96  3357.9  421.26  3400.8  410.95
  3443.8  404.13  3512.1  397.40  3527.0  394.19  3528.6  393.39  3542.7  394.19
  3572.1  394.19  6425.4  394.21  6588.9  399.85  6708.7  399.27  6751.4  395.74
  6781.5  397.21  6783.8  397.40  7013.9  406.55  7128.1  404.33  7170.9  407.80
  7212.6  407.45  7341.2  412.06  7397.1  410.86  7489.4  415.64  7593.2  414.21
#Mann=10,-1,0
  3144.4    0.16       0  3163.6    0.08       0  3177.5    0.05       0
  3265.7    0.16       0  3527.0   0.033       0  3542.7    0.16       0
  3572.1    0.05       0  6425.4    0.16       0  6708.7    0.05       0
  6781.5    0.16       0
Bank Sta=3512.1,6783.8
Exp/Cntr=0.3,0.1

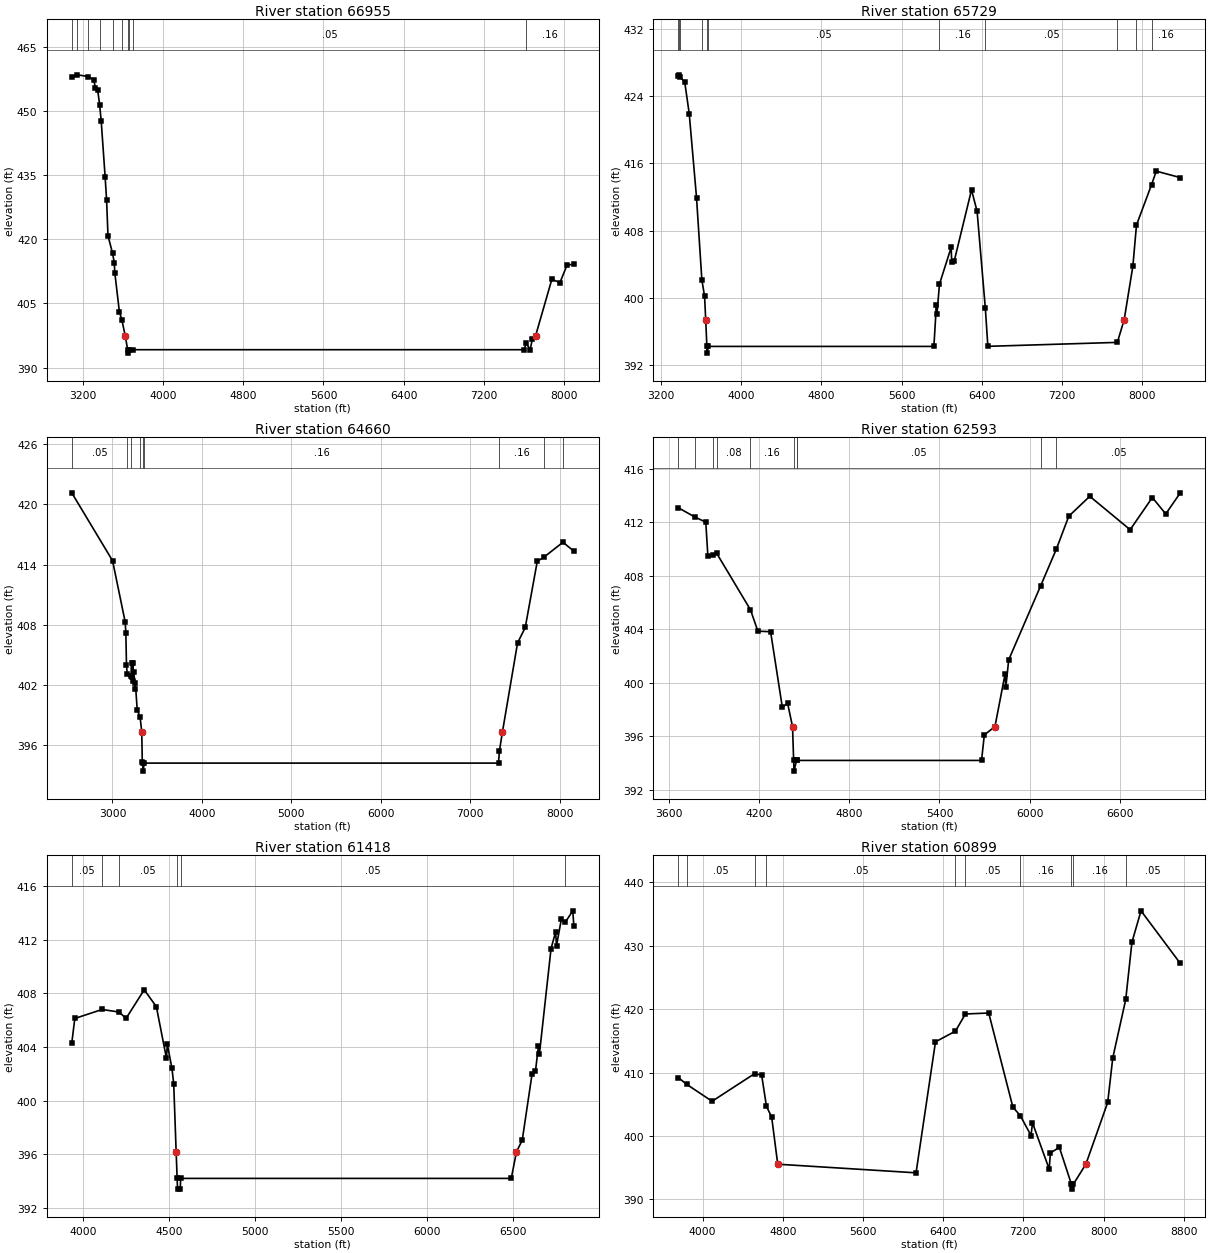
Type RM Length L Ch R = 1,66955,1226,1226,1226
BEGIN DESCRIPTION:
Mapping XS a18a4cb5
END DESCRIPTION:
XS GIS Cut Line= 3
      2910418.79      7011195.26      2908726.12      7012002.54
      2907008.25      7014631.40
#Sta/Elev= 30
  3085.8  458.06  3141.9  458.46  3252.9  458.05  3306.0  457.28  3322.7  455.28
  3344.8  454.89  3363.8  451.51  3379.6  447.72  3419.4  434.49  3433.5  429.21
  3447.7  420.82  3493.8  416.69  3510.2  414.56  3515.7  412.20  3561.1  403.10
  3585.7  401.20  3620.5  397.38  3644.0  394.19  3645.6  393.39  3659.9  394.19
  3696.7  394.19  7607.4  394.19  7622.8  395.83  7664.7  394.19  7687.7  396.72
  7718.5  397.38  7881.9  410.66  7962.5  409.88  8034.1  414.01  8101.5  414.15
#Mann=10,-1,0
  3085.8    0.16       0  3141.9    0.05       0  3252.9    0.08       0
  3363.8    0.16       0  3493.8    0.05       0  3585.7    0.08       0
  3644.0   0.033       0  3659.9    0.08       0  3696.7    0.05       0
  7622.8    0.16       0
Bank Sta=3620.5,7718.5
Exp/Cntr=0.3,0.1

Type RM Length L Ch R = 1,65729,1069,1069,1069
BEGIN DESCRIPTION:
DRY CREEK 52.0
END DESCRIPTION:
XS GIS Cut Line= 3
      2909100.04      7010549.98      2907685.68      7011361.42
      2906525.89      7014540.79
#Sta/Elev= 30
  3369.4  426.42  3374.0  426.56  3390.1  426.28  3434.2  425.70  3479.0  421.95
  3552.1  411.92  3605.4  402.10  3632.6  400.18  3643.7  397.37  3655.5  394.19
  3657.1  393.39  3671.4  394.19  5922.9  394.19  5948.1  399.15  5953.4  398.05
  5978.7  401.61  6095.6  406.00  6100.9  404.20  6126.1  404.37  6298.8  412.85
  6354.6  410.28  6436.8  398.74  6462.1  394.20  7755.4  394.67  7823.6  397.37
  7910.3  403.75  7946.6  408.66  8097.5  413.48  8144.1  415.08  8384.3  414.31
#Mann=11,-1,0
  3369.4    0.16       0  3374.0    0.05       0  3390.1    0.08       0
  3605.4    0.05       0  3655.5   0.033       0  3671.4    0.05       0
  5978.7    0.16       0  6436.8    0.05       0  7755.4    0.16       0
  7946.6    0.08       0  8097.5    0.16       0
Bank Sta=3643.7,7823.6
Exp/Cntr=0.3,0.1

Type RM Length L Ch R = 1,64660,2067,2067,2067
BEGIN DESCRIPTION:
Mapping XS 756effc2
END DESCRIPTION:
XS GIS Cut Line= 3
      2908466.93      7008992.04      2907164.86      7010315.81
      2904799.72      7013234.26
#Sta/Elev= 30
  2544.7  421.15  3000.7  414.38  3142.1  408.26  3149.3  407.20  3156.3  404.01
  3164.2  403.07  3206.9  402.89  3212.8  404.15  3220.0  402.73  3227.0  404.13
  3234.1  402.40  3241.1  403.30  3248.3  401.62  3255.3  402.19  3276.5  399.51
  3308.8  398.76  3327.0  397.32  3333.1  394.27  3337.7  394.19  3340.2  393.39
  3356.9  394.19  7315.8  394.19  7325.6  395.39  7360.0  397.32  7528.5  406.17
  7614.7  407.72  7749.1  414.32  7820.4  414.71  8036.2  416.22  8158.0  415.33
#Mann=9,-1,0
  2544.7    0.05       0  3164.2    0.08       0  3206.9     0.1       0
  3308.8    0.16       0  3337.7   0.033       0  3356.9    0.16       0
  7325.6    0.16       0  7820.4    0.05       0  8036.2    0.16       0
Bank Sta=3327,7360
Exp/Cntr=0.3,0.1

Type RM Length L Ch R = 1,62593,1175,1175,1175
BEGIN DESCRIPTION:
Mapping XS 673c8be2
END DESCRIPTION:
XS GIS Cut Line= 3
      2905906.17      7008926.94      2904929.62      7009870.93
      2904202.63      7011715.52
#Sta/Elev= 30
  3661.6  413.10  3771.8  412.40  3844.8  412.02  3859.0  409.45  3891.6  409.57
  3917.1  409.69  4142.3  405.46  4191.6  403.86  4276.2  403.82  4354.2  398.17
  4389.4  398.46  4422.2  396.72  4429.5  394.19  4432.0  393.39  4448.7  394.19
  4449.1  394.19  5679.9  394.19  5698.3  396.10  5769.0  396.72  5836.3  400.65
  5841.7  399.70  5860.7  401.72  6073.4  407.26  6177.6  410.00  6260.3  412.46
  6400.0  413.95  6668.7  411.45  6816.3  413.86  6905.6  412.63  7002.5  414.21
#Mann=10,-1,0
  3661.6    0.05       0  3771.8    0.08       0  3891.6    0.05       0
  3917.1    0.08       0  4142.3    0.16       0  4429.5   0.033       0
  4448.7    0.16       0  4449.1    0.05       0  6073.4    0.08       0
  6177.6    0.05       0
Bank Sta=4422.2,5769
Exp/Cntr=0.3,0.1

Type RM Length L Ch R = 1,61418,519,519,519
BEGIN DESCRIPTION:
Mapping XS f6160759
END DESCRIPTION:
XS GIS Cut Line= 3
      2905242.57      7009169.79      2904218.24      7009039.58
      2902343.21      7009230.56
#Sta/Elev= 30
  3936.3  404.28  3954.0  406.12  4112.3  406.79  4211.8  406.60  4251.6  406.12
  4357.2  408.26  4427.8  407.00  4486.5  403.15  4491.5  404.20  4518.5  402.39
  4528.6  401.25  4542.8  396.17  4548.5  394.19  4551.0  393.39  4566.6  393.39
  4569.1  394.19  6489.9  394.19  6520.2  396.17  6553.7  397.04  6610.6  401.96
  6630.7  402.21  6648.2  404.08  6653.3  403.44  6721.1  411.33  6747.8  412.58
  6752.9  411.55  6781.4  413.55  6804.4  413.31  6847.4  414.15  6853.6  413.03
#Mann=6,-1,0
  3936.3    0.05       0  4112.3    0.16       0  4211.8    0.05       0
  4548.5   0.033       0  4569.1    0.05       0  6804.4    0.08       0
Bank Sta=4542.8,6520.2
Exp/Cntr=0.3,0.1

Type RM Length L Ch R = 1,60899,69,69,69
BEGIN DESCRIPTION:
Mapping XS 4b3e5474
END DESCRIPTION:
XS GIS Cut Line= 4
      2905459.53      7008640.27      2904639.99      7008528.96
      2903014.01      7008537.38      2900475.59      7008827.41
#Sta/Elev= 30
  3757.8  409.22  3841.0  408.16  4095.4  405.48  4519.8  409.84  4589.9  409.60
  4637.7  404.69  4689.9  402.97  4750.2  395.56  6129.9  394.20  6323.8  414.85
  6522.5  416.53  6622.5  419.24  6854.8  419.39  7095.6  404.56  7169.7  403.21
  7276.8  400.08  7291.4  402.08  7457.9  394.79  7470.1  397.34  7559.5  398.21
  7679.1  392.43  7681.6  391.63  7699.7  392.43  7823.8  395.56  8041.7  405.31
  8092.0  412.31  8221.6  421.54  8283.3  430.56  8373.9  435.50  8765.8  427.21
#Mann=10,-1,0
  3757.8     0.1       0  3841.0    0.05       0  4519.8    0.08       0
  4637.7    0.05       0  6522.5     0.1       0  6622.5    0.05       0
  7169.7    0.16       0  7679.1   0.033       0  7699.7    0.16       0
  8221.6    0.05       0
Bank Sta=4750.2,7823.8
Exp/Cntr=0.3,0.1

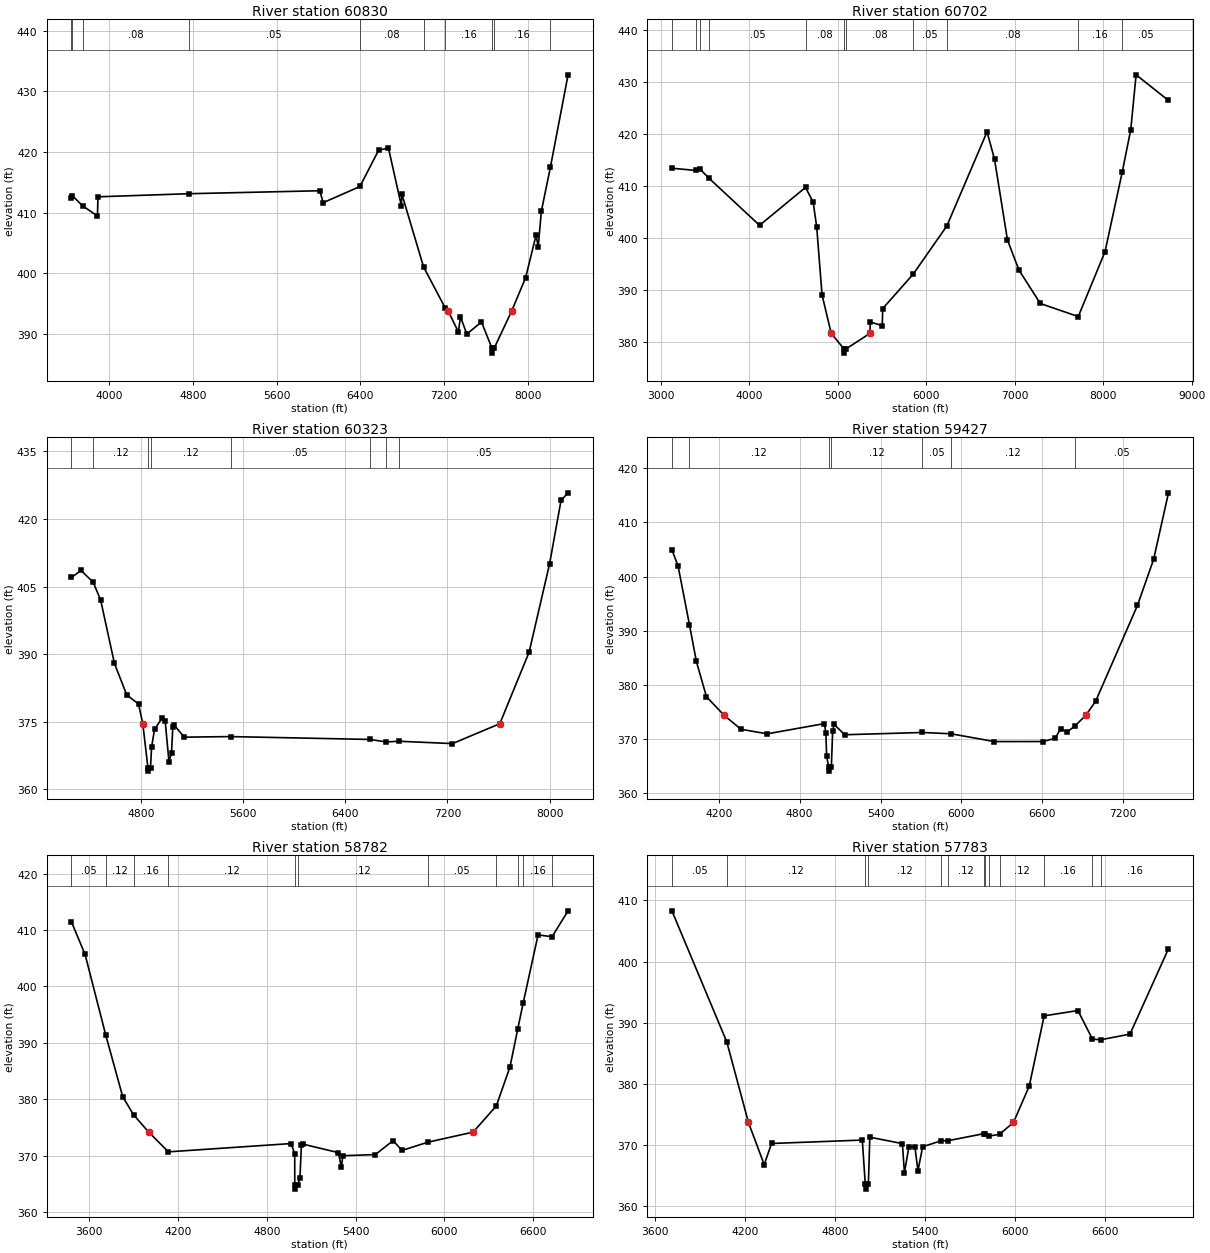
Type RM Length L Ch R = 1,60830,128,128,128
BEGIN DESCRIPTION:
Mapping XS 81a62bc8
END DESCRIPTION:
XS GIS Cut Line= 4
      2905586.77      7008461.83      2904642.30      7008454.89
      2903031.19      7008482.66      2900850.63      7008656.28
#Sta/Elev= 30
  3641.1  412.45  3648.8  412.79  3747.8  411.10  3889.1  409.44  3894.1  412.60
  4760.3  413.11  6013.1  413.60  6045.2  411.63  6396.1  414.30  6574.3  420.26
  6668.5  420.66  6791.7  411.15  6796.7  413.06  7003.8  401.06  7209.4  394.32
  7240.3  393.73  7336.7  390.32  7356.8  392.83  7417.0  389.97  7557.4  391.97
  7657.5  387.63  7660.0  386.83  7678.1  387.63  7844.6  393.73  7978.8  399.26
  8079.1  406.30  8099.1  404.30  8129.2  410.23  8215.4  417.45  8384.4  432.71
#Mann=10,-1,0
  3641.1    0.08       0  3648.8    0.05       0  3747.8    0.08       0
  4760.3    0.05       0  6396.1    0.08       0  7003.8    0.05       0
  7209.4    0.16       0  7657.5    0.03       0  7678.1    0.16       0
  8215.4    0.05       0
Bank Sta=7240.3,7844.6
Exp/Cntr=0.3,0.1

Type RM Length L Ch R = 1,60702,379,379,379
BEGIN DESCRIPTION:
Mapping XS 7366bb46
END DESCRIPTION:
XS GIS Cut Line= 3
      2906099.98      7008400.00      2904313.72      7008327.78
      2900500.04      7008600.00
#Sta/Elev= 30
  3126.3  413.47  3394.2  413.05  3447.6  413.24  3546.7  411.52  4116.7  402.49
  4636.0  409.78  4722.6  406.93  4762.6  402.13  4822.7  389.10  4926.3  381.70
  5071.6  378.70  5074.1  377.90  5092.2  378.70  5364.1  381.70  5367.7  383.89
  5503.1  383.18  5508.1  386.47  5853.6  393.11  6233.0  402.37  6687.2  420.47
  6771.8  415.20  6917.8  399.67  7047.6  393.88  7288.8  387.45  7717.9  384.93
  8020.6  397.44  8215.2  412.77  8311.2  420.91  8371.5  431.44  8737.4  426.51
#Mann=11,-1,0
  3126.3    0.16       0  3394.2    0.05       0  3447.6    0.08       0
  3546.7    0.05       0  4636.0    0.08       0  5071.6    0.07       0
  5092.2    0.08       0  5853.6    0.05       0  6233.0    0.08       0
  7717.9    0.16       0  8215.2    0.05       0
Bank Sta=4926.3,5364.1
Exp/Cntr=0.3,0.1

Type RM Length L Ch R = 1,60323,896,896,896
BEGIN DESCRIPTION:
DRY CREEK 50.0
END DESCRIPTION:
XS GIS Cut Line= 3
      2904956.05      7008188.88      2904275.00      7007975.00
      2901100.01      7007850.00
#Sta/Elev= 30
  4253.7  407.02  4328.2  408.58  4423.3  405.98  4481.9  402.03  4590.2  387.94
  4686.8  380.94  4778.8  378.94  4812.4  374.56  4852.4  364.83  4854.9  364.03
  4873.0  364.83  4881.3  369.40  4904.7  373.35  4964.9  375.82  4987.6  375.17
  5017.6  366.12  5037.6  368.12  5047.6  373.75  5057.6  374.26  5137.7  371.57
  5500.0  371.70  6593.2  371.06  6722.1  370.51  6821.2  370.66  7239.3  370.14
  7610.1  374.56  7839.8  390.45  7999.9  410.02  8090.0  424.14  8145.0  425.81
#Mann=8,-1,0
  4253.7    0.05       0  4423.3    0.12       0  4852.4    0.07       0
  4873.0    0.12       0  5500.0    0.05       0  6593.2    0.12       0
  6722.1    0.16       0  6821.2    0.05       0
Bank Sta=4812.4,7610.1
Exp/Cntr=0.3,0.1

Type RM Length L Ch R = 1,59427,645,645,645
BEGIN DESCRIPTION:
DRY CREEK 49.0
END DESCRIPTION:
XS GIS Cut Line= 3
      2905325.02      7007625.01      2904249.65      7007225.43
      2901714.78      7007236.63
#Sta/Elev= 30
  3852.8  404.93  3898.4  401.96  3982.6  391.14  4034.1  384.35  4108.9  377.84
  4239.9  374.40  4364.9  371.83  4559.2  370.99  4982.6  372.87  4994.3  371.23
  4999.8  366.97  5014.4  364.91  5016.9  364.11  5035.0  364.91  5044.7  371.46
  5054.7  372.74  5134.7  370.82  5709.4  371.24  5921.5  371.00  6244.7  369.56
  6604.7  369.57  6694.7  370.17  6734.7  371.90  6784.7  371.37  6839.2  372.39
  6922.0  374.40  6994.7  377.00  7304.7  394.67  7424.7  403.17  7534.9  415.44
#Mann=7,-1,0
  3852.8    0.16       0  3982.6    0.12       0  5014.4    0.07       0
  5035.0    0.12       0  5709.4    0.05       0  5921.5    0.12       0
  6839.2    0.05       0
Bank Sta=4239.9,6922
Exp/Cntr=0.3,0.1

Type RM Length L Ch R = 1,58782,999,999,999
BEGIN DESCRIPTION:
DRY CREEK 48.0
END DESCRIPTION:
XS GIS Cut Line= 3
      2905625.00      7007225.00      2904219.27      7006646.00
      2902382.09      7006637.02
#Sta/Elev= 30
  3479.7  411.44  3571.6  405.67  3710.4  391.47  3825.8  380.47  3899.0  377.26
  4001.7  374.18  4134.8  370.68  4965.0  372.15  4988.9  370.31  4989.3  364.87
  4991.8  364.07  5009.9  364.87  5024.3  366.06  5034.3  371.92  5044.3  372.05
  5284.3  370.54  5304.3  367.95  5314.3  369.99  5534.3  370.20  5654.3  372.67
  5714.3  370.93  5889.4  372.39  6195.4  374.18  6351.9  378.82  6444.3  385.72
  6497.0  392.47  6533.0  396.99  6634.3  409.14  6728.8  408.82  6837.2  413.41
#Mann=11,-1,0
  3479.7    0.05       0  3710.4    0.12       0  3899.0    0.16       0
  4134.8    0.12       0  4989.3    0.07       0  5009.9    0.12       0
  5889.4    0.05       0  6351.9    0.16       0  6497.0    0.12       0
  6533.0    0.16       0  6728.8    0.05       0
Bank Sta=4001.7,6195.4
Exp/Cntr=0.3,0.1

Type RM Length L Ch R = 1,57783,972,972,972
BEGIN DESCRIPTION:
DRY CREEK 47.0
END DESCRIPTION:
XS GIS Cut Line= 3
      2905775.04      7006575.01      2904684.17      7006209.94
      2902528.94      7006043.35
#Sta/Elev= 30
  3713.0  408.30  4079.6  386.81  4223.3  373.67  4328.7  366.75  4377.4  370.22
  4982.9  370.78  5002.7  363.55  5005.2  362.75  5023.3  363.55  5033.0  371.25
  5250.2  370.20  5263.7  365.42  5293.8  369.72  5333.9  369.61  5354.0  365.75
  5385.3  369.69  5506.6  370.65  5555.1  370.68  5794.0  371.83  5799.1  371.76
  5830.2  371.44  5899.0  371.73  5991.1  373.67  6096.2  379.60  6195.7  391.11
  6420.9  391.98  6518.1  387.30  6573.8  387.20  6768.2  388.12  7025.0  402.10
#Mann=13,-1,0
  3713.0    0.05       0  4079.6    0.12       0  5002.7    0.07       0
  5023.3    0.12       0  5506.6    0.16       0  5555.1    0.12       0
  5794.0    0.16       0  5799.1    0.05       0  5830.2    0.16       0
  5899.0    0.12       0  6195.7    0.16       0  6518.1    0.12       0
  6573.8    0.16       0
Bank Sta=4223.3,5991.1
Exp/Cntr=0.3,0.1