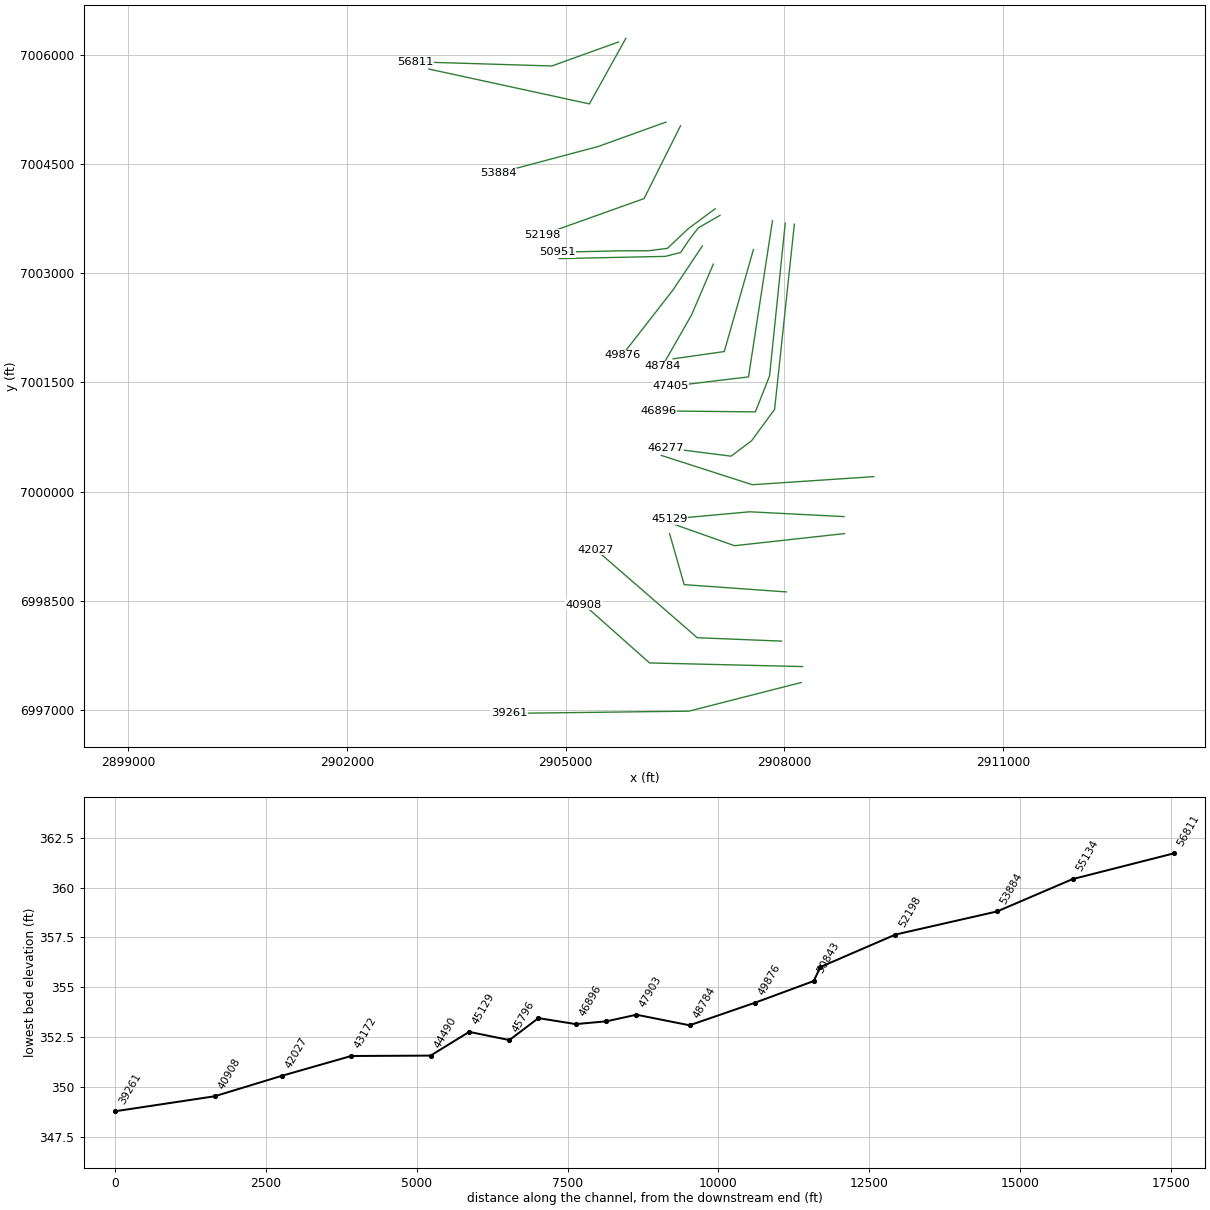
HEC-RAS study DRY CREEK.prj: DRY CREEK Base Level Engineering

--- DRY CREEK.g01 (geometry) --- (continued)

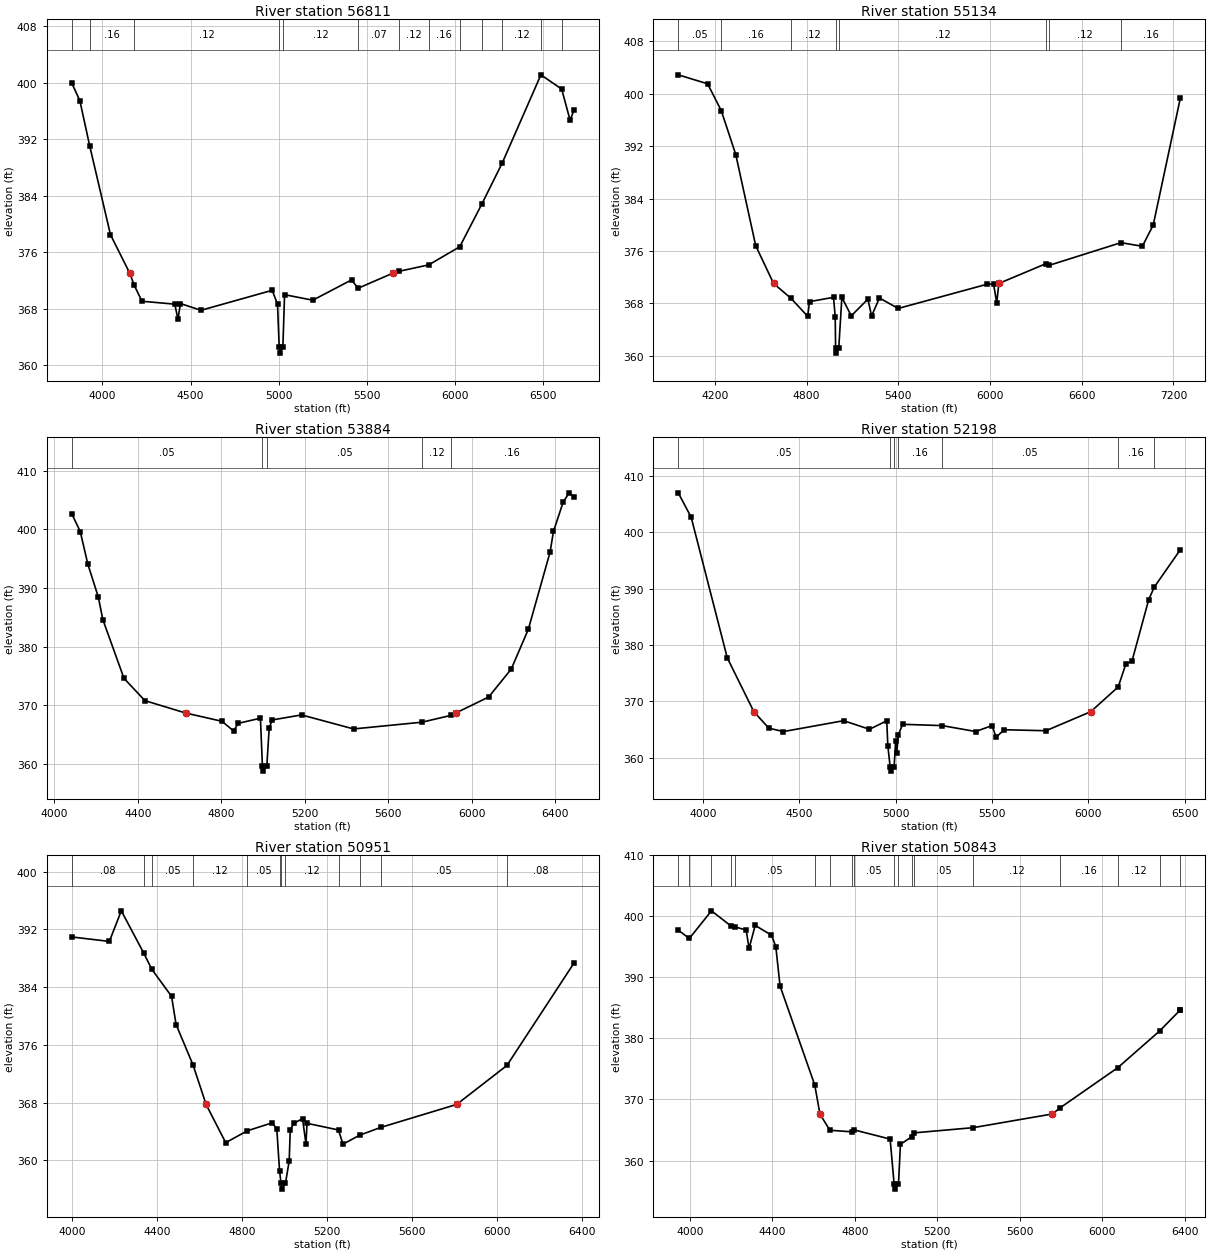
Type RM Length L Ch R = 1,56811,1677,1677,1677
BEGIN DESCRIPTION:
DRY CREEK 46.0
END DESCRIPTION:
XS GIS Cut Line= 3
      2905724.95      7006174.98      2904809.17      7005845.35
      2902934.15      7005902.65
#Sta/Elev= 30
  3825.8  399.93  3871.8  397.42  3927.6  391.03  4045.4  378.47  4154.7  373.03
  4179.8  371.33  4224.3  369.05  4410.3  368.64  4428.6  366.49  4442.2  368.73
  4559.1  367.77  4963.3  370.60  4993.4  368.62  5003.0  362.51  5005.5  361.71
  5023.7  362.51  5033.4  369.98  5193.5  369.20  5413.6  372.07  5450.6  370.89
  5648.4  373.03  5683.6  373.29  5851.5  374.20  6027.5  376.76  6153.1  382.82
  6268.9  388.63  6488.1  401.09  6606.1  399.07  6654.1  394.63  6675.0  396.08
#Mann=13,-1,0
  3825.8    0.05       0  3927.6    0.16       0  4179.8    0.12       0
  5003.0    0.07       0  5023.7    0.12       0  5450.6    0.07       0
  5683.6    0.12       0  5851.5    0.16       0  6027.5    0.12       0
  6153.1    0.16       0  6268.9    0.12       0  6488.1    0.16       0
  6606.1    0.12       0
Bank Sta=4154.7,5648.4
Exp/Cntr=0.3,0.1

Type RM Length L Ch R = 1,55134,1250,1250,1250
BEGIN DESCRIPTION:
DRY CREEK 45.0
END DESCRIPTION:
XS GIS Cut Line= 3
      2905824.98      7006224.96      2905325.00      7005325.00
      2903121.71      7005803.68
#Sta/Elev= 30
  3960.7  402.90  4152.8  401.53  4242.0  397.44  4337.0  390.73  4467.4  376.82
  4584.4  371.05  4697.1  368.81  4807.2  366.05  4819.8  368.28  4976.5  368.94
  4987.4  366.01  4990.1  361.22  4992.6  360.42  5010.8  361.22  5031.1  368.94
  5092.5  366.11  5201.1  368.66  5225.6  366.09  5276.7  368.84  5399.5  367.24
  5982.8  370.95  6023.8  370.94  6044.2  368.07  6057.6  371.05  6368.5  374.10
  6386.8  373.82  6856.6  377.28  6996.6  376.73  7067.6  379.96  7244.9  399.33
#Mann=8,-1,0
  3960.7    0.05       0  4242.0    0.16       0  4697.1    0.12       0
  4990.1    0.07       0  5010.8    0.12       0  6368.5    0.07       0
  6386.8    0.12       0  6856.6    0.16       0
Bank Sta=4584.4,6057.6
Exp/Cntr=0.3,0.1

Type RM Length L Ch R = 1,53884,1686,1686,1686
BEGIN DESCRIPTION:
DRY CREEK 44.0
END DESCRIPTION:
XS GIS Cut Line= 3
      2906375.02      7005075.01      2905446.93      7004740.54
      2904075.01      7004375.00
#Sta/Elev= 30
  4083.8  402.65  4124.5  399.63  4160.6  394.10  4211.3  388.43  4232.6  384.63
  4334.1  374.61  4434.6  370.81  4628.9  368.71  4803.9  367.29  4859.8  365.63
  4881.0  366.94  4988.0  367.82  4997.6  359.60  5000.1  358.80  5018.5  359.60
  5029.9  366.12  5044.1  367.52  5185.0  368.38  5434.5  365.99  5762.5  367.14
  5900.7  368.30  5924.6  368.71  6081.8  371.43  6190.0  376.19  6272.0  382.98
  6376.3  396.14  6392.4  399.65  6438.4  404.59  6467.5  406.23  6490.1  405.54
#Mann=5,-1,0
  4083.8    0.05       0  4997.6    0.03       0  5018.5    0.05       0
  5762.5    0.12       0  5900.7    0.16       0
Bank Sta=4628.9,5924.6
Exp/Cntr=0.3,0.1

Type RM Length L Ch R = 1,52198,1247,1247,1247
BEGIN DESCRIPTION:
DRY CREEK 43.0
END DESCRIPTION:
XS GIS Cut Line= 3
      2906574.98      7005024.97      2906075.00      7004025.00
      2904675.01      7003525.00
#Sta/Elev= 30
  3872.6  406.98  3939.6  402.66  4126.9  377.73  4264.9  368.18  4342.1  365.27
  4417.6  364.65  4730.7  366.58  4864.8  365.06  4954.3  366.56  4959.9  362.12
  4971.8  358.44  4974.3  357.64  4992.7  358.44  5000.7  363.06  5006.0  360.78
  5013.8  364.02  5036.8  365.94  5242.4  365.71  5415.3  364.66  5500.3  365.71
  5521.5  363.66  5564.0  364.98  5780.1  364.80  6012.6  368.18  6155.2  372.58
  6195.3  376.71  6226.1  377.09  6313.1  388.03  6342.1  390.27  6477.2  396.89
#Mann=7,-1,0
  3872.6    0.05       0  4971.8    0.03       0  4992.7    0.05       0
  5013.8    0.16       0  5242.4    0.05       0  6155.2    0.16       0
  6342.1    0.05       0
Bank Sta=4264.9,6012.6
Exp/Cntr=0.3,0.1

Type RM Length L Ch R = 1,50951,108,108,108
BEGIN DESCRIPTION:
Mapping XS 52727fbb
END DESCRIPTION:
XS GIS Cut Line= 6
      2907050.99      7003886.13      2906679.60      7003610.46
      2906396.23      7003342.41      2906132.02      7003307.95
      2905745.27      7003307.95      2904888.77      7003288.83
#Sta/Elev= 30
  3998.1  390.96  4174.9  390.34  4231.2  394.58  4336.6  388.73  4374.0  386.51
  4467.6  382.73  4489.0  378.82  4569.0  373.20  4630.1  367.75  4722.4  362.45
  4824.0  364.09  4942.1  365.21  4962.9  364.31  4975.9  358.52  4982.7  356.81
  4985.2  356.01  5003.6  356.81  5021.1  359.90  5026.2  364.23  5043.5  365.14
  5083.9  365.78  5100.1  362.29  5105.2  365.13  5253.2  364.21  5274.2  362.24
  5352.5  363.48  5451.6  364.56  5809.3  367.75  6045.7  373.15  6360.6  387.31
#Mann=12,-1,0
  3998.1    0.08       0  4336.6    0.16       0  4374.0    0.05       0
  4569.0    0.12       0  4824.0    0.05       0  4975.9    0.12       0
  4982.7    0.07       0  5003.6    0.12       0  5253.2    0.05       0
  5352.5    0.08       0  5451.6    0.05       0  6045.7    0.08       0
Bank Sta=4630.1,5809.3
Exp/Cntr=0.3,0.1

Type RM Length L Ch R = 1,50843,967,967,967
BEGIN DESCRIPTION:
Mapping XS 457fcdd9
END DESCRIPTION:
XS GIS Cut Line= 6
      2907116.15      7003794.27      2906817.45      7003621.94
      2906687.25      7003449.63      2906576.21      7003284.97
      2906365.60      7003231.36      2904908.38      7003200.78
#Sta/Elev= 30
  3944.0  397.75  3997.8  396.38  4105.1  400.91  4201.8  398.37  4217.9  398.30
  4273.5  397.75  4287.4  394.75  4317.1  398.52  4396.1  396.92  4417.0  395.06
  4437.8  388.58  4605.9  372.37  4631.1  367.62  4678.9  364.96  4785.1  364.70
  4795.2  365.03  4971.4  363.51  4990.9  356.11  4993.4  355.31  5011.9  356.11
  5021.4  362.66  5075.9  363.88  5087.9  364.53  5373.8  365.38  5758.5  367.63
  5796.5  368.65  6074.6  375.19  6279.0  381.25  6378.1  384.67  6378.4  384.68
#Mann=18,-1,0
  3944.0    0.08       0  3997.8    0.05       0  4105.1    0.08       0
  4201.8    0.16       0  4217.9    0.05       0  4605.9    0.12       0
  4678.9    0.08       0  4785.1    0.12       0  4795.2    0.05       0
  4990.9    0.04       0  5011.9    0.05       0  5075.9    0.12       0
  5087.9    0.05       0  5373.8    0.12       0  5796.5    0.16       0
  6074.6    0.12       0  6279.0    0.05       0  6378.1    0.08       0
Bank Sta=4631.1,5758.5
Exp/Cntr=0.3,0.1

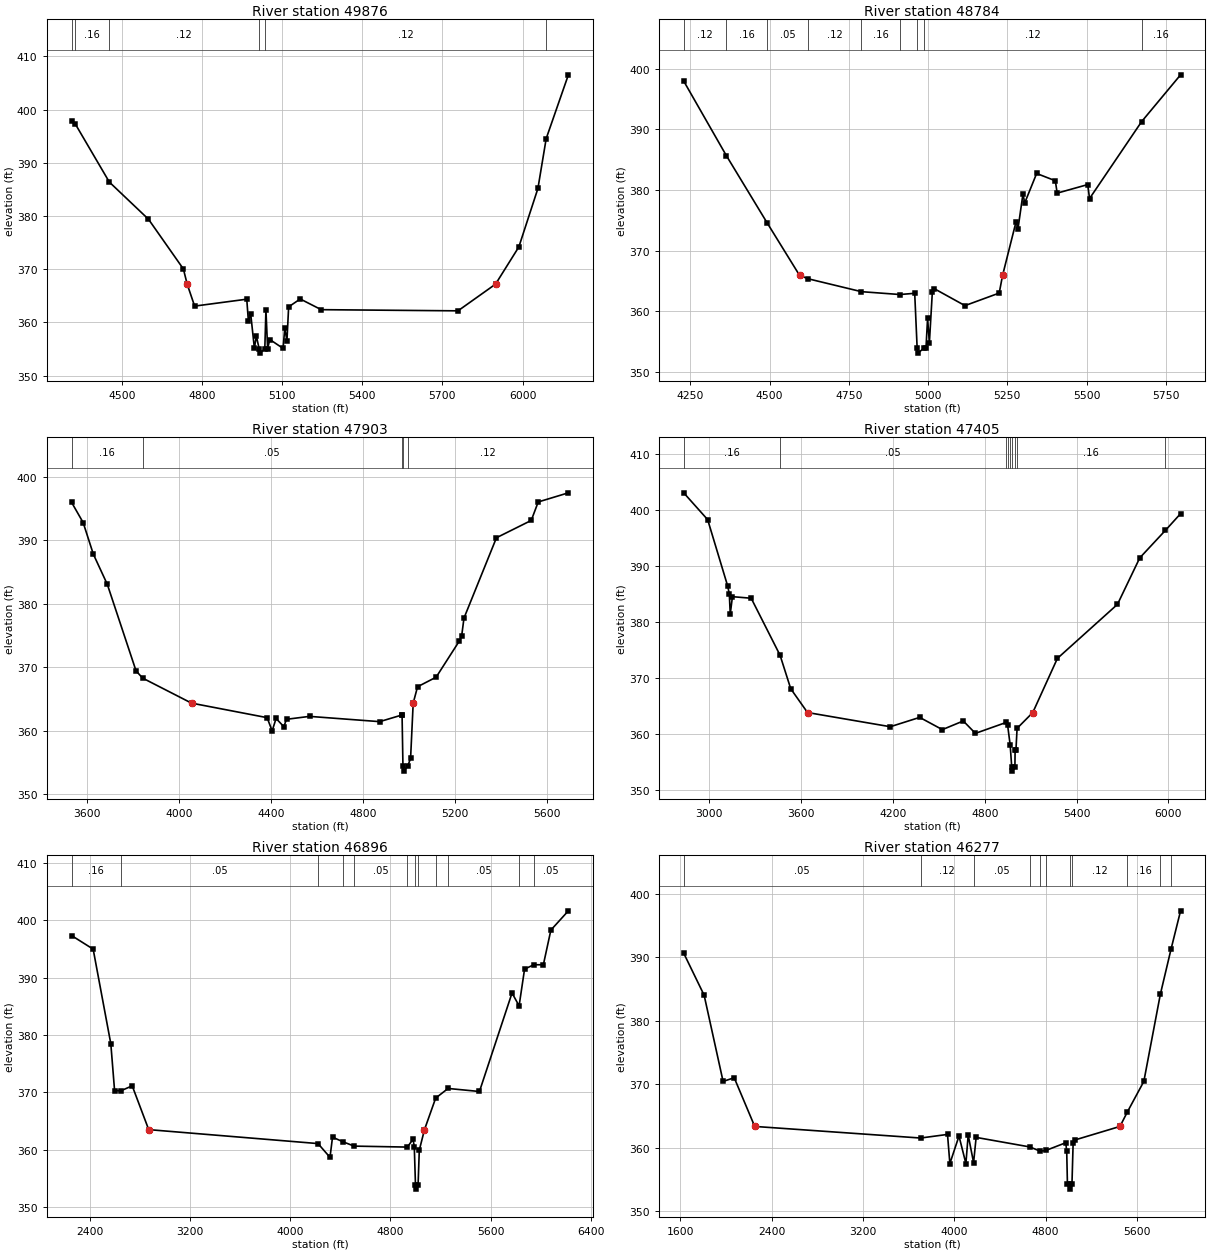
Type RM Length L Ch R = 1,49876,1092,1092,1092
BEGIN DESCRIPTION:
DRY CREEK 41.0
END DESCRIPTION:
XS GIS Cut Line= 3
      2906874.99      7003374.98      2906475.00      7002775.00
      2905774.97      7001874.97
#Sta/Elev= 30
  4310.5  397.91  4324.2  397.35  4452.2  386.39  4598.9  379.40  4729.6  370.05
  4743.8  367.20  4771.7  363.07  4967.0  364.37  4973.0  360.31  4982.0  361.51
  4995.5  355.17  5003.0  357.41  5013.6  355.03  5016.1  354.23  5034.6  355.03
  5038.8  362.35  5045.2  355.10  5053.3  356.79  5103.1  355.12  5109.4  358.93
  5117.5  356.53  5123.9  362.93  5167.3  364.41  5246.0  362.40  5758.2  362.18
  5899.0  367.20  5986.3  374.20  6057.7  385.19  6088.7  394.56  6171.8  406.55
#Mann=6,-1,0
  4310.5    0.12       0  4324.2    0.16       0  4452.2    0.12       0
  5013.6    0.07       0  5034.6    0.12       0  6088.7    0.16       0
Bank Sta=4743.8,5899
Exp/Cntr=0.3,0.1

Type RM Length L Ch R = 1,48784,881,881,881
BEGIN DESCRIPTION:
DRY CREEK 40.0
END DESCRIPTION:
XS GIS Cut Line= 3
      2907025.00      7003124.99      2906725.00      7002425.00
      2906325.00      7001725.00
#Sta/Elev= 30
  4229.0  397.93  4363.6  385.64  4491.9  374.59  4594.8  365.89  4622.7  365.33
  4789.7  363.22  4911.0  362.75  4957.9  362.95  4965.6  353.89  4968.1  353.09
  4986.6  353.89  4993.5  353.92  4998.5  358.82  5004.2  354.81  5013.6  363.22
  5020.1  363.70  5116.5  360.92  5224.5  362.99  5235.1  365.89  5277.8  374.77
  5283.5  373.48  5299.4  379.30  5305.1  377.85  5342.6  382.70  5401.6  381.50
  5407.4  379.46  5503.8  380.87  5509.6  378.57  5673.9  391.25  5796.8  398.96
#Mann=9,-1,0
  4229.0    0.12       0  4363.6    0.16       0  4491.9    0.05       0
  4622.7    0.12       0  4789.7    0.16       0  4911.0    0.12       0
  4965.6    0.07       0  4986.6    0.12       0  5673.9    0.16       0
Bank Sta=4594.8,5235.1
Exp/Cntr=0.3,0.1

Type RM Length L Ch R = 1,47903,498,498,498
BEGIN DESCRIPTION:
DRY CREEK 39.0
END DESCRIPTION:
XS GIS Cut Line= 3
      2907575.00      7003325.01      2907175.00      7001925.00
      2906475.04      7001825.01
#Sta/Elev= 30
  3531.4  396.01  3582.1  392.80  3626.3  387.83  3687.4  383.05  3812.2  369.44
  3840.7  368.29  4053.9  364.34  4382.9  362.05  4405.0  359.96  4421.9  361.92
  4455.7  360.63  4467.4  361.79  4567.5  362.25  4873.0  361.42  4970.0  362.47
  4970.5  362.47  4974.3  354.42  4976.8  353.62  4995.3  354.42  5007.6  355.66
  5018.9  364.34  5037.9  366.92  5118.8  368.43  5219.8  374.13  5229.9  374.91
  5240.0  377.74  5381.4  390.41  5532.9  393.14  5563.2  396.05  5694.5  397.49
#Mann=5,-1,0
  3531.4    0.16       0  3840.7    0.05       0  4970.0    0.12       0
  4974.3    0.07       0  4995.3    0.12       0
Bank Sta=4053.9,5018.9
Exp/Cntr=0.3,0.1

Type RM Length L Ch R = 1,47405,509,509,509
BEGIN DESCRIPTION:
DRY CREEK 38.0
END DESCRIPTION:
XS GIS Cut Line= 3
      2907836.21      7003719.79      2907507.97      7001576.98
      2906435.59      7001448.07
#Sta/Elev= 30
  2832.2  403.11  2988.8  398.31  3120.3  386.36  3130.4  384.97  3136.4  381.40
  3150.7  384.52  3273.3  384.24  3462.1  374.03  3531.8  368.04  3641.5  363.78
  4182.6  361.24  4374.8  362.91  4522.9  360.72  4659.7  362.27  4739.0  360.05
  4940.5  362.01  4949.0  361.62  4966.3  357.96  4976.2  354.09  4978.7  353.29
  4997.2  354.09  4998.5  357.10  5004.0  357.10  5011.4  360.95  5114.1  363.78
  5274.9  373.47  5667.7  383.15  5813.2  391.46  5981.3  396.40  6080.1  399.38
#Mann=9,-1,0
  2832.2    0.16       0  3462.1    0.05       0  4940.5    0.12       0
  4949.0    0.16       0  4966.3    0.12       0  4976.2    0.07       0
  4997.2    0.12       0  5011.4    0.16       0  5981.3    0.12       0
Bank Sta=3641.5,5114.1
Exp/Cntr=0.3,0.1

Type RM Length L Ch R = 1,46896,619,619,619
BEGIN DESCRIPTION:
Mapping XS 622f046f
END DESCRIPTION:
XS GIS Cut Line= 4
      2908011.55      7003686.77      2907796.28      7001589.56
      2907601.83      7001096.51      2906275.45      7001110.40
#Sta/Elev= 30
  2255.3  397.31  2428.0  394.94  2569.0  378.46  2598.9  370.32  2648.1  370.26
  2739.6  371.14  2871.3  363.51  4222.4  361.08  4317.9  358.68  4338.0  362.20
  4423.9  361.37  4510.9  360.64  4935.1  360.47  4980.4  361.83  4990.4  360.57
  4999.9  353.95  5002.4  353.15  5020.9  353.95  5030.4  359.93  5071.9  363.51
  5161.1  369.00  5260.1  370.68  5510.4  370.15  5770.4  387.30  5826.8  385.06
  5870.4  391.46  5944.0  392.22  6020.4  392.22  6080.4  398.26  6220.0  401.61
#Mann=12,-1,0
  2255.3    0.16       0  2648.1    0.05       0  4222.4    0.16       0
  4423.9    0.12       0  4510.9    0.05       0  4935.1    0.12       0
  4999.9    0.07       0  5020.9    0.12       0  5161.1    0.16       0
  5260.1    0.05       0  5826.8    0.16       0  5944.0    0.05       0
Bank Sta=2871.3,5071.9
Exp/Cntr=0.3,0.1

Type RM Length L Ch R = 1,46277,481,481,481
BEGIN DESCRIPTION:
DRY CREEK 37.0
END DESCRIPTION:
XS GIS Cut Line= 5
      2908136.56      7003672.94      2907865.72      7001131.23
      2907550.00      7000700.00      2907268.03      7000488.61
      2906365.76      7000603.45
#Sta/Elev= 30
  1629.4  390.67  1808.3  384.04  1974.4  370.44  2071.8  371.02  2251.4  363.34
  3704.4  361.51  3940.3  362.08  3960.9  357.48  4040.9  361.82  4101.3  357.49
  4121.4  361.99  4168.6  357.63  4191.1  361.61  4662.7  360.10  4752.7  359.43
  4803.5  359.56  4976.2  360.77  4984.5  359.41  4990.8  354.25  5009.5  354.25
  5012.0  353.45  5030.5  354.25  5040.8  360.76  5055.4  361.20  5451.0  363.34
  5516.6  365.65  5660.1  370.44  5804.4  384.16  5897.9  391.27  5981.9  397.35
#Mann=11,-1,0
  1629.4    0.05       0  3704.4    0.12       0  4168.6    0.05       0
  4662.7    0.12       0  4752.7    0.05       0  4803.5    0.12       0
  5009.5    0.07       0  5030.5    0.12       0  5516.6    0.16       0
  5804.4    0.12       0  5897.9    0.16       0
Bank Sta=2251.4,5451
Exp/Cntr=0.3,0.1

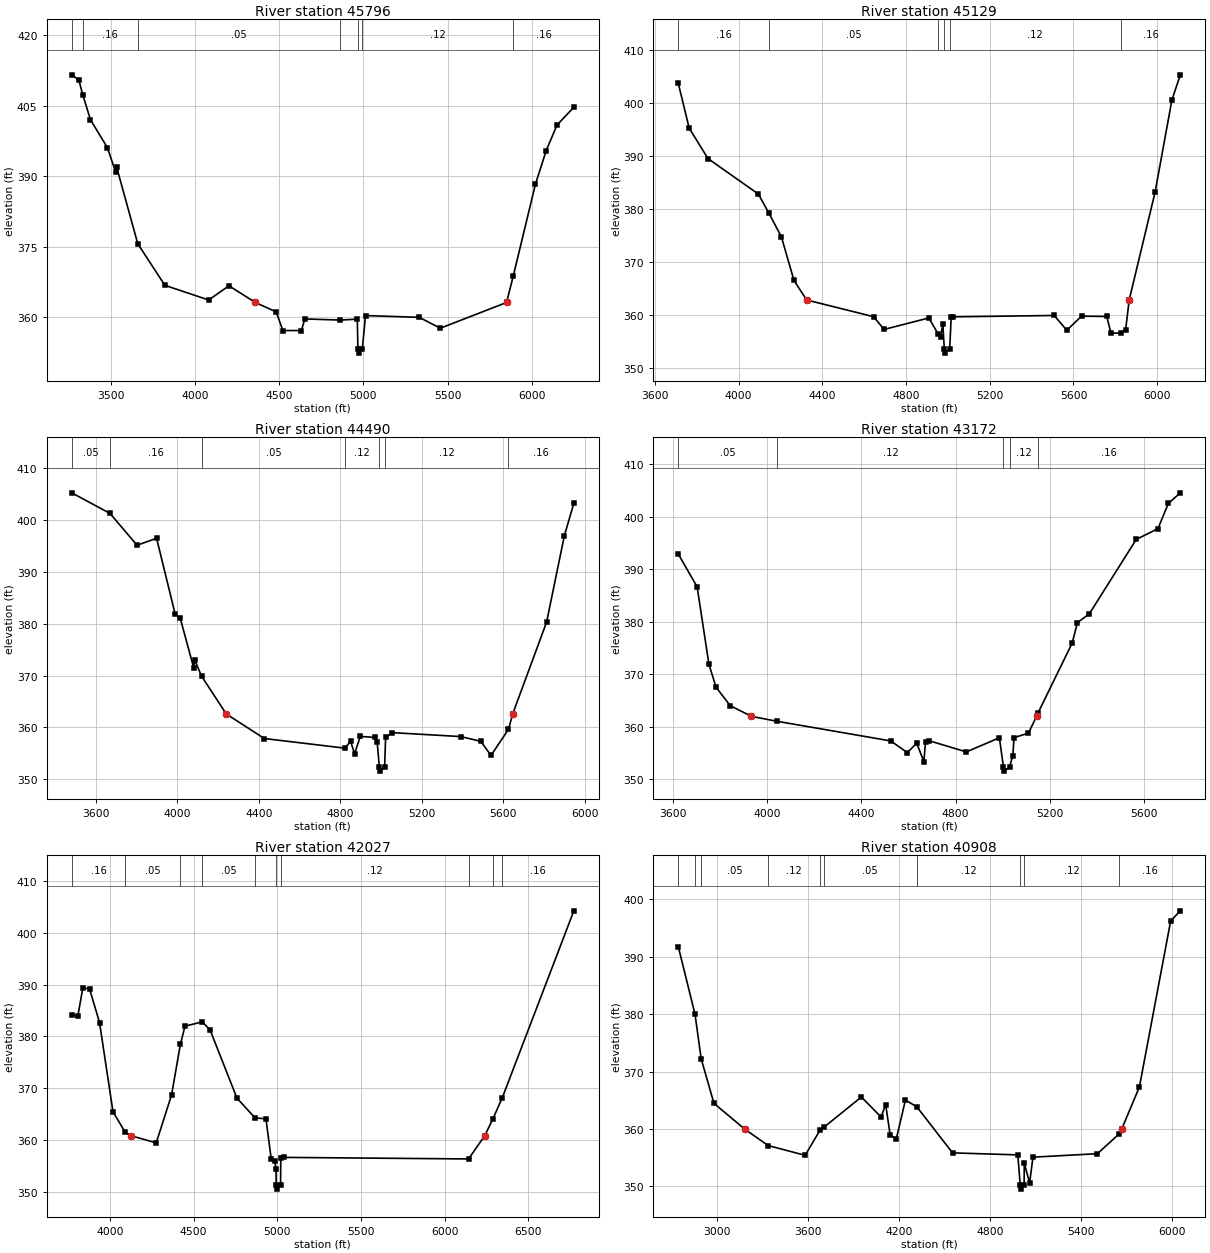
Type RM Length L Ch R = 1,45796,667,667,667
BEGIN DESCRIPTION:
Mapping XS 5dcf9abd
END DESCRIPTION:
XS GIS Cut Line= 3
      2909226.86      7000207.62      2907560.17      7000096.51
      2906310.15      7000499.29
#Sta/Elev= 30
  3267.1  411.60  3309.1  410.49  3332.4  407.36  3377.9  402.07  3479.4  396.05
  3528.3  390.84  3533.3  392.00  3659.2  375.65  3820.2  366.79  4080.8  363.66
  4201.0  366.68  4358.3  363.13  4481.7  361.13  4521.7  357.16  4632.0  357.16
  4652.0  359.63  4861.0  359.39  4963.9  359.58  4967.7  353.15  4971.9  352.35
  4993.5  353.15  5012.7  360.35  5331.7  359.97  5457.7  357.66  5850.9  363.13
  5891.5  368.87  6022.3  388.29  6086.5  395.47  6150.6  400.91  6250.8  404.70
#Mann=7,-1,0
  3267.1    0.05       0  3332.4    0.16       0  3659.2    0.05       0
  4861.0    0.12       0  4967.7    0.07       0  4993.5    0.12       0
  5891.5    0.16       0
Bank Sta=4358.3,5850.9
Exp/Cntr=0.3,0.1

Type RM Length L Ch R = 1,45129,639,639,639
BEGIN DESCRIPTION:
DRY CREEK 36.0
END DESCRIPTION:
XS GIS Cut Line= 3
      2908817.09      6999659.01      2907525.00      6999725.00
      2906425.01      6999625.00
#Sta/Elev= 30
  3712.0  403.81  3764.2  395.30  3854.3  389.54  4094.6  382.84  4145.9  379.17
  4204.7  374.76  4264.8  366.51  4325.3  362.81  4645.3  359.65  4695.4  357.24
  4909.2  359.41  4953.3  356.39  4965.7  355.75  4975.7  358.34  4982.9  353.56
  4987.1  352.76  5008.7  353.56  5015.8  359.53  5025.9  359.62  5507.8  359.88
  5568.1  357.09  5638.4  359.75  5758.9  359.69  5779.0  356.52  5826.0  356.58
  5849.2  357.21  5866.1  362.81  5989.8  383.20  6070.1  400.61  6110.3  405.38
#Mann=6,-1,0
  3712.0    0.16       0  4145.9    0.05       0  4953.3    0.12       0
  4982.9    0.07       0  5008.7    0.12       0  5826.0    0.16       0
Bank Sta=4325.3,5866.1
Exp/Cntr=0.3,0.1

Type RM Length L Ch R = 1,44490,1318,1318,1318
BEGIN DESCRIPTION:
DRY CREEK 35.0
END DESCRIPTION:
XS GIS Cut Line= 3
      2908823.66      6999425.63      2907316.02      6999259.19
      2906425.03      6999574.99
#Sta/Elev= 30
  3483.2  405.27  3670.8  401.29  3803.3  395.16  3899.2  396.49  3990.0  381.90
  4015.1  381.07  4080.9  371.55  4085.9  373.01  4120.0  369.88  4240.8  362.60
  4427.6  357.86  4823.5  356.00  4850.1  357.34  4870.2  354.96  4898.4  358.28
  4970.8  358.06  4980.9  357.14  4991.5  352.37  4995.8  351.57  5017.3  352.37
  5022.3  358.06  5054.1  359.00  5389.9  358.24  5489.1  357.32  5539.0  354.60
  5624.6  359.62  5645.4  362.60  5811.7  380.33  5899.0  397.03  5945.3  403.27
#Mann=7,-1,0
  3483.2    0.05       0  3670.8    0.16       0  4120.0    0.05       0
  4823.5    0.12       0  4991.5    0.07       0  5017.3    0.12       0
  5624.6    0.16       0
Bank Sta=4240.8,5645.4
Exp/Cntr=0.3,0.1

Type RM Length L Ch R = 1,43172,1145,1145,1145
BEGIN DESCRIPTION:
DRY CREEK 34.0
END DESCRIPTION:
XS GIS Cut Line= 3
      2908024.97      6998625.00      2906625.00      6998725.00
      2906425.01      6999424.95
#Sta/Elev= 30
  3622.5  392.90  3702.7  386.64  3752.8  371.89  3782.9  367.54  3843.0  364.02
  3933.2  361.98  4043.2  361.03  4524.8  357.30  4594.9  355.08  4635.0  356.87
  4665.1  353.37  4672.6  357.19  4685.2  357.37  4845.6  355.21  4985.9  357.90
  5003.1  352.35  5007.4  351.55  5029.0  352.35  5042.9  354.47  5048.1  357.93
  5109.2  358.78  5143.6  361.98  5150.1  362.64  5295.1  375.95  5317.2  379.83
  5367.9  381.51  5566.8  395.66  5659.1  397.72  5703.3  402.53  5754.0  404.54
#Mann=5,-1,0
  3622.5    0.05       0  4043.2    0.12       0  5003.1    0.07       0
  5029.0    0.12       0  5150.1    0.16       0
Bank Sta=3933.2,5143.6
Exp/Cntr=0.3,0.1

Type RM Length L Ch R = 1,42027,1119,1119,1119
BEGIN DESCRIPTION:
Mapping XS 02aaf028
END DESCRIPTION:
XS GIS Cut Line= 3
      2907960.89      6997949.43      2906804.59      6997996.31
      2905413.97      6999204.64
#Sta/Elev= 30
  3772.1  384.16  3808.0  383.87  3838.0  389.33  3878.1  389.20  3938.1  382.67
  4018.2  365.49  4091.5  361.52  4125.7  360.86  4276.6  359.48  4368.5  368.75
  4420.9  378.47  4448.5  381.98  4551.5  382.82  4598.7  381.24  4758.8  368.11
  4867.2  364.29  4932.2  364.12  4963.7  356.36  4984.6  355.99  4992.2  354.36
  4993.5  351.36  4997.8  350.56  5019.4  351.36  5020.7  356.53  5041.6  356.68
  6142.6  356.38  6239.2  360.86  6287.4  364.07  6343.5  368.13  6771.6  404.23
#Mann=10,-1,0
  3772.1    0.16       0  4091.5    0.05       0  4420.9    0.16       0
  4551.5    0.05       0  4867.2    0.12       0  4993.5    0.07       0
  5019.4    0.12       0  6142.6    0.16       0  6287.4    0.12       0
  6343.5    0.16       0
Bank Sta=4125.7,6239.2
Exp/Cntr=0.3,0.1

Type RM Length L Ch R = 1,40908,1647,1647,1647
BEGIN DESCRIPTION:
DRY CREEK 33.0
END DESCRIPTION:
XS GIS Cut Line= 3
      2908249.95      6997600.00      2906150.00      6997650.00
      2905250.01      6998450.00
#Sta/Elev= 30
  2747.8  391.76  2858.3  379.97  2898.7  372.23  2982.8  364.46  3185.8  359.97
  3339.2  357.12  3583.0  355.41  3682.2  359.85  3706.2  360.29  3953.1  365.56
  4083.1  362.08  4113.1  364.26  4143.1  358.89  4183.2  358.30  4243.2  365.03
  4317.8  363.87  4553.3  355.84  4983.0  355.49  4998.4  350.33  5002.8  349.53
  5024.4  350.33  5025.6  354.04  5060.7  350.61  5082.5  355.09  5507.3  355.70
  5652.1  359.20  5666.6  359.97  5783.2  367.31  5989.0  396.21  6052.5  397.97
#Mann=10,-1,0
  2747.8    0.05       0  2858.3    0.16       0  2898.7    0.05       0
  3339.2    0.12       0  3682.2    0.16       0  3706.2    0.05       0
  4317.8    0.12       0  4998.4    0.07       0  5024.4    0.12       0
  5652.1    0.16       0
Bank Sta=3185.8,5666.6
Exp/Cntr=0.3,0.1

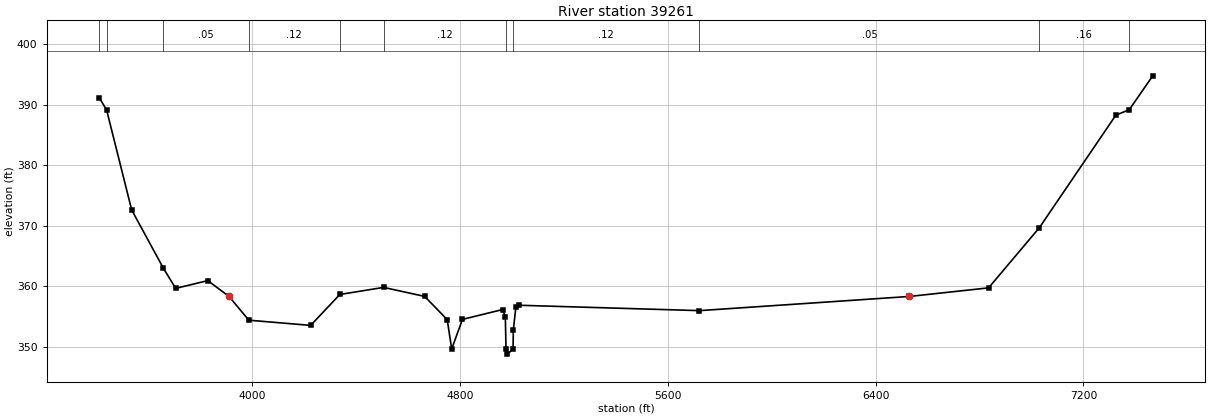
Type RM Length L Ch R = 1,39261,1049,1049,1049
BEGIN DESCRIPTION:
DRY CREEK 32.0
END DESCRIPTION:
XS GIS Cut Line= 3
      2908229.74      6997381.03      2906689.87      6996987.77
      2904222.85      6996957.42
#Sta/Elev= 30
  3410.7  391.13  3438.5  389.17  3535.2  372.62  3656.1  363.07  3704.6  359.65
  3828.4  360.93  3910.2  358.31  3986.3  354.39  4224.5  353.53  4336.8  358.64
  4505.5  359.81  4663.5  358.32  4750.3  354.48  4767.6  349.63  4808.9  354.52
  4963.7  356.15  4974.1  354.94  4976.8  349.58  4981.4  348.78  5003.8  349.58
  5004.9  352.77  5014.9  356.61  5024.9  356.86  5721.8  355.97  6529.3  358.31
  6835.0  359.73  7030.8  369.69  7325.0  388.27  7376.8  389.18  7467.2  394.78
#Mann=11,-1,0
  3410.7    0.05       0  3438.5    0.16       0  3656.1    0.05       0
  3986.3    0.12       0  4336.8    0.05       0  4505.5    0.12       0
  4976.8    0.07       0  5003.8    0.12       0  5721.8    0.05       0
  7030.8    0.16       0  7376.8    0.05       0
Bank Sta=3910.2,6529.3
Exp/Cntr=0.3,0.1