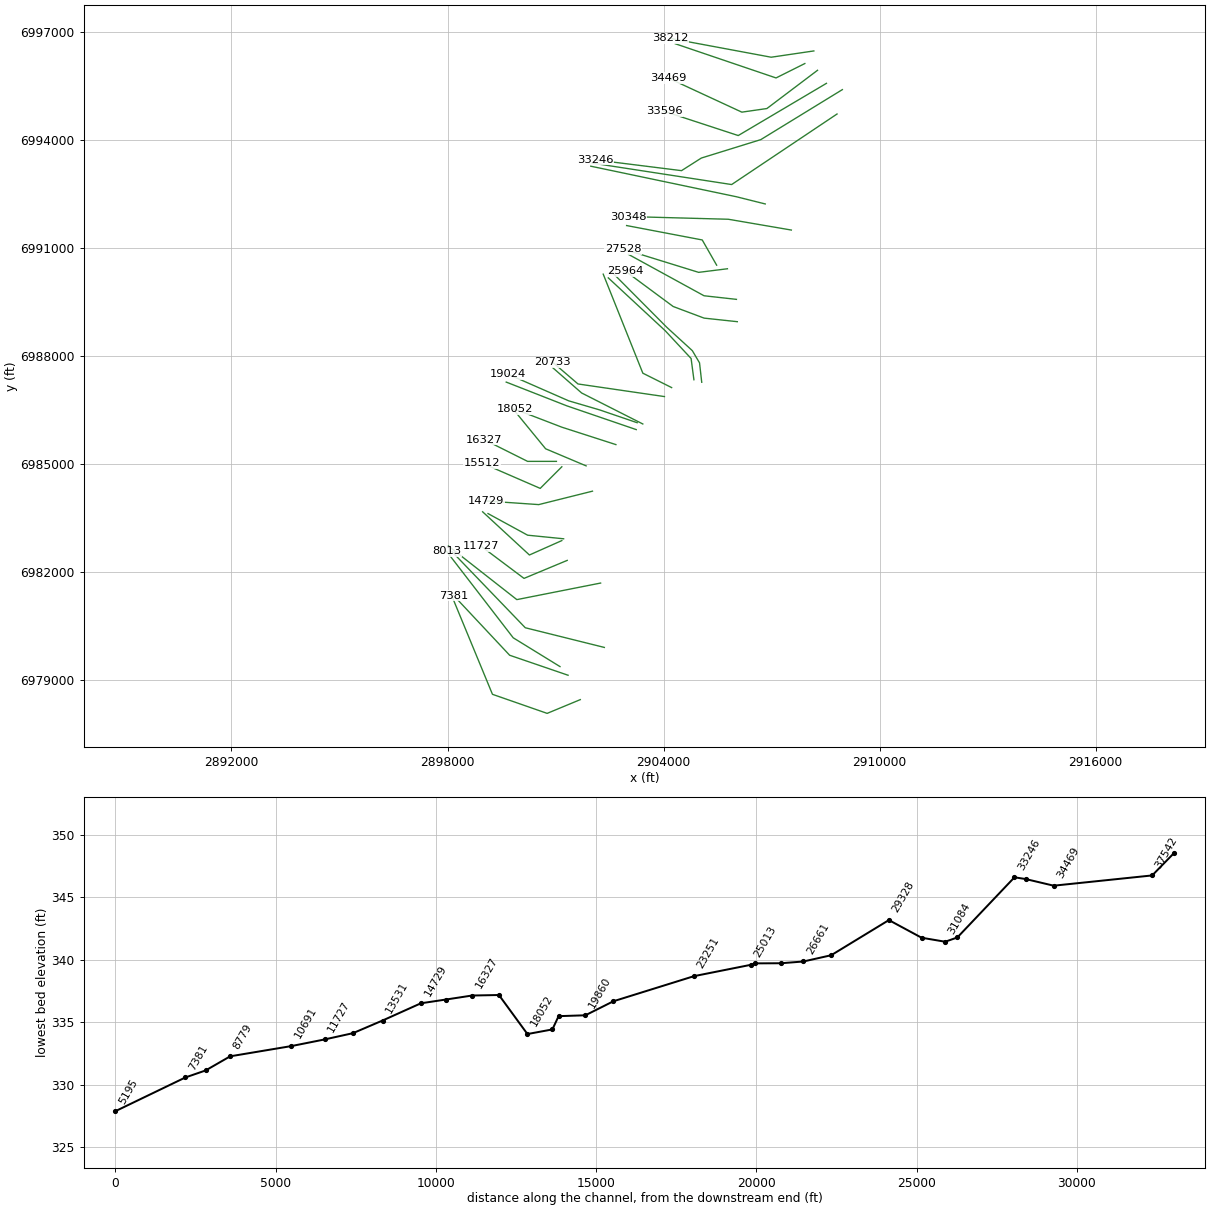
HEC-RAS study DRY CREEK.prj: DRY CREEK Base Level Engineering

--- DRY CREEK.g01 (geometry) --- (continued)

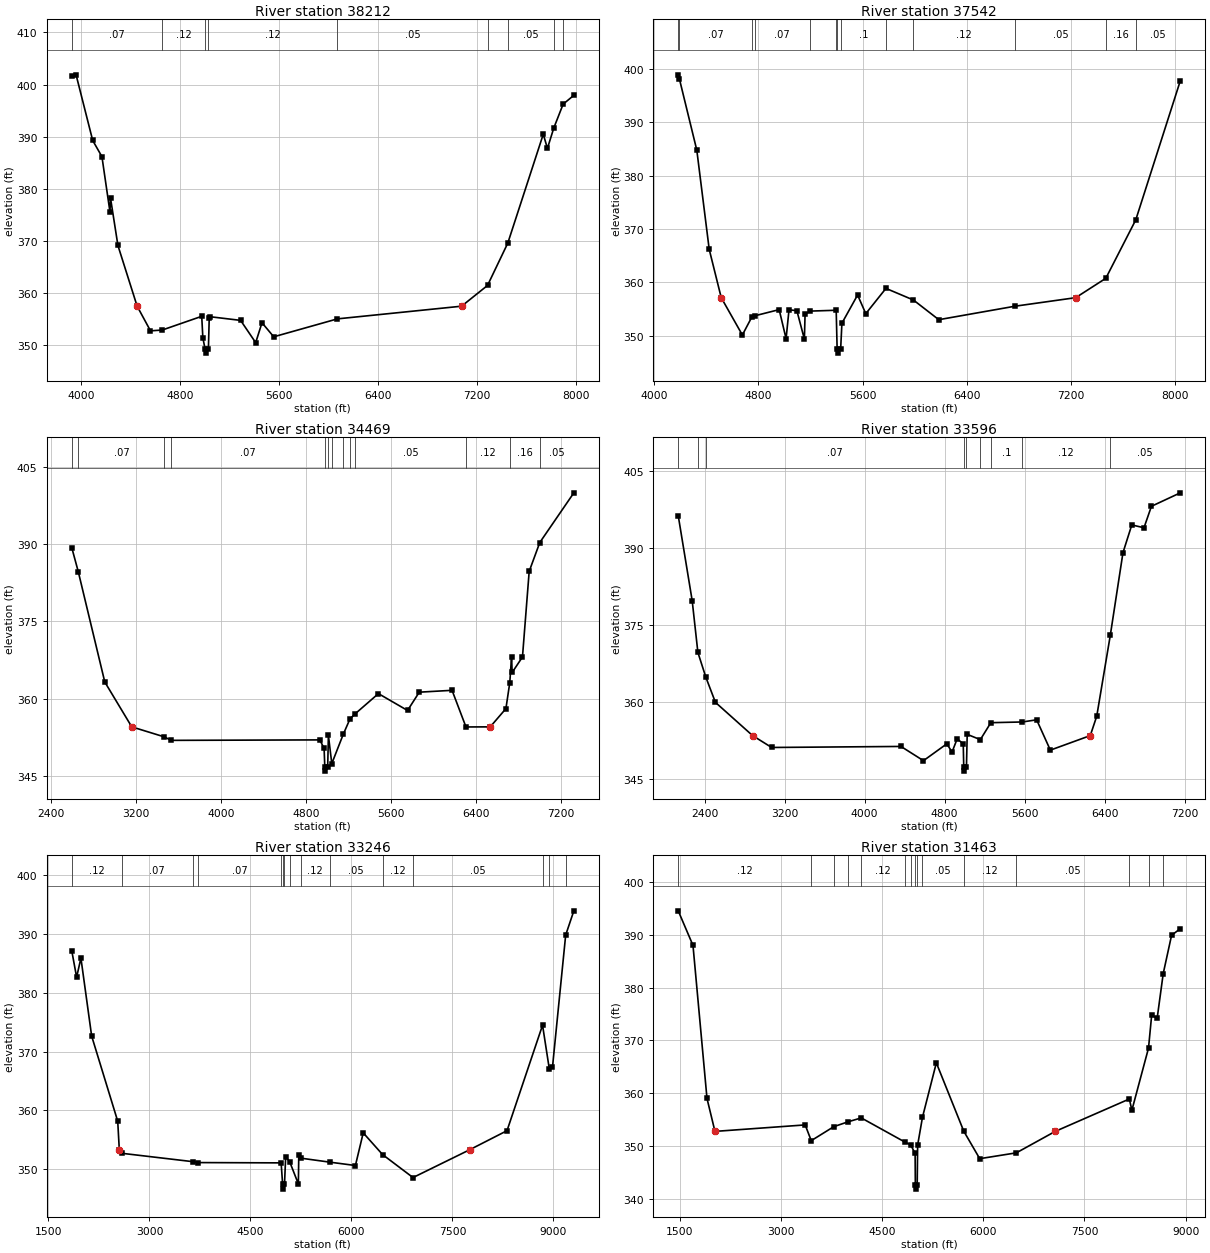
Type RM Length L Ch R = 1,38212,670,670,670
BEGIN DESCRIPTION:
DRY CREEK 31.0
END DESCRIPTION:
XS GIS Cut Line= 3
      2908175.02      6996475.00      2906989.63      6996300.50
      2904175.04      6996824.99
#Sta/Elev= 30
  3923.8  401.64  3958.7  401.86  4093.0  389.28  4167.8  386.17  4232.5  375.62
  4237.5  378.18  4297.1  369.14  4452.5  357.50  4560.6  352.77  4655.8  352.93
  4975.0  355.56  4984.1  351.44  5002.0  349.30  5006.6  348.50  5029.0  349.30
  5035.7  355.24  5045.8  355.47  5289.4  354.78  5411.5  350.51  5462.4  354.33
  5557.4  351.63  6072.7  355.07  7077.1  357.50  7286.8  361.48  7450.8  369.60
  7737.6  390.47  7771.4  387.76  7822.6  391.65  7898.4  396.24  7985.0  397.93
#Mann=9,-1,0
  3923.8    0.07       0  4655.8    0.12       0  5002.0    0.07       0
  5029.0    0.12       0  6072.7    0.05       0  7286.8    0.16       0
  7450.8    0.05       0  7822.6    0.16       0  7898.4    0.05       0
Bank Sta=4452.5,7077.1
Exp/Cntr=0.3,0.1

Type RM Length L Ch R = 1,37542,3073,3073,3073
BEGIN DESCRIPTION:
DRY CREEK 30.0
END DESCRIPTION:
XS GIS Cut Line= 3
      2907924.97      6996124.98      2907125.00      6995725.00
      2904324.96      6996675.01
#Sta/Elev= 30
  4186.5  398.93  4195.8  398.13  4329.0  384.79  4424.0  366.21  4516.3  357.14
  4678.4  350.14  4753.0  353.60  4773.6  353.74  4960.7  354.90  5013.8  349.44
  5036.2  354.88  5096.6  354.69  5154.1  349.36  5159.4  354.02  5196.0  354.62
  5398.1  354.78  5405.3  347.54  5410.0  346.74  5432.4  347.54  5442.0  352.35
  5562.3  357.64  5625.1  354.14  5779.7  358.88  5990.5  356.70  6185.1  353.01
  6769.9  355.54  7235.4  357.14  7466.2  360.77  7696.0  371.73  8037.7  397.82
#Mann=13,-1,0
  4186.5    0.05       0  4195.8    0.07       0  4753.0    0.12       0
  4773.6    0.07       0  5196.0    0.12       0  5398.1     0.1       0
  5405.3    0.07       0  5432.4     0.1       0  5779.7    0.05       0
  5990.5    0.12       0  6769.9    0.05       0  7466.2    0.16       0
  7696.0    0.05       0
Bank Sta=4516.3,7235.4
Exp/Cntr=0.3,0.1

Type RM Length L Ch R = 1,34469,873,873,873
BEGIN DESCRIPTION:
DRY CREEK 29.0
END DESCRIPTION:
XS GIS Cut Line= 4
      2908277.24      6995937.66      2906871.00      6994875.17
      2906175.00      6994775.00      2904125.00      6995725.00
#Sta/Elev= 30
  2594.4  389.28  2655.6  384.62  2905.0  363.22  3159.0  354.51  3466.3  352.56
  3528.9  351.89  4928.7  351.98  4969.1  350.34  4975.8  346.72  4980.5  345.92
  5002.9  346.72  5009.6  352.86  5041.5  347.38  5149.9  353.09  5212.8  356.05
  5260.2  357.02  5480.3  360.96  5754.4  357.69  5864.7  361.24  6173.3  361.60
  6304.2  354.49  6532.7  354.51  6680.2  358.05  6716.6  363.10  6733.3  368.08
  6738.8  365.06  6836.0  368.07  6899.2  384.68  6999.0  390.28  7319.5  399.92
#Mann=13,-1,0
  2594.4    0.05       0  2655.6    0.07       0  3466.3    0.12       0
  3528.9    0.07       0  4975.8    0.07       0  5002.9    0.07       0
  5041.5    0.12       0  5149.9    0.16       0  5212.8    0.12       0
  5260.2    0.05       0  6304.2    0.12       0  6716.6    0.16       0
  6999.0    0.05       0
Bank Sta=3159,6532.7
Exp/Cntr=0.3,0.1

Type RM Length L Ch R = 1,33596,350,350,350
BEGIN DESCRIPTION:
DRY CREEK 28.0
END DESCRIPTION:
XS GIS Cut Line= 3
      2908524.99      6995574.99      2906075.00      6994125.00
      2904010.22      6994801.51
#Sta/Elev= 30
  2136.2  396.33  2275.6  379.75  2332.6  369.64  2411.7  364.82  2508.0  359.88
  2879.6  353.39  3070.2  351.07  4363.0  351.27  4588.0  348.49  4821.2  351.78
  4873.9  350.18  4925.0  352.76  4985.7  351.77  4990.7  347.25  4995.4  346.45
  5017.8  347.25  5025.2  353.63  5156.6  352.60  5261.6  355.91  5576.7  356.05
  5719.7  356.47  5856.5  350.55  6255.7  353.39  6320.4  357.18  6456.0  372.99
  6582.6  389.11  6670.7  394.53  6792.8  393.98  6867.0  398.17  7155.9  400.80
#Mann=9,-1,0
  2136.2    0.16       0  2332.6    0.05       0  2411.7    0.07       0
  4990.7    0.07       0  5017.8    0.07       0  5156.6    0.05       0
  5261.6     0.1       0  5576.7    0.12       0  6456.0    0.05       0
Bank Sta=2879.6,6255.7
Exp/Cntr=0.3,0.1

Type RM Length L Ch R = 1,33246,1783,1783,1783
BEGIN DESCRIPTION:
double DRY CREEK 27.0
END DESCRIPTION:
XS GIS Cut Line= 5
      2908966.77      6995400.45      2906701.19      6994011.59
      2905050.00      6993500.00      2904500.00      6993150.00
      2902100.03      6993450.00
#Sta/Elev= 30
  1846.1  387.16  1918.1  382.67  1982.0  385.92  2141.4  372.65  2528.5  358.15
  2552.1  353.29  2590.4  352.69  3640.9  351.27  3713.7  351.11  4955.4  351.06
  4977.8  347.39  4982.7  346.59  5005.3  347.39  5023.0  352.08  5081.6  351.28
  5211.4  347.47  5217.5  352.45  5243.2  351.87  5680.1  351.18  6058.7  350.61
  6174.5  356.17  6462.4  352.47  6914.0  348.56  7754.9  353.29  8310.1  356.54
  8837.9  374.50  8938.0  367.07  8985.3  367.34  9181.4  389.84  9302.7  393.97
#Mann=15,-1,0
  1846.1    0.12       0  2590.4    0.07       0  3640.9    0.12       0
  3713.7    0.07       0  4955.4    0.12       0  4977.8    0.07       0
  5005.3    0.12       0  5081.6    0.07       0  5243.2    0.12       0
  5680.1    0.05       0  6462.4    0.12       0  6914.0    0.05       0
  8837.9     0.1       0  8938.0    0.16       0  9181.4    0.05       0
Bank Sta=2552.1,7754.9
Exp/Cntr=0.3,0.1

Type RM Length L Ch R = 1,31463,379,379,379
BEGIN DESCRIPTION:
double DRY CREEK 26.0
END DESCRIPTION:
XS GIS Cut Line= 3
      2908819.23      6994723.38      2905891.59      6992763.85
      2902015.41      6993360.28
#Sta/Elev= 30
  1477.1  394.61  1695.8  388.05  1903.4  359.00  2021.5  352.74  3359.4  353.97
  3449.2  350.98  3783.9  353.64  3997.9  354.57  4191.1  355.30  4844.2  350.67
  4923.7  350.18  4989.4  348.56  4992.9  342.58  4997.8  341.78  5020.4  342.58
  5026.9  350.13  5098.8  355.43  5304.3  365.75  5710.8  352.78  5947.6  347.56
  6490.8  348.67  7067.2  352.74  8165.7  358.89  8203.9  356.76  8450.2  368.55
  8497.3  374.83  8578.2  374.18  8668.5  382.71  8792.1  389.96  8921.8  391.23
#Mann=15,-1,0
  1477.1    0.12       0  3449.2    0.07       0  3783.9    0.12       0
  3997.9    0.07       0  4191.1    0.12       0  4844.2    0.07       0
  4923.7    0.12       0  4992.9    0.07       0  5020.4    0.12       0
  5098.8    0.05       0  5710.8    0.12       0  6490.8    0.05       0
  8165.7    0.16       0  8450.2    0.05       0  8668.5    0.16       0
Bank Sta=2021.5,7067.2
Exp/Cntr=0.3,0.1

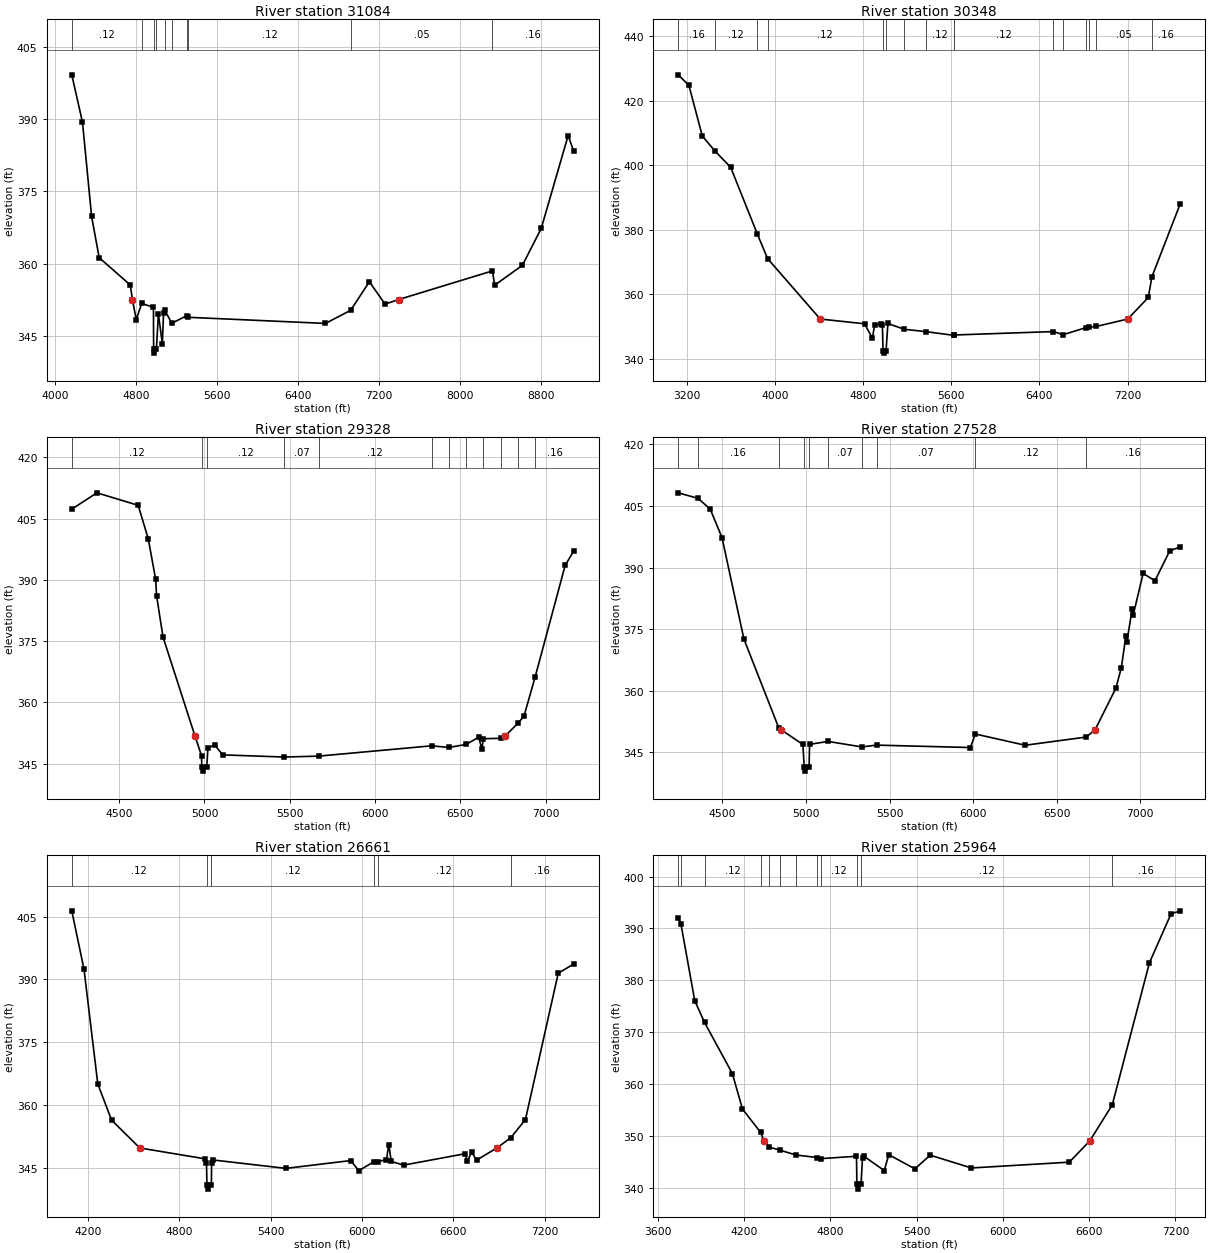
Type RM Length L Ch R = 1,31084,736,736,736
BEGIN DESCRIPTION:
double DRY CREEK 25.0
END DESCRIPTION:
XS GIS Cut Line= 3
      2906825.03      6992224.99      2906025.00      6992425.00
      2901979.50      6993273.63
#Sta/Elev= 30
  4167.5  399.16  4273.2  389.34  4363.4  369.78  4438.1  361.24  4744.8  355.58
  4766.7  352.56  4804.0  348.39  4858.4  351.76  4974.1  350.92  4975.8  342.24
  4980.7  341.44  5003.3  342.24  5022.8  349.58  5061.9  343.37  5073.9  349.69
  5083.9  350.42  5155.0  347.63  5301.8  349.19  5319.4  348.87  6672.8  347.60
  6922.2  350.33  7106.5  356.25  7261.3  351.60  7396.4  352.56  8322.2  358.50
  8343.5  355.52  8617.6  359.65  8803.3  367.29  9069.0  386.54  9125.7  383.27
#Mann=10,-1,0
  4167.5    0.12       0  4858.4    0.07       0  4975.8    0.07       0
  5003.3    0.07       0  5083.9    0.07       0  5155.0    0.12       0
  5301.8    0.07       0  5319.4    0.12       0  6922.2    0.05       0
  8322.2    0.16       0
Bank Sta=4766.7,7396.4
Exp/Cntr=0.3,0.1

Type RM Length L Ch R = 1,30348,1020,1020,1020
BEGIN DESCRIPTION:
double double DRY CREEK 24.0
END DESCRIPTION:
XS GIS Cut Line= 3
      2907550.03      6991500.00      2905800.00      6991800.00
      2903024.97      6991875.00
#Sta/Elev= 30
  3125.0  427.97  3221.4  424.72  3343.2  409.03  3455.9  404.45  3600.2  399.33
  3843.5  378.54  3934.8  371.05  4412.2  352.32  4814.3  350.85  4885.3  346.37
  4905.6  350.59  4965.6  350.74  4975.6  350.56  4981.8  342.56  4986.7  341.76
  5009.3  342.56  5025.6  350.94  5174.8  349.14  5367.1  348.43  5625.5  347.26
  5629.0  347.38  6526.0  348.44  6613.9  347.47  6817.6  349.62  6851.6  349.82
  6916.0  350.03  7199.9  352.32  7386.5  359.00  7419.1  365.40  7676.6  388.08
#Mann=16,-1,0
  3125.0    0.16       0  3455.9    0.12       0  3843.5    0.16       0
  3934.8    0.12       0  4981.8    0.07       0  5009.3    0.12       0
  5174.8    0.07       0  5367.1    0.12       0  5625.5    0.07       0
  5629.0    0.12       0  6526.0    0.05       0  6613.9    0.12       0
  6817.6    0.05       0  6851.6    0.16       0  6916.0    0.05       0
  7419.1    0.16       0
Bank Sta=4412.2,7199.9
Exp/Cntr=0.3,0.1

Type RM Length L Ch R = 1,29328,1800,1800,1800
BEGIN DESCRIPTION:
double DRY CREEK 23.0
END DESCRIPTION:
XS GIS Cut Line= 3
      2905475.02      6990524.97      2905075.00      6991225.00
      2902975.01      6991625.00
#Sta/Elev= 30
  4221.8  407.33  4369.4  411.32  4611.3  408.26  4670.3  400.06  4713.5  390.18
  4719.2  386.11  4756.7  376.02  4943.8  351.82  4982.7  346.95  4984.1  344.07
  4989.3  343.17  5012.9  344.07  5020.1  348.80  5059.2  349.64  5106.3  347.15
  5468.0  346.62  5671.0  346.85  6331.9  349.37  6433.1  348.97  6534.4  349.71
  6607.8  351.48  6626.3  348.57  6635.7  351.11  6736.9  351.21  6764.3  351.82
  6838.2  354.90  6873.8  356.69  6939.4  366.31  7114.9  393.55  7165.8  397.13
#Mann=12,-1,0
  4221.8    0.12       0  4984.1    0.07       0  5012.9    0.12       0
  5468.0    0.07       0  5671.0    0.12       0  6331.9    0.16       0
  6433.1    0.05       0  6534.4    0.16       0  6635.7     0.1       0
  6736.9    0.05       0  6838.2     0.1       0  6939.4    0.16       0
Bank Sta=4943.8,6764.3
Exp/Cntr=0.3,0.1

Type RM Length L Ch R = 1,27528,867,867,867
BEGIN DESCRIPTION:
double DRY CREEK 22.0
END DESCRIPTION:
XS GIS Cut Line= 3
      2905775.01      6990425.00      2904975.00      6990325.00
      2902875.03      6990974.99
#Sta/Elev= 30
  4235.4  408.21  4353.6  406.87  4426.9  404.24  4497.4  397.28  4628.4  372.57
  4836.2  350.98  4851.2  350.45  4981.2  346.86  4989.4  341.26  4994.6  340.36
  5018.2  341.26  5021.5  346.88  5131.6  347.60  5334.8  346.26  5422.9  346.70
  5983.8  346.11  6013.1  349.41  6311.7  346.67  6677.4  348.67  6729.9  350.45
  6854.4  360.59  6887.0  365.58  6914.4  373.40  6919.6  371.77  6952.3  379.97
  6957.5  378.32  7017.5  388.57  7087.9  386.77  7177.1  394.10  7239.9  395.02
#Mann=10,-1,0
  4235.4    0.12       0  4353.6    0.16       0  4836.2    0.12       0
  4989.4    0.07       0  5018.2    0.12       0  5131.6    0.07       0
  5334.8    0.12       0  5422.9    0.07       0  6013.1    0.12       0
  6677.4    0.16       0
Bank Sta=4851.2,6729.9
Exp/Cntr=0.3,0.1

Type RM Length L Ch R = 1,26661,697,697,697
BEGIN DESCRIPTION:
double DRY CREEK 21.0
END DESCRIPTION:
XS GIS Cut Line= 3
      2906024.96      6989575.00      2905125.00      6989675.00
      2903024.97      6990825.02
#Sta/Elev= 30
  4092.4  406.39  4172.9  392.40  4263.4  365.00  4354.0  356.36  4539.5  349.70
  4967.7  347.11  4977.8  346.04  4981.0  340.76  4986.2  339.86  5009.8  340.76
  5011.7  346.07  5020.7  346.83  5499.6  344.82  5925.7  346.69  5978.4  344.28
  6075.8  346.35  6103.3  346.43  6160.8  346.93  6176.1  350.51  6192.2  346.47
  6273.7  345.60  6676.7  348.32  6692.8  346.58  6720.4  348.72  6752.6  346.79
  6886.3  349.70  6978.3  352.17  7074.0  356.49  7289.6  391.48  7392.2  393.69
#Mann=6,-1,0
  4092.4    0.12       0  4981.0    0.07       0  5009.8    0.12       0
  6075.8    0.07       0  6103.3    0.12       0  6978.3    0.16       0
Bank Sta=4539.5,6886.3
Exp/Cntr=0.3,0.1

Type RM Length L Ch R = 1,25964,826,826,826
BEGIN DESCRIPTION:
double Mapping XS 9ab015b3
END DESCRIPTION:
XS GIS Cut Line= 4
      2906049.21      6988954.83      2905127.30      6989053.79
      2904267.92      6989376.71      2902945.02      6990355.86
#Sta/Elev= 30
  3743.2  392.10  3761.4  390.94  3858.1  376.06  3925.9  371.88  4119.6  362.00
  4190.0  355.16  4316.6  350.65  4338.6  349.04  4372.3  347.85  4452.6  347.22
  4560.2  346.31  4708.4  345.82  4732.7  345.60  4982.7  346.06  4985.3  340.62
  4990.5  339.72  5014.1  340.62  5024.6  345.78  5036.1  346.02  5175.8  343.30
  5207.0  346.37  5388.6  343.63  5495.4  346.27  5781.9  343.80  6462.4  344.92
  6605.5  349.04  6761.2  355.98  7019.7  383.39  7170.0  392.83  7234.3  393.40
#Mann=12,-1,0
  3743.2    0.12       0  3761.4    0.16       0  3925.9    0.12       0
  4316.6    0.16       0  4372.3    0.12       0  4452.6    0.16       0
  4560.2    0.12       0  4708.4    0.16       0  4732.7    0.12       0
  4985.3    0.07       0  5014.1    0.12       0  6761.2    0.16       0
Bank Sta=4338.6,6605.5
Exp/Cntr=0.3,0.1

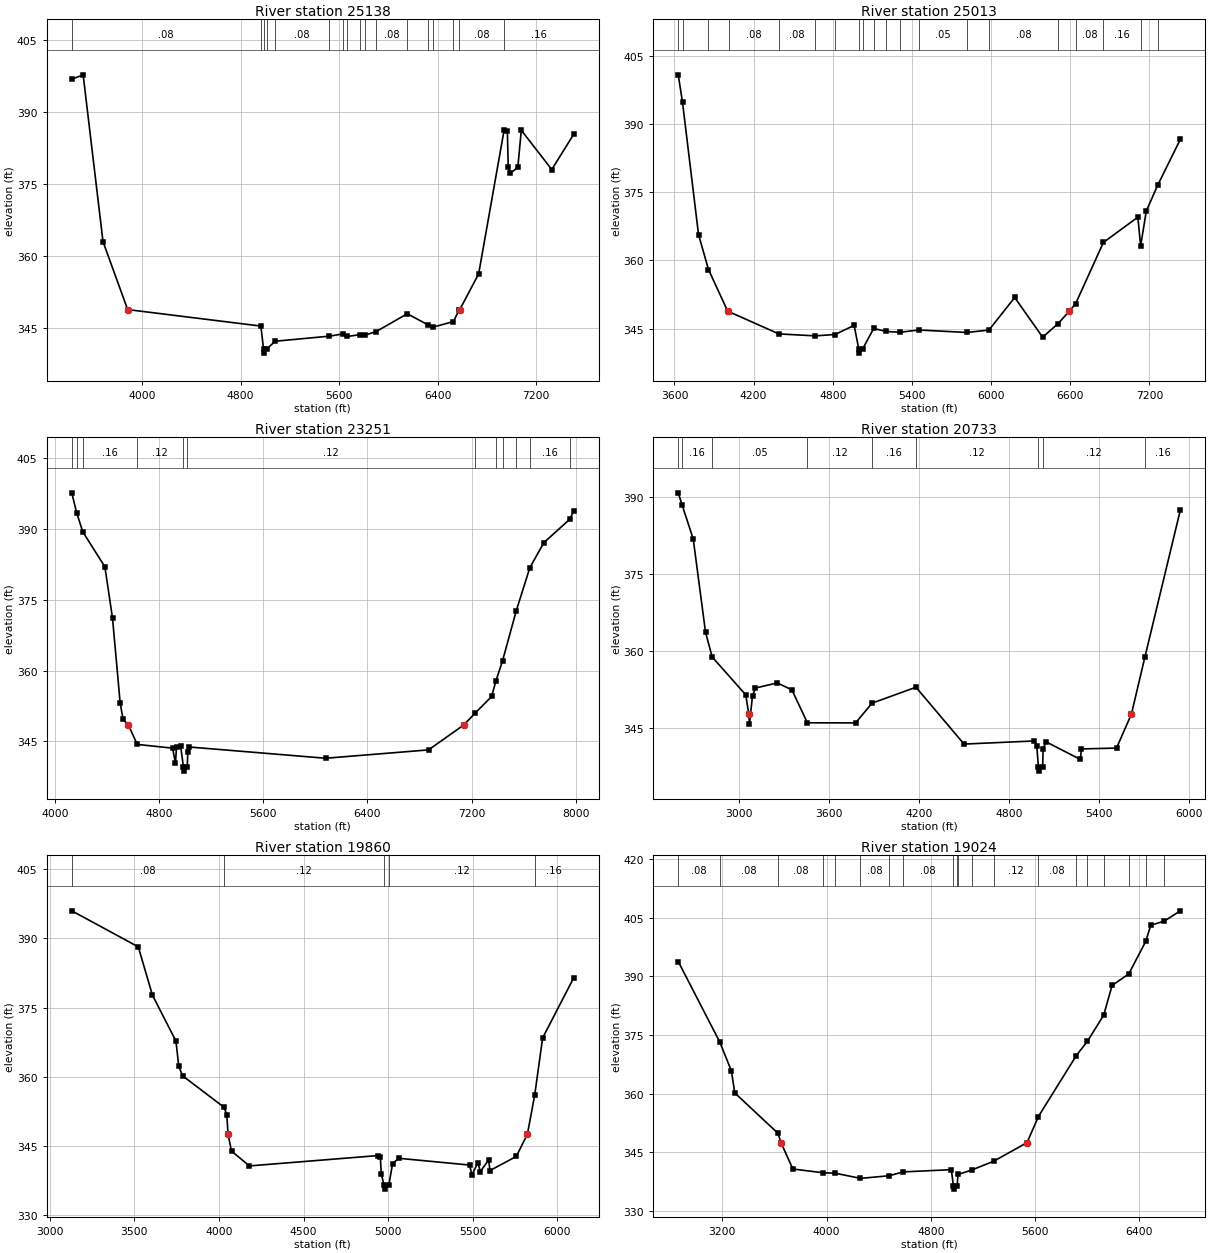
Type RM Length L Ch R = 1,25138,125,125,125
BEGIN DESCRIPTION:
double Mapping XS 94e723dc
END DESCRIPTION:
XS GIS Cut Line= 5
      2905060.90      6987272.95      2905000.13      6987811.17
      2904800.48      6988149.71      2904088.67      6988800.75
      2902552.24      6990345.87
#Sta/Elev= 30
  3428.2  396.81  3520.6  397.74  3681.9  362.97  3882.1  348.79  4964.0  345.35
  4986.0  340.61  4991.2  339.71  5014.8  340.61  5079.6  342.19  5521.5  343.25
  5630.5  343.71  5665.3  343.18  5765.4  343.55  5809.1  343.45  5900.3  344.20
  6153.5  347.92  6323.0  345.59  6360.0  345.10  6528.1  346.30  6574.6  348.70
  6580.1  348.79  6733.2  356.23  6939.9  386.19  6966.5  386.05  6973.6  378.55
  6987.7  377.17  7051.4  378.43  7079.7  386.19  7327.2  377.99  7506.5  385.39
#Mann=17,-1,0
  3428.2    0.08       0  4964.0     0.1       0  4986.0    0.07       0
  5014.8     0.1       0  5079.6    0.08       0  5521.5    0.05       0
  5630.5    0.08       0  5665.3    0.05       0  5765.4    0.12       0
  5809.1    0.05       0  5900.3    0.08       0  6153.5    0.12       0
  6323.0    0.05       0  6360.0    0.12       0  6528.1    0.05       0
  6574.6    0.08       0  6939.9    0.16       0
Bank Sta=3882.1,6580.1
Exp/Cntr=0.3,0.1

Type RM Length L Ch R = 1,25013,1762,1762,1762
BEGIN DESCRIPTION:
double Mapping XS c5587a07
END DESCRIPTION:
XS GIS Cut Line= 4
      2904843.88      6987342.43      2904765.75      6987932.70
      2904045.27      6988705.27      2902466.62      6990171.16
#Sta/Elev= 30
  3628.6  400.85  3661.1  394.77  3782.5  365.68  3857.9  357.99  4004.3  348.77
  4012.7  348.71  4391.6  343.82  4668.1  343.39  4817.0  343.69  4962.1  345.70
  4997.1  340.49  5002.3  339.59  5025.9  340.49  5110.7  345.03  5203.6  344.36
  5310.2  344.18  5450.5  344.68  5817.4  344.14  5984.3  344.67  6179.2  351.84
  6391.3  343.09  6508.0  346.09  6592.0  348.77  6641.1  350.47  6851.7  363.96
  7113.0  369.52  7133.8  363.17  7177.0  370.89  7262.9  376.54  7434.7  386.63
#Mann=20,-1,0
  3628.6    0.08       0  3661.1    0.12       0  3857.9    0.05       0
  4012.7    0.08       0  4391.6    0.08       0  4668.1    0.12       0
  4817.0    0.12       0  4997.1    0.07       0  5025.9    0.12       0
  5110.7    0.08       0  5203.6    0.12       0  5310.2    0.05       0
  5450.5    0.05       0  5817.4    0.12       0  5984.3    0.08       0
  6508.0    0.16       0  6641.1    0.08       0  6851.7    0.16       0
  7133.8    0.08       0  7262.9    0.16       0
Bank Sta=4004.3,6592
Exp/Cntr=0.3,0.1

Type RM Length L Ch R = 1,23251,2518,2518,2518
BEGIN DESCRIPTION:
double DRY CREEK 18.0
END DESCRIPTION:
XS GIS Cut Line= 3
      2904225.00      6987125.00      2903425.00      6987525.00
      2902324.99      6990275.03
#Sta/Elev= 30
  4129.6  397.67  4166.9  393.48  4214.2  389.40  4383.9  382.00  4442.6  371.11
  4501.3  353.12  4523.7  349.68  4564.4  348.48  4632.3  344.35  4903.8  343.56
  4926.2  340.42  4934.6  343.86  4965.3  344.07  4987.3  339.59  4992.5  338.69
  5016.1  339.59  5021.2  342.71  5033.4  343.80  6079.5  341.42  6869.8  343.19
  7141.1  348.48  7229.9  351.05  7354.5  354.51  7387.2  357.79  7438.8  362.13
  7543.2  372.63  7647.6  381.79  7755.6  387.11  7953.3  392.04  7985.9  393.82
#Mann=12,-1,0
  4129.6    0.08       0  4166.9    0.05       0  4214.2    0.16       0
  4632.3    0.12       0  4987.3    0.07       0  5016.1    0.12       0
  7229.9    0.16       0  7387.2    0.12       0  7438.8    0.16       0
  7543.2    0.12       0  7647.6    0.16       0  7953.3    0.12       0
Bank Sta=4564.4,7141.1
Exp/Cntr=0.3,0.1

Type RM Length L Ch R = 1,20733,873,873,873
BEGIN DESCRIPTION:
double DRY CREEK 17.0
END DESCRIPTION:
XS GIS Cut Line= 3
      2904024.98      6986875.00      2901625.00      6987225.00
      2900925.01      6987824.99
#Sta/Elev= 30
  2596.3  390.81  2621.9  388.47  2696.3  381.82  2778.2  363.70  2822.7  358.88
  3046.3  351.52  3066.9  347.76  3071.2  345.87  3091.5  351.35  3111.3  352.84
  3256.4  353.84  3354.2  352.48  3457.4  346.08  3778.7  346.06  3888.5  349.90
  4181.3  353.00  4501.6  341.94  4971.1  342.55  4986.7  341.60  4997.2  337.58
  5002.4  336.68  5026.0  337.58  5028.8  341.07  5049.7  342.36  5276.8  338.96
  5284.5  341.00  5518.3  341.16  5617.5  347.76  5708.3  358.96  5943.6  387.44
#Mann=9,-1,0
  2596.3    0.08       0  2621.9    0.16       0  2822.7    0.05       0
  3457.4    0.12       0  3888.5    0.16       0  4181.3    0.12       0
  4997.2    0.07       0  5026.0    0.12       0  5708.3    0.16       0
Bank Sta=3066.9,5617.5
Exp/Cntr=0.3,0.1

Type RM Length L Ch R = 1,19860,836,836,836
BEGIN DESCRIPTION:
double DRY CREEK 16.0
END DESCRIPTION:
XS GIS Cut Line= 3
      2903423.95      6986113.96      2901725.00      6986975.00
      2900925.00      6987675.00
#Sta/Elev= 30
  3130.2  396.00  3523.3  388.18  3606.8  377.71  3746.0  367.70  3762.7  362.24
  3785.0  360.17  4029.8  353.35  4046.6  351.74  4053.8  347.49  4074.5  343.82
  4180.2  340.60  4937.5  342.84  4954.1  342.63  4959.7  338.89  4975.6  336.46
  4980.8  335.56  5004.4  336.46  5026.6  341.11  5062.9  342.26  5481.4  340.79
  5495.7  338.65  5530.8  341.32  5545.0  339.37  5594.4  341.90  5602.0  339.59
  5757.6  342.66  5823.3  347.49  5866.6  355.98  5913.3  368.39  6097.9  381.51
#Mann=5,-1,0
  3130.2    0.08       0  4029.8    0.12       0  4975.6    0.07       0
  5004.4    0.12       0  5866.6    0.16       0
Bank Sta=4053.8,5823.3
Exp/Cntr=0.3,0.1

Type RM Length L Ch R = 1,19024,193,193,193
BEGIN DESCRIPTION:
Mapping XS b0314528
END DESCRIPTION:
XS GIS Cut Line= 4
      2903267.70      6986148.68      2902226.05      6986504.58
      2901366.68      6986756.31      2899665.31      6987502.83
#Sta/Elev= 30
  2861.6  393.84  3180.9  373.16  3269.5  365.81  3295.6  360.15  3627.7  349.79
  3650.2  347.41  3741.6  340.65  3972.3  339.69  4066.6  339.57  4260.4  338.25
  4482.2  338.92  4586.1  339.90  4958.0  340.48  4973.8  336.39  4979.1  335.49
  5002.9  336.39  5009.1  339.24  5118.3  340.44  5282.4  342.63  5539.2  347.41
  5626.3  354.09  5915.8  369.65  6003.2  373.41  6127.6  380.09  6192.0  387.69
  6320.2  390.66  6451.3  399.06  6488.5  403.12  6593.9  404.21  6715.8  406.83
#Mann=20,-1,0
  2861.6    0.08       0  3180.9    0.08       0  3627.7    0.08       0
  3972.3    0.05       0  4066.6    0.08       0  4260.4    0.08       0
  4482.2    0.05       0  4586.1    0.08       0  4973.8    0.07       0
  5002.9    0.08       0  5009.1    0.12       0  5118.3    0.08       0
  5282.4    0.12       0  5626.3    0.08       0  5915.8    0.05       0
  6003.2    0.08       0  6127.6     0.1       0  6320.2    0.08       0
  6451.3    0.16       0  6593.9    0.05       0
Bank Sta=3650.2,5539.2
Exp/Cntr=0.3,0.1

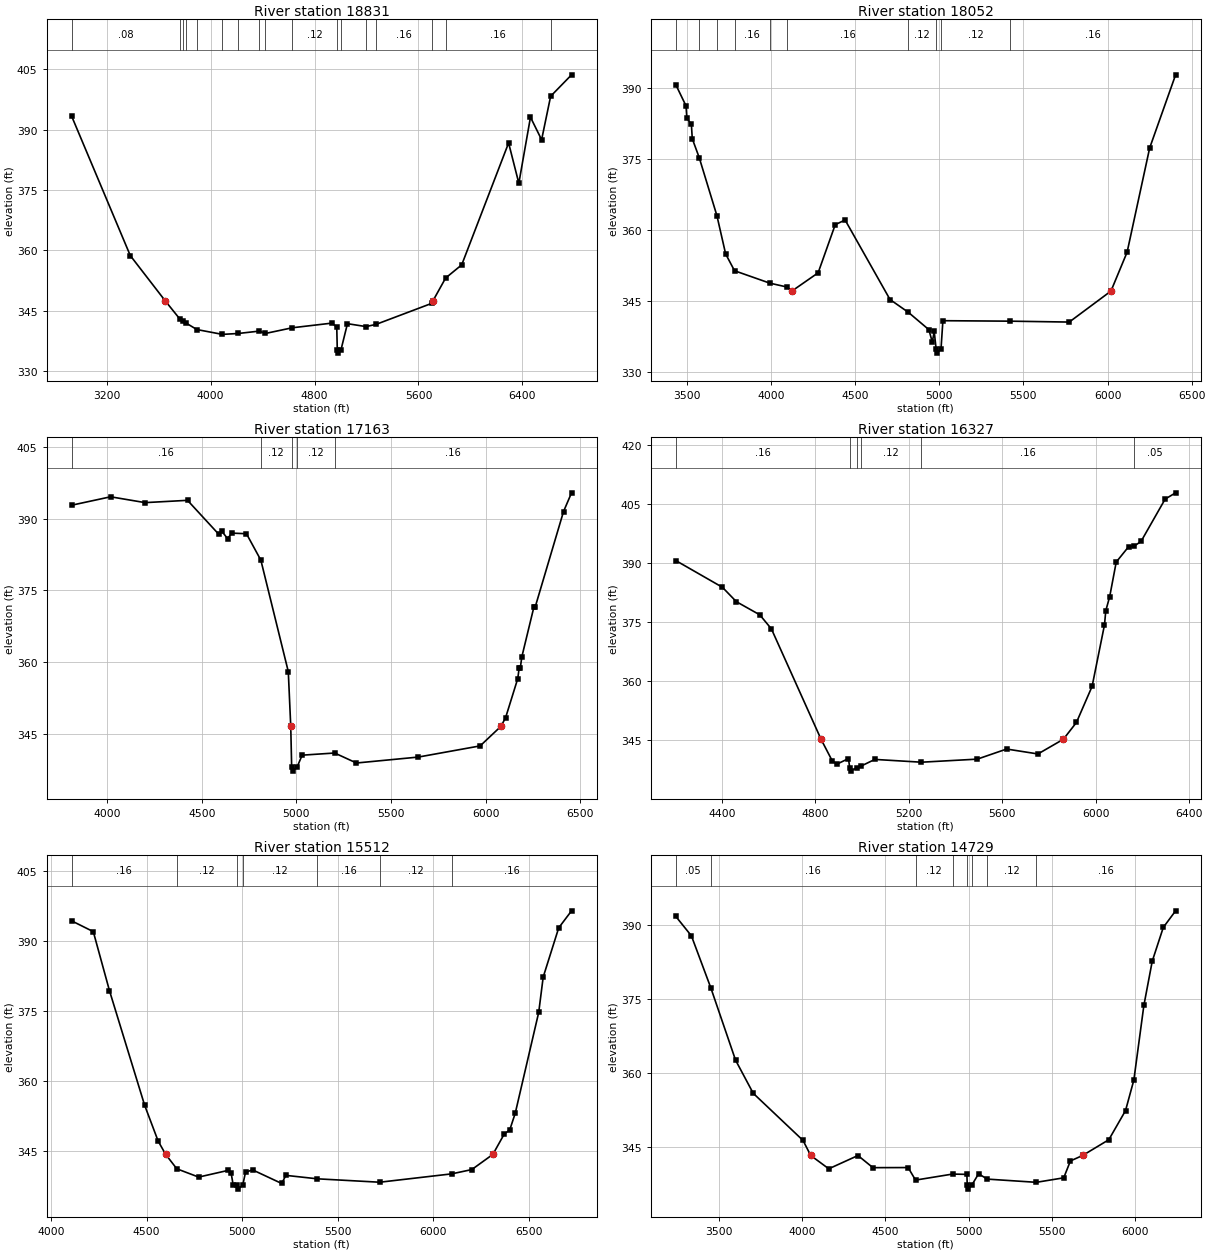
Type RM Length L Ch R = 1,18831,779,779,779
BEGIN DESCRIPTION:
Mapping XS ef47308a
END DESCRIPTION:
XS GIS Cut Line= 3
      2903241.71      6985957.69      2901314.59      6986617.42
      2899630.52      6987277.16
#Sta/Elev= 30
  2931.8  393.32  3382.8  358.68  3652.5  347.39  3766.0  342.83  3789.7  342.39
  3808.5  341.97  3895.2  340.29  4091.4  339.09  4211.7  339.31  4374.2  339.90
  4422.7  339.32  4628.3  340.73  4936.6  341.90  4971.2  340.85  4975.2  335.33
  4980.5  334.43  5004.3  335.33  5053.4  341.75  5196.1  341.03  5272.0  341.56
  5702.5  346.81  5710.5  347.39  5808.7  353.10  5932.4  356.37  6293.2  386.68
  6371.9  376.65  6461.4  393.08  6547.1  387.47  6616.5  398.28  6777.4  403.61
#Mann=17,-1,0
  2931.8    0.08       0  3766.0    0.16       0  3789.7    0.05       0
  3808.5    0.08       0  3895.2    0.16       0  4091.4    0.08       0
  4211.7    0.16       0  4374.2    0.08       0  4422.7    0.16       0
  4628.3    0.12       0  4975.2    0.07       0  5004.3    0.12       0
  5196.1    0.05       0  5272.0    0.16       0  5702.5    0.08       0
  5808.7    0.16       0  6616.5    0.08       0
Bank Sta=3652.5,5710.5
Exp/Cntr=0.3,0.1

Type RM Length L Ch R = 1,18052,889,889,889
BEGIN DESCRIPTION:
DRY CREEK 14.0
END DESCRIPTION:
XS GIS Cut Line= 3
      2902677.41      6985541.05      2901175.00      6986025.00
      2899874.97      6986525.01
#Sta/Elev= 30
  3433.4  390.79  3494.5  386.29  3499.7  383.68  3526.5  382.36  3531.8  379.35
  3573.3  375.33  3678.2  363.10  3730.1  355.01  3783.0  351.46  3992.6  348.84
  4095.0  348.02  4123.9  347.17  4279.8  351.02  4381.5  361.19  4440.2  362.18
  4707.2  345.38  4816.5  342.67  4938.3  339.01  4958.5  336.38  4969.8  338.64
  4981.2  334.96  4986.5  334.06  5010.3  334.96  5021.5  340.91  5421.1  340.81
  5772.5  340.62  6020.5  347.17  6116.5  355.39  6250.4  377.38  6404.7  392.84
#Mann=10,-1,0
  3433.4    0.08       0  3573.3    0.16       0  3678.2    0.08       0
  3783.0    0.16       0  3992.6    0.05       0  4095.0    0.16       0
  4816.5    0.12       0  4981.2    0.07       0  5010.3    0.12       0
  5421.1    0.16       0
Bank Sta=4123.9,6020.5
Exp/Cntr=0.3,0.1

Type RM Length L Ch R = 1,17163,836,836,836
BEGIN DESCRIPTION:
DRY CREEK 13.0
END DESCRIPTION:
XS GIS Cut Line= 3
      2901849.96      6984950.02      2900725.00      6985425.00
      2899825.00      6986525.00
#Sta/Elev= 30
  3812.1  392.82  4018.0  394.58  4200.3  393.36  4424.5  393.84  4588.5  386.79
  4606.7  387.33  4635.9  385.85  4659.6  386.98  4736.1  386.85  4812.2  381.32
  4957.2  358.01  4970.2  346.54  4975.0  338.08  4980.2  337.18  5004.1  338.08
  5030.5  340.52  5202.4  340.97  5317.5  338.88  5644.1  340.12  5971.4  342.46
  6080.9  346.54  6105.6  348.33  6170.2  356.55  6177.4  358.69  6183.9  358.86
  6191.8  361.11  6255.7  371.55  6262.1  371.49  6412.1  391.50  6454.5  395.41
#Mann=5,-1,0
  3812.1    0.16       0  4812.2    0.12       0  4975.0    0.07       0
  5004.1    0.12       0  5202.4    0.16       0
Bank Sta=4970.2,6080.9
Exp/Cntr=0.3,0.1

Type RM Length L Ch R = 1,16327,815,815,815
BEGIN DESCRIPTION:
DRY CREEK 12.0
END DESCRIPTION:
XS GIS Cut Line= 3
      2901025.02      6985075.00      2900225.00      6985075.00
      2899024.97      6985675.02
#Sta/Elev= 30
  4201.2  390.72  4401.2  383.91  4461.2  380.24  4561.2  376.91  4611.2  373.32
  4823.9  345.24  4871.2  339.82  4891.2  338.90  4941.2  340.33  4946.7  338.04
  4951.9  337.14  4975.8  338.04  4995.7  338.44  5054.3  340.12  5253.8  339.41
  5493.2  340.19  5618.9  342.76  5753.1  341.51  5861.9  345.24  5918.0  349.52
  5985.1  358.70  6038.2  374.35  6043.8  377.96  6060.6  381.56  6088.5  390.33
  6141.6  394.24  6164.9  394.37  6194.7  395.57  6298.1  406.35  6342.9  407.94
#Mann=6,-1,0
  4201.2    0.16       0  4946.7    0.07       0  4975.8    0.16       0
  4995.7    0.12       0  5253.8    0.16       0  6164.9    0.05       0
Bank Sta=4823.9,5861.9
Exp/Cntr=0.3,0.1

Type RM Length L Ch R = 1,15512,783,783,783
BEGIN DESCRIPTION:
DRY CREEK 11.0
END DESCRIPTION:
XS GIS Cut Line= 3
      2901175.02      6984925.02      2900575.00      6984325.00
      2898953.45      6985028.90
#Sta/Elev= 30
  4108.2  394.32  4221.4  392.01  4306.2  379.34  4490.1  354.80  4560.8  347.12
  4600.1  344.27  4658.4  341.18  4772.9  339.40  4928.5  340.85  4942.6  340.31
  4953.2  337.79  4974.7  337.72  4979.9  336.82  5003.8  337.72  5018.1  340.43
  5054.9  340.95  5207.5  338.03  5229.3  339.77  5394.0  339.03  5720.3  338.30
  6096.8  340.09  6202.4  341.01  6312.8  344.27  6372.1  348.62  6401.0  349.51
  6429.9  353.10  6552.7  374.72  6576.1  382.27  6657.4  392.83  6724.5  396.47
#Mann=7,-1,0
  4108.2    0.16       0  4658.4    0.12       0  4974.7    0.07       0
  5003.8    0.12       0  5394.0    0.16       0  5720.3    0.12       0
  6096.8    0.16       0
Bank Sta=4600.1,6312.8
Exp/Cntr=0.3,0.1

Type RM Length L Ch R = 1,14729,1198,1198,1198
BEGIN DESCRIPTION:
DRY CREEK 10.0
END DESCRIPTION:
XS GIS Cut Line= 3
      2902026.38      6984247.63      2900533.34      6983874.37
      2899075.00      6983975.00
#Sta/Elev= 30
  3241.6  391.81  3335.8  387.85  3452.1  377.33  3600.8  362.66  3706.9  355.94
  4005.8  346.39  4052.0  343.34  4160.4  340.64  4335.6  343.33  4425.4  340.87
  4636.7  340.89  4681.2  338.35  4903.2  339.57  4989.4  339.51  4991.5  337.42
  4996.8  336.52  5020.6  337.42  5059.6  339.63  5111.9  338.55  5406.4  337.90
  5570.8  338.81  5610.9  342.23  5684.2  343.34  5841.4  346.53  5941.7  352.43
  5991.8  358.64  6051.9  373.75  6102.1  382.71  6168.5  389.56  6242.4  392.92
#Mann=8,-1,0
  3241.6    0.05       0  3452.1    0.16       0  4681.2    0.12       0
  4903.2    0.16       0  4991.5    0.07       0  5020.6    0.16       0
  5111.9    0.12       0  5406.4    0.16       0
Bank Sta=4052,5684.2
Exp/Cntr=0.3,0.1

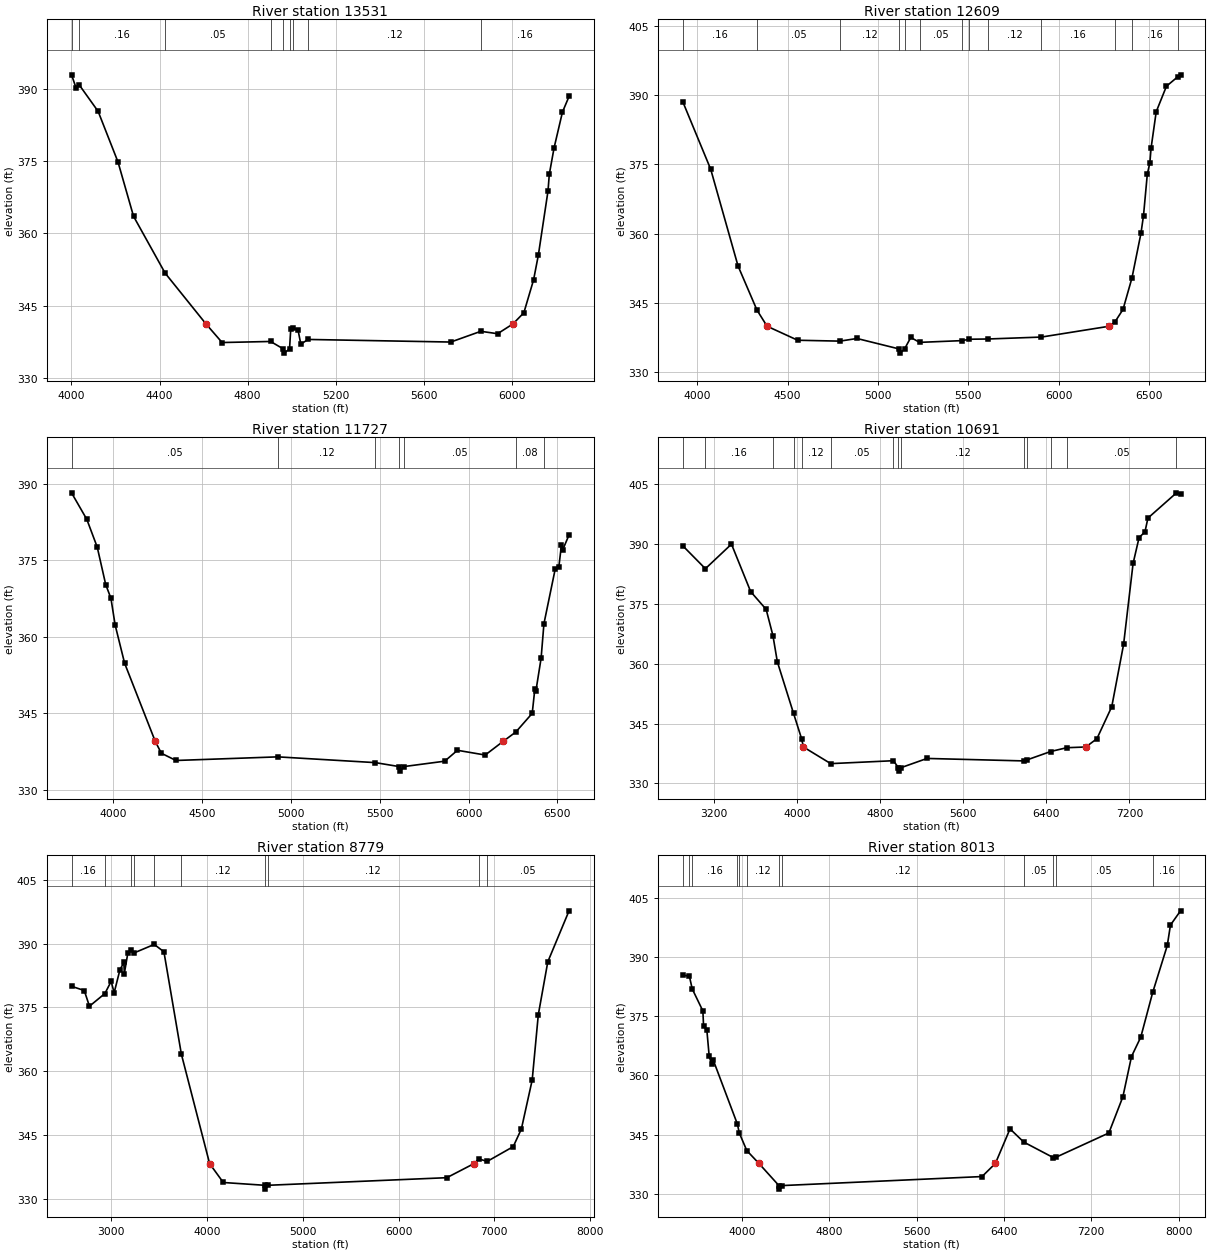
Type RM Length L Ch R = 1,13531,922,922,922
BEGIN DESCRIPTION:
DRY CREEK 9.0
END DESCRIPTION:
XS GIS Cut Line= 3
      2901224.99      6982925.00      2900225.00      6983025.00
      2899124.98      6983625.01
#Sta/Elev= 30
  4000.7  392.91  4020.8  390.25  4035.3  390.84  4121.3  385.33  4211.7  374.80
  4282.1  363.54  4425.4  351.75  4610.7  341.21  4684.1  337.34  4904.1  337.56
  4960.9  336.04  4966.2  335.14  4990.1  336.04  4995.6  340.10  5003.8  340.43
  5028.5  339.98  5041.3  337.01  5074.4  337.98  5721.9  337.44  5858.3  339.67
  5934.5  339.17  6004.3  341.21  6053.6  343.52  6097.8  350.36  6119.6  355.54
  6163.3  368.83  6169.0  372.24  6190.8  377.76  6228.8  385.18  6258.7  388.43
#Mann=9,-1,0
  4000.7    0.05       0  4035.3    0.16       0  4425.4    0.05       0
  4904.1    0.08       0  4960.9    0.07       0  4990.1    0.08       0
  5003.8    0.05       0  5074.4    0.12       0  5858.3    0.16       0
Bank Sta=4610.7,6004.3
Exp/Cntr=0.3,0.1

Type RM Length L Ch R = 1,12609,882,882,882
BEGIN DESCRIPTION:
DRY CREEK 8.0
END DESCRIPTION:
XS GIS Cut Line= 3
      2901175.03      6982875.01      2900275.00      6982475.00
      2898975.00      6983675.00
#Sta/Elev= 30
  3921.4  388.46  4074.6  373.96  4225.8  353.02  4330.7  343.45  4386.6  339.96
  4556.1  336.92  4789.7  336.73  4884.4  337.30  5118.3  335.03  5123.6  334.13
  5147.5  335.03  5182.2  337.52  5231.0  336.46  5466.8  336.84  5506.4  337.14
  5607.5  337.19  5905.4  337.61  6281.5  339.96  6311.1  340.82  6357.1  343.60
  6406.5  350.41  6456.3  360.07  6470.5  363.94  6491.5  372.89  6505.7  375.39
  6512.5  378.59  6540.8  386.42  6597.5  391.95  6661.1  394.03  6675.5  394.42
#Mann=13,-1,0
  3921.4    0.16       0  4330.7    0.05       0  4789.7    0.12       0
  5118.3    0.07       0  5147.5    0.12       0  5231.0    0.05       0
  5466.8     0.1       0  5506.4    0.05       0  5607.5    0.12       0
  5905.4    0.16       0  6311.1    0.12       0  6406.5    0.16       0
  6661.1    0.05       0
Bank Sta=4386.6,6281.5
Exp/Cntr=0.3,0.1

Type RM Length L Ch R = 1,11727,1036,1036,1036
BEGIN DESCRIPTION:
DRY CREEK 7.0
END DESCRIPTION:
XS GIS Cut Line= 3
      2901325.01      6982325.01      2900125.00      6981825.00
      2898925.01      6982724.99
#Sta/Elev= 30
  3765.0  388.26  3851.1  383.04  3909.6  377.60  3957.3  370.25  3986.6  367.57
  4010.4  362.31  4063.5  354.83  4235.9  339.49  4270.4  337.14  4352.7  335.72
  4925.9  336.43  5474.7  335.30  5607.7  334.53  5613.0  333.63  5636.9  334.53
  5865.0  335.58  5936.9  337.72  6093.1  336.79  6194.8  339.49  6265.5  341.31
  6357.7  344.97  6372.3  349.69  6378.6  349.40  6407.7  355.78  6423.7  362.57
  6486.9  373.26  6507.7  373.75  6522.3  378.04  6528.6  377.01  6565.0  380.00
#Mann=7,-1,0
  3765.0    0.05       0  4925.9    0.12       0  5474.7    0.05       0
  5607.7    0.07       0  5636.9    0.05       0  6265.5    0.08       0
  6423.7    0.16       0
Bank Sta=4235.9,6194.8
Exp/Cntr=0.3,0.1

Type RM Length L Ch R = 1,10691,1912,1912,1912
BEGIN DESCRIPTION:
DRY CREEK 6.0
END DESCRIPTION:
XS GIS Cut Line= 3
      2902252.10      6981695.55      2899925.70      6981235.48
      2898024.98      6982725.02
#Sta/Elev= 30
  2905.7  389.52  3120.7  383.84  3371.7  390.00  3556.5  378.09  3705.2  373.65
  3770.5  367.08  3812.8  360.52  3968.9  347.57  4045.7  341.27  4063.7  339.15
  4326.5  334.98  4929.5  335.71  4977.1  334.00  4982.4  333.10  5006.3  334.00
  5253.1  336.28  6182.1  335.66  6211.1  335.88  6442.9  338.02  6596.9  338.97
  6780.7  339.15  6887.3  341.22  7030.2  349.24  7144.1  364.87  7235.4  385.15
  7293.3  391.66  7349.4  393.05  7378.3  396.53  7653.0  402.86  7692.0  402.66
#Mann=14,-1,0
  2905.7    0.05       0  3120.7    0.16       0  3770.5    0.05       0
  3968.9    0.16       0  4045.7    0.12       0  4326.5    0.05       0
  4929.5    0.12       0  4977.1    0.07       0  5006.3    0.12       0
  6182.1    0.16       0  6211.1    0.12       0  6442.9    0.16       0
  6596.9    0.05       0  7653.0    0.16       0
Bank Sta=4063.7,6780.7
Exp/Cntr=0.3,0.1

Type RM Length L Ch R = 1,8779,766,766,766
BEGIN DESCRIPTION:
Mapping XS 48b75bbc
END DESCRIPTION:
XS GIS Cut Line= 3
      2902356.27      6979907.35      2900160.08      6980454.23
      2898129.42      6982563.00
#Sta/Elev= 30
  2588.2  379.98  2720.8  378.99  2775.0  375.30  2935.5  378.26  3001.7  381.14
  3032.6  378.45  3092.6  383.82  3133.9  385.63  3139.0  382.98  3175.2  387.76
  3208.3  388.57  3235.4  387.78  3451.1  389.83  3552.0  388.10  3734.0  364.03
  4029.0  338.27  4171.6  333.84  4605.1  333.18  4610.4  332.28  4634.3  333.18
  6503.6  334.97  6786.4  338.27  6840.3  339.37  6925.0  338.80  7196.6  342.27
  7281.5  346.41  7394.5  357.94  7458.3  373.30  7557.3  385.74  7779.0  397.73
#Mann=10,-1,0
  2588.2    0.16       0  2935.5    0.12       0  3208.3    0.16       0
  3235.4    0.12       0  3451.1    0.16       0  3734.0    0.12       0
  4605.1    0.07       0  4634.3    0.12       0  6840.3    0.16       0
  6925.0    0.05       0
Bank Sta=4029,6786.4
Exp/Cntr=0.3,0.1

Type RM Length L Ch R = 1,8013,632,632,632
BEGIN DESCRIPTION:
DRY CREEK 5.0
END DESCRIPTION:
XS GIS Cut Line= 3
      2901125.02      6979374.99      2899825.00      6980175.00
      2897975.01      6982574.98
#Sta/Elev= 30
  3461.2  385.42  3519.3  385.15  3545.3  381.93  3642.9  376.34  3649.1  372.61
  3679.5  371.43  3700.8  364.85  3722.1  362.84  3737.5  363.90  3958.4  347.69
  3976.7  345.38  4045.3  340.92  4156.5  337.66  4339.4  332.05  4344.7  331.15
  4368.6  332.05  6199.8  334.34  6322.0  337.66  6456.1  346.43  6581.5  343.09
  6854.3  339.12  6873.2  339.19  7361.4  345.39  7489.8  354.57  7568.6  364.77
  7653.7  369.70  7762.7  381.02  7896.5  392.94  7925.5  398.12  8017.9  401.73
#Mann=12,-1,0
  3461.2    0.16       0  3519.3    0.12       0  3545.3    0.16       0
  3958.4    0.12       0  3976.7    0.16       0  4045.3    0.12       0
  4339.4    0.07       0  4368.6    0.12       0  6581.5    0.05       0
  6854.3    0.16       0  6873.2    0.05       0  7762.7    0.16       0
Bank Sta=4156.5,6322
Exp/Cntr=0.3,0.1

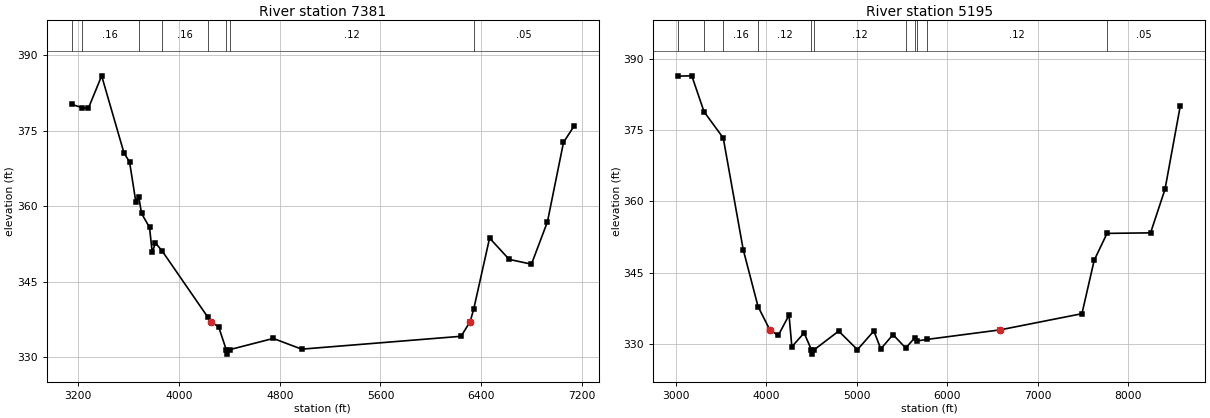
Type RM Length L Ch R = 1,7381,2186,2186,2186
BEGIN DESCRIPTION:
Mapping XS 4cd80cd4
END DESCRIPTION:
XS GIS Cut Line= 3
      2901349.36      6979134.77      2899726.05      6979690.34
      2898172.25      6981348.30
#Sta/Elev= 30
  3148.2  380.26  3229.1  379.62  3279.6  379.46  3385.6  385.94  3562.8  370.61
  3607.3  368.80  3656.7  360.93  3679.9  361.93  3702.4  358.58  3765.8  355.79
  3787.1  350.84  3813.1  352.71  3868.4  351.02  4226.9  338.01  4252.5  337.07
  4315.4  335.98  4374.8  331.49  4380.1  330.59  4404.0  331.49  4748.8  333.71
  4974.1  331.58  6240.7  334.14  6312.8  337.07  6340.9  339.56  6466.9  353.67
  6622.7  349.43  6799.5  348.48  6926.5  356.91  7054.0  372.70  7136.2  375.88
#Mann=8,-1,0
  3148.2    0.12       0  3229.1    0.16       0  3679.9    0.12       0
  3868.4    0.16       0  4226.9    0.12       0  4374.8    0.07       0
  4404.0    0.12       0  6340.9    0.05       0
Bank Sta=4252.5,6312.8
Exp/Cntr=0.3,0.1

Type RM Length L Ch R = 1,5195,0,0,0
BEGIN DESCRIPTION:
DRY CREEK 4.0
END DESCRIPTION:
XS GIS Cut Line= 4
      2901687.86      6978457.70      2900767.72      6978075.76
      2899248.62      6978605.27      2898125.00      6981325.01
#Sta/Elev= 30
  3027.1  386.35  3177.0  386.41  3312.1  378.87  3524.5  373.34  3744.8  349.89
  3909.1  337.89  4039.3  332.99  4132.4  331.83  4251.4  336.10  4282.5  329.45
  4418.1  332.34  4498.8  328.79  4504.1  327.89  4528.0  328.79  4800.2  332.74
  5007.1  328.82  5188.3  332.76  5265.3  328.99  5400.5  331.99  5540.8  329.17
  5638.9  331.29  5662.6  330.64  5778.7  330.99  6583.6  332.99  7487.7  336.39
  7623.5  347.64  7765.1  353.28  8246.1  353.39  8405.8  362.57  8574.8  380.13
#Mann=11,-1,0
  3027.1    0.16       0  3312.1    0.12       0  3524.5    0.16       0
  3909.1    0.12       0  4498.8    0.07       0  4528.0    0.12       0
  5540.8    0.05       0  5638.9    0.12       0  5662.6    0.07       0
  5778.7    0.12       0  7765.1    0.05       0
Bank Sta=4039.3,6583.6
Exp/Cntr=0.3,0.1

Chan Stop Cuts=-1