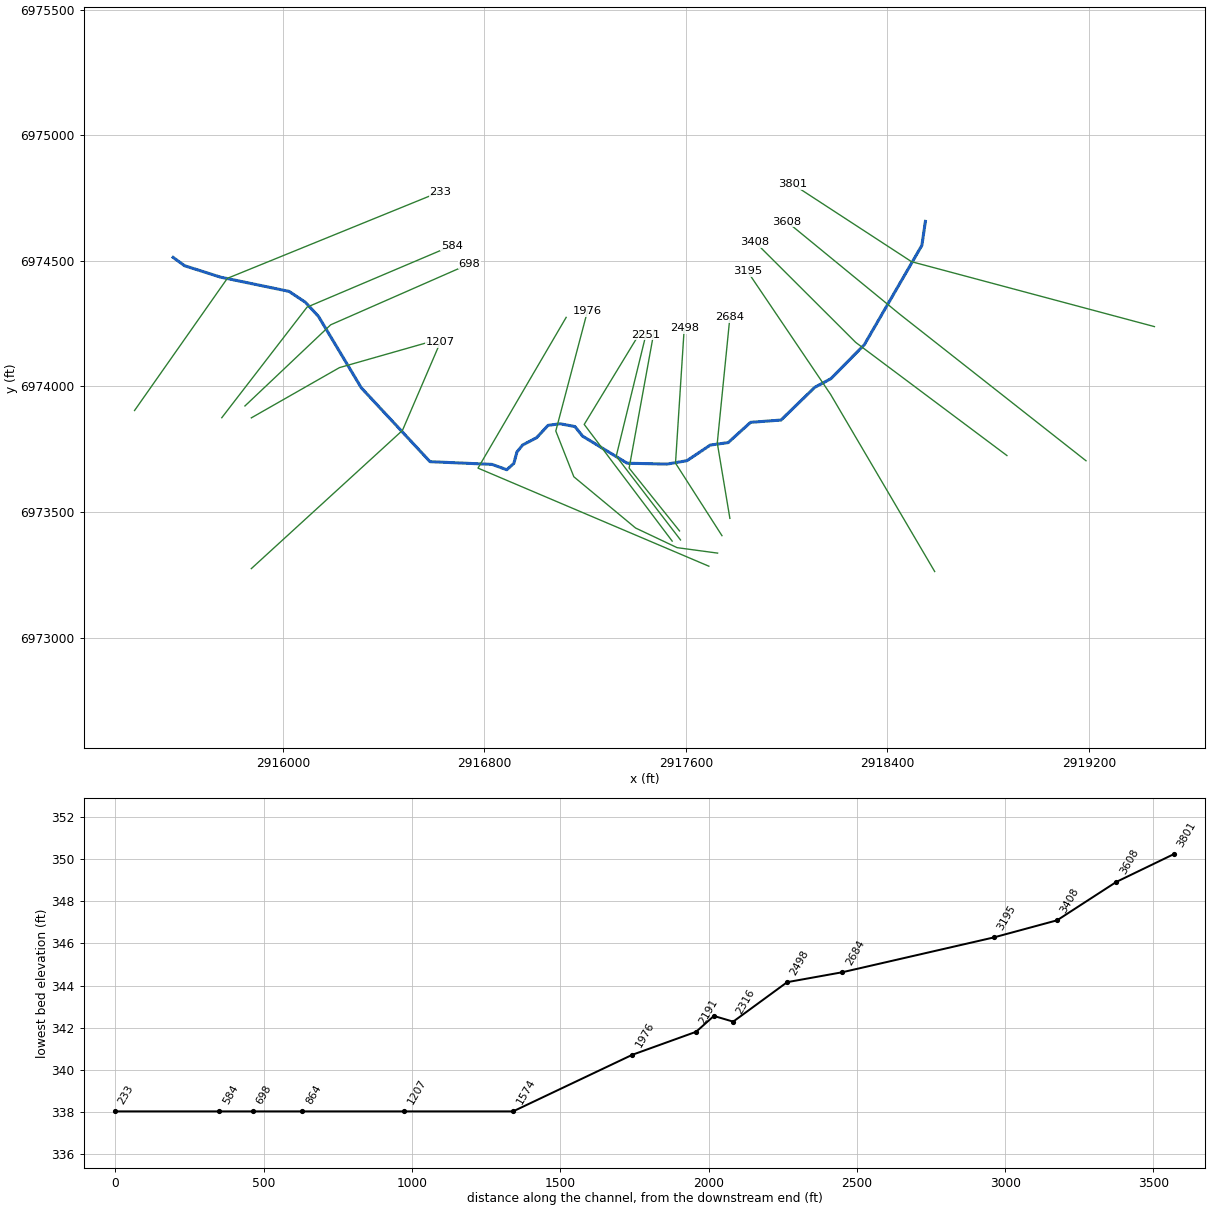
--- DUCK POND BRANCH.prj (project) ---

Proj Title=DUCK POND BRANCH Base Level Engineering
Current Plan=p01
Default Exp/Contr=0.3,0.1
English Units
Geom File=g01
Flow File=f01
Plan File=p01
BEGIN DESCRIPTION:
DUCK POND BRANCH
END DESCRIPTION:

--- DUCK POND BRANCH.p01 (plan) ---

Plan Title=Multiple Run
Short Identifier=Multiple
Geom File=g01
Flow File=f01
Subcritical Flow
K Sum by GR= 0
Std Step Tol= 0.01
Critical Tol= 0.01
Num of Std Step Trials= 20
Max Error Tol= 0.3
Flow Tol Ratio= 0.001
Split Flow NTrial= 30
Split Flow Tol= 0.02
Split Flow Ratio= 0.02
Log Output Level= 0
Friction Slope Method= 1
Unsteady Friction Slope Method= 2
Unsteady Bridges Friction Slope Method= 1
Parabolic Critical Depth
Global Vel Dist=  1 , 1 , 1
Global Log Level= 0
CheckData=True
Encroach Param= -1, 0, 0, 0
BEGIN DESCRIPTION:
Multiple Run
END DESCRIPTION:

--- DUCK POND BRANCH.f01 (steady flow) ---

Flow Title=Multiple
Number of Profiles=7
Profile Names=10-year,25-year,50-year,1pct_min,100-year,1pct_plu,500-year
River Rch & RM= DUCK POND BRANCH,Reach-1,3801
     246     315     368     216     430     858     586
River Rch & RM= DUCK POND BRANCH,Reach-1,1207
     429     571     686     412     821    1638    1176
Boundary for River Rch & Prof#=DUCK POND BRANCH,Reach-1,1
Up Type=0
Dn Type=3
Dn Slope=0.005
Boundary for River Rch & Prof#=DUCK POND BRANCH,Reach-1,2
Up Type=0
Dn Type=3
Dn Slope=0.005
Boundary for River Rch & Prof#=DUCK POND BRANCH,Reach-1,3
Up Type=0
Dn Type=3
Dn Slope=0.005
Boundary for River Rch & Prof#=DUCK POND BRANCH,Reach-1,4
Up Type=0
Dn Type=3
Dn Slope=0.005
Boundary for River Rch & Prof#=DUCK POND BRANCH,Reach-1,5
Up Type=0
Dn Type=3
Dn Slope=0.005
Boundary for River Rch & Prof#=DUCK POND BRANCH,Reach-1,6
Up Type=0
Dn Type=3
Dn Slope=0.005
Boundary for River Rch & Prof#=DUCK POND BRANCH,Reach-1,7
Up Type=0
Dn Type=3
Dn Slope=0.005

--- DUCK POND BRANCH.g01 (geometry) ---

Geom Title=Existing Conditions

River Reach=DUCK POND BRANCH,Reach-1
Reach XY= 30
      2918551.25      6974657.10      2918537.36      6974561.61
      2918308.63      6974165.85      2918176.22      6974030.98
      2918111.79      6973996.38      2917978.21      6973866.30
      2917857.08      6973857.12      2917768.09      6973776.48
      2917697.22      6973766.76      2917604.06      6973704.39
      2917525.46      6973691.02      2917367.15      6973694.48
      2917190.12      6973802.32      2917159.96      6973840.34
      2917100.59      6973851.59      2917053.18      6973845.24
      2917007.82      6973796.13      2916952.16      6973767.03
      2916929.55      6973739.09      2916917.38      6973693.96
      2916889.38      6973668.53      2916830.49      6973689.86
      2916584.45      6973700.60      2916311.48      6973994.84
      2916141.77      6974278.62      2916089.69      6974335.04
      2916024.58      6974378.44      2915753.32      6974434.87
      2915610.09      6974480.44      2915564.52      6974513.57

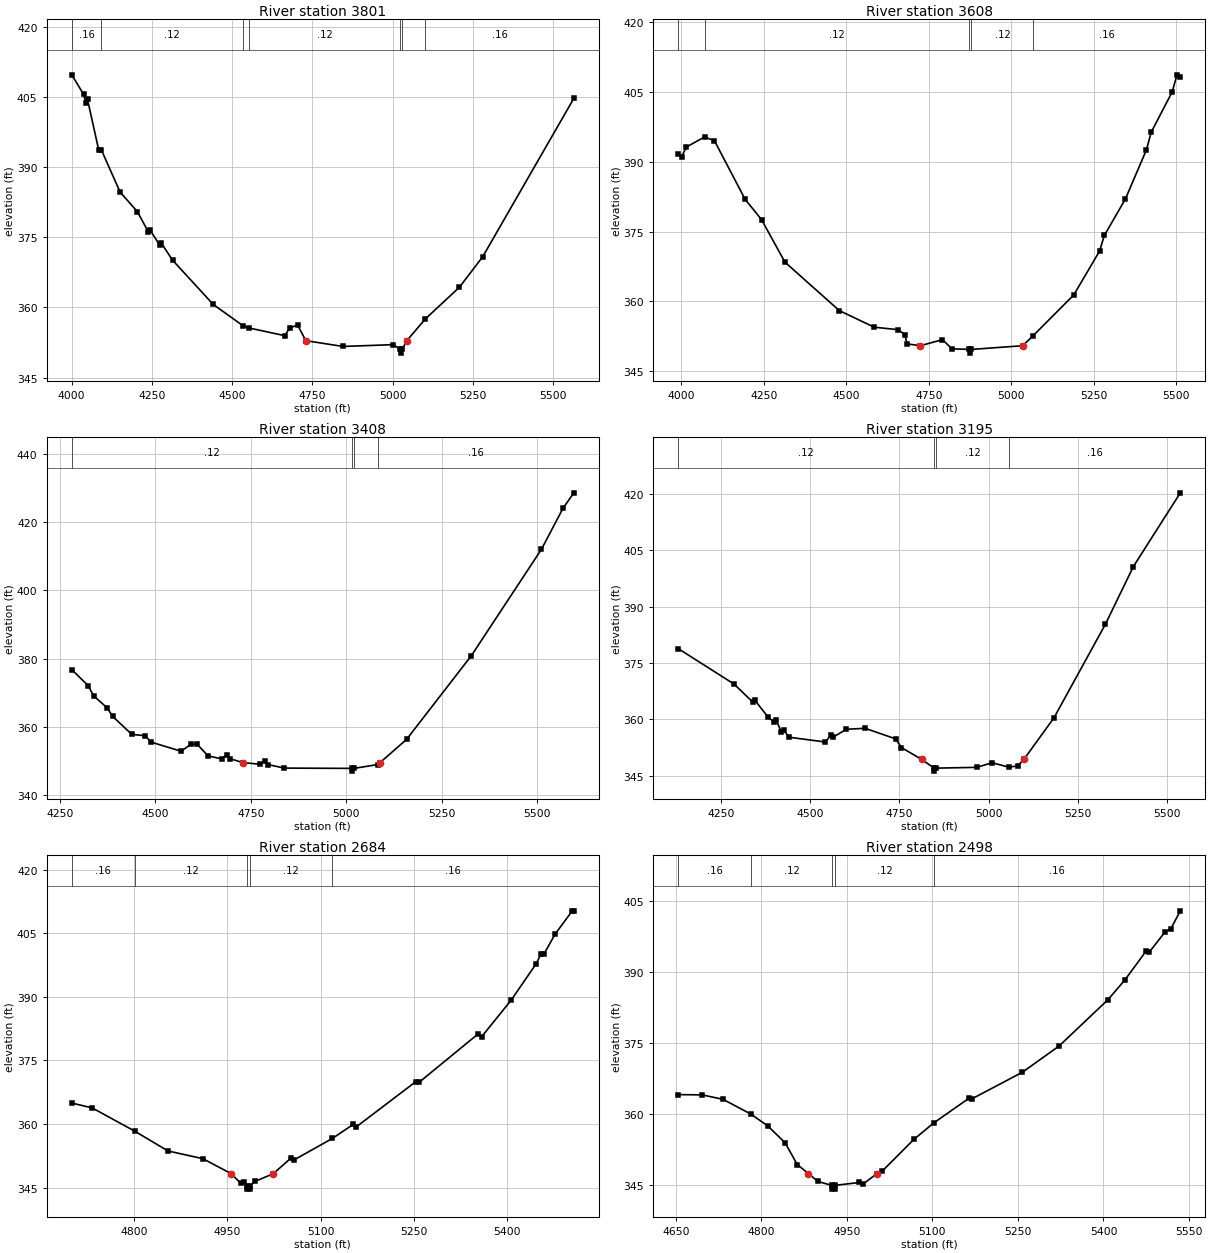
Type RM Length L Ch R = 1,3801,193,193,193
BEGIN DESCRIPTION:
DUCK POND BRANCH 10.0
END DESCRIPTION:
XS GIS Cut Line= 3
      2919460.60      6974238.17      2918496.51      6974496.51
      2918023.12      6974805.86
#Sta/Elev= 30
  4000.7  409.69  4037.6  405.51  4044.6  403.69  4049.7  404.44  4084.6  393.64
  4093.2  393.59  4151.4  384.62  4204.7  380.48  4239.5  376.09  4244.7  376.52
  4274.4  373.29  4279.5  373.73  4314.4  370.10  4441.3  360.62  4534.0  356.07
  4553.6  355.58  4664.2  353.95  4679.4  355.64  4704.2  356.20  4729.6  352.88
  4845.1  351.65  5002.0  352.03  5024.0  351.02  5024.5  350.22  5030.0  351.02
  5044.0  352.88  5101.5  357.50  5208.0  364.31  5280.4  370.81  5564.3  404.66
#Mann=7,-1,0
  4000.7    0.16       0  4093.2    0.12       0  4534.0    0.16       0
  4553.6    0.12       0  5024.0    0.07       0  5030.0    0.12       0
  5101.5    0.16       0
Bank Sta=4729.6,5044
Exp/Cntr=0.3,0.1

Type RM Length L Ch R = 1,3608,200,200,200
BEGIN DESCRIPTION:
Mapping XS 91d80d0a
END DESCRIPTION:
XS GIS Cut Line= 3
      2919188.92      6973704.29      2918449.31      6974287.65
      2918001.41      6974655.69
#Sta/Elev= 30
  3990.9  391.79  4001.2  391.11  4015.6  393.18  4070.6  395.34  4100.6  394.54
  4193.6  381.95  4243.3  377.60  4314.3  368.45  4479.0  358.05  4584.8  354.48
  4657.0  353.95  4677.8  352.91  4684.2  350.90  4724.7  350.50  4791.6  351.81
  4820.5  349.83  4873.6  349.71  4874.1  348.91  4879.6  349.71  5034.9  350.50
  5067.1  352.69  5189.7  361.41  5267.9  370.83  5282.3  374.18  5346.1  382.01
  5410.0  392.60  5424.4  396.37  5488.2  405.06  5502.6  408.69  5512.6  408.13
#Mann=5,-1,0
  3990.9    0.16       0  4070.6    0.12       0  4873.6    0.07       0
  4879.6    0.12       0  5067.1    0.16       0
Bank Sta=4724.7,5034.9
Exp/Cntr=0.3,0.1

Type RM Length L Ch R = 1,3408,213,213,213
BEGIN DESCRIPTION:
DUCK POND BRANCH 9.0
END DESCRIPTION:
XS GIS Cut Line= 3
      2918875.00      6973725.00      2918275.00      6974175.00
      2917874.99      6974575.01
#Sta/Elev= 30
  4280.7  376.82  4323.4  372.15  4338.0  369.14  4373.4  365.62  4388.0  363.11
  4438.0  357.85  4473.4  357.46  4488.0  355.60  4567.2  352.92  4594.2  355.05
  4608.8  355.01  4638.0  351.54  4673.4  350.69  4688.0  351.94  4694.2  350.77
  4728.4  349.61  4773.4  349.10  4788.0  350.02  4794.2  349.02  4838.0  347.98
  5014.2  347.89  5014.7  347.09  5020.2  347.89  5082.4  349.01  5088.8  349.61
  5158.0  356.38  5327.7  380.88  5511.5  412.06  5568.1  424.10  5596.4  428.60
#Mann=4,-1,0
  4280.7    0.12       0  5014.2    0.07       0  5020.2    0.12       0
  5082.4    0.16       0
Bank Sta=4728.4,5088.8
Exp/Cntr=0.3,0.1

Type RM Length L Ch R = 1,3195,511,511,511
BEGIN DESCRIPTION:
DUCK POND BRANCH 8.0
END DESCRIPTION:
XS GIS Cut Line= 3
      2918588.17      6973263.38      2918175.00      6973968.20
      2917845.16      6974457.76
#Sta/Elev= 30
  4130.2  378.81  4286.7  369.40  4339.5  364.58  4345.3  365.07  4382.5  360.57
  4398.1  359.36  4403.9  359.96  4419.6  356.64  4425.4  357.17  4441.1  355.28
  4542.7  354.01  4558.4  355.90  4564.2  355.29  4601.3  357.39  4653.7  357.66
  4740.1  354.83  4755.8  352.54  4812.4  349.39  4847.7  347.08  4848.2  346.28
  4853.7  347.08  4967.4  347.28  5009.7  348.51  5056.2  347.35  5081.7  347.65
  5099.0  349.39  5183.6  360.47  5327.6  385.31  5405.6  400.55  5537.5  420.19
#Mann=4,-1,0
  4130.2    0.12       0  4847.7    0.07       0  4853.7    0.12       0
  5056.2    0.16       0
Bank Sta=4812.4,5099
Exp/Cntr=0.3,0.1

Type RM Length L Ch R = 1,2684,186,186,186
BEGIN DESCRIPTION:
DUCK POND BRANCH 7.0
END DESCRIPTION:
XS GIS Cut Line= 3
      2917775.00      6973475.00      2917725.00      6973775.00
      2917775.00      6974274.97
#Sta/Elev= 30
  4700.4  364.94  4733.3  363.78  4801.2  358.33  4855.0  353.63  4910.8  351.82
  4956.8  348.26  4971.6  346.05  4976.7  346.42  4981.3  345.43  4981.8  344.63
  4986.8  344.63  4987.3  345.43  4994.4  346.43  5024.1  348.26  5052.3  351.93
  5057.3  351.50  5119.0  356.58  5152.8  359.91  5157.8  359.35  5253.3  370.00
  5258.3  369.81  5353.8  381.31  5358.8  380.56  5406.5  389.24  5446.7  397.84
  5454.3  400.14  5459.3  400.16  5476.9  404.77  5504.5  410.27  5507.0  410.27
#Mann=5,-1,0
  4700.4    0.16       0  4801.2    0.12       0  4981.3    0.07       0
  4987.3    0.12       0  5119.0    0.16       0
Bank Sta=4956.8,5024.1
Exp/Cntr=0.3,0.1

Type RM Length L Ch R = 1,2498,182,182,182
BEGIN DESCRIPTION:
Mapping XS b14823a5
END DESCRIPTION:
XS GIS Cut Line= 3
      2917743.60      6973406.11      2917559.12      6973694.76
      2917593.74      6974231.47
#Sta/Elev= 30
  4654.4  364.10  4696.4  364.04  4732.8  363.11  4782.1  359.97  4811.5  357.48
  4841.9  353.92  4863.1  349.34  4882.8  347.44  4899.4  345.77  4923.5  344.96
  4924.0  344.16  4929.0  344.16  4929.5  344.96  4972.2  345.56  4978.1  345.20
  5003.0  347.44  5011.5  347.89  5067.4  354.63  5102.4  358.12  5164.3  363.34
  5169.3  363.20  5257.8  368.81  5322.1  374.34  5408.1  384.14  5438.1  388.36
  5474.9  394.40  5479.9  394.09  5508.3  398.45  5518.3  399.10  5534.8  402.87
#Mann=5,-1,0
  4654.4    0.16       0  4782.1    0.12       0  4923.5    0.07       0
  4929.5    0.12       0  5102.4    0.16       0
Bank Sta=4882.8,5003
Exp/Cntr=0.3,0.1

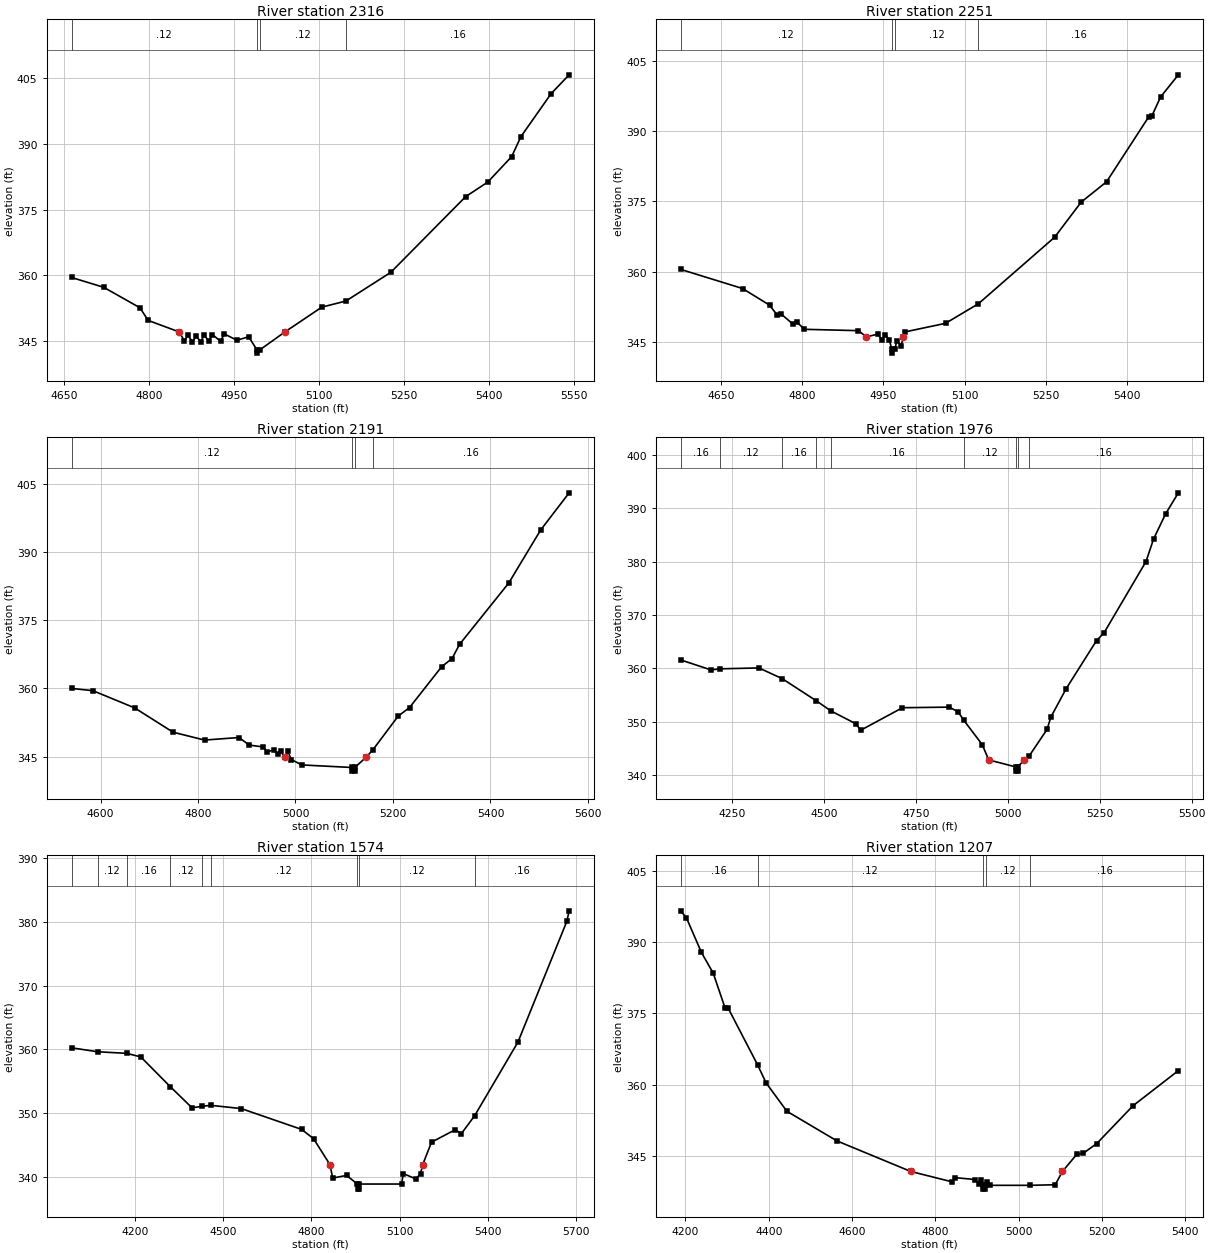
Type RM Length L Ch R = 1,2316,65,65,65
BEGIN DESCRIPTION:
DUCK POND BRANCH 6.0
END DESCRIPTION:
XS GIS Cut Line= 3
      2917575.01      6973424.99      2917375.00      6973675.00
      2917475.00      6974225.01
#Sta/Elev= 30
  4662.9  359.54  4719.7  357.30  4783.8  352.63  4798.2  349.75  4853.6  347.10
  4862.2  345.05  4868.6  346.37  4876.6  344.84  4883.0  346.18  4891.0  344.90
  4897.4  346.40  4905.4  345.00  4911.8  346.52  4926.2  344.99  4932.6  346.68
  4955.1  345.23  4975.9  346.02  4990.2  343.09  4990.7  342.29  4996.2  343.09
  5039.7  347.10  5105.0  352.77  5147.7  354.17  5227.0  360.71  5359.1  377.95
  5398.5  381.31  5440.5  387.09  5457.0  391.67  5510.3  401.46  5542.1  405.74
#Mann=4,-1,0
  4662.9    0.12       0  4990.2    0.07       0  4996.2    0.12       0
  5147.7    0.16       0
Bank Sta=4853.6,5039.7
Exp/Cntr=0.3,0.1

Type RM Length L Ch R = 1,2251,60,60,60
BEGIN DESCRIPTION:
Mapping XS e84c7aa9
END DESCRIPTION:
XS GIS Cut Line= 3
      2917578.99      6973389.11      2917323.81      6973722.41
      2917441.86      6974206.76
#Sta/Elev= 30
  4576.1  360.45  4690.1  356.37  4739.9  352.82  4754.5  350.64  4760.8  350.98
  4783.5  348.72  4789.8  349.27  4804.3  347.65  4904.1  347.36  4918.5  346.03
  4939.4  346.61  4947.6  345.41  4953.9  346.49  4961.3  345.36  4965.4  343.36
  4965.9  342.56  4971.4  343.36  4974.7  345.23  4983.0  344.18  4987.0  346.03
  4989.3  347.08  5064.8  348.93  5125.5  353.12  5266.1  367.33  5315.0  374.82
  5361.9  379.17  5440.1  393.12  5445.3  393.20  5461.7  397.31  5494.4  402.03
#Mann=4,-1,0
  4576.1    0.12       0  4965.4    0.07       0  4971.4    0.12       0
  5125.5    0.16       0
Bank Sta=4918.5,4987
Exp/Cntr=0.3,0.1

Type RM Length L Ch R = 1,2191,215,215,215
BEGIN DESCRIPTION:
DUCK POND BRANCH 5.0
END DESCRIPTION:
XS GIS Cut Line= 3
      2917545.90      6973384.48      2917196.70      6973848.84
      2917424.99      6974224.98
#Sta/Elev= 30
  4540.5  360.00  4584.3  359.50  4669.7  355.73  4748.8  350.37  4813.3  348.64
  4884.2  349.20  4905.0  347.54  4934.1  347.12  4941.5  345.98  4955.0  346.51
  4963.3  345.52  4969.5  346.24  4977.8  344.81  4984.1  346.18  4991.6  344.33
  5013.3  343.17  5115.8  342.61  5116.3  341.81  5121.3  341.81  5121.8  342.61
  5144.3  344.81  5158.1  346.40  5210.7  353.91  5234.0  355.79  5299.8  364.76
  5321.2  366.56  5336.6  369.68  5437.5  383.17  5503.0  394.83  5561.5  403.01
#Mann=4,-1,0
  4540.5    0.12       0  5115.8    0.07       0  5121.8    0.12       0
  5158.1    0.16       0
Bank Sta=4977.8,5144.3
Exp/Cntr=0.3,0.1

Type RM Length L Ch R = 1,1976,402,402,402
BEGIN DESCRIPTION:
Mapping XS f59f52a9
END DESCRIPTION:
XS GIS Cut Line= 6
      2917726.22      6973336.69      2917565.63      6973358.39
      2917400.70      6973436.52      2917155.47      6973640.51
      2917083.86      6973822.80      2917209.69      6974300.11
#Sta/Elev= 30
  4110.9  361.57  4192.9  359.70  4217.8  359.90  4323.4  360.07  4386.5  358.07
  4479.2  353.92  4519.1  352.01  4586.2  349.63  4600.5  348.40  4713.8  352.61
  4841.2  352.72  4865.2  351.83  4880.6  350.25  4930.6  345.69  4948.3  342.82
  5021.3  341.52  5021.8  340.72  5026.8  340.72  5027.3  341.52  5045.3  342.82
  5059.1  343.64  5106.9  348.55  5117.3  350.85  5158.7  356.16  5241.4  365.19
  5262.1  366.68  5375.9  380.01  5396.6  384.25  5429.3  388.97  5463.9  392.90
#Mann=9,-1,0
  4110.9    0.16       0  4217.8    0.12       0  4386.5    0.16       0
  4479.2    0.12       0  4519.1    0.16       0  4880.6    0.12       0
  5021.3    0.07       0  5027.3    0.12       0  5059.1    0.16       0
Bank Sta=4948.3,5045.3
Exp/Cntr=0.3,0.1

Type RM Length L Ch R = 1,1574,367,367,367
BEGIN DESCRIPTION:
DUCK POND BRANCH 4.0
END DESCRIPTION:
XS GIS Cut Line= 3
      2917691.47      6973284.62      2916775.00      6973675.00
      2917125.02      6974275.03
#Sta/Elev= 30
  3985.5  360.23  4074.3  359.61  4173.0  359.36  4220.8  358.80  4320.5  354.15
  4394.7  350.82  4429.2  351.04  4458.0  351.20  4561.9  350.69  4767.2  347.42
  4807.7  345.97  4863.4  341.90  4873.0  339.78  4919.9  340.19  4956.9  338.84
  4957.4  338.04  4962.4  338.04  4962.9  338.84  5106.9  338.84  5112.7  340.48
  5155.7  339.64  5171.4  340.48  5178.8  341.90  5208.6  345.41  5288.9  347.36
  5310.4  346.77  5355.1  349.56  5502.2  361.12  5668.4  380.09  5676.3  381.74
#Mann=9,-1,0
  3985.5    0.16       0  4074.3    0.12       0  4173.0    0.16       0
  4320.5    0.12       0  4429.2    0.16       0  4458.0    0.12       0
  4956.9    0.07       0  4962.9    0.12       0  5355.1    0.16       0
Bank Sta=4863.4,5178.8
Exp/Cntr=0.3,0.1

Type RM Length L Ch R = 1,1207,343,343,343
BEGIN DESCRIPTION:
DUCK POND BRANCH 3.0
END DESCRIPTION:
XS GIS Cut Line= 3
      2915875.02      6973275.02      2916475.00      6973825.00
      2916625.00      6974175.00
#Sta/Elev= 30
  4188.7  396.54  4202.5  395.04  4238.3  387.80  4266.7  383.43  4295.0  376.14
  4301.8  376.20  4373.0  364.20  4393.7  360.36  4443.6  354.40  4563.9  348.17
  4741.1  341.75  4839.8  339.58  4846.9  340.46  4896.2  340.05  4903.6  339.17
  4910.4  339.88  4914.8  338.84  4915.3  338.04  4920.3  338.04  4920.8  338.84
  4924.6  339.44  4932.0  338.84  5028.2  338.84  5087.8  338.96  5105.0  341.75
  5140.4  345.44  5154.9  345.56  5187.6  347.63  5274.6  355.57  5383.4  362.95
#Mann=5,-1,0
  4188.7    0.16       0  4373.0    0.12       0  4914.8    0.07       0
  4920.8    0.12       0  5028.2    0.16       0
Bank Sta=4741.1,5105
Exp/Cntr=0.3,0.1

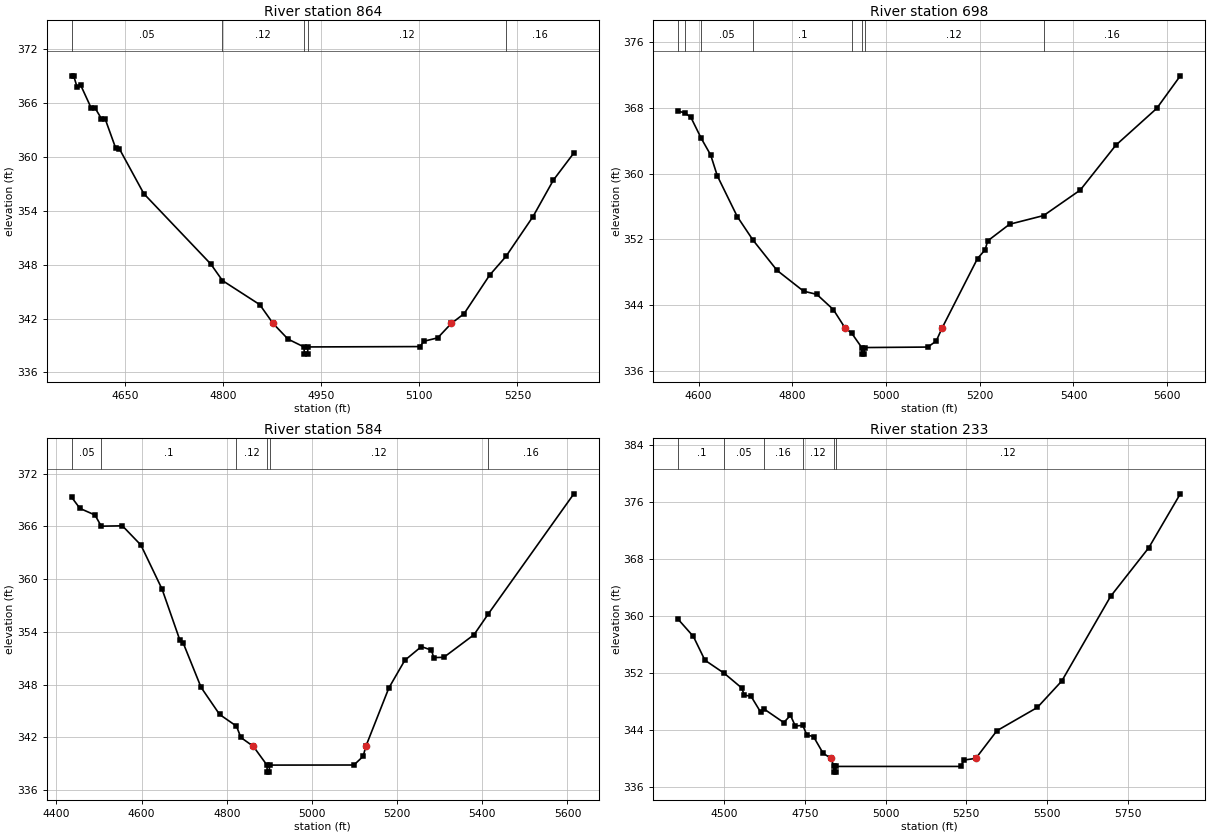
Type RM Length L Ch R = 1,864,166,166,166
BEGIN DESCRIPTION:
DUCK POND BRANCH 2.0
END DESCRIPTION:
XS GIS Cut Line= 3
      2915874.99      6973874.99      2916225.00      6974075.00
      2916574.97      6974174.99
#Sta/Elev= 30
  4569.1  369.02  4572.0  369.02  4577.0  367.82  4582.8  367.97  4598.6  365.46
  4604.4  365.47  4614.5  364.24  4620.2  364.21  4636.1  360.99  4641.8  360.90
  4679.2  355.90  4781.5  348.07  4799.3  346.23  4856.3  343.55  4876.7  341.45
  4899.5  339.71  4923.9  338.84  4924.4  338.04  4929.4  338.04  4929.9  338.84
  5100.9  338.88  5107.4  339.48  5128.2  339.85  5148.9  341.45  5168.5  342.54
  5207.5  346.83  5232.4  348.91  5273.8  353.35  5305.0  357.42  5336.2  360.43
#Mann=5,-1,0
  4569.1    0.05       0  4799.3    0.12       0  4923.9    0.07       0
  4929.9    0.12       0  5232.4    0.16       0
Bank Sta=4876.7,5148.9
Exp/Cntr=0.3,0.1

Type RM Length L Ch R = 1,698,114,114,114
BEGIN DESCRIPTION:
Mapping XS a3c96471
END DESCRIPTION:
XS GIS Cut Line= 3
      2915849.72      6973922.41      2916189.97      6974245.30
      2916741.05      6974487.92
#Sta/Elev= 30
  4556.7  367.60  4570.3  367.40  4583.5  366.87  4605.8  364.29  4625.9  362.27
  4640.1  359.73  4682.6  354.78  4716.1  351.92  4767.5  348.23  4824.1  345.70
  4852.4  345.31  4887.6  343.46  4913.0  341.19  4926.5  340.61  4948.2  338.84
  4948.7  338.04  4953.7  338.04  4954.2  338.84  5089.2  338.90  5107.1  339.63
  5119.4  341.19  5195.2  349.67  5211.4  350.73  5217.0  351.82  5263.5  353.84
  5336.3  354.90  5414.4  358.00  5490.2  363.45  5577.6  367.94  5627.9  371.90
#Mann=8,-1,0
  4556.7    0.05       0  4570.3     0.1       0  4605.8    0.05       0
  4716.1     0.1       0  4926.5    0.12       0  4948.2    0.07       0
  4954.2    0.12       0  5336.3    0.16       0
Bank Sta=4913,5119.4
Exp/Cntr=0.3,0.1

Type RM Length L Ch R = 1,584,351,351,351
BEGIN DESCRIPTION:
Mapping XS 00e52893
END DESCRIPTION:
XS GIS Cut Line= 3
      2915757.69      6973875.57      2916096.21      6974315.65
      2916670.32      6974559.84
#Sta/Elev= 30
  4435.9  369.29  4455.1  368.04  4490.4  367.29  4505.1  366.02  4554.8  366.06
  4598.3  363.87  4648.1  358.84  4689.8  353.05  4698.0  352.68  4739.6  347.68
  4783.1  344.60  4822.7  343.27  4833.0  341.98  4862.3  340.97  4894.3  338.84
  4894.8  338.04  4899.8  338.04  4900.3  338.84  5098.5  338.85  5120.2  339.84
  5126.5  340.97  5180.5  347.61  5218.0  350.76  5256.9  352.32  5280.5  351.92
  5286.0  351.07  5309.6  351.10  5380.5  353.67  5414.4  356.06  5615.0  369.70
#Mann=6,-1,0
  4435.9    0.05       0  4505.1     0.1       0  4822.7    0.12       0
  4894.3    0.07       0  4900.3    0.12       0  5414.4    0.16       0
Bank Sta=4862.3,5126.5
Exp/Cntr=0.3,0.1

Type RM Length L Ch R = 1,233,0,0,0
BEGIN DESCRIPTION:
DUCK POND BRANCH 1.0
END DESCRIPTION:
XS GIS Cut Line= 3
      2915411.29      6973904.15      2915779.75      6974430.26
      2916624.96      6974774.98
#Sta/Elev= 30
  4357.7  359.48  4404.6  357.08  4440.3  353.75  4500.5  351.90  4554.1  349.86
  4562.4  348.85  4583.3  348.68  4613.0  346.46  4621.9  346.95  4684.5  345.00
  4705.4  346.01  4720.2  344.52  4743.4  344.60  4755.9  343.28  4776.9  343.01
  4806.5  340.68  4831.4  339.97  4839.3  338.84  4839.8  338.04  4844.8  338.04
  4845.3  338.84  5232.3  338.84  5243.3  339.74  5279.4  339.97  5344.7  343.85
  5470.1  347.12  5545.7  350.83  5696.9  362.71  5815.2  369.54  5912.8  377.10
#Mann=6,-1,0
  4357.7     0.1       0  4500.5    0.05       0  4621.9    0.16       0
  4743.4    0.12       0  4839.3    0.07       0  4845.3    0.12       0
Bank Sta=4831.4,5279.4
Exp/Cntr=0.3,0.1

Chan Stop Cuts=-1