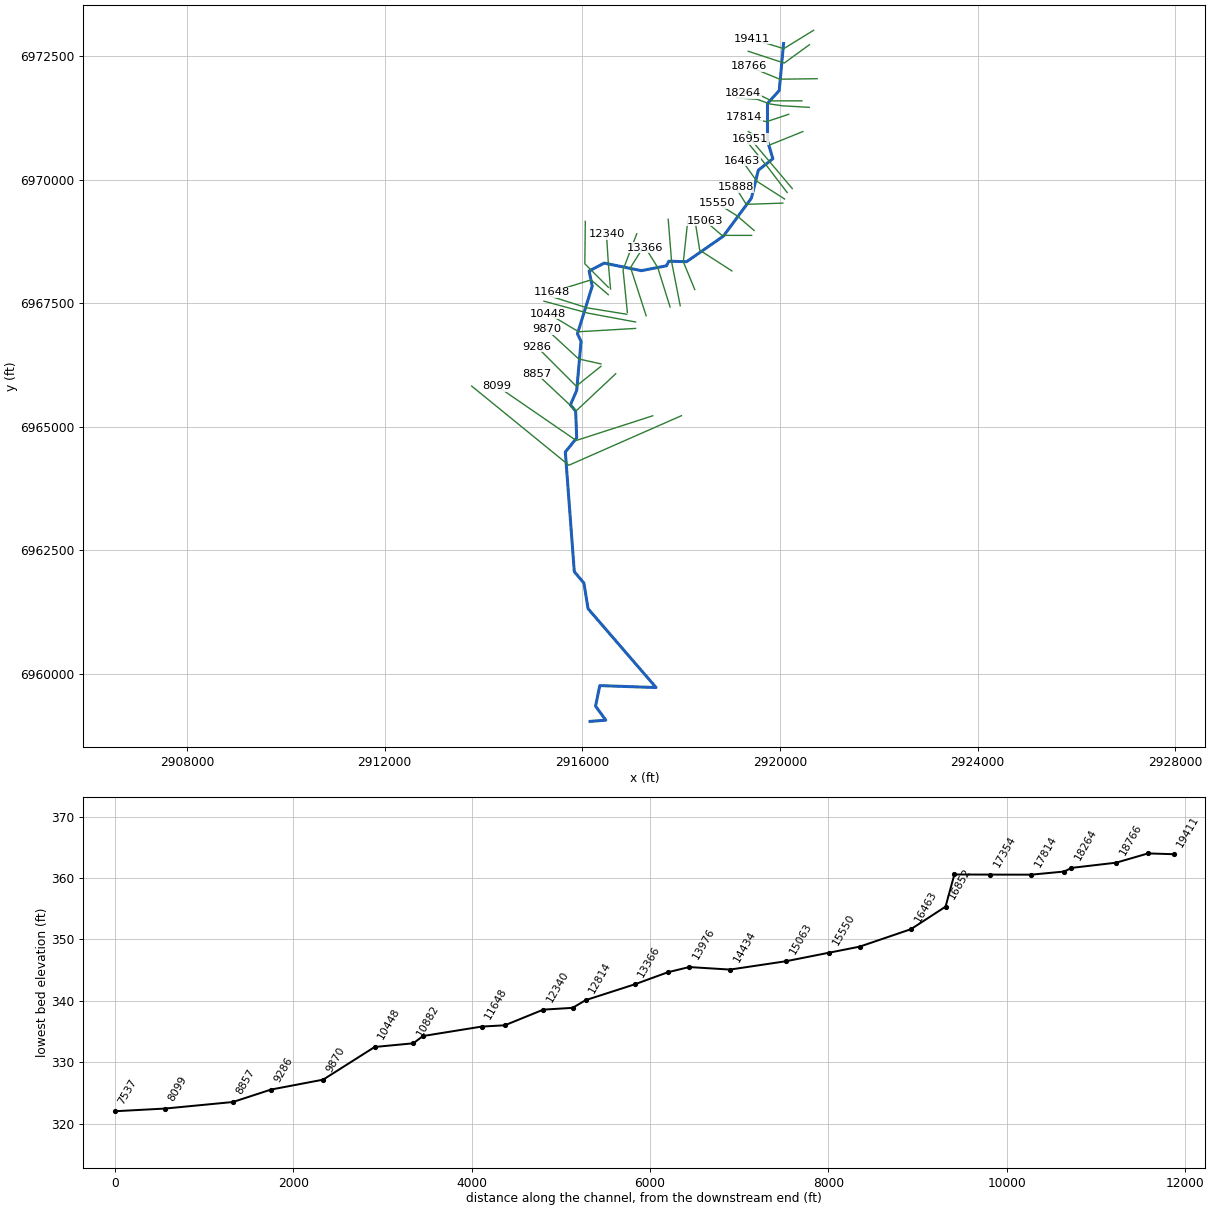
--- EDMOORE CREEK.prj (project) ---

Proj Title=EDMOORE CREEK Base Level Engineering
Current Plan=p01
Default Exp/Contr=0.3,0.1
English Units
Geom File=g01
Flow File=f01
Plan File=p01
BEGIN DESCRIPTION:
EDMOORE CREEK
END DESCRIPTION:

--- EDMOORE CREEK.p01 (plan) ---

Plan Title=Multiple Run
Short Identifier=Multiple
Geom File=g01
Flow File=f01
Subcritical Flow
K Sum by GR= 0
Std Step Tol= 0.01
Critical Tol= 0.01
Num of Std Step Trials= 20
Max Error Tol= 0.3
Flow Tol Ratio= 0.001
Split Flow NTrial= 30
Split Flow Tol= 0.02
Split Flow Ratio= 0.02
Log Output Level= 0
Friction Slope Method= 1
Unsteady Friction Slope Method= 2
Unsteady Bridges Friction Slope Method= 1
Parabolic Critical Depth
Global Vel Dist=  1 , 1 , 1
Global Log Level= 0
CheckData=True
Encroach Param= -1, 0, 0, 0
BEGIN DESCRIPTION:
Multiple Run
END DESCRIPTION:

--- EDMOORE CREEK.f01 (steady flow) ---

Flow Title=Multiple
Number of Profiles=7
Profile Names=10-year,25-year,50-year,1pct_min,100-year,1pct_plu,500-year
River Rch & RM= EDMOORE CREEK,Reach-1,19411
     530     715     867     524    1046    2087    1523
River Rch & RM= EDMOORE CREEK,Reach-1,19124
    1026    1435    1783    1101    2197    4384    3341
River Rch & RM= EDMOORE CREEK,Reach-1,15550
    1259    1775    2216    1374    2741    5469    4202
River Rch & RM= EDMOORE CREEK,Reach-1,11648
    1534    2177    2729    1697    3386    6756    5225
River Rch & RM= EDMOORE CREEK,Reach-1,6311
    1772    2525    3174    1977    3945    7872    6113
River Rch & RM= EDMOORE CREEK,Reach-1,2977
    2190    3146    3976    2489    4966    9908    7767
Boundary for River Rch & Prof#=EDMOORE CREEK,Reach-1,1
Up Type=0
Dn Type=3
Dn Slope=0.005
Boundary for River Rch & Prof#=EDMOORE CREEK,Reach-1,2
Up Type=0
Dn Type=3
Dn Slope=0.005
Boundary for River Rch & Prof#=EDMOORE CREEK,Reach-1,3
Up Type=0
Dn Type=3
Dn Slope=0.005
Boundary for River Rch & Prof#=EDMOORE CREEK,Reach-1,4
Up Type=0
Dn Type=3
Dn Slope=0.005
Boundary for River Rch & Prof#=EDMOORE CREEK,Reach-1,5
Up Type=0
Dn Type=3
Dn Slope=0.005
Boundary for River Rch & Prof#=EDMOORE CREEK,Reach-1,6
Up Type=0
Dn Type=3
Dn Slope=0.005
Boundary for River Rch & Prof#=EDMOORE CREEK,Reach-1,7
Up Type=0
Dn Type=3
Dn Slope=0.005

--- EDMOORE CREEK.g01 (geometry) ---

Geom Title=Existing Conditions

River Reach=EDMOORE CREEK,Reach-1
Reach XY= 30
      2920070.86      6972757.23      2919983.52      6971806.52
      2919745.98      6971545.64      2919746.32      6970785.92
      2919854.76      6970427.59      2919560.00      6970193.74
      2919420.09      6969628.36      2918854.36      6968860.38
      2918109.79      6968342.97      2917749.60      6968351.59
      2917700.99      6968259.57      2917193.90      6968161.48
      2916442.16      6968314.26      2916136.61      6968154.54
      2916199.11      6967845.94      2915900.45      6966884.14
      2915973.46      6966728.98      2915885.65      6965739.47
      2915757.80      6965445.10      2915864.55      6965320.32
      2915885.10      6964775.91      2915655.48      6964491.75
      2915836.64      6962071.14      2916031.90      6961839.18
      2916115.59      6961320.71      2917492.29      6959725.88
      2916352.81      6959765.13      2916267.06      6959349.93
      2916473.88      6959066.43      2916155.59      6959040.71

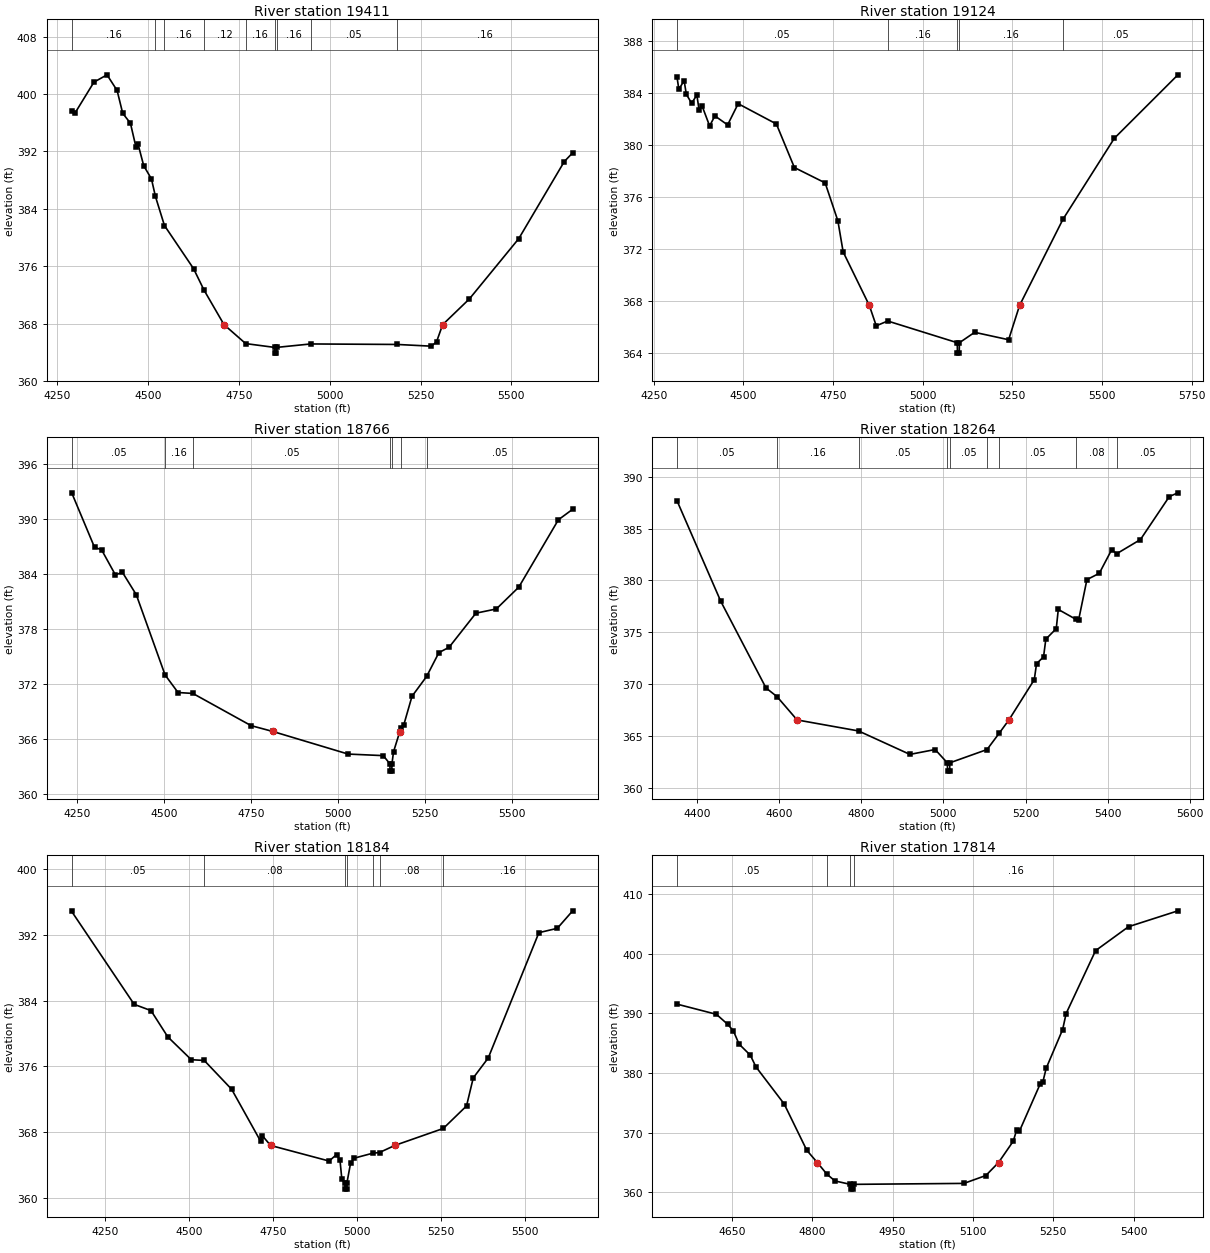
Type RM Length L Ch R = 1,19411,287,287,287
BEGIN DESCRIPTION:
EDMOORE CREEK 28.0
END DESCRIPTION:
XS GIS Cut Line= 3
      2920677.75      6973024.76      2920075.00      6972653.20
      2919433.02      6972850.56
#Sta/Elev= 30
  4289.2  397.63  4298.3  397.36  4350.4  401.67  4386.4  402.69  4414.2  400.51
  4429.6  397.33  4450.9  395.94  4466.3  392.58  4472.1  392.98  4487.5  390.01
  4508.8  388.17  4519.8  385.72  4544.6  381.67  4624.7  375.66  4653.6  372.66
  4708.7  367.84  4768.3  365.20  4847.7  364.67  4848.2  363.87  4853.2  363.87
  4853.7  364.67  4947.2  365.15  5185.3  365.08  5279.7  364.84  5294.0  365.45
  5310.8  367.84  5384.4  371.43  5520.4  379.84  5645.9  390.60  5668.9  391.81
#Mann=9,-1,0
  4289.2    0.16       0  4519.8    0.12       0  4544.6    0.16       0
  4653.6    0.12       0  4768.3    0.16       0  4847.7   0.033       0
  4853.7    0.16       0  4947.2    0.05       0  5185.3    0.16       0
Bank Sta=4708.7,5310.8
Exp/Cntr=0.3,0.1

Type RM Length L Ch R = 1,19124,358,358,358
BEGIN DESCRIPTION:
Mapping XS 399692f5
END DESCRIPTION:
XS GIS Cut Line= 3
      2920594.37      6972733.06      2920083.96      6972361.54
      2919356.53      6972600.55
#Sta/Elev= 30
  4314.7  385.25  4320.0  384.29  4334.7  384.95  4340.9  383.90  4355.6  383.22
  4370.2  383.84  4376.4  382.72  4384.9  383.00  4405.8  381.47  4420.5  382.24
  4456.0  381.55  4485.4  383.18  4592.0  381.62  4642.2  378.27  4728.0  377.09
  4763.5  374.17  4778.2  371.78  4851.1  367.67  4870.5  366.10  4902.3  366.47
  5096.4  364.80  5096.9  364.00  5101.9  364.00  5102.4  364.80  5144.9  365.60
  5239.6  365.03  5270.2  367.67  5390.9  374.28  5534.4  380.52  5711.7  385.40
#Mann=5,-1,0
  4314.7    0.05       0  4902.3    0.16       0  5096.4    0.07       0
  5102.4    0.16       0  5390.9    0.05       0
Bank Sta=4851.1,5270.2
Exp/Cntr=0.3,0.1

Type RM Length L Ch R = 1,18766,502,502,502
BEGIN DESCRIPTION:
Mapping XS 3f79e078
END DESCRIPTION:
XS GIS Cut Line= 3
      2920750.65      6972045.56      2919993.68      6972035.15
      2919361.78      6972295.55
#Sta/Elev= 30
  4234.2  392.83  4299.9  386.88  4319.9  386.63  4359.9  383.88  4379.9  384.17
  4419.9  381.72  4502.6  372.98  4539.9  371.06  4582.5  370.96  4749.9  367.45
  4812.0  366.82  5029.0  364.35  5130.1  364.18  5149.1  363.29  5149.6  362.49
  5154.6  362.49  5155.1  363.29  5159.5  364.59  5177.7  366.81  5180.2  367.19
  5188.8  367.50  5212.7  370.65  5254.7  372.81  5290.0  375.41  5319.3  375.99
  5396.5  379.71  5455.2  380.17  5519.8  382.55  5633.6  389.89  5674.7  391.04
#Mann=7,-1,0
  4234.2    0.05       0  4502.6    0.16       0  4582.5    0.05       0
  5149.1    0.03       0  5155.1    0.05       0  5180.2    0.16       0
  5254.7    0.05       0
Bank Sta=4812,5177.7
Exp/Cntr=0.3,0.1

Type RM Length L Ch R = 1,18264,80,80,80
BEGIN DESCRIPTION:
Mapping XS f1b8f079
END DESCRIPTION:
XS GIS Cut Line= 4
      2920441.57      6971597.65      2919827.02      6971597.65
      2919556.18      6971729.59      2919254.10      6971746.95
#Sta/Elev= 30
  4351.9  387.69  4458.5  377.99  4568.5  369.65  4595.4  368.81  4644.1  366.57
  4793.5  365.51  4918.5  363.25  4979.8  363.72  5009.5  362.44  5010.0  361.64
  5015.1  361.64  5015.6  362.44  5106.1  363.72  5136.2  365.32  5159.3  366.57
  5221.0  370.45  5226.5  371.99  5243.5  372.64  5249.1  374.35  5274.4  375.36
  5279.4  377.21  5322.2  376.26  5329.0  376.23  5349.0  380.08  5379.1  380.69
  5409.1  382.95  5421.6  382.58  5479.2  383.94  5549.4  388.08  5570.3  388.44
#Mann=9,-1,0
  4351.9    0.05       0  4595.4    0.16       0  4793.5    0.05       0
  5009.5    0.04       0  5015.6    0.05       0  5106.1    0.08       0
  5136.2    0.05       0  5322.2    0.08       0  5421.6    0.05       0
Bank Sta=4644.1,5159.3
Exp/Cntr=0.3,0.1

Type RM Length L Ch R = 1,18184,370,370,370
BEGIN DESCRIPTION:
Mapping XS c0aecdc4
END DESCRIPTION:
XS GIS Cut Line= 5
      2920590.93      6971465.70      2920049.24      6971496.95
      2919788.82      6971535.15      2919538.82      6971628.90
      2919119.33      6971656.63
#Sta/Elev= 30
  4149.3  394.86  4335.5  383.55  4385.6  382.79  4435.7  379.59  4505.8  376.81
  4544.3  376.72  4626.0  373.21  4712.1  366.90  4717.2  367.57  4742.1  366.37
  4916.6  364.47  4938.7  365.26  4948.9  364.60  4954.5  362.26  4963.7  361.85
  4964.2  361.05  4969.3  361.05  4969.8  361.85  4980.5  364.21  4991.2  364.82
  5046.1  365.42  5066.8  365.51  5112.2  366.37  5256.9  368.44  5326.1  371.18
  5346.2  374.60  5390.8  377.02  5541.8  392.28  5596.7  392.81  5642.5  394.94
#Mann=7,-1,0
  4149.3    0.05       0  4544.3    0.08       0  4963.7    0.07       0
  4969.8    0.08       0  5046.1    0.16       0  5066.8    0.08       0
  5256.9    0.16       0
Bank Sta=4742.1,5112.2
Exp/Cntr=0.3,0.1

Type RM Length L Ch R = 1,17814,460,460,460
BEGIN DESCRIPTION:
EDMOORE CREEK 26.0
END DESCRIPTION:
XS GIS Cut Line= 3
      2920174.96      6971324.99      2919725.00      6971175.00
      2919274.97      6971275.01
#Sta/Elev= 30
  4547.4  391.54  4621.1  389.83  4642.2  388.15  4652.8  387.05  4663.3  384.85
  4684.4  382.98  4694.9  381.02  4747.6  374.81  4789.8  367.05  4809.5  364.99
  4827.4  363.04  4842.5  361.91  4871.1  361.34  4871.6  360.54  4876.7  360.54
  4877.2  361.34  5083.2  361.50  5124.1  362.82  5147.8  364.99  5175.4  368.59
  5181.8  370.51  5186.9  370.27  5225.3  378.11  5230.4  378.44  5236.8  380.80
  5267.5  387.28  5274.0  389.96  5329.0  400.50  5390.5  404.51  5482.7  407.17
#Mann=4,-1,0
  4547.4    0.05       0  4827.4    0.16       0  4871.1    0.07       0
  4877.2    0.16       0
Bank Sta=4809.5,5147.8
Exp/Cntr=0.3,0.1

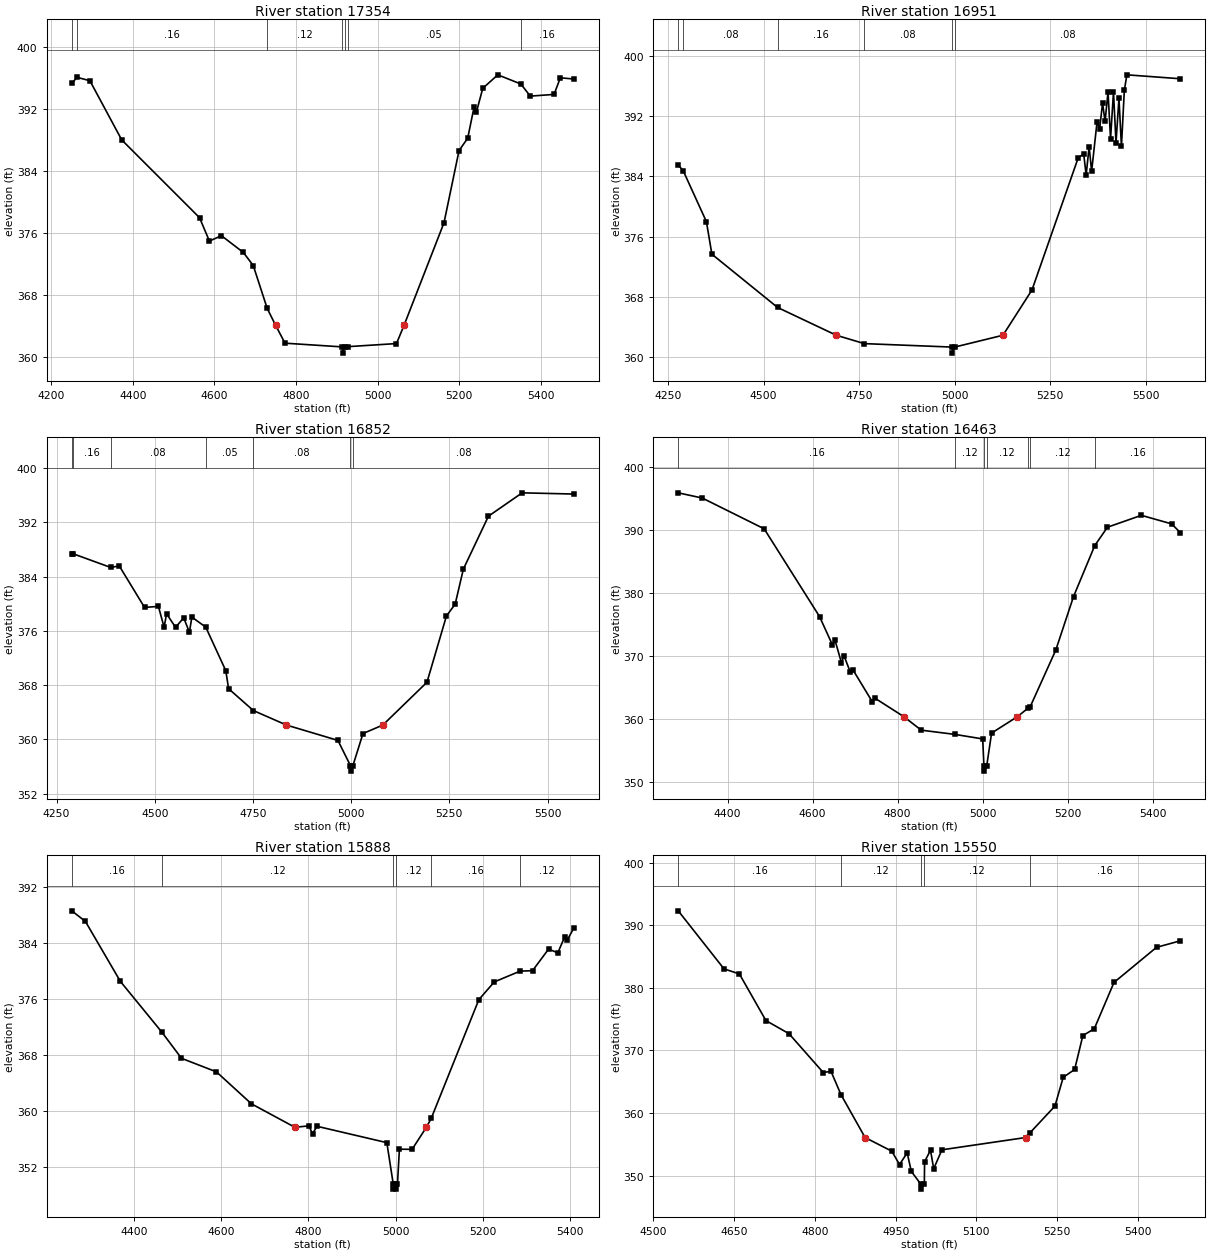
Type RM Length L Ch R = 1,17354,403,403,403
BEGIN DESCRIPTION:
Mapping XS 7dbdd268
END DESCRIPTION:
XS GIS Cut Line= 3
      2920462.44      6970976.12      2919799.24      6970708.76
      2919359.17      6970975.57
#Sta/Elev= 30
  4250.8  395.25  4263.6  396.04  4295.2  395.60  4373.1  387.99  4563.7  377.98
  4587.9  374.97  4617.4  375.66  4671.1  373.50  4695.3  371.82  4729.4  366.31
  4749.8  364.15  4773.1  361.83  4913.5  361.35  4914.0  360.55  4919.6  361.35
  4926.2  361.38  5046.1  361.78  5064.8  364.15  5162.5  377.33  5199.3  386.61
  5220.6  388.21  5236.1  392.21  5242.0  391.60  5257.5  394.63  5294.3  396.36
  5350.7  395.18  5373.8  393.62  5432.0  393.84  5447.5  395.98  5480.5  395.82
#Mann=7,-1,0
  4250.8    0.05       0  4263.6    0.16       0  4729.4    0.12       0
  4913.5    0.03       0  4919.6    0.12       0  4926.2    0.05       0
  5350.7    0.16       0
Bank Sta=4749.8,5064.8
Exp/Cntr=0.3,0.1

Type RM Length L Ch R = 1,16951,99,99,99
BEGIN DESCRIPTION:
Mapping XS d838e4fe
END DESCRIPTION:
XS GIS Cut Line= 3
      2920247.17      6969823.32      2919799.24      6970354.59
      2919399.95      6970826.80
#Sta/Elev= 30
  4276.6  385.50  4289.5  384.75  4350.3  377.99  4364.6  373.68  4536.5  366.62
  4690.0  362.94  4763.4  361.83  4993.4  361.37  4993.9  360.57  4999.5  361.37
  5126.0  362.94  5201.9  368.94  5322.8  386.45  5337.1  386.98  5343.6  384.19
  5351.4  387.94  5357.9  384.65  5372.2  391.26  5378.8  390.25  5386.5  393.70
  5393.1  391.28  5400.8  395.20  5407.4  388.98  5415.1  395.16  5421.7  388.45
  5429.4  394.34  5435.9  387.96  5443.5  395.42  5450.2  397.45  5589.9  396.93
#Mann=6,-1,0
  4276.6    0.16       0  4289.5    0.08       0  4536.5    0.16       0
  4763.4    0.08       0  4993.4    0.07       0  4999.5    0.08       0
Bank Sta=4690,5126
Exp/Cntr=0.3,0.1

Type RM Length L Ch R = 1,16852,389,389,389
BEGIN DESCRIPTION:
Mapping XS 8a93e064
END DESCRIPTION:
XS GIS Cut Line= 3
      2920143.02      6969743.44      2919736.74      6970274.73
      2919351.30      6970746.98
#Sta/Elev= 30
  4288.6  387.40  4290.5  387.40  4387.7  385.35  4409.5  385.58  4473.9  379.46
  4509.2  379.61  4523.7  376.53  4530.0  378.53  4552.8  376.52  4573.6  377.93
  4588.1  375.80  4594.4  378.03  4629.8  376.55  4680.8  370.13  4687.9  367.48
  4750.9  364.26  4835.3  362.12  4966.2  359.86  4998.3  356.13  4998.8  355.33
  5004.4  356.13  5030.1  360.87  5080.6  362.12  5193.0  368.43  5242.6  378.20
  5264.8  379.94  5285.7  385.11  5349.6  392.91  5435.4  396.35  5567.0  396.17
#Mann=7,-1,0
  4288.6    0.08       0  4290.5    0.16       0  4387.7    0.08       0
  4629.8    0.05       0  4750.9    0.08       0  4998.3    0.07       0
  5004.4    0.08       0
Bank Sta=4835.3,5080.6
Exp/Cntr=0.3,0.1

Type RM Length L Ch R = 1,16463,575,575,575
BEGIN DESCRIPTION:
Mapping XS 3922b65e
END DESCRIPTION:
XS GIS Cut Line= 3
      2920090.91      6969611.53      2919531.88      6969969.18
      2919229.92      6970389.14
#Sta/Elev= 30
  4283.9  395.83  4340.5  395.00  4486.0  390.12  4616.2  376.20  4646.6  371.69
  4652.6  372.45  4667.8  368.86  4673.7  369.99  4688.9  367.32  4694.9  367.73
  4740.5  362.65  4746.5  363.24  4814.4  360.31  4855.5  358.16  4934.7  357.49
  5000.0  356.77  5002.9  352.46  5003.4  351.66  5009.4  352.46  5020.9  357.70
  5081.8  360.31  5106.4  361.64  5111.9  361.90  5171.9  370.87  5213.6  379.36
  5263.6  387.46  5293.4  390.37  5373.2  392.26  5444.4  390.90  5464.8  389.52
#Mann=7,-1,0
  4283.9    0.16       0  4934.7    0.12       0  5002.9    0.07       0
  5009.4    0.12       0  5106.4    0.16       0  5111.9    0.12       0
  5263.6    0.16       0
Bank Sta=4814.4,5081.8
Exp/Cntr=0.3,0.1

Type RM Length L Ch R = 1,15888,338,338,338
BEGIN DESCRIPTION:
EDMOORE CREEK 23.0
END DESCRIPTION:
XS GIS Cut Line= 3
      2920056.19      6969528.20      2919314.61      6969503.16
      2919099.98      6969850.03
#Sta/Elev= 30
  4258.0  388.58  4289.2  387.07  4369.3  378.50  4464.3  371.25  4509.3  367.51
  4589.4  365.57  4669.4  361.01  4769.2  357.65  4800.9  357.86  4809.5  356.72
  4819.5  357.80  4979.6  355.46  4994.1  349.62  4994.6  348.82  5000.1  348.82
  5000.6  349.62  5004.0  349.62  5008.4  354.53  5037.4  354.50  5070.1  357.65
  5081.2  358.92  5190.3  375.89  5225.6  378.42  5284.6  379.96  5313.3  380.03
  5350.0  383.11  5371.2  382.58  5386.6  384.82  5392.5  384.37  5407.9  386.13
#Mann=6,-1,0
  4258.0    0.16       0  4464.3    0.12       0  4994.1    0.07       0
  5000.6    0.12       0  5081.2    0.16       0  5284.6    0.12       0
Bank Sta=4769.2,5070.1
Exp/Cntr=0.3,0.1

Type RM Length L Ch R = 1,15550,487,487,487
BEGIN DESCRIPTION:
EDMOORE CREEK 22.0
END DESCRIPTION:
XS GIS Cut Line= 3
      2919474.97      6968975.03      2919125.00      6969275.00
      2918725.03      6969524.98
#Sta/Elev= 30
  4546.2  392.30  4631.2  383.03  4659.8  382.22  4709.1  374.77  4751.9  372.68
  4815.6  366.47  4829.9  366.67  4848.5  362.94  4893.3  356.09  4942.9  353.91
  4957.2  351.78  4971.5  353.64  4979.1  350.69  4996.7  348.65  4997.2  347.85
  5003.3  348.65  5003.8  352.23  5014.8  354.07  5020.7  351.10  5036.0  354.13
  5191.5  356.09  5199.2  356.81  5245.9  361.11  5261.3  365.71  5282.5  366.96
  5297.8  372.38  5319.0  373.46  5355.6  380.86  5434.6  386.47  5478.8  387.51
#Mann=5,-1,0
  4546.2    0.16       0  4848.5    0.12       0  4996.7    0.07       0
  5003.3    0.12       0  5199.2    0.16       0
Bank Sta=4893.3,5191.5
Exp/Cntr=0.3,0.1

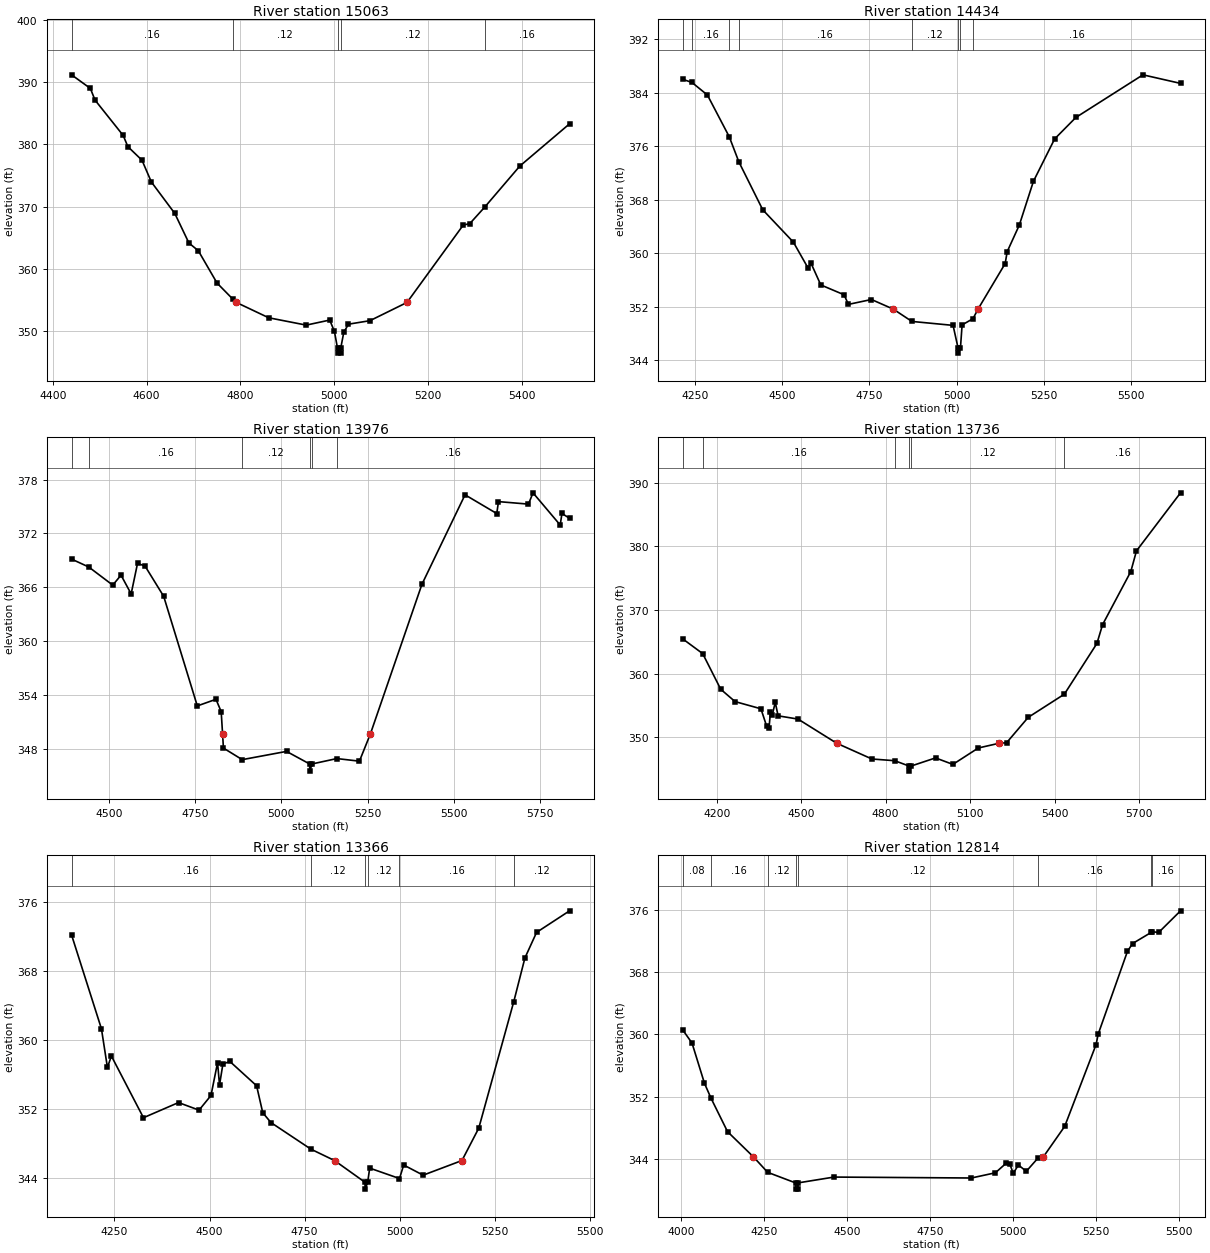
Type RM Length L Ch R = 1,15063,629,629,629
BEGIN DESCRIPTION:
EDMOORE CREEK 21.0
END DESCRIPTION:
XS GIS Cut Line= 3
      2919425.03      6968875.00      2918825.00      6968875.00
      2918475.01      6969174.99
#Sta/Elev= 30
  4440.2  391.15  4480.2  388.97  4490.2  387.09  4550.2  381.41  4560.2  379.61
  4590.2  377.44  4610.2  373.94  4660.2  368.88  4690.2  364.14  4710.2  362.90
  4750.2  357.70  4783.7  355.13  4791.3  354.59  4860.2  352.13  4940.2  350.95
  4990.2  351.76  5000.2  349.95  5006.8  347.25  5007.3  346.45  5013.2  346.45
  5013.7  347.25  5020.2  349.80  5030.2  351.10  5075.9  351.66  5154.9  354.59
  5274.6  367.01  5288.8  367.26  5321.0  369.95  5395.3  376.50  5501.2  383.28
#Mann=5,-1,0
  4440.2    0.16       0  4783.7    0.12       0  5006.8    0.07       0
  5013.7    0.12       0  5321.0    0.16       0
Bank Sta=4791.3,5154.9
Exp/Cntr=0.3,0.1

Type RM Length L Ch R = 1,14434,458,458,458
BEGIN DESCRIPTION:
EDMOORE CREEK 20.0
END DESCRIPTION:
XS GIS Cut Line= 3
      2919024.96      6968156.66      2918375.00      6968575.00
      2918271.67      6969221.34
#Sta/Elev= 30
  4214.2  386.05  4241.2  385.57  4285.5  383.69  4348.2  377.44  4375.6  373.70
  4444.1  366.53  4531.9  361.69  4574.1  357.81  4582.8  358.50  4610.5  355.29
  4677.1  353.82  4689.8  352.38  4755.7  353.11  4818.4  351.67  4871.7  349.83
  4989.7  349.24  5003.9  345.89  5004.4  345.09  5010.9  345.89  5015.6  349.31
  5046.8  350.24  5061.2  351.67  5139.1  358.49  5144.8  360.26  5179.6  364.24
  5220.1  370.79  5280.8  377.12  5341.6  380.33  5534.0  386.71  5641.7  385.43
#Mann=8,-1,0
  4214.2    0.12       0  4241.2    0.16       0  4348.2    0.12       0
  4375.6    0.16       0  4871.7    0.12       0  5003.9    0.07       0
  5010.9    0.12       0  5046.8    0.16       0
Bank Sta=4818.4,5061.2
Exp/Cntr=0.3,0.1

Type RM Length L Ch R = 1,13976,240,240,240
BEGIN DESCRIPTION:
EDMOORE CREEK 19.0
END DESCRIPTION:
XS GIS Cut Line= 3
      2918274.92      6967778.24      2918043.05      6968340.29
      2918132.54      6969170.28
#Sta/Elev= 30
  4392.0  369.14  4441.8  368.26  4511.3  366.24  4535.3  367.35  4564.6  365.26
  4583.1  368.66  4604.8  368.37  4658.9  364.99  4756.3  352.77  4810.4  353.51
  4825.5  352.13  4829.5  349.66  4832.0  348.07  4886.5  346.78  5014.8  347.70
  5081.7  346.30  5082.2  345.50  5088.7  346.30  5160.6  346.90  5226.0  346.61
  5257.9  349.66  5407.1  366.33  5532.0  376.31  5623.9  374.22  5628.9  375.55
  5715.8  375.27  5728.9  376.53  5807.7  372.94  5812.8  374.23  5834.8  373.69
#Mann=6,-1,0
  4392.0    0.05       0  4441.8    0.16       0  4886.5    0.12       0
  5081.7    0.07       0  5088.7    0.12       0  5160.6    0.16       0
Bank Sta=4829.5,5257.9
Exp/Cntr=0.3,0.1

Type RM Length L Ch R = 1,13736,370,370,370
BEGIN DESCRIPTION:
Mapping XS 20a627cd
END DESCRIPTION:
XS GIS Cut Line= 3
      2917979.79      6967451.84      2917806.18      6968337.23
      2917736.81      6969200.90
#Sta/Elev= 30
  4078.8  365.48  4150.4  363.14  4214.5  357.53  4265.4  355.59  4357.2  354.46
  4377.5  351.73  4386.1  351.50  4391.2  354.01  4397.9  353.56  4408.1  355.47
  4418.3  353.35  4489.0  352.84  4626.3  349.04  4751.4  346.56  4832.3  346.29
  4883.5  345.45  4884.0  344.65  4890.6  345.45  4977.4  346.73  5039.0  345.71
  5129.3  348.29  5203.6  349.04  5229.6  349.11  5306.5  353.11  5435.0  356.76
  5550.6  364.74  5570.7  367.70  5671.0  376.06  5691.1  379.31  5847.5  388.44
#Mann=6,-1,0
  4078.8    0.05       0  4150.4    0.16       0  4832.3    0.12       0
  4883.5    0.07       0  4890.6    0.12       0  5435.0    0.16       0
Bank Sta=4626.3,5203.6
Exp/Cntr=0.3,0.1

Type RM Length L Ch R = 1,13366,552,552,552
BEGIN DESCRIPTION:
EDMOORE CREEK 18.0
END DESCRIPTION:
XS GIS Cut Line= 3
      2917775.01      6967424.98      2917525.00      6968225.00
      2917274.99      6968625.02
#Sta/Elev= 30
  4137.1  372.20  4215.7  361.30  4231.4  356.82  4241.9  358.14  4326.2  350.98
  4418.4  352.74  4472.4  351.86  4503.8  353.56  4521.1  357.37  4526.3  354.78
  4535.2  357.22  4553.6  357.51  4623.8  354.69  4640.0  351.56  4661.5  350.42
  4766.7  347.33  4828.8  346.01  4908.8  343.49  4909.4  342.69  4916.0  343.49
  4921.3  345.13  4999.7  343.92  5010.7  345.49  5061.9  344.31  5164.0  346.01
  5208.2  349.77  5300.3  364.46  5329.6  369.53  5360.3  372.50  5447.0  375.00
#Mann=6,-1,0
  4137.1    0.16       0  4766.7    0.12       0  4908.8    0.07       0
  4916.0    0.12       0  4999.7    0.16       0  5300.3    0.12       0
Bank Sta=4828.8,5164
Exp/Cntr=0.3,0.1

Type RM Length L Ch R = 1,12814,145,145,145
BEGIN DESCRIPTION:
EDMOORE CREEK 17.0
END DESCRIPTION:
XS GIS Cut Line= 3
      2917290.56      6967247.83      2916975.00      6968225.00
      2917225.02      6968625.03
#Sta/Elev= 30
  4004.7  360.61  4033.3  358.88  4070.8  353.70  4090.6  351.78  4140.1  347.50
  4218.0  344.26  4260.9  342.27  4344.9  340.91  4345.5  340.11  4351.6  340.11
  4352.1  340.91  4460.5  341.66  4873.9  341.54  4946.2  342.21  4978.3  343.43
  4989.5  343.33  5000.0  342.15  5015.5  343.21  5039.2  342.40  5074.7  344.12
  5090.6  344.26  5154.8  348.18  5249.1  358.68  5255.6  360.04  5343.5  370.66
  5358.8  371.67  5415.6  373.12  5416.7  373.19  5437.8  373.11  5503.3  375.88
#Mann=8,-1,0
  4004.7    0.08       0  4090.6    0.16       0  4260.9    0.12       0
  4344.9    0.07       0  4352.1    0.12       0  5074.7    0.16       0
  5415.6    0.12       0  5416.7    0.16       0
Bank Sta=4218,5090.6
Exp/Cntr=0.3,0.1

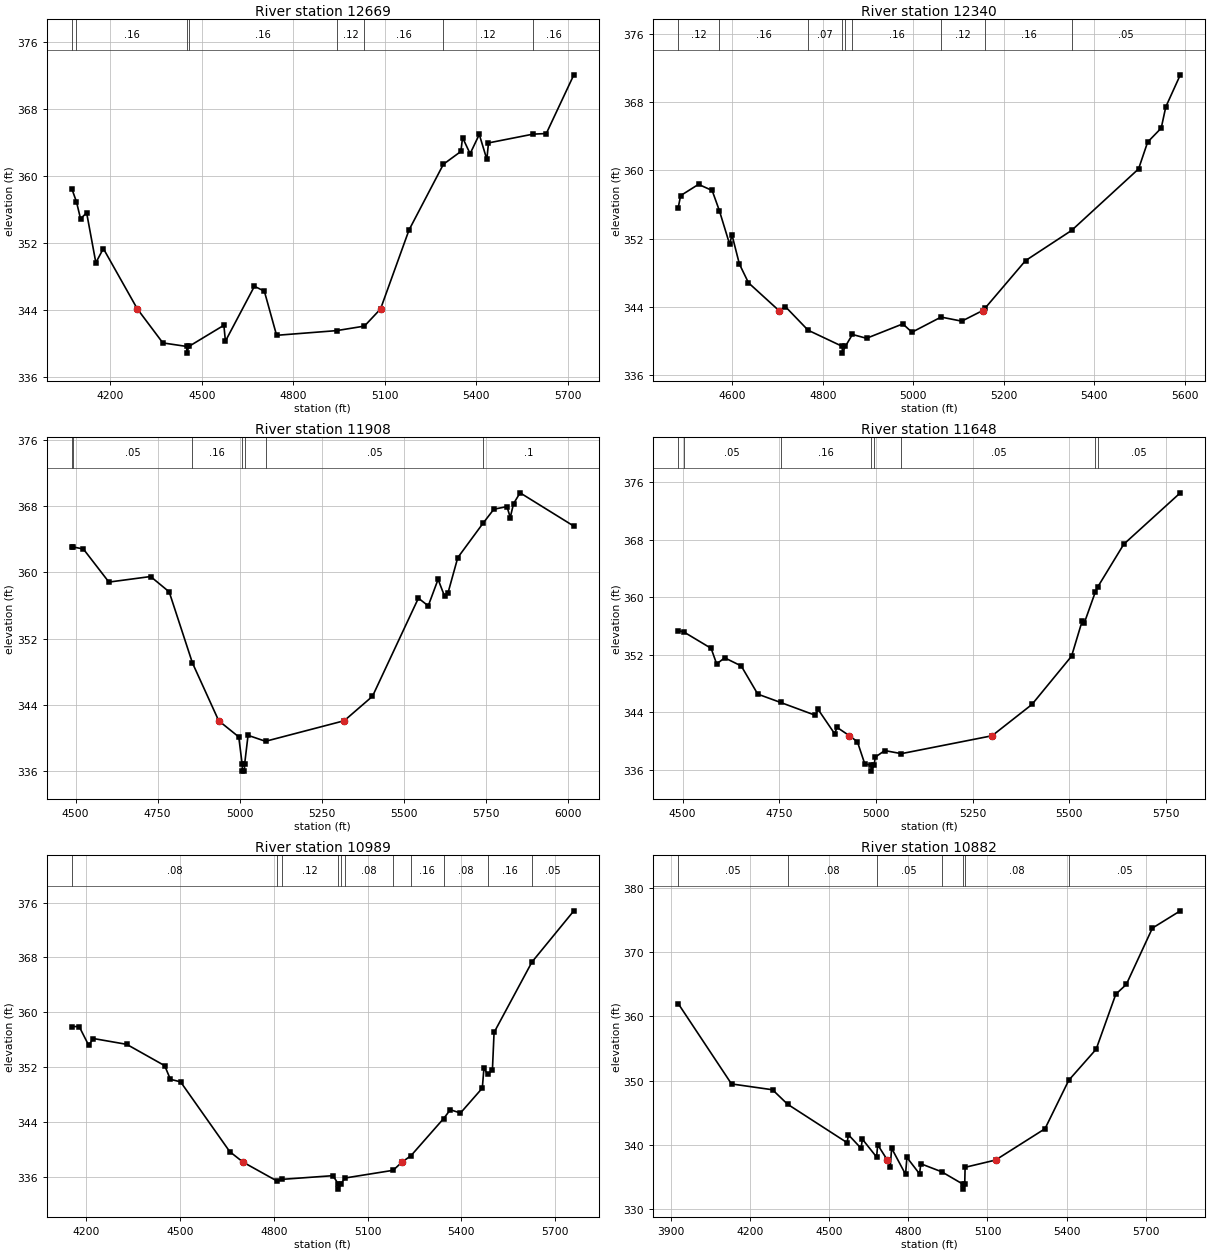
Type RM Length L Ch R = 1,12669,329,329,329
BEGIN DESCRIPTION:
Mapping XS c94cb09b
END DESCRIPTION:
XS GIS Cut Line= 3
      2916910.34      6967316.44      2916823.54      6968177.51
      2917100.63      6968908.31
#Sta/Elev= 30
  4073.6  358.53  4089.1  356.94  4102.3  354.93  4122.4  355.63  4152.6  349.67
  4177.2  351.36  4288.8  344.14  4372.4  340.08  4450.5  339.66  4451.0  338.86
  4457.7  339.66  4572.6  342.19  4577.6  340.29  4672.7  346.85  4705.3  346.27
  4745.5  340.99  4942.3  341.55  5033.6  342.09  5086.5  344.14  5179.9  353.58
  5292.7  361.44  5350.1  362.97  5355.5  364.63  5380.3  362.70  5410.4  365.00
  5435.2  362.02  5440.6  363.99  5586.7  365.04  5630.2  365.11  5720.6  372.13
#Mann=8,-1,0
  4073.6    0.08       0  4089.1    0.16       0  4450.5    0.07       0
  4457.7    0.16       0  4942.3    0.12       0  5033.6    0.16       0
  5292.7    0.12       0  5586.7    0.16       0
Bank Sta=4288.8,5086.5
Exp/Cntr=0.3,0.1

Type RM Length L Ch R = 1,12340,432,432,432
BEGIN DESCRIPTION:
Mapping XS ea9a9970
END DESCRIPTION:
XS GIS Cut Line= 3
      2916570.07      6967790.32      2916526.67      6968293.83
      2916487.61      6968897.09
#Sta/Elev= 30
  4480.5  355.65  4485.8  357.05  4525.3  358.37  4555.5  357.65  4571.4  355.29
  4594.2  351.33  4599.2  352.46  4615.7  349.02  4635.8  346.82  4703.2  343.56
  4717.6  344.01  4767.5  341.26  4842.9  339.37  4843.4  338.57  4850.1  339.37
  4865.5  340.76  4896.7  340.31  4977.0  342.00  4997.1  341.02  5061.5  342.80
  5107.3  342.32  5153.3  343.56  5159.4  343.88  5248.2  349.42  5350.2  352.97
  5498.1  360.18  5518.2  363.33  5548.2  364.97  5558.3  367.46  5590.4  371.22
#Mann=9,-1,0
  4480.5    0.12       0  4571.4    0.16       0  4767.5    0.07       0
  4842.9    0.07       0  4850.1    0.07       0  4865.5    0.16       0
  5061.5    0.12       0  5159.4    0.16       0  5350.2    0.05       0
Bank Sta=4703.2,5153.3
Exp/Cntr=0.3,0.1

Type RM Length L Ch R = 1,11908,260,260,260
BEGIN DESCRIPTION:
EDMOORE CREEK 16.0
END DESCRIPTION:
XS GIS Cut Line= 3
      2916525.02      6967824.98      2916050.00      6968300.00
      2916059.65      6969158.87
#Sta/Elev= 30
  4488.5  363.07  4492.3  363.07  4523.9  362.82  4601.7  358.83  4728.9  359.50
  4785.5  357.65  4856.3  349.08  4936.5  342.10  4997.6  340.15  5008.1  336.82
  5008.7  336.02  5014.9  336.02  5015.4  336.82  5025.9  340.34  5079.2  339.62
  5319.1  342.10  5405.3  345.05  5545.3  356.89  5575.3  355.96  5605.3  359.16
  5625.3  357.10  5635.3  357.49  5665.3  361.78  5743.1  365.97  5775.3  367.62
  5815.3  367.94  5825.3  366.62  5835.3  368.29  5855.3  369.60  6019.2  365.58
#Mann=7,-1,0
  4488.5    0.12       0  4492.3    0.05       0  4856.3    0.16       0
  5008.1    0.07       0  5015.4    0.16       0  5079.2    0.05       0
  5743.1     0.1       0
Bank Sta=4936.5,5319.1
Exp/Cntr=0.3,0.1

Type RM Length L Ch R = 1,11648,659,659,659
BEGIN DESCRIPTION:
EDMOORE CREEK 15.0
END DESCRIPTION:
XS GIS Cut Line= 3
      2916525.02      6967674.98      2916175.00      6967975.00
      2915374.96      6967724.99
#Sta/Elev= 30
  4488.5  355.35  4502.5  355.18  4573.6  352.89  4587.9  350.72  4608.7  351.57
  4651.5  350.44  4694.3  346.52  4753.5  345.36  4843.6  343.57  4850.2  344.41
  4893.0  341.03  4899.6  341.89  4931.5  340.73  4952.1  339.90  4971.0  336.85
  4987.4  336.61  4988.1  335.81  4995.4  336.61  4998.2  337.75  5022.8  338.67
  5065.8  338.24  5300.6  340.73  5403.7  345.08  5506.3  351.80  5533.6  356.67
  5538.8  356.35  5568.0  360.76  5573.6  361.39  5641.5  367.38  5787.7  374.52
#Mann=8,-1,0
  4488.5    0.16       0  4502.5    0.05       0  4753.5    0.16       0
  4987.4    0.07       0  4995.4    0.16       0  5065.8    0.05       0
  5568.0    0.16       0  5573.6    0.05       0
Bank Sta=4931.5,5300.6
Exp/Cntr=0.3,0.1

Type RM Length L Ch R = 1,10989,107,107,107
BEGIN DESCRIPTION:
Mapping XS c21fa54c
END DESCRIPTION:
XS GIS Cut Line= 3
      2916898.39      6967279.06      2916095.44      6967409.27
      2915340.21      6967647.99
#Sta/Elev= 30
  4154.0  357.94  4177.7  357.94  4208.1  355.21  4222.8  356.20  4329.7  355.35
  4451.2  352.24  4469.3  350.26  4501.9  349.89  4659.3  339.72  4702.1  338.19
  4811.5  335.42  4825.6  335.69  4988.9  336.23  5005.8  335.07  5006.5  334.27
  5013.8  335.07  5029.3  335.90  5181.6  337.01  5209.6  338.19  5238.5  339.13
  5343.2  344.55  5364.6  345.83  5396.9  345.35  5466.8  348.98  5472.0  351.87
  5484.1  350.97  5499.1  351.60  5504.4  357.08  5625.6  367.34  5759.5  374.79
#Mann=11,-1,0
  4154.0    0.08       0  4811.5    0.05       0  4825.6    0.12       0
  5005.8    0.07       0  5013.8    0.12       0  5029.3    0.08       0
  5181.6    0.12       0  5238.5    0.16       0  5343.2    0.08       0
  5484.1    0.16       0  5625.6    0.05       0
Bank Sta=4702.1,5209.6
Exp/Cntr=0.3,0.1

Type RM Length L Ch R = 1,10882,434,434,434
BEGIN DESCRIPTION:
Mapping XS eb72b0a5
END DESCRIPTION:
XS GIS Cut Line= 3
      2917076.32      6967122.82      2916117.15      6967300.76
      2915223.04      6967543.82
#Sta/Elev= 30
  3928.4  361.99  4130.2  349.48  4285.7  348.57  4342.6  346.32  4568.1  340.33
  4573.2  341.56  4621.0  339.45  4626.0  340.87  4679.9  338.09  4684.0  340.00
  4720.6  337.62  4731.7  336.57  4736.8  339.46  4789.6  335.39  4794.7  338.03
  4842.5  335.47  4847.6  337.04  4926.6  335.79  5005.8  333.89  5006.4  333.09
  5013.8  333.89  5015.2  336.49  5130.6  337.62  5317.9  342.50  5408.0  350.06
  5511.7  354.89  5586.1  363.46  5625.9  364.98  5724.8  373.76  5830.5  376.45
#Mann=7,-1,0
  3928.4    0.05       0  4342.6    0.08       0  4679.9    0.05       0
  4926.6    0.08       0  5005.8    0.07       0  5013.8    0.08       0
  5408.0    0.05       0
Bank Sta=4720.6,5130.6
Exp/Cntr=0.3,0.1

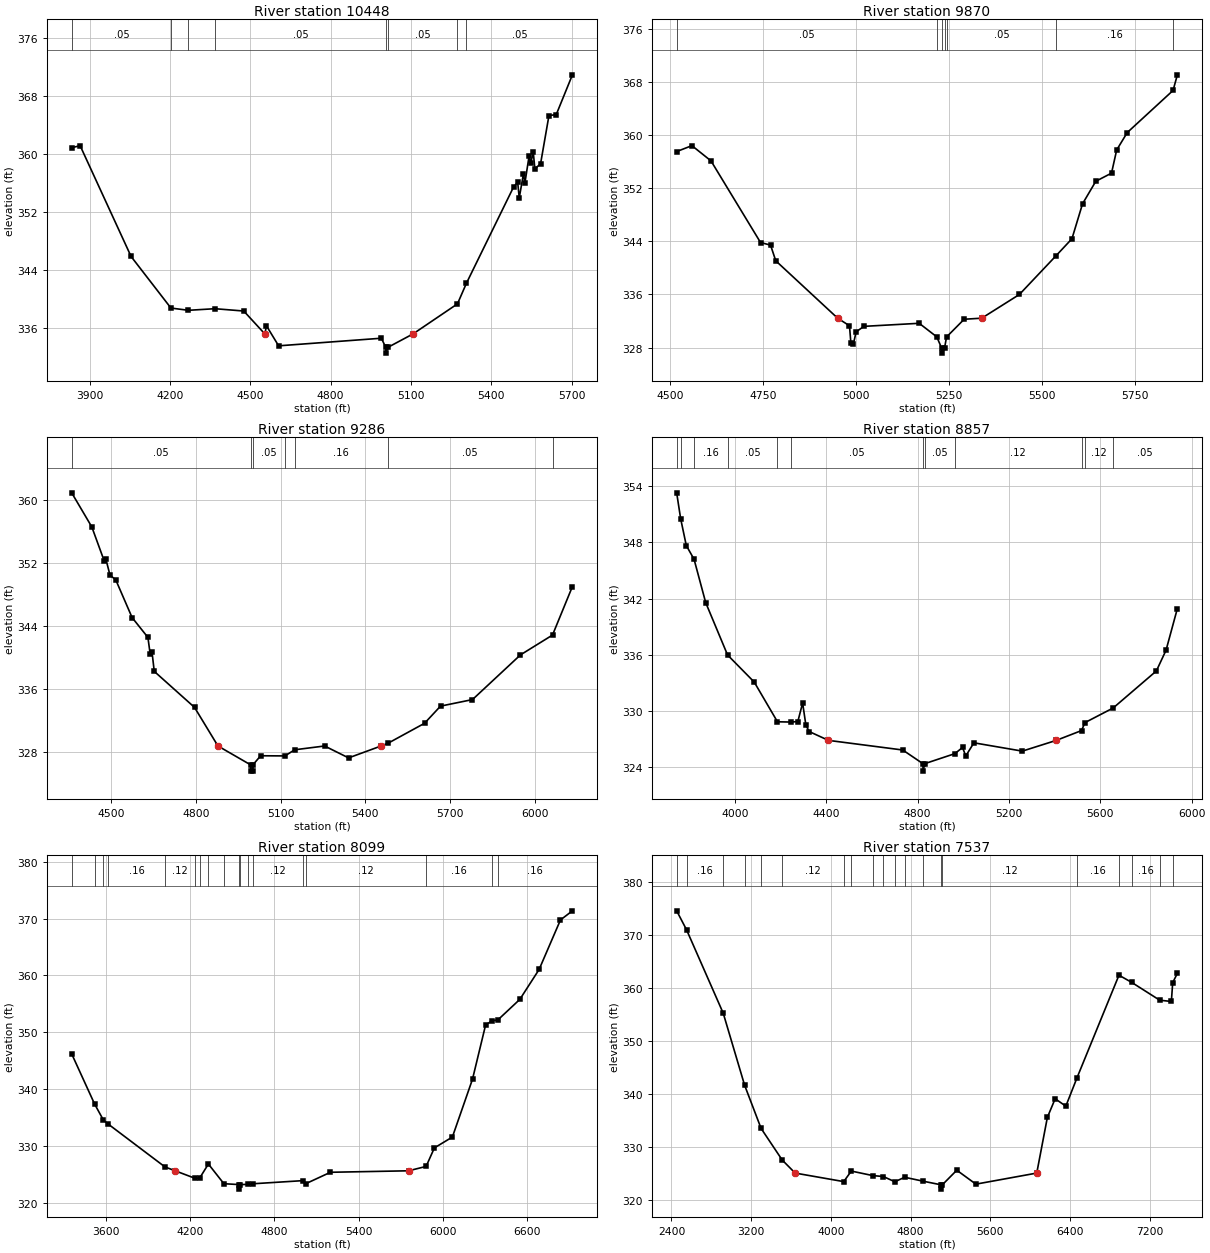
Type RM Length L Ch R = 1,10448,578,578,578
BEGIN DESCRIPTION:
EDMOORE CREEK 13.0
END DESCRIPTION:
XS GIS Cut Line= 3
      2917076.30      6966992.60      2915925.00      6966925.00
      2915309.97      6967292.02
#Sta/Elev= 30
  3833.5  360.88  3864.9  361.17  4055.2  345.85  4204.0  338.72  4269.3  338.41
  4368.3  338.63  4475.9  338.31  4554.7  335.14  4560.7  336.26  4606.1  333.50
  4989.7  334.55  5006.0  333.29  5006.7  332.49  5014.1  333.29  5107.7  335.14
  5273.8  339.30  5307.3  342.15  5483.1  355.44  5498.6  356.11  5504.5  353.95
  5520.0  357.24  5525.9  356.07  5541.4  359.77  5547.3  358.76  5557.0  360.23
  5562.8  357.95  5584.2  358.68  5615.4  365.33  5642.6  365.46  5703.0  370.96
#Mann=8,-1,0
  3833.5    0.05       0  4204.0    0.12       0  4269.3    0.16       0
  4368.3    0.05       0  5006.0    0.03       0  5014.1    0.05       0
  5273.8    0.16       0  5307.3    0.05       0
Bank Sta=4554.7,5107.7
Exp/Cntr=0.3,0.1

Type RM Length L Ch R = 1,9870,584,584,584
BEGIN DESCRIPTION:
EDMOORE CREEK 12.0
END DESCRIPTION:
XS GIS Cut Line= 3
      2916375.00      6966275.00      2915925.00      6966375.00
      2915274.97      6966975.02
#Sta/Elev= 30
  4517.9  357.51  4558.9  358.40  4610.1  356.11  4743.3  343.82  4770.2  343.43
  4784.2  341.07  4950.5  332.43  4982.3  331.29  4986.0  328.75  4992.8  328.51
  5000.1  330.37  5021.1  331.20  5169.7  331.66  5216.9  329.62  5229.7  327.97
  5230.4  327.17  5237.9  327.97  5243.2  329.60  5290.5  332.27  5337.8  332.43
  5439.0  336.00  5537.8  341.85  5580.2  344.39  5608.6  349.64  5644.3  353.04
  5686.5  354.26  5700.4  357.75  5728.8  360.37  5851.9  366.71  5863.5  369.06
#Mann=7,-1,0
  4517.9    0.05       0  5216.9    0.16       0  5229.7    0.03       0
  5237.9    0.16       0  5243.2    0.05       0  5537.8    0.16       0
  5851.9    0.05       0
Bank Sta=4950.5,5337.8
Exp/Cntr=0.3,0.1

Type RM Length L Ch R = 1,9286,429,429,429
BEGIN DESCRIPTION:
EDMOORE CREEK 11.0
END DESCRIPTION:
XS GIS Cut Line= 3
      2916375.00      6966225.00      2915875.00      6965825.00
      2915074.99      6966625.01
#Sta/Elev= 30
  4361.0  360.88  4432.2  356.55  4475.5  352.29  4481.9  352.48  4496.3  350.45
  4517.1  349.82  4574.7  345.05  4630.7  342.53  4638.7  340.40  4645.1  340.69
  4653.1  338.22  4795.6  333.65  4878.5  328.75  4994.0  326.36  4994.7  325.56
  5001.5  325.56  5002.2  326.36  5029.6  327.51  5115.6  327.49  5150.0  328.27
  5255.9  328.75  5340.7  327.24  5455.7  328.75  5480.3  329.10  5609.4  331.63
  5666.0  333.81  5779.1  334.64  5948.8  340.31  6062.3  342.83  6132.7  348.99
#Mann=7,-1,0
  4361.0    0.05       0  4994.0    0.03       0  5002.2    0.05       0
  5115.6    0.05       0  5150.0    0.16       0  5480.3    0.05       0
  6062.3     0.1       0
Bank Sta=4878.5,5455.7
Exp/Cntr=0.3,0.1

Type RM Length L Ch R = 1,8857,758,758,758
BEGIN DESCRIPTION:
EDMOORE CREEK 10.0
END DESCRIPTION:
XS GIS Cut Line= 3
      2916674.97      6966074.97      2915875.00      6965325.00
      2915075.02      6966074.98
#Sta/Elev= 30
  3744.4  353.31  3761.9  350.54  3786.6  347.67  3820.6  346.20  3871.6  341.56
  3967.3  335.96  4084.1  333.06  4185.9  328.81  4246.5  328.78  4275.1  328.84
  4296.1  330.82  4310.2  328.48  4324.4  327.77  4409.4  326.82  4734.7  325.79
  4822.9  324.33  4823.6  323.53  4831.1  324.33  4962.8  325.40  4996.5  326.06
  5010.7  325.15  5046.3  326.56  5258.3  325.67  5407.0  326.82  5517.7  327.87
  5532.6  328.72  5656.5  330.29  5845.5  334.25  5887.9  336.47  5937.5  340.93
#Mann=12,-1,0
  3744.4    0.16       0  3761.9    0.08       0  3820.6    0.16       0
  3967.3    0.05       0  4185.9    0.16       0  4246.5    0.05       0
  4822.9    0.07       0  4831.1    0.05       0  4962.8    0.12       0
  5517.7    0.16       0  5532.6    0.12       0  5656.5    0.05       0
Bank Sta=4409.4,5407
Exp/Cntr=0.3,0.1

Type RM Length L Ch R = 1,8099,562,562,562
BEGIN DESCRIPTION:
EDMOORE CREEK 9.0
END DESCRIPTION:
XS GIS Cut Line= 3
      2917425.00      6965225.00      2915875.00      6964725.00
      2914274.99      6965825.00
#Sta/Elev= 30
  3354.1  346.22  3517.1  337.43  3579.2  334.64  3611.5  333.95  4019.1  326.37
  4091.9  325.69  4232.7  324.38  4266.3  324.40  4328.7  326.88  4439.3  323.42
  4547.7  323.27  4548.4  322.47  4556.2  323.27  4609.9  323.30  4645.8  323.41
  5002.4  323.96  5024.6  323.44  5199.2  325.43  5756.2  325.69  5881.3  326.46
  5940.1  329.71  6068.6  331.62  6212.0  341.78  6305.5  351.31  6353.0  352.06
  6392.5  352.18  6549.6  355.80  6686.9  361.05  6839.2  369.75  6924.4  371.35
#Mann=18,-1,0
  3354.1    0.12       0  3517.1    0.16       0  3579.2    0.12       0
  3611.5    0.16       0  4019.1    0.12       0  4232.7    0.05       0
  4266.3    0.07       0  4328.7    0.12       0  4439.3    0.07       0
  4547.7    0.07       0  4556.2    0.07       0  4609.9    0.05       0
  4645.8    0.12       0  5002.4    0.05       0  5024.6    0.12       0
  5881.3    0.16       0  6353.0     0.1       0  6392.5    0.16       0
Bank Sta=4091.9,5756.2
Exp/Cntr=0.3,0.1

Type RM Length L Ch R = 1,7537,631,631,631
BEGIN DESCRIPTION:
Mapping XS 7299e7f5
END DESCRIPTION:
XS GIS Cut Line= 3
      2918005.14      6965226.75      2915726.52      6964224.16
      2913760.39      6965825.71
#Sta/Elev= 30
  2452.1  374.56  2552.1  370.95  2919.7  355.22  3133.9  341.65  3299.4  333.49
  3511.5  327.52  3641.3  325.06  4128.7  323.45  4204.9  325.44  4419.0  324.59
  4526.1  324.41  4641.9  323.42  4740.3  324.27  4927.8  323.52  5109.1  322.83
  5109.9  322.03  5117.6  322.83  5263.5  325.60  5455.2  322.97  6066.1  325.06
  6172.6  335.57  6250.9  339.09  6357.9  337.69  6470.4  343.06  6891.2  362.41
  7017.4  361.07  7300.4  357.69  7417.1  357.45  7430.6  361.01  7477.4  362.76
#Mann=20,-1,0
  2452.1    0.05       0  2552.1    0.16       0  2919.7    0.12       0
  3133.9    0.12       0  3299.4    0.16       0  3511.5    0.12       0
  4128.7    0.05       0  4204.9    0.07       0  4419.0    0.05       0
  4526.1    0.07       0  4641.9    0.05       0  4740.3    0.07       0
  4927.8    0.12       0  5109.1    0.07       0  5117.6    0.12       0
  6470.4    0.16       0  6891.2     0.1       0  7017.4    0.16       0
  7300.4    0.05       0  7430.6    0.16       0
Bank Sta=3641.3,6066.1
Exp/Cntr=0.3,0.1