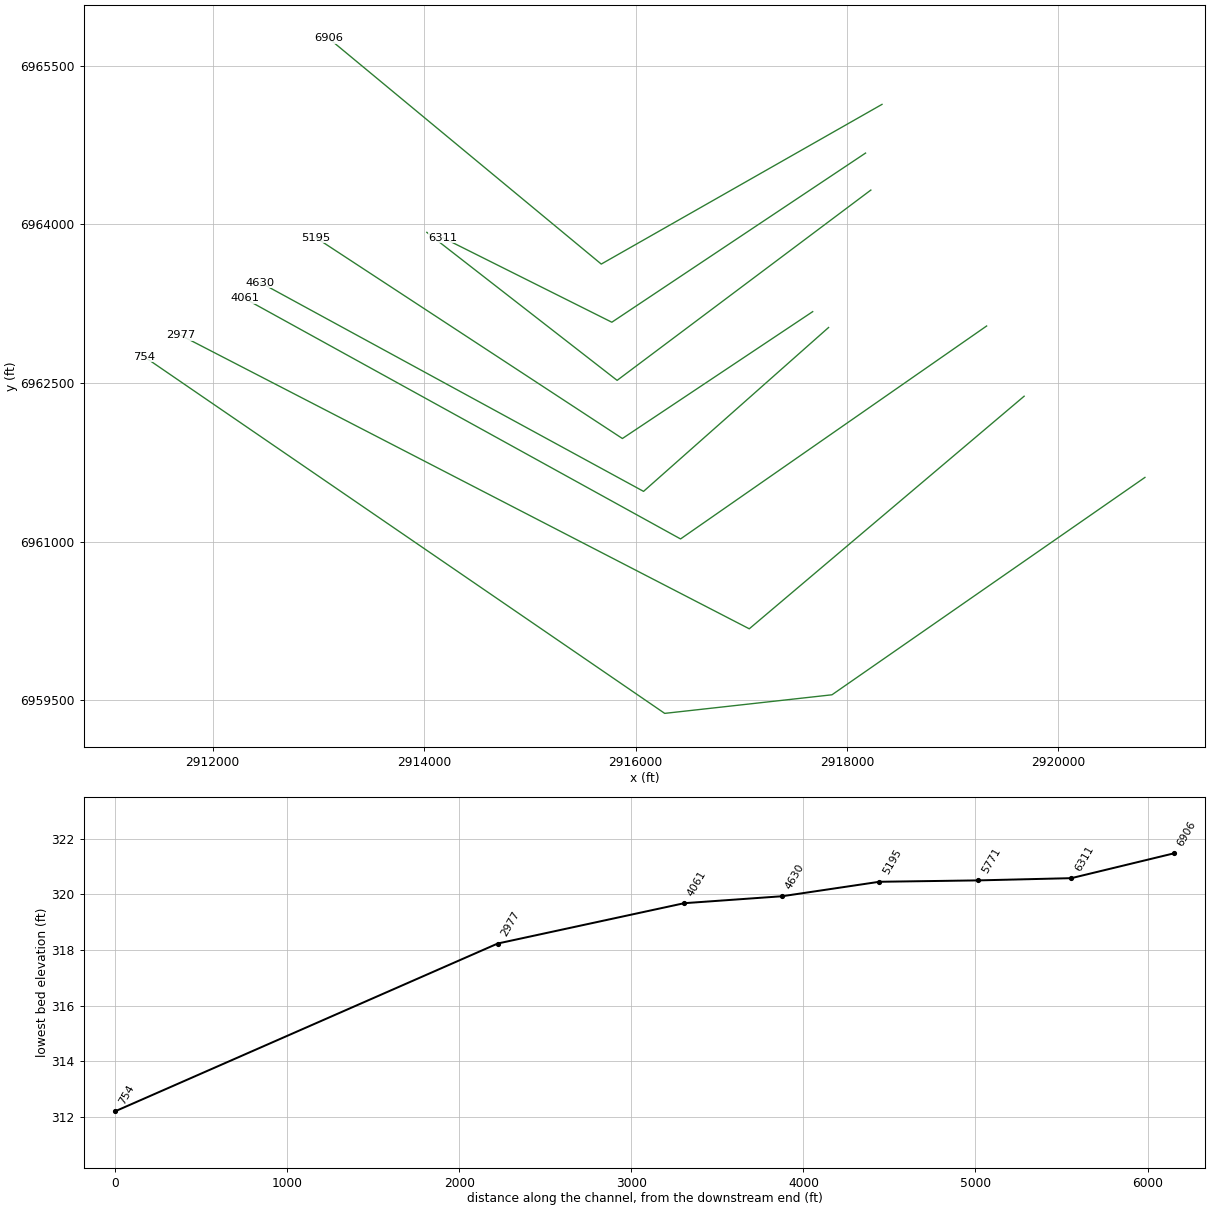
HEC-RAS study EDMOORE CREEK.prj: EDMOORE CREEK Base Level Engineering

--- EDMOORE CREEK.g01 (geometry) --- (continued)

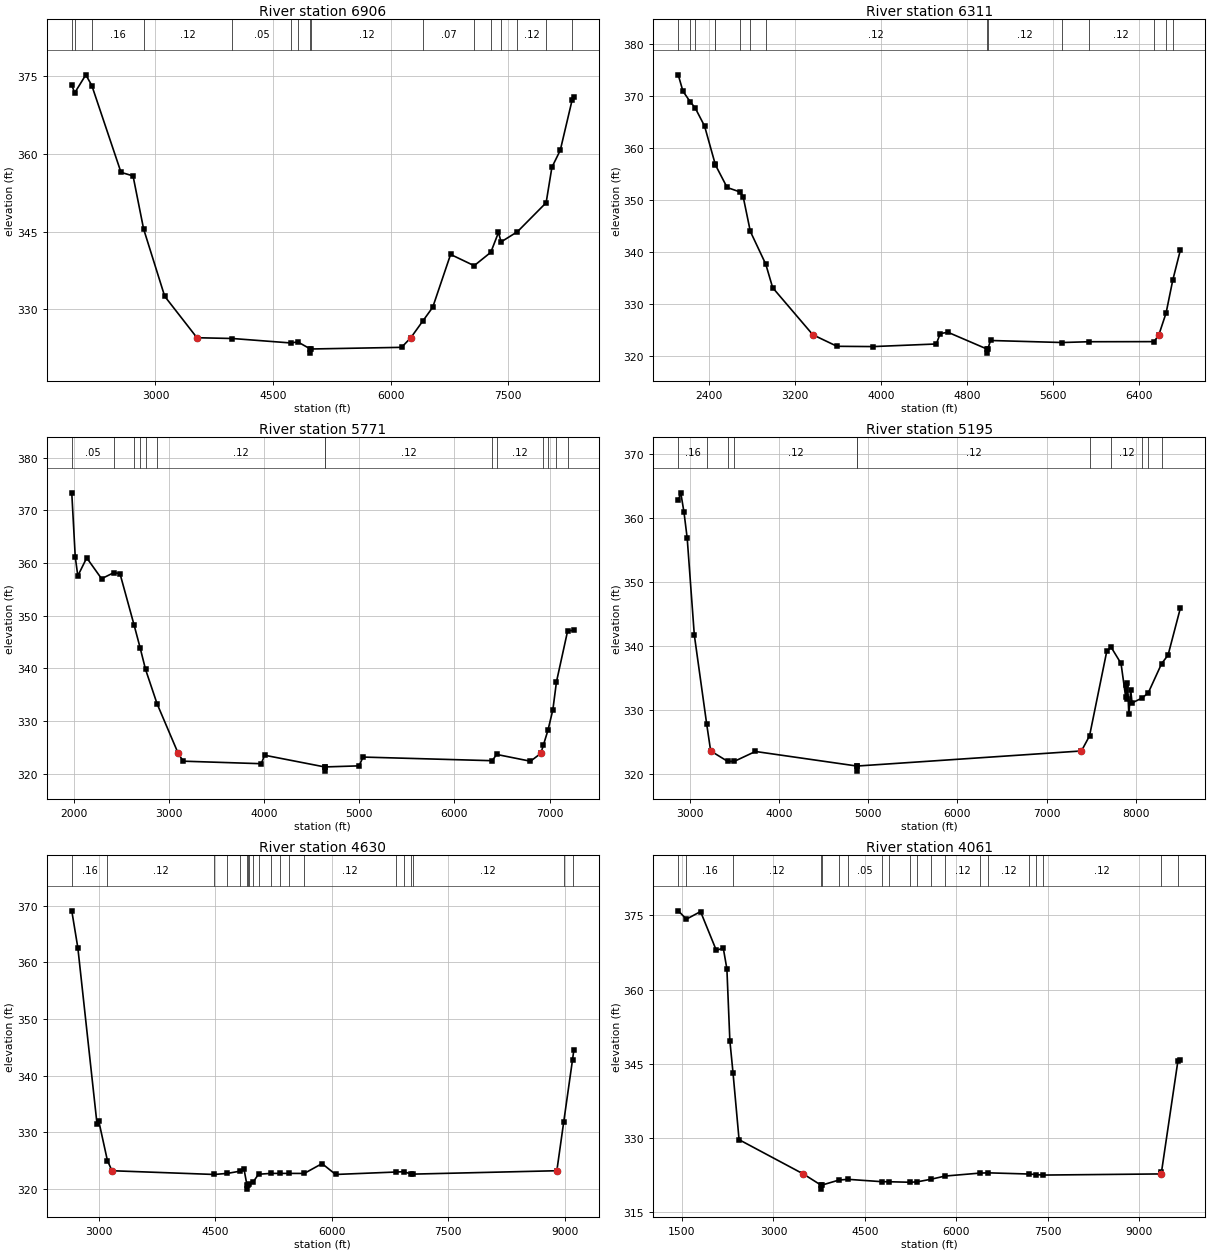
Type RM Length L Ch R = 1,6906,595,595,595
BEGIN DESCRIPTION:
EDMOORE CREEK 8.0
END DESCRIPTION:
XS GIS Cut Line= 3
      2918330.70      6965135.62      2915675.00      6963625.00
      2913096.68      6965760.31
#Sta/Elev= 30
  1932.5  373.34  1969.4  371.82  2111.6  375.32  2188.1  373.25  2560.3  356.45
  2714.0  355.76  2848.4  345.51  3117.6  332.47  3529.1  324.45  3981.5  324.30
  4724.0  323.44  4814.7  323.64  4975.5  322.27  4976.3  321.47  4984.2  322.27
  6138.5  322.59  6256.4  324.45  6405.8  327.61  6535.7  330.34  6763.7  340.57
  7064.3  338.39  7276.6  340.98  7374.5  344.82  7407.7  342.99  7616.6  344.97
  7982.0  350.57  8055.7  357.43  8162.5  360.73  8312.3  370.37  8335.5  371.05
#Mann=16,-1,0
  1932.5    0.16       0  1969.4    0.05       0  2188.1    0.16       0
  2848.4    0.12       0  3981.5    0.05       0  4724.0    0.07       0
  4814.7    0.12       0  4975.5    0.07       0  4984.2    0.12       0
  6405.8    0.07       0  7064.3    0.16       0  7276.6    0.05       0
  7407.7    0.16       0  7616.6    0.12       0  7982.0    0.16       0
  8312.3    0.07       0
Bank Sta=3529.1,6256.4
Exp/Cntr=0.3,0.1

Type RM Length L Ch R = 1,6311,540,540,540
BEGIN DESCRIPTION:
EDMOORE CREEK 7.0
END DESCRIPTION:
XS GIS Cut Line= 3
      2918175.02      6964675.01      2915775.00      6963075.00
      2914175.02      6963874.99
#Sta/Elev= 30
  2113.0  374.08  2156.6  370.94  2224.7  368.89  2269.6  367.76  2357.9  364.24
  2455.9  357.00  2459.1  356.76  2568.2  352.42  2688.7  351.56  2718.5  350.54
  2784.0  343.98  2927.9  337.67  2991.9  333.16  3365.8  324.11  3591.3  321.89
  3929.3  321.84  4515.2  322.34  4551.3  324.33  4623.4  324.59  4985.4  321.38
  4986.3  320.58  4994.6  321.38  5019.8  323.01  5686.9  322.62  5932.5  322.77
  6542.3  322.79  6586.8  324.11  6653.9  328.30  6715.9  334.60  6786.3  340.35
#Mann=15,-1,0
  2113.0    0.08       0  2224.7    0.16       0  2269.6    0.05       0
  2455.9    0.08       0  2459.1    0.05       0  2688.7    0.16       0
  2784.0    0.05       0  2927.9    0.12       0  4985.4    0.07       0
  4994.6    0.12       0  5686.9    0.07       0  5932.5    0.12       0
  6542.3    0.16       0  6653.9    0.12       0  6715.9    0.16       0
Bank Sta=3365.8,6586.8
Exp/Cntr=0.3,0.1

Type RM Length L Ch R = 1,5771,576,576,576
BEGIN DESCRIPTION:
EDMOORE CREEK 6.0
END DESCRIPTION:
XS GIS Cut Line= 3
      2918225.00      6964325.00      2915825.00      6962525.00
      2914024.96      6963925.03
#Sta/Elev= 30
  1975.4  373.35  2011.9  361.21  2038.9  357.58  2132.7  361.00  2288.9  357.04
  2418.6  358.20  2482.7  357.99  2629.5  348.33  2693.8  343.96  2751.2  339.82
  2872.8  333.28  3094.7  323.87  3147.3  322.39  3968.1  321.91  4003.5  323.52
  4634.3  321.30  4635.2  320.50  4643.5  321.30  4997.1  321.50  5038.7  323.17
  6397.3  322.48  6443.4  323.67  6799.7  322.38  6908.7  323.87  6935.7  325.46
  6983.4  328.26  7035.0  332.14  7073.1  337.47  7190.7  347.15  7255.8  347.22
#Mann=14,-1,0
  1975.4    0.05       0  2418.6    0.12       0  2629.5    0.16       0
  2693.8    0.12       0  2751.2    0.16       0  2872.8    0.12       0
  4634.3    0.07       0  4643.5    0.12       0  6397.3    0.07       0
  6443.4    0.12       0  6935.7    0.16       0  6983.4    0.12       0
  7073.1    0.16       0  7190.7    0.05       0
Bank Sta=3094.7,6908.7
Exp/Cntr=0.3,0.1

Type RM Length L Ch R = 1,5195,565,565,565
BEGIN DESCRIPTION:
EDMOORE CREEK 5.0
END DESCRIPTION:
XS GIS Cut Line= 3
      2917674.97      6963174.98      2915875.00      6961975.00
      2912974.98      6963875.01
#Sta/Elev= 30
  2870.0  362.74  2898.5  363.92  2934.6  360.88  2970.6  356.82  3050.2  341.73
  3189.0  327.81  3233.7  323.60  3423.9  321.98  3496.2  321.96  3735.3  323.52
  4871.0  321.25  4871.8  320.45  4880.2  321.25  7391.6  323.60  7482.4  325.96
  7675.7  339.18  7723.8  339.82  7835.5  337.27  7886.8  332.10  7892.8  333.83
  7901.9  331.75  7907.9  334.21  7923.0  329.30  7944.1  333.11  7959.2  331.10
  8075.0  331.90  8141.3  332.69  8290.3  337.23  8363.1  338.58  8500.3  345.88
#Mann=11,-1,0
  2870.0    0.16       0  3189.0    0.12       0  3423.9    0.07       0
  3496.2    0.12       0  4871.0    0.07       0  4880.2    0.12       0
  7482.4    0.16       0  7723.8    0.12       0  8075.0    0.16       0
  8141.3    0.12       0  8290.3    0.16       0
Bank Sta=3233.7,7391.6
Exp/Cntr=0.3,0.1

Type RM Length L Ch R = 1,4630,569,569,569
BEGIN DESCRIPTION:
EDMOORE CREEK 4.0
END DESCRIPTION:
XS GIS Cut Line= 3
      2917825.01      6963025.00      2916075.00      6961475.00
      2912450.04      6963449.98
#Sta/Elev= 30
  2650.2  369.10  2728.4  362.57  2976.0  331.36  2997.5  331.98  3109.1  324.98
  3168.0  323.18  4484.9  322.52  4654.1  322.71  4811.6  323.09  4867.7  323.51
  4905.1  320.73  4905.9  319.93  4914.4  320.73  4936.0  320.84  4987.7  321.23
  5055.2  322.56  5216.1  322.71  5330.3  322.71  5445.9  322.71  5643.7  322.70
  5873.4  324.44  6048.1  322.52  6820.7  322.95  6929.2  323.01  7016.9  322.60
  7038.5  322.58  8897.1  323.18  8984.9  331.74  9099.1  342.80  9116.0  344.50
#Mann=20,-1,0
  2650.2    0.16       0  3109.1    0.12       0  4484.9    0.05       0
  4654.1    0.12       0  4811.6    0.05       0  4905.1    0.03       0
  4914.4    0.05       0  4936.0    0.07       0  4987.7    0.05       0
  5055.2    0.07       0  5216.1    0.05       0  5330.3    0.07       0
  5445.9    0.07       0  5643.7    0.12       0  6820.7    0.05       0
  6929.2     0.1       0  7016.9    0.07       0  7038.5    0.12       0
  8984.9    0.05       0  9099.1    0.08       0
Bank Sta=3168,8897.1
Exp/Cntr=0.3,0.1

Type RM Length L Ch R = 1,4061,1084,1084,1084
BEGIN DESCRIPTION:
EDMOORE CREEK 3.0
END DESCRIPTION:
XS GIS Cut Line= 3
      2919320.26      6963039.26      2916425.00      6961025.00
      2912299.97      6963300.02
#Sta/Elev= 30
  1438.1  375.90  1573.0  374.22  1804.2  375.75  2063.4  367.90  2176.9  368.39
  2236.3  364.18  2285.1  349.68  2337.0  343.16  2436.1  329.67  3489.3  322.75
  3781.7  320.48  3782.6  319.68  3791.1  320.48  4074.3  321.51  4222.8  321.66
  4783.5  321.18  4897.1  321.17  5243.1  321.07  5358.7  321.15  5586.8  321.68
  5815.9  322.32  6388.6  322.92  6525.3  322.97  7191.7  322.73  7305.0  322.63
  7419.5  322.52  9356.0  322.75  9366.8  323.10  9636.2  345.56  9675.9  345.80
#Mann=20,-1,0
  1438.1    0.05       0  1573.0    0.16       0  2337.0    0.12       0
  3781.7    0.07       0  3791.1    0.12       0  4074.3    0.05       0
  4222.8    0.05       0  4783.5    0.07       0  4897.1    0.12       0
  5243.1    0.07       0  5358.7    0.12       0  5586.8    0.07       0
  5815.9    0.12       0  6388.6    0.05       0  6525.3    0.12       0
  7191.7    0.05       0  7305.0     0.1       0  7419.5    0.12       0
  9366.8    0.16       0  9636.2    0.08       0
Bank Sta=3489.3,9356
Exp/Cntr=0.3,0.1

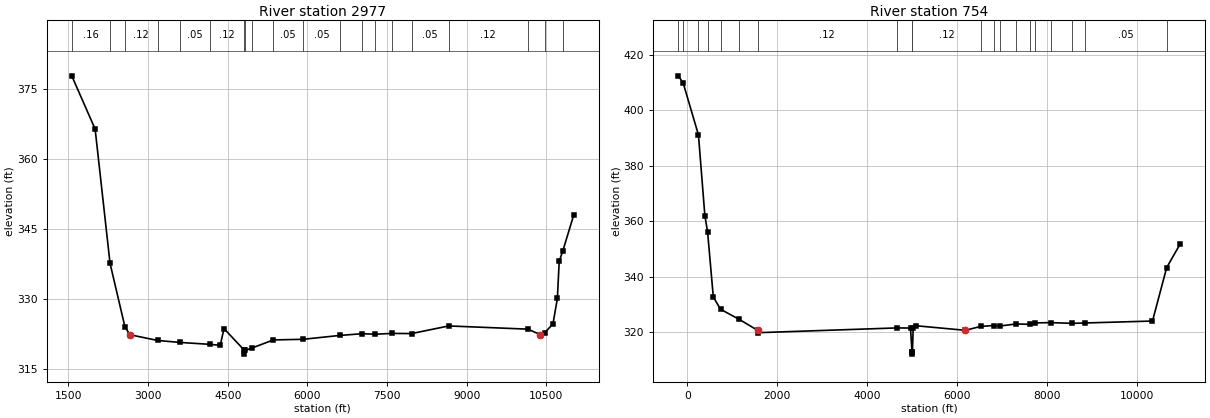
Type RM Length L Ch R = 1,2977,2223,2223,2223
BEGIN DESCRIPTION:
EDMOORE CREEK 2.0
END DESCRIPTION:
XS GIS Cut Line= 3
      2919675.03      6962375.03      2917075.00      6960175.00
      2911699.99      6962950.00
#Sta/Elev= 30
  1561.8  377.85  2001.9  366.43  2282.3  337.69  2561.8  324.13  2656.0  322.39
  3181.2  321.15  3595.6  320.74  4157.2  320.33  4357.4  320.12  4428.9  323.70
  4813.6  319.03  4814.4  318.23  4824.2  319.03  4965.1  319.58  5357.2  321.27
  5921.7  321.41  6603.9  322.23  7026.4  322.60  7278.0  322.50  7595.1  322.67
  7959.8  322.63  8660.8  324.27 10153.0  323.58 10387.5  322.39 10471.0  322.84
 10623.7  324.72 10706.6  330.15 10741.1  338.12 10809.3  340.35 11016.8  348.12
#Mann=20,-1,0
  1561.8    0.16       0  2282.3    0.12       0  2561.8    0.12       0
  3181.2    0.05       0  3595.6    0.05       0  4157.2    0.12       0
  4813.6    0.07       0  4824.2    0.12       0  4965.1    0.12       0
  5357.2    0.05       0  5921.7    0.05       0  6603.9    0.07       0
  7026.4    0.07       0  7278.0    0.05       0  7595.1    0.05       0
  7959.8    0.05       0  8660.8    0.12       0 10153.0    0.05       0
 10471.0    0.05       0 10809.3    0.05       0
Bank Sta=2656,10387.5
Exp/Cntr=0.3,0.1

Type RM Length L Ch R = 1,754,0,0,0
BEGIN DESCRIPTION:
EDMOORE CREEK 1.0
END DESCRIPTION:
XS GIS Cut Line= 4
      2920817.63      6961606.94      2917857.47      6959550.83
      2916275.00      6959375.00      2911350.03      6962749.98
#Sta/Elev= 30
  -201.5  412.45   -91.9  409.89   248.1  391.15   390.7  362.13   451.3  356.24
   578.4  332.79   738.7  328.36  1159.0  324.68  1564.1  320.78  1569.3  319.92
  4660.9  321.64  4964.7  321.60  4996.9  313.00  4997.7  312.20  5007.7  313.00
  5023.3  321.50  5089.0  322.42  6184.3  320.78  6522.8  322.17  6811.4  322.51
  6956.9  322.33  7313.7  323.07  7623.4  322.93  7742.6  323.45  8083.5  323.55
  8558.4  323.29  8840.4  323.42 10346.6  324.12 10662.2  343.38 10965.3  351.97
#Mann=20,-1,0
  -201.5    0.05       0   -91.9    0.16       0   248.1    0.16       0
   451.3    0.05       0   738.7    0.12       0  1159.0    0.05       0
  1569.3    0.12       0  4660.9    0.12       0  4996.9    0.07       0
  5007.7    0.12       0  6522.8    0.12       0  6811.4    0.05       0
  6956.9    0.05       0  7313.7    0.07       0  7623.4    0.07       0
  7742.6    0.12       0  8083.5    0.05       0  8558.4    0.07       0
  8840.4    0.05       0 10662.2    0.05       0
Bank Sta=1564.1,6184.3
Exp/Cntr=0.3,0.1

Chan Stop Cuts=-1