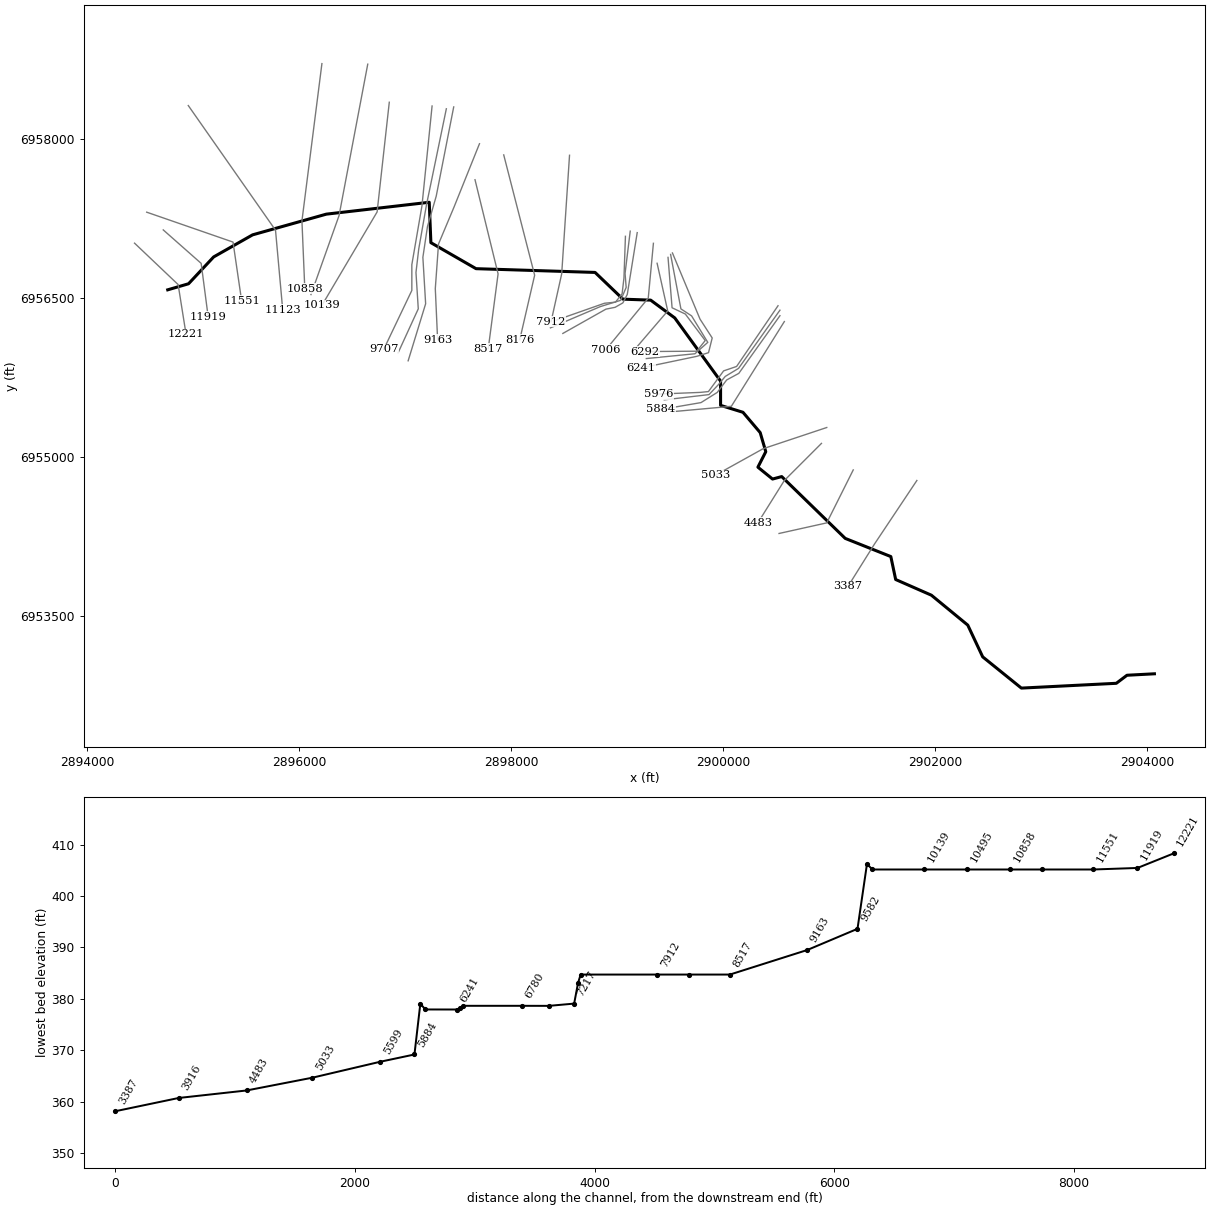
--- FOURMILE BRANCH.prj (project) ---

Proj Title=FOURMILE BRANCH Base Level Engineering
Current Plan=p01
Default Exp/Contr=0.3,0.1
English Units
Geom File=g01
Flow File=f01
Plan File=p01
BEGIN DESCRIPTION:
FOURMILE BRANCH
END DESCRIPTION:

--- FOURMILE BRANCH.p01 (plan) ---

Plan Title=Multiple Run
Short Identifier=Multiple
Geom File=g01
Flow File=f01
Subcritical Flow
K Sum by GR= 0
Std Step Tol= 0.01
Critical Tol= 0.01
Num of Std Step Trials= 20
Max Error Tol= 0.3
Flow Tol Ratio= 0.001
Split Flow NTrial= 30
Split Flow Tol= 0.02
Split Flow Ratio= 0.02
Log Output Level= 0
Friction Slope Method= 1
Unsteady Friction Slope Method= 2
Unsteady Bridges Friction Slope Method= 1
Parabolic Critical Depth
Global Vel Dist=  1 , 1 , 1
Global Log Level= 0
CheckData=True
Encroach Param= -1, 0, 0, 0
BEGIN DESCRIPTION:
Multiple Run
END DESCRIPTION:

--- FOURMILE BRANCH.f01 (steady flow) ---

Flow Title=Multiple
Number of Profiles=7
Profile Names=10-year,25-year,50-year,1pct_min,100-year,1pct_plu,500-year
River Rch & RM= FOURMILE BRANCH,Reach-1,12221
     578     785     956     580    1157    2309    1697
River Rch & RM= FOURMILE BRANCH,Reach-1,11123
    1008    1408    1746    1076    2147    4284    3252
River Rch & RM= FOURMILE BRANCH,Reach-1,5599
    1192    1677    2089    1293    2579    5146    3939
River Rch & RM= FOURMILE BRANCH,Reach-1,1762
    1230    1732    2160    1337    2667    5322    4078
River Rch & RM= FOURMILE BRANCH,Reach-1,520
    2024    2920    3702    2327    4642    9262    7318
Boundary for River Rch & Prof#=FOURMILE BRANCH,Reach-1,1
Up Type=0
Dn Type=3
Dn Slope=0.005
Boundary for River Rch & Prof#=FOURMILE BRANCH,Reach-1,2
Up Type=0
Dn Type=3
Dn Slope=0.005
Boundary for River Rch & Prof#=FOURMILE BRANCH,Reach-1,3
Up Type=0
Dn Type=3
Dn Slope=0.005
Boundary for River Rch & Prof#=FOURMILE BRANCH,Reach-1,4
Up Type=0
Dn Type=3
Dn Slope=0.005
Boundary for River Rch & Prof#=FOURMILE BRANCH,Reach-1,5
Up Type=0
Dn Type=3
Dn Slope=0.005
Boundary for River Rch & Prof#=FOURMILE BRANCH,Reach-1,6
Up Type=0
Dn Type=3
Dn Slope=0.005
Boundary for River Rch & Prof#=FOURMILE BRANCH,Reach-1,7
Up Type=0
Dn Type=3
Dn Slope=0.005

--- FOURMILE BRANCH.g01 (geometry) ---

Geom Title=Existing Conditions

River Reach=FOURMILE BRANCH,Reach-1
Reach XY= 30
      2894759.01      6956574.43      2894955.50      6956631.70
      2895192.34      6956884.95      2895559.52      6957093.28
      2896254.84      6957288.60      2897225.59      6957400.71
      2897241.24      6957019.40      2897666.98      6956774.08
      2898789.74      6956738.65      2899052.93      6956486.29
      2899314.12      6956477.17      2899541.30      6956309.43
      2899973.59      6955713.08      2899973.59      6955483.91
      2900184.83      6955418.61      2900347.20      6955227.03
      2900399.98      6955046.82      2900325.59      6954900.71
      2900463.66      6954788.70      2900550.15      6954811.85
      2901149.28      6954228.52      2901579.31      6954057.12
      2901625.14      6953840.41      2901962.03      6953692.46
      2902305.17      6953410.04      2902445.83      6953110.54
      2902810.63      6952815.73      2903706.17      6952861.03
      2903806.81      6952936.99      2904065.59      6952950.71

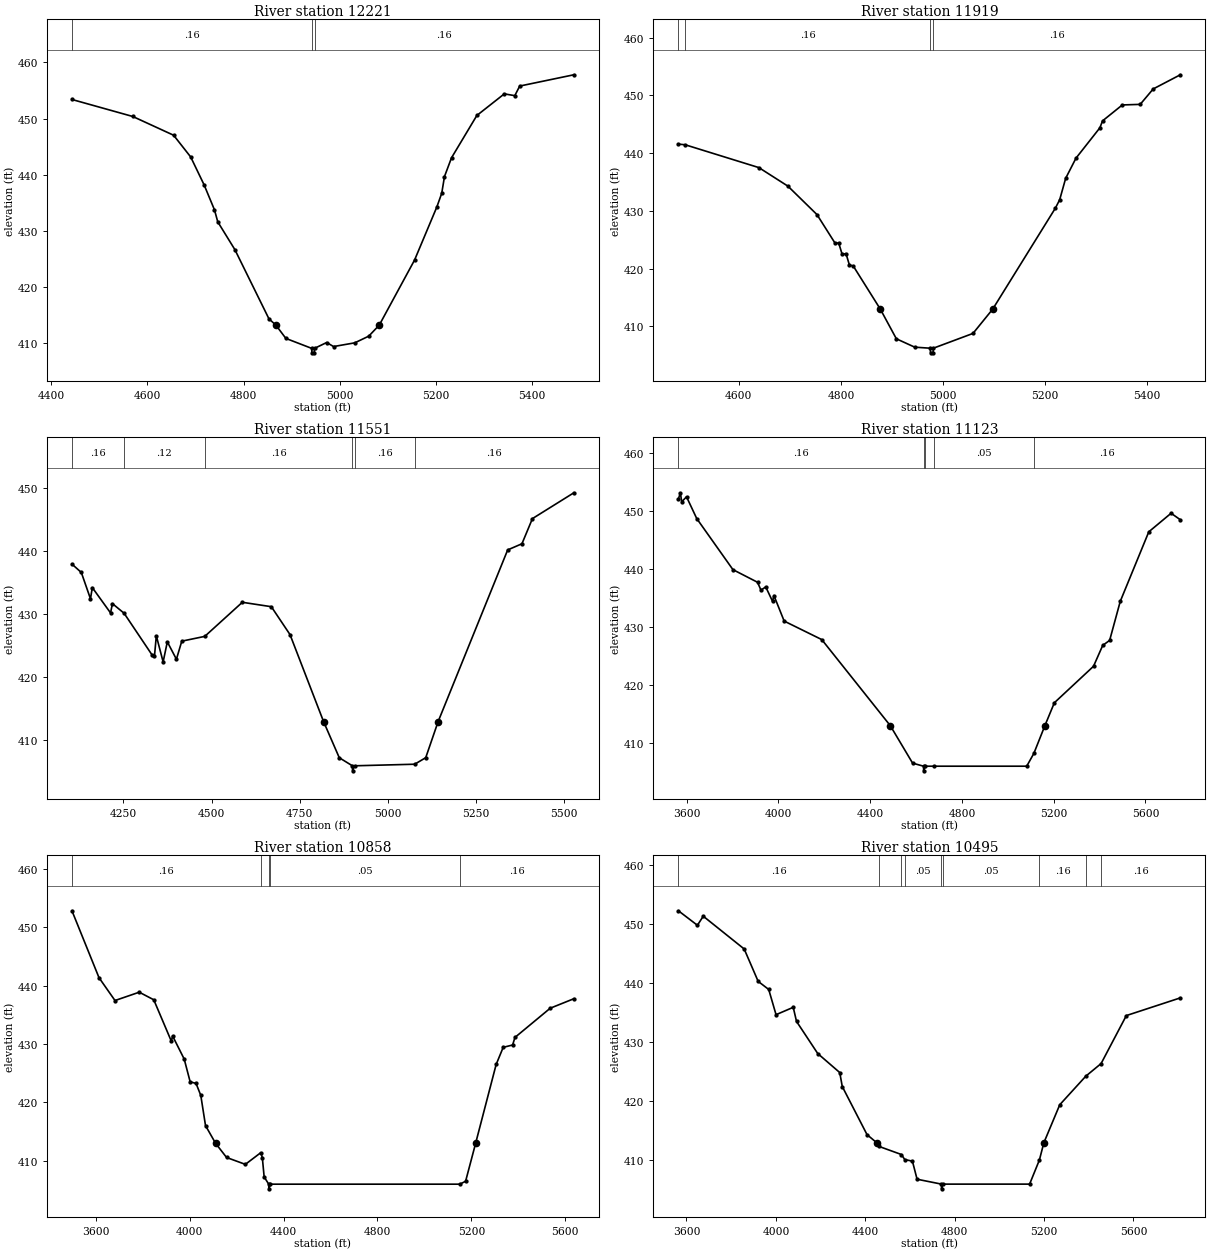
Type RM Length L Ch R = 1,12221,302,302,302
BEGIN DESCRIPTION:
FOURMILE BRANCH 23.0
END DESCRIPTION:
XS GIS Cut Line= 3
      2894446.04      6957014.93      2894857.38      6956623.89
      2894932.17      6956153.76
#Sta/Elev= 30
  4443.0  453.40  4569.5  450.37  4654.4  447.03  4689.9  443.16  4717.9  438.17
  4739.3  433.75  4746.2  431.60  4781.8  426.65  4852.6  414.33  4867.0  413.21
  4887.8  410.84  4941.4  409.07  4941.9  408.27  4946.9  408.27  4947.4  409.07
  4972.7  410.11  4986.9  409.39  5031.0  410.05  5060.1  411.24  5082.0  413.21
  5155.4  424.80  5201.8  434.27  5211.9  436.70  5217.6  439.67  5232.2  443.01
  5284.9  450.55  5342.0  454.40  5363.8  454.08  5374.0  455.79  5486.6  457.80
#Mann=3,-1,0
  4443.0    0.16       0  4941.4    0.07       0  4947.4    0.16       0
Bank Sta=4867,5082
Exp/Cntr=0.3,0.1

Type RM Length L Ch R = 1,11919,368,368,368
BEGIN DESCRIPTION:
Mapping XS 449ec4d1
END DESCRIPTION:
XS GIS Cut Line= 3
      2894716.90      6957139.90      2895074.53      6956823.94
      2895140.25      6956322.33
#Sta/Elev= 30
  4481.6  441.55  4494.9  441.44  4639.2  437.49  4696.1  434.28  4753.0  429.36
  4788.1  424.46  4795.6  424.43  4802.3  422.49  4809.9  422.60  4816.5  420.64
  4824.1  420.46  4877.1  413.00  4908.5  407.87  4944.5  406.42  4974.9  406.24
  4975.4  405.44  4980.4  405.44  4980.9  406.24  5058.6  408.80  5097.2  413.00
  5220.0  430.48  5228.4  431.93  5240.1  435.63  5260.3  439.12  5307.2  444.38
  5312.3  445.57  5351.1  448.33  5386.1  448.43  5411.6  451.10  5464.7  453.55
#Mann=4,-1,0
  4481.6    0.12       0  4494.9    0.16       0  4974.9    0.07       0
  4980.9    0.16       0
Bank Sta=4877.1,5097.2
Exp/Cntr=0.3,0.1

Type RM Length L Ch R = 1,11551,428,428,428
BEGIN DESCRIPTION:
FOURMILE BRANCH 22.0
END DESCRIPTION:
XS GIS Cut Line= 3
      2894560.65      6957307.27      2895375.00      6957025.00
      2895456.39      6956469.31
#Sta/Elev= 30
  4104.2  437.95  4130.8  436.62  4156.7  432.45  4162.0  434.22  4213.7  430.20
  4219.0  431.68  4252.1  430.15  4331.1  423.56  4338.2  423.32  4343.5  426.57
  4362.8  422.43  4374.7  425.61  4400.5  422.85  4415.7  425.72  4480.9  426.48
  4587.4  431.89  4669.7  431.19  4722.7  426.76  4817.9  412.95  4862.4  407.22
  4899.6  405.94  4900.1  405.14  4905.6  405.94  5076.3  406.19  5107.6  407.23
  5142.7  412.95  5340.0  440.20  5380.5  441.18  5410.2  445.17  5527.7  449.27
#Mann=6,-1,0
  4104.2    0.16       0  4252.1    0.12       0  4480.9    0.16       0
  4899.6   0.033       0  4905.6    0.16       0  5076.3    0.16       0
Bank Sta=4817.9,5142.7
Exp/Cntr=0.3,0.1

Type RM Length L Ch R = 1,11123,265,265,265
BEGIN DESCRIPTION:
FOURMILE BRANCH 21.0
END DESCRIPTION:
XS GIS Cut Line= 3
      2894952.98      6958313.54      2895775.75      6957137.23
      2895843.47      6956388.19
#Sta/Elev= 30
  3564.5  452.00  3572.8  453.08  3578.9  451.52  3599.8  452.39  3644.3  448.64
  3802.1  439.83  3909.4  437.65  3924.2  436.30  3945.1  436.85  3974.8  434.36
  3980.9  435.36  4025.4  430.96  4189.3  427.77  4487.8  412.94  4585.2  406.47
  4632.8  405.94  4633.3  405.14  4638.8  405.94  4676.5  405.94  5082.6  405.94
  5113.7  408.14  5161.9  412.94  5203.1  416.88  5373.8  423.17  5413.9  426.77
  5444.0  427.63  5490.3  434.36  5614.7  446.35  5711.9  449.55  5752.1  448.43
#Mann=5,-1,0
  3564.5    0.16       0  4632.8   0.033       0  4638.8    0.16       0
  4676.5    0.05       0  5113.7    0.16       0
Bank Sta=4487.8,5161.9
Exp/Cntr=0.3,0.1

Type RM Length L Ch R = 1,10858,363,363,363
BEGIN DESCRIPTION:
FOURMILE BRANCH 20.0
END DESCRIPTION:
XS GIS Cut Line= 3
      2896213.41      6958709.32      2896025.00      6957225.00
      2896051.96      6956584.39
#Sta/Elev= 30
  3498.8  452.85  3614.0  441.37  3682.1  437.45  3785.4  438.88  3847.2  437.58
  3922.2  430.46  3927.3  431.38  3976.9  427.40  4002.2  423.50  4027.3  423.23
  4047.5  421.17  4067.6  415.99  4110.7  412.94  4157.3  410.52  4237.3  409.34
  4303.1  411.35  4309.6  410.47  4317.3  407.19  4336.8  405.94  4337.3  405.14
  4342.8  405.94  5150.4  405.94  5175.2  406.44  5217.8  412.94  5305.3  426.48
  5335.3  429.42  5375.4  429.82  5385.4  431.12  5535.5  436.13  5636.2  437.76
#Mann=5,-1,0
  3498.8    0.16       0  4303.1    0.05       0  4336.8   0.033       0
  4342.8    0.05       0  5150.4    0.16       0
Bank Sta=4110.7,5217.8
Exp/Cntr=0.3,0.1

Type RM Length L Ch R = 1,10495,356,356,356
BEGIN DESCRIPTION:
FOURMILE BRANCH 19.0
END DESCRIPTION:
XS GIS Cut Line= 3
      2896645.71      6958704.15      2896375.00      6957275.00
      2896110.16      6956529.62
#Sta/Elev= 30
  3563.9  452.29  3648.9  449.83  3675.0  451.37  3858.2  445.81  3920.7  440.32
  3967.9  438.95  4000.7  434.67  4077.6  435.92  4092.3  433.53  4187.3  428.08
  4285.7  424.86  4297.0  422.49  4407.8  414.33  4451.9  412.94  4461.6  412.33
  4561.6  410.96  4576.4  410.11  4610.9  409.83  4631.7  406.77  4740.7  405.94
  4741.2  405.14  4746.7  405.94  5135.2  405.94  5178.9  410.02  5198.8  412.94
  5270.1  419.40  5386.8  424.25  5455.0  426.38  5568.0  434.52  5809.5  437.52
#Mann=9,-1,0
  3563.9    0.16       0  4461.6    0.05       0  4561.6    0.08       0
  4576.4    0.05       0  4740.7   0.033       0  4746.7    0.05       0
  5178.9    0.16       0  5386.8    0.08       0  5455.0    0.16       0
Bank Sta=4451.9,5198.8
Exp/Cntr=0.3,0.1

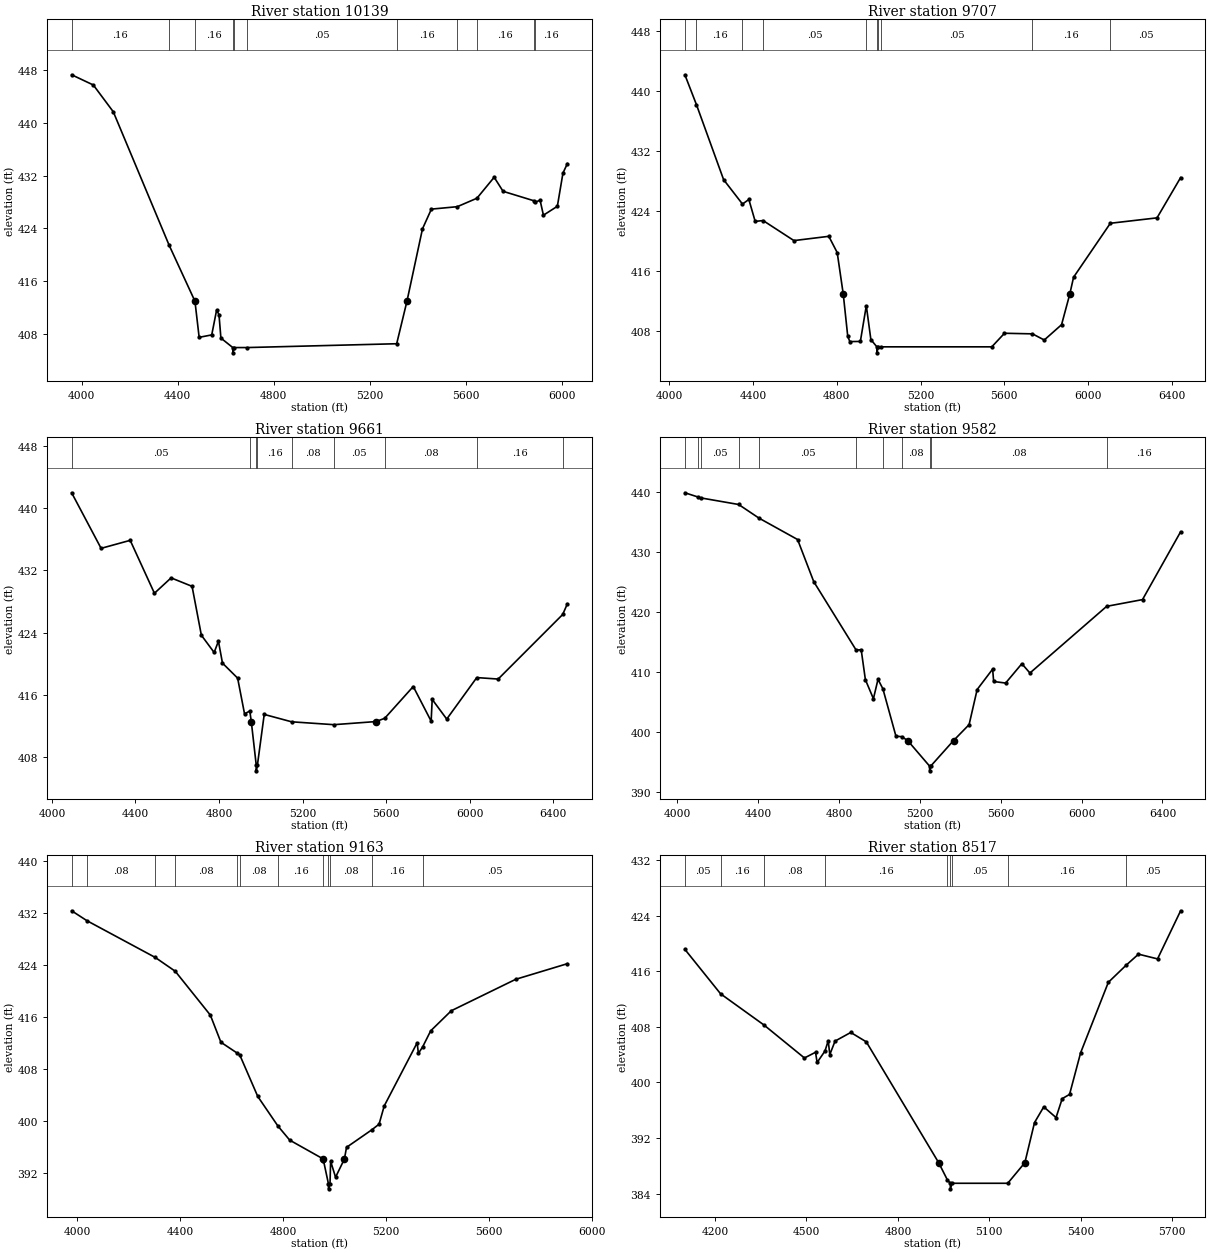
Type RM Length L Ch R = 1,10139,432,432,432
BEGIN DESCRIPTION:
FOURMILE BRANCH 18.0
END DESCRIPTION:
XS GIS Cut Line= 3
      2896848.83      6958344.78      2896734.00      6957309.43
      2896213.97      6956429.05
#Sta/Elev= 30
  3958.3  447.30  4048.6  445.75  4131.7  441.69  4364.3  421.45  4471.7  412.97
  4471.8  412.94  4489.2  407.49  4541.6  407.86  4561.8  411.60  4571.8  410.95
  4579.8  407.38  4629.2  405.94  4629.7  405.14  4635.2  405.94  4688.2  405.94
  5311.7  406.52  5354.3  412.94  5419.1  423.94  5456.2  426.93  5564.0  427.30
  5645.8  428.58  5717.6  431.76  5754.7  429.63  5882.8  428.20  5886.4  427.96
  5908.8  428.28  5922.7  426.01  5980.7  427.36  6004.0  432.39  6022.5  433.84
#Mann=11,-1,0
  3958.3    0.16       0  4364.3    0.05       0  4471.7    0.16       0
  4629.2   0.033       0  4635.2    0.16       0  4688.2    0.05       0
  5311.7    0.16       0  5564.0    0.08       0  5645.8    0.16       0
  5882.8    0.08       0  5886.4    0.16       0
Bank Sta=4471.8,5354.3
Exp/Cntr=0.3,0.1

Type RM Length L Ch R = 1,9707,46,46,46
BEGIN DESCRIPTION:
Mapping XS df39447a
END DESCRIPTION:
XS GIS Cut Line= 5
      2897252.48      6958309.19      2897156.99      6957367.34
      2897061.51      6956811.78      2897061.51      6956568.73
      2896796.77      6956013.22
#Sta/Elev= 30
  4073.9  442.20  4129.3  438.21  4259.0  428.22  4349.2  424.97  4379.6  425.58
  4409.8  422.66  4447.8  422.77  4595.0  420.10  4761.6  420.67  4801.8  418.50
  4830.8  412.94  4852.1  407.34  4862.1  406.64  4912.4  406.66  4940.8  411.42
  4962.6  406.91  4991.2  405.94  4991.7  405.14  4997.4  405.94  5009.6  405.94
  5540.4  405.94  5601.1  407.75  5734.7  407.67  5791.1  406.85  5873.8  408.89
  5912.8  412.94  5931.2  415.22  6106.9  422.41  6329.9  423.13  6442.7  428.50
#Mann=10,-1,0
  4073.9    0.05       0  4129.3    0.16       0  4349.2    0.08       0
  4447.8    0.05       0  4940.8    0.16       0  4991.2    0.07       0
  4997.4    0.16       0  5009.6    0.05       0  5734.7    0.16       0
  6106.9    0.05       0
Bank Sta=4830.8,5912.8
Exp/Cntr=0.3,0.1

Type RM Length L Ch R = 1,9661,79,79,79
BEGIN DESCRIPTION:
Mapping XS 97bc9549
END DESCRIPTION:
XS GIS Cut Line= 6
      2897387.02      6958283.12      2897200.40      6957380.36
      2897126.61      6956959.35      2897100.57      6956738.00
      2897122.27      6956395.12      2896931.66      6955979.24
#Sta/Elev= 30
  4094.6  441.98  4235.6  434.83  4374.9  435.86  4490.9  429.05  4570.7  431.03
  4671.1  429.94  4715.6  423.65  4776.8  421.43  4797.3  422.88  4816.7  420.06
  4889.2  418.13  4922.3  413.53  4947.5  413.90  4954.6  412.54  4978.0  407.00
  4978.5  406.20  4984.2  407.00  5016.5  413.46  5147.5  412.51  5349.9  412.14
  5551.1  412.54  5593.3  412.96  5729.9  417.05  5815.6  412.59  5820.6  415.39
  5890.2  412.86  6034.0  418.20  6136.4  418.01  6445.3  426.32  6467.8  427.70
#Mann=9,-1,0
  4094.6    0.05       0  4947.5    0.16       0  4978.0    0.07       0
  4984.2    0.16       0  5147.5    0.08       0  5349.9    0.05       0
  5593.3    0.08       0  6034.0    0.16       0  6445.3    0.05       0
Bank Sta=4954.6,5551.1
Exp/Cntr=0.3,0.1

Type RM Length L Ch R = 1,9582,419,419,419
BEGIN DESCRIPTION:
Mapping XS d297055a
END DESCRIPTION:
XS GIS Cut Line= 6
      2897456.48      6958300.53      2897291.54      6957458.48
      2897209.08      6957172.03      2897165.67      6956881.23
      2897191.71      6956442.86      2897026.79      6955904.67
#Sta/Elev= 30
  4037.6  439.88  4103.2  439.17  4117.6  439.02  4303.6  437.93  4403.8  435.67
  4595.1  432.10  4675.0  425.09  4884.9  413.69  4909.7  413.76  4930.5  408.77
  4970.2  405.60  4992.9  408.83  5017.0  407.26  5081.7  399.36  5110.0  399.29
  5139.7  398.64  5247.7  394.40  5248.2  393.60  5253.9  394.40  5366.6  398.64
  5443.5  401.29  5483.3  407.13  5559.9  410.53  5564.9  408.47  5624.2  408.21
  5704.4  411.43  5744.4  409.88  6124.0  420.98  6301.2  422.10  6489.8  433.39
#Mann=11,-1,0
  4037.6    0.05       0  4103.2    0.08       0  4117.6    0.05       0
  4303.6    0.08       0  4403.8    0.05       0  4884.9    0.08       0
  5017.0    0.16       0  5110.0    0.08       0  5247.7    0.07       0
  5253.9    0.08       0  6124.0    0.16       0
Bank Sta=5139.7,5366.6
Exp/Cntr=0.3,0.1

Type RM Length L Ch R = 1,9163,646,646,646
BEGIN DESCRIPTION:
Mapping XS dce346e2
END DESCRIPTION:
XS GIS Cut Line= 5
      2897699.51      6957953.24      2897460.81      6957358.66
      2897313.24      6957007.10      2897282.86      6956586.09
      2897304.56      6956104.37
#Sta/Elev= 30
  3978.7  432.37  4038.1  430.84  4303.2  425.18  4381.3  423.04  4517.6  416.28
  4558.7  412.09  4622.6  410.40  4632.1  410.12  4701.9  403.73  4780.4  399.16
  4826.1  396.99  4956.2  394.09  4957.3  393.84  4976.4  390.28  4976.9  389.48
  4982.6  390.28  4985.0  393.74  5004.2  391.27  5038.6  394.09  5046.8  395.88
  5144.2  398.56  5173.2  399.45  5193.3  402.27  5321.1  412.00  5326.1  410.39
  5342.0  411.33  5373.8  413.85  5453.9  416.95  5704.2  421.80  5905.0  424.21
#Mann=12,-1,0
  3978.7    0.05       0  4038.1    0.08       0  4303.2    0.05       0
  4381.3    0.08       0  4622.6    0.05       0  4632.1    0.08       0
  4780.4    0.16       0  4957.3    0.08       0  4976.4    0.07       0
  4982.6    0.08       0  5144.2    0.16       0  5342.0    0.05       0
Bank Sta=4956.2,5038.6
Exp/Cntr=0.3,0.1

Type RM Length L Ch R = 1,8517,341,341,341
BEGIN DESCRIPTION:
FOURMILE BRANCH 15.0
END DESCRIPTION:
XS GIS Cut Line= 3
      2897657.39      6957613.49      2897875.00      6956725.00
      2897782.42      6956019.90
#Sta/Elev= 30
  4101.4  419.14  4218.5  412.75  4360.6  408.27  4493.5  403.52  4529.9  404.34
  4535.1  402.87  4560.9  404.52  4571.5  406.00  4576.7  404.01  4594.0  405.95
  4645.5  407.19  4696.4  405.84  4933.8  388.46  4961.7  386.04  4971.8  385.50
  4972.3  384.70  4978.1  385.50  5160.3  385.50  5216.4  388.46  5248.1  394.23
  5278.4  396.49  5318.7  394.95  5338.9  397.67  5363.0  398.28  5399.4  404.28
  5490.2  414.40  5548.5  416.86  5589.1  418.45  5651.6  417.77  5727.3  424.69
#Mann=9,-1,0
  4101.4    0.05       0  4218.5    0.16       0  4360.6    0.08       0
  4560.9    0.16       0  4961.7    0.05       0  4971.8   0.033       0
  4978.1    0.05       0  5160.3    0.16       0  5548.5    0.05       0
Bank Sta=4933.8,5216.4
Exp/Cntr=0.3,0.1

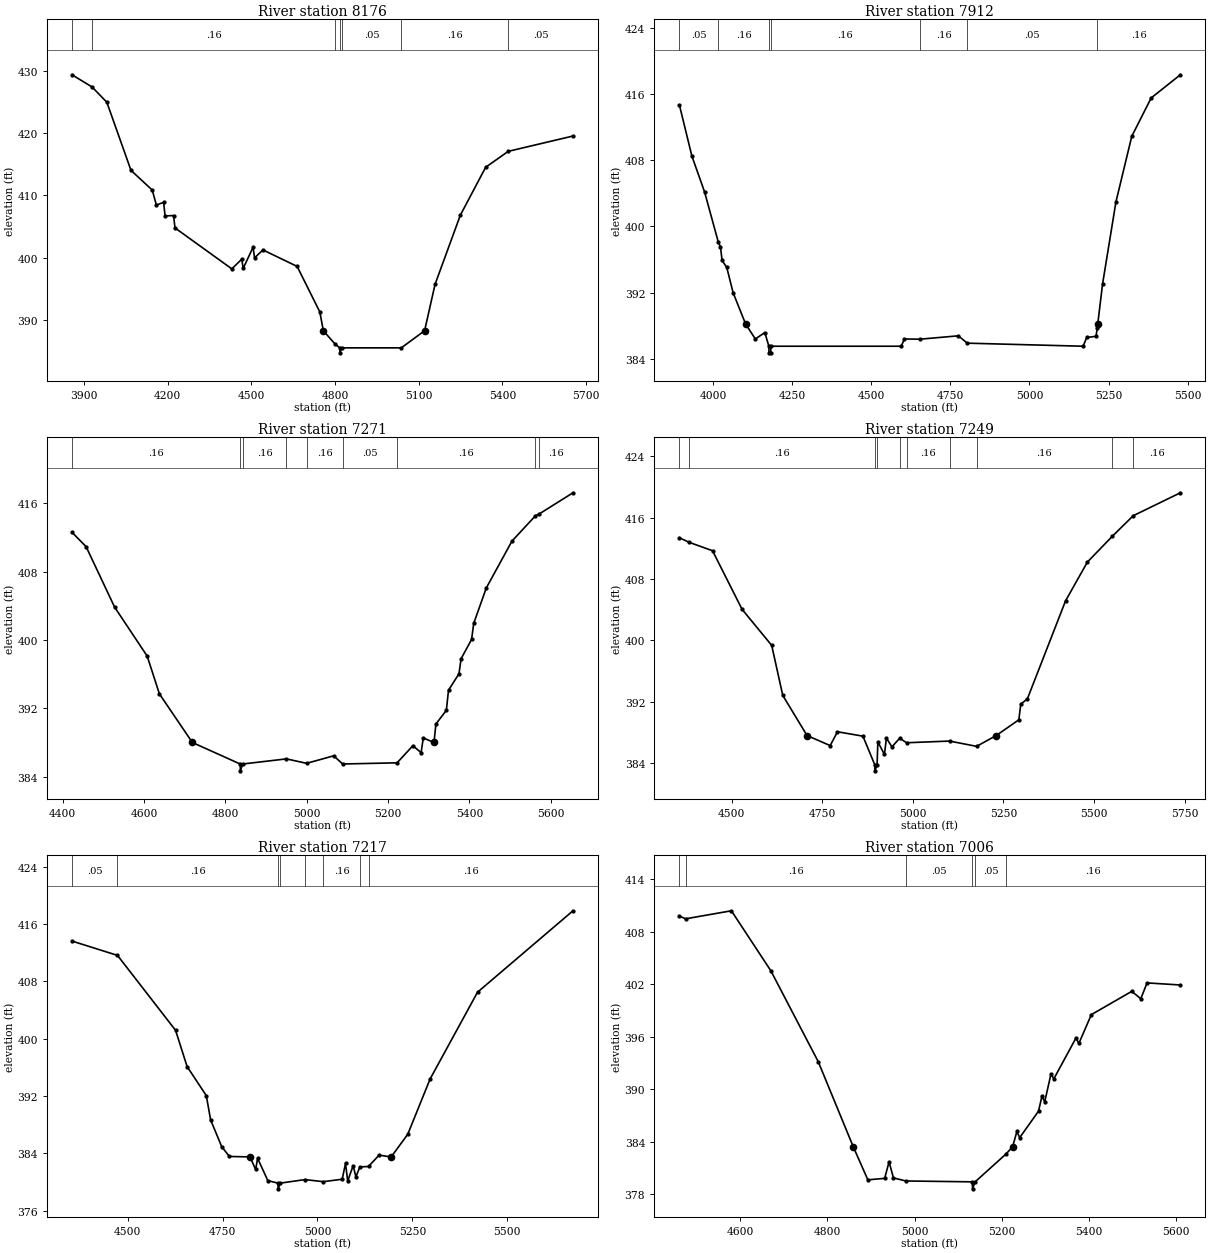
Type RM Length L Ch R = 1,8176,264,264,264
BEGIN DESCRIPTION:
Mapping XS 4b11afc1
END DESCRIPTION:
XS GIS Cut Line= 3
      2897928.22      6957847.87      2898219.90      6956712.42
      2898079.63      6956104.60
#Sta/Elev= 30
  3856.9  429.33  3928.8  427.37  3981.6  424.93  4068.3  413.99  4144.6  410.82
  4159.3  408.42  4185.3  408.85  4190.5  406.68  4220.9  406.73  4226.1  404.75
  4429.8  398.18  4465.4  399.73  4470.6  398.25  4506.1  401.66  4511.3  399.94
  4541.3  401.22  4664.0  398.57  4745.4  391.26  4757.9  388.25  4800.0  386.11
  4816.9  385.50  4817.4  384.70  4823.2  385.50  5037.5  385.50  5121.0  388.25
  5158.5  395.70  5249.2  406.80  5339.8  414.48  5420.8  417.04  5653.0  419.50
#Mann=7,-1,0
  3856.9    0.05       0  3928.8    0.16       0  4800.0    0.05       0
  4816.9   0.033       0  4823.2    0.05       0  5037.5    0.16       0
  5420.8    0.05       0
Bank Sta=4757.9,5121
Exp/Cntr=0.3,0.1

Type RM Length L Ch R = 1,7912,641,641,641
BEGIN DESCRIPTION:
FOURMILE BRANCH 14.0
END DESCRIPTION:
XS GIS Cut Line= 3
      2898548.89      6957844.32      2898475.00      6956725.00
      2898375.01      6956275.03
#Sta/Elev= 30
  3894.0  414.69  3933.4  408.51  3973.5  404.17  4017.1  398.07  4023.6  397.54
  4028.8  395.89  4043.6  395.03  4063.7  391.97  4103.0  388.20  4133.8  386.38
  4163.9  387.15  4176.6  385.50  4177.1  384.70  4182.5  384.70  4183.0  385.50
  4594.8  385.50  4604.9  386.38  4653.6  386.35  4775.2  386.76  4803.5  385.87
  5169.4  385.50  5180.9  386.56  5210.4  386.70  5214.1  387.75  5215.7  388.20
  5230.9  393.03  5273.1  402.96  5323.1  410.90  5384.5  415.55  5476.7  418.35
#Mann=7,-1,0
  3894.0    0.05       0  4017.1    0.16       0  4176.6   0.033       0
  4183.0    0.16       0  4653.6    0.16       0  4803.5    0.05       0
  5214.1    0.16       0
Bank Sta=4103,5215.7
Exp/Cntr=0.3,0.1

Type RM Length L Ch R = 1,7271,22,22,22
BEGIN DESCRIPTION:
Mapping XS 60864e1a
END DESCRIPTION:
XS GIS Cut Line= 6
      2899076.21      6957079.61      2899062.32      6956687.25
      2899044.96      6956537.94      2898982.46      6956458.08
      2898878.29      6956447.66      2898423.43      6956287.94
#Sta/Elev= 30
  4423.4  412.62  4458.0  410.94  4528.1  403.86  4608.1  398.13  4638.1  393.71
  4719.1  388.02  4836.6  385.50  4837.1  384.70  4843.0  385.50  4950.2  386.10
  5000.0  385.58  5066.5  386.46  5088.4  385.50  5222.3  385.64  5261.0  387.64
  5281.3  386.83  5286.6  388.55  5313.0  388.02  5317.6  390.18  5343.3  391.78
  5348.6  394.14  5374.3  396.06  5379.6  397.83  5405.3  400.08  5410.6  401.97
  5441.6  406.12  5504.5  411.59  5562.1  414.55  5572.1  414.79  5654.5  417.25
#Mann=9,-1,0
  4423.4    0.16       0  4836.6    0.07       0  4843.0    0.16       0
  4950.2    0.05       0  5000.0    0.16       0  5088.4    0.05       0
  5222.3    0.16       0  5562.1    0.05       0  5572.1    0.16       0
Bank Sta=4719.1,5313
Exp/Cntr=0.3,0.1

Type RM Length L Ch R = 1,7249,32,32,32
BEGIN DESCRIPTION:
Mapping XS 130feac9
END DESCRIPTION:
XS GIS Cut Line= 6
      2899121.34      6957128.22      2899072.73      6956728.91
      2899083.15      6956596.97      2899031.07      6956475.44
      2898840.09      6956416.41      2898368.90      6956215.46
#Sta/Elev= 30
  4355.7  413.38  4383.3  412.77  4447.1  411.69  4528.7  404.05  4610.4  399.36
  4641.0  392.84  4708.0  387.61  4771.9  386.30  4792.0  388.10  4862.2  387.53
  4894.9  383.81  4895.4  383.01  4901.3  383.81  4903.5  386.78  4921.7  385.14
  4927.1  387.28  4942.3  386.13  4963.6  387.26  4982.8  386.67  5101.5  386.89
  5175.9  386.20  5230.3  387.61  5292.6  389.66  5298.0  391.70  5316.2  392.39
  5421.5  405.15  5481.8  410.21  5550.6  413.57  5608.4  416.25  5738.5  419.24
#Mann=10,-1,0
  4355.7    0.05       0  4383.3    0.16       0  4894.9    0.07       0
  4901.3    0.16       0  4963.6    0.05       0  4982.8    0.16       0
  5101.5    0.05       0  5175.9    0.16       0  5550.6    0.05       0
  5608.4    0.16       0
Bank Sta=4708,5230.3
Exp/Cntr=0.3,0.1

Type RM Length L Ch R = 1,7217,211,211,211
BEGIN DESCRIPTION:
Mapping XS 673fc99f
END DESCRIPTION:
XS GIS Cut Line= 6
      2899187.31      6957114.30      2899093.57      6956531.00
      2899051.90      6956451.13      2898978.98      6956409.47
      2898892.18      6956392.11      2898485.93      6956162.94
#Sta/Elev= 30
  4353.4  413.64  4473.2  411.64  4626.2  401.18  4656.6  396.12  4707.2  392.06
  4718.5  388.68  4747.7  384.94  4768.0  383.57  4822.1  383.51  4837.2  381.75
  4842.3  383.32  4869.2  380.20  4895.9  379.85  4896.4  379.05  4902.4  379.85
  4967.1  380.34  5015.4  380.05  5065.2  380.39  5073.9  382.60  5079.7  380.15
  5094.0  382.28  5101.3  380.73  5111.8  382.11  5134.5  382.17  5162.3  383.75
  5194.3  383.51  5238.0  386.68  5296.8  394.39  5421.7  406.50  5673.2  417.87
#Mann=8,-1,0
  4353.4    0.05       0  4473.2    0.16       0  4895.9   0.033       0
  4902.4    0.16       0  4967.1    0.05       0  5015.4    0.16       0
  5111.8    0.05       0  5134.5    0.16       0
Bank Sta=4822.1,5194.3
Exp/Cntr=0.3,0.1

Type RM Length L Ch R = 1,7006,226,226,226
BEGIN DESCRIPTION:
Mapping XS e33bf65a
END DESCRIPTION:
XS GIS Cut Line= 3
      2899340.09      6957013.64      2899291.48      6956496.27
      2898892.20      6956010.18
#Sta/Elev= 30
  4460.8  409.82  4474.8  409.50  4580.0  410.42  4670.4  403.56  4779.2  393.15
  4859.3  383.44  4892.9  379.64  4931.5  379.81  4941.5  381.70  4951.6  379.86
  4980.0  379.51  5132.4  379.41  5132.9  378.61  5138.9  379.41  5210.4  382.63
  5225.0  383.44  5234.6  385.17  5241.1  384.47  5284.2  387.49  5292.0  389.19
  5298.5  388.58  5312.9  391.77  5319.3  391.19  5370.2  395.87  5376.7  395.24
  5405.4  398.54  5498.0  401.20  5518.8  400.36  5533.1  402.17  5609.5  401.93
#Mann=6,-1,0
  4460.8    0.05       0  4474.8    0.16       0  4980.0    0.05       0
  5132.4   0.033       0  5138.9    0.05       0  5210.4    0.16       0
Bank Sta=4859.3,5225
Exp/Cntr=0.3,0.1

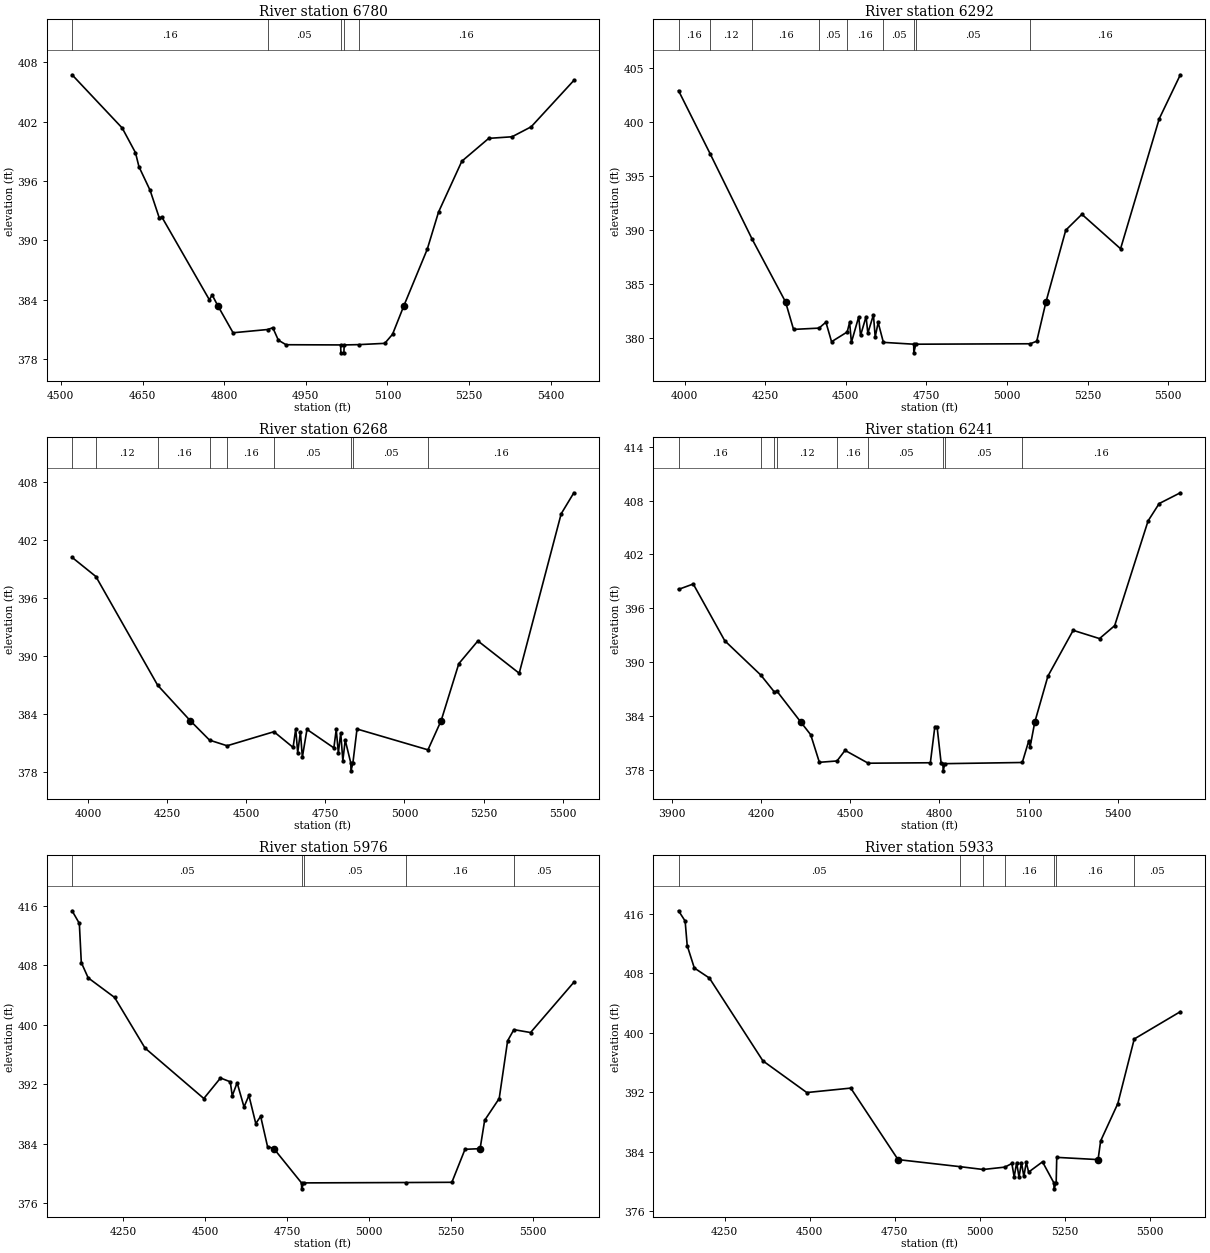
Type RM Length L Ch R = 1,6780,488,488,488
BEGIN DESCRIPTION:
FOURMILE BRANCH 12.0
END DESCRIPTION:
XS GIS Cut Line= 3
      2899375.01      6956824.97      2899475.00      6956375.00
      2899175.02      6956025.02
#Sta/Elev= 30
  4520.6  406.74  4612.8  401.35  4637.1  398.86  4643.5  397.44  4664.0  395.05
  4680.6  392.30  4685.8  392.33  4772.8  383.99  4778.0  384.47  4788.5  383.37
  4816.4  380.65  4880.1  380.98  4889.4  381.16  4899.6  379.90  4913.7  379.44
  5014.0  379.42  5014.5  378.62  5020.0  378.62  5020.5  379.42  5047.1  379.45
  5095.1  379.58  5109.4  380.50  5130.1  383.37  5173.1  389.09  5193.9  392.86
  5236.7  398.00  5286.1  400.31  5328.9  400.47  5364.1  401.48  5442.5  406.17
#Mann=5,-1,0
  4520.6    0.16       0  4880.1    0.05       0  5014.0   0.033       0
  5020.5    0.05       0  5047.1    0.16       0
Bank Sta=4788.5,5130.1
Exp/Cntr=0.3,0.1

Type RM Length L Ch R = 1,6292,24,24,24
BEGIN DESCRIPTION:
Mapping XS 0fd45943
END DESCRIPTION:
XS GIS Cut Line= 6
      2899477.94      6956880.70      2899516.14      6956404.95
      2899641.14      6956345.93      2899828.64      6956095.93
      2899748.78      6955995.23      2899259.60      6955991.76
#Sta/Elev= 30
  3980.9  402.90  4078.7  397.07  4209.2  389.15  4312.8  383.34  4337.7  380.79
  4416.7  380.91  4438.1  381.46  4455.6  379.65  4504.1  380.55  4511.6  381.44
  4517.2  379.59  4539.9  381.96  4545.5  380.23  4562.7  381.97  4568.2  380.44
  4585.5  382.14  4591.0  380.09  4600.2  381.43  4616.4  379.59  4710.4  379.42
  4710.9  378.62  4716.9  379.42  5072.0  379.46  5092.2  379.70  5120.8  383.34
  5182.2  389.98  5232.2  391.45  5352.2  388.26  5472.2  400.30  5537.6  404.37
#Mann=9,-1,0
  3980.9    0.16       0  4078.7    0.12       0  4209.2    0.16       0
  4416.7    0.05       0  4504.1    0.16       0  4616.4    0.05       0
  4710.4   0.033       0  4716.9    0.05       0  5072.0    0.16       0
Bank Sta=4312.8,5120.8
Exp/Cntr=0.3,0.1

Type RM Length L Ch R = 1,6268,27,27,27
BEGIN DESCRIPTION:
Mapping XS b27e41ae
END DESCRIPTION:
XS GIS Cut Line= 6
      2899502.25      6956908.39      2899599.47      6956394.54
      2899700.16      6956328.57      2899852.94      6956078.57
      2899731.41      6955970.93      2899273.05      6955925.78
#Sta/Elev= 30
  3949.3  400.18  4024.6  398.20  4219.9  386.97  4322.6  383.32  4384.0  381.30
  4439.4  380.72  4587.5  382.17  4648.0  380.55  4656.4  382.46  4662.6  379.99
  4671.1  382.16  4677.3  379.54  4691.9  382.41  4776.9  380.50  4784.4  382.40
  4791.1  379.98  4798.6  382.05  4805.3  379.18  4812.8  381.30  4830.5  378.93
  4831.0  378.13  4837.0  378.93  4850.1  382.45  5074.4  380.30  5116.1  383.32
  5171.9  389.20  5232.2  391.55  5362.8  388.21  5495.5  404.68  5535.6  406.85
#Mann=9,-1,0
  3949.3    0.16       0  4024.6    0.12       0  4219.9    0.16       0
  4384.0    0.12       0  4439.4    0.16       0  4587.5    0.05       0
  4830.5   0.033       0  4837.0    0.05       0  5074.4    0.16       0
Bank Sta=4322.6,5116.1
Exp/Cntr=0.3,0.1

Type RM Length L Ch R = 1,6241,265,265,265
BEGIN DESCRIPTION:
Mapping XS 46403b75
END DESCRIPTION:
XS GIS Cut Line= 6
      2899519.60      6956922.35      2899780.03      6956297.32
      2899894.61      6956120.23      2899859.89      6955981.34
      2899748.78      6955946.62      2899218.76      6955835.77
#Sta/Elev= 30
  3921.6  398.11  3971.1  398.71  4077.2  392.39  4198.7  388.56  4243.3  386.72
  4253.6  386.74  4333.2  383.33  4366.5  381.92  4395.7  378.85  4455.0  379.00
  4482.1  380.18  4560.0  378.75  4769.3  378.80  4784.4  382.83  4792.0  382.77
  4805.4  378.80  4811.8  378.70  4812.3  377.90  4818.3  378.70  5078.7  378.83
  5100.1  381.19  5105.2  380.60  5120.8  383.33  5165.0  388.45  5250.0  393.55
  5338.7  392.63  5389.7  394.07  5502.2  405.74  5539.5  407.67  5610.7  408.87
#Mann=9,-1,0
  3921.6    0.16       0  4198.7    0.12       0  4243.3    0.16       0
  4253.6    0.12       0  4455.0    0.16       0  4560.0    0.05       0
  4811.8   0.033       0  4818.3    0.05       0  5078.7    0.16       0
Bank Sta=4333.2,5120.8
Exp/Cntr=0.3,0.1

Type RM Length L Ch R = 1,5976,43,43,43
BEGIN DESCRIPTION:
Mapping XS 511c55c0
END DESCRIPTION:
XS GIS Cut Line= 6
      2900515.36      6956424.15      2900124.73      6955851.22
      2900002.33      6955809.55      2899859.10      6955614.24
      2899780.98      6955606.43      2899392.93      6955590.80
#Sta/Elev= 30
  4093.0  415.34  4115.2  413.64  4121.2  408.37  4142.2  406.31  4222.9  403.67
  4315.7  396.86  4495.2  390.07  4546.1  392.83  4575.9  392.32  4582.0  390.43
  4596.9  392.19  4617.9  388.93  4632.8  390.48  4653.8  386.70  4668.7  387.67
  4689.7  383.60  4709.0  383.32  4793.4  378.71  4793.9  377.91  4800.1  378.71
  5112.8  378.76  5252.4  378.79  5292.5  383.23  5338.6  383.32  5352.5  387.14
  5396.9  390.07  5422.6  397.84  5441.7  399.34  5492.6  398.95  5624.8  405.72
#Mann=5,-1,0
  4093.0    0.05       0  4793.4   0.033       0  4800.1    0.05       0
  5112.8    0.16       0  5441.7    0.05       0
Bank Sta=4709,5338.6
Exp/Cntr=0.3,0.1

Type RM Length L Ch R = 1,5933,49,49,49
BEGIN DESCRIPTION:
Mapping XS 76cfa0de
END DESCRIPTION:
XS GIS Cut Line= 6
      2900533.57      6956382.46      2900142.96      6955832.99
      2900017.96      6955757.47      2899952.85      6955679.35
      2899864.31      6955585.60      2899442.48      6955536.12
#Sta/Elev= 30
  4114.4  416.38  4133.8  415.00  4139.9  411.70  4160.8  408.69  4205.1  407.34
  4362.5  396.21  4491.6  391.95  4620.8  392.55  4759.9  382.94  4942.2  381.99
  5010.1  381.61  5074.3  381.93  5094.6  382.42  5101.4  380.60  5108.7  382.54
  5115.6  380.58  5122.9  382.53  5129.8  380.68  5137.0  382.57  5143.9  381.26
  5184.7  382.64  5218.2  379.81  5218.7  379.01  5224.9  379.81  5226.6  383.24
  5348.1  382.94  5355.7  385.45  5406.1  390.46  5454.5  399.15  5590.0  402.82
#Mann=7,-1,0
  4114.4    0.05       0  4942.2    0.08       0  5010.1    0.05       0
  5074.3    0.16       0  5218.2    0.07       0  5224.9    0.16       0
  5454.5    0.05       0
Bank Sta=4759.9,5348.1
Exp/Cntr=0.3,0.1

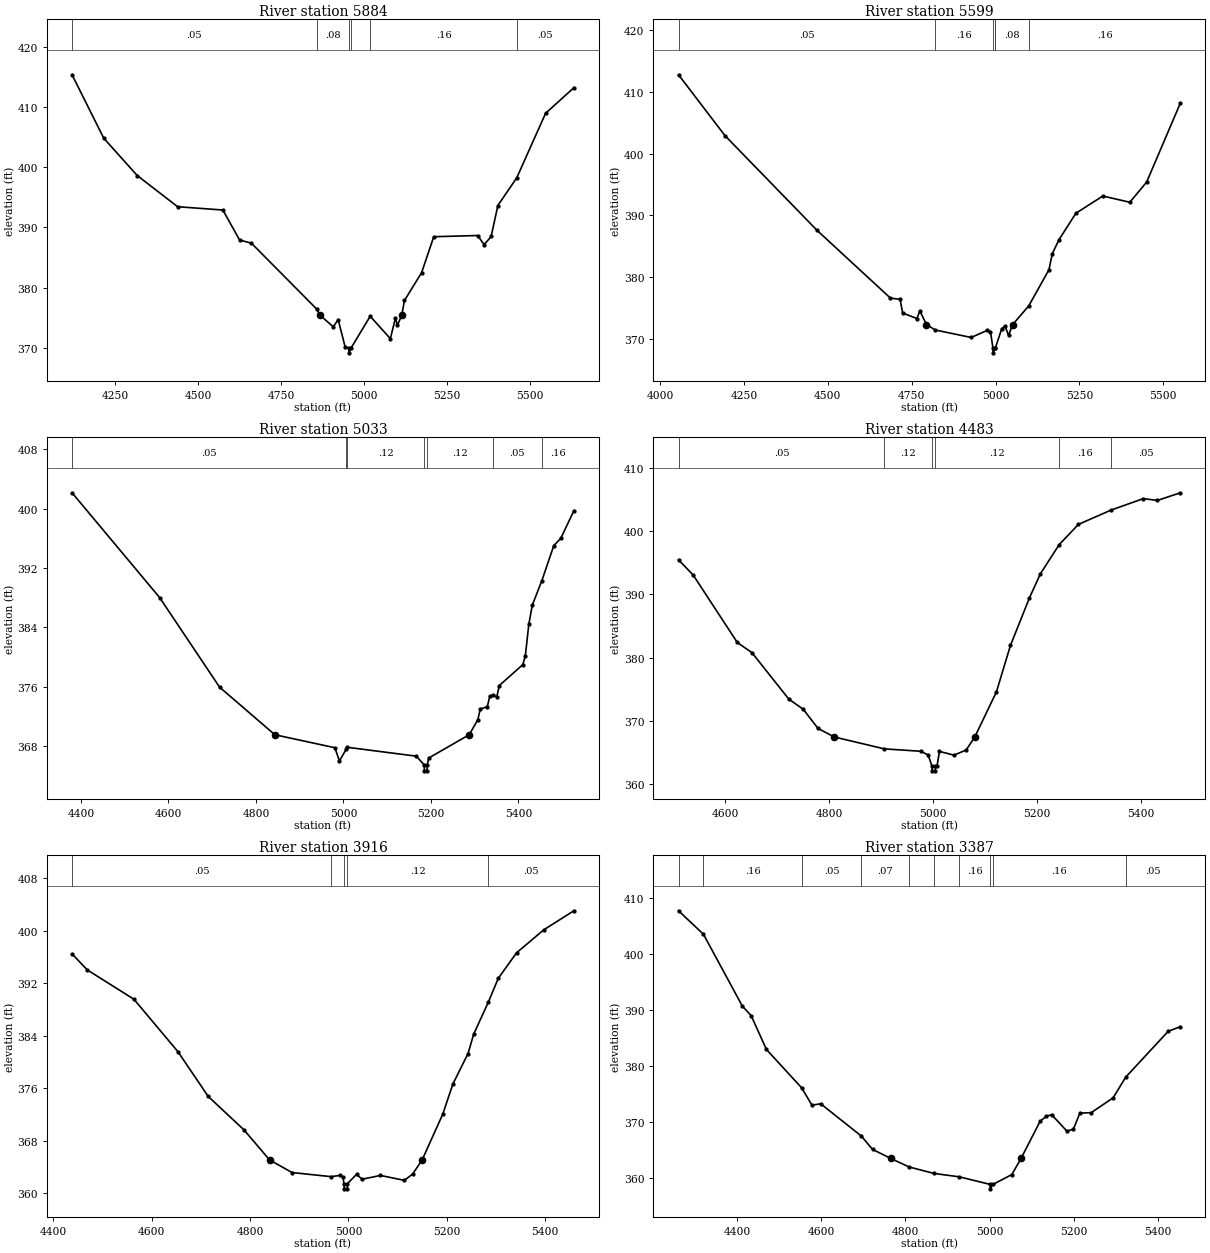
Type RM Length L Ch R = 1,5884,285,285,285
BEGIN DESCRIPTION:
Mapping XS 51d1a58e
END DESCRIPTION:
XS GIS Cut Line= 6
      2900533.56      6956330.35      2900145.56      6955786.12
      2900030.98      6955723.62      2899942.44      6955606.43
      2899788.79      6955510.08      2899409.25      6955445.09
#Sta/Elev= 30
  4120.5  415.39  4216.0  404.84  4316.8  398.64  4438.5  393.45  4574.9  392.90
  4625.3  387.92  4661.0  387.38  4857.4  376.45  4868.1  375.39  4907.6  373.48
  4922.5  374.68  4943.3  370.15  4954.5  369.95  4955.0  369.15  4961.2  369.95
  5019.0  375.23  5079.7  371.51  5095.0  374.92  5100.9  373.72  5113.9  375.39
  5122.3  377.87  5173.9  382.49  5210.5  388.46  5342.8  388.66  5362.3  387.14
  5383.4  388.50  5403.7  393.65  5460.7  398.27  5547.5  408.98  5632.7  413.24
#Mann=6,-1,0
  4120.5    0.05       0  4857.4    0.08       0  4954.5    0.07       0
  4961.2    0.08       0  5019.0    0.16       0  5460.7    0.05       0
Bank Sta=4868.1,5113.9
Exp/Cntr=0.3,0.1

Type RM Length L Ch R = 1,5599,566,566,566
BEGIN DESCRIPTION:
FOURMILE BRANCH 10.0
END DESCRIPTION:
XS GIS Cut Line= 3
      2900575.00      6956275.00      2900075.00      6955475.00
      2899524.97      6955425.00
#Sta/Elev= 30
  4055.2  412.78  4193.8  402.91  4467.9  387.59  4686.7  376.61  4715.6  376.41
  4723.2  374.19  4765.7  373.30  4774.5  374.52  4794.3  372.32  4820.5  371.44
  4927.3  370.23  4975.6  371.38  4985.0  371.17  4992.3  368.54  4992.8  367.74
  4999.1  368.54  4999.7  368.54  5018.7  371.67  5028.7  372.06  5038.8  370.56
  5051.2  372.32  5099.0  375.34  5159.3  381.20  5169.3  383.81  5189.4  386.08
  5239.6  390.35  5319.9  393.14  5400.3  392.13  5450.5  395.40  5550.9  408.18
#Mann=6,-1,0
  4055.2    0.05       0  4820.5    0.16       0  4992.3    0.07       0
  4999.1    0.16       0  4999.7    0.08       0  5099.0    0.16       0
Bank Sta=4794.3,5051.2
Exp/Cntr=0.3,0.1

Type RM Length L Ch R = 1,5033,550,550,550
BEGIN DESCRIPTION:
FOURMILE BRANCH 9.0
END DESCRIPTION:
XS GIS Cut Line= 3
      2900974.96      6955274.99      2900375.00      6955075.00
      2899924.99      6954825.00
#Sta/Elev= 30
  4379.7  402.16  4579.9  388.02  4717.0  375.93  4843.3  369.51  4980.5  367.76
  4991.0  365.97  5007.0  367.62  5008.7  367.82  5166.5  366.62  5184.8  365.44
  5185.3  364.64  5191.2  364.64  5191.7  365.44  5195.1  366.37  5287.6  369.51
  5307.3  371.53  5313.0  372.98  5329.0  373.30  5334.7  374.71  5341.7  374.85
  5350.7  374.62  5356.4  376.15  5410.2  378.97  5415.9  380.13  5423.9  384.40
  5431.9  387.00  5453.6  390.28  5481.1  395.04  5497.1  396.02  5526.9  399.74
#Mann=7,-1,0
  4379.7    0.05       0  5007.0    0.16       0  5008.7    0.12       0
  5184.8    0.03       0  5191.7    0.12       0  5341.7    0.05       0
  5453.6    0.16       0
Bank Sta=4843.3,5287.6
Exp/Cntr=0.3,0.1

Type RM Length L Ch R = 1,4483,567,567,567
BEGIN DESCRIPTION:
FOURMILE BRANCH 8.0
END DESCRIPTION:
XS GIS Cut Line= 3
      2900925.03      6955125.03      2900575.00      6954775.00
      2900325.00      6954375.01
#Sta/Elev= 30
  4510.0  395.47  4538.3  393.06  4623.2  382.42  4651.5  380.81  4722.2  373.50
  4750.5  371.85  4778.7  368.85  4809.9  367.50  4906.5  365.62  4976.7  365.24
  4990.9  364.65  4998.0  362.95  4998.5  362.15  5004.5  362.15  5005.0  362.95
  5008.0  362.95  5012.7  365.22  5040.4  364.63  5064.0  365.43  5080.7  367.50
  5122.3  374.59  5149.5  381.97  5186.0  389.46  5207.3  393.29  5243.3  397.87
  5280.4  401.07  5343.1  403.32  5405.4  405.14  5432.5  404.85  5476.7  406.06
#Mann=6,-1,0
  4510.0    0.05       0  4906.5    0.12       0  4998.0    0.07       0
  5005.0    0.12       0  5243.3    0.16       0  5343.1    0.05       0
Bank Sta=4809.9,5080.7
Exp/Cntr=0.3,0.1

Type RM Length L Ch R = 1,3916,529,529,529
BEGIN DESCRIPTION:
FOURMILE BRANCH 7.0
END DESCRIPTION:
XS GIS Cut Line= 3
      2901225.00      6954874.99      2900975.00      6954375.00
      2900524.99      6954275.00
#Sta/Elev= 30
  4438.2  396.46  4468.9  394.03  4564.0  389.55  4653.4  381.57  4714.9  374.76
  4787.6  369.67  4839.7  365.09  4885.4  363.17  4964.2  362.55  4983.2  362.73
  4988.8  362.44  4990.9  361.49  4991.4  360.69  4997.4  360.69  4998.0  361.49
  5016.4  362.89  5027.9  362.15  5065.1  362.73  5113.7  361.98  5130.4  362.94
  5149.8  365.09  5191.8  372.07  5212.3  376.65  5243.1  381.29  5254.6  384.24
  5284.1  389.07  5304.5  392.73  5341.7  396.62  5396.7  400.10  5458.2  403.02
#Mann=5,-1,0
  4438.2    0.05       0  4964.2    0.12       0  4990.9    0.07       0
  4998.0    0.12       0  5284.1    0.05       0
Bank Sta=4839.7,5149.8
Exp/Cntr=0.3,0.1

Type RM Length L Ch R = 1,3387,553,553,553
BEGIN DESCRIPTION:
FOURMILE BRANCH 6.0
END DESCRIPTION:
XS GIS Cut Line= 3
      2901824.99      6954774.99      2901425.00      6954175.00
      2901175.00      6953774.99
#Sta/Elev= 30
  4260.6  407.77  4319.8  403.58  4412.3  390.74  4433.3  389.04  4469.4  383.01
  4553.5  376.13  4577.6  373.06  4598.6  373.30  4695.4  367.52  4721.8  365.15
  4765.5  363.53  4808.8  362.01  4867.9  360.86  4928.3  360.25  5001.0  358.91
  5001.6  358.11  5008.3  358.91  5053.0  360.67  5074.7  363.53  5120.3  370.20
  5135.0  371.07  5147.4  371.36  5183.9  368.41  5199.3  368.78  5214.6  371.63
  5241.7  371.72  5293.6  374.36  5323.7  378.07  5424.5  386.24  5453.4  387.07
#Mann=10,-1,0
  4260.6    0.05       0  4319.8    0.16       0  4553.5    0.05       0
  4695.4    0.07       0  4808.8    0.16       0  4867.9    0.07       0
  4928.3    0.16       0  5001.0    0.07       0  5008.3    0.16       0
  5323.7    0.05       0
Bank Sta=4765.5,5074.7
Exp/Cntr=0.3,0.1