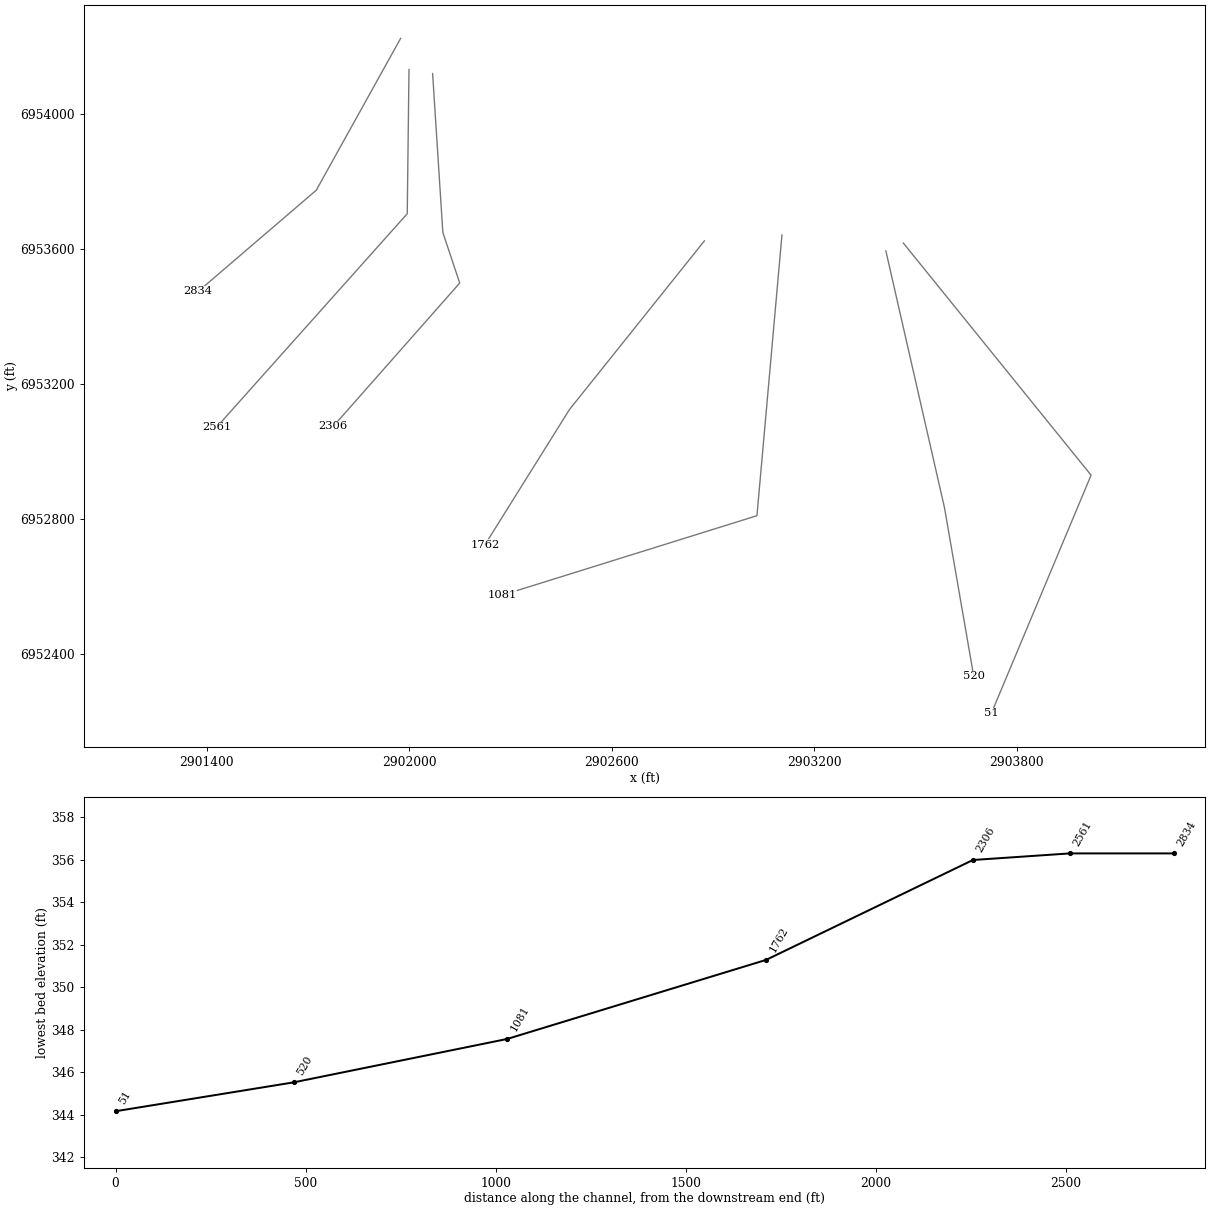
HEC-RAS study FOURMILE BRANCH.prj: FOURMILE BRANCH Base Level Engineering

--- FOURMILE BRANCH.g01 (geometry) --- (continued)

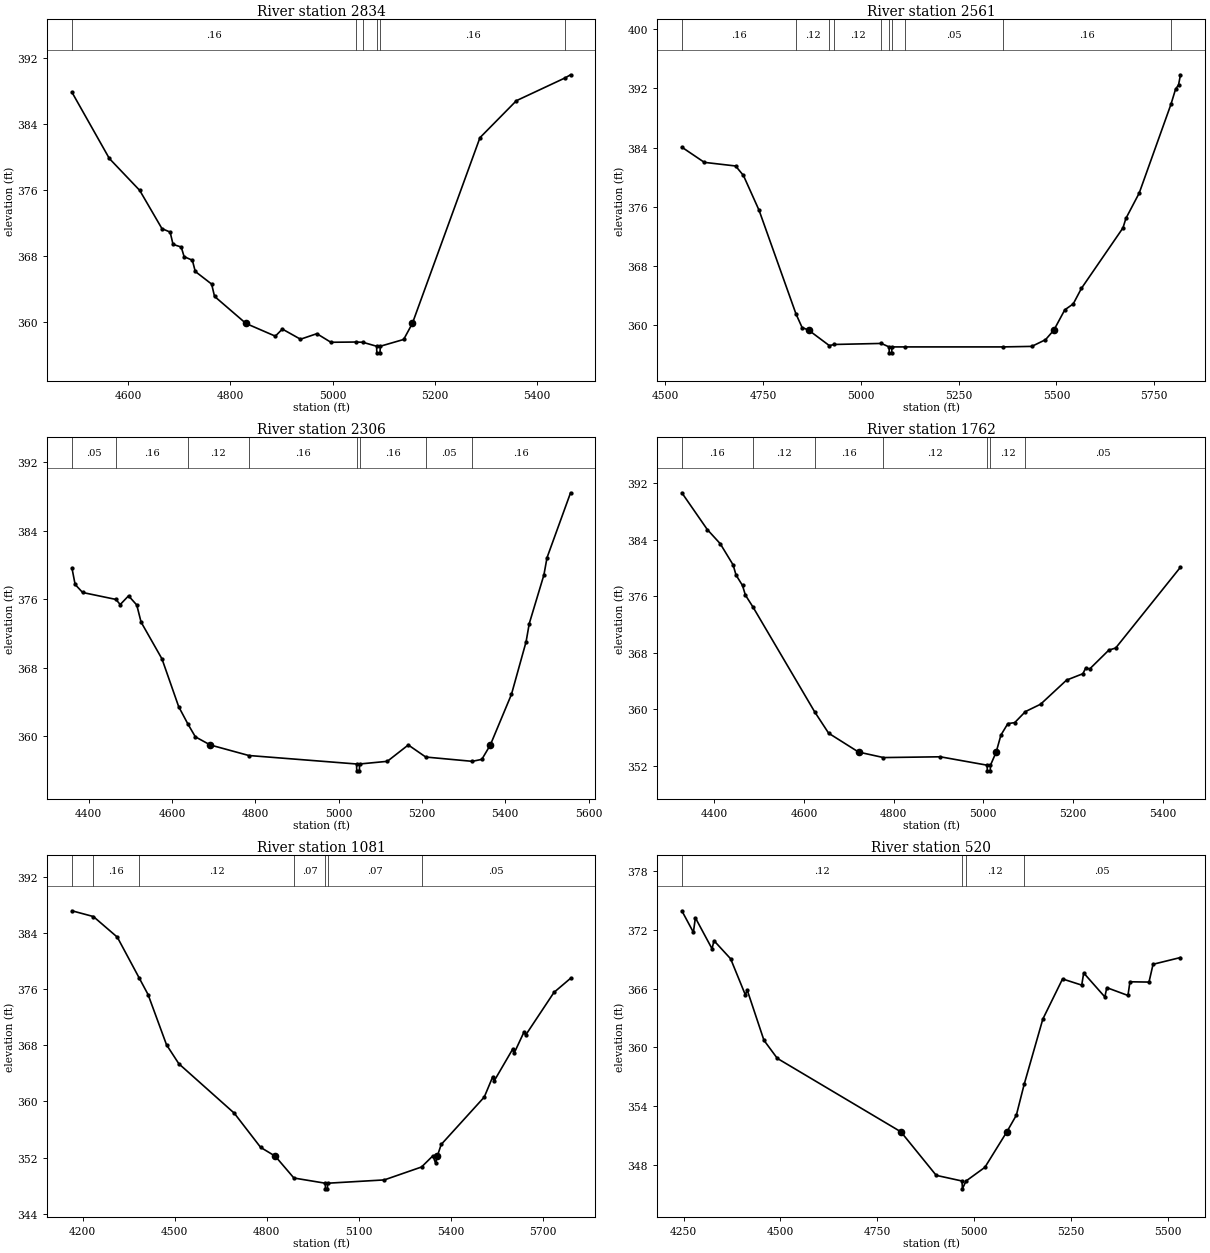
Type RM Length L Ch R = 1,2834,273,273,273
BEGIN DESCRIPTION:
FOURMILE BRANCH 5.0
END DESCRIPTION:
XS GIS Cut Line= 3
      2901975.00      6954225.00      2901725.00      6953775.00
      2901374.97      6953474.98
#Sta/Elev= 30
  4489.9  387.87  4563.1  379.84  4622.6  375.97  4666.1  371.34  4682.1  370.92
  4687.8  369.43  4703.8  369.11  4709.5  367.94  4725.6  367.51  4731.3  366.15
  4763.3  364.62  4769.0  363.13  4830.5  359.85  4888.0  358.31  4901.7  359.17
  4937.2  357.94  4969.2  358.61  4996.7  357.57  5044.9  357.60  5059.2  357.57
  5086.1  357.09  5086.6  356.29  5092.8  356.29  5093.4  357.09  5139.1  357.91
  5156.1  359.85  5288.4  382.36  5359.7  386.84  5455.3  389.61  5465.7  389.98
#Mann=6,-1,0
  4489.9    0.16       0  5044.9     0.1       0  5059.2    0.16       0
  5086.1    0.07       0  5093.4    0.16       0  5455.3    0.05       0
Bank Sta=4830.5,5156.1
Exp/Cntr=0.3,0.1

Type RM Length L Ch R = 1,2561,255,255,255
BEGIN DESCRIPTION:
Mapping XS aacac4df
END DESCRIPTION:
XS GIS Cut Line= 3
      2901999.73      6954132.49      2901994.52      6953705.39
      2901429.71      6953072.91
#Sta/Elev= 30
  4542.2  384.05  4599.7  382.00  4679.7  381.51  4699.7  380.23  4739.7  375.53
  4834.1  361.54  4849.7  359.71  4866.3  359.36  4919.3  357.27  4932.0  357.42
  5052.3  357.56  5072.1  357.09  5072.7  356.29  5078.9  356.29  5079.5  357.09
  5111.6  357.09  5362.9  357.09  5437.0  357.16  5472.1  358.06  5493.6  359.36
  5521.4  362.09  5543.1  362.90  5564.1  365.00  5670.2  373.15  5677.7  374.43
  5711.8  377.86  5792.9  389.83  5804.8  391.89  5812.3  392.45  5817.3  393.82
#Mann=10,-1,0
  4542.2    0.16       0  4834.1    0.12       0  4919.3    0.16       0
  4932.0    0.12       0  5052.3    0.07       0  5072.1    0.07       0
  5079.5    0.07       0  5111.6    0.05       0  5362.9    0.16       0
  5792.9    0.05       0
Bank Sta=4866.3,5493.6
Exp/Cntr=0.3,0.1

Type RM Length L Ch R = 1,2306,544,544,544
BEGIN DESCRIPTION:
FOURMILE BRANCH 4.0
END DESCRIPTION:
XS GIS Cut Line= 4
      2902069.70      6954120.62      2902100.00      6953650.00
      2902150.00      6953500.00      2901775.00      6953075.00
#Sta/Elev= 30
  4360.1  379.68  4367.8  377.74  4385.8  376.80  4465.7  375.99  4476.0  375.39
  4496.0  376.41  4515.7  375.34  4526.1  373.34  4576.2  369.05  4616.3  363.47
  4638.6  361.43  4656.3  359.95  4692.1  359.00  4784.6  357.77  5043.0  356.78
  5043.6  355.98  5049.9  355.98  5050.4  356.78  5116.9  357.09  5167.2  359.00
  5209.2  357.59  5320.7  357.09  5343.7  357.32  5364.1  359.00  5414.8  364.91
  5449.9  371.05  5457.5  373.17  5492.6  378.84  5500.1  380.86  5556.6  388.44
#Mann=8,-1,0
  4360.1    0.05       0  4465.7    0.16       0  4638.6    0.12       0
  4784.6    0.16       0  5043.0    0.07       0  5050.4    0.16       0
  5209.2    0.05       0  5320.7    0.16       0
Bank Sta=4692.1,5364.1
Exp/Cntr=0.3,0.1

Type RM Length L Ch R = 1,1762,681,681,681
BEGIN DESCRIPTION:
FOURMILE BRANCH 3.0
END DESCRIPTION:
XS GIS Cut Line= 3
      2902875.00      6953624.99      2902475.00      6953125.00
      2902225.00      6952725.00
#Sta/Elev= 30
  4327.8  390.67  4384.6  385.46  4413.4  383.46  4442.2  380.45  4448.7  379.01
  4463.1  377.54  4469.5  376.18  4486.5  374.48  4623.8  359.66  4655.2  356.61
  4721.9  353.94  4777.5  353.16  4904.1  353.27  5008.6  352.08  5009.1  351.28
  5015.5  351.28  5016.1  352.08  5028.8  353.94  5039.4  356.35  5054.8  357.97
  5070.1  358.11  5093.9  359.67  5127.9  360.72  5185.7  364.13  5222.2  365.04
  5228.1  365.80  5237.6  365.73  5280.0  368.38  5295.3  368.68  5439.8  380.13
#Mann=7,-1,0
  4327.8    0.16       0  4486.5    0.12       0  4623.8    0.16       0
  4777.5    0.12       0  5008.6    0.07       0  5016.1    0.12       0
  5093.9    0.05       0
Bank Sta=4721.9,5028.8
Exp/Cntr=0.3,0.1

Type RM Length L Ch R = 1,1081,561,561,561
BEGIN DESCRIPTION:
FOURMILE BRANCH 2.0
END DESCRIPTION:
XS GIS Cut Line= 3
      2903104.71      6953642.40      2903030.59      6952810.70
      2902275.00      6952575.00
#Sta/Elev= 30
  4165.0  387.13  4235.0  386.31  4313.0  383.38  4384.8  377.54  4413.4  375.21
  4473.6  368.06  4513.8  365.36  4694.5  358.33  4780.6  353.46  4828.4  352.20
  4889.1  349.10  4991.5  348.36  4992.1  347.56  4998.5  347.56  4999.1  348.36
  5183.9  348.83  5305.5  350.67  5342.2  352.25  5351.5  351.21  5356.8  352.20
  5369.5  353.87  5510.0  360.62  5537.2  363.46  5542.5  362.93  5602.3  367.41
  5607.5  366.87  5640.0  369.91  5645.2  369.45  5737.5  375.52  5791.5  377.52
#Mann=7,-1,0
  4165.0    0.12       0  4235.0    0.16       0  4384.8    0.12       0
  4889.1    0.07       0  4991.5    0.07       0  4999.1    0.07       0
  5305.5    0.05       0
Bank Sta=4828.4,5356.8
Exp/Cntr=0.3,0.1

Type RM Length L Ch R = 1,520,469,469,469
BEGIN DESCRIPTION:
Mapping XS 52483302
END DESCRIPTION:
XS GIS Cut Line= 3
      2903412.51      6953595.34      2903586.12      6952834.89
      2903672.93      6952334.89
#Sta/Elev= 30
  4245.7  373.95  4275.5  371.75  4280.7  373.23  4323.6  370.07  4328.8  370.89
  4371.7  369.04  4409.6  365.36  4414.7  365.82  4457.7  360.71  4492.2  358.86
  4811.3  351.35  4902.5  346.90  4969.2  346.32  4970.1  345.52  4979.5  346.32
  5028.2  347.72  5084.9  351.35  5109.4  353.05  5129.5  356.19  5177.8  362.88
  5228.7  366.98  5278.2  366.35  5283.3  367.59  5337.9  365.14  5343.0  366.09
  5397.6  365.29  5402.7  366.69  5451.9  366.66  5462.4  368.48  5533.2  369.17
#Mann=4,-1,0
  4245.7    0.12       0  4969.2    0.07       0  4979.5    0.12       0
  5129.5    0.05       0
Bank Sta=4811.3,5084.9
Exp/Cntr=0.3,0.1

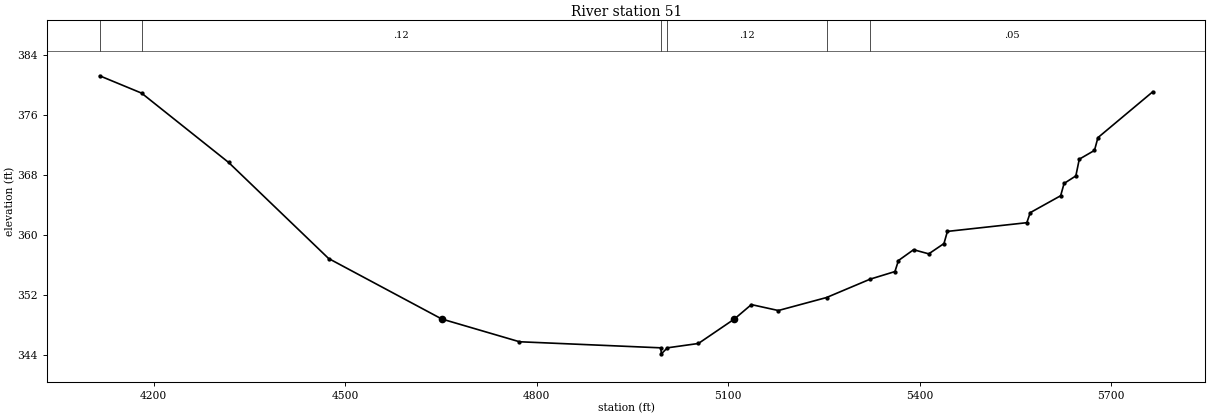
Type RM Length L Ch R = 1,51,0,0,0
BEGIN DESCRIPTION:
FOURMILE BRANCH 1.0
END DESCRIPTION:
XS GIS Cut Line= 3
      2903464.19      6953618.60      2904020.57      6952930.75
      2903725.02      6952225.04
#Sta/Elev= 30
  4115.3  381.20  4181.0  378.89  4317.3  369.66  4474.0  356.86  4651.3  348.80
  4773.0  345.77  4994.4  344.96  4995.3  344.16  5004.7  344.96  5053.3  345.54
  5109.7  348.80  5136.3  350.72  5178.5  349.93  5254.0  351.66  5322.4  354.11
  5361.2  355.12  5366.7  356.59  5390.4  358.03  5414.2  357.48  5438.0  358.85
  5443.4  360.47  5567.8  361.63  5573.2  362.97  5620.8  365.22  5626.2  366.86
  5644.6  367.86  5650.0  370.09  5673.8  371.26  5679.2  372.96  5765.1  379.07
#Mann=6,-1,0
  4115.3    0.16       0  4181.0    0.12       0  4994.4    0.07       0
  5004.7    0.12       0  5254.0    0.16       0  5322.4    0.05       0
Bank Sta=4651.3,5109.7
Exp/Cntr=0.3,0.1

Chan Stop Cuts=-1