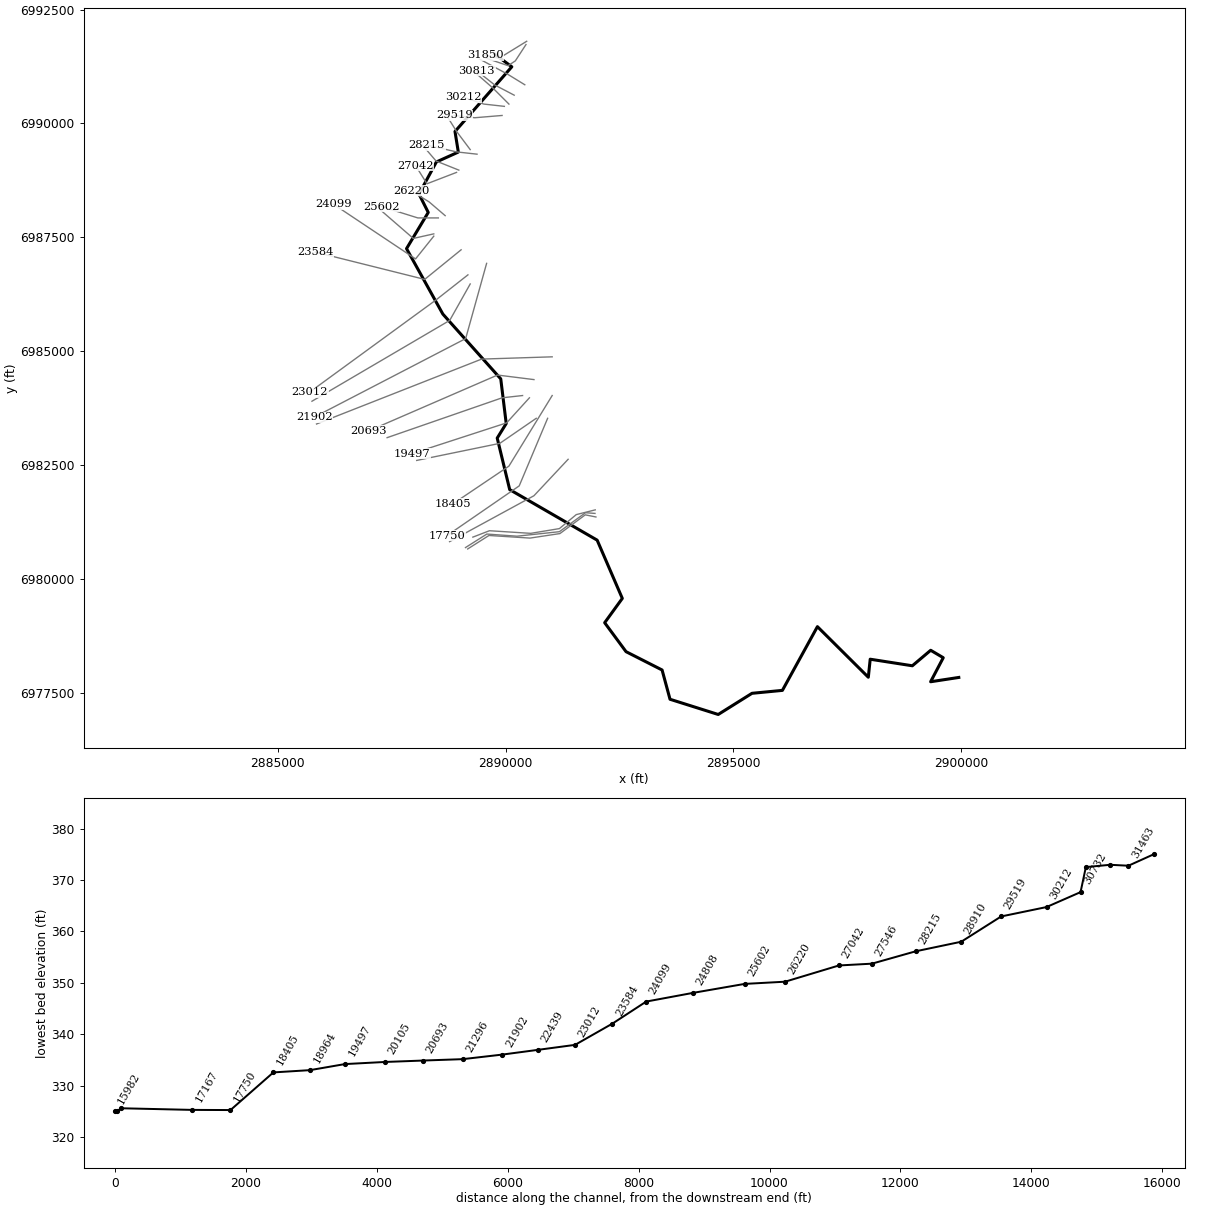
--- GEORGE SLOUGH.prj (project) ---

Proj Title=GEORGE SLOUGH Base Level Engineering
Current Plan=p01
Default Exp/Contr=0.3,0.1
English Units
Geom File=g01
Flow File=f01
Plan File=p01
BEGIN DESCRIPTION:
GEORGE SLOUGH
END DESCRIPTION:

--- GEORGE SLOUGH.p01 (plan) ---

Plan Title=Multiple Run
Short Identifier=Multiple
Geom File=g01
Flow File=f01
Subcritical Flow
K Sum by GR= 0
Std Step Tol= 0.01
Critical Tol= 0.01
Num of Std Step Trials= 20
Max Error Tol= 0.3
Flow Tol Ratio= 0.001
Split Flow NTrial= 30
Split Flow Tol= 0.02
Split Flow Ratio= 0.02
Log Output Level= 0
Friction Slope Method= 1
Unsteady Friction Slope Method= 2
Unsteady Bridges Friction Slope Method= 1
Parabolic Critical Depth
Global Vel Dist=  1 , 1 , 1
Global Log Level= 0
CheckData=True
Encroach Param= -1, 0, 0, 0
BEGIN DESCRIPTION:
Multiple Run
END DESCRIPTION:

--- GEORGE SLOUGH.f01 (steady flow) ---

Flow Title=Multiple
Number of Profiles=7
Profile Names=10-year,25-year,50-year,1pct_min,100-year,1pct_plu,500-year
River Rch & RM= GEORGE SLOUGH,Reach-1,31850
     385     507     604     359     715    1428    1005
River Rch & RM= GEORGE SLOUGH,Reach-1,31463
     708     963    1175     712    1421    2835    2081
River Rch & RM= GEORGE SLOUGH,Reach-1,24099
     989    1366    1682    1028    2050    4091    3055
River Rch & RM= GEORGE SLOUGH,Reach-1,18405
    1208    1681    2079    1275    2545    5077    3821
River Rch & RM= GEORGE SLOUGH,Reach-1,14538
    1522    2129    2641    1623    3238    6460    4880
River Rch & RM= GEORGE SLOUGH,Reach-1,4279
    1688    2365    2936    1804    3600    7183    5429
Boundary for River Rch & Prof#=GEORGE SLOUGH,Reach-1,1
Up Type=0
Dn Type=3
Dn Slope=0.005
Boundary for River Rch & Prof#=GEORGE SLOUGH,Reach-1,2
Up Type=0
Dn Type=3
Dn Slope=0.005
Boundary for River Rch & Prof#=GEORGE SLOUGH,Reach-1,3
Up Type=0
Dn Type=3
Dn Slope=0.005
Boundary for River Rch & Prof#=GEORGE SLOUGH,Reach-1,4
Up Type=0
Dn Type=3
Dn Slope=0.005
Boundary for River Rch & Prof#=GEORGE SLOUGH,Reach-1,5
Up Type=0
Dn Type=3
Dn Slope=0.005
Boundary for River Rch & Prof#=GEORGE SLOUGH,Reach-1,6
Up Type=0
Dn Type=3
Dn Slope=0.005
Boundary for River Rch & Prof#=GEORGE SLOUGH,Reach-1,7
Up Type=0
Dn Type=3
Dn Slope=0.005

--- GEORGE SLOUGH.g01 (geometry) ---

Geom Title=Existing Conditions

River Reach=GEORGE SLOUGH,Reach-1
Reach XY= 30
      2889757.95      6991524.77      2890138.15      6991243.52
      2888890.87      6989822.97      2888963.66      6989371.25
      2888481.49      6989153.49      2888100.01      6988449.57
      2888303.46      6988045.95      2887826.49      6987250.83
      2888623.87      6985814.16      2889895.59      6984390.71
      2890015.54      6983410.50      2889817.90      6983090.76
      2890092.04      6981959.41      2892012.49      6980849.43
      2892564.90      6979570.20      2892177.39      6979036.45
      2892646.73      6978400.52      2893438.27      6977998.33
      2893612.59      6977355.49      2894670.71      6977021.38
      2895412.70      6977486.30      2896080.10      6977550.47
      2896849.21      6978950.01      2897966.72      6977839.08
      2898008.38      6978234.91      2898933.73      6978090.81
      2899336.51      6978431.09      2899612.55      6978267.90
      2899334.77      6977740.12      2899953.47      6977834.55

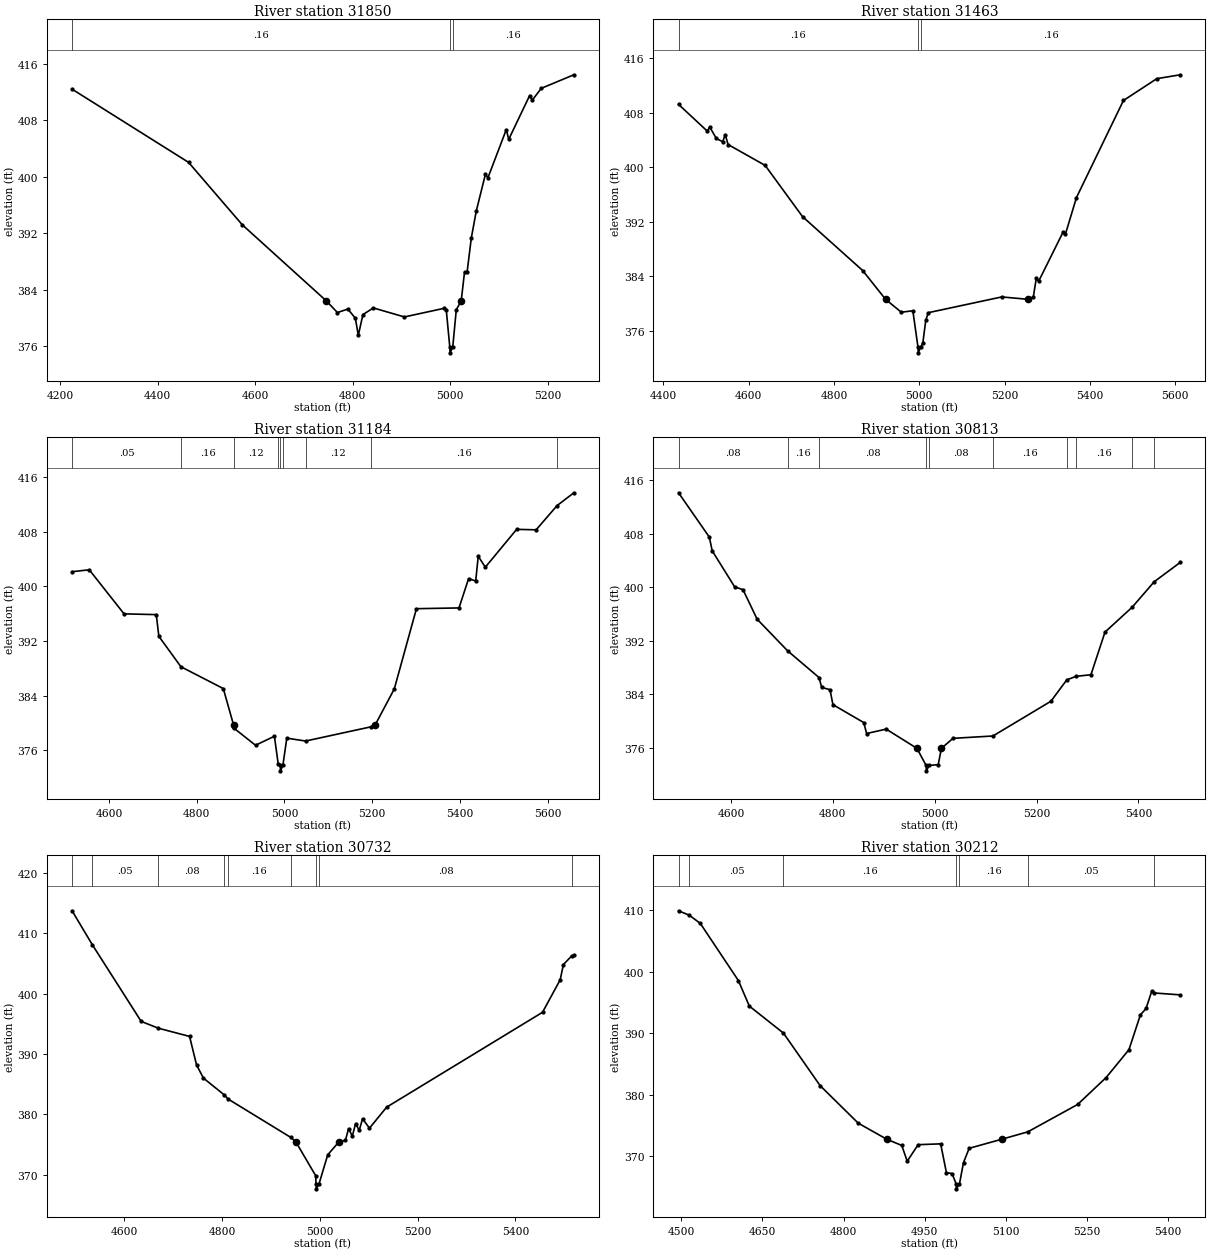
Type RM Length L Ch R = 1,31850,387,387,387
BEGIN DESCRIPTION:
GEORGE SLOUGH 32.0
END DESCRIPTION:
XS GIS Cut Line= 3
      2890465.13      6991804.08      2889855.74      6991429.54
      2889550.04      6991499.99
#Sta/Elev= 30
  4224.8  412.41  4463.7  402.03  4573.8  393.18  4746.3  382.38  4769.0  380.73
  4790.3  381.23  4805.7  379.93  4811.8  377.50  4821.2  380.44  4842.5  381.39
  4906.3  380.11  4986.8  381.32  4992.2  381.07  4999.4  375.82  4999.9  375.02
  5005.4  375.82  5012.7  381.14  5022.8  382.38  5029.6  386.48  5034.8  386.43
  5043.5  391.30  5053.7  395.13  5072.4  400.34  5077.6  399.85  5115.2  406.67
  5120.3  405.30  5163.1  411.50  5168.3  410.84  5187.1  412.53  5253.8  414.45
#Mann=3,-1,0
  4224.8    0.16       0  4999.4    0.07       0  5005.4    0.16       0
Bank Sta=4746.3,5022.8
Exp/Cntr=0.3,0.1

Type RM Length L Ch R = 1,31463,279,279,279
BEGIN DESCRIPTION:
Mapping XS 76e51e4c
END DESCRIPTION:
XS GIS Cut Line= 4
      2890449.47      6991732.23      2890215.12      6991372.90
      2890056.26      6991268.73      2889528.76      6991448.03
#Sta/Elev= 30
  4435.8  409.23  4503.1  405.31  4509.1  405.91  4524.2  404.24  4539.3  403.75
  4545.3  404.80  4551.9  403.34  4638.8  400.28  4726.4  392.77  4867.4  384.86
  4921.0  380.64  4957.9  378.75  4985.0  378.96  4997.1  373.59  4997.6  372.79
  5003.1  373.59  5008.4  374.23  5015.2  377.54  5021.2  378.68  5193.4  380.99
  5254.9  380.64  5267.3  380.96  5274.4  383.76  5279.7  383.27  5337.2  390.51
  5342.5  390.18  5368.5  395.57  5478.6  409.80  5556.8  413.00  5611.9  413.57
#Mann=3,-1,0
  4435.8    0.16       0  4997.1    0.07       0  5003.1    0.16       0
Bank Sta=4921,5254.9
Exp/Cntr=0.3,0.1

Type RM Length L Ch R = 1,31184,371,371,371
BEGIN DESCRIPTION:
Mapping XS 9755bb2f
END DESCRIPTION:
XS GIS Cut Line= 3
      2890423.41      6990849.49      2890045.85      6991081.23
      2889429.33      6991414.20
#Sta/Elev= 30
  4516.1  402.16  4555.3  402.44  4634.6  395.98  4708.0  395.87  4713.9  392.69
  4764.2  388.23  4860.8  385.03  4884.4  379.65  4885.5  379.20  4934.2  376.72
  4977.3  378.04  4986.0  373.95  4990.6  373.77  4991.1  372.97  4996.6  373.77
  5005.5  377.76  5048.4  377.34  5196.6  379.41  5206.5  379.65  5250.5  384.97
  5301.0  396.74  5398.0  396.85  5419.9  401.15  5436.1  400.80  5441.8  404.43
  5458.0  402.82  5529.4  408.37  5573.8  408.30  5621.5  411.85  5659.8  413.73
#Mann=9,-1,0
  4516.1    0.05       0  4764.2    0.16       0  4885.5    0.12       0
  4986.0    0.16       0  4990.6    0.07       0  4996.6    0.16       0
  5048.4    0.12       0  5196.6    0.16       0  5621.5    0.05       0
Bank Sta=4884.4,5206.5
Exp/Cntr=0.3,0.1

Type RM Length L Ch R = 1,30813,81,81,81
BEGIN DESCRIPTION:
Mapping XS 6dd1386b
END DESCRIPTION:
XS GIS Cut Line= 3
      2890190.75      6990620.46      2889763.65      6990844.43
      2889368.90      6991156.07
#Sta/Elev= 30
  4497.0  414.10  4557.5  407.47  4563.1  405.42  4607.2  400.03  4623.6  399.61
  4651.3  395.20  4711.1  390.47  4773.0  386.46  4778.0  384.99  4794.4  384.66
  4800.1  382.42  4860.6  379.74  4866.3  378.10  4904.7  378.76  4965.1  375.88
  4983.1  373.32  4983.6  372.52  4989.1  373.32  5006.9  373.45  5013.1  375.88
  5035.8  377.38  5114.3  377.73  5228.2  382.93  5259.2  386.12  5277.4  386.65
  5306.7  386.89  5334.3  393.27  5387.7  396.99  5430.8  400.79  5482.2  403.70
#Mann=10,-1,0
  4497.0    0.08       0  4711.1    0.16       0  4773.0    0.08       0
  4983.1    0.07       0  4989.1    0.08       0  5114.3    0.16       0
  5259.2    0.08       0  5277.4    0.16       0  5387.7    0.08       0
  5430.8    0.05       0
Bank Sta=4965.1,5013.1
Exp/Cntr=0.3,0.1

Type RM Length L Ch R = 1,30732,520,520,520
BEGIN DESCRIPTION:
GEORGE SLOUGH 31.0
END DESCRIPTION:
XS GIS Cut Line= 3
      2890075.01      6990424.99      2889725.00      6990775.00
      2889325.00      6991125.00
#Sta/Elev= 30
  4493.1  413.75  4534.3  408.15  4634.5  395.41  4669.6  394.28  4733.5  392.92
  4747.7  388.20  4761.8  386.01  4804.8  383.20  4811.9  382.56  4940.0  376.20
  4950.9  375.44  4991.4  369.83  4992.2  368.45  4992.7  367.65  4998.2  368.45
  5016.1  373.29  5039.0  375.44  5052.2  375.67  5058.8  377.64  5066.4  376.38
  5073.0  378.45  5080.6  377.36  5087.3  379.27  5101.5  377.71  5136.6  381.19
  5455.5  396.92  5491.6  402.30  5498.2  404.84  5515.5  406.29  5519.6  406.39
#Mann=9,-1,0
  4493.1    0.16       0  4534.3    0.05       0  4669.6    0.08       0
  4804.8    0.05       0  4811.9    0.16       0  4940.0    0.08       0
  4992.2    0.07       0  4998.2    0.08       0  5515.5    0.05       0
Bank Sta=4950.9,5039
Exp/Cntr=0.3,0.1

Type RM Length L Ch R = 1,30212,693,693,693
BEGIN DESCRIPTION:
GEORGE SLOUGH 30.0
END DESCRIPTION:
XS GIS Cut Line= 3
      2889974.95      6990375.01      2889525.00      6990425.00
      2889074.97      6990575.01
#Sta/Elev= 30
  4495.2  409.87  4515.3  409.14  4535.4  407.82  4605.8  398.54  4626.0  394.40
  4689.0  390.02  4756.8  381.49  4827.2  375.40  4879.7  372.80  4907.7  371.78
  4917.7  369.22  4937.9  371.91  4979.5  372.04  4990.1  367.38  5000.6  367.22
  5008.1  365.54  5008.6  364.74  5014.2  365.54  5021.7  369.00  5032.2  371.32
  5092.8  372.80  5140.5  373.99  5232.5  378.43  5285.2  382.80  5327.4  387.33
  5348.5  392.97  5359.0  394.01  5369.6  396.85  5374.0  396.53  5422.3  396.22
#Mann=7,-1,0
  4495.2    0.16       0  4515.3    0.05       0  4689.0    0.16       0
  5008.1    0.07       0  5014.2    0.16       0  5140.5    0.05       0
  5374.0    0.16       0
Bank Sta=4879.7,5092.8
Exp/Cntr=0.3,0.1

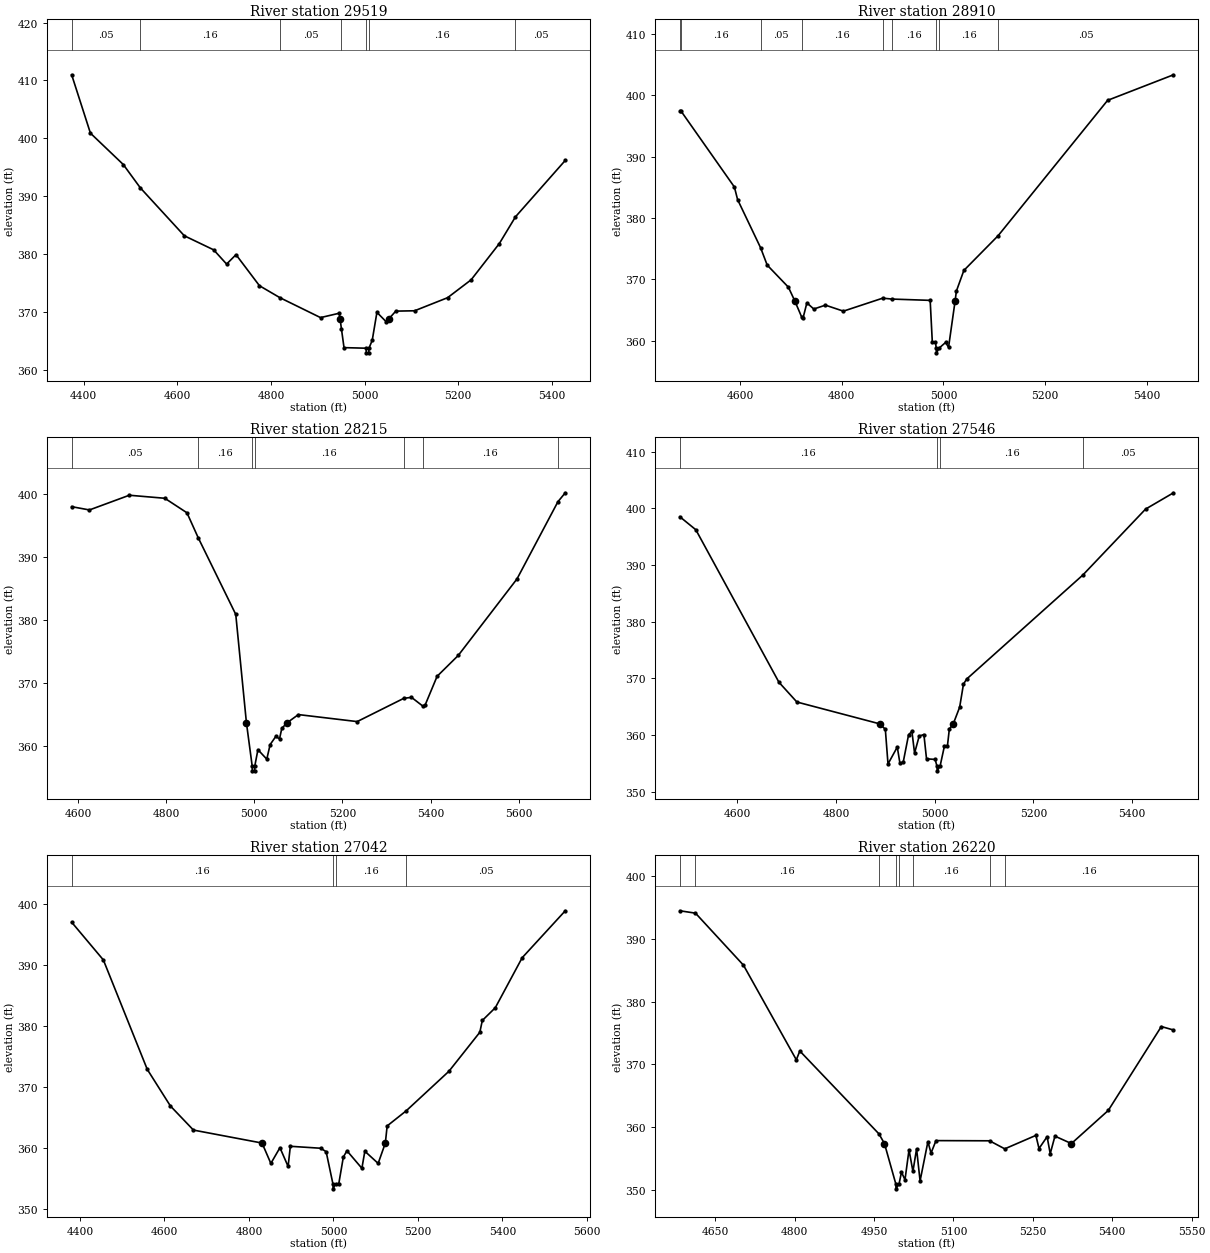
Type RM Length L Ch R = 1,29519,609,609,609
BEGIN DESCRIPTION:
GEORGE SLOUGH 29.0
END DESCRIPTION:
XS GIS Cut Line= 3
      2889924.96      6990175.00      2889325.00      6990125.00
      2888875.01      6990175.00
#Sta/Elev= 30
  4374.1  410.97  4414.2  400.88  4484.4  395.46  4520.8  391.43  4614.9  383.14
  4677.6  380.71  4705.2  378.25  4725.3  379.88  4775.4  374.51  4819.2  372.44
  4905.9  369.00  4946.0  369.76  4947.7  368.75  4950.6  367.04  4956.1  363.81
  5003.3  363.71  5003.8  362.91  5008.9  362.91  5009.4  363.71  5016.4  365.08
  5026.4  369.91  5046.6  368.25  5051.5  368.75  5066.7  370.12  5106.9  370.18
  5177.4  372.44  5227.7  375.53  5288.0  381.80  5322.5  386.42  5428.9  396.17
#Mann=7,-1,0
  4374.1    0.05       0  4520.8    0.16       0  4819.2    0.05       0
  4950.6    0.16       0  5003.3    0.07       0  5009.4    0.16       0
  5322.5    0.05       0
Bank Sta=4947.7,5051.5
Exp/Cntr=0.3,0.1

Type RM Length L Ch R = 1,28910,695,695,695
BEGIN DESCRIPTION:
GEORGE SLOUGH 28.0
END DESCRIPTION:
XS GIS Cut Line= 3
      2889225.02      6989424.98      2888925.00      6989825.00
      2888675.01      6990224.98
#Sta/Elev= 30
  4481.3  397.48  4483.1  397.48  4588.6  385.04  4594.9  382.99  4640.2  375.13
  4653.2  372.30  4694.9  368.70  4707.5  366.46  4720.8  363.88  4724.0  363.75
  4731.3  366.14  4744.9  365.14  4767.8  365.77  4803.2  364.79  4880.6  366.91
  4899.0  366.76  4974.0  366.55  4978.2  359.76  4984.3  359.76  4985.9  358.79
  4986.4  357.99  4992.0  358.79  5004.3  359.68  5010.2  358.90  5023.1  366.46
  5025.6  368.06  5040.3  371.43  5107.8  377.10  5323.3  399.18  5453.0  403.35
#Mann=9,-1,0
  4481.3    0.05       0  4483.1    0.16       0  4640.2    0.05       0
  4720.8    0.16       0  4880.6    0.05       0  4899.0    0.16       0
  4985.9    0.07       0  4992.0    0.16       0  5107.8    0.05       0
Bank Sta=4707.5,5023.1
Exp/Cntr=0.3,0.1

Type RM Length L Ch R = 1,28215,669,669,669
BEGIN DESCRIPTION:
GEORGE SLOUGH 27.0
END DESCRIPTION:
XS GIS Cut Line= 3
      2889375.04      6989325.00      2888925.00      6989375.00
      2888274.99      6989525.00
#Sta/Elev= 30
  4585.6  397.97  4625.9  397.45  4716.4  399.78  4796.9  399.30  4847.2  397.00
  4872.5  393.08  4957.9  380.91  4982.1  363.75  4995.1  356.93  4995.6  356.13
  5000.7  356.13  5001.2  356.93  5008.2  359.48  5028.3  357.98  5035.9  360.29
  5048.7  361.57  5057.2  361.20  5062.4  362.86  5074.5  363.75  5100.0  365.04
  5233.4  363.93  5339.0  367.61  5356.6  367.77  5382.2  366.39  5387.3  366.51
  5414.7  371.10  5462.6  374.40  5596.0  386.53  5688.8  398.75  5705.5  400.17
#Mann=7,-1,0
  4585.6    0.05       0  4872.5    0.16       0  4995.1    0.07       0
  5001.2    0.16       0  5339.0    0.05       0  5382.2    0.16       0
  5688.8    0.05       0
Bank Sta=4982.1,5074.5
Exp/Cntr=0.3,0.1

Type RM Length L Ch R = 1,27546,504,504,504
BEGIN DESCRIPTION:
GEORGE SLOUGH 26.0
END DESCRIPTION:
XS GIS Cut Line= 3
      2888974.97      6988975.01      2888475.00      6989175.00
      2888174.98      6989525.03
#Sta/Elev= 30
  4484.1  398.50  4516.4  396.21  4684.7  369.33  4721.0  365.85  4888.3  362.01
  4900.1  361.05  4905.5  354.93  4924.3  357.91  4929.7  355.04  4936.4  355.29
  4947.2  360.08  4953.9  360.68  4959.3  356.84  4968.7  359.85  4978.2  360.12
  4983.5  355.84  5001.0  355.73  5004.7  354.52  5005.2  353.72  5010.9  354.52
  5019.9  358.15  5025.9  358.15  5029.7  361.08  5037.7  362.01  5050.6  364.94
  5058.3  369.00  5064.8  369.90  5300.0  388.23  5427.0  399.85  5483.6  402.73
#Mann=4,-1,0
  4484.1    0.16       0  5004.7    0.07       0  5010.9    0.16       0
  5300.0    0.05       0
Bank Sta=4888.3,5037.7
Exp/Cntr=0.3,0.1

Type RM Length L Ch R = 1,27042,822,822,822
BEGIN DESCRIPTION:
GEORGE SLOUGH 25.0
END DESCRIPTION:
XS GIS Cut Line= 3
      2888925.02      6988925.01      2888275.00      6988675.00
      2888025.02      6989074.97
#Sta/Elev= 30
  4380.6  396.98  4455.6  390.81  4559.5  372.91  4614.2  366.93  4668.8  362.98
  4831.1  360.86  4852.0  357.53  4873.5  360.10  4892.8  357.03  4898.1  360.33
  4969.9  360.01  4982.8  359.45  4998.9  354.17  4999.4  353.37  5005.1  354.17
  5012.8  354.24  5023.5  358.56  5032.0  359.60  5067.4  356.73  5074.4  359.52
  5105.9  357.53  5122.9  360.86  5127.2  363.66  5172.1  366.12  5273.4  372.60
  5346.5  378.98  5352.4  380.91  5383.1  382.99  5446.7  391.17  5548.7  398.85
#Mann=4,-1,0
  4380.6    0.16       0  4998.9    0.07       0  5005.1    0.16       0
  5172.1    0.05       0
Bank Sta=4831.1,5122.9
Exp/Cntr=0.3,0.1

Type RM Length L Ch R = 1,26220,618,618,618
BEGIN DESCRIPTION:
GEORGE SLOUGH 24.0
END DESCRIPTION:
XS GIS Cut Line= 3
      2888674.96      6987975.03      2888325.00      6988275.00
      2887925.02      6988524.99
#Sta/Elev= 30
  4583.1  394.43  4612.6  394.05  4703.2  385.78  4803.1  370.73  4809.7  372.13
  4959.2  358.95  4969.6  357.41  4991.0  351.01  4991.5  350.21  4997.2  351.01
  5001.8  352.86  5008.4  351.65  5016.0  356.41  5023.4  352.98  5030.3  356.58
  5036.9  351.47  5051.7  357.71  5057.6  355.90  5067.0  357.88  5168.2  357.85
  5196.9  356.57  5255.7  358.71  5261.6  356.62  5276.9  358.50  5282.8  355.80
  5291.7  358.59  5322.8  357.41  5392.5  362.68  5492.7  376.02  5515.7  375.47
#Mann=8,-1,0
  4583.1    0.05       0  4612.6    0.16       0  4959.2    0.12       0
  4991.0    0.07       0  4997.2    0.12       0  5023.4    0.16       0
  5168.2    0.12       0  5196.9    0.16       0
Bank Sta=4969.6,5322.8
Exp/Cntr=0.3,0.1

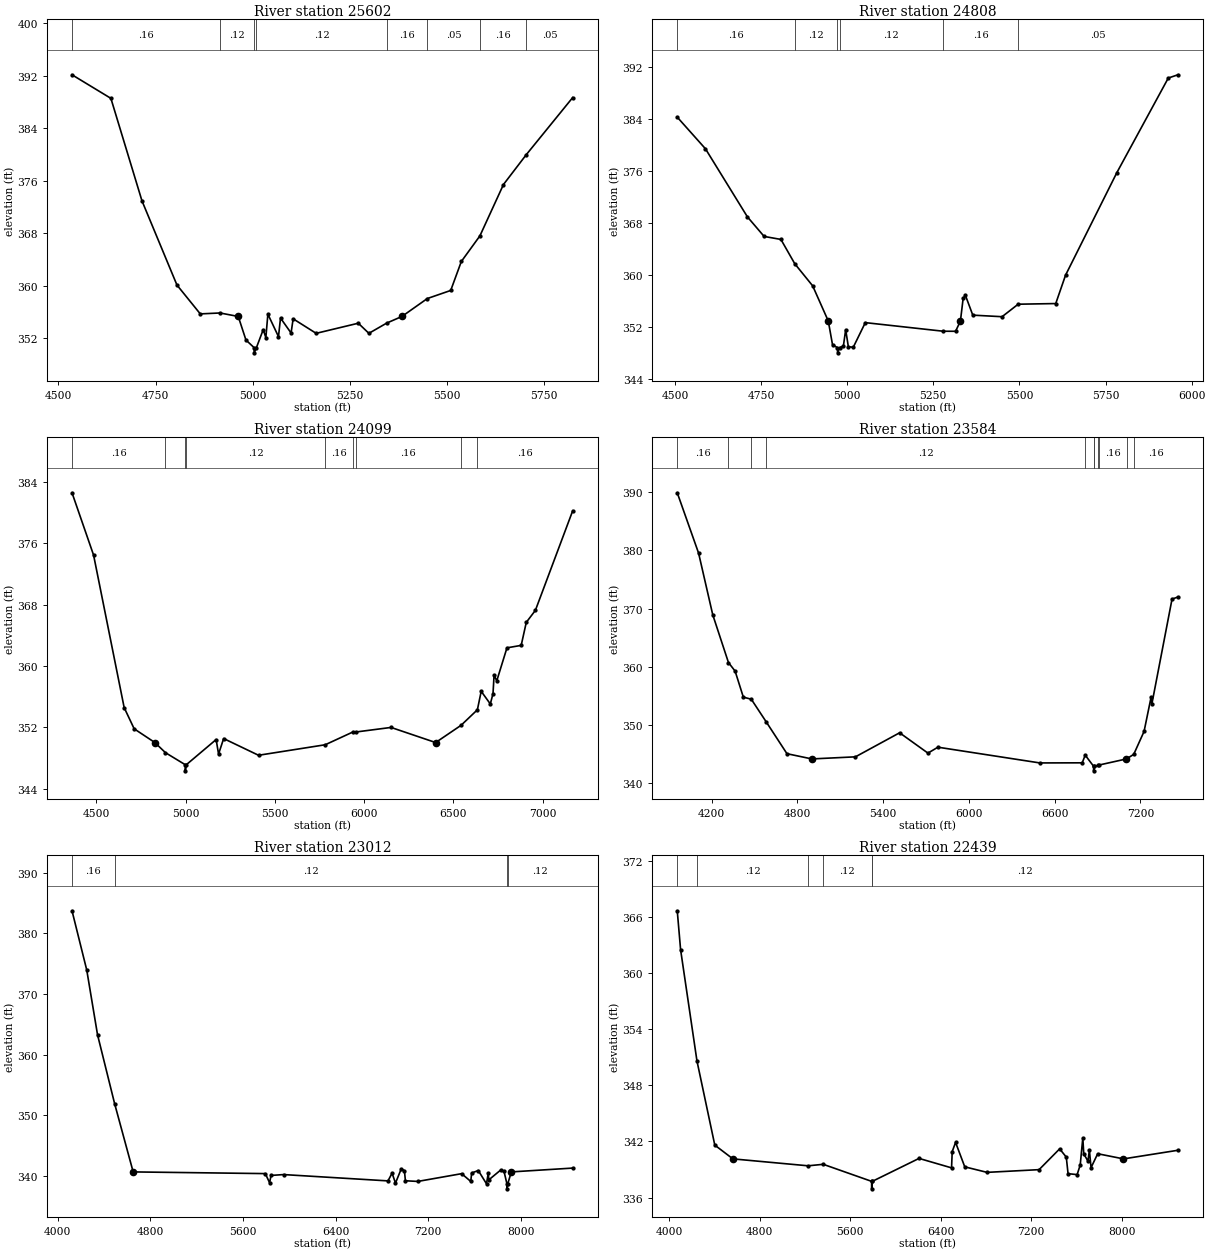
Type RM Length L Ch R = 1,25602,794,794,794
BEGIN DESCRIPTION:
GEORGE SLOUGH 23.0
END DESCRIPTION:
XS GIS Cut Line= 3
      2888524.97      6987925.00      2888075.00      6987925.00
      2887275.02      6988174.99
#Sta/Elev= 30
  4535.0  392.12  4635.0  388.53  4715.0  372.92  4805.0  360.10  4865.0  355.71
  4915.8  355.85  4962.7  355.32  4982.5  351.73  5003.3  350.58  5003.8  349.78
  5009.5  350.58  5026.9  353.31  5033.7  352.10  5038.9  355.67  5066.2  352.25
  5071.4  355.08  5098.6  352.80  5103.9  354.96  5163.1  352.75  5271.5  354.29
  5298.8  352.75  5344.6  354.31  5383.8  355.32  5449.2  358.05  5509.3  359.28
  5536.6  363.69  5584.4  367.59  5645.0  375.41  5703.9  379.97  5823.1  388.65
#Mann=8,-1,0
  4535.0    0.16       0  4915.8    0.12       0  5003.3    0.07       0
  5009.5    0.12       0  5344.6    0.16       0  5449.2    0.05       0
  5584.4    0.16       0  5703.9    0.05       0
Bank Sta=4962.7,5383.8
Exp/Cntr=0.3,0.1

Type RM Length L Ch R = 1,24808,709,709,709
BEGIN DESCRIPTION:
GEORGE SLOUGH 22.0
END DESCRIPTION:
XS GIS Cut Line= 3
      2888424.95      6987574.99      2887975.00      6987475.00
      2887225.00      6988125.00
#Sta/Elev= 30
  4506.8  384.22  4588.7  379.36  4710.4  368.91  4759.0  365.90  4807.7  365.44
  4848.0  361.70  4899.9  358.31  4945.2  352.91  4957.5  349.27  4971.8  348.82
  4972.3  348.02  4978.0  348.82  4989.1  349.06  4995.7  351.58  5003.4  348.98
  5017.6  348.86  5052.7  352.66  5278.8  351.34  5314.8  351.33  5328.8  352.91
  5336.7  356.37  5343.3  356.85  5364.7  353.81  5449.7  353.57  5496.4  355.49
  5605.5  355.59  5634.0  359.95  5783.1  375.72  5932.2  390.23  5960.2  390.73
#Mann=6,-1,0
  4506.8    0.16       0  4848.0    0.12       0  4971.8    0.07       0
  4978.0    0.12       0  5278.8    0.16       0  5496.4    0.05       0
Bank Sta=4945.2,5328.8
Exp/Cntr=0.3,0.1

Type RM Length L Ch R = 1,24099,515,515,515
BEGIN DESCRIPTION:
GEORGE SLOUGH 21.0
END DESCRIPTION:
XS GIS Cut Line= 3
      2888424.98      6987524.98      2888025.00      6987025.00
      2886225.01      6988224.99
#Sta/Elev= 30
  4364.4  382.60  4485.2  374.47  4656.5  354.58  4712.5  351.82  4828.3  350.03
  4887.6  348.71  4998.4  347.14  4998.9  346.34  5004.6  347.14  5171.4  350.42
  5185.0  348.53  5213.5  350.55  5408.8  348.37  5782.2  349.74  5938.6  351.42
  5952.6  351.40  6150.9  352.00  6400.6  350.03  6543.1  352.28  6634.3  354.30
  6655.7  356.71  6706.8  355.06  6721.8  356.41  6727.8  358.81  6742.9  358.08
  6799.9  362.38  6879.6  362.70  6908.1  365.70  6959.2  367.27  7168.0  380.25
#Mann=9,-1,0
  4364.4    0.16       0  4887.6    0.12       0  4998.4    0.07       0
  5004.6    0.12       0  5782.2    0.16       0  5938.6    0.12       0
  5952.6    0.16       0  6543.1    0.12       0  6634.3    0.16       0
Bank Sta=4828.3,6400.6
Exp/Cntr=0.3,0.1

Type RM Length L Ch R = 1,23584,572,572,572
BEGIN DESCRIPTION:
GEORGE SLOUGH 20.0
END DESCRIPTION:
XS GIS Cut Line= 3
      2889025.01      6987225.01      2888225.00      6986575.00
      2885824.96      6987175.01
#Sta/Elev= 30
  3958.3  389.92  4107.7  379.53  4206.8  368.92  4316.7  360.70  4363.4  359.22
  4420.9  354.74  4476.5  354.39  4581.8  350.46  4726.2  345.01  4900.5  344.11
  5205.6  344.47  5514.8  348.61  5713.2  345.11  5782.8  346.13  6496.6  343.42
  6793.0  343.44  6814.0  344.76  6872.3  342.86  6872.8  342.06  6878.6  342.86
  6902.9  342.98  6910.8  343.06  7102.7  344.11  7108.2  344.19  7153.7  344.90
  7225.9  348.84  7274.8  354.69  7280.0  353.50  7421.7  371.62  7463.0  371.98
#Mann=11,-1,0
  3958.3    0.16       0  4316.7    0.12       0  4476.5    0.16       0
  4581.8    0.12       0  6814.0    0.16       0  6872.3    0.07       0
  6878.6    0.16       0  6902.9    0.12       0  6910.8    0.16       0
  7108.2    0.12       0  7153.7    0.16       0
Bank Sta=4900.5,7102.7
Exp/Cntr=0.3,0.1

Type RM Length L Ch R = 1,23012,573,573,573
BEGIN DESCRIPTION:
GEORGE SLOUGH 19.0
END DESCRIPTION:
XS GIS Cut Line= 3
      2889174.97      6986674.98      2888475.00      6986125.00
      2885699.98      6984099.99
#Sta/Elev= 30
  4123.5  383.72  4250.9  373.95  4344.0  363.29  4491.9  351.92  4651.8  340.70
  5793.6  340.42  5830.5  338.91  5843.1  340.12  5951.8  340.26  6853.2  339.22
  6888.7  340.49  6918.1  338.86  6968.3  341.22  6995.3  340.90  7003.8  339.24
  7110.4  339.13  7489.6  340.41  7568.4  339.13  7576.2  340.52  7633.3  340.93
  7704.4  338.74  7719.1  340.44  7725.2  339.40  7825.7  340.99  7855.0  340.84
  7881.2  338.71  7881.7  337.91  7887.5  338.71  7919.0  340.70  8449.0  341.33
#Mann=4,-1,0
  4123.5    0.16       0  4491.9    0.12       0  7881.2    0.07       0
  7887.5    0.12       0
Bank Sta=4651.8,7919
Exp/Cntr=0.3,0.1

Type RM Length L Ch R = 1,22439,537,537,537
BEGIN DESCRIPTION:
GEORGE SLOUGH 18.0
END DESCRIPTION:
XS GIS Cut Line= 3
      2889225.00      6986475.00      2888775.00      6985675.00
      2885749.99      6983899.99
#Sta/Elev= 30
  4072.1  366.63  4101.7  362.47  4246.3  350.59  4403.9  341.60  4563.9  340.13
  5229.0  339.39  5362.4  339.55  5789.9  337.73  5790.4  336.93  5796.2  337.73
  6209.2  340.18  6496.5  339.17  6502.3  340.91  6532.0  341.89  6613.2  339.28
  6810.3  338.69  7270.2  338.98  7451.9  341.20  7510.5  340.32  7526.2  338.55
  7606.3  338.45  7633.6  339.47  7656.7  342.38  7664.9  340.67  7702.1  339.89
  7714.7  341.06  7729.4  339.19  7788.0  340.68  8016.2  340.13  8497.3  341.05
#Mann=6,-1,0
  4072.1    0.16       0  4246.3    0.12       0  5229.0    0.07       0
  5362.4    0.12       0  5789.9    0.07       0  5796.2    0.12       0
Bank Sta=4563.9,8016.2
Exp/Cntr=0.3,0.1

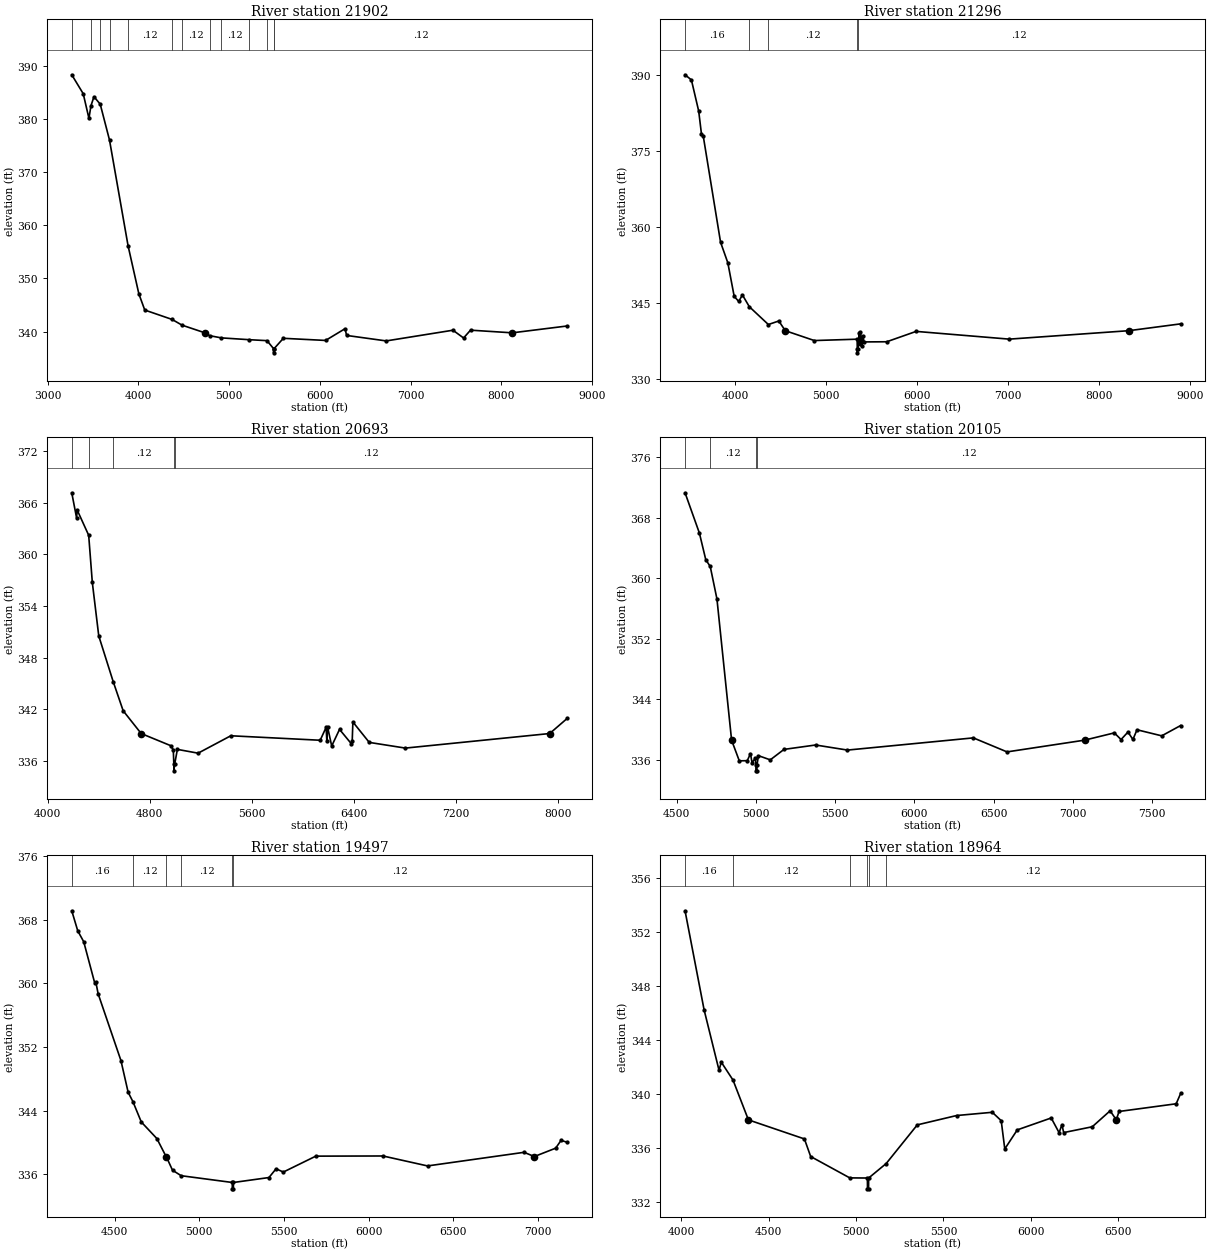
Type RM Length L Ch R = 1,21902,606,606,606
BEGIN DESCRIPTION:
GEORGE SLOUGH 17.0
END DESCRIPTION:
XS GIS Cut Line= 3
      2889585.13      6986927.34      2889125.00      6985275.00
      2885800.04      6983550.02
#Sta/Elev= 30
  3267.2  388.26  3393.6  384.70  3456.5  380.07  3478.6  382.43  3511.8  384.14
  3580.8  382.74  3683.1  376.00  3887.6  356.14  4006.6  347.10  4071.6  344.06
  4372.0  342.30  4482.6  341.22  4734.5  339.78  4787.9  339.24  4915.5  338.83
  5222.6  338.49  5418.5  338.31  5490.5  336.82  5491.0  336.02  5497.2  336.82
  5598.8  338.75  6063.9  338.35  6279.0  340.56  6295.5  339.29  6732.3  338.26
  7467.6  340.27  7584.8  338.81  7661.1  340.28  8121.1  339.78  8728.2  341.07
#Mann=13,-1,0
  3267.2    0.12       0  3478.6    0.16       0  3580.8    0.12       0
  3683.1    0.16       0  3887.6    0.12       0  4372.0    0.16       0
  4482.6    0.12       0  4787.9    0.05       0  4915.5    0.12       0
  5222.6    0.07       0  5418.5    0.12       0  5490.5    0.07       0
  5497.2    0.12       0
Bank Sta=4734.5,8121.1
Exp/Cntr=0.3,0.1

Type RM Length L Ch R = 1,21296,603,603,603
BEGIN DESCRIPTION:
GEORGE SLOUGH 16.0
END DESCRIPTION:
XS GIS Cut Line= 3
      2891024.96      6984875.00      2889475.00      6984825.00
      2885850.00      6983400.00
#Sta/Elev= 30
  3449.9  390.12  3519.9  389.10  3599.9  382.94  3630.0  378.46  3650.0  378.00
  3840.1  357.01  3920.1  352.93  3990.1  346.29  4040.2  345.29  4080.2  346.59
  4156.3  344.25  4365.4  340.73  4480.4  341.43  4551.2  339.51  4870.6  337.56
  5340.7  337.83  5342.8  335.93  5343.3  335.13  5349.5  335.93  5365.1  339.08
  5370.5  336.95  5376.7  339.26  5394.9  336.46  5400.3  338.52  5419.3  337.29
  5665.9  337.32  5989.2  339.37  7012.5  337.84  8326.4  339.51  8895.7  340.86
#Mann=5,-1,0
  3449.9    0.16       0  4156.3    0.05       0  4365.4    0.12       0
  5342.8    0.07       0  5349.5    0.12       0
Bank Sta=4551.2,8326.4
Exp/Cntr=0.3,0.1

Type RM Length L Ch R = 1,20693,588,588,588
BEGIN DESCRIPTION:
GEORGE SLOUGH 15.0
END DESCRIPTION:
XS GIS Cut Line= 3
      2890624.98      6984375.00      2889825.00      6984475.00
      2886999.97      6983249.99
#Sta/Elev= 30
  4187.6  367.13  4225.4  364.22  4230.4  365.12  4320.3  362.20  4348.8  356.72
  4399.2  350.52  4512.3  345.22  4590.7  341.83  4731.8  339.19  4963.6  337.78
  4983.7  337.28  4987.8  335.66  4988.3  334.86  4994.7  335.66  5015.6  337.35
  5178.0  336.91  5434.5  338.93  6135.2  338.41  6181.9  339.91  6187.5  338.28
  6193.0  339.97  6225.5  337.74  6286.9  339.67  6378.1  338.03  6386.2  338.27
  6391.6  340.53  6519.9  338.16  6803.2  337.50  7934.6  339.19  8073.0  340.96
#Mann=5,-1,0
  4187.6     0.1       0  4320.3    0.16       0  4512.3    0.12       0
  4987.8    0.07       0  4994.7    0.12       0
Bank Sta=4731.8,7934.6
Exp/Cntr=0.3,0.1

Type RM Length L Ch R = 1,20105,608,608,608
BEGIN DESCRIPTION:
GEORGE SLOUGH 14.0
END DESCRIPTION:
XS GIS Cut Line= 3
      2890374.98      6984025.00      2889925.00      6983975.00
      2887399.96      6983099.99
#Sta/Elev= 30
  4553.3  371.28  4643.8  365.96  4684.1  362.44  4712.2  361.55  4754.5  357.26
  4846.8  338.63  4895.4  335.90  4945.7  335.92  4965.8  336.85  4975.9  335.65
  4996.0  336.25  5000.0  335.38  5000.5  334.58  5006.5  334.58  5007.0  335.38
  5016.3  336.58  5090.7  336.03  5177.3  337.41  5376.5  337.99  5577.6  337.32
  6371.3  338.93  6583.6  337.08  7072.9  338.63  7260.3  339.59  7302.6  338.71
  7346.3  339.70  7377.5  338.72  7403.3  340.00  7559.1  339.20  7678.4  340.56
#Mann=4,-1,0
  4553.3    0.16       0  4712.2    0.12       0  5000.0    0.07       0
  5007.0    0.12       0
Bank Sta=4846.8,7072.9
Exp/Cntr=0.3,0.1

Type RM Length L Ch R = 1,19497,533,533,533
BEGIN DESCRIPTION:
GEORGE SLOUGH 13.0
END DESCRIPTION:
XS GIS Cut Line= 3
      2890525.01      6983975.01      2890025.00      6983425.00
      2887950.04      6982750.01
#Sta/Elev= 30
  4247.2  369.12  4282.7  366.59  4317.8  365.23  4382.0  360.10  4388.8  360.21
  4403.0  358.68  4537.4  350.30  4580.0  346.31  4608.2  345.13  4657.7  342.57
  4749.6  340.49  4803.5  338.25  4804.9  338.23  4841.9  336.51  4893.0  335.82
  5194.6  334.97  5195.1  334.17  5201.1  334.17  5201.7  334.97  5411.1  335.59
  5453.2  336.69  5496.1  336.28  5687.7  338.28  6084.2  338.30  6347.1  337.05
  6917.0  338.76  6977.7  338.23  7103.4  339.28  7135.3  340.26  7172.5  340.02
#Mann=6,-1,0
  4247.2    0.16       0  4608.2    0.12       0  4803.5    0.07       0
  4893.0    0.12       0  5194.6    0.07       0  5201.7    0.12       0
Bank Sta=4804.9,6977.7
Exp/Cntr=0.3,0.1

Type RM Length L Ch R = 1,18964,559,559,559
BEGIN DESCRIPTION:
GEORGE SLOUGH 12.0
END DESCRIPTION:
XS GIS Cut Line= 3
      2890674.96      6983524.97      2889875.00      6982975.00
      2888050.01      6982600.00
#Sta/Elev= 30
  4022.7  353.55  4131.6  346.23  4216.8  341.77  4230.3  342.35  4297.1  341.03
  4385.0  338.09  4705.3  336.68  4741.1  335.38  4964.6  333.80  5065.4  333.79
  5066.0  332.99  5072.1  332.99  5072.6  333.79  5172.8  334.86  5350.8  337.72
  5575.4  338.41  5779.6  338.65  5830.6  338.03  5851.0  335.94  5922.5  337.35
  6116.5  338.23  6161.7  337.14  6177.7  337.73  6187.9  337.15  6351.3  337.58
  6453.4  338.76  6488.8  338.09  6504.1  338.71  6831.1  339.28  6856.6  340.04
#Mann=6,-1,0
  4022.7    0.16       0  4297.1    0.12       0  4964.6    0.07       0
  5065.4    0.07       0  5072.6    0.07       0  5172.8    0.12       0
Bank Sta=4385,6488.8
Exp/Cntr=0.3,0.1

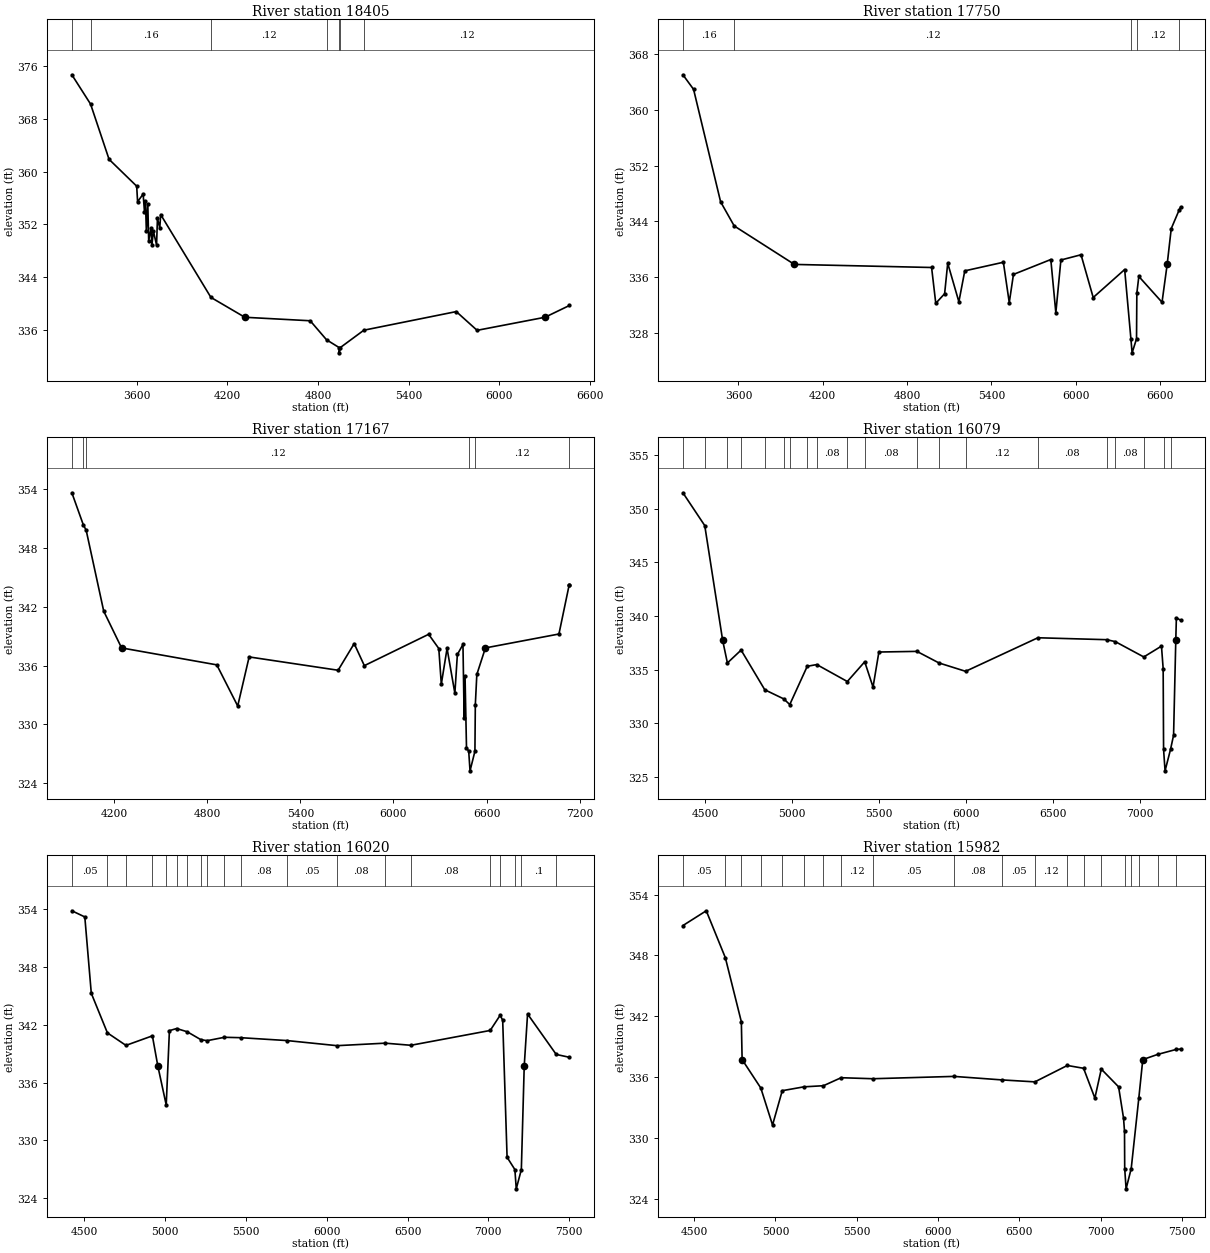
Type RM Length L Ch R = 1,18405,655,655,655
BEGIN DESCRIPTION:
GEORGE SLOUGH 11.0
END DESCRIPTION:
XS GIS Cut Line= 3
      2891025.00      6984025.00      2890075.00      6982475.00
      2888849.98      6981649.99
#Sta/Elev= 30
  3170.9  374.68  3294.8  370.24  3417.2  361.87  3600.2  357.80  3606.1  355.44
  3642.8  356.61  3651.8  353.91  3658.3  355.56  3664.1  351.01  3673.7  355.09
  3679.6  349.53  3695.0  351.43  3700.9  348.84  3710.4  351.03  3731.7  348.88
  3737.6  352.93  3753.0  351.47  3758.9  353.50  4091.6  340.95  4316.1  337.94
  4749.0  337.41  4857.1  334.53  4940.4  333.35  4941.1  332.55  4948.4  333.35
  5104.3  335.98  5716.1  338.80  5854.0  335.96  6303.7  337.94  6465.8  339.73
#Mann=7,-1,0
  3170.9     0.1       0  3294.8    0.16       0  4091.6    0.12       0
  4857.1    0.07       0  4940.4    0.07       0  4948.4    0.07       0
  5104.3    0.12       0
Bank Sta=4316.1,6303.7
Exp/Cntr=0.3,0.1

Type RM Length L Ch R = 1,17750,583,583,583
BEGIN DESCRIPTION:
GEORGE SLOUGH 10.0
END DESCRIPTION:
XS GIS Cut Line= 3
      2890924.98      6983524.96      2890300.72      6982040.74
      2888710.61      6980945.96
#Sta/Elev= 30
  3205.0  364.97  3280.9  362.89  3473.3  346.81  3570.1  343.36  3998.4  337.86
  4974.5  337.42  5004.2  332.30  5067.2  333.67  5089.2  338.03  5168.6  332.52
  5210.6  336.94  5485.2  338.17  5527.1  332.40  5556.9  336.43  5822.7  338.56
  5858.5  330.95  5894.4  338.49  6037.7  339.24  6124.3  333.13  6348.2  337.13
  6392.6  327.22  6401.1  325.22  6432.6  327.22  6434.8  333.75  6449.0  336.14
  6614.0  332.45  6650.6  337.86  6679.6  342.98  6736.1  345.65  6745.7  346.04
#Mann=5,-1,0
  3205.0    0.16       0  3570.1    0.12       0  6392.6    0.07       0
  6432.6    0.12       0  6736.1    0.16       0
Bank Sta=3998.4,6650.6
Exp/Cntr=0.3,0.1

Type RM Length L Ch R = 1,17167,1088,1088,1088
BEGIN DESCRIPTION:
GEORGE SLOUGH 9.0
END DESCRIPTION:
XS GIS Cut Line= 3
      2891374.98      6982624.97      2890625.00      6981825.00
      2888772.14      6980816.48
#Sta/Elev= 30
  3927.9  353.64  4001.4  350.38  4020.2  349.81  4133.2  341.55  4248.3  337.80
  4861.6  336.07  4996.4  331.87  5070.0  336.88  5643.2  335.52  5746.8  338.24
  5812.3  335.99  6226.4  339.19  6291.9  337.74  6308.1  334.10  6345.2  337.75
  6395.5  333.17  6411.6  337.13  6447.6  338.15  6455.3  330.66  6461.0  334.89
  6470.4  327.61  6484.7  327.25  6493.2  325.25  6524.7  327.25  6527.3  332.01
  6537.0  335.09  6592.3  337.80  7066.0  339.22  7131.9  344.23  7134.0  344.23
#Mann=6,-1,0
  3927.9    0.12       0  4001.4    0.16       0  4020.2    0.12       0
  6484.7    0.07       0  6524.7    0.12       0  7131.9    0.16       0
Bank Sta=4248.3,6592.3
Exp/Cntr=0.3,0.1

Type RM Length L Ch R = 1,16079,59,59,59
BEGIN DESCRIPTION:
Mapping XS 0e3f9670
END DESCRIPTION:
XS GIS Cut Line= 6
      2891970.12      6981514.53      2891553.49      6981410.37
      2891183.70      6981103.08      2890553.49      6980998.91
      2889647.24      6981056.20      2889282.70      6980915.59
#Sta/Elev= 30
  4371.1  351.50  4496.8  348.44  4599.8  337.73  4627.0  335.63  4705.8  336.83
  4841.9  333.13  4950.9  332.28  4985.6  331.75  5086.1  335.32  5140.9  335.48
  5316.6  333.90  5416.6  335.74  5464.4  333.38  5498.1  336.65  5716.6  336.71
  5843.7  335.63  5996.8  334.85  6412.3  337.98  6808.2  337.80  6857.4  337.62
  7021.3  336.19  7123.0  337.20  7132.7  335.11  7135.1  327.57  7143.6  325.57
  7175.1  327.57  7192.6  328.89  7205.3  337.74  7208.7  339.84  7232.6  339.62
#Mann=20,-1,0
  4371.1    0.05       0  4496.8    0.12       0  4627.0    0.08       0
  4705.8    0.12       0  4841.9    0.08       0  4950.9    0.12       0
  4985.6    0.08       0  5086.1    0.12       0  5140.9    0.08       0
  5316.6    0.12       0  5416.6    0.08       0  5716.6    0.12       0
  5843.7    0.08       0  5996.8    0.12       0  6412.3    0.08       0
  6808.2    0.12       0  6857.4    0.08       0  7021.3    0.12       0
  7135.1    0.07       0  7175.1    0.12       0
Bank Sta=4599.8,7205.3
Exp/Cntr=0.3,0.1

Type RM Length L Ch R = 1,16020,38,38,38
BEGIN DESCRIPTION:
Mapping XS b1c2aeea
END DESCRIPTION:
XS GIS Cut Line= 6
      2891964.93      6981436.41      2891756.62      6981452.04
      2891183.70      6981035.37      2890251.41      6980936.41
      2889589.95      6980983.29      2889121.20      6980686.41
#Sta/Elev= 30
  4422.0  353.85  4502.2  353.21  4542.3  345.28  4642.0  341.17  4756.8  339.87
  4920.5  340.86  4954.4  337.71  5006.2  333.68  5025.9  341.40  5070.6  341.62
  5136.7  341.28  5220.8  340.46  5259.9  340.36  5366.5  340.71  5466.1  340.67
  5753.9  340.37  6063.6  339.84  6361.3  340.10  6521.0  339.88  7011.8  341.42
  7073.5  343.00  7089.1  342.48  7116.3  328.25  7164.6  326.97  7173.1  324.97
  7204.6  326.97  7222.4  337.71  7243.1  343.13  7420.5  338.93  7502.7  338.63
#Mann=20,-1,0
  4422.0    0.05       0  4642.0    0.08       0  4756.8    0.08       0
  4920.5    0.05       0  5006.2    0.08       0  5070.6    0.05       0
  5136.7    0.08       0  5220.8    0.05       0  5259.9    0.08       0
  5366.5    0.05       0  5466.1    0.08       0  5753.9    0.05       0
  6063.6    0.08       0  6361.3    0.05       0  6521.0    0.08       0
  7011.8    0.05       0  7073.5     0.1       0  7164.6    0.04       0
  7204.6     0.1       0  7420.5    0.08       0
Bank Sta=4954.4,7222.4
Exp/Cntr=0.3,0.1

Type RM Length L Ch R = 1,15982,383,383,383
BEGIN DESCRIPTION:
Mapping XS 8e3ea7e7
END DESCRIPTION:
XS GIS Cut Line= 6
      2891985.76      6981358.29      2891751.41      6981405.16
      2891194.12      6980993.70      2890537.87      6980894.74
      2889636.83      6980952.04      2889169.01      6980655.75
#Sta/Elev= 30
  4430.8  350.95  4574.4  352.41  4691.7  347.78  4790.1  341.45  4794.9  337.72
  4909.8  334.91  4981.9  331.26  5041.7  334.65  5175.1  335.03  5294.8  335.14
  5403.6  335.93  5599.0  335.83  6097.4  336.06  6394.9  335.71  6594.5  335.52
  6794.2  337.14  6894.0  336.86  6963.5  333.92  7002.9  336.78  7109.3  335.03
  7139.7  331.94  7145.7  330.63  7146.9  326.96  7155.4  324.96  7186.9  326.96
  7233.9  333.96  7258.0  337.72  7349.5  338.23  7465.0  338.73  7490.1  338.75
#Mann=20,-1,0
  4430.8    0.05       0  4691.7    0.12       0  4790.1    0.08       0
  4909.8    0.05       0  5041.7    0.05       0  5175.1    0.05       0
  5294.8    0.08       0  5403.6    0.12       0  5599.0    0.05       0
  6097.4    0.08       0  6394.9    0.05       0  6594.5    0.12       0
  6794.2    0.07       0  6894.0    0.12       0  7002.9    0.05       0
  7146.9    0.04       0  7186.9    0.12       0  7233.9    0.08       0
  7349.5    0.05       0  7465.0    0.08       0
Bank Sta=4794.9,7258
Exp/Cntr=0.3,0.1