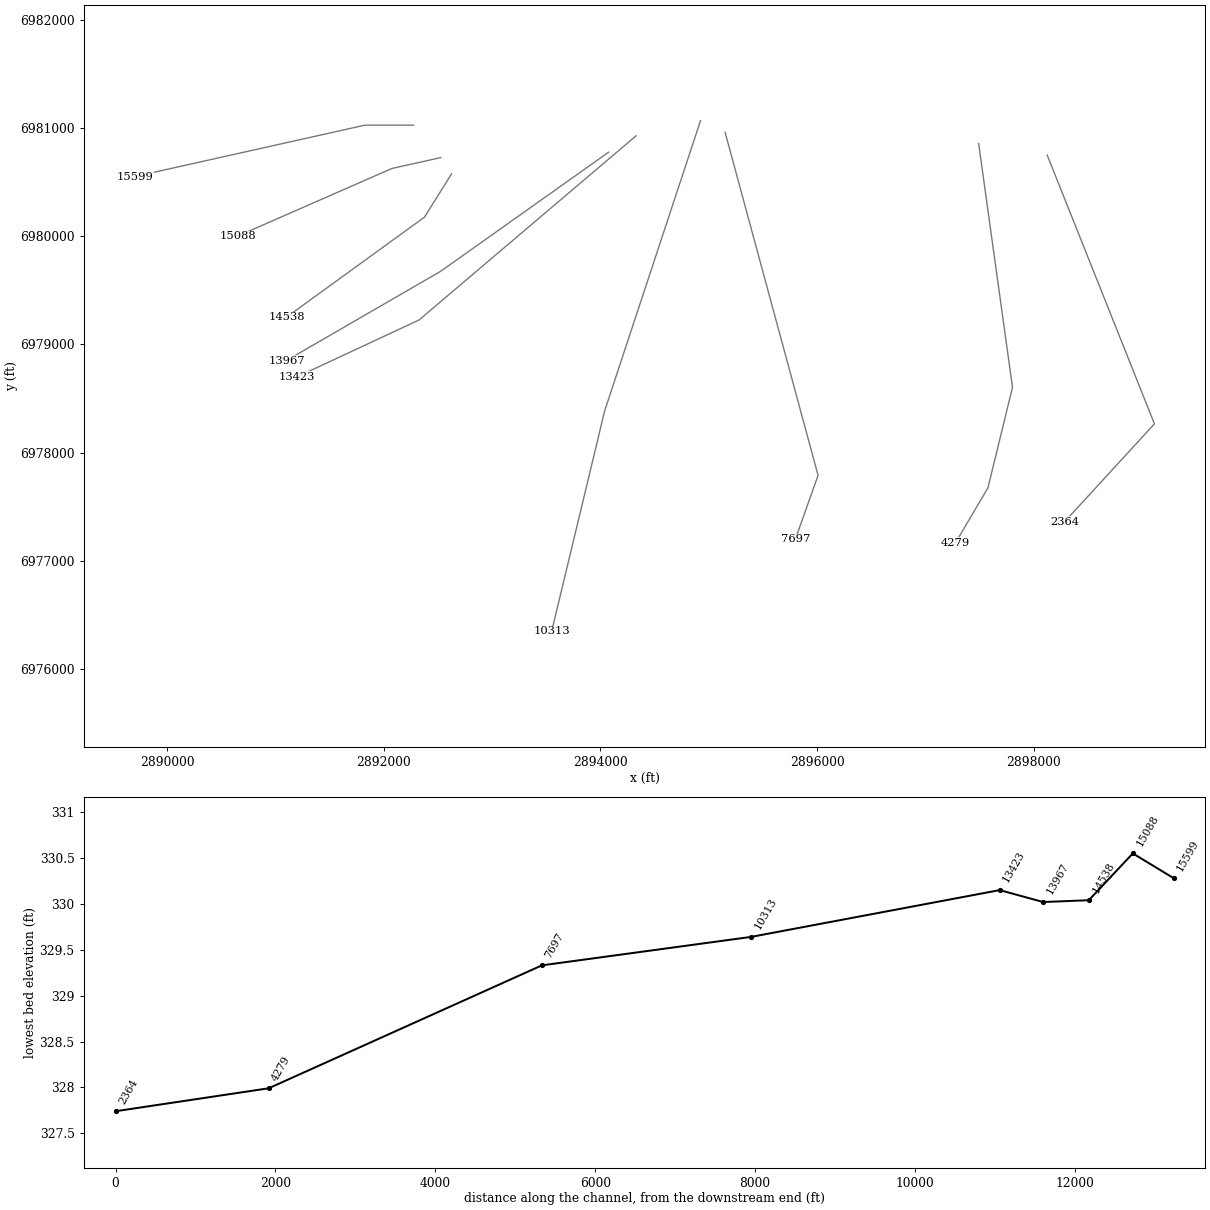
HEC-RAS study GEORGE SLOUGH.prj: GEORGE SLOUGH Base Level Engineering

--- GEORGE SLOUGH.g01 (geometry) --- (continued)

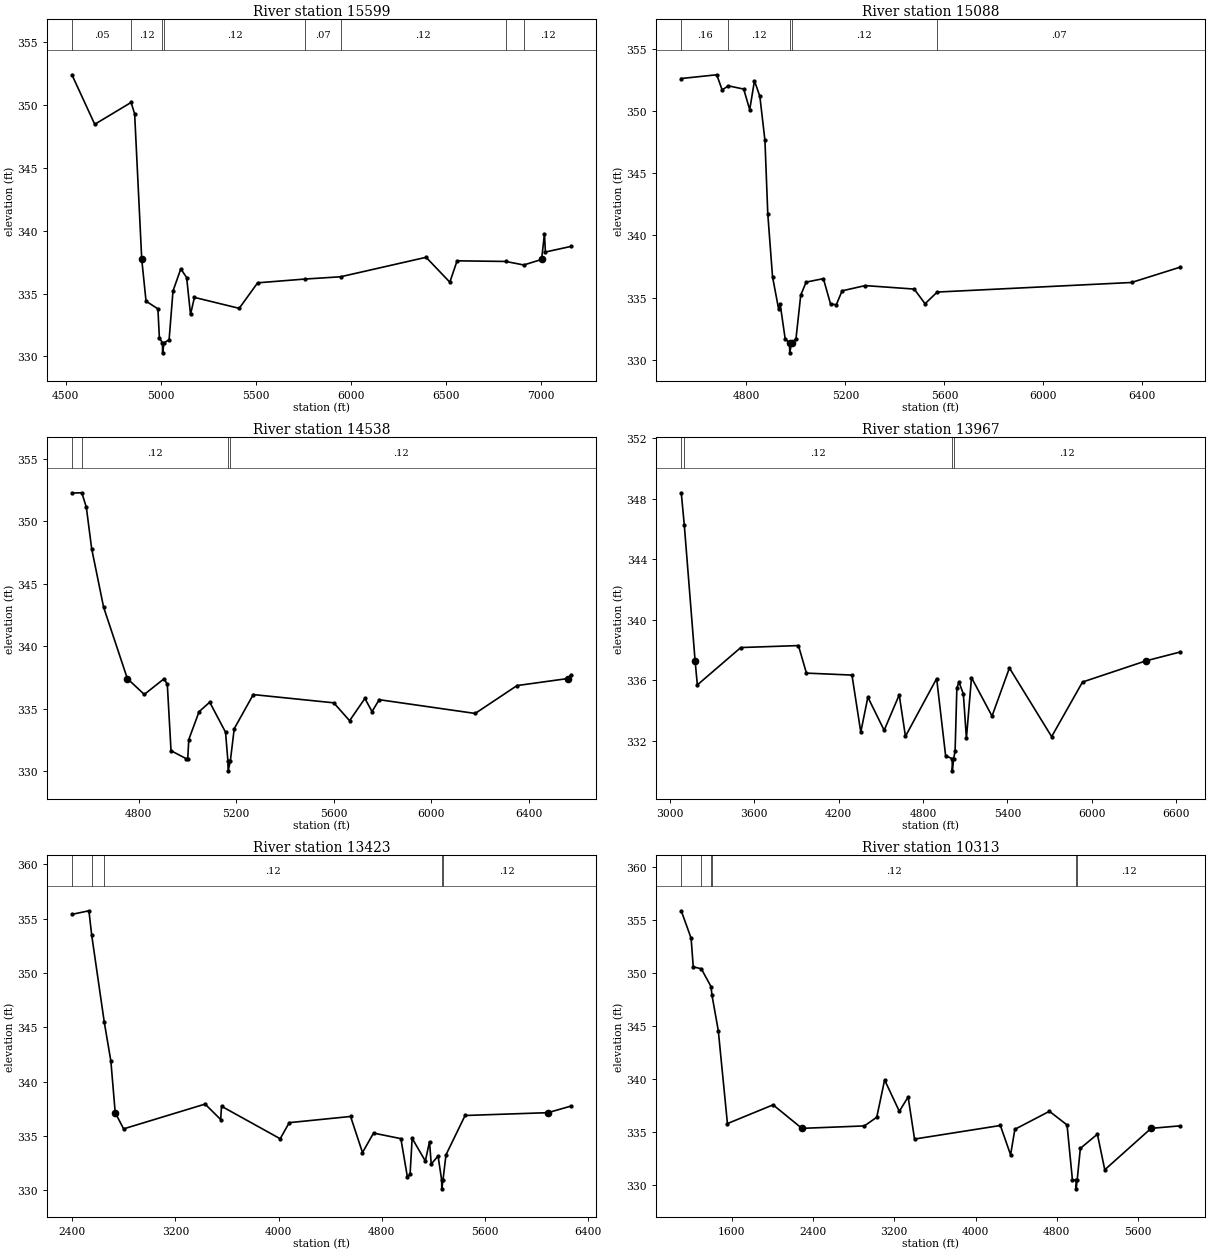
Type RM Length L Ch R = 1,15599,511,511,511
BEGIN DESCRIPTION:
GEORGE SLOUGH 7.0
END DESCRIPTION:
XS GIS Cut Line= 3
      2892274.95      6981025.00      2891825.00      6981025.00
      2889699.99      6980550.00
#Sta/Elev= 30
  4533.1  352.40  4653.1  348.46  4844.6  350.20  4863.1  349.29  4900.5  337.71
  4923.1  334.39  4985.6  333.78  4993.3  331.47  5009.5  331.08  5010.3  330.28
  5018.0  331.08  5044.5  331.32  5065.0  335.20  5106.0  336.96  5136.8  336.27
  5157.2  333.33  5177.7  334.69  5413.4  333.82  5510.5  335.85  5759.3  336.15
  5946.7  336.33  6397.1  337.88  6522.0  335.90  6560.2  337.60  6815.9  337.55
  6911.3  337.27  7005.1  337.71  7020.0  339.74  7025.1  338.30  7160.5  338.75
#Mann=8,-1,0
  4533.1    0.05       0  4844.6    0.12       0  5009.5    0.07       0
  5018.0    0.12       0  5759.3    0.07       0  5946.7    0.12       0
  6815.9    0.07       0  6911.3    0.12       0
Bank Sta=4900.5,7005.1
Exp/Cntr=0.3,0.1

Type RM Length L Ch R = 1,15088,550,550,550
BEGIN DESCRIPTION:
GEORGE SLOUGH 6.0
END DESCRIPTION:
XS GIS Cut Line= 3
      2892525.02      6980725.01      2892075.00      6980625.00
      2890650.04      6980000.02
#Sta/Elev= 30
  4536.7  352.62  4680.1  352.92  4701.9  351.70  4726.9  352.03  4789.0  351.77
  4813.3  350.11  4832.5  352.44  4854.3  351.18  4874.8  347.65  4886.3  341.74
  4905.5  336.67  4929.8  334.11  4936.2  334.49  4956.7  331.66  4974.2  331.35
  4975.0  330.55  4982.7  331.35  5000.4  331.70  5019.5  335.20  5041.4  336.24
  5111.0  336.52  5139.9  334.48  5163.2  334.42  5186.6  335.54  5280.1  335.96
  5477.9  335.68  5521.8  334.50  5570.8  335.44  6355.9  336.21  6553.7  337.45
#Mann=5,-1,0
  4536.7    0.16       0  4726.9    0.12       0  4974.2    0.07       0
  4982.7    0.12       0  5570.8    0.07       0
Bank Sta=4974.2,4982.7
Exp/Cntr=0.3,0.1

Type RM Length L Ch R = 1,14538,571,571,571
BEGIN DESCRIPTION:
GEORGE SLOUGH 5.0
END DESCRIPTION:
XS GIS Cut Line= 3
      2892625.02      6980575.03      2892375.00      6980175.00
      2891100.03      6979250.02
#Sta/Elev= 30
  4527.0  352.26  4567.6  352.28  4586.0  351.12  4607.8  347.82  4656.8  343.13
  4754.2  337.42  4823.6  336.15  4904.4  337.40  4918.0  336.97  4933.3  331.65
  4995.8  331.01  5001.8  331.01  5006.1  332.54  5048.2  334.77  5091.9  335.53
  5156.8  333.13  5166.5  330.84  5167.5  330.04  5176.6  330.84  5192.4  333.41
  5270.5  336.14  5600.6  335.48  5665.5  334.05  5728.2  335.83  5757.5  334.78
  5786.9  335.73  6180.4  334.63  6352.1  336.86  6559.5  337.42  6573.9  337.73
#Mann=4,-1,0
  4527.0    0.16       0  4567.6    0.12       0  5166.5    0.07       0
  5176.6    0.12       0
Bank Sta=4754.2,6559.5
Exp/Cntr=0.3,0.1

Type RM Length L Ch R = 1,13967,544,544,544
BEGIN DESCRIPTION:
GEORGE SLOUGH 4.0
END DESCRIPTION:
XS GIS Cut Line= 3
      2894074.99      6980774.99      2892525.00      6979675.00
      2891100.03      6978850.01
#Sta/Elev= 30
  3082.0  348.40  3103.5  346.28  3180.4  337.29  3196.4  335.70  3505.2  338.17
  3914.8  338.30  3971.4  336.48  4295.0  336.35  4357.7  332.58  4408.1  334.89
  4523.8  332.70  4630.8  335.04  4675.1  332.30  4896.8  336.12  4960.5  331.02
  5007.0  330.82  5008.0  330.02  5017.1  330.82  5027.8  331.31  5040.4  335.49
  5055.1  335.89  5086.6  335.10  5108.2  332.17  5144.4  336.18  5290.4  333.64
  5413.9  336.82  5713.8  332.28  5933.3  335.89  6383.7  337.29  6629.2  337.88
#Mann=4,-1,0
  3082.0    0.16       0  3103.5    0.12       0  5007.0    0.07       0
  5017.1    0.12       0
Bank Sta=3180.4,6383.7
Exp/Cntr=0.3,0.1

Type RM Length L Ch R = 1,13423,3110,3110,3110
BEGIN DESCRIPTION:
GEORGE SLOUGH 3.0
END DESCRIPTION:
XS GIS Cut Line= 3
      2894328.85      6980926.49      2892325.00      6979225.00
      2891199.96      6978699.98
#Sta/Elev= 30
  2398.3  355.41  2530.0  355.74  2551.0  353.54  2648.7  345.51  2700.2  341.90
  2733.8  337.16  2799.0  335.67  3430.6  337.95  3551.4  336.53  3558.0  337.75
  4012.8  334.76  4083.0  336.24  4558.6  336.81  4650.9  333.49  4736.6  335.28
  4948.5  334.77  4999.1  331.24  5019.9  331.49  5035.8  334.80  5138.2  332.71
  5170.5  334.49  5183.9  332.43  5236.8  333.17  5264.8  330.95  5265.7  330.15
  5275.0  330.95  5298.2  333.28  5446.4  336.90  6089.1  337.16  6268.6  337.77
#Mann=5,-1,0
  2398.3    0.05       0  2551.0    0.16       0  2648.7    0.12       0
  5264.8    0.07       0  5275.0    0.12       0
Bank Sta=2733.8,6089.1
Exp/Cntr=0.3,0.1

Type RM Length L Ch R = 1,10313,2616,2616,2616
BEGIN DESCRIPTION:
Mapping XS 20eb94a9
END DESCRIPTION:
XS GIS Cut Line= 3
      2894924.14      6981067.23      2894038.72      6978384.93
      2893550.01      6976350.05
#Sta/Elev= 30
  1101.3  355.89  1198.4  353.30  1219.5  350.60  1299.3  350.41  1394.8  348.73
  1403.1  347.97  1466.2  344.57  1556.2  335.80  2005.9  337.57  2289.9  335.35
  2905.3  335.58  3027.1  336.40  3104.5  339.92  3249.3  336.96  3336.2  338.31
  3399.3  334.34  4244.7  335.62  4345.5  332.85  4387.5  335.26  4728.1  336.96
  4901.6  335.67  4954.3  330.51  4990.7  330.44  4991.6  329.64  5001.0  330.44
  5032.6  333.46  5200.6  334.80  5273.1  331.44  5729.4  335.35  6018.7  335.59
#Mann=6,-1,0
  1101.3    0.16       0  1299.3    0.12       0  1394.8    0.16       0
  1403.1    0.12       0  4990.7    0.07       0  5001.0    0.12       0
Bank Sta=2289.9,5729.4
Exp/Cntr=0.3,0.1

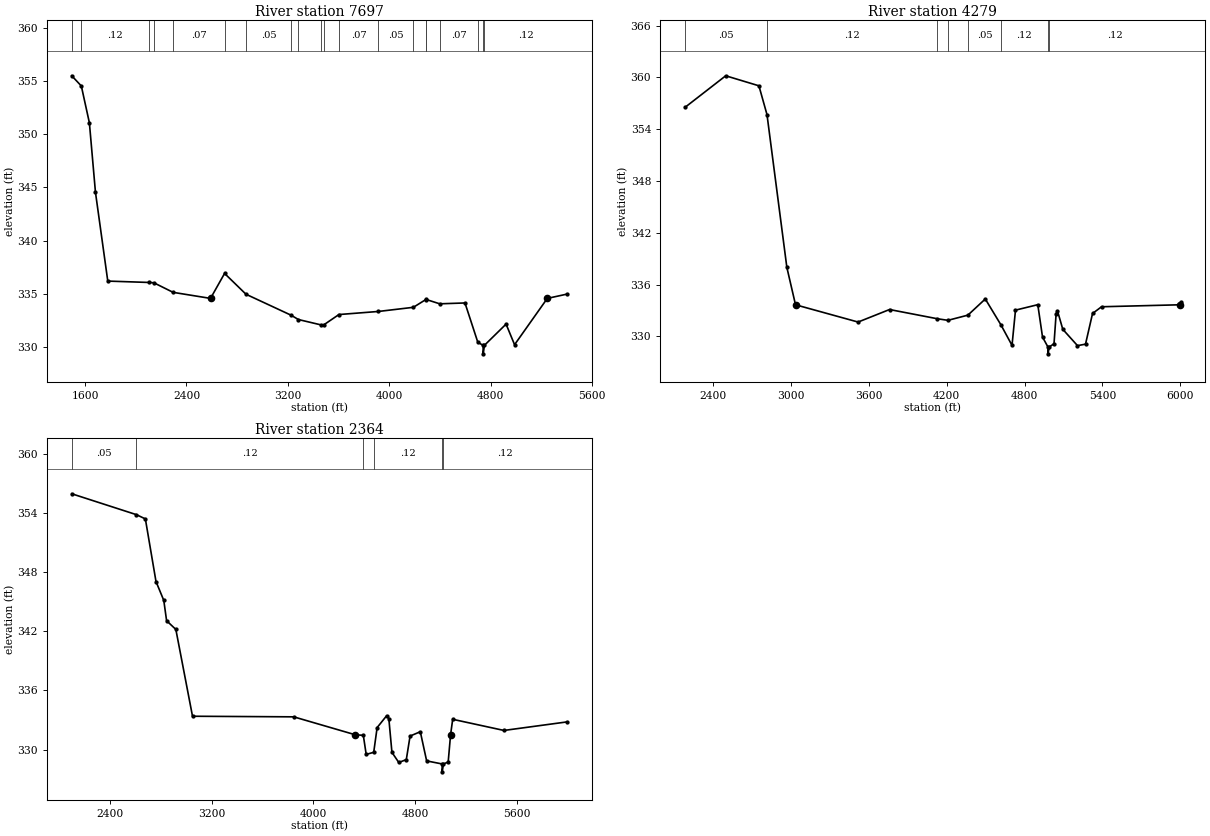
Type RM Length L Ch R = 1,7697,3418,3418,3418
BEGIN DESCRIPTION:
GEORGE SLOUGH 2.0
END DESCRIPTION:
XS GIS Cut Line= 3
      2895150.84      6980959.28      2896009.33      6977789.48
      2895800.02      6977200.04
#Sta/Elev= 30
  1495.2  355.51  1570.7  354.55  1634.3  351.08  1682.1  344.55  1779.4  336.18
  2105.7  336.05  2142.8  336.02  2294.7  335.12  2590.0  334.55  2700.8  336.90
  2869.9  334.94  3225.1  332.97  3283.3  332.56  3459.8  332.06  3484.8  332.07
  3603.0  333.03  3914.1  333.32  4190.0  333.71  4288.5  334.44  4290.8  334.45
  4398.1  334.04  4597.4  334.12  4698.7  330.42  4740.4  330.13  4741.3  329.33
  4750.7  330.13  4921.6  332.13  4988.6  330.19  5246.8  334.55  5404.7  334.96
#Mann=20,-1,0
  1495.2    0.05       0  1570.7    0.12       0  2105.7    0.05       0
  2142.8    0.12       0  2294.7    0.07       0  2700.8    0.12       0
  2869.9    0.05       0  3225.1    0.07       0  3283.3    0.05       0
  3459.8    0.12       0  3484.8    0.05       0  3603.0    0.07       0
  3914.1    0.05       0  4190.0    0.12       0  4288.5    0.07       0
  4290.8    0.12       0  4398.1    0.07       0  4698.7    0.12       0
  4740.4    0.07       0  4750.7    0.12       0
Bank Sta=2590,5246.8
Exp/Cntr=0.3,0.1

Type RM Length L Ch R = 1,4279,1915,1915,1915
BEGIN DESCRIPTION:
Mapping XS 16a3254a
END DESCRIPTION:
XS GIS Cut Line= 4
      2897492.08      6980855.17      2897804.58      6978602.60
      2897577.91      6977674.03      2897279.33      6977167.68
#Sta/Elev= 30
  2184.6  356.53  2497.7  360.18  2753.4  359.02  2815.7  355.68  2968.6  338.00
  3035.3  333.67  3517.4  331.67  3759.7  333.12  4128.9  332.05  4209.7  331.87
  4363.5  332.47  4497.4  334.34  4618.1  331.34  4703.3  328.97  4730.1  333.05
  4901.9  333.68  4938.4  329.93  4979.8  328.79  4980.6  327.99  4990.6  328.79
  5026.9  329.16  5043.0  332.60  5053.3  332.98  5094.5  330.83  5207.7  328.94
  5269.5  329.11  5323.7  332.66  5393.0  333.44  5999.2  333.67  6002.4  333.94
#Mann=8,-1,0
  2184.6    0.05       0  2815.7    0.12       0  4128.9    0.05       0
  4209.7    0.12       0  4363.5    0.05       0  4618.1    0.12       0
  4979.8    0.07       0  4990.6    0.12       0
Bank Sta=3035.3,5999.2
Exp/Cntr=0.3,0.1

Type RM Length L Ch R = 1,2364,0,0,0
BEGIN DESCRIPTION:
GEORGE SLOUGH 1.0
END DESCRIPTION:
XS GIS Cut Line= 3
      2898125.25      6980747.97      2899115.21      6978265.21
      2898285.16      6977360.03
#Sta/Elev= 30
  2098.0  355.95  2607.4  353.83  2677.5  353.40  2761.1  347.05  2822.5  345.13
  2844.6  343.07  2917.4  342.19  3048.6  333.38  3845.2  333.32  4327.4  331.51
  4393.2  331.44  4415.8  329.51  4475.0  329.72  4501.9  332.23  4577.3  333.44
  4594.1  333.14  4618.4  329.72  4672.3  328.69  4731.6  328.98  4761.2  331.37
  4841.8  331.81  4891.7  328.85  5013.3  328.54  5014.1  327.74  5024.2  328.54
  5061.3  328.74  5080.1  331.51  5096.8  333.07  5500.3  331.94  5999.0  332.81
#Mann=6,-1,0
  2098.0    0.05       0  2607.4    0.12       0  4393.2    0.07       0
  4475.0    0.12       0  5013.3    0.07       0  5024.2    0.12       0
Bank Sta=4327.4,5080.1
Exp/Cntr=0.3,0.1

Chan Stop Cuts=-1