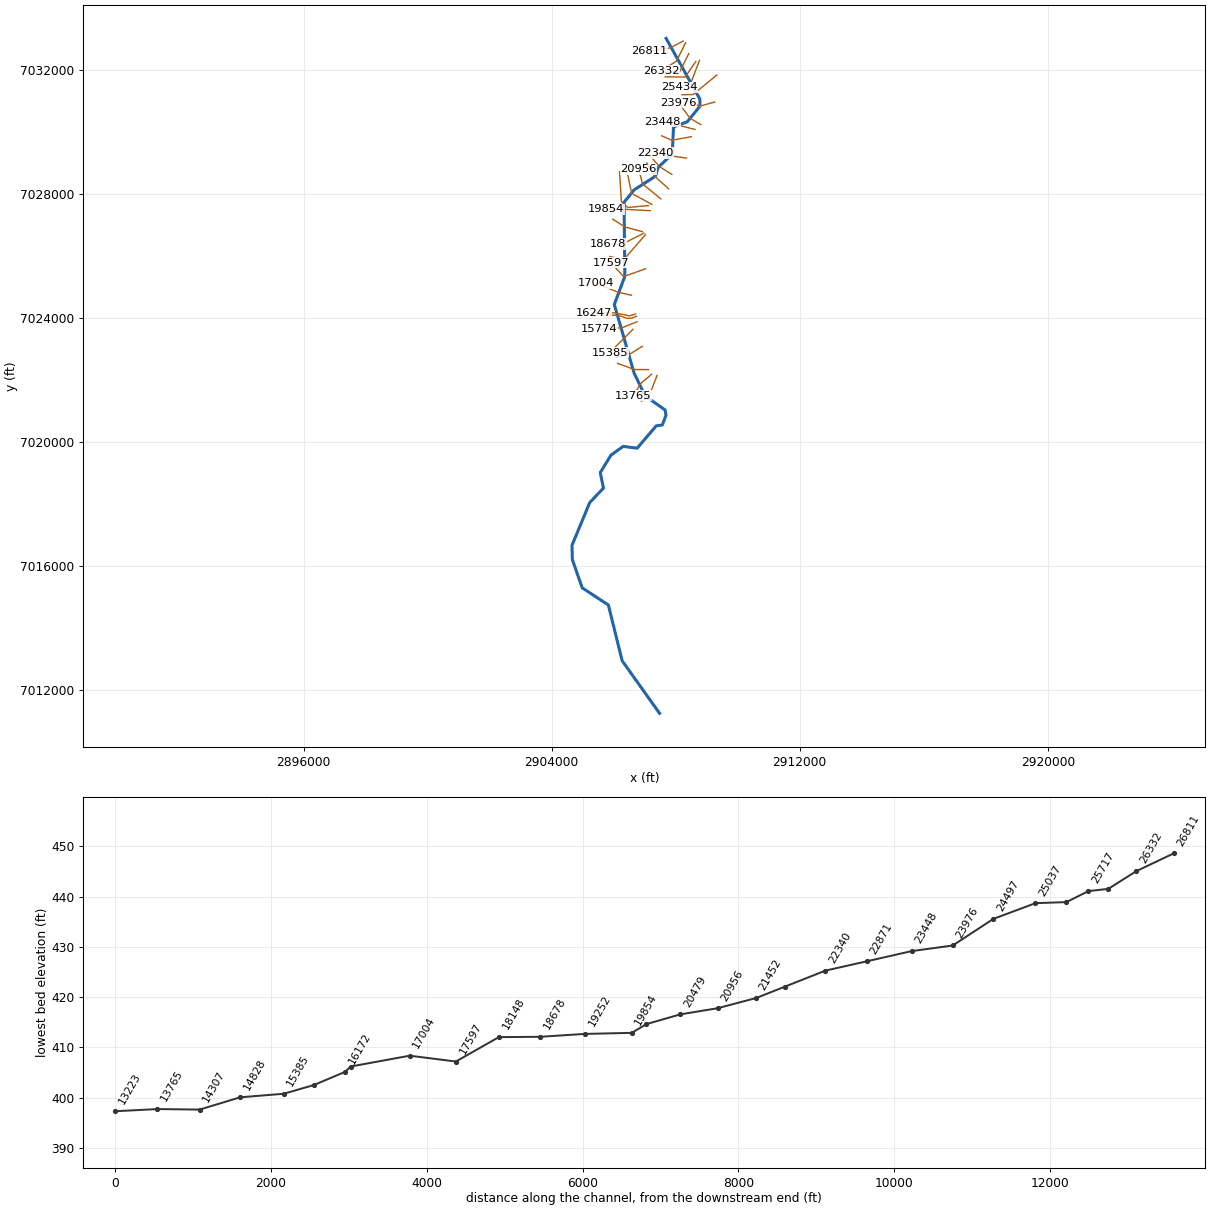
--- GLADE BRANCH.prj (project) ---

Proj Title=GLADE BRANCH Base Level Engineering
Current Plan=p01
Default Exp/Contr=0.3,0.1
English Units
Geom File=g01
Flow File=f01
Plan File=p01
BEGIN DESCRIPTION:
GLADE BRANCH
END DESCRIPTION:

--- GLADE BRANCH.p01 (plan) ---

Plan Title=Multiple Run
Short Identifier=Multiple
Geom File=g01
Flow File=f01
Subcritical Flow
K Sum by GR= 0
Std Step Tol= 0.01
Critical Tol= 0.01
Num of Std Step Trials= 20
Max Error Tol= 0.3
Flow Tol Ratio= 0.001
Split Flow NTrial= 30
Split Flow Tol= 0.02
Split Flow Ratio= 0.02
Log Output Level= 0
Friction Slope Method= 1
Unsteady Friction Slope Method= 2
Unsteady Bridges Friction Slope Method= 1
Parabolic Critical Depth
Global Vel Dist=  1 , 1 , 1
Global Log Level= 0
CheckData=True
Encroach Param= -1, 0, 0, 0
BEGIN DESCRIPTION:
Multiple Run
END DESCRIPTION:

--- GLADE BRANCH.f01 (steady flow) ---

Flow Title=Multiple
Number of Profiles=7
Profile Names=10-year,25-year,50-year,1pct_min,100-year,1pct_plu,500-year
River Rch & RM= GLADE BRANCH,Reach-1,26811
     519     695     838     503    1004    2003    1441
River Rch & RM= GLADE BRANCH,Reach-1,25037
     850    1168    1433     874    1744    3479    2585
River Rch & RM= GLADE BRANCH,Reach-1,19854
    1503    2122    2650    1641    3274    6532    5009
River Rch & RM= GLADE BRANCH,Reach-1,14307
    1573    2213    2757    1702    3396    6776    5165
River Rch & RM= GLADE BRANCH,Reach-1,7522
    2187    3113    3910    2430    4848    9673    7475
River Rch & RM= GLADE BRANCH,Reach-1,4053
    2197    3119    3909    2423    4835    9648    7420
Boundary for River Rch & Prof#=GLADE BRANCH,Reach-1,1
Up Type=0
Dn Type=3
Dn Slope=0.005
Boundary for River Rch & Prof#=GLADE BRANCH,Reach-1,2
Up Type=0
Dn Type=3
Dn Slope=0.005
Boundary for River Rch & Prof#=GLADE BRANCH,Reach-1,3
Up Type=0
Dn Type=3
Dn Slope=0.005
Boundary for River Rch & Prof#=GLADE BRANCH,Reach-1,4
Up Type=0
Dn Type=3
Dn Slope=0.005
Boundary for River Rch & Prof#=GLADE BRANCH,Reach-1,5
Up Type=0
Dn Type=3
Dn Slope=0.005
Boundary for River Rch & Prof#=GLADE BRANCH,Reach-1,6
Up Type=0
Dn Type=3
Dn Slope=0.005
Boundary for River Rch & Prof#=GLADE BRANCH,Reach-1,7
Up Type=0
Dn Type=3
Dn Slope=0.005

--- GLADE BRANCH.g01 (geometry) ---

Geom Title=Existing Conditions

River Reach=GLADE BRANCH,Reach-1
Reach XY= 30
      2907691.37      7033014.21      2908779.35      7031053.12
      2908784.08      7030826.45      2908375.92      7030321.93
      2907930.42      7030153.54      2907890.90      7029280.36
      2907433.56      7028846.98      2907348.24      7028564.11
      2906659.33      7028123.05      2906336.80      7027725.18
      2906360.28      7025331.09      2906021.74      7024424.84
      2906660.93      7022208.21      2907015.67      7021473.89
      2907658.90      7021020.76      2907687.54      7020851.49
      2907570.35      7020536.39      2907375.04      7020510.35
      2906757.85      7019787.69      2906307.33      7019844.98
      2905914.10      7019563.73      2905568.05      7018999.36
      2905672.22      7018498.06      2905229.95      7018035.82
      2904657.03      7016653.88      2904667.45      7016193.81
      2904986.89      7015280.62      2905830.64      7014726.80
      2906275.08      7012926.45      2907482.15      7011229.77

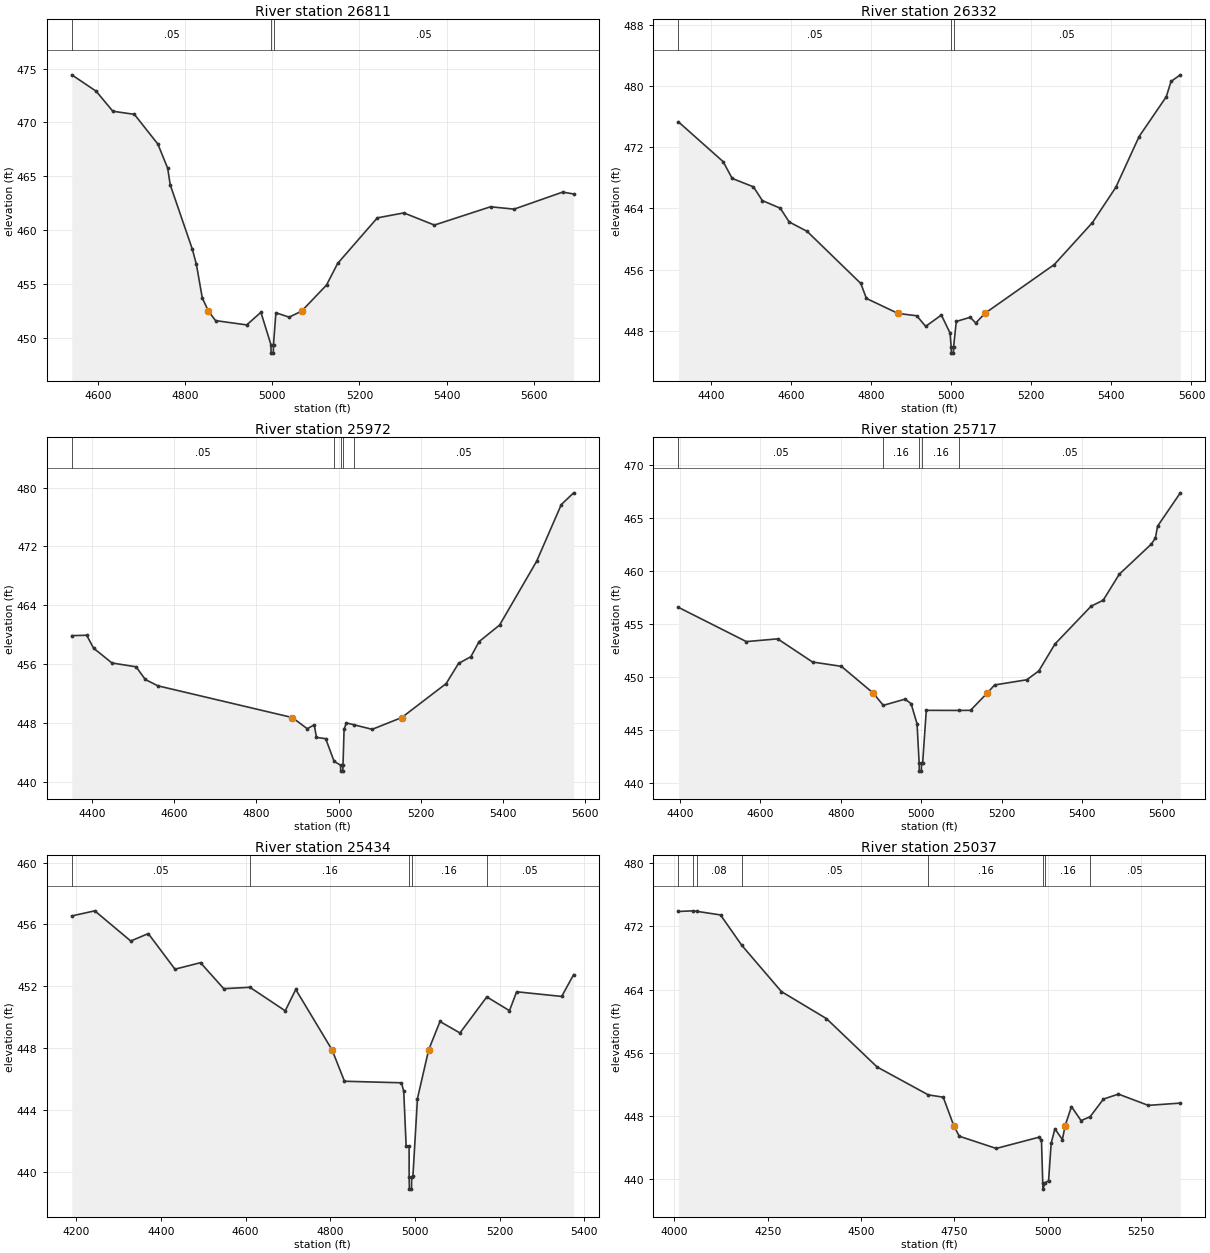
Type RM Length L Ch R = 1,26811,479,479,479
BEGIN DESCRIPTION:
GLADE BRANCH 46.0
END DESCRIPTION:
XS GIS Cut Line= 3
      2908239.42      7032926.35      2907833.08      7032709.67
      2907150.03      7032600.00
#Sta/Elev= 30
  4539.5  474.42  4595.5  472.90  4633.8  471.04  4683.3  470.75  4737.2  467.99
  4759.8  465.74  4765.5  464.22  4816.5  458.21  4825.7  456.81  4839.2  453.70
  4853.3  452.48  4869.6  451.60  4941.2  451.20  4973.8  452.37  4996.7  449.38
  4997.2  448.58  5002.2  448.58  5002.7  449.38  5008.2  452.33  5038.6  451.92
  5067.3  452.48  5124.4  454.90  5150.0  456.91  5241.1  461.14  5301.9  461.60
  5372.1  460.47  5501.0  462.17  5555.1  461.95  5666.5  463.53  5691.8  463.36
#Mann=3,-1,0
  4539.5    0.05       0  4996.7    0.03       0  5002.7    0.05       0
Bank Sta=4853.3,5067.3
Exp/Cntr=0.3,0.1

Type RM Length L Ch R = 1,26332,360,360,360
BEGIN DESCRIPTION:
GLADE BRANCH 45.0
END DESCRIPTION:
XS GIS Cut Line= 3
      2908325.01      7032875.01      2908025.00      7032275.00
      2907525.03      7031975.02
#Sta/Elev= 30
  4318.3  475.33  4430.1  470.12  4452.5  467.93  4505.6  466.83  4527.9  465.03
  4572.7  464.03  4595.0  462.23  4639.8  461.00  4773.9  454.18  4787.9  452.22
  4866.8  450.26  4913.7  449.95  4936.0  448.56  4975.2  450.05  4996.9  447.69
  4999.7  445.86  5000.2  445.06  5005.2  445.06  5005.7  445.86  5012.5  449.21
  5047.4  449.75  5061.1  449.00  5083.8  450.26  5257.4  456.66  5352.6  462.15
  5410.9  466.75  5469.2  473.41  5537.2  478.63  5548.9  480.62  5572.2  481.49
#Mann=3,-1,0
  4318.3    0.05       0  4999.7    0.03       0  5005.7    0.05       0
Bank Sta=4866.8,5083.8
Exp/Cntr=0.3,0.1

Type RM Length L Ch R = 1,25972,255,255,255
BEGIN DESCRIPTION:
GLADE BRANCH 44.0
END DESCRIPTION:
XS GIS Cut Line= 3
      2908424.99      7032524.98      2908125.00      7031925.00
      2907575.00      7031925.00
#Sta/Elev= 30
  4350.7  459.91  4387.0  459.96  4403.8  458.21  4448.5  456.20  4507.2  455.68
  4529.6  453.96  4560.3  453.10  4887.0  448.80  4923.7  447.28  4940.4  447.81
  4946.0  446.11  4968.4  445.93  4988.7  442.88  5004.5  442.33  5005.0  441.53
  5010.0  441.53  5010.5  442.33  5013.1  447.21  5018.7  448.07  5036.2  447.83
  5081.5  447.20  5153.4  448.80  5261.5  453.41  5291.5  456.14  5321.5  457.05
  5341.5  459.10  5391.5  461.35  5481.5  470.00  5541.5  477.69  5571.5  479.28
#Mann=5,-1,0
  4350.7    0.05       0  4988.7    0.16       0  5004.5    0.07       0
  5010.5    0.16       0  5036.2    0.05       0
Bank Sta=4887,5153.4
Exp/Cntr=0.3,0.1

Type RM Length L Ch R = 1,25717,283,283,283
BEGIN DESCRIPTION:
GLADE BRANCH 43.0
END DESCRIPTION:
XS GIS Cut Line= 3
      2908648.29      7032265.11      2908307.87      7031766.67
      2907663.08      7031770.32
#Sta/Elev= 30
  4396.4  456.58  4565.3  453.34  4643.2  453.60  4729.9  451.41  4801.7  451.00
  4881.2  448.46  4905.9  447.31  4960.2  447.90  4975.1  447.47  4989.9  445.57
  4995.1  441.89  4995.6  441.09  5000.6  441.09  5001.1  441.89  5003.9  441.89
  5012.9  446.84  5094.8  446.83  5122.9  446.84  5164.1  448.46  5182.9  449.24
  5262.9  449.73  5292.9  450.57  5332.9  453.11  5422.9  456.69  5452.9  457.25
  5492.9  459.71  5572.9  462.57  5582.9  463.15  5588.1  464.25  5644.8  467.41
#Mann=5,-1,0
  4396.4    0.05       0  4905.9    0.16       0  4995.1    0.07       0
  5001.1    0.16       0  5094.8    0.05       0
Bank Sta=4881.2,5164.1
Exp/Cntr=0.3,0.1

Type RM Length L Ch R = 1,25434,397,397,397
BEGIN DESCRIPTION:
Mapping XS f907f314
END DESCRIPTION:
XS GIS Cut Line= 3
      2908768.08      7032303.94      2908485.96      7031561.77
      2908118.52      7031427.76
#Sta/Elev= 30
  4189.4  456.55  4243.7  456.88  4328.7  454.93  4370.1  455.41  4433.1  453.11
  4493.4  453.53  4548.3  451.85  4610.1  451.94  4693.5  450.42  4718.3  451.80
  4804.0  447.90  4833.4  445.87  4968.0  445.77  4973.3  445.22  4979.0  441.69
  4986.0  441.69  4986.1  439.70  4986.6  438.90  4991.6  438.90  4992.1  439.70
  4995.1  439.78  5005.7  444.75  5032.2  447.90  5058.9  449.73  5106.1  448.99
  5169.5  451.32  5223.0  450.43  5239.9  451.65  5346.3  451.35  5374.5  452.76
#Mann=5,-1,0
  4189.4    0.05       0  4610.1    0.16       0  4986.1    0.07       0
  4992.1    0.16       0  5169.5    0.05       0
Bank Sta=4804,5032.2
Exp/Cntr=0.3,0.1

Type RM Length L Ch R = 1,25037,540,540,540
BEGIN DESCRIPTION:
Mapping XS 2fbc6fc0
END DESCRIPTION:
XS GIS Cut Line= 3
      2909327.95      7031830.84      2908564.09      7031201.53
      2908209.10      7031192.87
#Sta/Elev= 30
  4010.7  473.90  4050.6  473.98  4059.2  473.92  4123.4  473.46  4180.2  469.62
  4286.6  463.74  4407.4  460.31  4543.0  454.18  4680.3  450.64  4720.2  450.35
  4748.4  446.75  4763.2  445.40  4862.2  443.85  4975.6  445.26  4983.4  444.96
  4986.9  439.49  4987.4  438.69  4993.0  439.49  5002.5  439.76  5009.5  444.54
  5019.5  446.33  5039.5  444.98  5046.9  446.75  5063.8  449.16  5089.5  447.38
  5113.8  447.87  5149.5  450.11  5189.6  450.74  5269.6  449.31  5355.5  449.60
#Mann=8,-1,0
  4010.7    0.08       0  4050.6    0.05       0  4059.2    0.08       0
  4180.2    0.05       0  4680.3    0.16       0  4986.9    0.07       0
  4993.0    0.16       0  5113.8    0.05       0
Bank Sta=4748.4,5046.9
Exp/Cntr=0.3,0.1

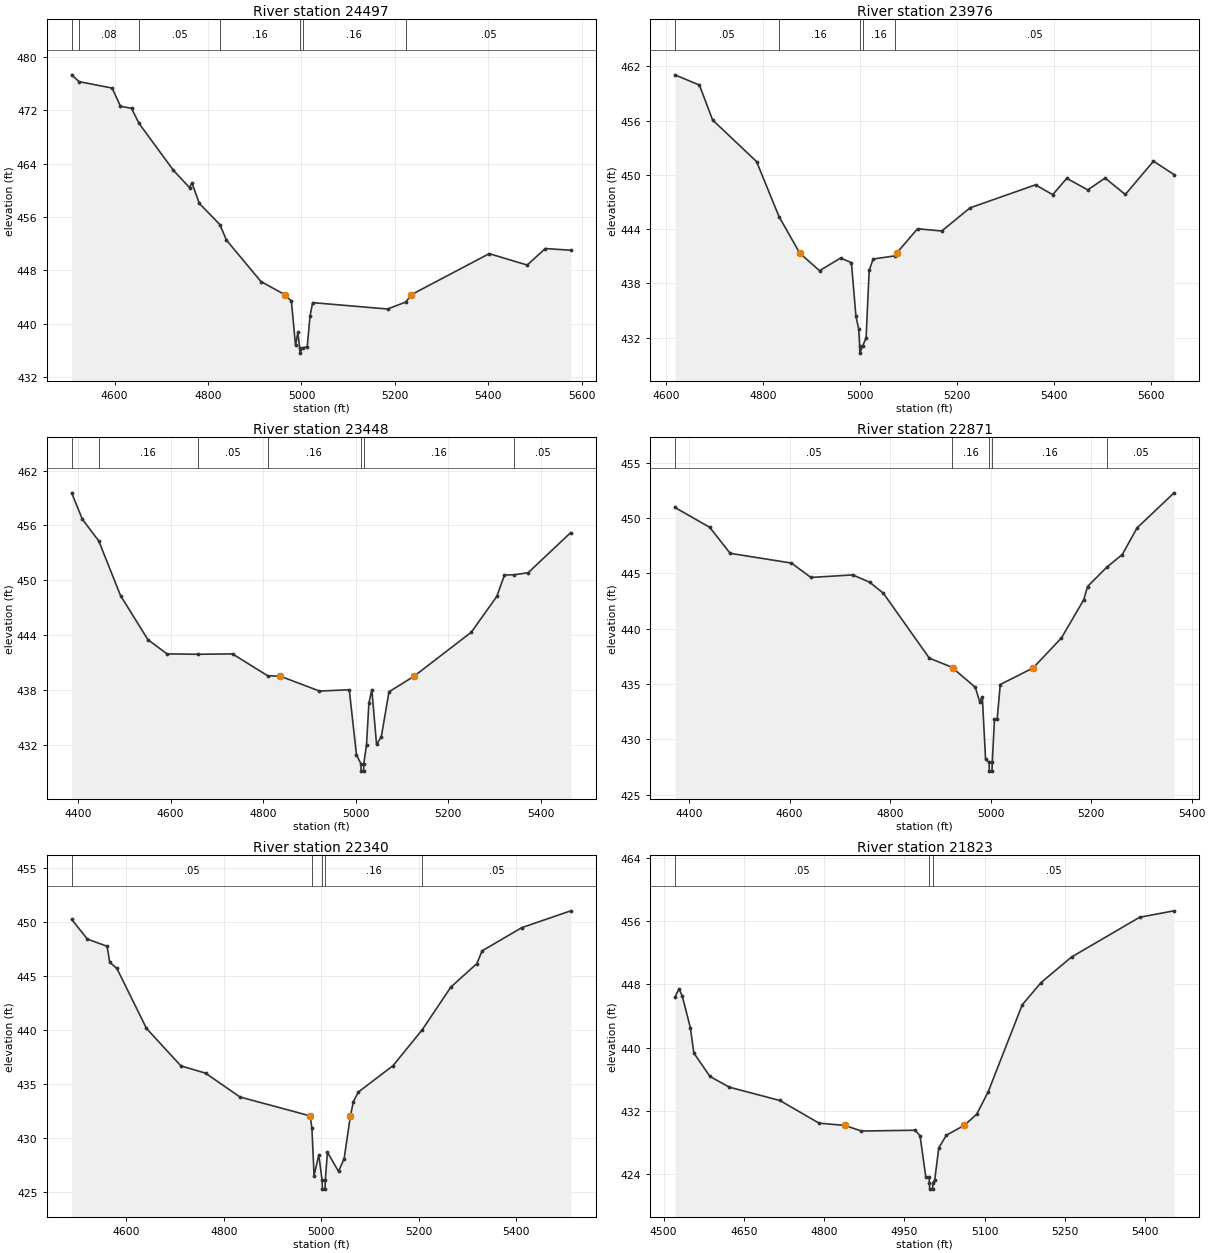
Type RM Length L Ch R = 1,24497,521,521,521
BEGIN DESCRIPTION:
GLADE BRANCH 42.0
END DESCRIPTION:
XS GIS Cut Line= 3
      2909258.54      7030958.47      2908775.00      7030825.00
      2908260.24      7031062.65
#Sta/Elev= 30
  4507.9  477.34  4523.8  476.32  4594.6  475.35  4612.5  472.62  4636.1  472.31
  4652.1  470.06  4725.9  463.00  4760.3  460.41  4765.5  461.11  4781.3  458.04
  4825.3  454.86  4839.4  452.53  4913.3  446.31  4965.1  444.32  4978.4  443.37
  4987.2  436.74  4992.3  438.68  4996.1  436.37  4996.6  435.57  5002.2  436.37
  5012.3  436.53  5018.2  441.08  5023.8  443.15  5184.4  442.19  5224.0  443.26
  5234.6  444.32  5401.9  450.50  5483.1  448.79  5522.1  451.27  5576.5  451.01
#Mann=7,-1,0
  4507.9    0.05       0  4523.8    0.08       0  4652.1    0.05       0
  4825.3    0.16       0  4996.1    0.07       0  5002.2    0.16       0
  5224.0    0.05       0
Bank Sta=4965.1,5234.6
Exp/Cntr=0.3,0.1

Type RM Length L Ch R = 1,23976,528,528,528
BEGIN DESCRIPTION:
GLADE BRANCH 41.0
END DESCRIPTION:
XS GIS Cut Line= 3
      2908811.50      7030233.64      2908475.00      7030425.00
      2908086.68      7030936.74
#Sta/Elev= 30
  4618.3  461.07  4668.8  459.94  4696.2  456.07  4786.8  451.47  4833.1  445.38
  4876.0  441.33  4916.7  439.40  4960.0  440.80  4982.4  440.29  4991.7  434.37
  4997.5  432.94  4999.4  431.08  4999.9  430.28  5005.6  431.08  5012.7  431.97
  5019.0  439.43  5027.2  440.69  5071.9  441.04  5075.5  441.33  5118.8  444.04
  5168.7  443.79  5226.9  446.35  5362.1  448.90  5397.5  447.81  5426.6  449.62
  5469.9  448.34  5505.6  449.65  5547.3  447.83  5605.4  451.52  5647.8  450.03
#Mann=5,-1,0
  4618.3    0.05       0  4833.1    0.16       0  4999.4    0.07       0
  5005.6    0.16       0  5071.9    0.05       0
Bank Sta=4876,5075.5
Exp/Cntr=0.3,0.1

Type RM Length L Ch R = 1,23448,577,577,577
BEGIN DESCRIPTION:
GLADE BRANCH 40.0
END DESCRIPTION:
XS GIS Cut Line= 3
      2908625.00      7030075.00      2908025.00      7030225.00
      2907575.04      7030324.99
#Sta/Elev= 30
  4385.9  459.57  4409.1  456.69  4444.6  454.31  4491.6  448.35  4550.8  443.53
  4592.1  441.97  4658.4  441.93  4733.8  441.97  4809.9  439.58  4837.2  439.53
  4921.9  437.91  4986.3  438.05  5001.8  430.96  5011.5  429.96  5012.0  429.16
  5017.2  429.16  5017.7  429.96  5023.6  432.06  5028.7  436.57  5035.1  438.07
  5045.3  432.07  5055.6  432.93  5072.2  437.83  5126.3  439.53  5250.2  444.34
  5305.3  448.25  5321.9  450.59  5343.1  450.62  5373.1  450.84  5465.3  455.23
#Mann=7,-1,0
  4385.9    0.05       0  4444.6    0.16       0  4658.4    0.05       0
  4809.9    0.16       0  5011.5    0.07       0  5017.7    0.16       0
  5343.1    0.05       0
Bank Sta=4837.2,5126.3
Exp/Cntr=0.3,0.1

Type RM Length L Ch R = 1,22871,531,531,531
BEGIN DESCRIPTION:
GLADE BRANCH 39.0
END DESCRIPTION:
XS GIS Cut Line= 3
      2908503.27      7029838.67      2907875.00      7029725.00
      2907550.85      7029869.07
#Sta/Elev= 30
  4371.8  450.97  4441.2  449.17  4481.8  446.82  4603.8  445.94  4642.3  444.64
  4725.7  444.87  4759.4  444.21  4786.7  443.21  4878.2  437.34  4922.7  436.53
  4924.4  436.46  4969.6  434.71  4978.4  433.39  4983.5  433.85  4990.0  428.20
  4997.0  427.93  4997.5  427.13  5002.8  427.13  5003.3  427.93  5007.7  431.81
  5013.0  431.81  5019.2  434.96  5084.6  436.46  5140.9  439.17  5185.4  442.63
  5192.9  443.82  5231.2  445.57  5262.0  446.71  5291.4  449.12  5365.0  452.29
#Mann=5,-1,0
  4371.8    0.05       0  4922.7    0.16       0  4997.0    0.07       0
  5003.3    0.16       0  5231.2    0.05       0
Bank Sta=4924.4,5084.6
Exp/Cntr=0.3,0.1

Type RM Length L Ch R = 1,22340,517,517,517
BEGIN DESCRIPTION:
GLADE BRANCH 38.0
END DESCRIPTION:
XS GIS Cut Line= 3
      2908347.03      7029148.58      2907825.00      7029225.00
      2907335.84      7029313.50
#Sta/Elev= 30
  4487.8  450.26  4520.2  448.43  4560.6  447.77  4566.1  446.28  4580.8  445.71
  4641.5  440.16  4712.2  436.69  4762.7  436.02  4833.5  433.81  4977.6  432.06
  4981.1  430.91  4985.5  426.54  4995.2  428.45  5002.1  426.08  5002.6  425.28
  5008.0  425.28  5008.5  426.08  5012.9  428.70  5035.7  426.92  5047.2  428.10
  5060.1  432.06  5066.2  433.39  5076.4  434.27  5147.5  436.71  5207.6  440.04
  5266.3  443.99  5319.8  446.17  5330.4  447.34  5411.7  449.49  5512.5  451.05
#Mann=5,-1,0
  4487.8    0.05       0  4981.1    0.16       0  5002.1    0.07       0
  5008.5    0.16       0  5207.6    0.05       0
Bank Sta=4977.6,5060.1
Exp/Cntr=0.3,0.1

Type RM Length L Ch R = 1,21823,371,371,371
BEGIN DESCRIPTION:
GLADE BRANCH 37.0
END DESCRIPTION:
XS GIS Cut Line= 3
      2907875.00      7028625.00      2907475.00      7028875.00
      2907174.99      7029225.02
#Sta/Elev= 30
  4521.2  446.38  4528.9  447.45  4534.8  446.57  4550.1  442.53  4556.6  439.33
  4586.7  436.36  4623.2  435.00  4717.5  433.32  4790.7  430.45  4838.6  430.17
  4869.7  429.46  4969.9  429.56  4979.3  428.86  4990.0  423.67  4996.2  423.67
  4996.8  422.91  4997.3  422.11  5002.7  422.11  5003.2  422.91  5006.6  423.22
  5014.3  427.33  5028.6  428.94  5061.8  430.17  5085.1  431.58  5106.5  434.40
  5170.2  445.42  5205.3  448.23  5262.4  451.47  5389.7  456.50  5453.9  457.31
#Mann=3,-1,0
  4521.2    0.05       0  4996.8   0.035       0  5003.2    0.05       0
Bank Sta=4838.6,5061.8
Exp/Cntr=0.3,0.1

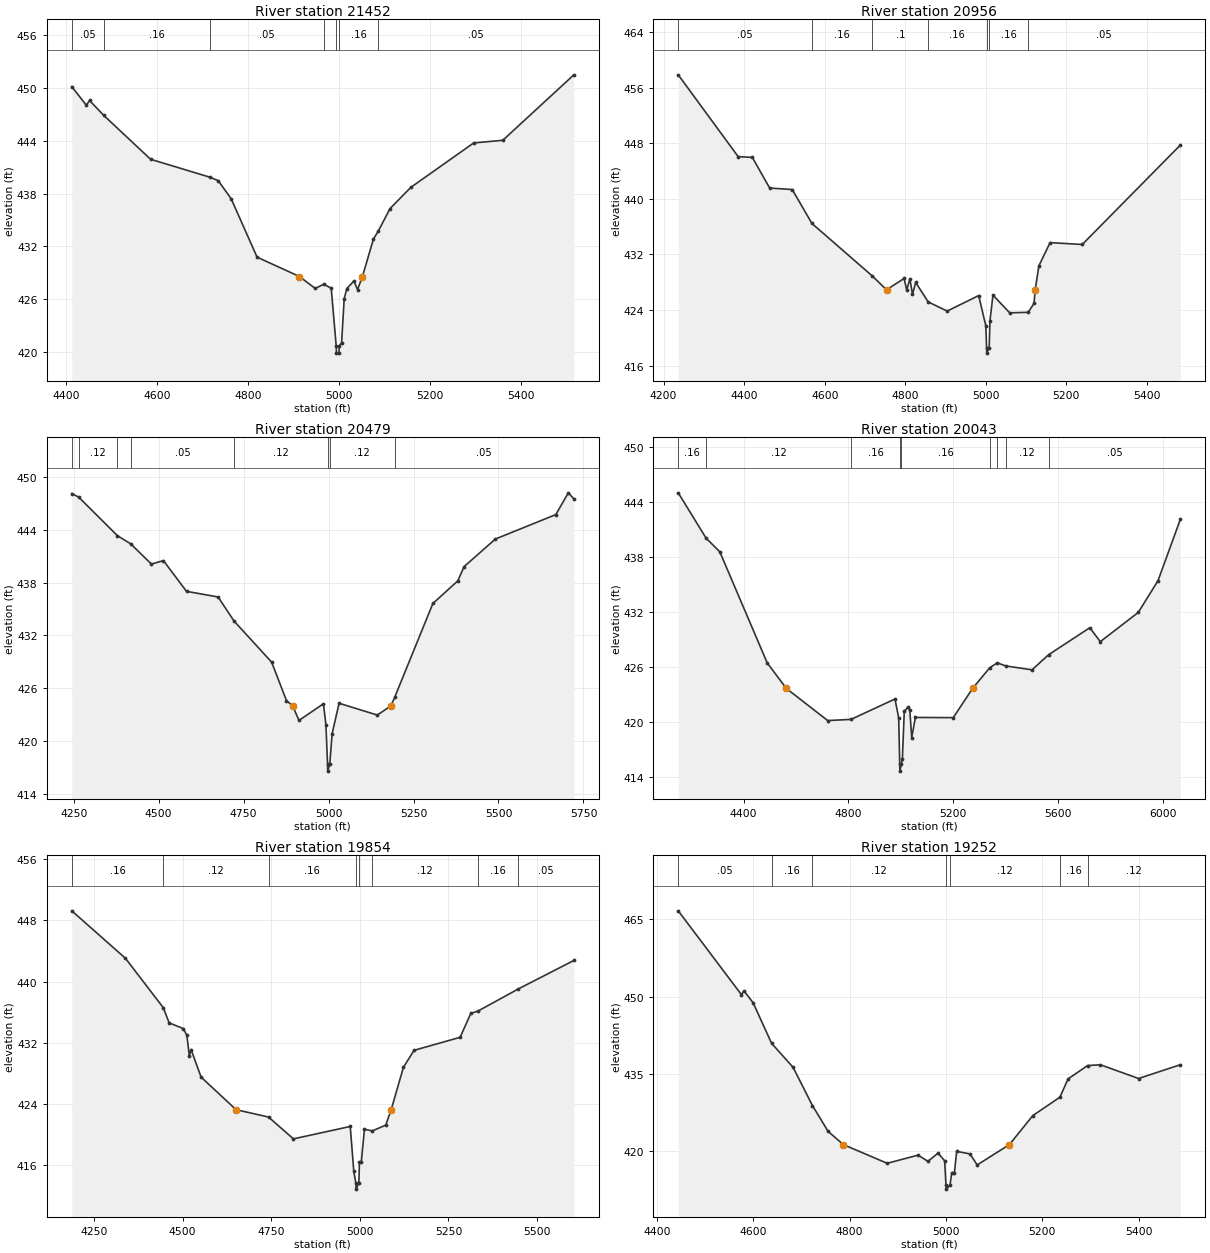
Type RM Length L Ch R = 1,21452,496,496,496
BEGIN DESCRIPTION:
GLADE BRANCH 36.0
END DESCRIPTION:
XS GIS Cut Line= 3
      2907774.19      7028158.96      2907335.97      7028550.27
      2907067.38      7028991.20
#Sta/Elev= 30
  4412.5  450.17  4444.5  448.05  4451.6  448.59  4482.9  446.89  4585.8  441.90
  4716.2  439.86  4734.6  439.46  4763.0  437.40  4819.9  430.76  4913.0  428.56
  4947.7  427.20  4966.4  427.68  4982.9  427.23  4993.9  420.64  4994.4  419.84
  4999.9  419.84  5000.4  420.64  5005.7  421.01  5011.4  426.03  5017.3  427.19
  5032.8  428.05  5040.7  427.07  5051.5  428.56  5075.8  432.83  5086.5  433.74
  5112.2  436.29  5157.8  438.70  5296.1  443.76  5360.1  444.06  5516.3  451.51
#Mann=7,-1,0
  4412.5    0.05       0  4482.9    0.16       0  4716.2    0.05       0
  4966.4    0.16       0  4993.9    0.07       0  5000.4    0.16       0
  5086.5    0.05       0
Bank Sta=4913,5051.5
Exp/Cntr=0.3,0.1

Type RM Length L Ch R = 1,20956,477,477,477
BEGIN DESCRIPTION:
GLADE BRANCH 35.0
END DESCRIPTION:
XS GIS Cut Line= 3
      2907522.43      7027833.46      2906932.06      7028317.77
      2906806.27      7028784.00
#Sta/Elev= 30
  4236.4  457.84  4385.2  446.07  4420.4  445.96  4463.4  441.55  4519.4  441.34
  4568.4  436.45  4718.6  428.88  4753.5  426.91  4797.1  428.54  4803.6  426.88
  4811.5  428.51  4818.0  426.24  4825.8  427.98  4856.9  425.17  4904.1  423.85
  4982.3  426.08  5000.0  421.74  5001.9  418.60  5002.4  417.80  5008.4  418.60
  5010.3  422.47  5017.8  426.14  5059.3  423.60  5105.3  423.67  5119.7  424.96
  5122.6  426.91  5131.8  430.36  5159.6  433.70  5239.4  433.43  5482.9  447.73
#Mann=7,-1,0
  4236.4    0.05       0  4568.4    0.16       0  4718.6     0.1       0
  4856.9    0.16       0  5001.9    0.07       0  5008.4    0.16       0
  5105.3    0.05       0
Bank Sta=4753.5,5122.6
Exp/Cntr=0.3,0.1

Type RM Length L Ch R = 1,20479,436,436,436
BEGIN DESCRIPTION:
Mapping XS 8ec22a7f
END DESCRIPTION:
XS GIS Cut Line= 3
      2907231.64      7027655.51      2906580.58      7028011.42
      2906428.88      7028730.92
#Sta/Elev= 30
  4244.4  448.11  4264.5  447.72  4378.8  443.33  4417.7  442.41  4478.6  440.11
  4514.1  440.50  4582.0  437.01  4675.0  436.37  4721.8  433.64  4832.5  428.97
  4876.1  424.61  4894.2  424.00  4913.0  422.35  4984.9  424.24  4992.2  421.88
  4997.0  417.39  4997.5  416.59  5003.6  417.39  5010.5  420.85  5030.9  424.30
  5143.3  422.96  5183.6  424.00  5194.7  424.99  5306.9  435.63  5380.2  438.20
  5398.8  439.82  5490.8  442.95  5668.7  445.73  5705.4  448.20  5721.7  447.52
#Mann=8,-1,0
  4244.4    0.16       0  4264.5    0.12       0  4378.8    0.16       0
  4417.7    0.05       0  4721.8    0.12       0  4997.0    0.07       0
  5003.6    0.12       0  5194.7    0.05       0
Bank Sta=4894.2,5183.6
Exp/Cntr=0.3,0.1

Type RM Length L Ch R = 1,20043,189,189,189
BEGIN DESCRIPTION:
GLADE BRANCH 34.0
END DESCRIPTION:
XS GIS Cut Line= 4
      2907123.08      7027616.45      2906450.37      7027555.69
      2906250.00      7027750.00      2906189.98      7028709.76
#Sta/Elev= 30
  4150.3  444.98  4256.6  440.04  4309.0  438.55  4489.8  426.45  4563.0  423.66
  4720.7  420.16  4809.8  420.29  4977.5  422.51  4991.7  420.45  4995.6  415.45
  4996.1  414.65  5002.2  415.45  5005.8  416.00  5013.0  421.17  5027.2  421.62
  5034.1  421.30  5041.3  418.30  5055.5  420.50  5200.0  420.48  5273.6  423.66
  5339.3  425.92  5367.8  426.45  5401.0  426.11  5500.6  425.69  5563.6  427.33
  5721.1  430.28  5761.1  428.76  5906.2  431.95  5981.6  435.42  6066.5  442.08
#Mann=9,-1,0
  4150.3    0.16       0  4256.6    0.12       0  4809.8    0.16       0
  4995.6    0.07       0  5002.2    0.16       0  5339.3    0.12       0
  5367.8    0.16       0  5401.0    0.12       0  5563.6    0.05       0
Bank Sta=4563,5273.6
Exp/Cntr=0.3,0.1

Type RM Length L Ch R = 1,19854,602,602,602
BEGIN DESCRIPTION:
GLADE BRANCH 33.0
END DESCRIPTION:
XS GIS Cut Line= 3
      2907179.24      7027451.46      2906367.90      7027496.67
      2905764.30      7027494.86
#Sta/Elev= 30
  4187.4  449.24  4338.9  443.04  4445.6  436.59  4462.1  434.61  4502.1  433.87
  4512.1  432.97  4518.9  430.33  4523.9  431.13  4552.2  427.53  4650.9  423.28
  4742.4  422.32  4812.6  419.47  4972.9  421.09  4982.9  415.23  4988.7  413.71
  4989.4  412.91  4997.1  413.71  4998.9  416.39  5003.9  416.39  5012.9  420.72
  5035.5  420.52  5072.9  421.26  5088.4  423.28  5122.9  428.81  5152.9  431.03
  5282.9  432.73  5312.9  435.85  5333.4  436.16  5447.3  439.05  5603.6  442.76
#Mann=8,-1,0
  4187.4    0.16       0  4445.6    0.12       0  4742.4    0.16       0
  4988.7    0.07       0  4997.1    0.16       0  5035.5    0.12       0
  5333.4    0.16       0  5447.3    0.05       0
Bank Sta=4650.9,5088.4
Exp/Cntr=0.3,0.1

Type RM Length L Ch R = 1,19252,574,574,574
BEGIN DESCRIPTION:
GLADE BRANCH 32.0
END DESCRIPTION:
XS GIS Cut Line= 3
      2906924.96      7026775.01      2906375.00      7026925.00
      2905975.04      7027174.98
#Sta/Elev= 30
  4444.5  466.59  4575.7  450.35  4580.9  451.10  4599.9  448.78  4638.1  440.95
  4682.9  436.27  4722.9  428.89  4755.4  423.89  4787.0  421.33  4878.1  417.70
  4942.0  419.28  4962.7  418.08  4983.4  419.67  4997.3  418.19  5000.0  413.50
  5000.7  412.70  5008.4  413.50  5012.0  415.89  5017.5  415.89  5022.2  420.01
  5049.9  419.52  5064.7  417.38  5131.7  421.33  5180.2  426.94  5236.4  430.50
  5253.3  434.04  5293.8  436.63  5320.6  436.78  5399.6  434.12  5486.2  436.79
#Mann=7,-1,0
  4444.5    0.05       0  4638.1    0.16       0  4722.9    0.12       0
  5000.0    0.07       0  5008.4    0.12       0  5236.4    0.16       0
  5293.8    0.12       0
Bank Sta=4787,5131.7
Exp/Cntr=0.3,0.1

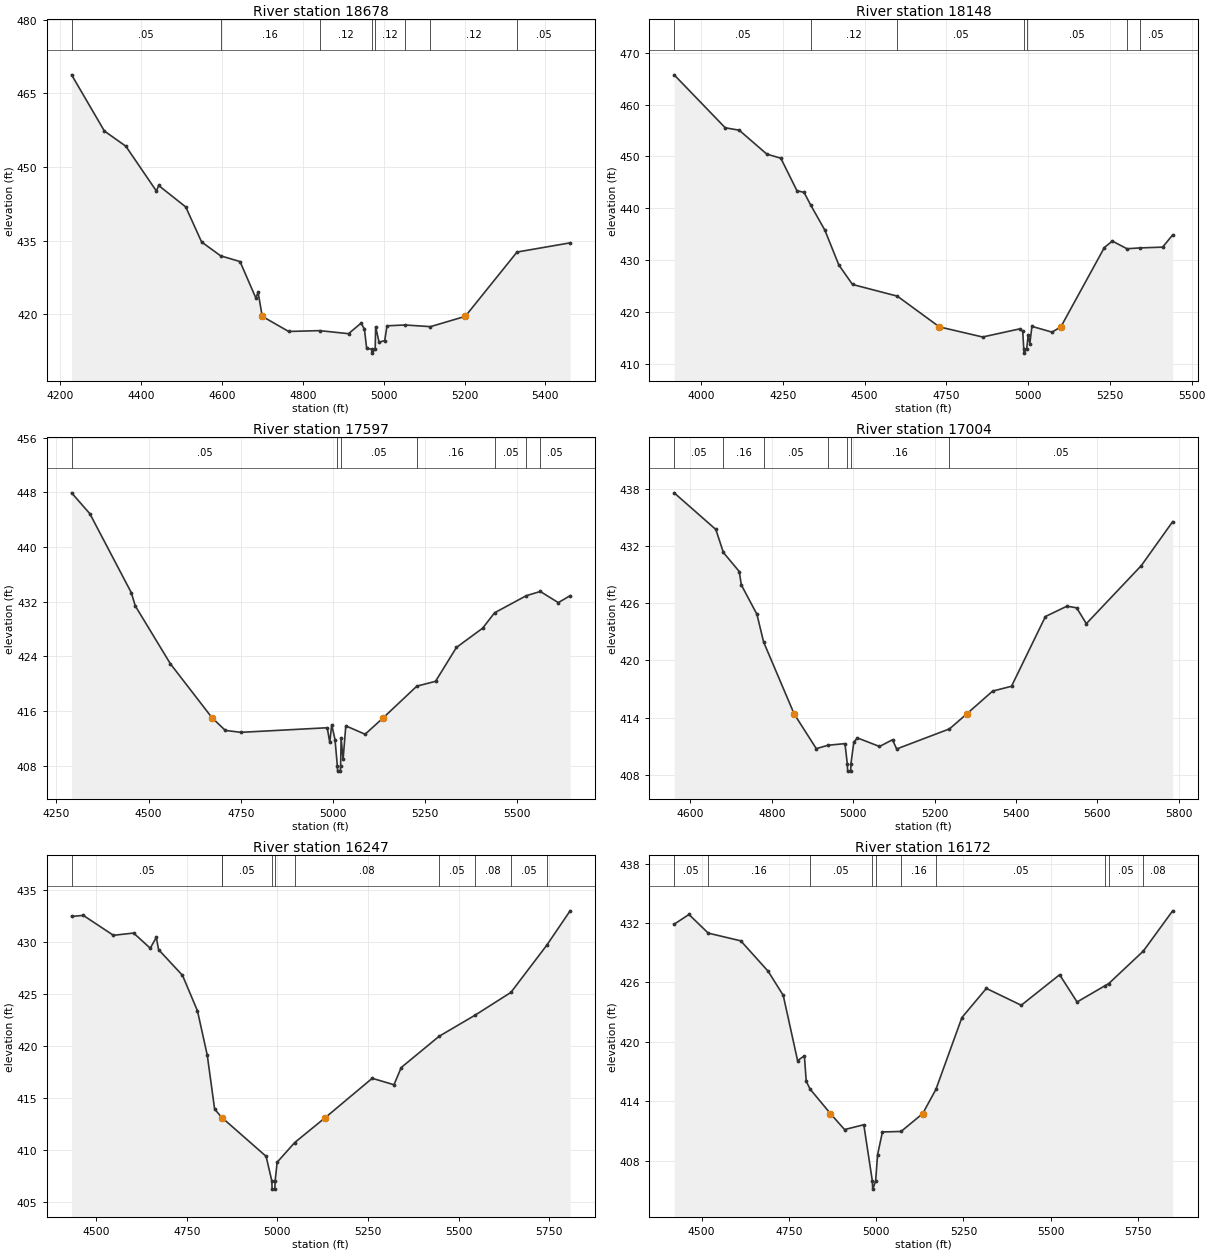
Type RM Length L Ch R = 1,18678,530,530,530
BEGIN DESCRIPTION:
GLADE BRANCH 31.0
END DESCRIPTION:
XS GIS Cut Line= 3
      2906975.03      7026725.02      2906275.00      7026375.00
      2905824.96      7026375.00
#Sta/Elev= 30
  4228.4  468.79  4309.5  457.35  4362.6  454.25  4438.1  445.13  4443.7  446.26
  4510.7  441.89  4549.9  434.76  4597.0  431.94  4644.9  430.77  4684.0  423.36
  4689.6  424.51  4699.8  419.62  4765.1  416.54  4841.7  416.71  4913.2  416.09
  4944.0  418.22  4952.4  417.07  4958.0  413.13  4970.3  412.93  4971.1  412.13
  4979.1  412.93  4980.3  417.50  4988.7  414.35  5002.7  414.69  5008.3  417.69
  5053.1  417.86  5115.8  417.52  5201.9  419.62  5329.8  432.71  5461.1  434.58
#Mann=8,-1,0
  4228.4    0.05       0  4597.0    0.16       0  4841.7    0.12       0
  4970.3    0.07       0  4979.1    0.12       0  5053.1    0.16       0
  5115.8    0.12       0  5329.8    0.05       0
Bank Sta=4699.8,5201.9
Exp/Cntr=0.3,0.1

Type RM Length L Ch R = 1,18148,551,551,551
BEGIN DESCRIPTION:
GLADE BRANCH 30.0
END DESCRIPTION:
XS GIS Cut Line= 3
      2907025.02      7026675.03      2906325.00      7025875.00
      2905875.03      7025974.99
#Sta/Elev= 30
  3917.9  465.73  4074.1  455.52  4116.8  455.05  4201.2  450.44  4244.0  449.65
  4293.3  443.39  4315.1  443.06  4334.8  440.68  4378.7  435.77  4421.4  429.06
  4463.2  425.30  4600.2  423.05  4728.8  417.12  4860.9  415.17  4973.8  416.73
  4983.5  416.31  4986.8  412.86  4987.6  412.06  4995.6  412.86  5000.2  415.52
  5005.3  413.88  5011.7  417.22  5073.1  416.11  5100.1  417.12  5233.2  432.43
  5257.5  433.67  5302.2  432.19  5341.3  432.35  5411.2  432.50  5441.9  434.86
#Mann=7,-1,0
  3917.9    0.05       0  4334.8    0.12       0  4600.2    0.05       0
  4986.8    0.03       0  4995.6    0.05       0  5302.2    0.16       0
  5341.3    0.05       0
Bank Sta=4728.8,5100.1
Exp/Cntr=0.3,0.1

Type RM Length L Ch R = 1,17597,593,593,593
BEGIN DESCRIPTION:
GLADE BRANCH 29.0
END DESCRIPTION:
XS GIS Cut Line= 3
      2907027.32      7025576.46      2906325.00      7025325.00
      2905911.87      7025767.43
#Sta/Elev= 30
  4291.5  447.95  4341.0  444.89  4453.3  433.34  4464.1  431.40  4559.5  422.91
  4672.1  415.03  4708.2  413.17  4750.5  412.89  4984.4  413.56  4991.3  411.43
  4996.6  414.00  5005.6  411.81  5011.8  408.01  5012.6  407.21  5019.8  407.21
  5020.7  408.01  5022.1  412.06  5027.4  408.92  5034.8  413.84  5087.1  412.61
  5136.5  415.03  5227.3  419.65  5278.1  420.36  5334.7  425.32  5405.6  428.13
  5438.1  430.39  5523.9  432.89  5562.0  433.51  5610.8  431.88  5642.8  432.89
#Mann=7,-1,0
  4291.5    0.05       0  5011.8    0.03       0  5020.7    0.05       0
  5227.3    0.16       0  5438.1    0.05       0  5523.9    0.16       0
  5562.0    0.05       0
Bank Sta=4672.1,5136.5
Exp/Cntr=0.3,0.1

Type RM Length L Ch R = 1,17004,757,757,757
BEGIN DESCRIPTION:
GLADE BRANCH 28.0
END DESCRIPTION:
XS GIS Cut Line= 3
      2906575.04      7024724.99      2906125.00      7024825.00
      2905419.41      7025119.76
#Sta/Elev= 30
  4559.8  437.62  4662.3  433.77  4680.9  431.35  4719.9  429.35  4725.0  427.94
  4763.4  424.85  4779.7  421.95  4855.0  414.37  4909.4  410.73  4937.9  411.09
  4979.8  411.26  4985.5  409.17  4986.4  408.37  4993.8  408.37  4994.6  409.17
  5001.6  411.43  5010.6  411.86  5064.7  410.96  5096.7  411.67  5106.9  410.70
  5236.8  412.81  5278.9  414.37  5342.8  416.78  5389.3  417.29  5472.7  424.62
  5525.7  425.71  5549.5  425.53  5573.3  423.87  5708.6  429.98  5785.5  434.59
#Mann=7,-1,0
  4559.8    0.05       0  4680.9    0.16       0  4779.7    0.05       0
  4937.9    0.16       0  4985.5    0.07       0  4994.6    0.16       0
  5236.8    0.05       0
Bank Sta=4855,5278.9
Exp/Cntr=0.3,0.1

Type RM Length L Ch R = 1,16247,75,75,75
BEGIN DESCRIPTION:
Mapping XS 461e8d18
END DESCRIPTION:
XS GIS Cut Line= 5
      2906706.13      7024115.52      2906494.33      7024056.50
      2906386.69      7024087.75      2905997.80      7024153.72
      2905349.24      7024160.66
#Sta/Elev= 30
  4432.4  432.50  4464.7  432.60  4547.8  430.68  4603.4  430.90  4649.3  429.44
  4666.0  430.47  4672.4  429.30  4738.3  426.82  4779.6  423.40  4806.6  419.13
  4826.9  413.94  4846.3  413.13  4846.6  413.12  4848.6  413.07  4968.9  409.38
  4984.6  407.02  4985.5  406.22  4993.0  406.22  4993.9  407.02  4999.4  408.81
  5047.8  410.71  5132.4  413.12  5261.6  416.90  5321.6  416.28  5341.6  417.94
  5446.1  420.95  5545.1  422.98  5644.2  425.18  5743.3  429.74  5807.4  433.04
#Mann=10,-1,0
  4432.4    0.05       0  4846.3    0.16       0  4848.6    0.05       0
  4984.6    0.04       0  4993.9    0.05       0  5047.8    0.08       0
  5446.1    0.05       0  5545.1    0.08       0  5644.2    0.05       0
  5743.3    0.08       0
Bank Sta=4846.6,5132.4
Exp/Cntr=0.3,0.1

Type RM Length L Ch R = 1,16172,398,398,398
BEGIN DESCRIPTION:
Mapping XS 33e8b282
END DESCRIPTION:
XS GIS Cut Line= 6
      2906733.89      7024042.60      2906553.36      7023980.11
      2906431.83      7023976.64      2906258.22      7024042.61
      2906067.25      7024077.33      2905331.13      7024084.27
#Sta/Elev= 30
  4421.1  431.88  4463.6  432.86  4518.8  430.98  4612.1  430.20  4690.5  427.13
  4733.7  424.70  4774.9  418.11  4794.3  418.60  4799.7  416.02  4810.9  415.23
  4869.1  412.76  4909.5  411.15  4964.6  411.64  4989.2  405.94  4990.1  405.14
  4998.5  405.94  5004.0  408.59  5018.0  410.91  5071.4  410.96  5133.3  412.76
  5171.3  415.21  5245.8  422.46  5315.8  425.40  5415.8  423.70  5525.8  426.78
  5575.8  424.03  5655.8  425.67  5666.6  425.89  5765.7  429.17  5849.7  433.23
#Mann=10,-1,0
  4421.1    0.05       0  4518.8    0.16       0  4810.9    0.05       0
  4989.2    0.04       0  4998.5    0.05       0  5071.4    0.16       0
  5171.3    0.05       0  5655.8    0.08       0  5666.6    0.05       0
  5765.7    0.08       0
Bank Sta=4869.1,5133.3
Exp/Cntr=0.3,0.1

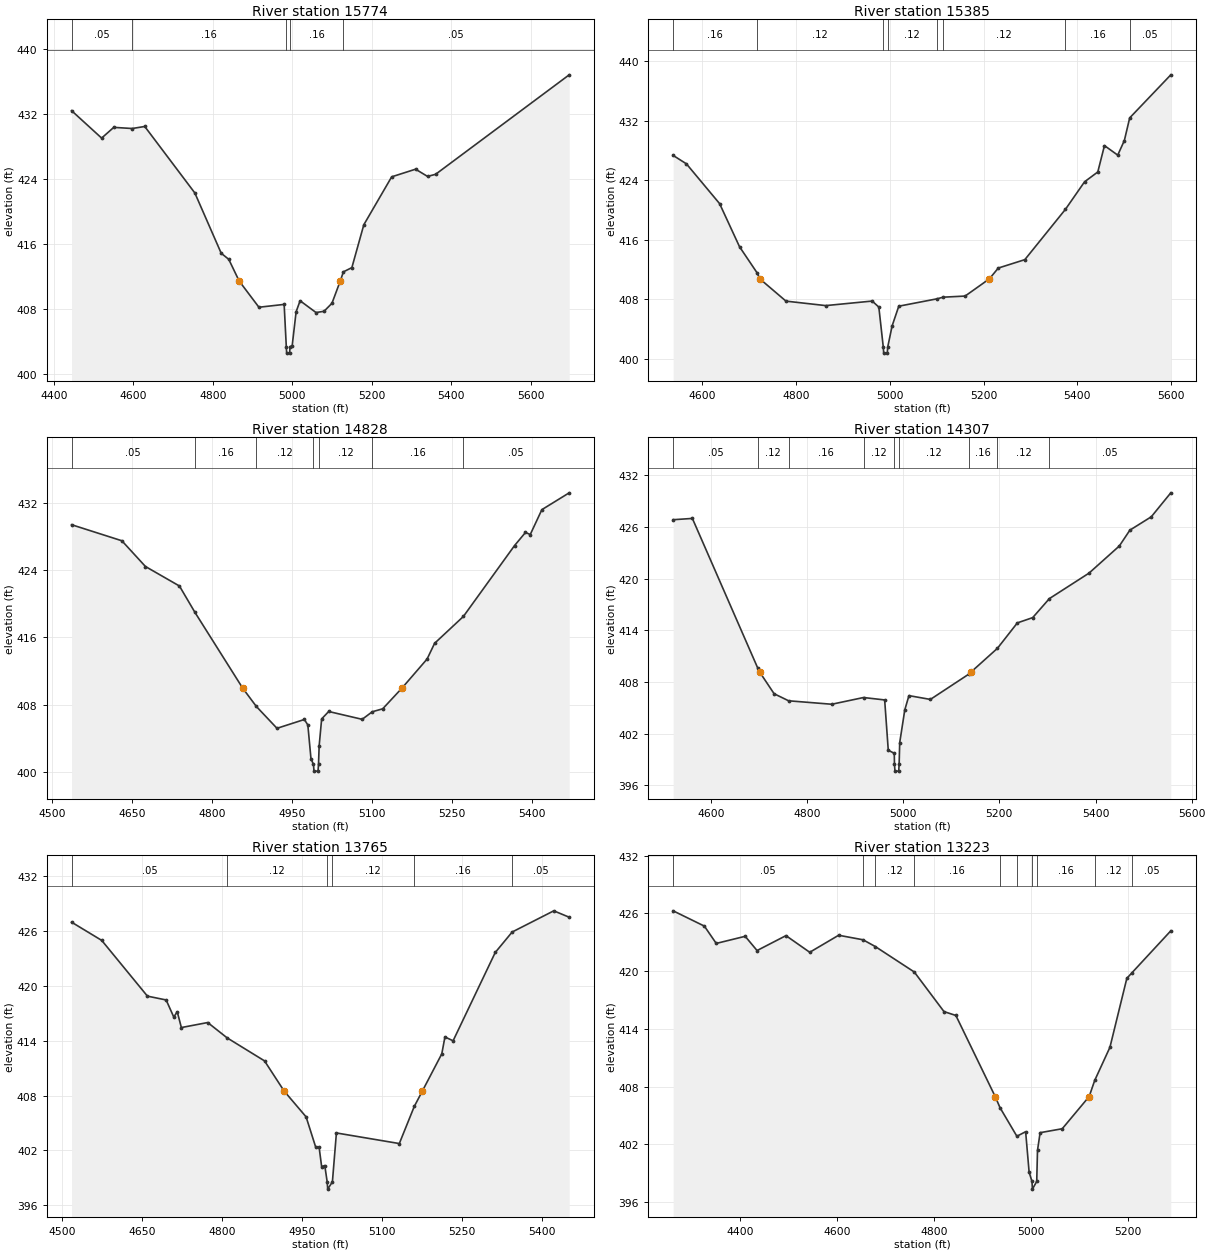
Type RM Length L Ch R = 1,15774,389,389,389
BEGIN DESCRIPTION:
Mapping XS e2065353
END DESCRIPTION:
XS GIS Cut Line= 3
      2906753.85      7023866.38      2906267.77      7023675.42
      2905539.27      7023627.72
#Sta/Elev= 30
  4444.7  432.40  4520.4  429.02  4550.9  430.34  4597.3  430.20  4628.9  430.45
  4755.0  422.26  4821.3  414.84  4840.3  414.09  4866.5  411.42  4916.2  408.19
  4979.7  408.54  4985.1  403.34  4986.0  402.54  4993.5  402.54  4994.4  403.34
  4999.8  403.41  5009.8  407.63  5019.8  408.99  5059.9  407.54  5080.0  407.69
  5100.0  408.68  5120.9  411.42  5128.8  412.55  5150.1  413.07  5180.2  418.35
  5250.3  424.25  5310.4  425.19  5340.5  424.30  5360.8  424.56  5697.0  436.81
#Mann=5,-1,0
  4444.7    0.05       0  4597.3    0.16       0  4985.1    0.07       0
  4994.4    0.16       0  5128.8    0.05       0
Bank Sta=4866.5,5120.9
Exp/Cntr=0.3,0.1

Type RM Length L Ch R = 1,15385,557,557,557
BEGIN DESCRIPTION:
GLADE BRANCH 25.0
END DESCRIPTION:
XS GIS Cut Line= 3
      2906625.03      7023625.03      2906275.00      7023275.00
      2905875.00      7022875.00
#Sta/Elev= 30
  4538.3  427.34  4566.6  426.21  4637.3  420.87  4679.8  415.08  4717.4  411.56
  4723.1  410.77  4778.8  407.78  4863.6  407.18  4962.6  407.79  4976.7  406.98
  4986.2  401.60  4987.1  400.80  4994.7  400.80  4995.6  401.60  5005.0  404.45
  5019.2  407.10  5100.7  408.09  5113.8  408.31  5160.6  408.46  5212.3  410.77
  5231.3  412.22  5287.9  413.35  5374.5  420.11  5415.2  423.80  5443.4  425.12
  5457.6  428.66  5485.9  427.38  5500.0  429.34  5511.4  432.38  5599.0  438.16
#Mann=8,-1,0
  4538.3    0.16       0  4717.4    0.12       0  4986.2    0.07       0
  4995.6    0.12       0  5100.7    0.16       0  5113.8    0.12       0
  5374.5    0.16       0  5511.4    0.05       0
Bank Sta=4723.1,5212.3
Exp/Cntr=0.3,0.1

Type RM Length L Ch R = 1,14828,521,521,521
BEGIN DESCRIPTION:
GLADE BRANCH 24.0
END DESCRIPTION:
XS GIS Cut Line= 3
      2906924.96      7023074.98      2906525.00      7022825.00
      2906075.03      7022725.01
#Sta/Elev= 30
  4536.8  429.40  4631.1  427.49  4675.3  424.43  4739.0  422.11  4768.0  418.98
  4857.7  409.95  4883.1  407.79  4921.8  405.19  4973.1  406.24  4979.6  405.59
  4985.5  401.57  4990.2  400.90  4991.1  400.10  4998.7  400.10  4999.6  400.90
  5000.8  403.09  5005.5  406.31  5018.7  407.19  5081.4  406.26  5100.4  407.16
  5119.9  407.51  5155.7  409.95  5203.1  413.43  5217.2  415.30  5271.1  418.49
  5367.0  426.92  5387.5  428.48  5396.4  428.23  5418.2  431.19  5469.4  433.19
#Mann=7,-1,0
  4536.8    0.05       0  4768.0    0.16       0  4883.1    0.12       0
  4990.2    0.07       0  4999.6    0.12       0  5100.4    0.16       0
  5271.1    0.05       0
Bank Sta=4857.7,5155.7
Exp/Cntr=0.3,0.1

Type RM Length L Ch R = 1,14307,542,542,542
BEGIN DESCRIPTION:
GLADE BRANCH 23.0
END DESCRIPTION:
XS GIS Cut Line= 3
      2907124.97      7022325.00      2906675.00      7022325.00
      2906125.01      7022525.00
#Sta/Elev= 30
  4521.4  426.83  4561.4  426.98  4697.5  409.60  4701.2  409.17  4731.4  406.64
  4761.6  405.82  4851.4  405.42  4917.4  406.20  4961.4  405.92  4968.9  400.08
  4981.4  399.73  4981.8  398.46  4982.8  397.66  4990.6  397.66  4991.5  398.46
  4992.7  400.97  5003.3  404.78  5011.9  406.42  5056.5  405.98  5135.8  408.89
  5141.3  409.17  5196.0  411.91  5237.4  414.86  5269.3  415.47  5304.1  417.68
  5386.4  420.63  5449.5  423.78  5471.5  425.62  5516.0  427.17  5556.6  429.95
#Mann=9,-1,0
  4521.4    0.05       0  4697.5    0.12       0  4761.6    0.16       0
  4917.4    0.12       0  4981.8    0.07       0  4991.5    0.12       0
  5135.8    0.16       0  5196.0    0.12       0  5304.1    0.05       0
Bank Sta=4701.2,5141.3
Exp/Cntr=0.3,0.1

Type RM Length L Ch R = 1,13765,542,542,542
BEGIN DESCRIPTION:
GLADE BRANCH 22.0
END DESCRIPTION:
XS GIS Cut Line= 3
      2907225.02      7022175.02      2906875.00      7021875.00
      2906625.00      7021475.01
#Sta/Elev= 30
  4517.8  426.99  4574.4  424.99  4660.0  418.89  4695.1  418.47  4709.4  416.60
  4715.9  417.18  4723.6  415.45  4773.0  416.00  4809.4  414.32  4879.5  411.80
  4916.2  408.50  4957.4  405.67  4975.5  402.34  4981.8  402.34  4986.5  400.23
  4992.4  400.34  4996.9  398.56  4997.9  397.76  5006.7  398.56  5014.2  403.91
  5132.1  402.75  5160.2  406.82  5175.3  408.50  5211.7  412.57  5217.6  414.42
  5232.9  414.00  5311.9  423.67  5343.6  425.91  5421.6  428.23  5450.5  427.53
#Mann=6,-1,0
  4517.8    0.05       0  4809.4    0.12       0  4996.9    0.07       0
  5006.7    0.12       0  5160.2    0.16       0  5343.6    0.05       0
Bank Sta=4916.2,5175.3
Exp/Cntr=0.3,0.1

Type RM Length L Ch R = 1,13223,510,510,510
BEGIN DESCRIPTION:
GLADE BRANCH 21.0
END DESCRIPTION:
XS GIS Cut Line= 3
      2907403.36      7022140.17      2907125.00      7021425.00
      2906892.97      7021306.86
#Sta/Elev= 30
  4261.0  426.27  4325.5  424.68  4350.0  422.88  4409.8  423.62  4434.3  422.14
  4494.0  423.69  4543.1  421.96  4602.8  423.73  4653.1  423.26  4678.4  422.56
  4759.0  419.91  4820.4  415.79  4844.9  415.39  4926.1  406.96  4936.1  405.80
  4970.9  402.83  4989.0  403.30  4996.2  399.09  5002.1  398.13  5003.0  397.33
  5011.9  398.13  5013.5  401.36  5018.9  403.20  5064.6  403.61  5120.2  406.96
  5131.7  408.64  5163.1  412.08  5198.0  419.25  5208.8  419.84  5288.8  424.19
#Mann=10,-1,0
  4261.0    0.05       0  4653.1    0.16       0  4678.4    0.12       0
  4759.0    0.16       0  4936.1    0.12       0  4970.9    0.16       0
  5002.1    0.07       0  5011.9    0.16       0  5131.7    0.12       0
  5208.8    0.05       0
Bank Sta=4926.1,5120.2
Exp/Cntr=0.3,0.1