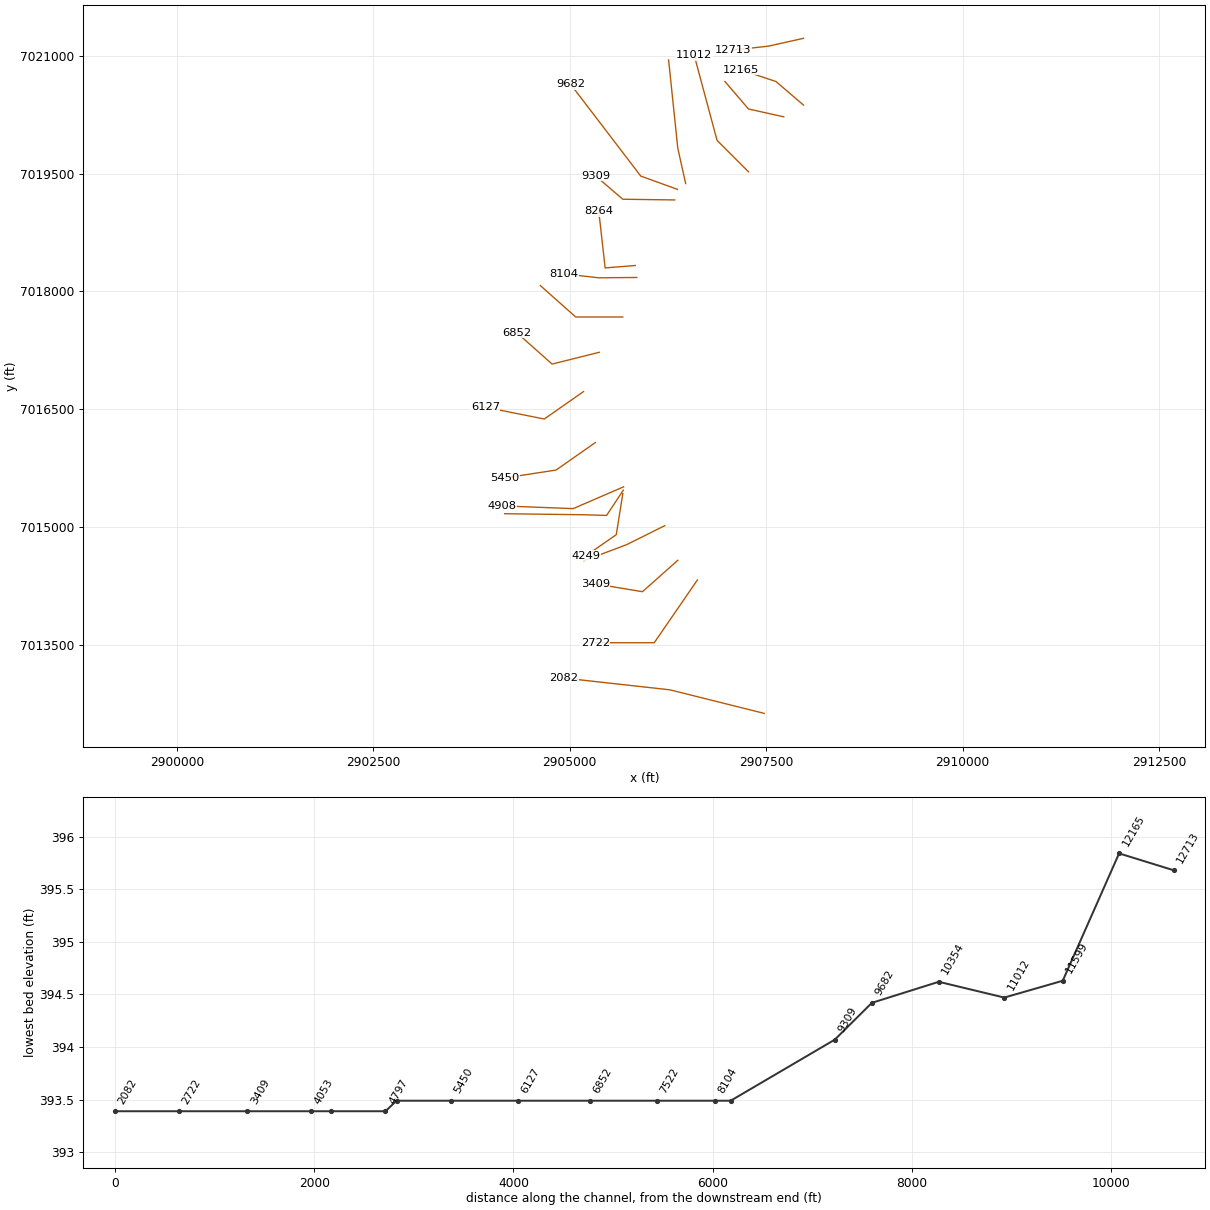
HEC-RAS study GLADE BRANCH.prj: GLADE BRANCH Base Level Engineering

--- GLADE BRANCH.g01 (geometry) --- (continued)

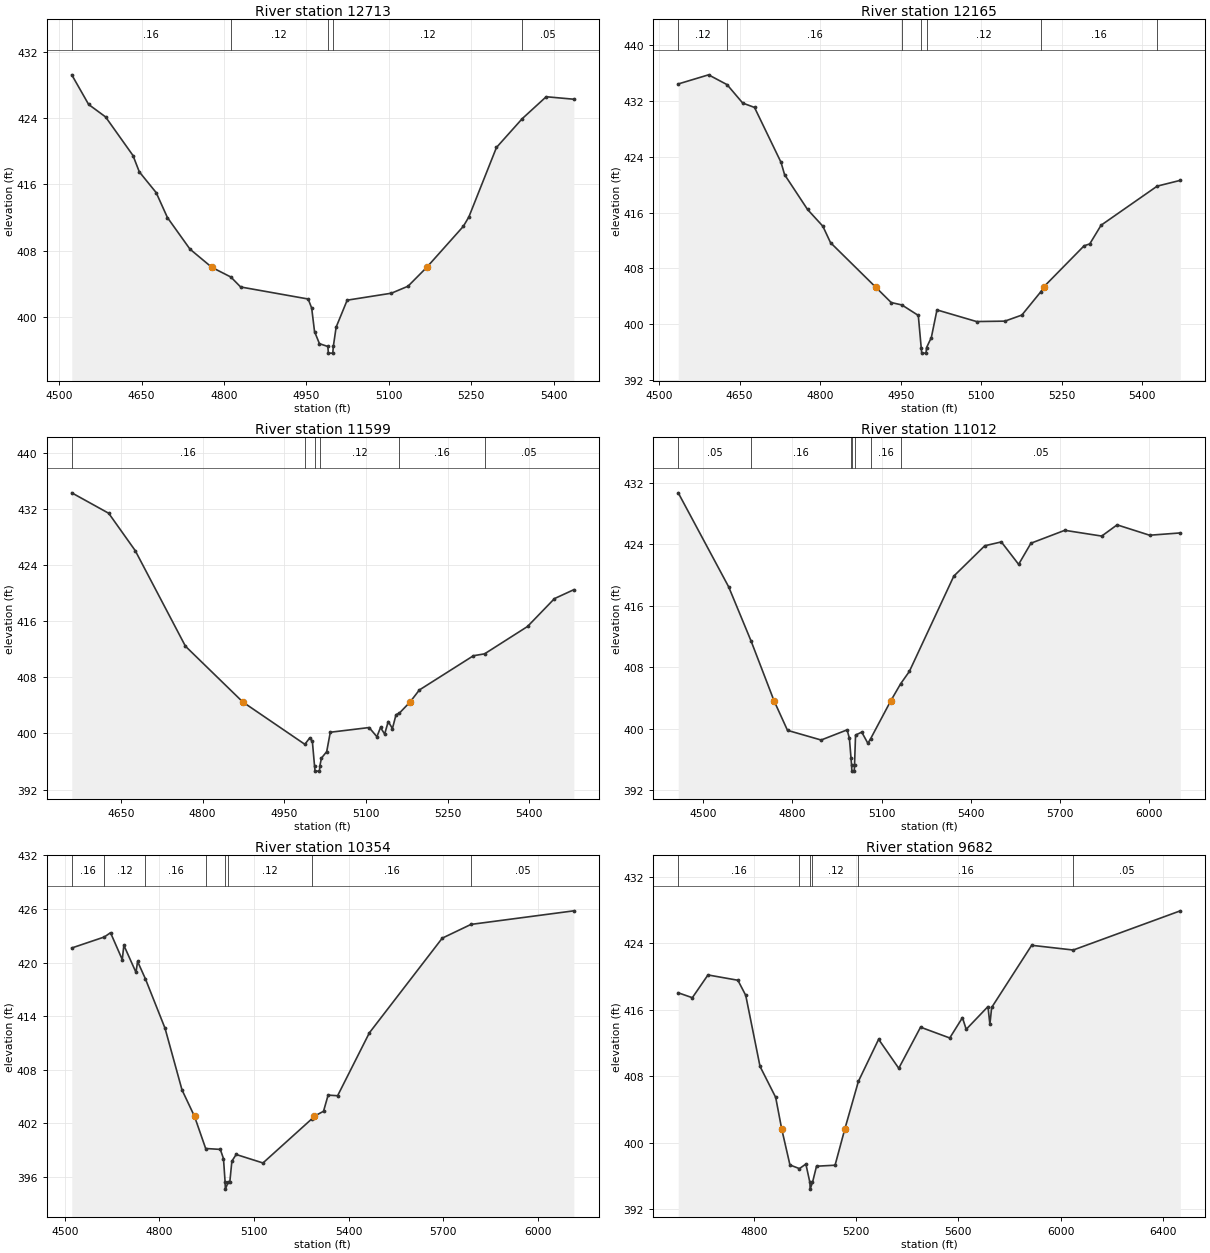
Type RM Length L Ch R = 1,12713,548,548,548
BEGIN DESCRIPTION:
GLADE BRANCH 20.0
END DESCRIPTION:
XS GIS Cut Line= 3
      2907974.99      7021225.00      2907525.00      7021125.00
      2907075.04      7021075.00
#Sta/Elev= 30
  4523.1  429.21  4553.8  425.64  4584.6  424.14  4634.5  419.49  4646.0  417.52
  4676.7  415.02  4697.2  412.01  4738.2  408.21  4778.1  406.01  4812.6  404.85
  4830.4  403.65  4953.3  402.20  4959.7  401.11  4964.9  398.28  4973.8  396.82
  4989.1  396.48  4990.1  395.68  4998.1  395.68  4999.1  396.48  5004.2  398.81
  5024.3  402.06  5104.8  402.90  5135.0  403.74  5169.0  406.01  5235.6  410.95
  5245.7  412.08  5296.0  420.46  5342.9  423.93  5386.5  426.57  5436.8  426.27
#Mann=5,-1,0
  4523.1    0.16       0  4812.6    0.12       0  4989.1    0.07       0
  4999.1    0.12       0  5342.9    0.05       0
Bank Sta=4778.1,5169
Exp/Cntr=0.3,0.1

Type RM Length L Ch R = 1,12165,566,566,566
BEGIN DESCRIPTION:
GLADE BRANCH 19.0
END DESCRIPTION:
XS GIS Cut Line= 3
      2907974.96      7020375.03      2907625.00      7020675.00
      2907174.97      7020825.01
#Sta/Elev= 30
  4535.6  434.46  4592.1  435.77  4626.6  434.36  4655.7  431.72  4677.7  431.09
  4727.1  423.21  4733.7  421.45  4776.5  416.45  4805.0  414.05  4819.3  411.69
  4903.1  405.33  4932.3  403.10  4952.3  402.75  4982.8  401.25  4988.2  396.64
  4989.2  395.84  4997.2  395.84  4998.2  396.64  5007.1  398.08  5017.6  402.04
  5091.4  400.37  5144.1  400.43  5175.7  401.30  5211.3  404.67  5216.3  405.33
  5291.7  411.24  5302.2  411.51  5323.3  414.19  5427.8  419.80  5470.9  420.63
#Mann=7,-1,0
  4535.6    0.12       0  4626.6    0.16       0  4952.3    0.12       0
  4988.2    0.07       0  4998.2    0.12       0  5211.3    0.16       0
  5427.8    0.05       0
Bank Sta=4903.1,5216.3
Exp/Cntr=0.3,0.1

Type RM Length L Ch R = 1,11599,587,587,587
BEGIN DESCRIPTION:
GLADE BRANCH 18.0
END DESCRIPTION:
XS GIS Cut Line= 3
      2907724.97      7020225.01      2907275.00      7020325.00
      2906975.02      7020674.98
#Sta/Elev= 30
  4559.8  434.28  4627.6  431.37  4676.3  426.05  4768.5  412.43  4874.0  404.47
  4987.8  398.45  4996.4  399.33  5001.5  398.93  5005.5  395.43  5006.5  394.63
  5014.5  394.63  5015.5  395.43  5018.2  396.48  5027.9  397.41  5034.5  400.17
  5105.8  400.84  5120.1  399.53  5126.7  400.85  5134.3  399.91  5140.9  401.70
  5148.6  400.70  5155.2  402.67  5161.4  402.90  5180.9  404.47  5198.0  406.19
  5297.3  411.07  5317.8  411.34  5396.7  415.24  5446.1  419.21  5481.7  420.48
#Mann=6,-1,0
  4559.8    0.16       0  4987.8    0.12       0  5005.5    0.07       0
  5015.5    0.12       0  5161.4    0.16       0  5317.8    0.05       0
Bank Sta=4874,5180.9
Exp/Cntr=0.3,0.1

Type RM Length L Ch R = 1,11012,658,658,658
BEGIN DESCRIPTION:
GLADE BRANCH 17.0
END DESCRIPTION:
XS GIS Cut Line= 3
      2907275.00      7019525.00      2906875.00      7019925.00
      2906583.44      7021010.44
#Sta/Elev= 30
  4415.6  430.70  4585.3  418.46  4660.6  411.42  4738.1  403.62  4783.3  399.78
  4896.4  398.52  4983.9  399.84  4991.6  398.75  4996.9  396.23  4998.9  395.27
  4999.9  394.47  5007.9  394.47  5008.9  395.27  5012.3  399.16  5033.1  399.55
  5053.8  398.09  5063.3  398.71  5130.8  403.62  5164.0  405.84  5193.4  407.45
  5343.0  419.86  5447.2  423.81  5502.9  424.31  5561.1  421.39  5602.5  424.14
  5716.4  425.82  5840.7  425.07  5892.5  426.53  6002.0  425.18  6105.2  425.48
#Mann=7,-1,0
  4415.6    0.05       0  4660.6    0.16       0  4996.9    0.12       0
  4998.9    0.07       0  5008.9    0.12       0  5063.3    0.16       0
  5164.0    0.05       0
Bank Sta=4738.1,5130.8
Exp/Cntr=0.3,0.1

Type RM Length L Ch R = 1,10354,672,672,672
BEGIN DESCRIPTION:
GLADE BRANCH 16.0
END DESCRIPTION:
XS GIS Cut Line= 3
      2906475.00      7019374.99      2906375.00      7019825.00
      2906257.82      7020950.02
#Sta/Elev= 30
  4522.4  421.63  4625.6  422.86  4645.3  423.34  4682.5  420.33  4687.6  421.93
  4726.0  418.90  4731.1  420.12  4755.8  418.18  4818.2  412.63  4872.0  405.73
  4911.6  402.77  4947.0  399.17  4993.4  399.07  5003.5  398.04  5008.6  395.42
  5009.5  394.62  5018.6  395.42  5023.6  395.43  5030.1  397.75  5043.7  398.50
  5128.7  397.55  5284.3  402.51  5290.6  402.77  5320.7  403.34  5335.3  405.15
  5365.4  405.08  5466.0  412.12  5697.2  422.73  5788.4  424.27  6114.5  425.79
#Mann=8,-1,0
  4522.4    0.16       0  4625.6    0.12       0  4755.8    0.16       0
  4947.0    0.12       0  5008.6    0.07       0  5018.6    0.12       0
  5284.3    0.16       0  5788.4    0.05       0
Bank Sta=4911.6,5290.6
Exp/Cntr=0.3,0.1

Type RM Length L Ch R = 1,9682,373,373,373
BEGIN DESCRIPTION:
GLADE BRANCH 15.0
END DESCRIPTION:
XS GIS Cut Line= 3
      2906370.67      7019300.76      2905903.69      7019469.98
      2905012.18      7020637.54
#Sta/Elev= 30
  4503.3  418.06  4558.5  417.47  4619.7  420.21  4736.9  419.57  4767.6  417.75
  4823.5  409.20  4884.8  405.47  4908.2  401.69  4940.7  397.33  4977.8  396.89
  5003.0  397.44  5018.8  395.22  5019.8  394.42  5028.9  395.22  5044.7  397.18
  5117.3  397.30  5155.8  401.69  5208.7  407.40  5287.8  412.46  5366.7  408.97
  5452.0  413.92  5566.3  412.62  5616.1  415.07  5630.7  413.66  5715.9  416.40
  5723.5  414.27  5730.4  416.29  5887.0  423.78  6049.7  423.21  6469.0  427.93
#Mann=6,-1,0
  4503.3    0.16       0  4977.8    0.12       0  5018.8    0.07       0
  5028.9    0.12       0  5208.7    0.16       0  6049.7    0.05       0
Bank Sta=4908.2,5155.8
Exp/Cntr=0.3,0.1

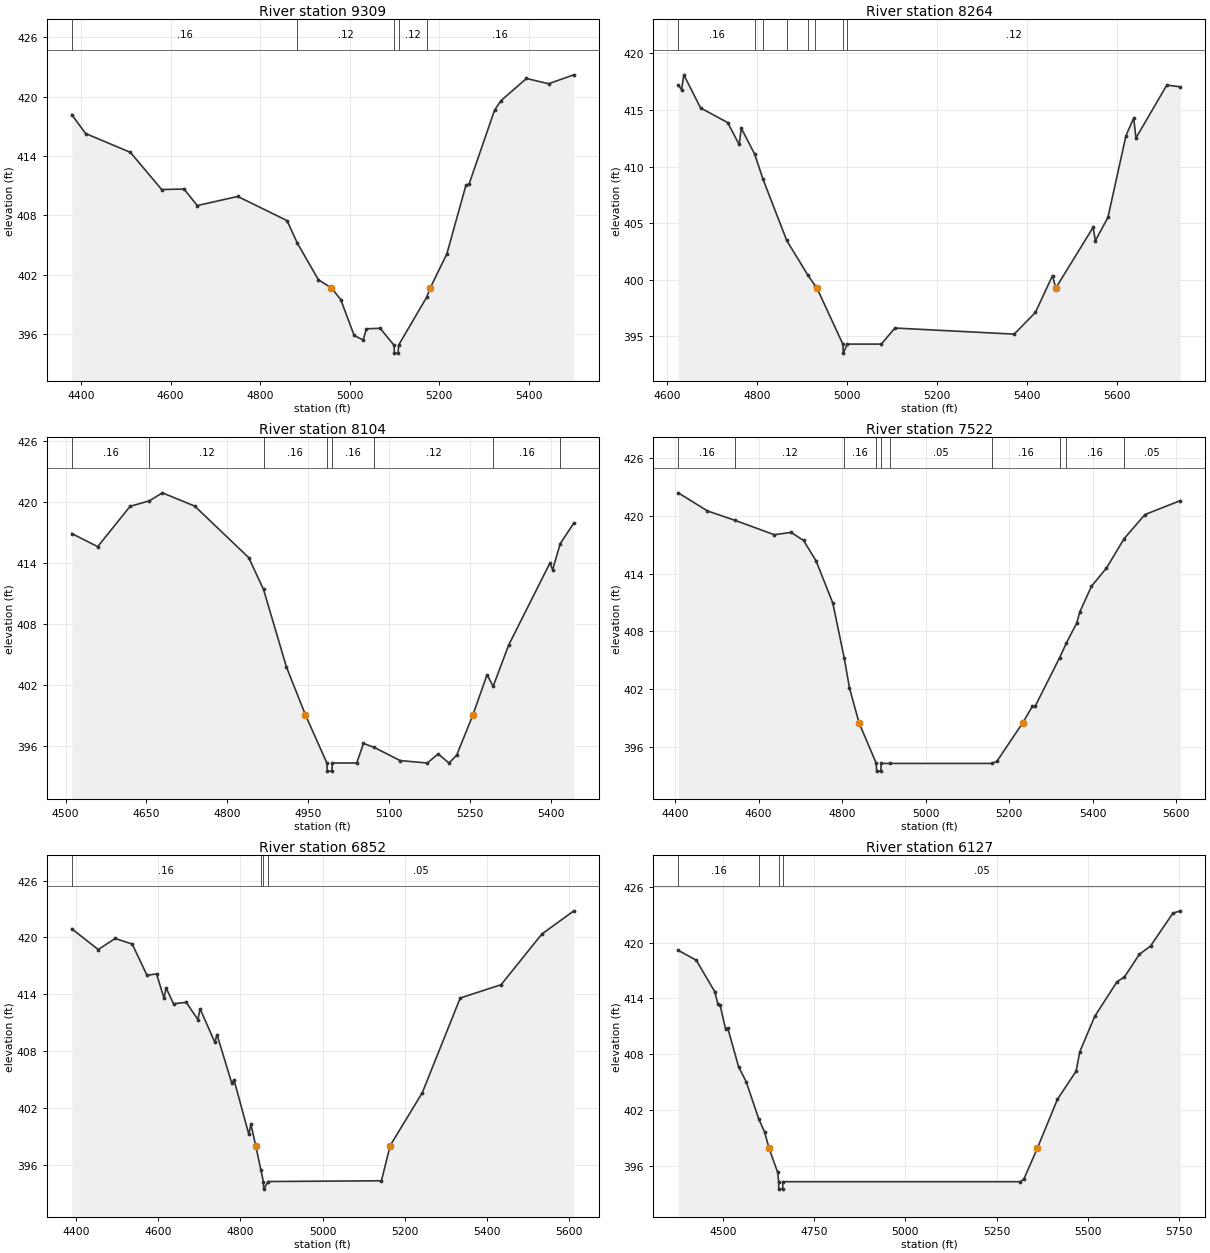
Type RM Length L Ch R = 1,9309,1045,1045,1045
BEGIN DESCRIPTION:
GLADE BRANCH 14.0
END DESCRIPTION:
XS GIS Cut Line= 3
      2906335.91      7019166.22      2905675.00      7019175.00
      2905325.04      7019474.97
#Sta/Elev= 30
  4379.3  418.17  4410.2  416.26  4510.2  414.36  4580.2  410.60  4630.2  410.65
  4659.6  408.98  4750.2  409.90  4860.3  407.46  4883.1  405.21  4930.3  401.49
  4959.6  400.65  4980.3  399.48  5010.3  395.86  5030.3  395.40  5037.8  396.53
  5068.3  396.58  5099.4  394.87  5100.4  394.07  5108.6  394.07  5109.5  394.87
  5172.2  399.71  5180.2  400.65  5217.5  404.11  5260.3  411.07  5266.9  411.13
  5324.0  418.62  5338.3  419.58  5395.3  421.82  5444.7  421.29  5501.2  422.19
#Mann=5,-1,0
  4379.3    0.16       0  4883.1    0.12       0  5099.4    0.07       0
  5109.5    0.12       0  5172.2    0.16       0
Bank Sta=4959.6,5180.2
Exp/Cntr=0.3,0.1

Type RM Length L Ch R = 1,8264,160,160,160
BEGIN DESCRIPTION:
GLADE BRANCH 13.0
END DESCRIPTION:
XS GIS Cut Line= 3
      2905834.39      7018330.83      2905450.00      7018300.00
      2905368.68      7019024.82
#Sta/Elev= 30
  4624.7  417.21  4632.1  416.81  4637.1  418.11  4674.3  415.18  4734.4  413.89
  4759.9  411.95  4764.9  413.38  4794.5  411.09  4813.0  408.87  4865.6  403.46
  4912.1  400.42  4929.1  399.43  4932.8  399.24  4990.2  394.29  4991.2  393.49
  5000.4  394.29  5075.7  394.29  5105.9  395.71  5370.8  395.17  5417.9  397.09
  5455.9  400.35  5463.0  399.24  5546.1  404.62  5551.1  403.44  5578.9  405.49
  5619.1  412.74  5636.2  414.29  5641.2  412.52  5709.7  417.20  5739.7  417.05
#Mann=8,-1,0
  4624.7    0.16       0  4794.5    0.12       0  4813.0    0.16       0
  4865.6    0.12       0  4912.1    0.16       0  4929.1    0.12       0
  4990.2    0.07       0  5000.4    0.12       0
Bank Sta=4932.8,5463
Exp/Cntr=0.3,0.1

Type RM Length L Ch R = 1,8104,582,582,582
BEGIN DESCRIPTION:
GLADE BRANCH 12.0
END DESCRIPTION:
XS GIS Cut Line= 3
      2905853.08      7018178.49      2905364.60      7018174.28
      2904925.01      7018225.00
#Sta/Elev= 30
  4511.5  416.89  4559.6  415.60  4619.6  419.57  4655.3  420.11  4679.6  420.90
  4739.6  419.59  4839.6  414.52  4867.1  411.38  4909.6  403.74  4944.9  399.02
  4984.5  394.29  4985.5  393.49  4993.7  393.49  4994.7  394.29  5039.9  394.29
  5052.4  396.22  5072.6  395.82  5120.4  394.53  5170.7  394.29  5190.9  395.18
  5211.0  394.29  5225.2  395.06  5255.3  399.02  5281.5  402.98  5292.9  401.85
  5321.7  405.91  5398.1  413.98  5403.1  413.33  5417.3  415.90  5442.5  417.93
#Mann=8,-1,0
  4511.5    0.16       0  4655.3    0.12       0  4867.1    0.16       0
  4984.5    0.07       0  4994.7    0.16       0  5072.6    0.12       0
  5292.9    0.16       0  5417.3    0.12       0
Bank Sta=4944.9,5255.3
Exp/Cntr=0.3,0.1

Type RM Length L Ch R = 1,7522,670,670,670
BEGIN DESCRIPTION:
GLADE BRANCH 11.0
END DESCRIPTION:
XS GIS Cut Line= 3
      2905674.97      7017675.00      2905075.00      7017675.00
      2904625.03      7018074.97
#Sta/Elev= 30
  4407.8  422.39  4477.8  420.51  4544.6  419.52  4637.8  418.04  4677.8  418.28
  4707.8  417.45  4737.8  415.32  4777.8  410.95  4805.3  405.22  4817.8  402.12
  4840.7  398.50  4882.0  394.29  4882.7  393.49  4892.9  393.49  4893.5  394.29
  4915.3  394.29  5157.8  394.29  5170.4  394.49  5232.4  398.50  5255.7  400.22
  5262.4  400.23  5320.6  405.25  5337.0  406.79  5361.9  408.88  5369.0  410.00
  5397.0  412.68  5433.0  414.58  5475.4  417.64  5525.0  420.13  5609.8  421.58
#Mann=10,-1,0
  4407.8    0.16       0  4544.6    0.12       0  4805.3    0.16       0
  4882.0   0.033       0  4893.5    0.16       0  4915.3    0.05       0
  5157.8    0.16       0  5320.6    0.12       0  5337.0    0.16       0
  5475.4    0.05       0
Bank Sta=4840.7,5232.4
Exp/Cntr=0.3,0.1

Type RM Length L Ch R = 1,6852,725,725,725
BEGIN DESCRIPTION:
GLADE BRANCH 10.0
END DESCRIPTION:
XS GIS Cut Line= 3
      2905374.99      7017225.00      2904775.00      7017075.00
      2904325.03      7017474.97
#Sta/Elev= 30
  4390.4  420.92  4454.8  418.73  4496.0  419.90  4537.3  419.31  4573.4  416.01
  4596.5  416.17  4614.6  413.61  4619.7  414.69  4637.8  413.02  4668.7  413.17
  4697.0  411.36  4702.2  412.50  4738.3  408.95  4743.4  409.78  4779.5  404.63
  4784.7  405.02  4820.7  399.28  4825.9  400.32  4837.5  398.08  4850.2  395.50
  4856.2  394.29  4856.9  393.49  4867.7  394.29  5143.1  394.37  5164.5  398.08
  5242.6  403.66  5334.6  413.62  5434.1  415.03  5532.8  420.35  5610.9  422.81
#Mann=4,-1,0
  4390.4    0.16       0  4850.2    0.05       0  4856.2   0.033       0
  4867.7    0.05       0
Bank Sta=4837.5,5164.5
Exp/Cntr=0.3,0.1

Type RM Length L Ch R = 1,6127,677,677,677
BEGIN DESCRIPTION:
GLADE BRANCH 9.0
END DESCRIPTION:
XS GIS Cut Line= 3
      2905175.02      7016725.02      2904675.00      7016375.00
      2903925.01      7016525.00
#Sta/Elev= 30
  4377.7  419.18  4427.0  418.12  4477.6  414.74  4486.3  413.43  4492.4  413.29
  4507.2  410.73  4513.3  410.83  4543.0  406.66  4563.9  405.04  4598.3  401.03
  4614.5  399.61  4626.3  397.90  4650.2  395.28  4652.7  394.29  4653.3  393.49
  4663.6  393.49  4664.2  394.29  5314.4  394.29  5324.6  394.59  5361.4  397.90
  5416.4  403.16  5467.4  406.17  5477.6  408.27  5518.4  412.07  5579.5  415.80
  5599.9  416.32  5640.7  418.75  5671.3  419.64  5732.5  423.17  5752.9  423.43
#Mann=4,-1,0
  4377.7    0.16       0  4598.3    0.05       0  4652.7   0.033       0
  4664.2    0.05       0
Bank Sta=4626.3,5361.4
Exp/Cntr=0.3,0.1

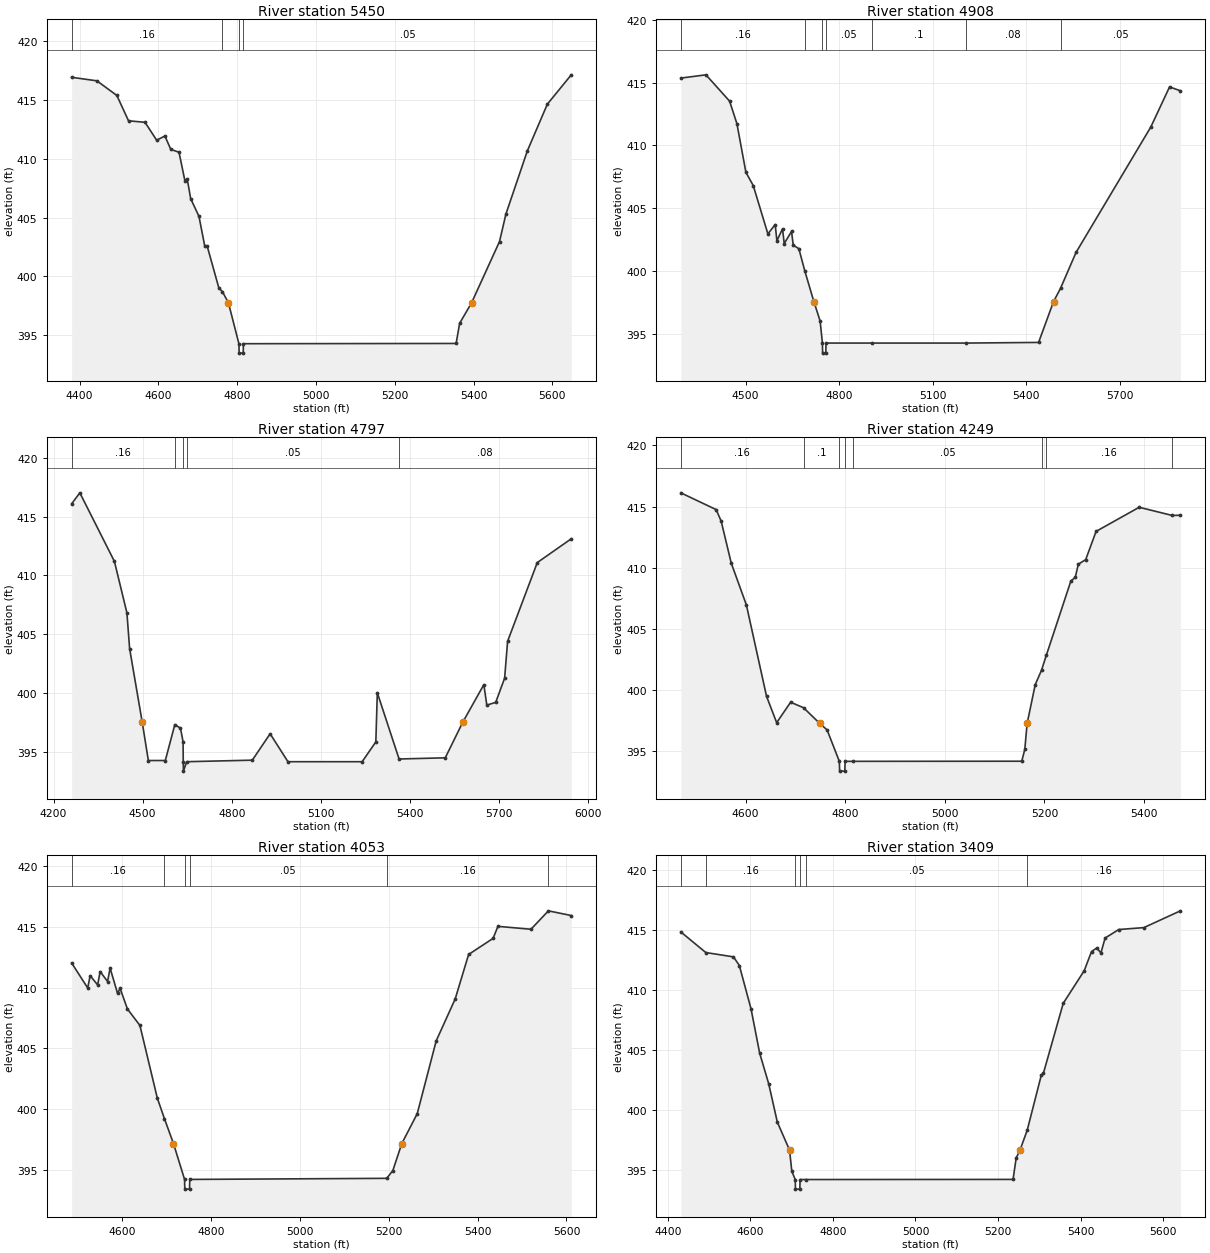
Type RM Length L Ch R = 1,5450,542,542,542
BEGIN DESCRIPTION:
GLADE BRANCH 8.0
END DESCRIPTION:
XS GIS Cut Line= 3
      2905325.01      7016075.01      2904825.00      7015725.00
      2904174.99      7015625.00
#Sta/Elev= 30
  4379.8  416.90  4443.9  416.60  4494.5  415.36  4524.1  413.21  4566.0  413.08
  4595.6  411.56  4616.5  411.92  4631.4  410.78  4652.3  410.54  4667.1  408.14
  4673.2  408.26  4681.9  406.60  4702.9  405.10  4717.7  402.56  4723.8  402.57
  4753.4  399.02  4762.4  398.71  4777.7  397.76  4804.3  394.29  4804.9  393.49
  4815.2  393.49  4815.8  394.29  5355.6  394.31  5364.5  396.02  5394.8  397.76
  5465.7  402.96  5482.1  405.31  5536.5  410.67  5587.1  414.62  5647.8  417.11
#Mann=4,-1,0
  4379.8    0.16       0  4762.4    0.05       0  4804.3   0.033       0
  4815.8    0.05       0
Bank Sta=4777.7,5394.8
Exp/Cntr=0.3,0.1

Type RM Length L Ch R = 1,4908,111,111,111
BEGIN DESCRIPTION:
Mapping XS 83827eee
END DESCRIPTION:
XS GIS Cut Line= 3
      2905685.28      7015511.40      2905042.95      7015233.64
      2904140.13      7015268.36
#Sta/Elev= 30
  4292.0  415.35  4372.6  415.61  4448.5  413.52  4472.0  411.73  4500.9  407.86
  4524.4  406.81  4571.4  402.97  4594.9  403.71  4600.3  402.42  4618.4  403.37
  4623.8  402.20  4647.3  403.16  4652.8  402.07  4670.8  401.79  4689.6  400.05
  4719.0  397.58  4739.0  396.05  4746.4  394.29  4747.0  393.49  4757.3  393.49
  4757.9  394.29  4906.5  394.29  5207.2  394.29  5440.1  394.34  5488.0  397.58
  5510.5  398.64  5560.2  401.49  5800.4  411.47  5860.4  414.65  5895.3  414.34
#Mann=7,-1,0
  4292.0    0.16       0  4689.6    0.05       0  4746.4    0.07       0
  4757.9    0.05       0  4906.5     0.1       0  5207.2    0.08       0
  5510.5    0.05       0
Bank Sta=4719,5488
Exp/Cntr=0.3,0.1

Type RM Length L Ch R = 1,4797,548,548,548
BEGIN DESCRIPTION:
Mapping XS 3236d30c
END DESCRIPTION:
XS GIS Cut Line= 4
      2905680.99      7015468.04      2905468.30      7015146.83
      2905173.16      7015155.51      2904170.55      7015168.53
#Sta/Elev= 30
  4260.8  416.08  4288.4  417.01  4404.9  411.19  4447.0  406.82  4456.1  403.79
  4498.6  397.54  4519.2  394.29  4576.4  394.29  4608.4  397.34  4627.5  397.03
  4636.2  395.88  4636.8  394.19  4637.4  393.39  4648.4  394.19  4869.4  394.32
  4929.5  396.56  4989.5  394.19  5239.5  394.19  5285.6  395.87  5290.6  400.04
  5363.9  394.42  5519.5  394.52  5578.4  397.54  5649.5  400.73  5659.5  398.99
  5689.5  399.23  5719.5  401.28  5729.5  404.41  5829.5  411.09  5944.0  413.11
#Mann=5,-1,0
  4260.8    0.16       0  4608.4    0.05       0  4636.8   0.033       0
  4648.4    0.05       0  5363.9    0.08       0
Bank Sta=4498.6,5578.4
Exp/Cntr=0.3,0.1

Type RM Length L Ch R = 1,4249,196,196,196
BEGIN DESCRIPTION:
GLADE BRANCH 7.0
END DESCRIPTION:
XS GIS Cut Line= 3
      2905675.00      7015424.99      2905591.83      7014901.56
      2905203.50      7014631.67
#Sta/Elev= 30
  4470.0  416.13  4540.9  414.76  4551.0  413.82  4571.2  410.39  4601.6  406.97
  4642.1  399.50  4662.4  397.35  4690.4  399.02  4716.4  398.57  4748.8  397.29
  4763.6  396.76  4788.2  394.19  4788.8  393.39  4799.2  393.39  4799.8  394.19
  4815.8  394.19  5154.4  394.20  5160.5  395.17  5165.2  397.29  5181.4  400.45
  5194.1  401.64  5203.6  402.84  5253.0  408.93  5261.8  409.22  5267.9  410.30
  5282.7  410.67  5303.6  412.98  5390.1  414.95  5456.5  414.28  5472.9  414.30
#Mann=8,-1,0
  4470.0    0.16       0  4716.4     0.1       0  4788.2   0.033       0
  4799.8     0.1       0  4815.8    0.05       0  5194.1    0.12       0
  5203.6    0.16       0  5456.5    0.12       0
Bank Sta=4748.8,5165.2
Exp/Cntr=0.3,0.1

Type RM Length L Ch R = 1,4053,644,644,644
BEGIN DESCRIPTION:
GLADE BRANCH 6.0
END DESCRIPTION:
XS GIS Cut Line= 3
      2906210.43      7015017.08      2905725.00      7014775.00
      2905180.66      7014569.72
#Sta/Elev= 30
  4486.6  412.04  4522.7  409.98  4528.3  410.99  4545.1  410.23  4550.7  411.33
  4567.5  410.51  4573.1  411.62  4589.9  409.53  4595.5  409.95  4612.2  408.24
  4640.2  406.89  4679.4  400.89  4695.4  399.20  4715.7  397.15  4740.7  394.19
  4741.2  393.39  4751.8  393.39  4752.4  394.19  5195.6  394.28  5209.3  394.92
  5229.5  397.15  5264.2  399.61  5306.9  405.62  5349.6  409.07  5379.8  412.74
  5434.9  414.07  5445.8  415.06  5520.1  414.82  5559.4  416.34  5610.8  415.95
#Mann=6,-1,0
  4486.6    0.16       0  4695.4    0.05       0  4740.7   0.033       0
  4752.4    0.05       0  5195.6    0.16       0  5559.4    0.12       0
Bank Sta=4715.7,5229.5
Exp/Cntr=0.3,0.1

Type RM Length L Ch R = 1,3409,687,687,687
BEGIN DESCRIPTION:
GLADE BRANCH 5.0
END DESCRIPTION:
XS GIS Cut Line= 3
      2906375.03      7014575.02      2905925.00      7014175.00
      2905324.99      7014275.00
#Sta/Elev= 30
  4431.5  414.84  4492.1  413.12  4559.1  412.76  4573.3  412.04  4601.7  408.41
  4622.6  404.72  4644.4  402.18  4665.3  398.98  4694.9  396.65  4700.4  394.88
  4708.7  394.19  4709.3  393.39  4719.9  393.39  4720.4  394.19  4734.6  394.19
  5236.4  394.20  5244.0  395.99  5253.3  396.65  5270.6  398.29  5304.8  402.89
  5309.9  403.05  5358.0  408.89  5408.7  411.60  5426.5  413.20  5439.1  413.50
  5449.3  413.09  5459.4  414.33  5492.4  415.04  5553.2  415.20  5641.9  416.60
#Mann=6,-1,0
  4431.5    0.08       0  4492.1    0.16       0  4708.7   0.033       0
  4720.4    0.16       0  4734.6    0.05       0  5270.6    0.16       0
Bank Sta=4694.9,5253.3
Exp/Cntr=0.3,0.1

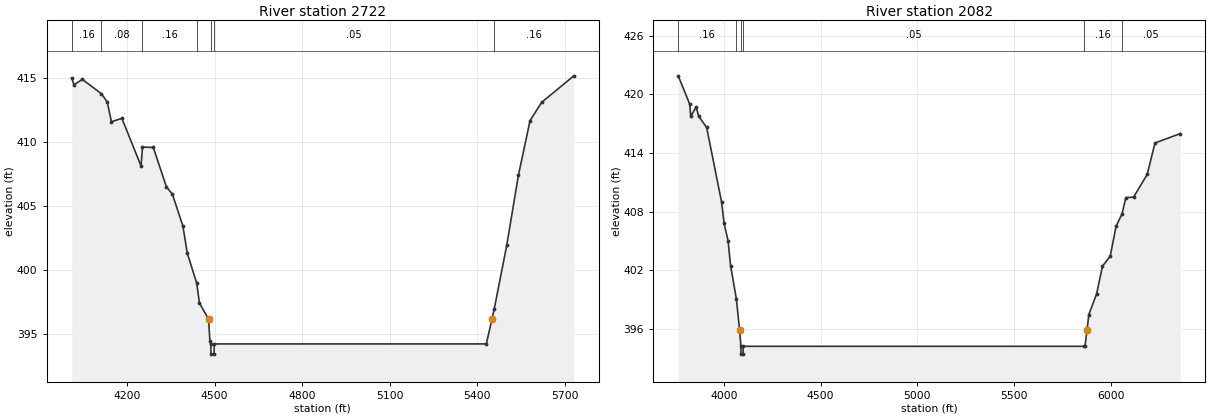
Type RM Length L Ch R = 1,2722,640,640,640
BEGIN DESCRIPTION:
GLADE BRANCH 4.0
END DESCRIPTION:
XS GIS Cut Line= 3
      2906625.00      7014325.00      2906075.00      7013525.00
      2905325.02      7013525.00
#Sta/Elev= 30
  4010.4  415.01  4017.8  414.49  4046.8  414.91  4111.8  413.79  4131.8  413.15
  4146.4  411.59  4182.2  411.86  4247.9  408.12  4252.8  409.61  4289.8  409.58
  4334.5  406.51  4355.4  405.91  4391.3  403.42  4406.2  401.31  4438.4  398.96
  4448.1  397.39  4479.2  396.13  4484.0  394.41  4486.9  394.19  4487.5  393.39
  4498.1  393.39  4498.7  394.19  5431.2  394.19  5450.5  396.13  5458.2  396.91
  5501.2  401.91  5541.2  407.40  5581.2  411.69  5621.2  413.12  5731.2  415.19
#Mann=7,-1,0
  4010.4    0.16       0  4111.8    0.08       0  4252.8    0.16       0
  4438.4    0.05       0  4486.9   0.033       0  4498.7    0.05       0
  5458.2    0.16       0
Bank Sta=4479.2,5450.5
Exp/Cntr=0.3,0.1

Type RM Length L Ch R = 1,2082,659,659,659
BEGIN DESCRIPTION:
GLADE BRANCH 3.0
END DESCRIPTION:
XS GIS Cut Line= 3
      2907475.04      7012624.99      2906275.00      7012925.00
      2904924.98      7013075.00
#Sta/Elev= 30
  3764.2  421.91  3823.5  419.01  3828.7  417.77  3857.0  418.71  3869.9  417.76
  3911.1  416.62  3988.4  408.96  4001.3  406.78  4021.9  405.00  4034.8  402.45
  4064.8  399.04  4081.3  395.86  4088.2  394.19  4088.7  393.39  4099.4  393.39
  4100.0  394.19  5859.4  394.19  5866.5  394.19  5877.5  395.86  5886.6  397.44
  5926.8  399.56  5957.0  402.39  5997.3  403.44  6027.4  406.49  6058.6  407.78
  6077.8  409.43  6118.0  409.48  6188.4  411.81  6228.7  415.03  6359.5  415.99
#Mann=6,-1,0
  3764.2    0.16       0  4064.8    0.05       0  4088.2   0.033       0
  4100.0    0.05       0  5859.4    0.16       0  6058.6    0.05       0
Bank Sta=4081.3,5877.5
Exp/Cntr=0.3,0.1