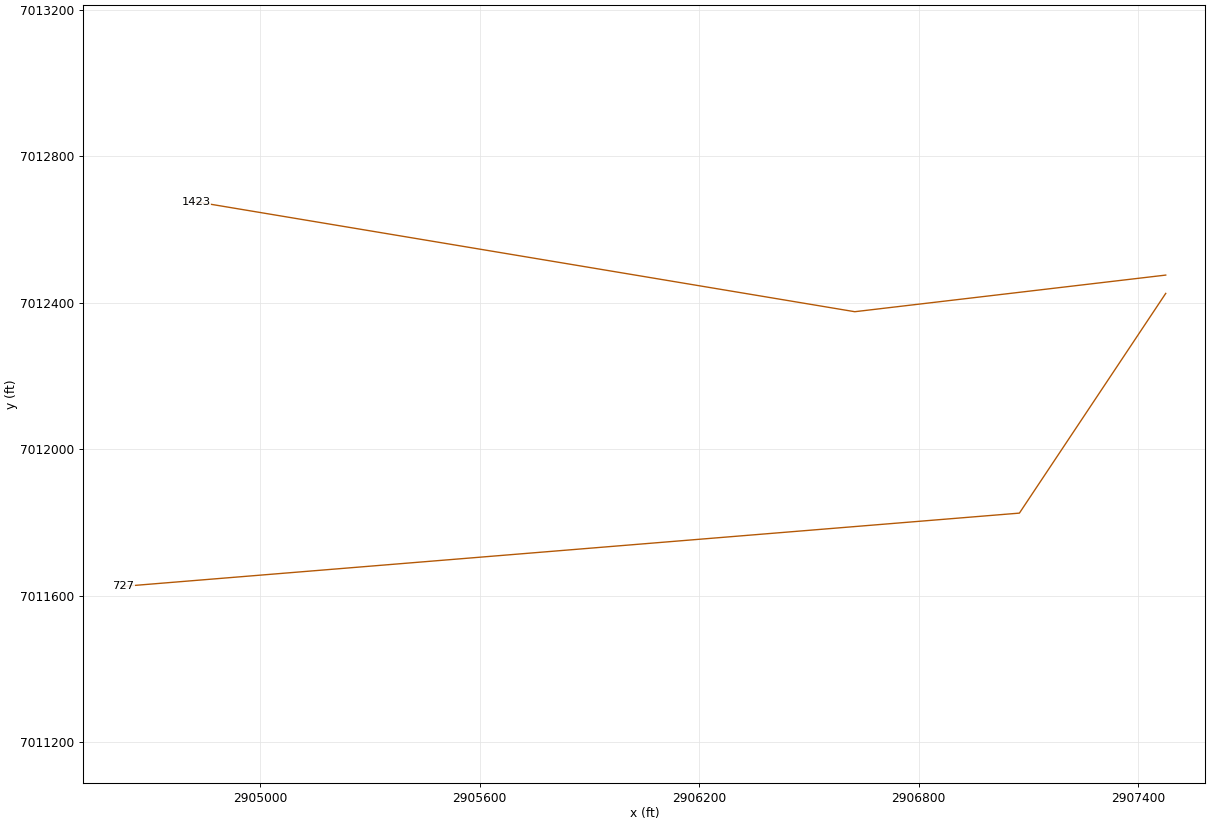
HEC-RAS study GLADE BRANCH.prj: GLADE BRANCH Base Level Engineering

--- GLADE BRANCH.g01 (geometry) --- (continued)

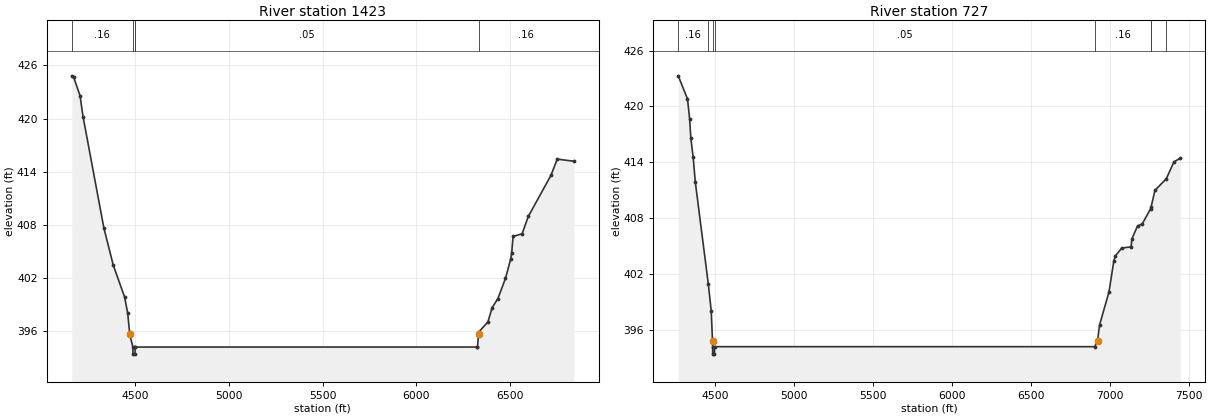
Type RM Length L Ch R = 1,1423,696,696,696
BEGIN DESCRIPTION:
GLADE BRANCH 2.0
END DESCRIPTION:
XS GIS Cut Line= 3
      2907474.98      7012475.00      2906625.00      7012375.00
      2904824.97      7012675.00
#Sta/Elev= 30
  4160.3  424.83  4170.4  424.68  4204.3  422.59  4220.7  420.20  4331.5  407.66
  4381.8  403.44  4442.2  399.85  4458.6  398.06  4470.1  395.61  4486.6  394.19
  4487.1  393.39  4498.0  393.39  4498.5  394.19  4499.9  394.19  6321.4  394.19
  6326.5  394.23  6332.0  395.61  6333.1  395.89  6382.2  397.02  6405.0  398.65
  6435.5  399.67  6476.0  401.95  6503.9  404.14  6509.0  404.79  6516.6  406.69
  6564.7  406.98  6597.7  408.94  6719.3  413.61  6752.3  415.42  6841.0  415.18
#Mann=5,-1,0
  4160.3    0.16       0  4486.6   0.033       0  4498.5    0.16       0
  4499.9    0.05       0  6333.1    0.16       0
Bank Sta=4470.1,6332
Exp/Cntr=0.3,0.1

Type RM Length L Ch R = 1,727,0,0,0
BEGIN DESCRIPTION:
GLADE BRANCH 1.0
END DESCRIPTION:
XS GIS Cut Line= 3
      2907475.00      7012425.00      2907075.00      7011825.00
      2904624.96      7011625.00
#Sta/Elev= 30
  4268.2  423.29  4326.8  420.81  4340.3  418.69  4347.8  416.63  4362.8  414.52
  4376.4  411.86  4458.3  400.97  4477.0  398.05  4485.2  394.79  4486.0  394.19
  4486.5  393.39  4497.5  393.39  4498.0  394.19  6905.6  394.19  6923.2  394.79
  6935.8  396.50  6996.0  400.08  7026.1  403.36  7036.1  403.94  7076.2  404.78
  7135.8  404.92  7140.8  405.77  7176.6  407.16  7206.7  407.38  7259.8  409.03
  7262.2  409.17  7286.9  410.98  7358.9  412.24  7407.3  414.05  7447.5  414.44
#Mann=8,-1,0
  4268.2    0.16       0  4458.3    0.05       0  4486.0   0.033       0
  4498.0    0.05       0  6905.6    0.16       0  7259.8    0.08       0
  7262.2    0.05       0  7358.9    0.16       0
Bank Sta=4485.2,6923.2
Exp/Cntr=0.3,0.1

Chan Stop Cuts=-1