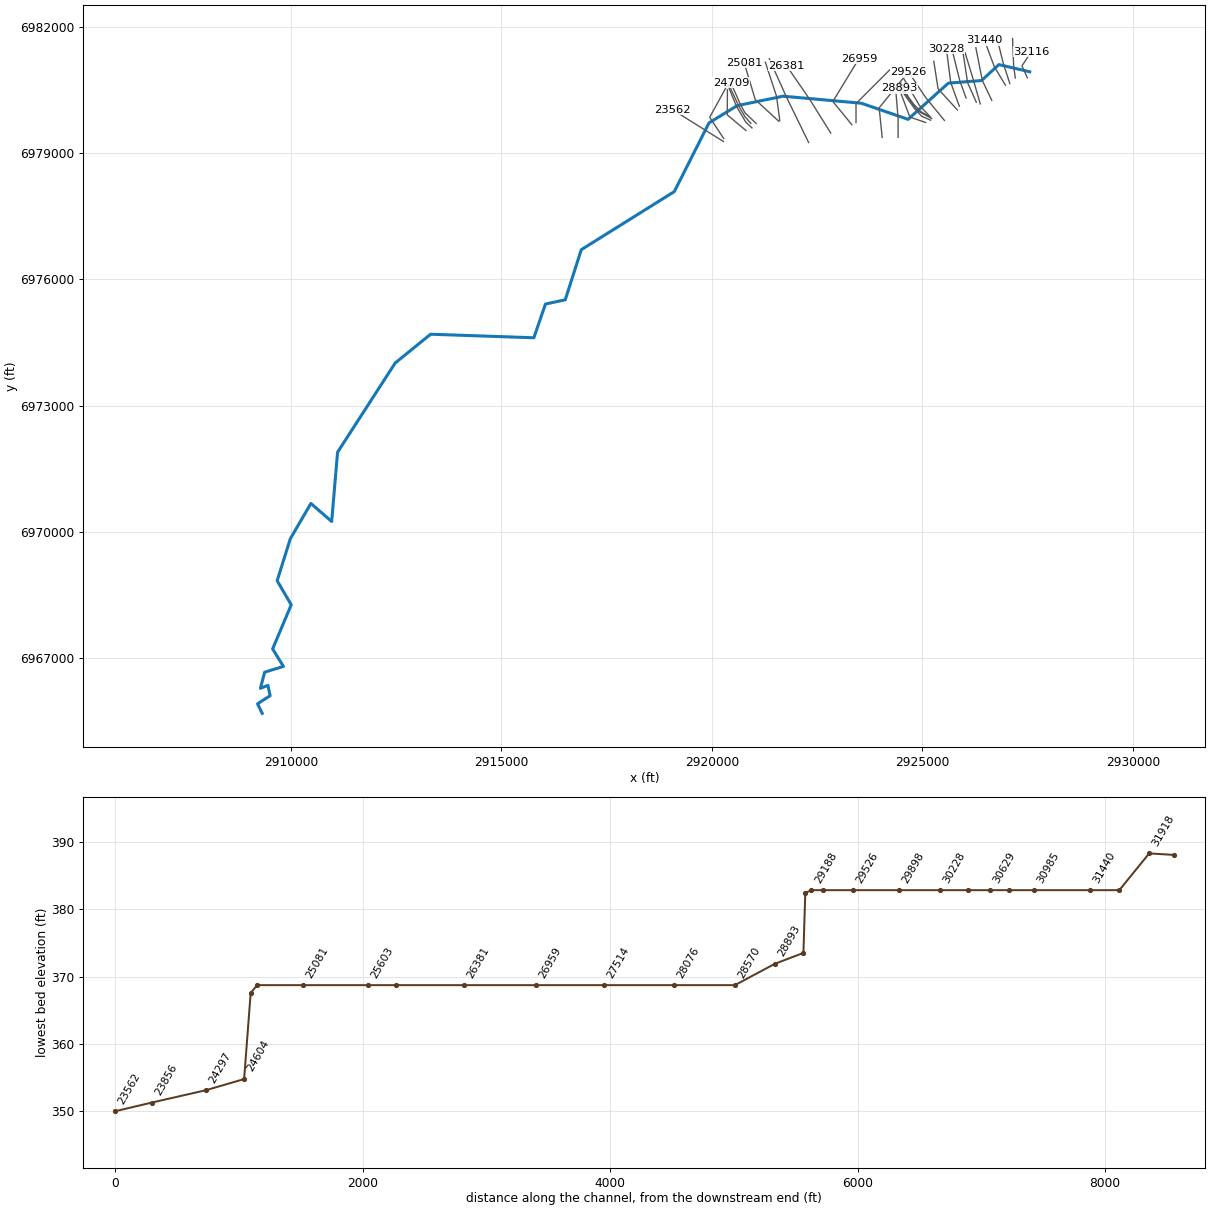
--- GLADE CREEK.prj (project) ---

Proj Title=GLADE CREEK Base Level Engineering
Current Plan=p01
Default Exp/Contr=0.3,0.1
English Units
Geom File=g01
Flow File=f01
Plan File=p01
Y Axis Title=Elevation
X Axis Title(PF)=Main Channel Distance
X Axis Title(XS)=Station
BEGIN DESCRIPTION:
GLADE CREEK
END DESCRIPTION:
DSS Export Rating Curves= 0
DSS Export Rating Curve Sorted= 0
DSS Export Volume Flow Curves= 0
DXF OffsetX= 0
DXF OffsetY= 0
DXF ScaleX= 1
DXF ScaleY= 10

--- GLADE CREEK.p01 (plan) ---

Plan Title=Multiple Run
Short Identifier=Multiple
Geom File=g01
Flow File=f01
Subcritical Flow
K Sum by GR= 0
Std Step Tol= 0.01
Critical Tol= 0.01
Num of Std Step Trials= 20
Max Error Tol= 0.3
Flow Tol Ratio= 0.001
Split Flow NTrial= 30
Split Flow Tol= 0.02
Split Flow Ratio= 0.02
Log Output Level= 0
Friction Slope Method= 1
Unsteady Friction Slope Method= 2
Unsteady Bridges Friction Slope Method= 1
Parabolic Critical Depth
Global Vel Dist=  1 , 1 , 1
Global Log Level= 0
CheckData=True
Encroach Param= -1, 0, 0, 0
BEGIN DESCRIPTION:
Multiple Run
END DESCRIPTION:

--- GLADE CREEK.f01 (steady flow) ---

Flow Title=Multiple
Program Version=5.07
Number of Profiles= 7
Profile Names=10-year,25-year,50-year,1pct_min,100-year,1pct_plu,500-year
River Rch & RM=GLADE CREEK,Reach-1         ,32116
     569     767     929     561    1119    2232    1622
River Rch & RM=GLADE CREEK,Reach-1         ,28570
    1150    1608    1997    1231    2456    4901    3725
River Rch & RM=GLADE CREEK,Reach-1         ,26381
    1840    2618    3288    2046    4082    8144    6308
River Rch & RM=GLADE CREEK,Reach-1         ,23562
    2460    3537    4473    2799    5586   11145    8735
River Rch & RM=GLADE CREEK,Reach-1         ,19440
    2512    3606    4554    2846    5679   11332    8857
River Rch & RM=GLADE CREEK,Reach-1         ,15956
    2601    3727    4702    2935    5856   11684    9105
River Rch & RM=GLADE CREEK,Reach-1         ,10815
    3064    4409    5578    3489    6961   13888   10868
River Rch & RM=GLADE CREEK,Reach-1         ,6667
    3352    4825    6106    3818    7618   15199   11889
Boundary for River Rch & Prof#=GLADE CREEK,Reach-1         , 1
Up Type= 0
Dn Type= 3
Dn Slope=0.00153
Boundary for River Rch & Prof#=GLADE CREEK,Reach-1         , 2
Up Type= 0
Dn Type= 3
Dn Slope=0.00153
Boundary for River Rch & Prof#=GLADE CREEK,Reach-1         , 3
Up Type= 0
Dn Type= 3
Dn Slope=0.00153
Boundary for River Rch & Prof#=GLADE CREEK,Reach-1         , 4
Up Type= 0
Dn Type= 3
Dn Slope=0.00153
Boundary for River Rch & Prof#=GLADE CREEK,Reach-1         , 5
Up Type= 0
Dn Type= 3
Dn Slope=0.00153
Boundary for River Rch & Prof#=GLADE CREEK,Reach-1         , 6
Up Type= 0
Dn Type= 3
Dn Slope=0.00153
Boundary for River Rch & Prof#=GLADE CREEK,Reach-1         , 7
Up Type= 0
Dn Type= 3
Dn Slope=0.00153
DSS Import GetInterval= 0
DSS Import GetPeak= 0
DSS Import FillOption= 0

--- GLADE CREEK.g01 (geometry) ---

Geom Title=Existing Conditions
Program Version=5.07

River Reach=GLADE CREEK     ,Reach-1
Reach XY= 30
      2927550.52      6980930.17      2926819.29      6981101.39
       2926406.1      6980722.92       2925617.9      6980660.42
      2924660.77      6979801.14      2923551.49      6980183.86
      2921693.86      6980350.52      2920604.56      6980127.15
      2919933.82      6979717.24      2919109.42      6978084.99
      2916899.56      6976704.72      2916517.64      6975513.57
      2916048.89      6975414.61      2915772.85      6974612.53
      2913320.59      6974696.71      2912478.83      6974012.93
      2911110.16      6971893.55      2910970.51      6970247.97
      2910477.06      6970677.15      2909988.25       6969839.6
       2909675.4      6968841.97       2910009.6       6968269.6
       2909567.6      6967220.65      2909825.43      6966806.73
      2909378.79      6966669.11      2909277.41      6966286.16
      2909456.64      6966355.11       2909508.3      6966109.78
       2909209.4      6965918.45      2909320.56      6965690.65

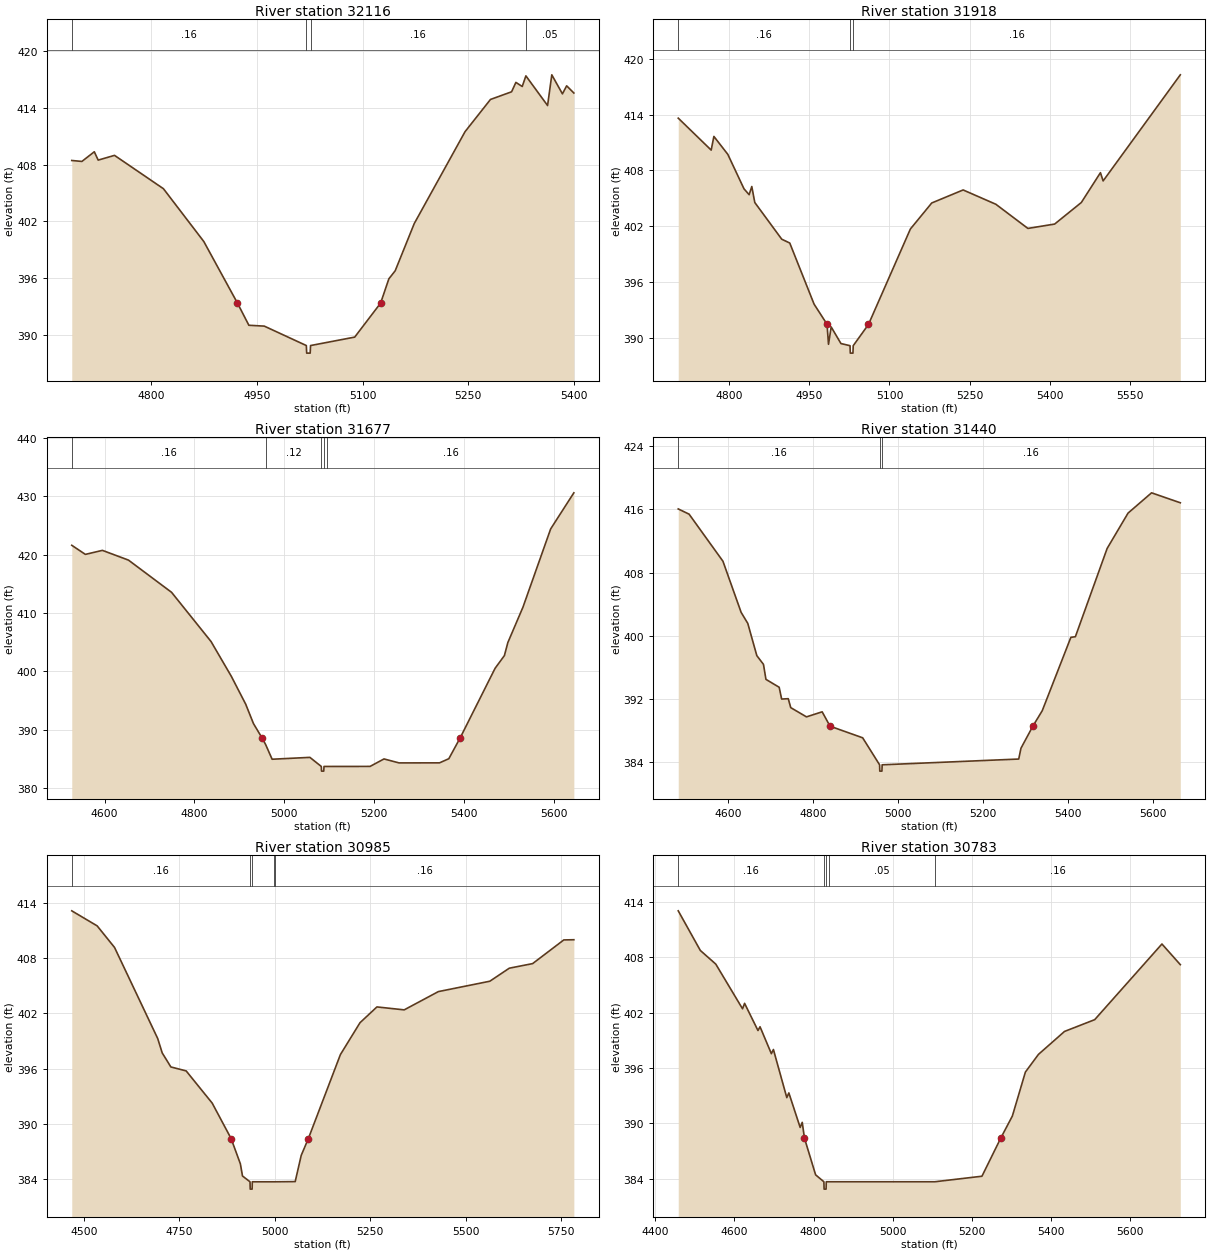
Type RM Length L Ch R = 1 ,32116   ,198,198,198
BEGIN DESCRIPTION:
GLADE CREEK 44.0
END DESCRIPTION:
XS GIS Cut Line= 3
      2927495.27      6980785.54      2927367.03      6981071.18
      2927588.61      6981404.08
#Sta/Elev= 30
  4686.9  408.43  4701.3  408.33  4718.9  409.35  4724.4  408.47  4747.6  408.97
  4817.1  405.45  4874.4  399.88  4922.2  393.38  4938.4  391.04  4960.3  390.95
    5020   388.9  5020.5   388.1  5025.5   388.1    5026   388.9  5088.7  389.79
  5125.5  393.38  5137.2  395.94  5146.2  396.79  5173.3  401.78  5245.4  411.47
  5281.5  414.87  5311.5  415.68  5317.6  416.67  5326.6  416.24  5331.8  417.36
  5362.6  414.23  5368.6  417.47  5383.7  415.46  5389.7  416.31  5399.9  415.55
#Mann= 4 ,-1 , 0
  4686.9     .16       0    5020     .07       0    5026     .16       0
  5331.8     .05       0
Bank Sta=4922.2,5125.5
XS Rating Curve= 0 ,0
Exp/Cntr=0.3,0.1

Type RM Length L Ch R = 1 ,31918   ,241,241,241
BEGIN DESCRIPTION:
Mapping XS 14079af8
END DESCRIPTION:
XS GIS Cut Line= 3
      2927209.23      6980782.99      2927170.18      6981058.99
      2927144.14      6981720.23
#Sta/Elev= 30
  4704.3  413.61    4766  410.17  4771.1  411.64  4797.2  409.71  4827.5     406
  4837.1  405.37  4842.1  406.25  4847.7  404.53  4898.2  400.58  4913.2  400.17
  4958.8  393.59    4983  391.43  4985.8  389.27  4990.8  391.14  5009.1  389.35
  5026.1  389.12  5026.6  388.32  5031.6  388.32  5032.1  389.12  5060.7  391.41
  5139.2  401.68  5179.2  404.48    5238  405.88  5299.3  404.34  5359.3  401.74
  5409.4  402.21  5459.4  404.53  5495.2  407.74  5500.2  406.85  5644.8  418.27
#Mann= 3 ,-1 , 0
  4704.3     .16       0  5026.1     .07       0  5032.1     .16       0
Bank Sta=4983,5060.7
XS Rating Curve= 0 ,0
Exp/Cntr=0.3,0.1

Type RM Length L Ch R = 1 ,31677   ,237,237,237
BEGIN DESCRIPTION:
GLADE CREEK 43.0
END DESCRIPTION:
XS GIS Cut Line= 3
      2927079.03      6980650.15        2926925.        6981125.
      2926774.99      6981725.03
#Sta/Elev= 30
  4527.1   421.6  4557.4  420.04  4595.3  420.73  4653.3  419.06  4749.3  413.53
  4837.1   405.1  4882.4  399.11  4914.4  394.33  4931.7     391  4950.4  388.59
  4958.8   387.4  4973.1   384.9  5057.2  385.22  5082.6  383.66  5083.1  382.86
  5088.1  382.86  5088.6  383.66  5095.8  383.66  5191.2  383.67  5222.2  384.95
  5255.7  384.27  5345.8  384.28  5366.5  384.99  5391.9  388.59  5469.5   400.5
  5490.2  402.68  5497.9  404.92  5531.4  410.96  5593.2  424.41  5644.8   430.6
#Mann= 5 ,-1 , 0
  4527.1     .16       0  4958.8     .12       0  5082.6     .07       0
  5088.6     .12       0  5095.8     .16       0
Bank Sta=4950.4,5391.9
XS Rating Curve= 0 ,0
Exp/Cntr=0.3,0.1

Type RM Length L Ch R = 1 ,31440   ,455,455,455
BEGIN DESCRIPTION:
GLADE CREEK 42.0
END DESCRIPTION:
XS GIS Cut Line= 3
      2926974.85      6980611.09      2926709.21      6981053.81
      2926477.47      6981676.17
#Sta/Elev= 30
  4483.7  416.06  4509.2   415.4  4588.8  409.44  4631.6  402.96  4647.2  401.57
  4668.5  397.48  4684.1  396.38  4689.9  394.48    4721  393.48  4726.8  391.99
  4742.4  392.03  4748.2   390.9  4785.2  389.73  4822.1  390.37  4840.6  388.55
  4917.3  387.08  4957.1  383.66  4957.6  382.86  4962.6  382.86  4963.1  383.66
  5284.2  384.39  5289.5  385.76  5317.4  388.55  5339.5  390.51  5406.8   399.8
  5417.4  399.88  5492.1  411.06  5541.2  415.53  5596.5   418.1  5664.1  416.84
#Mann= 3 ,-1 , 0
  4483.7     .16       0  4957.1     .07       0  4963.1     .16       0
Bank Sta=4840.6,5317.4
XS Rating Curve= 0 ,0
Exp/Cntr=0.3,0.1

Type RM Length L Ch R = 1 ,30985   ,202,202,202
BEGIN DESCRIPTION:
GLADE CREEK 41.0
END DESCRIPTION:
XS GIS Cut Line= 3
      2926649.36      6980251.67        2926425.        6980725.
      2926271.91      6981500.83
#Sta/Elev= 30
  4468.2  413.18  4534.7  411.54  4580.2  409.19  4693.2  399.27    4705   397.7
  4727.7  396.17  4767.7  395.74  4835.9  392.23  4885.4  388.37  4909.7  385.61
  4915.2  384.29  4934.9  383.66  4935.4  382.86  4940.4  382.86  4940.9  383.66
    4999  383.66  5001.2  383.66  5053.2  383.68    5069  386.54  5087.7  388.37
  5171.6  397.52  5222.9  400.99  5267.2  402.71  5338.6  402.39  5428.1  404.38
  5562.8  405.51  5613.8  406.93  5674.9  407.43  5756.5  410.01  5782.8  410.03
#Mann= 5 ,-1 , 0
  4468.2     .16       0  4934.9    .035       0  4940.9     .16       0
    4999     .05       0  5001.2     .16       0
Bank Sta=4885.4,5087.7
XS Rating Curve= 0 ,0
Exp/Cntr=0.3,0.1

Type RM Length L Ch R = 1 ,30783   ,154,154,154
BEGIN DESCRIPTION:
Mapping XS ddd37bd7
END DESCRIPTION:
XS GIS Cut Line= 3
       2926375.9      6980168.39      2926224.87      6980697.01
      2926016.54      6981384.47
#Sta/Elev= 30
    4458  413.06  4513.8  408.76  4552.8  407.28  4620.4  402.43  4625.6  403.02
  4659.4  400.07  4664.6  400.48  4693.2  397.56  4698.4  398.01  4732.2  392.79
  4737.4   393.3    4766  389.55  4771.2  390.11  4776.8  388.39    4805  384.41
  4825.9  383.66  4826.4  382.86  4831.4  382.86  4831.9  383.66    4839  383.66
  5106.1  383.66  5225.1  384.26  5272.4  388.38  5301.9  390.79  5334.8  395.56
  5367.8  397.48  5433.6  399.97  5509.9  401.25  5679.7  409.46  5726.1  407.22
#Mann= 5 ,-1 , 0
    4458     .16       0  4825.9    .033       0  4831.9     .16       0
    4839     .05       0  5106.1     .16       0
Bank Sta=4776.8,5272.4
XS Rating Curve= 0 ,0
Exp/Cntr=0.3,0.1

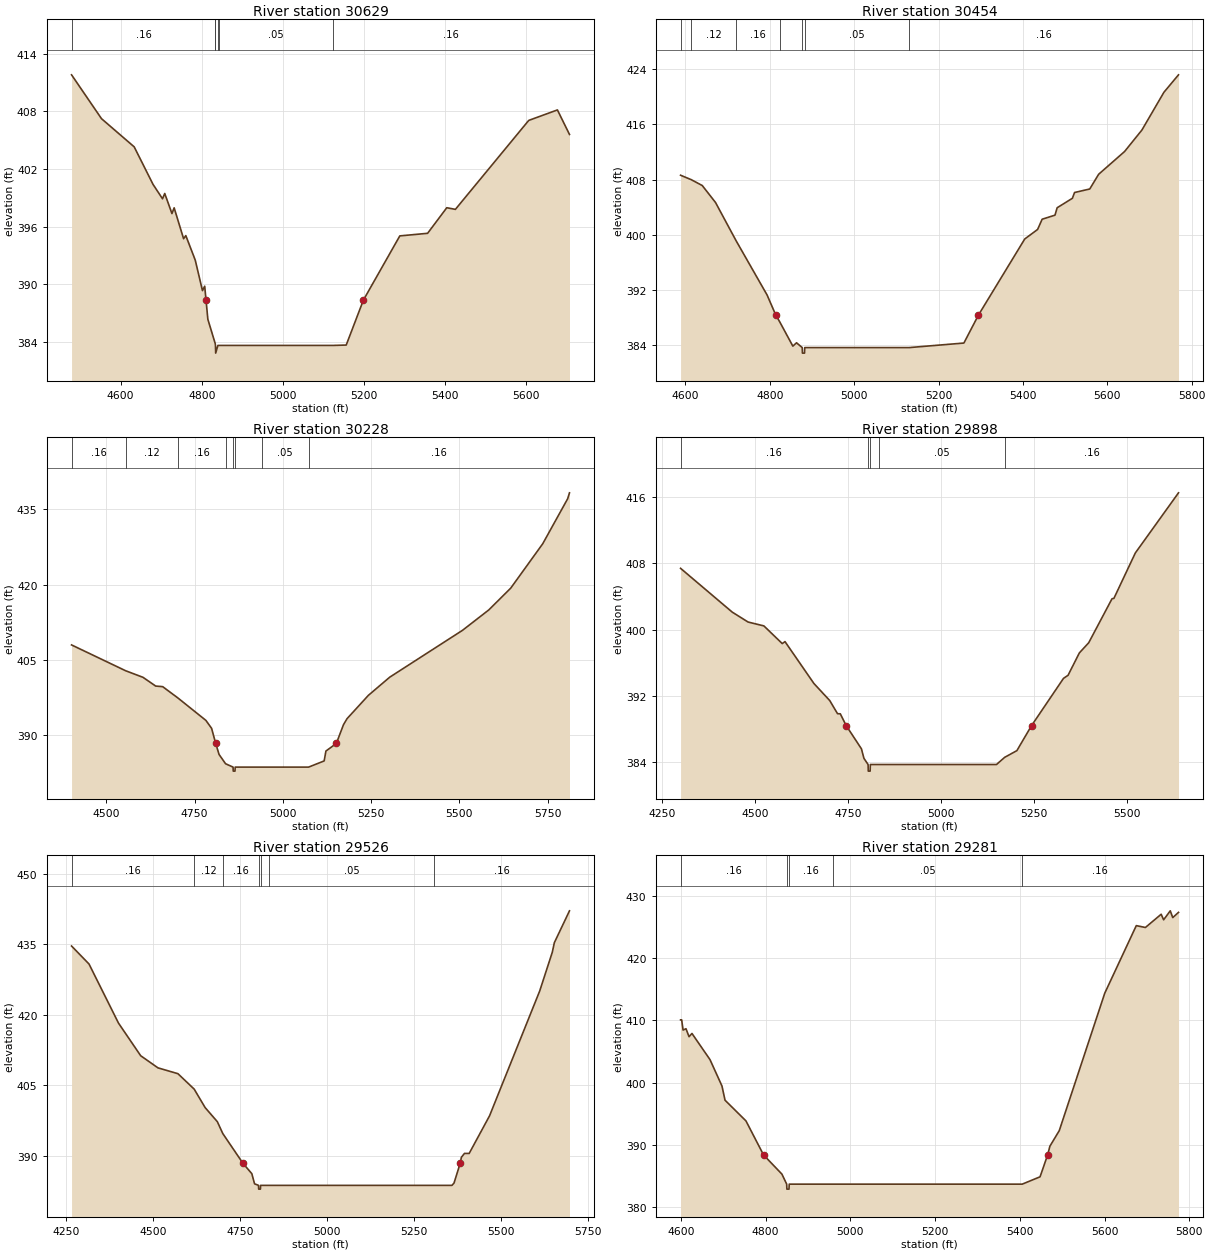
Type RM Length L Ch R = 1 ,30629   ,175,175,175
BEGIN DESCRIPTION:
GLADE CREEK 40.0
END DESCRIPTION:
XS GIS Cut Line= 3
      2926282.14      6980207.47        2926075.        6980675.
      2925967.06      6981384.47
#Sta/Elev= 30
  4478.8   411.8  4552.7  407.24  4633.4  404.31    4680   400.4  4703.3  398.91
  4708.8  399.46  4726.6  397.37    4732  397.97  4755.3  394.76  4760.8  395.08
  4784.1  392.53  4801.9  389.36  4807.4  389.82  4810.7  388.38  4815.2  386.38
  4833.4  383.85    4834  383.66  4834.5  382.86    4840  383.66  4843.2  383.66
    5124  383.66  5156.7   383.7  5199.2  388.38    5289  395.05  5357.6  395.32
  5404.9  397.98  5426.2  397.81  5607.2  407.06    5678  408.15  5707.8   405.6
#Mann= 6 ,-1 , 0
  4478.8     .16       0  4833.4     .07       0    4834    .033       0
    4840     .07       0  4843.2     .05       0    5124     .16       0
Bank Sta=4810.7,5199.2
XS Rating Curve= 0 ,0
Exp/Cntr=0.3,0.1

Type RM Length L Ch R = 1 ,30454   ,226,226,226
BEGIN DESCRIPTION:
Mapping XS 048c99dc
END DESCRIPTION:
XS GIS Cut Line= 3
      2926039.97      6980306.69      2925890.66      6980716.41
      2925710.11      6981438.61
#Sta/Elev= 30
  4588.4  408.62    4614  407.97  4639.8  407.13  4671.2  404.68  4720.2  399.12
  4793.5  391.28  4814.1  388.38  4823.4   387.4  4854.6  383.87  4863.3  384.36
  4876.8  383.66  4877.3  382.86  4882.3  382.86  4882.8  383.66  5130.1  383.66
  5260.1  384.32  5294.7  388.38  5404.4  399.39  5434.9  400.77  5445.6  402.25
  5476.1  402.84  5481.2  403.91  5517.3  405.28  5522.5  406.12  5558.5  406.63
  5579.6  408.76    5641  412.05  5682.2  415.17  5734.3  420.63  5768.9  423.16
#Mann= 7 ,-1 , 0
  4588.4     .16       0    4614     .12       0  4720.2     .16       0
  4823.4     .05       0  4876.8    .033       0  4882.8     .05       0
  5130.1     .16       0
Bank Sta=4814.1,5294.7
XS Rating Curve= 0 ,0
Exp/Cntr=0.3,0.1

Type RM Length L Ch R = 1 ,30228   ,330,330,330
BEGIN DESCRIPTION:
GLADE CREEK 39.0
END DESCRIPTION:
XS GIS Cut Line= 3
      2925880.24      6980112.26        2925675.        6980675.
      2925571.24      6981480.14
#Sta/Elev= 30
  4401.3  407.99  4554.5  402.85  4603.7  401.54  4639.6   399.8  4659.5  399.68
  4702.6  397.43  4781.8  392.97  4798.1  391.38  4809.7  388.37  4819.3  386.17
  4837.7  384.33  4858.9  383.66  4859.4  382.86  4864.4  382.86  4864.9  383.66
  4940.9  383.66  5072.9  383.66    5117  384.89    5122  386.86  5151.5  388.37
  5171.7   392.1  5181.8   393.3  5242.3  397.95  5302.8  401.57  5509.2  410.91
  5583.6  414.97  5645.6   419.3  5736.3  428.14  5806.9   437.1  5812.1  438.28
#Mann= 8 ,-1 , 0
  4401.3     .16       0  4554.5     .12       0  4702.6     .16       0
  4837.7     .07       0  4858.9    .033       0  4864.9     .07       0
  4940.9     .05       0  5072.9     .16       0
Bank Sta=4809.7,5151.5
XS Rating Curve= 0 ,0
Exp/Cntr=0.3,0.1

Type RM Length L Ch R = 1 ,29898   ,372,372,372
BEGIN DESCRIPTION:
GLADE CREEK 38.0
END DESCRIPTION:
XS GIS Cut Line= 3
      2925831.64      6980025.43        2925375.        6980525.
      2925272.61       6981178.2
#Sta/Elev= 30
    4300  407.41  4438.8  402.11  4481.3  400.91  4523.9  400.44  4573.2   398.3
  4580.6  398.54  4658.3  393.47  4700.9   391.4  4721.8  389.81  4729.2   389.8
  4745.2  388.36    4786  385.56  4792.7  384.41  4803.9  383.66  4804.4  382.86
  4809.4  382.86  4809.9  383.66  4832.3  383.66  5148.9  383.66  5170.9  384.53
  5203.7  385.34    5243  388.36    5329  394.09  5341.2  394.46  5371.6  397.17
  5396.7   398.4  5459.4  403.73  5464.4  403.77    5522  409.27    5638  416.55
#Mann= 5 ,-1 , 0
    4300     .16       0  4803.9    .033       0  4809.9     .16       0
  4832.3     .05       0  5170.9     .16       0
Bank Sta=4745.2,5243
XS Rating Curve= 0 ,0
Exp/Cntr=0.3,0.1

Type RM Length L Ch R = 1 ,29526   ,245,245,245
BEGIN DESCRIPTION:
GLADE CREEK 37.0
END DESCRIPTION:
XS GIS Cut Line= 3
        2925525.        6979775.        2925075.        6980325.
      2924675.02      6980924.97
#Sta/Elev= 30
  4265.9   434.6  4316.1  430.77  4400.8   418.2  4464.7  411.25  4514.3  408.67
  4571.7  407.43  4618.4  404.15  4649.9  400.22  4685.1  397.21  4700.7  394.69
  4758.7  388.36  4784.2  386.15  4792.1  383.99  4803.4  383.66  4803.9  382.86
  4808.9  382.86  4809.4  383.66    4835  383.66  5307.7  383.66  5359.6  383.66
  5365.6  384.15  5383.3  388.36  5386.7  389.63  5395.7  390.46  5409.2  390.46
  5467.8  398.47    5612  425.04  5648.1  433.26  5654.1  435.32  5697.6  442.09
#Mann= 7 ,-1 , 0
  4265.9     .16       0  4618.4     .12       0  4700.7     .16       0
  4803.4    .033       0  4809.4     .16       0    4835     .05       0
  5307.7     .16       0
Bank Sta=4758.7,5383.3
XS Rating Curve= 0 ,0
Exp/Cntr=0.3,0.1

Type RM Length L Ch R = 1 ,29281   ,93,93,93
BEGIN DESCRIPTION:
Mapping XS 5dcd815c
END DESCRIPTION:
XS GIS Cut Line= 3
      2925194.45       6979856.2      2924928.86      6980134.81
      2924530.44      6980817.08
#Sta/Elev= 30
  4599.3  410.08  4601.9  410.08  4605.2  408.44  4612.1  408.65  4619.3  407.37
  4626.2  407.89  4668.7  403.69    4697  399.44  4704.2  397.16  4753.6  393.83
  4795.1  388.36  4838.5  385.27  4849.7  383.66  4850.2  382.86  4855.2  382.86
  4855.7  383.66  4959.2  383.66  5405.5  383.66  5447.6  384.84  5465.5  388.36
  5470.8  389.76  5492.9  392.26  5600.3  414.37  5674.7  425.23  5696.2  424.93
  5733.4  427.06  5739.2  426.17  5754.9  427.61  5760.7  426.52  5774.3  427.36
#Mann= 5 ,-1 , 0
  4599.3     .16       0  4849.7    .033       0  4855.7     .16       0
  4959.2     .05       0  5405.5     .16       0
Bank Sta=4795.1,5465.5
XS Rating Curve= 0 ,0
Exp/Cntr=0.3,0.1

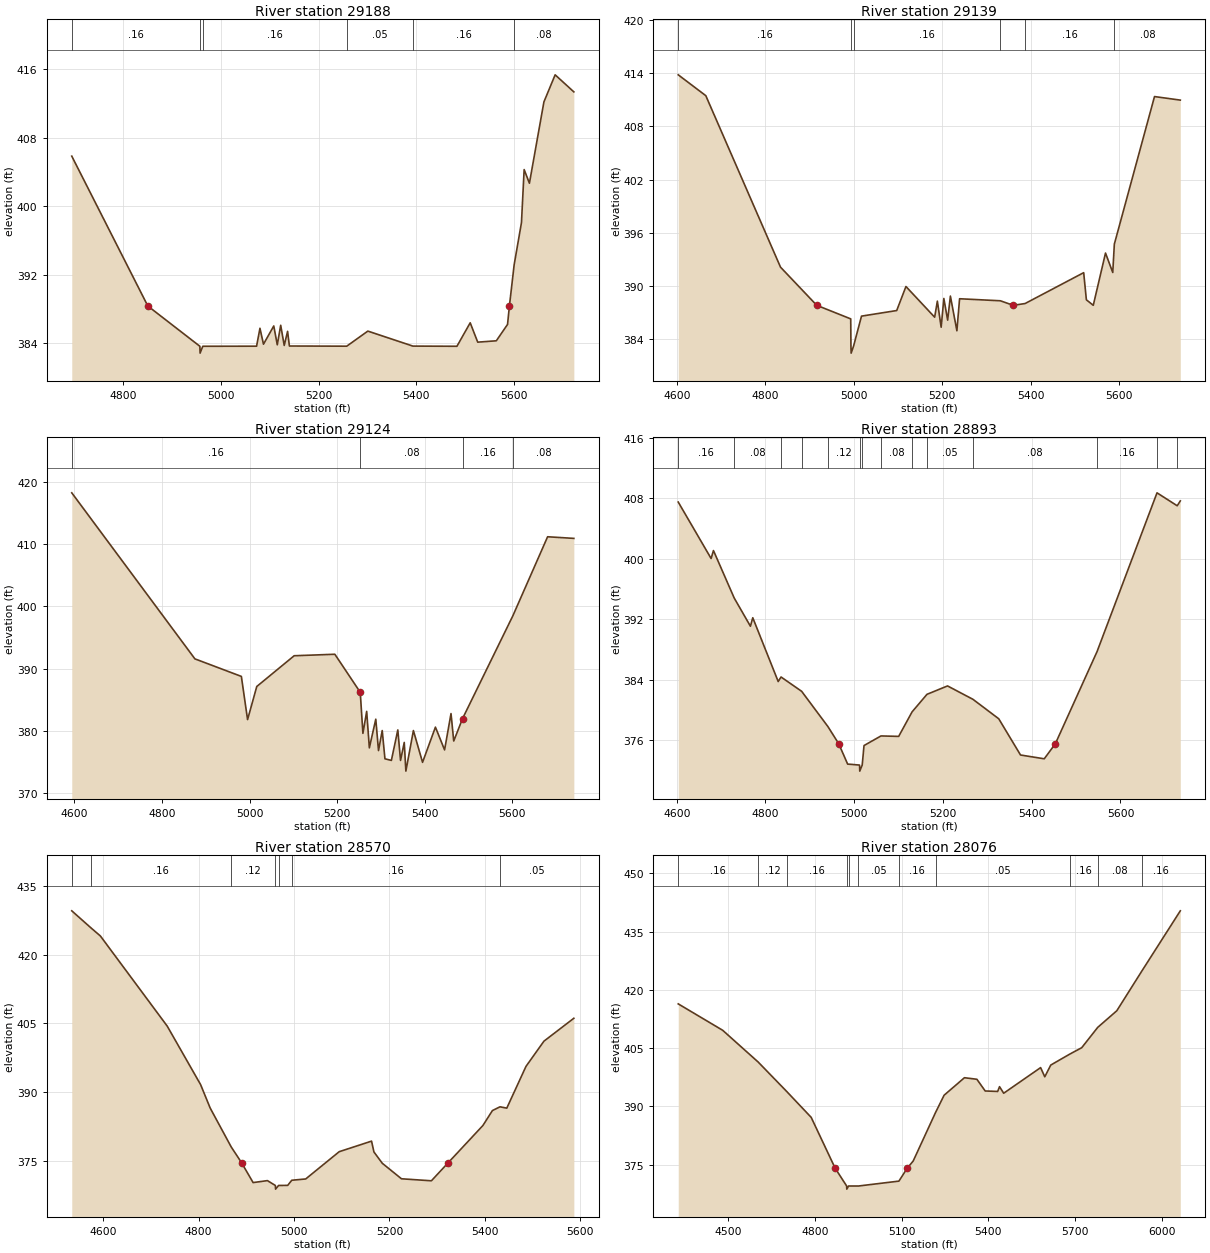
Type RM Length L Ch R = 1 ,29188   ,49,49,49
BEGIN DESCRIPTION:
Mapping XS 1ddc1608
END DESCRIPTION:
XS GIS Cut Line= 6
        2925140.      6979885.15      2924966.36      6979982.82
      2924794.92      6980160.77      2924684.24      6980310.51
      2924567.05      6980501.48      2924495.43      6980657.76
#Sta/Elev= 30
  4694.4  405.85  4850.2  388.36  4956.8  383.66  4957.3  382.86  4962.8  383.66
    5073  383.67  5079.9  385.76  5087.1   383.9  5108.2  386.03  5115.4  383.83
  5122.4  386.11  5129.6  383.76  5136.5   385.4  5140.2  383.69  5257.7  383.67
  5300.9  385.43  5393.2  383.68  5483.4  383.66  5510.6   386.4    5526  384.14
  5564.1   384.3  5587.1  386.21  5590.9  388.36  5600.6  393.16  5615.6  398.09
  5621.1  404.28  5631.9  402.69  5661.6  412.18  5684.6  415.34  5722.9  413.35
#Mann= 6 ,-1 , 0
  4694.4     .16       0  4956.8     .07       0  4962.8     .16       0
  5257.7     .05       0  5393.2     .16       0  5600.6     .08       0
Bank Sta=4850.2,5590.9
XS Rating Curve= 0 ,0
Exp/Cntr=0.3,0.1

Type RM Length L Ch R = 1 ,29139   ,15,15,15
BEGIN DESCRIPTION:
Mapping XS 276d21b1
END DESCRIPTION:
XS GIS Cut Line= 5
      2925224.65      6979820.04      2924881.72      6980006.69
       2924723.3      6980225.87      2924564.88      6980445.06
      2924469.72      6980626.73
#Sta/Elev= 30
  4602.5  413.82  4664.9  411.47    4834  392.14    4916  387.84  4992.9  386.31
  4993.4  383.25  4993.9  382.45  4999.4  383.25  5017.3  386.62    5097  387.25
  5117.9  389.96  5182.9   386.5    5189  388.31  5197.6  385.37  5203.7  388.61
  5212.3  386.17  5218.5  388.88  5233.2  384.97  5239.3  388.58  5331.6  388.35
  5360.8  387.84  5387.6  388.04  5520.2  391.52  5526.3  388.46  5541.9  387.84
  5569.6  393.73    5586  391.54  5589.6  394.74  5680.5  411.37  5738.9  410.97
#Mann= 6 ,-1 , 0
  4602.5     .16       0  4993.4     .07       0  4999.4     .16       0
  5331.6     .05       0  5387.6     .16       0  5589.6     .08       0
Bank Sta=4916,5360.8
XS Rating Curve= 0 ,0
Exp/Cntr=0.3,0.1

Type RM Length L Ch R = 1 ,29124   ,231,231,231
BEGIN DESCRIPTION:
Mapping XS 062c55c1
END DESCRIPTION:
XS GIS Cut Line= 5
      2925196.42      6979780.98      2924981.55      6979876.48
      2924810.11      6980065.28      2924573.56      6980392.97
      2924460.73      6980618.63
#Sta/Elev= 30
  4593.9  418.26  4875.1  391.58  4981.2  388.76  4995.4  381.82  5016.4  387.14
  5101.8  392.08  5194.7  392.32  5252.7  386.21  5258.8  379.61  5267.4  383.14
  5273.5  377.28  5288.2  381.89  5294.4  376.84  5302.9  380.06  5309.1  375.52
  5323.8  375.26  5338.5  380.16  5344.7  375.26  5353.2  378.15  5356.9  373.54
  5374.1  380.06    5395  374.95  5424.4  380.61  5445.3  376.95    5460  382.79
  5466.2  378.38  5486.4  381.99  5601.3  398.51  5680.6   411.2  5740.5  410.94
#Mann= 4 ,-1 , 0
  4593.9     .16       0  5252.7     .08       0  5486.4     .16       0
  5601.3     .08       0
Bank Sta=5252.7,5486.4
XS Rating Curve= 0 ,0
Exp/Cntr=0.3,0.1

Type RM Length L Ch R = 1 ,28893   ,323,323,323
BEGIN DESCRIPTION:
GLADE CREEK 36.0
END DESCRIPTION:
XS GIS Cut Line= 3
      2925079.91      6979725.95      2924704.66      6979854.31
      2924445.16      6980541.87
#Sta/Elev= 30
  4603.4  407.48  4677.5  400.02  4682.8  401.07  4729.6  394.79  4766.1  391.07
  4771.4  392.19  4828.7  383.76  4835.1  384.36  4881.5  382.47  4940.6  377.82
    4965  375.55  4985.2  372.85    5012  372.72  5012.5  371.92    5018  372.72
  5022.1   375.3  5060.3  376.57  5100.2  376.51  5130.4  379.75    5164  382.07
  5210.3  383.18  5267.6  381.41  5325.7  378.84  5374.8  374.05  5428.3  373.55
  5453.4  375.55  5547.3  387.72  5682.4   408.7  5727.9  406.99  5734.9  407.63
#Mann= 14 ,-1 , 0
  4603.4     .16       0  4729.6     .08       0  4835.1     .05       0
  4881.5     .08       0  4940.6     .12       0    5012     .07       0
    5018     .12       0  5060.3     .08       0  5130.4     .16       0
    5164     .05       0  5267.6     .08       0  5547.3     .16       0
  5682.4     .08       0  5727.9     .05       0
Bank Sta=4965,5453.4
XS Rating Curve= 0 ,0
Exp/Cntr=0.3,0.1

Type RM Length L Ch R = 1 ,28570   ,494,494,494
BEGIN DESCRIPTION:
GLADE CREEK 35.0
END DESCRIPTION:
XS GIS Cut Line= 3
        2924425.      6979374.96        2924425.        6979825.
        2924375.      6980424.98
#Sta/Elev= 30
  4534.2  429.57  4574.7  425.82  4594.2  424.07  4734.2  404.38  4804.2  391.59
  4824.2  386.48  4868.2  377.99  4890.1  374.51  4914.2  370.18  4944.2  370.61
  4960.8  369.55  4961.3  368.75  4967.6  369.55  4986.7  369.57  4995.2  370.69
  5024.4  370.97  5094.6  376.93  5162.4  379.24  5167.4  376.87  5184.9   374.4
  5225.1  371.01  5287.8  370.57  5322.9  374.51  5395.7  382.65  5415.7  385.92
  5431.6  386.74  5445.8  386.45    5486  395.57  5523.6  401.08  5586.3  406.09
#Mann= 7 ,-1 , 0
  4534.2     .05       0  4574.7     .16       0  4868.2     .12       0
  4960.8     .07       0  4967.6     .12       0  4995.2     .16       0
  5431.6     .05       0
Bank Sta=4890.1,5322.9
XS Rating Curve= 0 ,0
Exp/Cntr=0.3,0.1

Type RM Length L Ch R = 1 ,28076   ,562,562,562
BEGIN DESCRIPTION:
GLADE CREEK 34.0
END DESCRIPTION:
XS GIS Cut Line= 3
      2924046.63      6979371.76        2923975.        6980075.
      2924625.03      6980875.03
#Sta/Elev= 30
  4327.2  416.39  4481.2  409.59  4603.9  401.43  4702.4  393.88  4787.4   387.2
  4870.2  374.15  4910.1  369.55  4910.6  368.75  4916.9  369.55  4950.9  369.55
    5091  370.81  5119.9  374.15  5140.4  375.98    5218  388.49  5247.4   392.9
  5317.8   397.4  5360.9     397  5389.6  393.99  5432.8  393.87  5439.2   395.1
  5453.6  393.41  5581.4     400  5595.8  397.64  5616.6  400.66  5681.6  403.44
  5723.7  405.12  5779.2  410.36  5845.1  414.62  5931.9  424.85  6064.9  440.32
#Mann= 11 ,-1 , 0
  4327.2     .16       0  4603.9     .12       0  4702.4     .16       0
  4910.1    .033       0  4916.9     .16       0  4950.9     .05       0
    5091     .16       0    5218     .05       0  5681.6     .16       0
  5779.2     .08       0  5931.9     .16       0
Bank Sta=4870.2,5119.9
XS Rating Curve= 0 ,0
Exp/Cntr=0.3,0.1

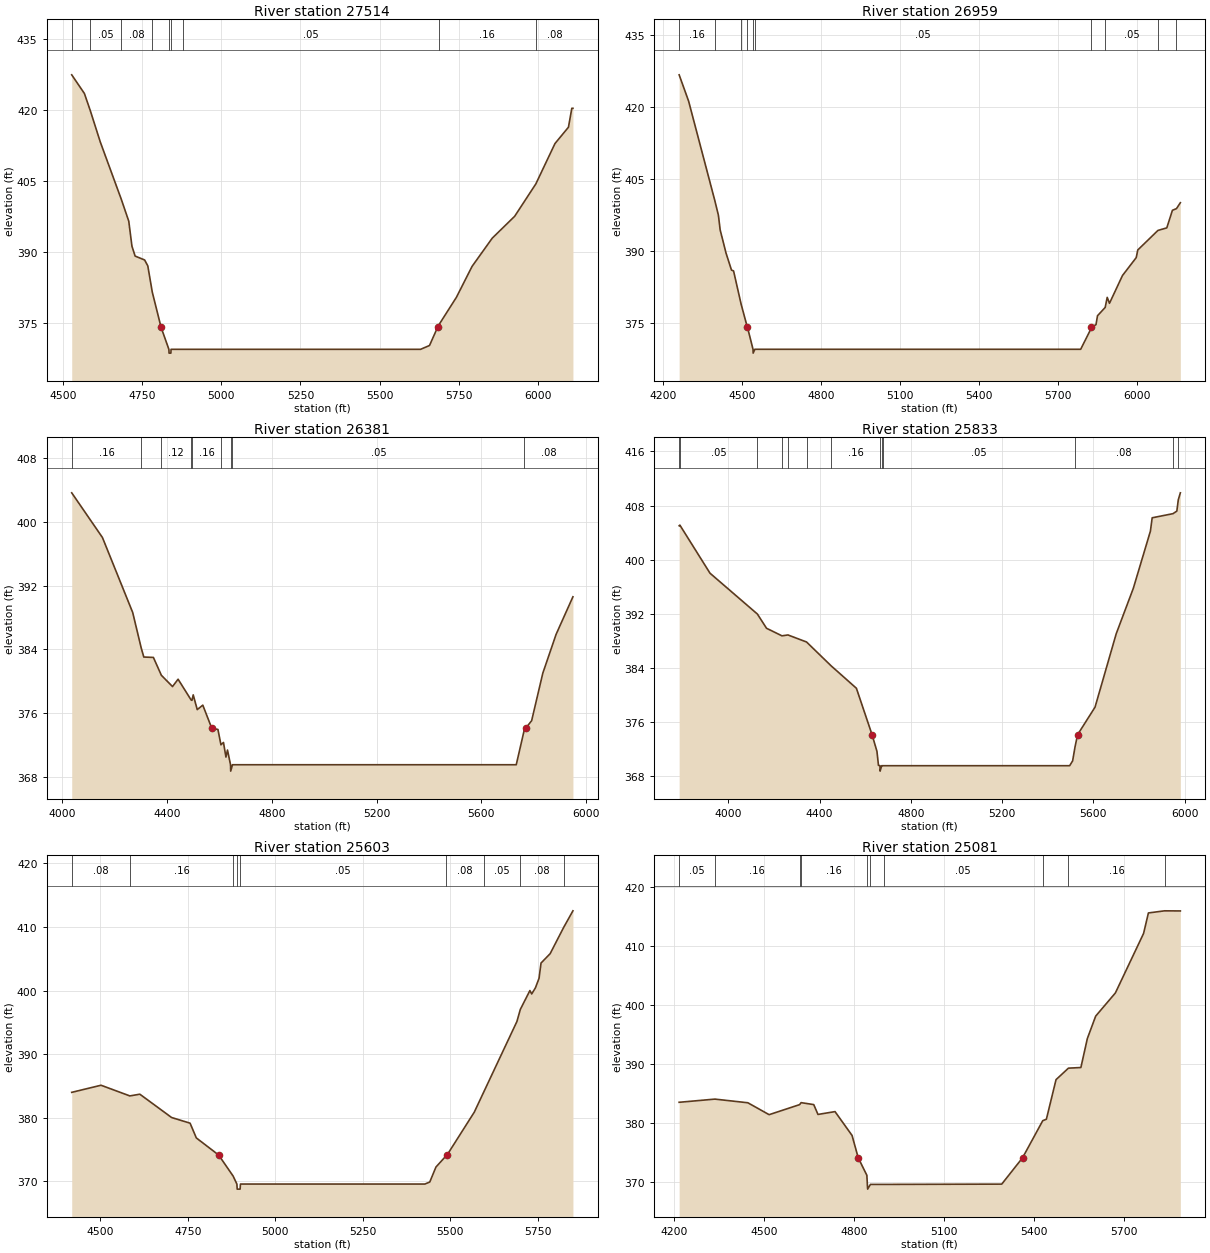
Type RM Length L Ch R = 1 ,27514   ,555,555,555
BEGIN DESCRIPTION:
GLADE CREEK 33.0
END DESCRIPTION:
XS GIS Cut Line= 3
        2923425.      6979724.97        2923425.        6980175.
        2924225.        6980975.
#Sta/Elev= 30
  4528.2  427.36  4568.2  423.43  4586.8  419.82  4618.2  413.24  4684.7  401.13
  4708.2  396.53  4718.2  391.27  4728.2  389.19  4758.2  388.37  4768.2  387.13
  4782.5  381.56  4810.3  374.15  4834.8  369.55  4835.3  368.75  4841.1  368.75
  4841.6  369.55  4880.4  369.55  5628.8  369.55  5657.1  370.36  5682.4  374.15
  5686.6   374.7  5741.9   380.5  5791.4  387.02    5855  392.96  5925.8  397.57
  5992.6  404.39    6053  412.89  6095.5  416.33  6106.1  420.31  6109.6  420.31
#Mann= 9 ,-1 , 0
  4528.2     .16       0  4586.8     .05       0  4684.7     .08       0
  4782.5     .16       0  4834.8    .033       0  4841.6     .16       0
  4880.4     .05       0  5686.6     .16       0  5992.6     .08       0
Bank Sta=4810.3,5682.4
XS Rating Curve= 0 ,0
Exp/Cntr=0.3,0.1

Type RM Length L Ch R = 1 ,26959   ,578,578,578
BEGIN DESCRIPTION:
GLADE CREEK 32.0
END DESCRIPTION:
XS GIS Cut Line= 3
      2923325.03      6979674.97        2922875.        6980225.
      2923496.14      6981244.97
#Sta/Elev= 30
  4260.9  426.76  4296.8  421.29  4395.7  400.71  4410.2  397.47  4416.7  394.46
    4439  389.62  4459.8  386.06  4467.7  385.89  4496.4  378.97  4519.7  374.22
  4520.5  374.14  4541.7  369.55  4542.2  368.75  4548.6  369.55    5787  369.55
  5826.7  373.89  5827.7  374.14  5845.1  374.68    5851  376.55  5880.1  378.27
  5887.8  380.37  5896.5  379.14  5945.9  384.93  5998.1  388.66    6004  390.25
  6080.5  394.32  6114.3  394.86  6135.7  398.53  6151.1  398.87  6165.8   400.1
#Mann= 10 ,-1 , 0
  4260.9     .16       0  4395.7     .05       0  4496.4     .08       0
  4519.7     .05       0  4541.7    .033       0  4548.6     .05       0
  5826.7     .16       0  5880.1     .05       0  6080.5     .08       0
  6151.1     .16       0
Bank Sta=4520.5,5827.7
XS Rating Curve= 0 ,0
Exp/Cntr=0.3,0.1

Type RM Length L Ch R = 1 ,26381   ,548,548,548
BEGIN DESCRIPTION:
GLADE CREEK 31.0
END DESCRIPTION:
XS GIS Cut Line= 3
      2922824.99      6979475.01        2922325.        6980275.
      2921775.01      6981074.99
#Sta/Elev= 30
  4035.4  403.63  4152.7  398.03  4268.3  388.63  4300.6  384.21  4310.7  383.05
  4347.3     383  4377.8  380.76  4420.4  379.35  4441.6  380.27  4491.6  377.66
  4494.7  377.62  4499.4  378.31  4514.8  376.46    4536  377.02  4570.1  374.14
  4593.8  373.97  4605.3  372.05    4615  372.34  4624.4  370.51  4630.3  371.39
  4641.9  369.55  4642.5  368.75  4649.4  369.55  5733.1  369.55  5763.8  373.92
  5769.5  374.14  5791.9  375.07  5834.6  381.03  5885.3  385.89  5949.6   390.6
#Mann= 9 ,-1 , 0
  4035.4     .16       0  4300.6     .08       0  4377.8     .12       0
  4491.6     .05       0  4494.7     .16       0  4605.3     .05       0
  4641.9    .033       0  4649.4     .05       0  5763.8     .08       0
Bank Sta=4570.1,5769.5
XS Rating Curve= 0 ,0
Exp/Cntr=0.3,0.1

Type RM Length L Ch R = 1 ,25833   ,230,230,230
BEGIN DESCRIPTION:
GLADE CREEK 30.0
END DESCRIPTION:
XS GIS Cut Line= 3
      2922300.01      6979249.97        2921775.        6980325.
      2921365.34       6981237.7
#Sta/Elev= 30
  3784.3  405.02  3787.4  405.12  3919.5  398.01  4127.3  391.97  4167.2  389.87
    4235  388.75  4261.2  388.88  4342.7  387.84  4450.3  384.32  4561.2     381
  4629.9  374.13  4651.3  371.67  4657.9  369.61  4664.5  369.55  4665.1  368.75
    4672  369.55  4675.9  369.55  5495.9  369.55    5509  370.27  5519.4  372.32
  5530.6  374.13  5607.2  378.21  5699.9  389.05  5774.9  395.77  5849.9  404.23
  5857.6   406.2  5948.9  406.81  5965.7  407.19  5972.1  408.86  5981.1  409.89
#Mann= 13 ,-1 , 0
  3784.3     .16       0  3787.4     .05       0  4127.3     .08       0
    4235     .05       0  4261.2     .08       0  4342.7     .05       0
  4450.3     .16       0  4664.5    .033       0    4672     .16       0
  4675.9     .05       0  5519.4     .08       0  5948.9     .05       0
  5972.1     .08       0
Bank Sta=4629.9,5530.6
XS Rating Curve= 0 ,0
Exp/Cntr=0.3,0.1

Type RM Length L Ch R = 1 ,25603   ,522,522,522
BEGIN DESCRIPTION:
GLADE CREEK 29.0
END DESCRIPTION:
XS GIS Cut Line= 3
      2921614.57      6979772.06      2921537.29       6980348.8
       2921271.6      6981156.95
#Sta/Elev= 30
  4418.1  383.98  4501.8   385.1  4584.2  383.42  4612.8  383.69  4703.6  380.02
  4756.4  379.13  4774.2  376.81    4838  374.12  4879.4  370.81  4890.2  369.55
  4891.1  368.75  4899.4  368.75  4900.4  369.55  5427.6  369.55  5441.5  369.87
  5459.2  372.23  5488.1  373.98    5491  374.12  5568.7  380.86  5595.5     384
  5690.6  395.13  5700.3  397.03  5727.7     400  5732.9  399.47  5743.4  400.42
  5753.9  401.94  5759.5  404.33  5785.5   405.8  5824.2  409.94  5850.7  412.55
#Mann= 9 ,-1 , 0
  4418.1     .08       0  4584.2     .16       0  4879.4     .05       0
  4890.2    .033       0  4900.4     .05       0  5488.1     .08       0
  5595.5     .05       0  5700.3     .08       0  5824.2     .05       0
Bank Sta=4838,5491
XS Rating Curve= 0 ,0
Exp/Cntr=0.3,0.1

Type RM Length L Ch R = 1 ,25081   ,372,372,372
BEGIN DESCRIPTION:
Mapping XS 4b27e365
END DESCRIPTION:
XS GIS Cut Line= 3
      2921589.29      6979755.93      2921032.02      6980268.93
      2920769.49      6981142.28
#Sta/Elev= 30
  4217.6  383.48  4336.8  384.02  4446.4   383.4  4517.3  381.38  4618.7  383.08
  4623.9  383.42  4665.9  383.09    4680  381.42  4736.8   381.9  4793.5  377.86
  4814.1  374.06  4842.8   371.1  4844.5  369.55  4845.4  368.75  4854.7  369.55
    4899  369.55  5292.1   369.6  5361.3  374.06  5428.7  380.36  5440.8  380.61
  5472.9  387.32  5514.2  389.27  5555.7  389.38  5577.2  394.29    5605   398.1
  5670.6  402.03  5764.5  412.12  5780.6   415.6  5834.6  415.96    5887  415.94
#Mann= 10 ,-1 , 0
  4217.6     .05       0  4336.8     .16       0  4618.7     .08       0
  4623.9     .16       0  4844.5    .033       0  4854.7     .16       0
    4899     .05       0  5428.7     .08       0  5514.2     .16       0
  5834.6     .08       0
Bank Sta=4814.1,5361.3
XS Rating Curve= 0 ,0
Exp/Cntr=0.3,0.1

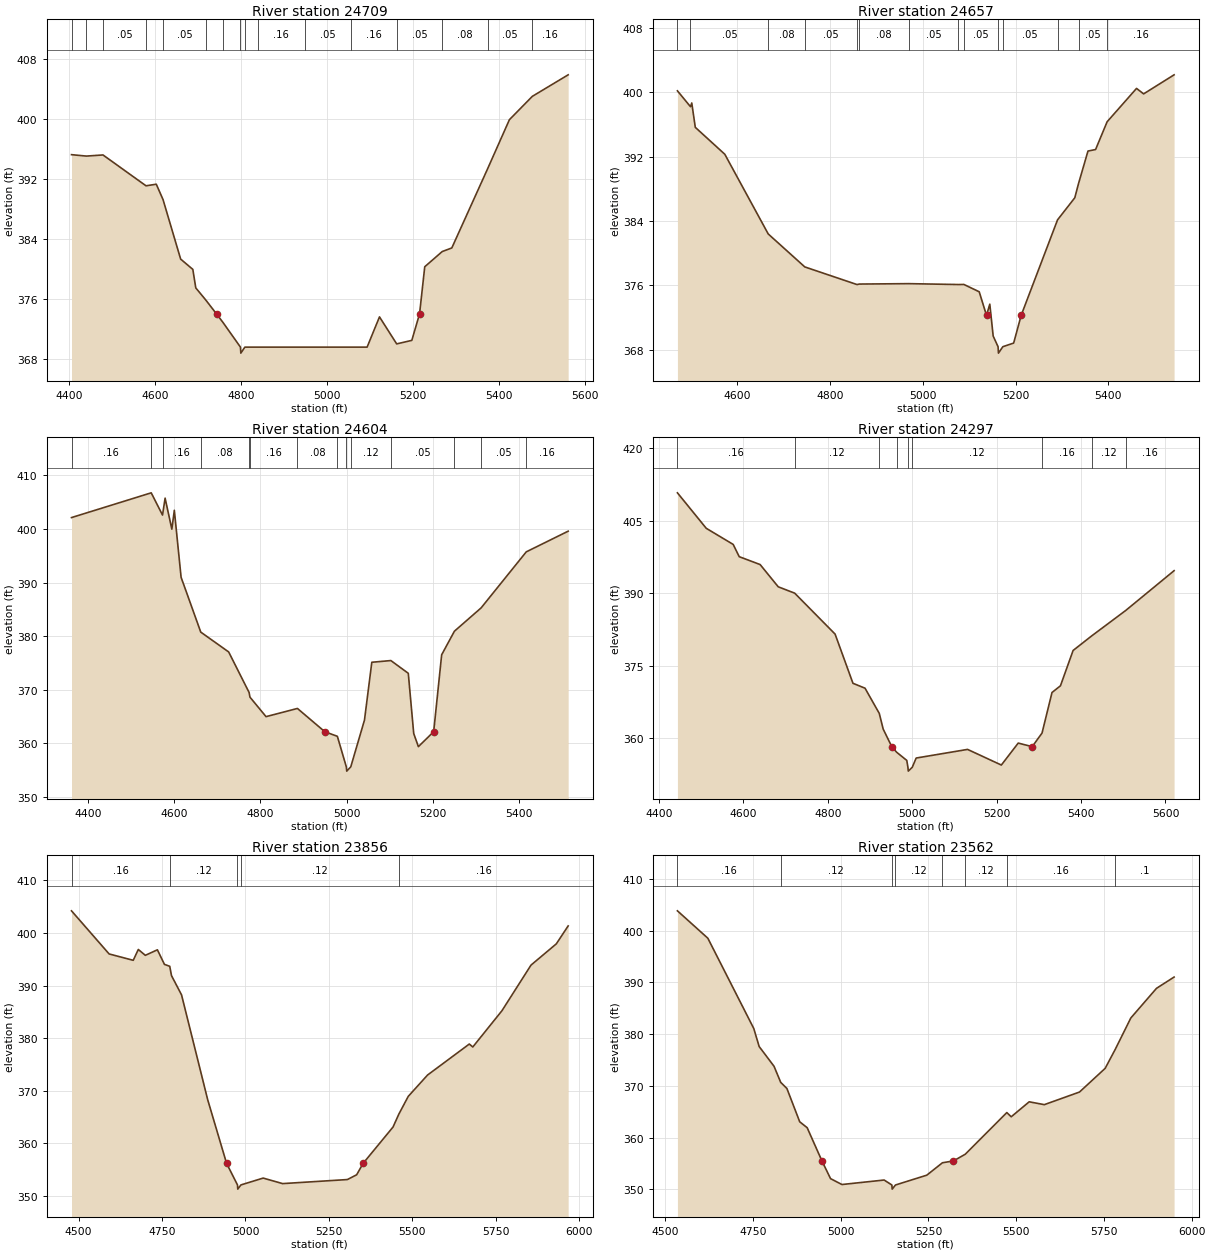
Type RM Length L Ch R = 1 ,24709   ,52,52,52
BEGIN DESCRIPTION:
Mapping XS 0fb80ecc
END DESCRIPTION:
XS GIS Cut Line= 4
      2921052.83      6979703.85      2920789.83      6979953.83
      2920688.27      6980136.12      2920451.29      6980669.96
#Sta/Elev= 30
  4406.1   395.2  4440.8  395.01  4479.4  395.16  4579.5  391.05  4603.4  391.26
  4619.1  389.21  4660.1  381.28  4688.4  379.91  4695.3  377.44  4718.1  375.86
  4743.6  373.97  4758.8  372.82  4799.2  369.55  4800.1  368.75  4809.5  369.55
    4839  369.55  4949.6  369.55  5056.7  369.55  5093.9  369.55  5122.7  373.58
  5162.7  369.98  5197.9  370.45  5215.9  373.97    5228  380.26  5268.7  382.29
    5291  382.77  5374.6  393.36    5425  399.86  5478.3  402.97  5561.7  405.84
#Mann= 16 ,-1 , 0
  4406.1     .16       0  4440.8     .08       0  4479.4     .05       0
  4579.5     .16       0  4619.1     .05       0  4718.1     .12       0
  4758.8     .05       0  4799.2     .04       0  4809.5     .05       0
    4839     .16       0  4949.6     .05       0  5056.7     .16       0
  5162.7     .05       0  5268.7     .08       0  5374.6     .05       0
  5478.3     .16       0
Bank Sta=4743.6,5215.9
XS Rating Curve= 0 ,0
Exp/Cntr=0.3,0.1

Type RM Length L Ch R = 1 ,24657   ,53,53,53
BEGIN DESCRIPTION:
Mapping XS 40dad8c5
END DESCRIPTION:
XS GIS Cut Line= 4
      2920927.84      6979703.84      2920787.23      6979865.28
       2920646.6      6980102.26       2920401.8      6980628.34
#Sta/Elev= 30
  4471.7  400.19  4499.8  398.22  4502.6  398.68  4510.2  395.65  4573.8   392.3
  4667.3  382.39  4746.1  378.29  4858.4   376.1  4863.6  376.16  4970.2  376.21
  5076.9   376.1  5088.8  376.11  5121.8   375.2  5137.5  372.27  5144.6  373.66
  5151.9  369.69  5162.4  368.37  5163.3  367.57  5172.7  368.37    5196  368.82
  5212.2  372.27  5290.5  384.14  5327.7  386.89  5335.7  388.65  5356.1   392.7
  5372.5  392.89  5397.3  396.34  5460.7  400.49    5476  399.81  5541.6  402.18
#Mann= 14 ,-1 , 0
  4471.7     .16       0  4499.8     .05       0  4667.3     .08       0
  4746.1     .05       0  4858.4     .16       0  4863.6     .08       0
  4970.2     .05       0  5076.9     .16       0  5088.8     .05       0
  5162.4     .04       0  5172.7     .05       0  5290.5     .08       0
  5335.7     .05       0  5397.3     .16       0
Bank Sta=5137.5,5212.2
XS Rating Curve= 0 ,0
Exp/Cntr=0.3,0.1

Type RM Length L Ch R = 1 ,24604   ,307,307,307
BEGIN DESCRIPTION:
Mapping XS 2d895b76
END DESCRIPTION:
XS GIS Cut Line= 4
      2920953.86      6979597.08      2920808.06      6979732.47
      2920586.71      6980107.47      2920391.38      6980586.67
#Sta/Elev= 30
  4361.9  402.13  4546.8  406.75    4573   402.6    4579  405.76  4594.6  399.97
  4600.4  403.49  4616.1  390.98  4661.7  380.75  4726.4  377.05  4773.8  369.48
  4775.8  368.61  4813.1  364.97  4885.9   366.5  4949.5  362.15  4978.5   361.3
  4999.3   355.6  5000.3   354.8  5009.6   355.6  5041.4  364.33  5058.4  375.12
  5102.6  375.44    5143  373.06  5155.6  361.82  5166.4  359.37  5201.9  362.16
  5220.4  376.52    5250  380.92  5311.9  385.27  5416.6  395.73  5513.8  399.59
#Mann= 14 ,-1 , 0
  4361.9     .16       0  4546.8     .05       0    4573     .16       0
  4661.7     .08       0  4773.8     .05       0  4775.8     .16       0
  4885.9     .08       0  4978.5     .12       0  4999.3     .07       0
  5009.6     .12       0  5102.6     .05       0    5250     .16       0
  5311.9     .05       0  5416.6     .16       0
Bank Sta=4949.5,5201.9
XS Rating Curve= 0 ,0
Exp/Cntr=0.3,0.1

Type RM Length L Ch R = 1 ,24297   ,441,441,441
BEGIN DESCRIPTION:
Mapping XS bb551903
END DESCRIPTION:
XS GIS Cut Line= 3
      2920811.54      6979535.42      2920367.09      6979906.95
      2920370.56      6980504.15
#Sta/Elev= 30
  4443.9  410.81  4512.2  403.46    4576  400.12  4590.3  397.58  4639.8  395.95
  4682.7  391.34  4721.7  390.02  4817.4  381.54  4859.7  371.35  4888.3  370.33
    4922  365.12  4931.3  361.86  4951.7  358.22    4963  357.08  4987.2  355.37
  4989.9  353.95  4990.8  353.15  5000.2  353.95  5009.4  355.86  5131.2  357.65
  5211.2  354.41  5251.2  358.96  5284.3  358.22  5307.6  361.04  5331.2  369.44
  5351.2  370.83  5381.2  378.15  5424.8  381.14  5505.6  386.42  5620.4  394.68
#Mann= 9 ,-1 , 0
  4443.9     .16       0  4721.7     .12       0    4922     .16       0
    4963     .12       0  4989.9     .07       0  5000.2     .12       0
  5307.6     .16       0  5424.8     .12       0  5505.6     .16       0
Bank Sta=4951.7,5284.3
XS Rating Curve= 0 ,0
Exp/Cntr=0.3,0.1

Type RM Length L Ch R = 1 ,23856   ,294,294,294
BEGIN DESCRIPTION:
GLADE CREEK 27.0
END DESCRIPTION:
XS GIS Cut Line= 3
      2920281.24      6979344.97        2919950.        6979850.
      2920374.98      6980624.96
#Sta/Elev= 30
  4478.8  404.22  4591.5  396.02  4663.8  394.81  4678.9  396.87    4700  395.76
  4736.1  396.81  4757.2  394.04  4773.1  393.67  4778.3  391.91  4808.5  388.23
  4886.8   368.3  4943.3  356.21    4976   352.1  4976.9   351.3  4986.3   352.1
  5052.9   353.4  5111.3  352.35  5305.2  353.12    5333  354.03  5352.5  356.21
    5442  363.11  5459.3  365.55  5487.6  368.94  5545.3  372.99  5670.5  378.89
  5680.9  378.33  5768.1  385.21  5855.3   393.9  5931.1  397.94  5966.6  401.35
#Mann= 5 ,-1 , 0
  4478.8     .16       0  4773.1     .12       0    4976     .07       0
  4986.3     .12       0  5459.3     .16       0
Bank Sta=4943.3,5352.5
XS Rating Curve= 0 ,0
Exp/Cntr=0.3,0.1

Type RM Length L Ch R = 1 ,23562   ,724,724,724
BEGIN DESCRIPTION:
double GLADE CREEK 26.0
END DESCRIPTION:
XS GIS Cut Line= 3
      2920274.98      6979275.01        2919875.        6979525.
      2919074.98      6980025.01
#Sta/Elev= 30
  4534.9  403.85  4621.6  398.55  4752.5  381.08  4767.8   377.6  4810.2  373.78
  4829.2  370.67  4846.8  369.49  4883.3  363.05  4904.6   361.9  4946.7  355.47
  4971.2  352.05  5003.6  350.91  5123.9  351.78  5145.9  350.82  5146.8  350.02
  5156.2  350.82  5245.4  352.72    5290  355.12  5321.2  355.47    5355  356.77
  5473.4  364.83  5485.9  364.01  5537.2  366.91  5580.3  366.36  5680.5   368.8
  5753.6  373.38  5782.3  377.05  5826.7  383.12  5899.9  388.86    5950  391.04
#Mann= 8 ,-1 , 0
  4534.9     .16       0  4829.2     .12       0  5145.9     .07       0
  5156.2     .12       0    5290     .16       0    5355     .12       0
  5473.4     .16       0  5782.3      .1       0
Bank Sta=4946.7,5321.2
XS Rating Curve= 0 ,0
Exp/Cntr=0.3,0.1