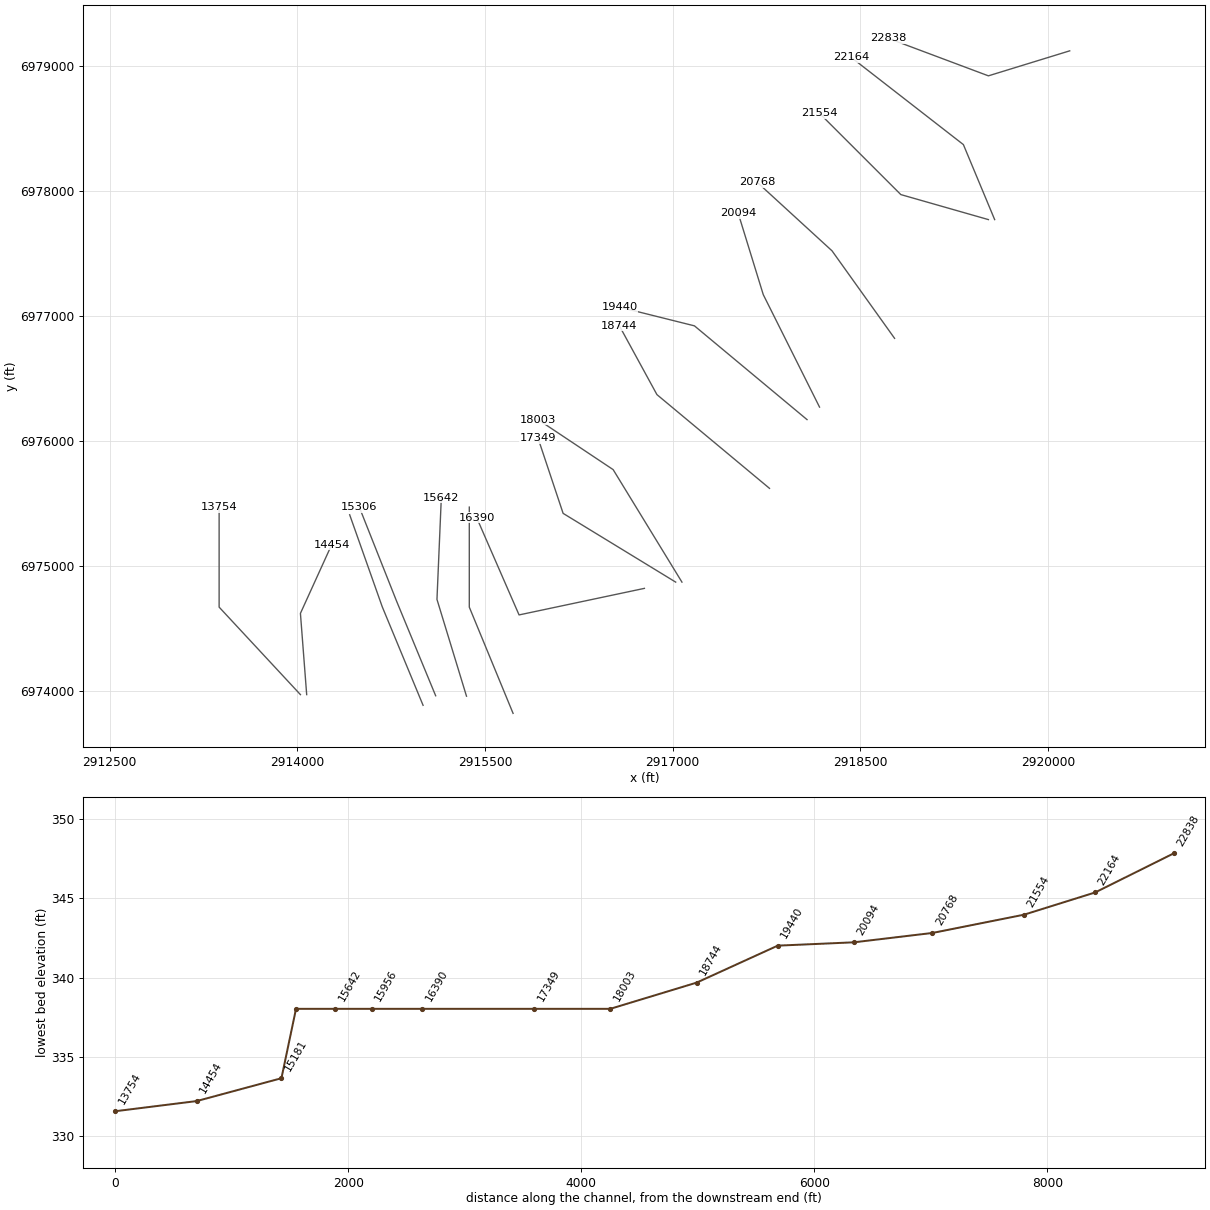
HEC-RAS study GLADE CREEK.prj: GLADE CREEK Base Level Engineering

--- GLADE CREEK.g01 (geometry) --- (continued)

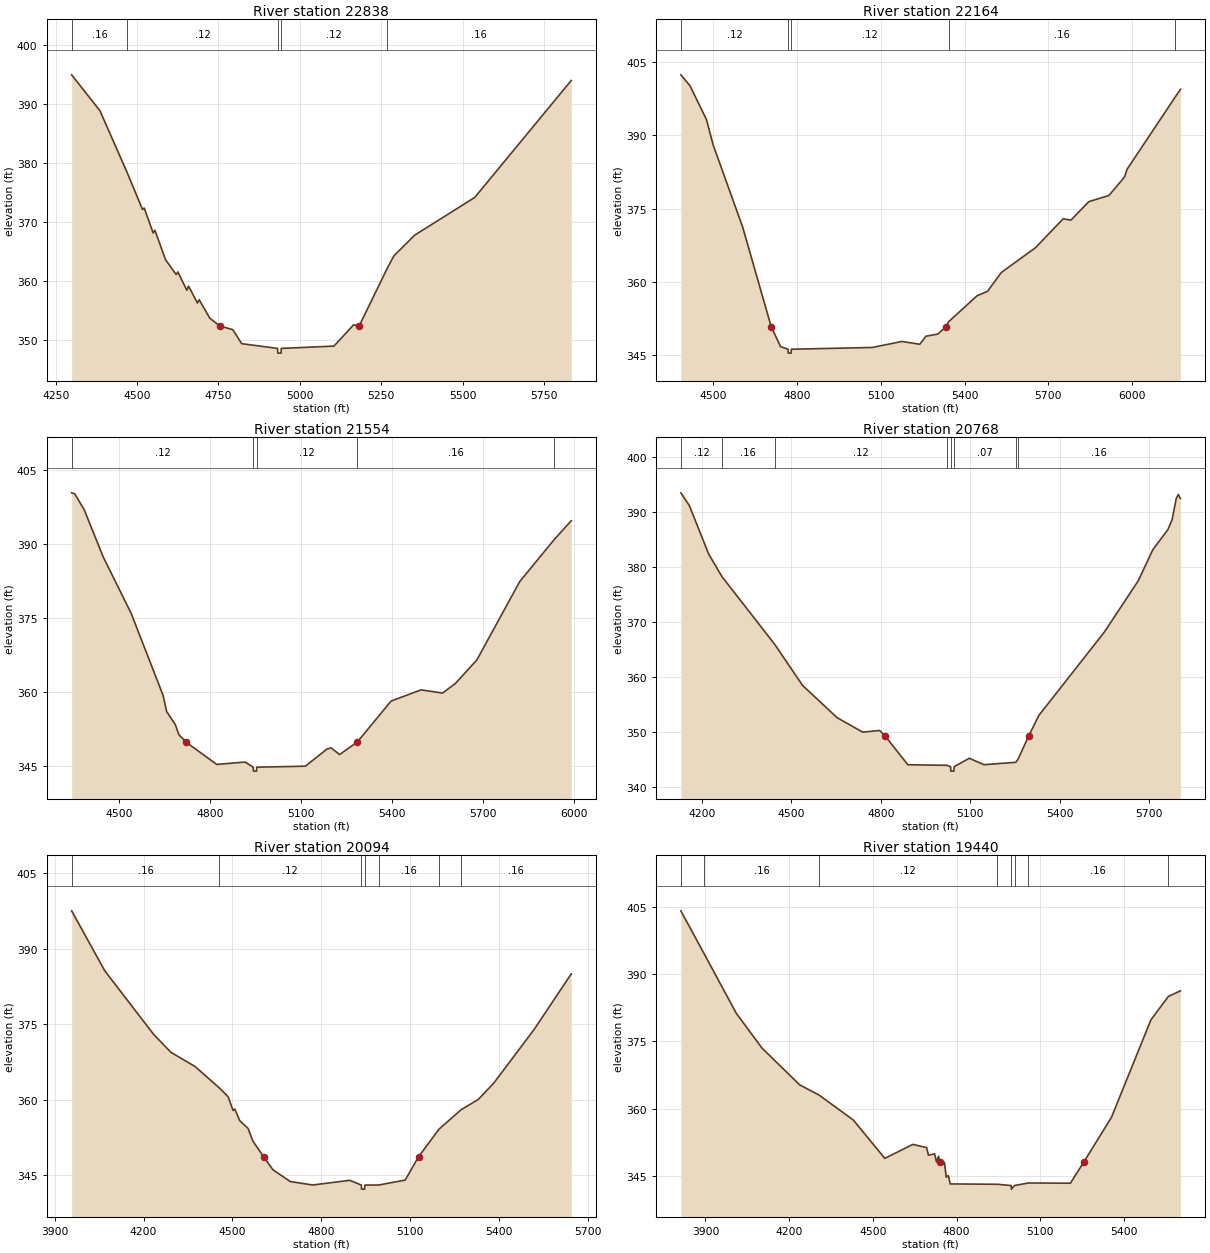
Type RM Length L Ch R = 1 ,22838   ,674,674,674
BEGIN DESCRIPTION:
GLADE CREEK 25.0
END DESCRIPTION:
XS GIS Cut Line= 3
      2920174.99        6979125.        2919525.        6978925.
      2918724.96      6979225.01
#Sta/Elev= 30
    4299  395.01    4386  388.92  4470.2  378.35  4516.7  372.18    4522  372.42
  4549.4  368.19  4554.7  368.67  4587.4  363.67  4620.1  361.15  4625.3   361.6
  4652.8  358.49    4658  359.19  4685.5  356.32  4690.7   356.9  4723.4  353.75
  4754.1  352.43    4794  351.81  4821.5  349.43  4931.5  348.63  4932.2  347.83
  4942.2  347.83  4942.9  348.63  5104.6  349.02  5165.1  352.62  5182.2  352.43
  5268.2  362.19  5288.8  364.32  5352.9  367.84  5537.1  374.22  5833.5  394.05
#Mann= 5 ,-1 , 0
    4299     .16       0  4470.2     .12       0  4931.5     .07       0
  4942.9     .12       0  5268.2     .16       0
Bank Sta=4754.1,5182.2
XS Rating Curve= 0 ,0
Exp/Cntr=0.3,0.1

Type RM Length L Ch R = 1 ,22164   ,610,610,610
BEGIN DESCRIPTION:
GLADE CREEK 24.0
END DESCRIPTION:
XS GIS Cut Line= 3
      2919575.01      6977774.97        2919325.        6978375.
        2918425.        6979075.
#Sta/Elev= 30
  4383.1  402.41  4415.6  400.19  4474.7  393.27  4498.5  388.11  4604.7  371.19
  4707.1  350.74  4740.6   346.7  4767.4  346.17    4768  345.37  4778.2  345.37
  4778.9  346.17  5069.3  346.53  5175.2  347.76  5239.4  347.19  5261.2  348.83
  5303.7  349.28    5333  350.74  5342.8  351.81  5444.9  357.14    5482  358.04
  5531.7  361.91  5653.9  366.98  5753.4  372.92  5780.6  372.62  5844.8  376.41
  5917.2  377.69  5973.3   381.5  5981.5     383  6153.1  397.73  6173.3  399.44
#Mann= 5 ,-1 , 0
  4383.1     .12       0  4767.4     .07       0  4778.9     .12       0
  5342.8     .16       0  6153.1     .08       0
Bank Sta=4707.1,5333
XS Rating Curve= 0 ,0
Exp/Cntr=0.3,0.1

Type RM Length L Ch R = 1 ,21554   ,786,786,786
BEGIN DESCRIPTION:
GLADE CREEK 23.0
END DESCRIPTION:
XS GIS Cut Line= 3
      2919525.03      6977774.99        2918825.        6977975.
      2918174.99      6978625.01
#Sta/Elev= 30
  4343.5   400.4  4353.9  400.19  4385.1  396.94  4447.5  387.41  4539.8  375.95
  4645.1  359.32  4656.8  356.05  4685.4   353.4  4697.1  351.37  4720.8  349.85
  4821.9  345.33  4915.5  345.81  4942.3  344.77  4942.9  343.97  4953.2  343.97
  4953.8  344.77    5114  344.97  5184.7  348.41  5198.8   348.7  5227.1  347.33
  5283.7   349.8  5285.1  349.85  5396.8  358.18  5495.8  360.45  5566.5   359.8
  5608.9  361.75  5679.7  366.52  5821.1  382.41  5935.4  390.97  5990.8  394.74
#Mann= 5 ,-1 , 0
  4343.5     .12       0  4942.3     .07       0  4953.8     .12       0
  5283.7     .16       0  5935.4     .08       0
Bank Sta=4720.8,5285.1
XS Rating Curve= 0 ,0
Exp/Cntr=0.3,0.1

Type RM Length L Ch R = 1 ,20768   ,674,674,674
BEGIN DESCRIPTION:
GLADE CREEK 22.0
END DESCRIPTION:
XS GIS Cut Line= 3
      2918774.99      6976825.01        2918275.        6977525.
      2917674.97      6978075.03
#Sta/Elev= 30
  4130.3  393.42  4158.6  391.12  4223.7  382.27  4267.9   378.2  4444.6  365.89
  4538.3   358.4  4653.8  352.54  4739.8  349.91  4796.4  350.21  4815.9  349.14
    4891  343.98  5022.4  343.88  5034.4  343.62    5035  342.82  5045.4  342.82
    5046  343.62  5096.9  345.16  5146.2  343.99  5252.6  344.42  5260.2  344.98
  5295.4  349.14    5330  352.95  5549.5   368.1  5662.9  377.41  5712.3  383.11
  5762.2  386.71  5776.4   388.5  5790.6   392.4  5797.4  393.12  5804.5  392.38
#Mann= 8 ,-1 , 0
  4130.3     .12       0  4267.9     .16       0  4444.6     .12       0
  5022.4     .07       0  5034.4     .07       0    5046     .07       0
  5252.6     .12       0  5260.2     .16       0
Bank Sta=4815.9,5295.4
XS Rating Curve= 0 ,0
Exp/Cntr=0.3,0.1

Type RM Length L Ch R = 1 ,20094   ,654,654,654
BEGIN DESCRIPTION:
GLADE CREEK 21.0
END DESCRIPTION:
XS GIS Cut Line= 3
      2918174.98      6976275.03        2917725.        6977175.
      2917524.99      6977825.03
#Sta/Elev= 30
  3957.3  397.52  4069.1  385.61    4234  372.98  4292.7   369.4  4373.7   366.6
  4455.4  362.36  4485.5  360.58  4502.3  357.84  4507.9  358.16  4524.7  355.83
  4552.6  354.31  4569.4  351.75  4605.6  348.64  4636.5  346.09  4695.2  343.74
  4770.6  343.05  4896.4  343.98  4935.3  343.03  4935.9  342.23  4946.3  342.23
  4946.9  343.03  4994.1  343.05  5083.2  344.03  5128.1  348.64  5197.5  354.16
  5272.3  358.02  5329.7  360.04    5382  363.28    5518  373.92  5643.6  384.99
#Mann= 7 ,-1 , 0
  3957.3     .16       0  4455.4     .12       0  4935.3     .07       0
  4946.9     .12       0  4994.1     .16       0  5197.5     .12       0
  5272.3     .16       0
Bank Sta=4605.6,5128.1
XS Rating Curve= 0 ,0
Exp/Cntr=0.3,0.1

Type RM Length L Ch R = 1 ,19440   ,696,696,696
BEGIN DESCRIPTION:
GLADE CREEK 20.0
END DESCRIPTION:
XS GIS Cut Line= 3
        2918075.        6976175.        2917175.        6976925.
        2916575.        6977075.
#Sta/Elev= 30
  3812.1  404.12  3894.9  394.62  4010.6  381.27    4103  373.48  4238.4  365.26
  4307.2  363.02  4429.8  357.45    4543  348.88  4643.2     352  4692.7  351.28
  4699.2  349.59  4721.3  349.89  4727.9  348.11  4735.7  349.36  4739.4  348.01
  4756.5  347.98    4763  344.69  4770.8  345.05  4777.3  343.18  4946.4   343.1
  4995.8  342.82  4996.3  342.02  5007.6  342.82  5057.2  343.39  5207.8  343.34
  5255.3  348.01  5354.7     358  5496.4   379.8  5558.9  385.02  5602.1  386.27
#Mann= 8 ,-1 , 0
  3812.1     .12       0  3894.9     .16       0  4307.2     .12       0
  4946.4     .07       0  4995.8     .07       0  5007.6     .07       0
  5057.2     .16       0  5558.9     .05       0
Bank Sta=4739.4,5255.3
XS Rating Curve= 0 ,0
Exp/Cntr=0.3,0.1

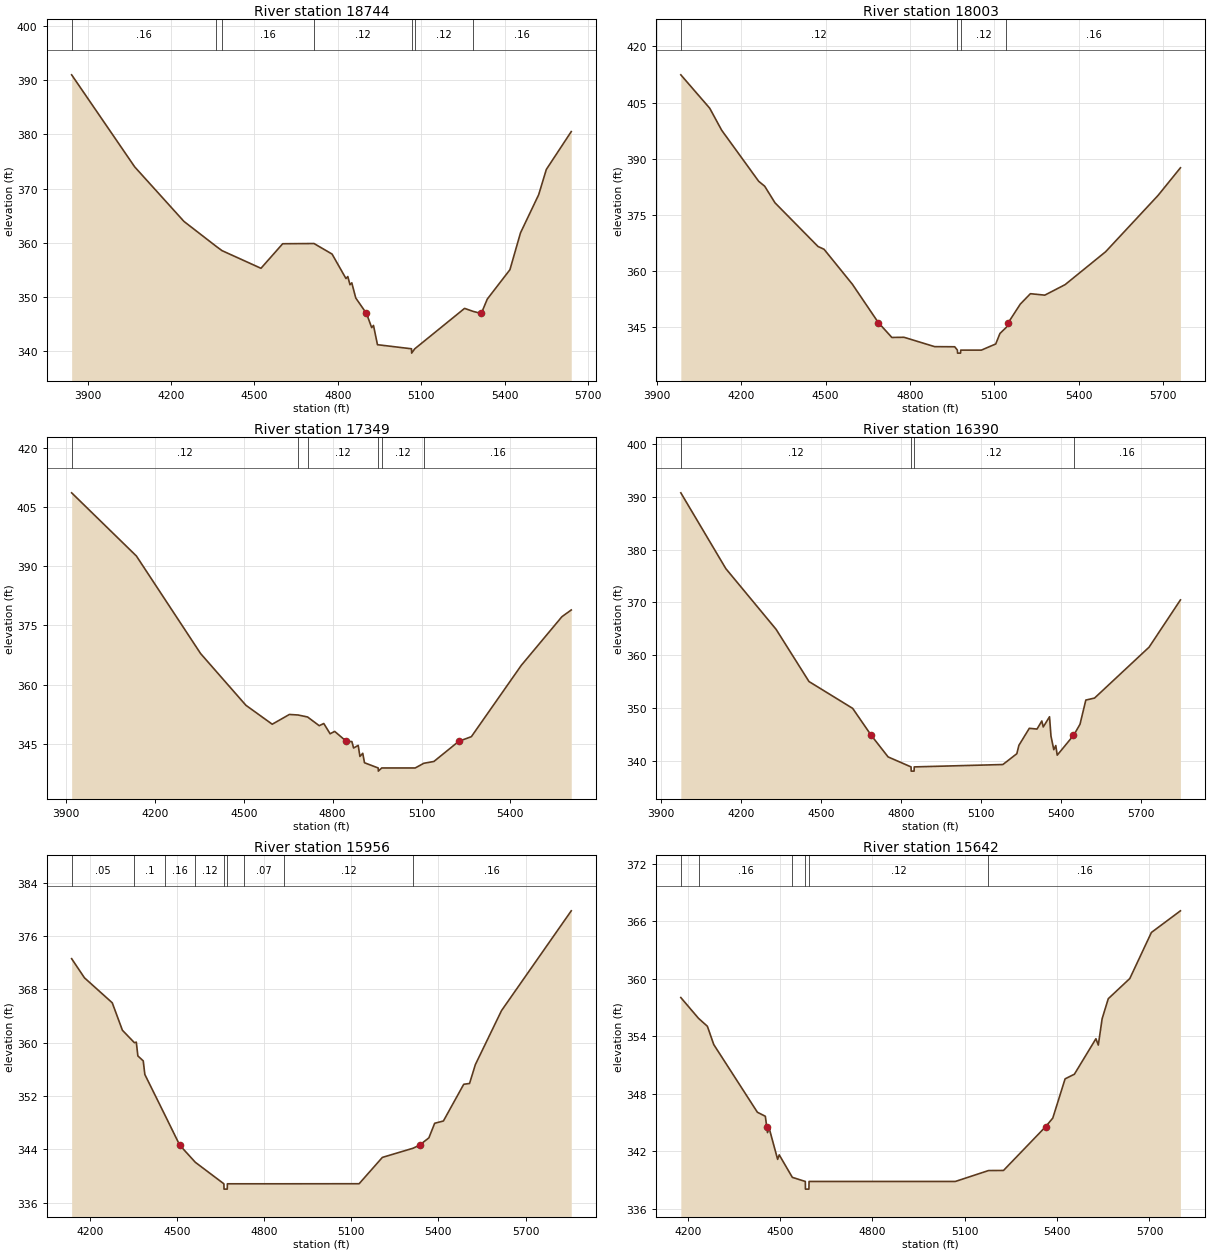
Type RM Length L Ch R = 1 ,18744   ,741,741,741
BEGIN DESCRIPTION:
GLADE CREEK 19.0
END DESCRIPTION:
XS GIS Cut Line= 3
      2917774.99      6975625.01        2916875.        6976375.
      2916575.01      6976924.98
#Sta/Elev= 30
  3842.1  390.93  4069.2  373.97  4246.3  363.94  4363.3  359.31  4383.3  358.56
  4523.5  355.31  4601.6  359.83  4714.3  359.87  4779.3  357.93  4829.4  353.42
  4835.9  353.79  4843.8  352.28  4850.3  352.63  4864.6  349.84  4903.2  346.99
  4921.9  344.39  4928.4  344.79  4942.7  341.24  5065.2  340.49  5065.7  339.69
    5077  340.49  5256.2  347.93  5287.3  347.37  5316.4  346.99  5337.8  349.63
  5419.4  355.05  5457.4  361.83  5522.9  368.86  5550.4  373.51  5640.1  380.48
#Mann= 7 ,-1 , 0
  3842.1     .16       0  4363.3     .12       0  4383.3     .16       0
  4714.3     .12       0  5065.2     .07       0    5077     .12       0
  5287.3     .16       0
Bank Sta=4903.2,5316.4
XS Rating Curve= 0 ,0
Exp/Cntr=0.3,0.1

Type RM Length L Ch R = 1 ,18003   ,654,654,654
BEGIN DESCRIPTION:
GLADE CREEK 18.0
END DESCRIPTION:
XS GIS Cut Line= 3
      2917075.02      6974874.97        2916525.        6975775.
        2915925.        6976175.
#Sta/Elev= 30
  3985.7   412.4  4088.3  403.49  4130.9   397.6  4262.5  383.95  4283.8  382.64
  4320.5   378.2  4473.4  366.53  4494.7   365.8  4595.4  356.46  4687.7  346.21
  4735.8  342.23  4779.2  342.27  4888.1  339.77  4959.3  339.74  4968.8  338.84
  4969.3  338.04  4980.1  338.04  4980.6  338.84    5054  338.84  5105.1  340.49
  5120.1   343.3  5143.3  344.97  5149.9  346.21  5192.2  351.12  5228.3  353.92
  5279.4  353.53  5351.5  356.33  5495.7  365.13    5682  380.17  5761.6  387.56
#Mann= 4 ,-1 , 0
  3985.7     .12       0  4968.8     .07       0  4980.6     .12       0
  5143.3     .16       0
Bank Sta=4687.7,5149.9
XS Rating Curve= 0 ,0
Exp/Cntr=0.3,0.1

Type RM Length L Ch R = 1 ,17349   ,959,959,959
BEGIN DESCRIPTION:
GLADE CREEK 17.0
END DESCRIPTION:
XS GIS Cut Line= 3
      2917025.02      6974874.99        2916125.        6975425.
      2915925.01      6976024.97
#Sta/Elev= 30
  3918.5   408.6  4137.2  392.58    4354  367.85  4506.9  354.74  4595.9  349.93
  4653.9  352.41  4683.3  352.27  4715.2  351.77  4754.6  349.56    4770  350.11
  4791.4  347.51  4806.8  348.11  4846.3  345.59  4864.9  345.53  4870.7   343.9
  4886.2  344.57    4892  341.77  4901.6  342.56  4907.5  340.16  4953.7  338.84
  4954.3  338.04  4965.6  338.84  5078.7  338.84  5107.8  340.03  5141.9  340.49
  5225.7  345.59  5268.4  346.78  5437.1  364.87  5574.1  377.19  5605.7   378.9
#Mann= 6 ,-1 , 0
  3918.5     .12       0  4683.3     .16       0  4715.2     .12       0
  4953.7     .07       0  4965.6     .12       0  5107.8     .16       0
Bank Sta=4846.3,5225.7
XS Rating Curve= 0 ,0
Exp/Cntr=0.3,0.1

Type RM Length L Ch R = 1 ,16390   ,434,434,434
BEGIN DESCRIPTION:
GLADE CREEK 16.0
END DESCRIPTION:
XS GIS Cut Line= 3
      2916774.97      6974824.99      2915772.85      6974612.53
      2915434.19      6975390.08
#Sta/Elev= 30
  3975.6  390.76  4144.3   376.4  4332.7   364.9    4456  355.01  4619.6  349.93
  4689.4  344.81  4752.5  340.73  4838.5  338.84    4839  338.04  4849.9  338.04
  4850.4  338.84  5182.6  339.29  5234.9  341.34  5242.7  342.93  5281.7  346.15
  5310.6  346.01  5328.6  347.54    5334  346.41  5357.5  348.34  5362.9  344.68
  5373.5   342.1  5380.9  342.89  5386.3  341.06  5447.3  344.81  5447.9  344.83
  5471.7  346.92  5493.5   351.5  5526.2  351.88  5730.7  361.53  5848.1  370.47
#Mann= 4 ,-1 , 0
  3975.6     .12       0  4838.5     .07       0  4850.4     .12       0
  5447.9     .16       0
Bank Sta=4689.4,5447.3
XS Rating Curve= 0 ,0
Exp/Cntr=0.3,0.1

Type RM Length L Ch R = 1 ,15956   ,314,314,314
BEGIN DESCRIPTION:
GLADE CREEK 15.0
END DESCRIPTION:
XS GIS Cut Line= 3
      2915725.01      6973824.98        2915375.        6974675.
        2915375.      6975475.03
#Sta/Elev= 30
  4138.1  372.61  4182.2  369.74  4277.9  365.99  4312.7  361.88    4354  360.01
  4360.6  360.09    4366  358.02  4384.5  357.28    4390  355.24  4458.8  349.18
    4510  344.64  4563.6  342.07    4662  338.84  4662.5  338.04  4673.6  338.04
  4674.1  338.84  4730.9  338.84  4868.9  338.84  5127.4  338.85  5207.4   342.8
  5312.7  344.17  5335.3  344.64  5367.4  345.73  5387.4  347.92  5417.4  348.26
  5487.4  353.77  5507.4  353.89  5527.4  356.72  5617.4  364.82  5857.4  379.79
#Mann= 9 ,-1 , 0
  4138.1     .05       0    4354      .1       0  4458.8     .16       0
  4563.6     .12       0    4662     .07       0  4674.1     .12       0
  4730.9     .07       0  4868.9     .12       0  5312.7     .16       0
Bank Sta=4510,5335.3
XS Rating Curve= 0 ,0
Exp/Cntr=0.3,0.1

Type RM Length L Ch R = 1 ,15642   ,336,336,336
BEGIN DESCRIPTION:
Mapping XS 7ee29474
END DESCRIPTION:
XS GIS Cut Line= 3
      2915352.65      6973962.45      2915116.55      6974736.74
      2915151.27      6975549.21
#Sta/Elev= 30
  4177.9  358.05  4235.4  355.88  4264.2  355.05  4284.9  353.14  4426.6  346.07
  4452.4  345.65  4456.9  344.55  4459.4  343.94  4464.7  344.42  4492.3  341.15
  4497.5  341.62  4540.1  339.27  4582.2  338.84  4582.7  338.04  4593.9  338.04
  4594.4  338.84  5069.5  338.84  5177.2  339.98  5225.9  339.99  5362.4  344.55
    5386  345.46    5426  349.56  5456.1  350.04  5526.1  353.75  5533.9  353.09
  5546.2  355.83  5566.2  357.93  5636.2  360.04  5706.3  364.85  5800.6  367.11
#Mann= 6 ,-1 , 0
  4177.9      .1       0  4235.4     .16       0  4540.1     .12       0
  4582.2     .07       0  4594.4     .12       0  5177.2     .16       0
Bank Sta=4456.9,5362.4
XS Rating Curve= 0 ,0
Exp/Cntr=0.3,0.1

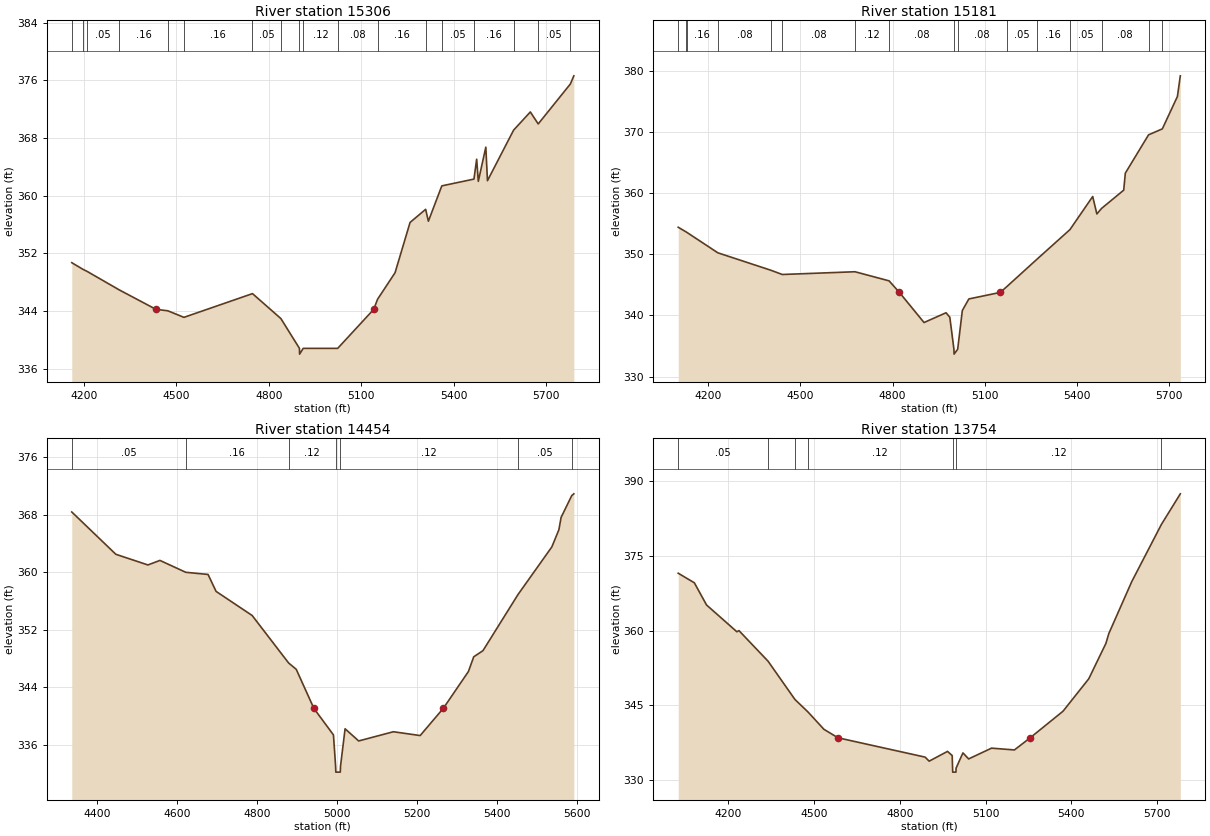
Type RM Length L Ch R = 1 ,15306   ,125,125,125
BEGIN DESCRIPTION:
Mapping XS dbd42612
END DESCRIPTION:
XS GIS Cut Line= 3
      2915106.14      6973965.89      2914793.63      6974722.86
      2914495.03      6975476.31
#Sta/Elev= 30
  4160.8  350.72  4197.5  349.79  4210.3  349.52  4315.2  346.94  4434.1  344.25
  4472.4  344.05  4524.9  343.14  4747.3  346.43  4839.5  342.97  4899.7  338.84
  4900.2  338.04  4911.9  338.84  5023.8  338.84  5140.8  344.25  5153.1  345.64
    5210  349.33  5258.7   356.3  5309.3  358.12  5318.1  356.47  5361.7  361.37
    5466  362.31  5474.8  365.07  5480.2     362  5504.5  366.74  5509.9  362.09
  5594.7   369.1    5649  371.62  5674.6  369.96  5778.9   375.5  5790.2  376.63
#Mann= 18 ,-1 , 0
  4160.8     .16       0  4197.5     .08       0  4210.3     .05       0
  4315.2     .16       0  4472.4     .05       0  4524.9     .16       0
  4747.3     .05       0  4839.5     .12       0  4899.7     .07       0
  4911.9     .12       0  5023.8     .08       0  5153.1     .16       0
  5309.3     .08       0  5361.7     .05       0    5466     .16       0
  5594.7     .08       0  5674.6     .05       0  5778.9     .16       0
Bank Sta=4434.1,5140.8
XS Rating Curve= 0 ,0
Exp/Cntr=0.3,0.1

Type RM Length L Ch R = 1 ,15181   ,727,727,727
BEGIN DESCRIPTION:
Mapping XS af11a848
END DESCRIPTION:
XS GIS Cut Line= 3
      2915005.44      6973889.51      2914679.05      6974677.72
      2914418.64      6975413.79
#Sta/Elev= 30
  4102.7  354.43  4126.7  353.72  4129.7  353.63  4231.6  350.25  4403.9   347.4
  4441.4   346.7    4678  347.15  4788.9  345.66  4822.4  343.77  4902.6  338.84
  4974.2  340.44  4986.5  339.71  4999.9  334.47  5000.4  333.67  5012.1  334.47
  5027.2   340.8  5048.4   342.7  5150.8  343.77  5171.6   344.7  5269.3  349.16
  5377.5  354.05  5451.5  359.46    5465  356.61  5480.5  357.52  5552.4   360.5
  5557.7  363.29  5633.2  369.55  5678.1  370.53  5727.2  375.83  5736.6  379.21
#Mann= 16 ,-1 , 0
  4102.7     .05       0  4126.7     .08       0  4129.7     .16       0
  4231.6     .08       0  4403.9     .16       0  4441.4     .08       0
    4678     .12       0  4788.9     .08       0  4999.9     .07       0
  5012.1     .08       0  5171.6     .05       0  5269.3     .16       0
  5377.5     .05       0  5480.5     .08       0  5633.2     .05       0
  5678.1     .08       0
Bank Sta=4822.4,5150.8
XS Rating Curve= 0 ,0
Exp/Cntr=0.3,0.1

Type RM Length L Ch R = 1 ,14454   ,700,700,700
BEGIN DESCRIPTION:
GLADE CREEK 13.0
END DESCRIPTION:
XS GIS Cut Line= 3
        2914075.      6973975.01        2914025.        6974625.
      2914275.02      6975175.04
#Sta/Elev= 30
  4337.1  368.37  4447.4  362.49  4527.6  361.01  4557.7  361.64  4622.3  359.99
  4678.1  359.69  4698.1  357.34  4788.4  353.99  4879.5   347.4  4898.7  346.51
  4942.9  341.08  4991.8   337.4  4997.2  333.03  4997.7  332.23  5008.9  332.23
  5009.4  333.03  5020.9  338.25  5054.9  336.56  5141.7  337.84  5208.7  337.31
  5266.5  341.08  5329.5  346.21  5342.7  348.25  5365.8   349.1  5453.5   356.9
  5538.2  363.52  5555.8   365.9  5561.3  367.61  5587.9  370.64  5593.2  370.89
#Mann= 7 ,-1 , 0
  4337.1     .05       0  4622.3     .16       0  4879.5     .12       0
  4997.2     .07       0  5009.4     .12       0  5453.5     .05       0
  5587.9     .08       0
Bank Sta=4942.9,5266.5
XS Rating Curve= 0 ,0
Exp/Cntr=0.3,0.1

Type RM Length L Ch R = 1 ,13754   ,730,730,730
BEGIN DESCRIPTION:
GLADE CREEK 12.0
END DESCRIPTION:
XS GIS Cut Line= 3
      2914025.01      6973974.99        2913375.        6974675.
        2913375.      6975475.03
#Sta/Elev= 30
  4025.7  371.49  4082.1  369.57  4124.7  365.12  4230.7  359.75    4238  359.98
  4339.8  353.84  4433.8  346.16  4478.3  343.72  4535.1  340.18  4584.1  338.48
  4888.9   334.6    4903  333.79  4967.1  335.75  4983.5  334.91  4984.8  332.39
  4985.3  331.59  4996.6  331.59  4997.1  332.39    5021  335.45    5041  334.24
    5121   336.4    5201  336.04  5256.2  338.48    5371  343.81    5461  350.32
    5521  357.43    5531  359.38    5611  369.78  5714.6  381.25    5781  387.42
#Mann= 7 ,-1 , 0
  4025.7     .05       0  4339.8     .07       0  4433.8     .16       0
  4478.3     .12       0  4984.8     .07       0  4997.1     .12       0
  5714.6     .05       0
Bank Sta=4584.1,5256.2
XS Rating Curve= 0 ,0
Exp/Cntr=0.3,0.1