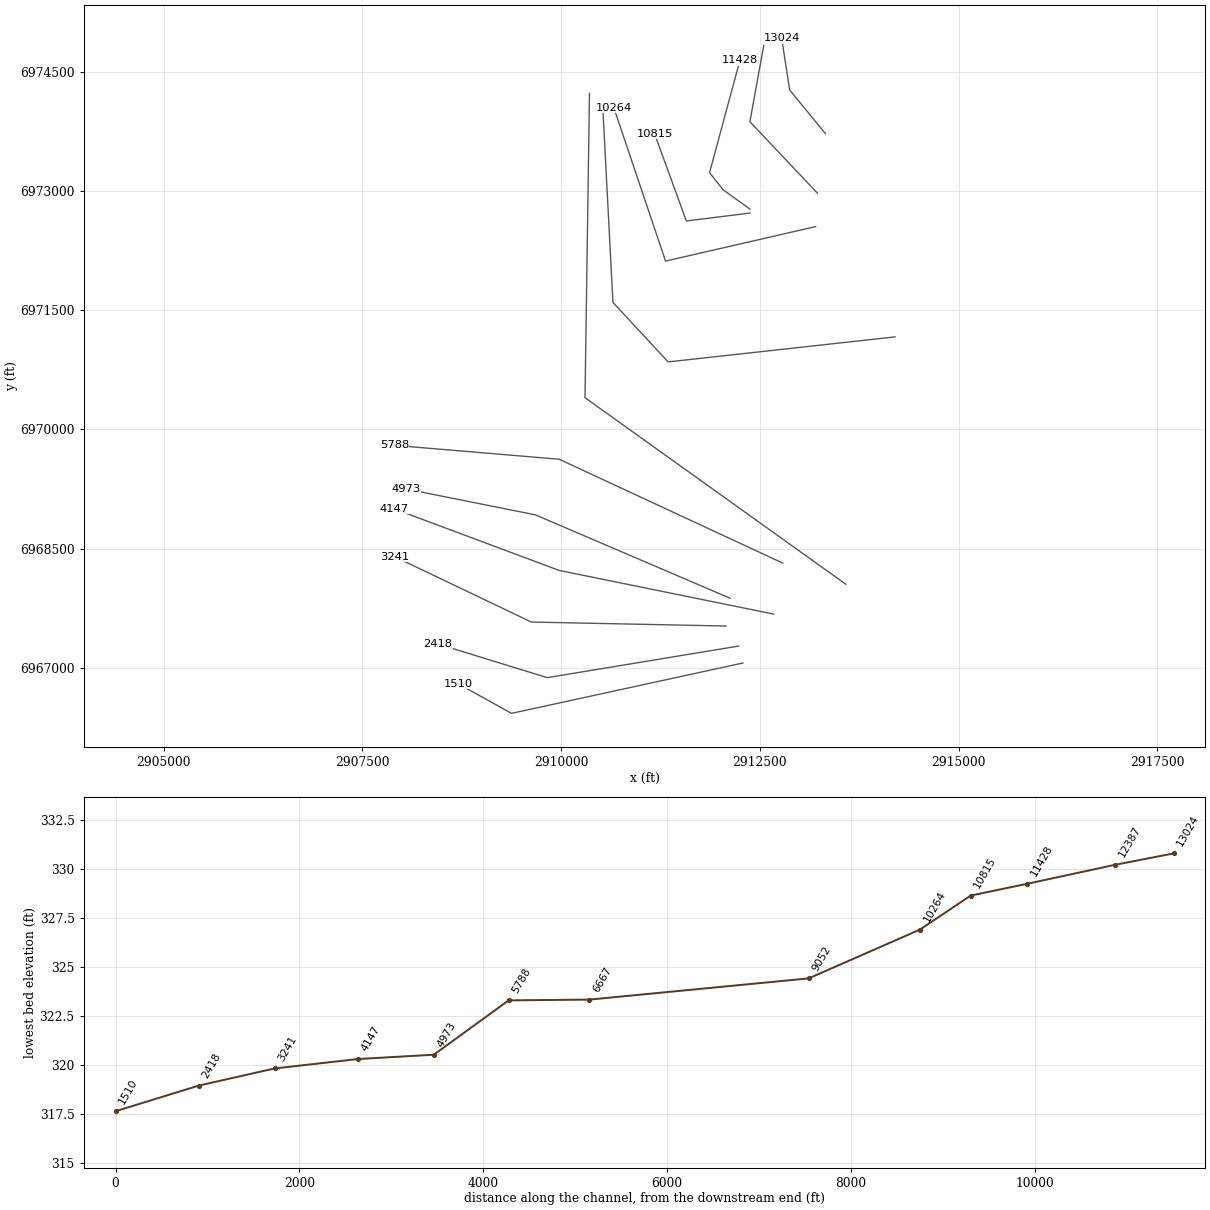
HEC-RAS study GLADE CREEK.prj: GLADE CREEK Base Level Engineering

--- GLADE CREEK.g01 (geometry) --- (continued)

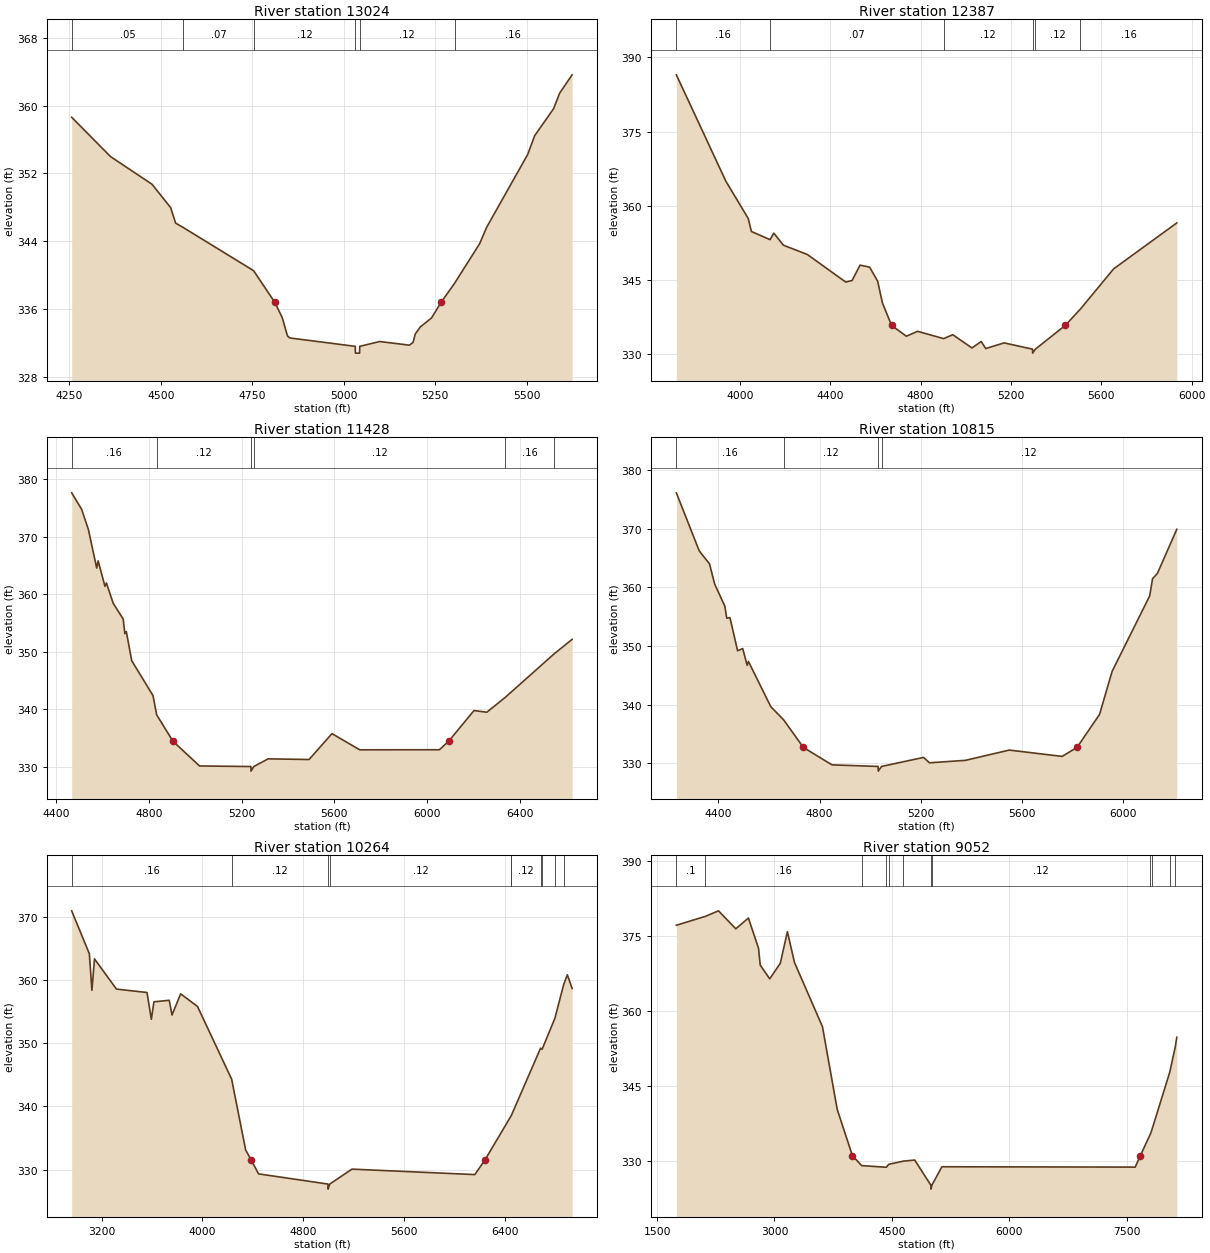
Type RM Length L Ch R = 1 ,13024   ,637,637,637
BEGIN DESCRIPTION:
GLADE CREEK 11.0
END DESCRIPTION:
XS GIS Cut Line= 3
      2913324.97      6973725.04        2912875.        6974275.
        2912775.      6974924.97
#Sta/Elev= 30
  4256.1  358.63  4362.3  353.99  4475.7  350.73  4526.7  347.97  4540.3  346.14
  4561.6  345.61  4753.5  340.53  4811.6  336.78  4831.7     335  4846.1  332.83
  4852.6  332.59  5031.4   331.6  5031.9   330.8  5043.2   330.8  5043.7   331.6
  5098.2  332.17  5179.2  331.74  5189.3  332.06  5195.6  333.07  5209.5   333.9
  5239.9  334.95  5265.9  336.78  5302.9  339.04  5371.4  343.71  5390.4  345.63
  5502.9  354.25  5521.9  356.46  5573.7  359.65  5590.2  361.48  5624.3  363.64
#Mann= 6 ,-1 , 0
  4256.1     .05       0  4561.6     .07       0  4753.5     .12       0
  5031.4     .07       0  5043.7     .12       0  5302.9     .16       0
Bank Sta=4811.6,5265.9
XS Rating Curve= 0 ,0
Exp/Cntr=0.3,0.1

Type RM Length L Ch R = 1 ,12387   ,959,959,959
BEGIN DESCRIPTION:
GLADE CREEK 10.0
END DESCRIPTION:
XS GIS Cut Line= 3
      2913225.03      6972974.97        2912375.        6973875.
      2912549.44      6974837.23
#Sta/Elev= 30
  3718.3  386.48  3937.8  364.95  4036.5  357.45  4050.7  354.81  4133.2  353.16
  4149.8  354.48  4192.3  352.04  4298.3  350.16  4468.2  344.59  4496.5   344.9
  4531.7  348.01  4574.2   347.6  4609.8  344.75  4630.8  340.36  4671.6  335.82
  4736.8  333.64  4786.6  334.63  4901.8  333.15  4942.3  333.94  5027.4  331.27
  5068.1  332.57  5088.4  331.15  5169.7  332.29  5295.6  331.02  5296.1  330.22
    5308  331.02  5440.2  335.82  5507.3  339.12  5654.7  347.26  5934.2  356.54
#Mann= 6 ,-1 , 0
  3718.3     .16       0  4133.2     .07       0  4901.8     .12       0
  5295.6     .07       0    5308     .12       0  5507.3     .16       0
Bank Sta=4671.6,5440.2
XS Rating Curve= 0 ,0
Exp/Cntr=0.3,0.1

Type RM Length L Ch R = 1 ,11428   ,613,613,613
BEGIN DESCRIPTION:
GLADE CREEK 9.0
END DESCRIPTION:
XS GIS Cut Line= 4
        2912375.        6972775.      2912037.48      6973018.85
      2911867.16       6973233.1        2912250.        6974650.
#Sta/Elev= 30
  4467.1  377.68    4510  374.82  4539.4  371.26    4575  364.58  4581.2  365.85
  4610.6   361.4  4616.8     362  4646.2  358.45  4689.2  355.72  4696.5  353.17
  4702.6  353.54  4725.9  348.48  4817.9  342.38  4833.5  339.05  4903.5  334.46
  5018.4  330.15  5239.8  330.05  5240.3  329.25  5252.2  330.05  5314.5  331.39
  5490.6  331.27  5589.4  335.78  5709.1  332.96  6052.5  332.97  6092.8  334.46
  6201.7  339.79  6257.2   339.5  6336.1  342.07  6548.9  349.71  6624.9  352.18
#Mann= 6 ,-1 , 0
  4467.1     .16       0  4833.5     .12       0  5239.8     .07       0
  5252.2     .12       0  6336.1     .16       0  6548.9     .12       0
Bank Sta=4903.5,6092.8
XS Rating Curve= 0 ,0
Exp/Cntr=0.3,0.1

Type RM Length L Ch R = 1 ,10815   ,551,551,551
BEGIN DESCRIPTION:
GLADE CREEK 8.0
END DESCRIPTION:
XS GIS Cut Line= 3
      2912375.04        6972725.        2911575.        6972625.
      2911175.01      6973724.97
#Sta/Elev= 30
  4234.4  376.12  4325.1  366.19  4365.4  364.01  4385.6  360.58  4425.9  356.79
  4433.5  354.73  4446.1  354.84  4476.3  349.18  4496.5  349.56  4514.1   346.7
  4519.1  347.36  4607.3  339.66  4658.7  337.37  4736.2  332.69  4849.2  329.72
  5031.3  329.45  5032.1  328.65    5045  329.45  5210.9  330.99  5234.2  330.07
  5376.5  330.49  5549.4  332.24  5758.2  331.16    5817  332.69  5905.9  338.31
  5955.8  345.68  6104.1  358.54  6115.4  361.47  6134.7  362.39  6211.1   369.9
#Mann= 4 ,-1 , 0
  4234.4     .16       0  4658.7     .12       0  5031.3     .07       0
    5045     .12       0
Bank Sta=4736.2,5817
XS Rating Curve= 0 ,0
Exp/Cntr=0.3,0.1

Type RM Length L Ch R = 1 ,10264   ,1212,1212,1212
BEGIN DESCRIPTION:
Mapping XS 97ee8804
END DESCRIPTION:
XS GIS Cut Line= 3
       2913201.6      6972554.31      2911313.58      6972120.28
      2910662.82      6974050.89
#Sta/Elev= 30
  2961.8  370.91    3102  364.13  3122.5  358.34    3143  363.31  3317.4  358.54
  3559.9     358  3594.5  353.77    3615  356.53  3736.4  356.77  3758.7  354.44
  3827.2  357.79  3960.9   355.8  4232.3   344.3  4343.5  333.11  4386.3  331.57
  4446.1  329.33  4997.4  327.72  4998.2  326.92  5011.1  327.72  5187.9  330.08
  6163.8  329.22  6245.1  331.57  6453.3  338.55  6454.9  338.62  6685.8   349.2
  6697.8  349.02  6799.6  353.92  6869.2  359.25  6898.5   360.8  6936.4  358.64
#Mann= 10 ,-1 , 0
  2961.8     .16       0  4232.3     .12       0  4997.4     .07       0
  5011.1     .12       0  6453.3     .16       0  6454.9     .12       0
  6685.8     .16       0  6697.8     .12       0  6799.6     .16       0
  6869.2     .12       0
Bank Sta=4386.3,6245.1
XS Rating Curve= 0 ,0
Exp/Cntr=0.3,0.1

Type RM Length L Ch R = 1 ,9052    ,2385,2385,2385
BEGIN DESCRIPTION:
Mapping XS 0ef21a91
END DESCRIPTION:
XS GIS Cut Line= 4
      2914199.87      6971165.42      2911346.13      6970850.75
      2910651.69      6971599.45      2910521.48      6974095.14
#Sta/Elev= 30
  1746.8  377.16  2116.4  378.93  2284.9  380.04  2506.2  376.45  2667.2   378.6
  2796.4  372.55  2818.1   369.2  2938.9  366.45  3074.1  369.54    3165  375.87
  3255.9  369.71  3612.9  356.89  3801.3  340.36  3995.5  331.12  4113.6  329.13
  4428.4   328.8  4460.1  329.39  4647.7  330.03  4791.4  330.24  4996.8  325.23
  4997.8  324.43    5011  325.23  5138.3   328.9  7607.2  328.83  7672.7  331.12
  7798.9  335.37  7815.2  336.04    8047  347.72  8118.1  352.78  8138.1  354.77
#Mann= 12 ,-1 , 0
  1746.8      .1       0  2116.4     .16       0  4113.6     .05       0
  4428.4     .12       0  4460.1     .05       0  4647.7     .12       0
  4996.8     .07       0    5011     .12       0  7798.9     .16       0
  7815.2     .12       0    8047     .16       0  8118.1     .12       0
Bank Sta=3995.5,7672.7
XS Rating Curve= 0 ,0
Exp/Cntr=0.3,0.1

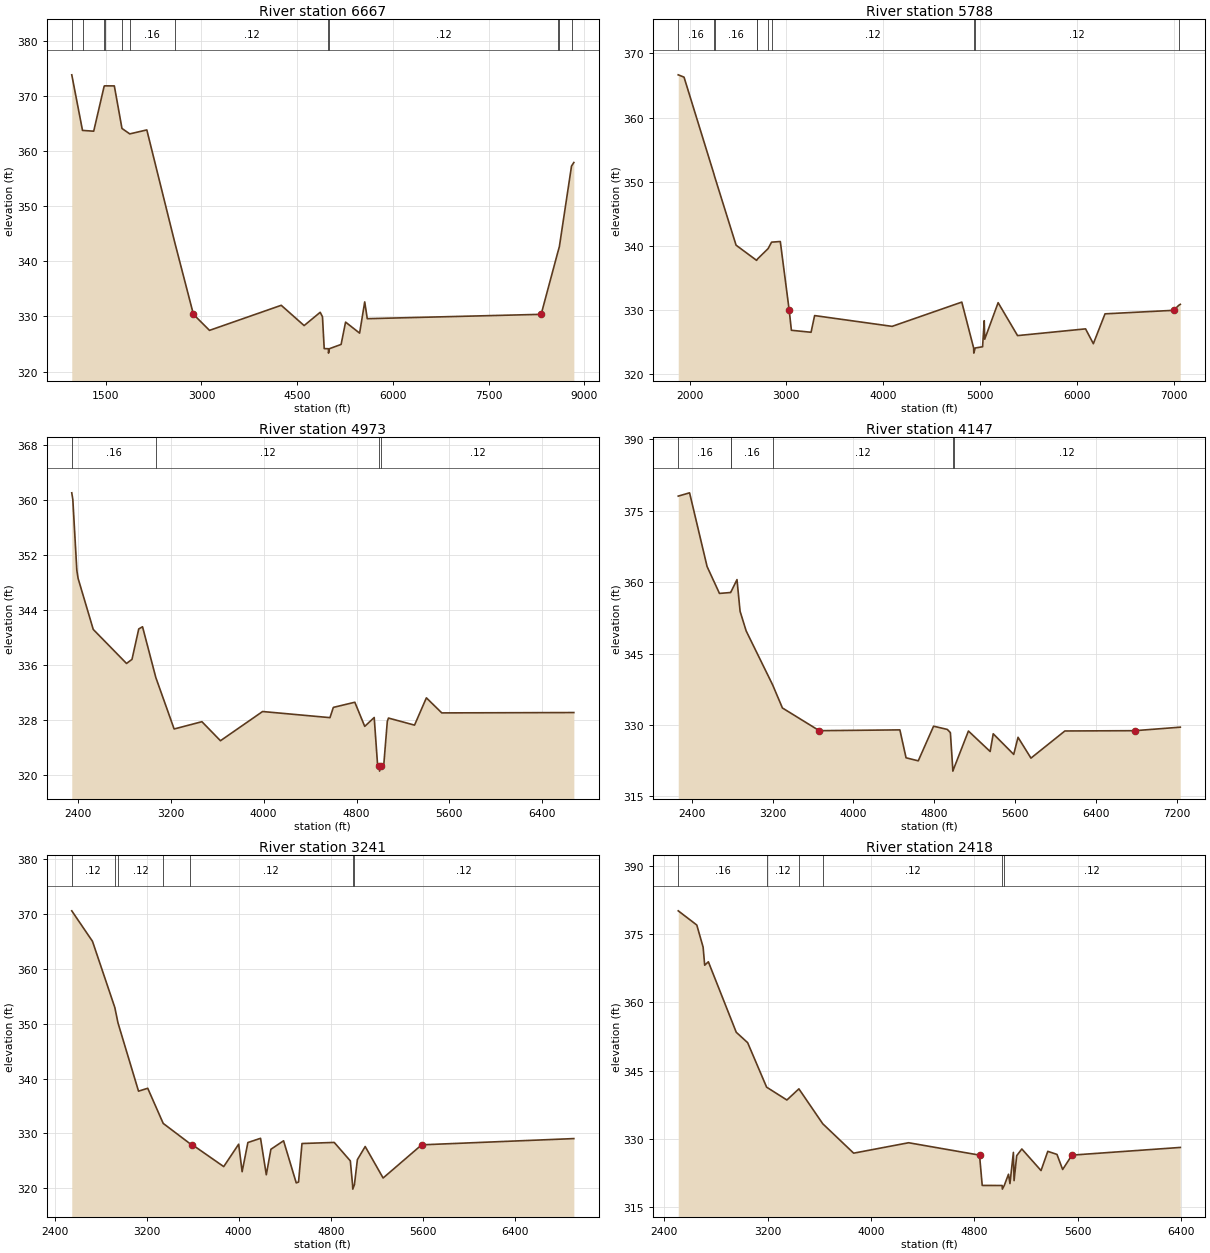
Type RM Length L Ch R = 1 ,6667    ,879,879,879
BEGIN DESCRIPTION:
GLADE CREEK 7.0
END DESCRIPTION:
XS GIS Cut Line= 3
      2913581.37      6968051.27        2910300.        6970400.
      2910356.09      6974231.55
#Sta/Elev= 30
   968.3  373.86  1136.7  363.77    1312  363.63  1476.3  371.81  1483.3  371.86
  1635.1  371.85    1755  364.13  1876.9  363.14  2144.4  363.86  2581.5  343.47
  2874.6  330.39  3126.5  327.48  4250.6  332.03  4609.3  328.35  4861.1  330.76
  4896.8  329.95  4923.8  324.17  4990.2  324.15  4991.3  323.35  5004.7  324.15
  5188.7  324.93  5258.7  328.98  5478.7  326.98  5558.7  332.65  5598.7   329.6
  8323.3  330.39  8586.4  341.75  8608.7  342.67    8799  357.29  8835.6  357.95
#Mann= 12 ,-1 , 0
   968.3     .05       0  1136.7     .16       0  1476.3     .12       0
  1483.3     .16       0    1755     .12       0  1876.9     .16       0
  2581.5     .12       0  4990.2     .07       0  5004.7     .12       0
  8586.4     .16       0  8608.7     .12       0    8799     .05       0
Bank Sta=2874.6,8323.3
XS Rating Curve= 0 ,0
Exp/Cntr=0.3,0.1

Type RM Length L Ch R = 1 ,5788    ,815,815,815
BEGIN DESCRIPTION:
GLADE CREEK 6.0
END DESCRIPTION:
XS GIS Cut Line= 3
      2912788.88      6968316.96        2909975.        6969625.
      2907900.01        6969800.
#Sta/Elev= 30
  1882.8  366.67  1942.6  366.31  2251.3  351.23  2257.9  350.86  2480.1  340.13
  2692.3  337.76    2701  337.97  2811.4   339.6  2846.7   340.6    2937   340.7
  3028.9  329.98  3051.5  326.87  3254.5  326.56  3291.4  329.16  4091.7  327.48
  4811.4  331.26  4933.8  324.11  4935.4  323.31  4949.7  324.11    5026   324.3
  5043.2  328.36  5048.2  325.48  5186.6  331.17  5387.3  326.04  6089.7  327.09
    6170  324.78  6290.5  329.43  6999.8  329.98    7052  330.76  7068.2  330.91
#Mann= 10 ,-1 , 0
  1882.8     .16       0  2251.3     .12       0  2257.9     .16       0
  2692.3     .12       0    2701      .1       0  2811.4     .16       0
  2846.7     .12       0  4933.8     .07       0  4949.7     .12       0
    7052     .07       0
Bank Sta=3028.9,6999.8
XS Rating Curve= 0 ,0
Exp/Cntr=0.3,0.1

Type RM Length L Ch R = 1 ,4973    ,826,826,826
BEGIN DESCRIPTION:
GLADE CREEK 5.0
END DESCRIPTION:
XS GIS Cut Line= 3
      2912125.04      6967874.98        2909675.        6968925.
      2908050.04      6969249.99
#Sta/Elev= 30
  2348.5  361.02  2357.6  360.04  2392.1  349.75  2402.9  348.58  2533.5  341.15
    2820   336.2  2867.1   336.8  2925.2  341.22  2957.8  341.54  3072.1  334.16
  3229.8  326.67  3469.1  327.73  3628.7  324.96  3991.4  329.21  4571.6  328.32
  4600.6  329.81  4785.6  330.56  4870.8  327.05  4952.4  328.34  4981.4  321.46
    4997  321.34  4998.7  320.54    5013  321.34  5034.5  321.39  5065.1  327.77
  5075.2  328.26  5299.6  327.23  5401.6   331.2  5534.2  329.01  6671.2  329.06
#Mann= 4 ,-1 , 0
  2348.5     .16       0  3072.1     .12       0    4997     .07       0
    5013     .12       0
Bank Sta=4997,5013
XS Rating Curve= 0 ,0
Exp/Cntr=0.3,0.1

Type RM Length L Ch R = 1 ,4147    ,906,906,906
BEGIN DESCRIPTION:
GLADE CREEK 4.0
END DESCRIPTION:
XS GIS Cut Line= 3
      2912675.01        6967675.        2909975.        6968225.
      2907899.96      6969000.01
#Sta/Elev= 30
    2266  378.06  2378.3  378.75  2551.8  363.26  2674.2  357.63  2784.6  357.82
    2785  357.82  2847.7  360.53  2878.3  353.88  2938.4  349.76  3200.8  338.42
  3297.4  333.58  3662.4  328.81  4460.2  328.98  4521.4  323.12  4642.2  322.48
  4793.9  329.75  4929.6  329.08  4960.2   328.4  4982.8  321.12  4984.5  320.32
  4998.8  321.12  5138.9  328.74  5353.9  324.44  5384.4  328.16  5587.2  323.83
  5629.9  327.42    5758  323.05  6093.7  328.75  6785.3  328.81  7236.5  329.55
#Mann= 6 ,-1 , 0
    2266     .16       0  2784.6     .05       0    2785     .16       0
  3200.8     .12       0  4982.8     .07       0  4998.8     .12       0
Bank Sta=3662.4,6785.3
XS Rating Curve= 0 ,0
Exp/Cntr=0.3,0.1

Type RM Length L Ch R = 1 ,3241    ,823,823,823
BEGIN DESCRIPTION:
GLADE CREEK 3.0
END DESCRIPTION:
XS GIS Cut Line= 3
      2912074.98        6967525.        2909625.        6967575.
      2907900.02      6968399.99
#Sta/Elev= 30
  2549.7  370.61  2729.7  365.05    2924  352.96  2951.4  350.16  3129.8  337.71
  3209.8  338.24  3344.2  331.83  3572.9   328.2  3598.3  327.92    3870  323.95
    4000  328.04    4030  323.02    4080  328.34    4190  329.11    4240  322.46
    4280  327.11  4390.1  328.66  4500.1  320.98  4520.1  321.13  4550.1  328.16
  4830.2  328.36  4970.2  324.99  4989.6  320.64  4991.4  319.84  5005.7  320.64
  5031.4  325.22  5099.4  327.61  5255.1  321.87    5590  327.92  6912.3  329.06
#Mann= 7 ,-1 , 0
  2549.7     .12       0    2924     .16       0  2951.4     .12       0
  3344.2     .16       0  3572.9     .12       0  4989.6     .07       0
  5005.7     .12       0
Bank Sta=3598.3,5590
XS Rating Curve= 0 ,0
Exp/Cntr=0.3,0.1

Type RM Length L Ch R = 1 ,2418    ,908,908,908
BEGIN DESCRIPTION:
GLADE CREEK 2.0
END DESCRIPTION:
XS GIS Cut Line= 3
       2912235.1      6967272.84        2909825.        6966875.
      2908444.43      6967300.28
#Sta/Elev= 30
  2507.4  380.11  2651.1  376.99  2700.1  372.12  2712.2  368.16  2740.6  368.92
  2956.6  353.43  3044.7  351.15  3191.7  341.37  3348.7  338.55  3441.6     341
  3626.3  333.33  3865.6  326.87  4291.3  329.16  4840.1  326.44    4861  319.78
  5015.1  319.77    5017  318.97  5031.6  319.77  5064.5  322.24  5075.7  320.19
  5102.4  327.04  5107.6  320.84    5128  326.32  5167.8  327.79  5316.3  323.05
  5368.7  327.27  5439.7   326.6  5483.8  323.28  5555.8  326.44  6394.7  328.13
#Mann= 6 ,-1 , 0
  2507.4     .16       0  3191.7     .12       0  3441.6     .16       0
  3626.3     .12       0  5015.1     .07       0  5031.6     .12       0
Bank Sta=4840.1,5555.8
XS Rating Curve= 0 ,0
Exp/Cntr=0.3,0.1

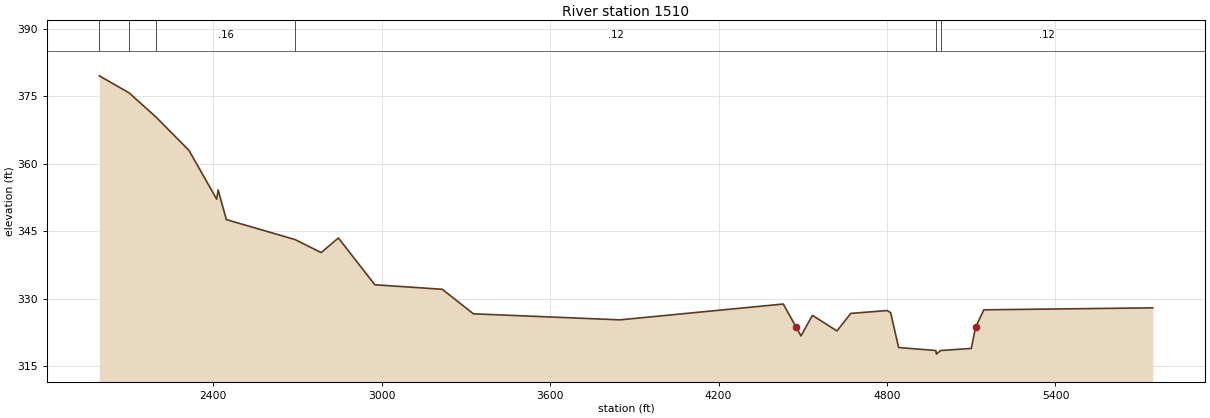
Type RM Length L Ch R = 1 ,1510    ,0,0,0
BEGIN DESCRIPTION:
GLADE CREEK 1.0
END DESCRIPTION:
XS GIS Cut Line= 3
      2912287.13      6967059.29        2909375.        6966425.
      2908699.99      6966800.01
#Sta/Elev= 30
    1994   379.6    2100  375.81  2196.6  370.38  2313.5  362.99  2412.1  352.14
  2417.2  354.21  2446.5   347.6  2691.6  343.15  2784.2  340.26  2845.6  343.51
  2975.5   333.1  3215.8  332.09  3326.7  326.63  3848.6  325.29  4430.5  328.81
  4476.4  323.63  4493.4  321.72  4534.3  326.29  4621.7  322.81  4670.7  326.72
  4800.4  327.36  4812.9  326.88  4841.4  319.13    4974  318.46    4976  317.66
  4990.8  318.46  5100.2  318.93  5115.4  323.63  5144.9  327.52  5746.6  327.96
#Mann= 6 ,-1 , 0
    1994     .16       0    2100     .12       0  2196.6     .16       0
  2691.6     .12       0    4974     .07       0  4990.8     .12       0
Bank Sta=4476.4,5115.4
XS Rating Curve= 0 ,0
Exp/Cntr=0.3,0.1
LCMann Table=0

Chan Stop Cuts=-1
Use User Specified Reach Order=0
Composite Channel Slope=5