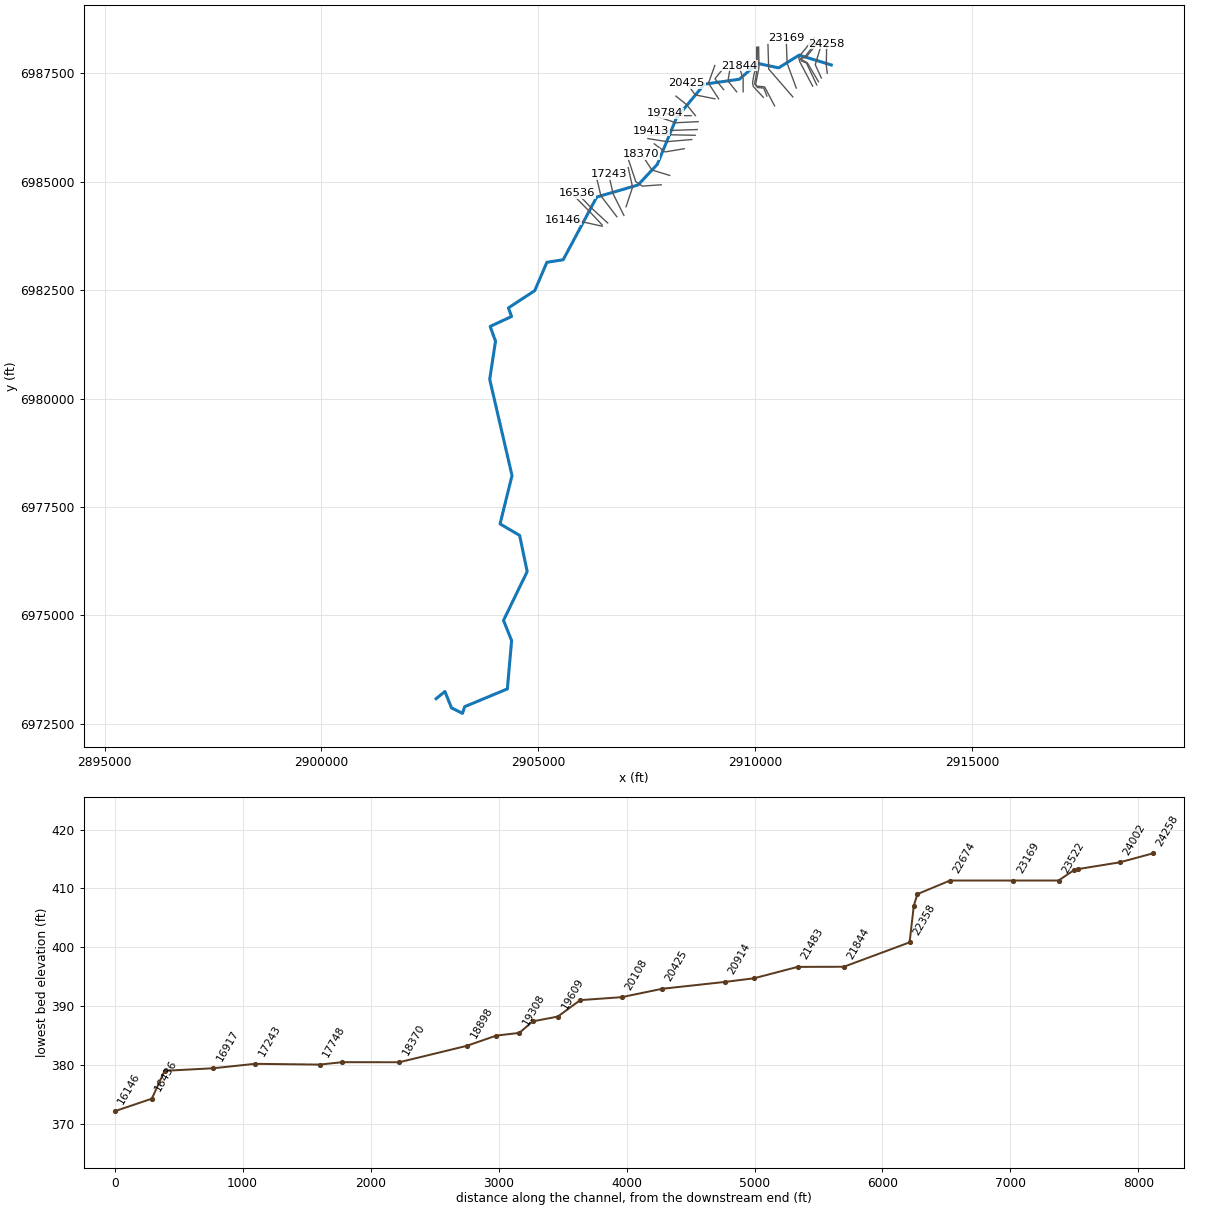
--- GRAVEYARD BRANCH.prj (project) ---

Proj Title=GRAVEYARD BRANCH Base Level Engineering
Current Plan=p01
Default Exp/Contr=0.3,0.1
English Units
Geom File=g01
Flow File=f01
Plan File=p01
BEGIN DESCRIPTION:
GRAVEYARD BRANCH
END DESCRIPTION:

--- GRAVEYARD BRANCH.p01 (plan) ---

Plan Title=Multiple Run
Short Identifier=Multiple
Geom File=g01
Flow File=f01
Subcritical Flow
K Sum by GR= 0
Std Step Tol= 0.01
Critical Tol= 0.01
Num of Std Step Trials= 20
Max Error Tol= 0.3
Flow Tol Ratio= 0.001
Split Flow NTrial= 30
Split Flow Tol= 0.02
Split Flow Ratio= 0.02
Log Output Level= 0
Friction Slope Method= 1
Unsteady Friction Slope Method= 2
Unsteady Bridges Friction Slope Method= 1
Parabolic Critical Depth
Global Vel Dist=  1 , 1 , 1
Global Log Level= 0
CheckData=True
Encroach Param= -1, 0, 0, 0
BEGIN DESCRIPTION:
Multiple Run
END DESCRIPTION:

--- GRAVEYARD BRANCH.f01 (steady flow) ---

Flow Title=Multiple
Number of Profiles=7
Profile Names=10-year,25-year,50-year,1pct_min,100-year,1pct_plu,500-year
River Rch & RM= GRAVEYARD BRANCH,Reach-1,24258
     275     348     403     233     464     926     616
River Rch & RM= GRAVEYARD BRANCH,Reach-1,22358
     472     619     735     434     866    1728    1203
River Rch & RM= GRAVEYARD BRANCH,Reach-1,17748
     728     977    1178     706    1408    2809    2014
River Rch & RM= GRAVEYARD BRANCH,Reach-1,11565
     940    1273    1545     929    1854    3699    2678
River Rch & RM= GRAVEYARD BRANCH,Reach-1,6261
    1079    1477    1806    1094    2183    4356    3199
Boundary for River Rch & Prof#=GRAVEYARD BRANCH,Reach-1,1
Up Type=0
Dn Type=3
Dn Slope=0.005
Boundary for River Rch & Prof#=GRAVEYARD BRANCH,Reach-1,2
Up Type=0
Dn Type=3
Dn Slope=0.005
Boundary for River Rch & Prof#=GRAVEYARD BRANCH,Reach-1,3
Up Type=0
Dn Type=3
Dn Slope=0.005
Boundary for River Rch & Prof#=GRAVEYARD BRANCH,Reach-1,4
Up Type=0
Dn Type=3
Dn Slope=0.005
Boundary for River Rch & Prof#=GRAVEYARD BRANCH,Reach-1,5
Up Type=0
Dn Type=3
Dn Slope=0.005
Boundary for River Rch & Prof#=GRAVEYARD BRANCH,Reach-1,6
Up Type=0
Dn Type=3
Dn Slope=0.005
Boundary for River Rch & Prof#=GRAVEYARD BRANCH,Reach-1,7
Up Type=0
Dn Type=3
Dn Slope=0.005

--- GRAVEYARD BRANCH.g01 (geometry) ---

Geom Title=Existing Conditions

River Reach=GRAVEYARD BRANCH,Reach-1
Reach XY= 30
      2911756.88      6987694.31      2911015.59      6987920.71
      2910545.04      6987627.15      2910055.90      6987730.02
      2909638.39      6987365.01      2908830.63      6987250.63
      2908186.10      6986471.55      2907744.54      6985400.44
      2907299.81      6984925.54      2906348.42      6984647.76
      2905574.81      6983201.46      2905199.78      6983142.92
      2904919.12      6982489.37      2904311.29      6982091.33
      2904384.27      6981893.01      2903890.92      6981663.69
      2904014.28      6981323.33      2903880.41      6980443.55
      2904395.17      6978224.80      2904119.13      6977110.22
      2904570.08      6976845.90      2904744.68      6976011.16
      2904198.59      6974884.66      2904385.67      6974421.21
      2904287.41      6973304.83      2903303.10      6972895.48
      2903252.14      6972740.77      2902999.19      6972867.38
      2902848.24      6973245.27      2902645.59      6973080.71

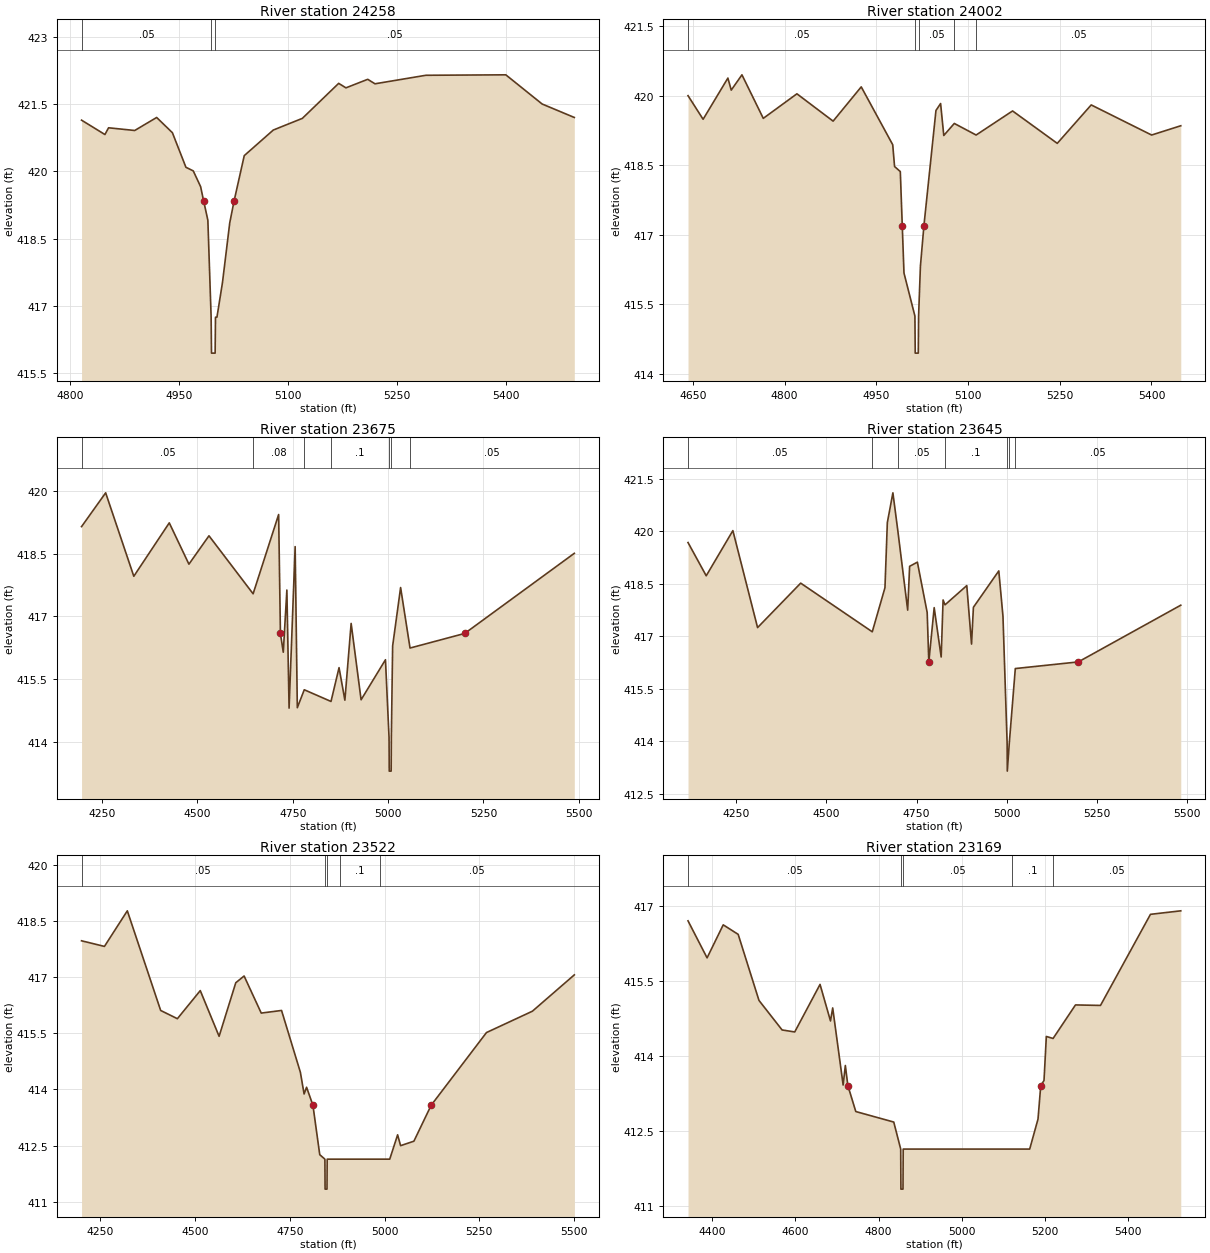
Type RM Length L Ch R = 1,24258,256,256,256
BEGIN DESCRIPTION:
GRAVEYARD BRANCH 43.0
END DESCRIPTION:
XS GIS Cut Line= 3
      2911664.27      6987502.27      2911642.70      6987684.79
      2911651.25      6988179.32
#Sta/Elev= 30
  4816.2  421.14  4848.4  420.82  4853.4  420.97  4889.4  420.91  4919.6  421.20
  4941.3  420.86  4959.9  420.09  4970.0  420.01  4980.1  419.66  4984.3  419.34
  4990.1  418.91  4994.6  416.75  4995.1  415.95  5000.1  415.95  5000.6  416.75
  5002.6  416.75  5010.2  417.52  5020.2  418.85  5026.2  419.34  5040.2  420.35
  5080.2  420.92  5120.2  421.18  5170.2  421.96  5180.2  421.86  5210.2  422.05
  5220.2  421.95  5290.2  422.14  5400.3  422.15  5450.3  421.50  5494.6  421.20
#Mann=3,-1,0
  4816.2    0.05       0  4994.6    0.03       0  5000.6    0.05       0
Bank Sta=4984.3,5026.2
Exp/Cntr=0.3,0.1

Type RM Length L Ch R = 1,24002,327,327,327
BEGIN DESCRIPTION:
Mapping XS 02f7b613
END DESCRIPTION:
XS GIS Cut Line= 3
      2911528.22      6987393.08      2911387.58      6987700.41
      2911522.99      6988148.31
#Sta/Elev= 30
  4642.0  420.00  4666.7  419.49  4707.2  420.38  4712.7  420.12  4730.2  420.45
  4765.1  419.51  4820.1  420.04  4879.3  419.45  4925.3  420.19  4976.8  418.94
  4979.8  418.47  4989.2  418.36  4992.4  417.19  4995.2  416.17  5013.1  415.24
  5013.6  414.44  5018.6  414.44  5019.1  415.24  5022.1  416.32  5027.8  417.19
  5047.5  419.68  5055.1  419.83  5060.3  419.14  5077.5  419.40  5113.2  419.15
  5172.8  419.67  5245.9  418.97  5301.4  419.80  5400.2  419.15  5447.9  419.35
#Mann=5,-1,0
  4642.0    0.05       0  5013.1    0.03       0  5019.1    0.05       0
  5077.5    0.08       0  5113.2    0.05       0
Bank Sta=4992.4,5027.8
Exp/Cntr=0.3,0.1

Type RM Length L Ch R = 1,23675,30,30,30
BEGIN DESCRIPTION:
Mapping XS 677eca24
END DESCRIPTION:
XS GIS Cut Line= 6
      2911463.11      6987307.17      2911205.29      6987742.08
      2911067.27      6987822.80      2911080.29      6987861.87
      2911168.83      6987864.47      2911480.66      6988249.06
#Sta/Elev= 30
  4196.2  419.15  4259.4  419.96  4333.2  417.96  4426.2  419.24  4477.7  418.25
  4530.3  418.93  4646.0  417.54  4712.9  419.44  4717.6  416.59  4725.1  416.14
  4734.5  417.63  4740.3  414.80  4756.2  418.67  4761.9  414.81  4780.1  415.24
  4850.2  414.96  4871.3  415.77  4886.6  414.99  4903.0  416.83  4929.1  415.00
  4993.0  415.96  5002.4  414.09  5002.9  413.29  5007.9  413.29  5008.4  414.09
  5011.8  416.29  5032.7  417.69  5057.4  416.24  5200.8  416.59  5488.1  418.51
#Mann=7,-1,0
  4196.2    0.05       0  4646.0    0.08       0  4780.1    0.05       0
  4850.2     0.1       0  5002.4    0.07       0  5008.4     0.1       0
  5057.4    0.05       0
Bank Sta=4717.6,5200.8
Exp/Cntr=0.3,0.1

Type RM Length L Ch R = 1,23645,123,123,123
BEGIN DESCRIPTION:
Mapping XS f25e5356
END DESCRIPTION:
XS GIS Cut Line= 6
      2911421.42      6987234.30      2911184.46      6987739.47
      2911067.27      6987786.35      2911046.44      6987843.64
      2911145.39      6987877.49      2911455.27      6988275.91
#Sta/Elev= 30
  4116.3  419.68  4166.8  418.73  4240.7  420.02  4309.2  417.25  4428.8  418.52
  4627.3  417.13  4662.5  418.39  4669.1  420.25  4684.5  421.10  4698.4  420.00
  4725.5  417.75  4730.9  419.00  4752.4  419.12  4779.6  417.68  4784.1  416.27
  4799.0  417.82  4818.4  416.41  4823.7  418.04  4829.0  417.90  4889.4  418.45
  4902.6  416.78  4907.8  417.83  4978.2  418.87  4989.8  417.57  5001.3  413.95
  5001.8  413.15  5007.3  413.95  5024.0  416.08  5198.8  416.27  5482.9  417.89
#Mann=7,-1,0
  4116.3    0.05       0  4627.3    0.08       0  4698.4    0.05       0
  4829.0     0.1       0  5001.3    0.07       0  5007.3     0.1       0
  5024.0    0.05       0
Bank Sta=4784.1,5198.8
Exp/Cntr=0.3,0.1

Type RM Length L Ch R = 1,23522,353,353,353
BEGIN DESCRIPTION:
Mapping XS 7fbe4a0a
END DESCRIPTION:
XS GIS Cut Line= 5
      2911327.68      6987205.63      2911033.41      6987762.91
      2911007.37      6987851.45      2911036.02      6987916.55
      2911358.91      6988307.15
#Sta/Elev= 30
  4200.5  417.97  4260.9  417.82  4321.3  418.77  4409.3  416.11  4453.4  415.89
  4513.8  416.64  4563.5  415.42  4607.5  416.85  4629.5  417.03  4674.7  416.04
  4728.3  416.11  4778.0  414.46  4787.8  413.88  4794.3  414.06  4811.1  413.58
  4829.1  412.26  4842.7  412.14  4843.2  411.34  4848.2  411.34  4848.7  412.14
  4882.1  412.14  4987.4  412.14  5013.8  412.14  5034.6  412.79  5042.5  412.50
  5077.6  412.62  5123.2  413.58  5269.1  415.52  5390.3  416.09  5500.9  417.06
#Mann=5,-1,0
  4200.5    0.05       0  4842.7    0.03       0  4848.7    0.05       0
  4882.1     0.1       0  4987.4    0.05       0
Bank Sta=4811.1,5123.2
Exp/Cntr=0.3,0.1

Type RM Length L Ch R = 1,23169,495,495,495
BEGIN DESCRIPTION:
Mapping XS dfac3df2
END DESCRIPTION:
XS GIS Cut Line= 3
      2910949.85      6987162.03      2910738.93      6987732.31
      2910718.09      6988307.79
#Sta/Elev= 30
  4342.0  416.70  4387.8  415.96  4426.6  416.62  4462.5  416.43  4512.5  415.11
  4568.0  414.52  4598.4  414.48  4659.2  415.43  4684.3  414.70  4689.6  414.96
  4714.7  413.42  4720.0  413.81  4726.0  413.41  4745.1  412.89  4836.3  412.68
  4853.0  412.14  4853.5  411.34  4858.5  411.34  4859.0  412.14  5121.3  412.14
  5162.9  412.14  5182.9  412.74  5189.5  413.41  5197.3  413.51  5202.9  414.39
  5219.1  414.35  5272.9  415.02  5333.0  415.01  5453.1  416.83  5525.9  416.90
#Mann=5,-1,0
  4342.0    0.05       0  4853.0   0.033       0  4859.0    0.05       0
  5121.3     0.1       0  5219.1    0.05       0
Bank Sta=4726,5189.5
Exp/Cntr=0.3,0.1

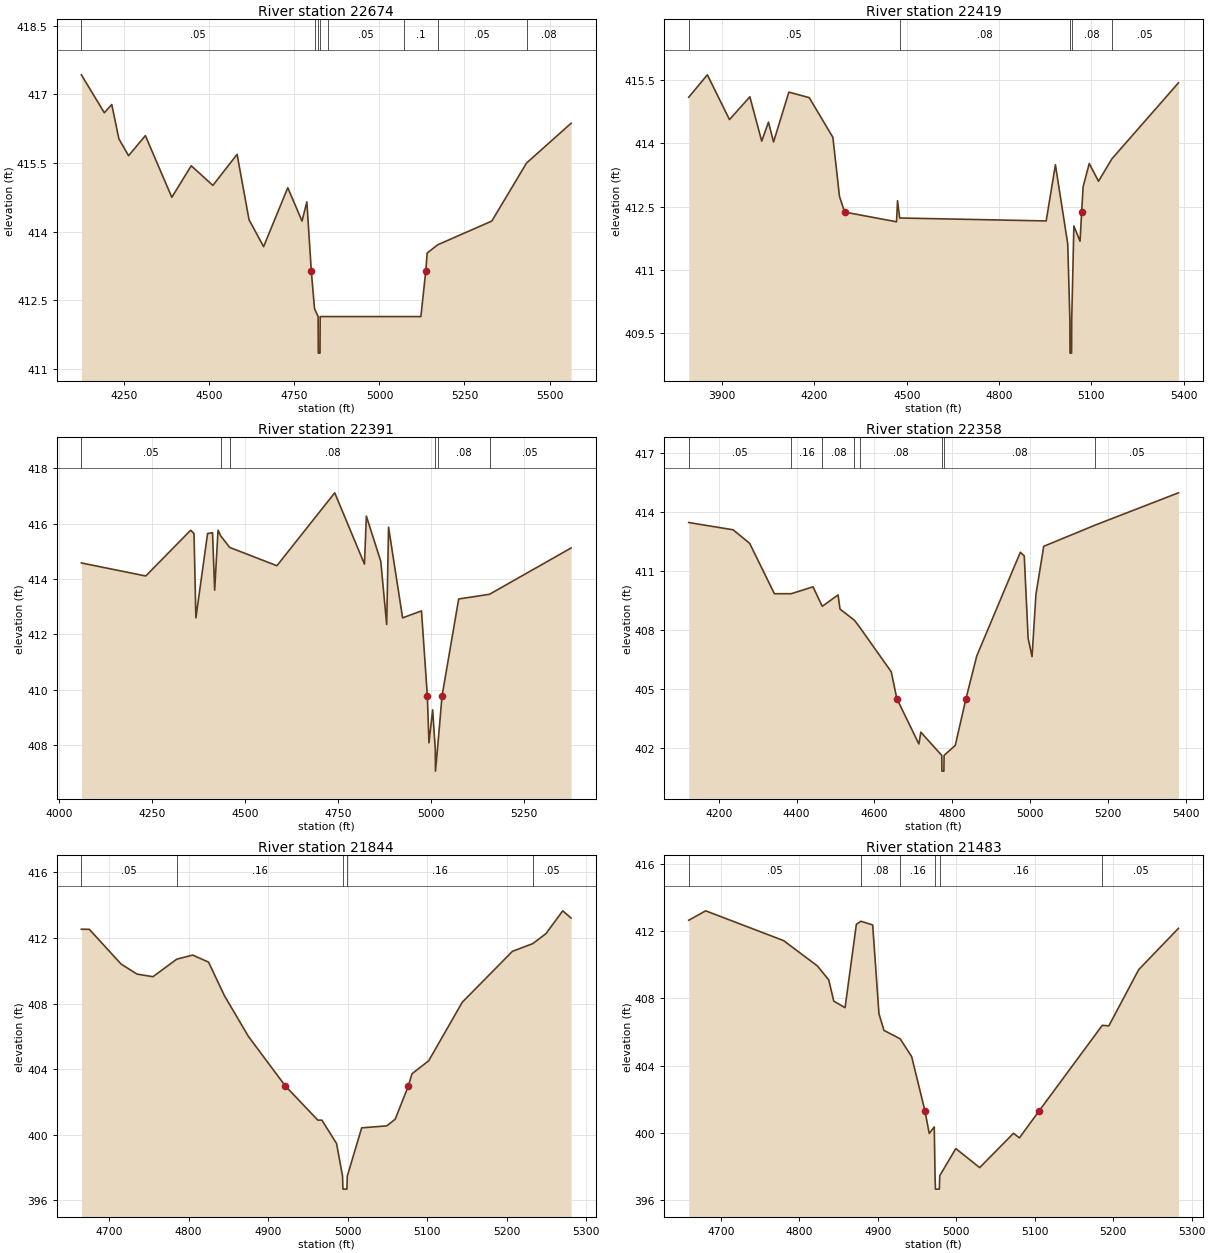
Type RM Length L Ch R = 1,22674,255,255,255
BEGIN DESCRIPTION:
Mapping XS 3afb9c68
END DESCRIPTION:
XS GIS Cut Line= 3
      2910871.75      6986956.25      2910314.45      6987599.50
      2910296.22      6988188.03
#Sta/Elev= 30
  4123.6  417.43  4191.0  416.60  4212.9  416.78  4233.8  416.03  4262.3  415.66
  4311.7  416.10  4389.5  414.75  4446.5  415.44  4510.2  415.01  4581.4  415.69
  4616.5  414.26  4659.3  413.67  4730.5  414.96  4772.3  414.23  4786.5  414.65
  4799.7  413.13  4809.1  412.31  4819.7  412.14  4820.2  411.34  4825.2  411.34
  4825.7  412.14  4848.6  412.14  5073.1  412.14  5121.8  412.14  5136.1  413.13
  5140.3  413.53  5171.0  413.71  5330.4  414.23  5432.5  415.50  5563.5  416.37
#Mann=8,-1,0
  4123.6    0.05       0  4809.1    0.16       0  4819.7   0.033       0
  4825.7    0.16       0  4848.6    0.05       0  5073.1     0.1       0
  5171.0    0.05       0  5432.5    0.08       0
Bank Sta=4799.7,5136.1
Exp/Cntr=0.3,0.1

Type RM Length L Ch R = 1,22419,28,28,28
BEGIN DESCRIPTION:
Mapping XS 47155e34
END DESCRIPTION:
XS GIS Cut Line= 6
      2910449.99      6986750.03      2910220.70      6987188.04
      2910041.01      6987206.27      2910012.36      6987242.73
      2910090.49      6987641.16      2910082.68      6988104.66
#Sta/Elev= 30
  3791.5  415.09  3852.0  415.62  3923.9  414.56  3990.1  415.10  4028.6  414.05
  4050.6  414.50  4067.1  414.03  4116.9  415.21  4183.1  415.08  4259.9  414.14
  4281.4  412.74  4298.1  412.37  4466.8  412.14  4470.0  412.64  4477.0  412.23
  4953.1  412.16  4983.1  413.49  5023.1  411.62  5030.1  409.83  5030.6  409.03
  5035.6  409.03  5036.1  409.83  5043.1  412.04  5063.1  411.68  5068.4  412.37
  5073.1  412.97  5093.1  413.52  5123.1  413.10  5166.6  413.63  5382.9  415.43
#Mann=5,-1,0
  3791.5    0.05       0  4477.0    0.08       0  5030.1    0.07       0
  5036.1    0.08       0  5166.6    0.05       0
Bank Sta=4298.1,5068.4
Exp/Cntr=0.3,0.1

Type RM Length L Ch R = 1,22391,33,33,33
BEGIN DESCRIPTION:
Mapping XS ef283e86
END DESCRIPTION:
XS GIS Cut Line= 6
      2910272.78      6986977.10      2910199.86      6987162.00
      2910059.24      6987172.41      2909988.93      6987258.35
      2910067.05      6987711.48      2910059.24      6988107.30
#Sta/Elev= 30
  4059.2  414.58  4232.3  414.11  4353.1  415.76  4362.2  415.64  4367.2  412.60
  4398.6  415.64  4412.0  415.67  4417.7  413.60  4426.8  415.76  4434.3  415.55
  4458.2  415.14  4585.1  414.48  4740.7  417.11  4820.7  414.54  4825.8  416.27
  4864.6  414.64  4880.5  412.36  4885.5  415.87  4923.3  412.60  4974.1  412.85
  4989.9  409.78  4994.2  408.09  5004.2  409.28  5011.2  407.87  5011.7  407.07
  5017.2  407.87  5029.4  409.78  5074.2  413.28  5157.1  413.45  5376.6  415.12
#Mann=6,-1,0
  4059.2    0.05       0  4434.3    0.16       0  4458.2    0.08       0
  5011.2    0.07       0  5017.2    0.08       0  5157.1    0.05       0
Bank Sta=4989.9,5029.4
Exp/Cntr=0.3,0.1

Type RM Length L Ch R = 1,22358,514,514,514
BEGIN DESCRIPTION:
Mapping XS 22d46bc3
END DESCRIPTION:
XS GIS Cut Line= 6
      2910189.43      6986948.47      2909957.68      6987198.46
      2909942.05      6987284.39      2909975.91      6987484.91
      2910035.80      6987659.39      2910035.80      6988101.03
#Sta/Elev= 30
  4123.0  413.47  4237.0  413.10  4279.5  412.41  4343.0  409.85  4386.0  409.85
  4442.2  410.20  4465.9  409.21  4506.5  409.79  4511.5  409.07  4548.6  408.50
  4562.7  408.13  4643.1  405.88  4657.4  404.52  4714.1  402.21  4719.1  402.81
  4772.8  401.63  4773.3  400.83  4778.3  400.83  4778.8  401.63  4807.5  402.14
  4835.1  404.52  4862.6  406.68  4974.7  411.96  4984.7  411.77  4994.7  407.58
  5004.7  406.65  5014.7  409.81  5034.7  412.26  5166.9  413.34  5380.7  414.98
#Mann=8,-1,0
  4123.0    0.05       0  4386.0    0.16       0  4465.9    0.08       0
  4548.6    0.16       0  4562.7    0.08       0  4772.8    0.07       0
  4778.8    0.08       0  5166.9    0.05       0
Bank Sta=4657.4,4835.1
Exp/Cntr=0.3,0.1

Type RM Length L Ch R = 1,21844,361,361,361
BEGIN DESCRIPTION:
GRAVEYARD BRANCH 39.0
END DESCRIPTION:
XS GIS Cut Line= 3
      2909725.00      6987075.00      2909725.00      6987375.00
      2909625.01      6987674.97
#Sta/Elev= 30
  4665.0  412.54  4675.0  412.53  4715.0  410.41  4735.0  409.80  4755.0  409.64
  4785.0  410.71  4805.0  410.96  4825.0  410.53  4845.0  408.48  4875.0  406.01
  4921.7  402.97  4962.5  400.89  4967.6  400.89  4986.1  399.46  4993.6  397.48
  4994.1  396.68  4999.1  396.68  4999.6  397.48  5017.7  400.42  5049.3  400.54
  5059.9  400.95  5076.4  402.97  5081.0  403.72  5102.0  404.51  5144.2  408.08
  5207.4  411.19  5233.0  411.66  5249.6  412.27  5270.7  413.66  5281.2  413.22
#Mann=5,-1,0
  4665.0    0.05       0  4785.0    0.16       0  4993.6    0.07       0
  4999.6    0.16       0  5233.0    0.05       0
Bank Sta=4921.7,5076.4
Exp/Cntr=0.3,0.1

Type RM Length L Ch R = 1,21483,341,341,341
BEGIN DESCRIPTION:
GRAVEYARD BRANCH 38.0
END DESCRIPTION:
XS GIS Cut Line= 3
      2909575.01      6987074.98      2909375.00      6987325.00
      2909425.00      6987624.98
#Sta/Elev= 30
  4658.9  412.65  4680.5  413.21  4779.8  411.44  4823.0  409.93  4837.4  409.10
  4843.8  407.84  4858.2  407.45  4872.6  412.41  4878.5  412.59  4893.4  412.37
  4901.4  407.09  4907.8  406.10  4928.4  405.60  4943.1  404.54  4960.0  401.32
  4965.5  399.97  4971.9  400.36  4972.9  397.46  4973.4  396.66  4978.4  396.66
  4978.9  397.46  4999.4  399.07  5029.8  397.94  5072.9  399.98  5080.5  399.71
  5105.7  401.32  5186.1  406.40  5194.5  406.37  5232.5  409.71  5283.2  412.17
#Mann=6,-1,0
  4658.9    0.05       0  4878.5    0.08       0  4928.4    0.16       0
  4972.9    0.07       0  4978.9    0.16       0  5186.1    0.05       0
Bank Sta=4960,5105.7
Exp/Cntr=0.3,0.1

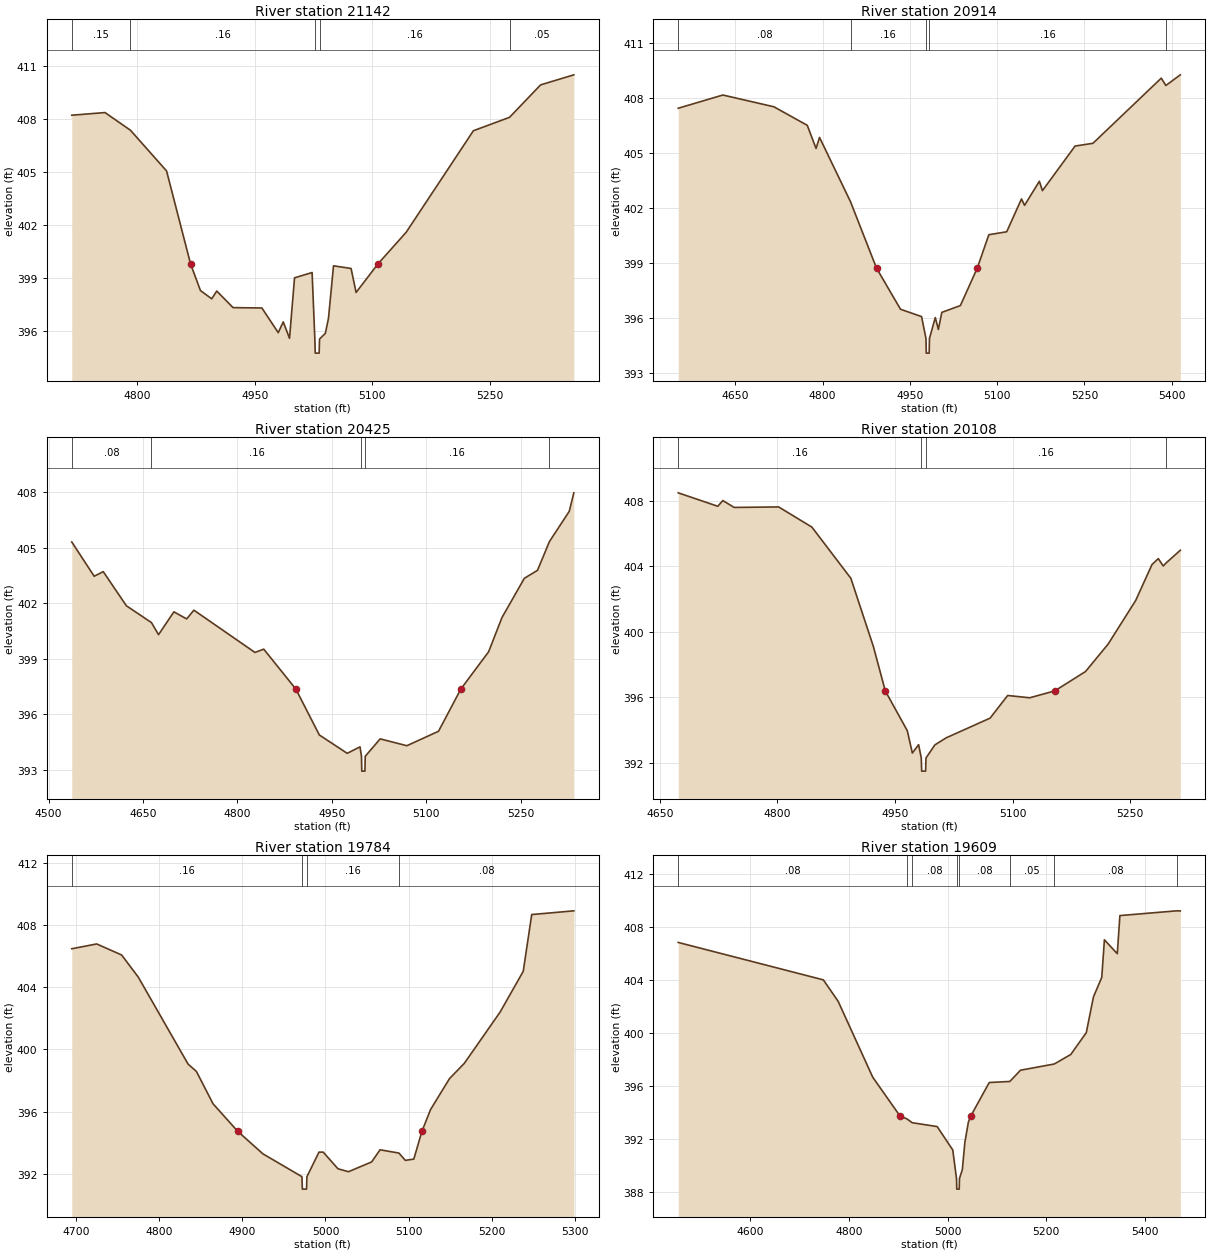
Type RM Length L Ch R = 1,21142,228,228,228
BEGIN DESCRIPTION:
GRAVEYARD BRANCH 37.0
END DESCRIPTION:
XS GIS Cut Line= 3
      2909275.00      6987125.00      2909075.00      6987375.00
      2909274.99      6987624.99
#Sta/Elev= 30
  4716.7  408.21  4759.1  408.36  4791.5  407.36  4837.6  405.05  4868.2  399.78
  4880.8  398.27  4895.2  397.80  4901.6  398.24  4922.4  397.30  4959.2  397.28
  4980.0  395.88  4986.4  396.49  4994.4  395.56  5000.8  398.99  5023.2  399.29
  5026.7  395.52  5027.2  394.72  5032.2  394.72  5032.7  395.52  5040.1  395.84
  5044.1  396.70  5050.5  399.67  5072.9  399.52  5079.3  398.16  5107.2  399.78
  5143.3  401.58  5228.9  407.33  5275.0  408.09  5314.6  409.93  5357.0  410.50
#Mann=5,-1,0
  4716.7    0.15       0  4791.5    0.16       0  5026.7    0.07       0
  5032.7    0.16       0  5275.0    0.05       0
Bank Sta=4868.2,5107.2
Exp/Cntr=0.3,0.1

Type RM Length L Ch R = 1,20914,489,489,489
BEGIN DESCRIPTION:
GRAVEYARD BRANCH 36.0
END DESCRIPTION:
XS GIS Cut Line= 3
      2909159.92      6986912.88      2908925.00      6987275.00
      2909071.18      6987680.51
#Sta/Elev= 30
  4552.1  407.44  4628.8  408.16  4716.4  407.52  4773.8  406.51  4788.9  405.25
  4794.9  405.85  4848.1  402.35  4892.8  398.73  4934.0  396.49  4970.2  396.09
  4977.8  394.90  4978.3  394.10  4983.3  394.10  4983.8  394.90  4993.8  396.04
  4999.1  395.39  5005.0  396.32  5036.9  396.69  5065.9  398.73  5085.8  400.55
  5116.5  400.71  5141.9  402.50  5147.2  402.15  5172.6  403.46  5177.9  402.95
  5234.0  405.38  5264.7  405.53  5382.1  409.08  5390.0  408.68  5414.8  409.26
#Mann=5,-1,0
  4552.1    0.08       0  4848.1    0.16       0  4977.8    0.07       0
  4983.8    0.16       0  5390.0    0.05       0
Bank Sta=4892.8,5065.9
Exp/Cntr=0.3,0.1

Type RM Length L Ch R = 1,20425,317,317,317
BEGIN DESCRIPTION:
GRAVEYARD BRANCH 35.0
END DESCRIPTION:
XS GIS Cut Line= 3
      2909074.02      6986912.86      2908619.75      6987003.36
      2908425.02      6987274.97
#Sta/Elev= 30
  4536.8  405.30  4572.4  403.45  4586.8  403.70  4623.5  401.86  4663.4  400.95
  4674.6  400.30  4699.0  401.53  4719.3  401.15  4730.8  401.62  4827.8  399.34
  4841.7  399.52  4892.6  397.37  4930.0  394.89  4974.3  393.90  4994.6  394.25
  4996.9  393.74  4997.4  392.94  5002.4  392.94  5002.9  393.74  5026.6  394.68
  5069.0  394.31  5119.3  395.09  5154.8  397.37  5198.9  399.38  5220.0  401.22
  5255.6  403.34  5276.5  403.77  5295.4  405.32  5326.9  406.95  5334.2  407.95
#Mann=5,-1,0
  4536.8    0.08       0  4663.4    0.16       0  4996.9    0.07       0
  5002.9    0.16       0  5295.4    0.05       0
Bank Sta=4892.6,5154.8
Exp/Cntr=0.3,0.1

Type RM Length L Ch R = 1,20108,324,324,324
BEGIN DESCRIPTION:
GRAVEYARD BRANCH 34.0
END DESCRIPTION:
XS GIS Cut Line= 3
      2908625.03      6986524.97      2908425.00      6986775.00
      2908174.97      6986975.03
#Sta/Elev= 30
  4673.5  408.47  4724.0  407.65  4730.4  408.00  4744.8  407.58  4801.6  407.61
  4844.0  406.38  4893.7  403.26  4922.5  399.09  4937.6  396.40  4965.7  393.97
  4972.1  392.61  4980.1  393.12  4983.5  392.31  4984.0  391.51  4989.0  391.51
  4989.5  392.31  5000.9  393.11  5015.3  393.54  5071.3  394.74  5093.7  396.12
  5121.8  395.98  5153.8  396.40  5193.0  397.58  5221.8  399.25  5257.0  401.91
  5277.8  404.10  5285.8  404.46  5292.2  404.01  5295.4  404.18  5313.9  404.97
#Mann=4,-1,0
  4673.5    0.16       0  4983.5    0.07       0  4989.5    0.16       0
  5295.4    0.05       0
Bank Sta=4937.6,5153.8
Exp/Cntr=0.3,0.1

Type RM Length L Ch R = 1,19784,175,175,175
BEGIN DESCRIPTION:
GRAVEYARD BRANCH 33.0
END DESCRIPTION:
XS GIS Cut Line= 3
      2908525.04      6986525.00      2908225.00      6986525.00
      2907924.98      6986575.00
#Sta/Elev= 30
  4694.7  406.47  4724.7  406.78  4754.7  406.07  4774.7  404.65  4834.7  399.05
  4844.7  398.58  4864.7  396.50  4894.4  394.73  4924.7  393.28  4971.7  391.81
  4972.2  391.01  4977.2  391.01  4977.7  391.81  4992.2  393.39  4997.3  393.39
  5015.0  392.32  5027.7  392.13  5055.6  392.76  5065.7  393.54  5088.4  393.33
  5096.1  392.86  5106.3  392.94  5116.1  394.73  5126.5  396.13  5149.3  398.12
  5167.1  399.10  5210.2  402.40  5238.0  405.02  5248.2  408.67  5298.9  408.91
#Mann=4,-1,0
  4694.7    0.16       0  4971.7    0.07       0  4977.7    0.16       0
  5088.4    0.08       0
Bank Sta=4894.4,5116.1
Exp/Cntr=0.3,0.1

Type RM Length L Ch R = 1,19609,196,196,196
BEGIN DESCRIPTION:
Mapping XS 4fc76198
END DESCRIPTION:
XS GIS Cut Line= 3
      2908688.58      6986386.82      2908169.92      6986360.78
      2907698.46      6986520.82
#Sta/Elev= 30
  4454.3  406.86  4748.3  404.03  4778.3  402.41  4848.4  396.67  4903.4  393.75
  4917.6  393.52  4928.4  393.23  4978.9  392.94  5010.5  391.17  5018.1  389.01
  5018.6  388.21  5023.6  388.21  5024.1  389.01  5029.9  389.69  5035.1  391.77
  5042.2  393.29  5047.2  393.75  5084.4  396.27  5126.1  396.35  5147.8  397.20
  5216.2  397.67  5249.6  398.39  5281.0  400.04  5295.6  402.75  5312.4  404.22
  5317.7  407.06  5343.8  406.01  5349.1  408.89  5464.0  409.25  5471.5  409.24
#Mann=8,-1,0
  4454.3    0.08       0  4917.6    0.05       0  4928.4    0.08       0
  5018.1    0.07       0  5024.1    0.08       0  5126.1    0.05       0
  5216.2    0.08       0  5464.0     0.1       0
Bank Sta=4903.4,5047.2
Exp/Cntr=0.3,0.1

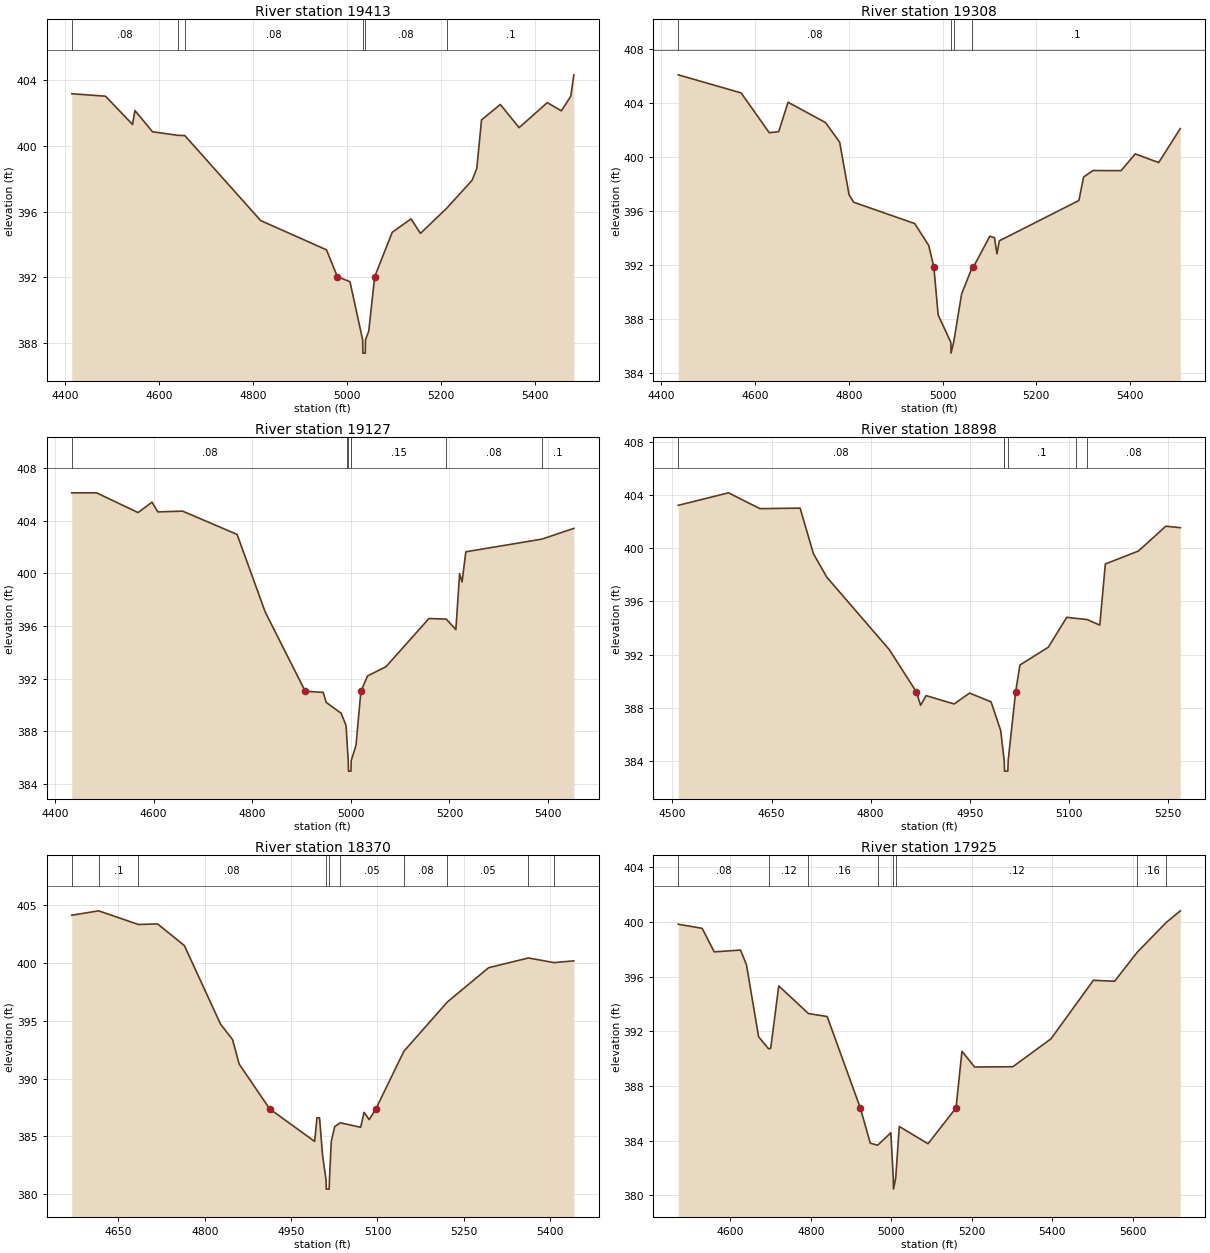
Type RM Length L Ch R = 1,19413,105,105,105
BEGIN DESCRIPTION:
Mapping XS 216692a0
END DESCRIPTION:
XS GIS Cut Line= 3
      2908666.83      6986204.53      2908098.30      6986185.00
      2907598.49      6986180.67
#Sta/Elev= 30
  4414.7  403.17  4486.6  403.02  4544.1  401.30  4549.1  402.15  4586.6  400.86
  4640.5  400.64  4655.2  400.63  4816.8  395.46  4956.9  393.68  4980.0  392.05
  5006.9  391.74  5033.9  388.20  5034.4  387.40  5039.4  387.40  5039.9  388.20
  5046.9  388.75  5059.5  392.05  5096.9  394.75  5136.9  395.56  5156.9  394.68
  5212.8  396.21  5266.9  397.91  5276.9  398.64  5286.9  401.58  5326.9  402.52
  5366.9  401.11  5426.9  402.63  5456.9  402.13  5476.9  403.02  5483.4  404.32
#Mann=6,-1,0
  4414.7    0.08       0  4640.5     0.1       0  4655.2    0.08       0
  5033.9    0.07       0  5039.9    0.08       0  5212.8     0.1       0
Bank Sta=4980,5059.5
Exp/Cntr=0.3,0.1

Type RM Length L Ch R = 1,19308,181,181,181
BEGIN DESCRIPTION:
Mapping XS fa3c5621
END DESCRIPTION:
XS GIS Cut Line= 3
      2908619.11      6986072.15      2908057.07      6986083.00
      2907548.88      6986070.03
#Sta/Elev= 30
  4436.5  406.06  4570.6  404.72  4630.6  401.77  4650.7  401.85  4670.7  404.03
  4750.7  402.52  4780.7  401.07  4800.7  397.18  4810.7  396.62  4940.7  395.04
  4970.7  393.41  4981.5  391.82  4990.7  388.27  5017.7  386.24  5018.2  385.44
  5023.7  386.24  5040.7  389.82  5062.1  391.70  5065.9  391.82  5100.8  394.10
  5110.8  393.99  5116.1  392.80  5121.1  393.76  5290.8  396.75  5300.8  398.49
  5320.8  398.97  5380.8  398.96  5410.9  400.20  5460.9  399.56  5507.0  402.08
#Mann=4,-1,0
  4436.5    0.08       0  5017.7    0.07       0  5023.7    0.08       0
  5062.1     0.1       0
Bank Sta=4981.5,5065.9
Exp/Cntr=0.3,0.1

Type RM Length L Ch R = 1,19127,229,229,229
BEGIN DESCRIPTION:
GRAVEYARD BRANCH 31.0
END DESCRIPTION:
XS GIS Cut Line= 3
      2908538.87      6985974.50      2907975.00      6985925.00
      2907528.76      6985996.01
#Sta/Elev= 30
  4434.3  406.11  4484.6  406.11  4568.7  404.61  4596.9  405.40  4608.8  404.66
  4659.0  404.72  4769.5  402.95  4826.7  397.04  4907.6  391.04  4944.1  390.95
  4950.2  390.19  4980.3  389.37  4990.3  388.45  4992.3  387.26  4994.8  385.77
  4995.3  384.97  5000.3  384.97  5000.8  385.77  5010.5  386.93  5020.5  391.04
  5034.0  392.20  5071.2  392.90  5158.4  396.56  5193.5  396.52  5213.0  395.72
  5220.6  399.97  5225.6  399.34  5233.2  401.63  5387.1  402.59  5452.2  403.41
#Mann=6,-1,0
  4434.3    0.08       0  4992.3    0.15       0  4994.8    0.07       0
  5000.8    0.15       0  5193.5    0.08       0  5387.1     0.1       0
Bank Sta=4907.6,5020.5
Exp/Cntr=0.3,0.1

Type RM Length L Ch R = 1,18898,528,528,528
BEGIN DESCRIPTION:
GRAVEYARD BRANCH 30.0
END DESCRIPTION:
XS GIS Cut Line= 3
      2908366.95      6985762.22      2907924.29      6985688.44
      2907675.02      6985874.98
#Sta/Elev= 30
  4508.8  403.23  4585.0  404.17  4632.4  402.98  4693.3  403.02  4713.5  399.59
  4733.8  397.82  4828.3  392.38  4869.2  389.21  4875.7  388.19  4884.0  388.92
  4926.4  388.29  4949.9  389.11  4982.4  388.45  4997.0  386.29  5001.8  384.25
  5002.3  384.04  5002.8  383.24  5007.8  383.24  5008.3  384.04  5019.6  389.21
  5026.1  391.22  5069.1  392.56  5097.0  394.81  5110.7  394.73  5127.7  394.64
  5147.0  394.22  5155.4  398.82  5205.4  399.79  5247.0  401.66  5268.9  401.55
#Mann=6,-1,0
  4508.8    0.08       0  5001.8     0.1       0  5002.3    0.07       0
  5008.3     0.1       0  5110.7    0.15       0  5127.7    0.08       0
Bank Sta=4869.2,5019.6
Exp/Cntr=0.3,0.1

Type RM Length L Ch R = 1,18370,445,445,445
BEGIN DESCRIPTION:
Mapping XS 2eb46e3e
END DESCRIPTION:
XS GIS Cut Line= 3
      2908032.22      6985146.34      2907622.49      6985271.34
      2907376.93      6985641.41
#Sta/Elev= 30
  4568.8  404.10  4615.5  404.48  4684.6  403.30  4718.0  403.35  4764.5  401.48
  4827.3  394.70  4848.2  393.36  4859.7  391.25  4912.9  387.37  4990.9  384.57
  4994.9  386.61  4999.4  386.61  5004.6  383.39  5010.6  381.25  5011.1  380.45
  5016.1  380.45  5016.6  381.25  5019.7  384.54  5025.7  385.85  5035.5  386.18
  5070.8  385.79  5076.8  387.08  5085.6  386.45  5097.2  387.37  5145.9  392.35
  5221.7  396.62  5293.3  399.57  5362.4  400.41  5406.7  400.01  5441.3  400.16
#Mann=10,-1,0
  4568.8    0.08       0  4615.5     0.1       0  4684.6    0.08       0
  5010.6    0.07       0  5016.6    0.08       0  5035.5    0.05       0
  5145.9    0.08       0  5221.7    0.05       0  5362.4    0.08       0
  5406.7    0.16       0
Bank Sta=4912.9,5097.2
Exp/Cntr=0.3,0.1

Type RM Length L Ch R = 1,17925,177,177,177
BEGIN DESCRIPTION:
GRAVEYARD BRANCH 29.0
END DESCRIPTION:
XS GIS Cut Line= 4
      2907834.31      6984931.07      2907400.00      6984900.00
      2907250.00      6985000.00      2907049.98      6985600.05
#Sta/Elev= 30
  4470.3  399.83  4529.8  399.53  4559.8  397.81  4625.2  397.94  4640.0  396.86
  4670.1  391.60  4694.9  390.72  4700.2  390.76  4720.2  395.32  4794.0  393.30
  4840.6  393.08  4922.9  386.40  4947.8  383.82  4966.0  383.67  4998.9  384.58
  5004.9  381.26  5005.4  380.46  5010.9  381.26  5019.9  385.04  5091.3  383.78
  5161.0  386.40  5175.6  390.54  5207.2  389.39  5302.1  389.41  5397.0  391.45
  5502.4  395.73  5555.1  395.66  5611.9  397.80  5683.9  399.97  5718.5  400.81
#Mann=8,-1,0
  4470.3    0.08       0  4694.9    0.12       0  4794.0    0.16       0
  4966.0    0.12       0  5004.9    0.07       0  5010.9    0.12       0
  5611.9    0.16       0  5683.9    0.08       0
Bank Sta=4922.9,5161
Exp/Cntr=0.3,0.1

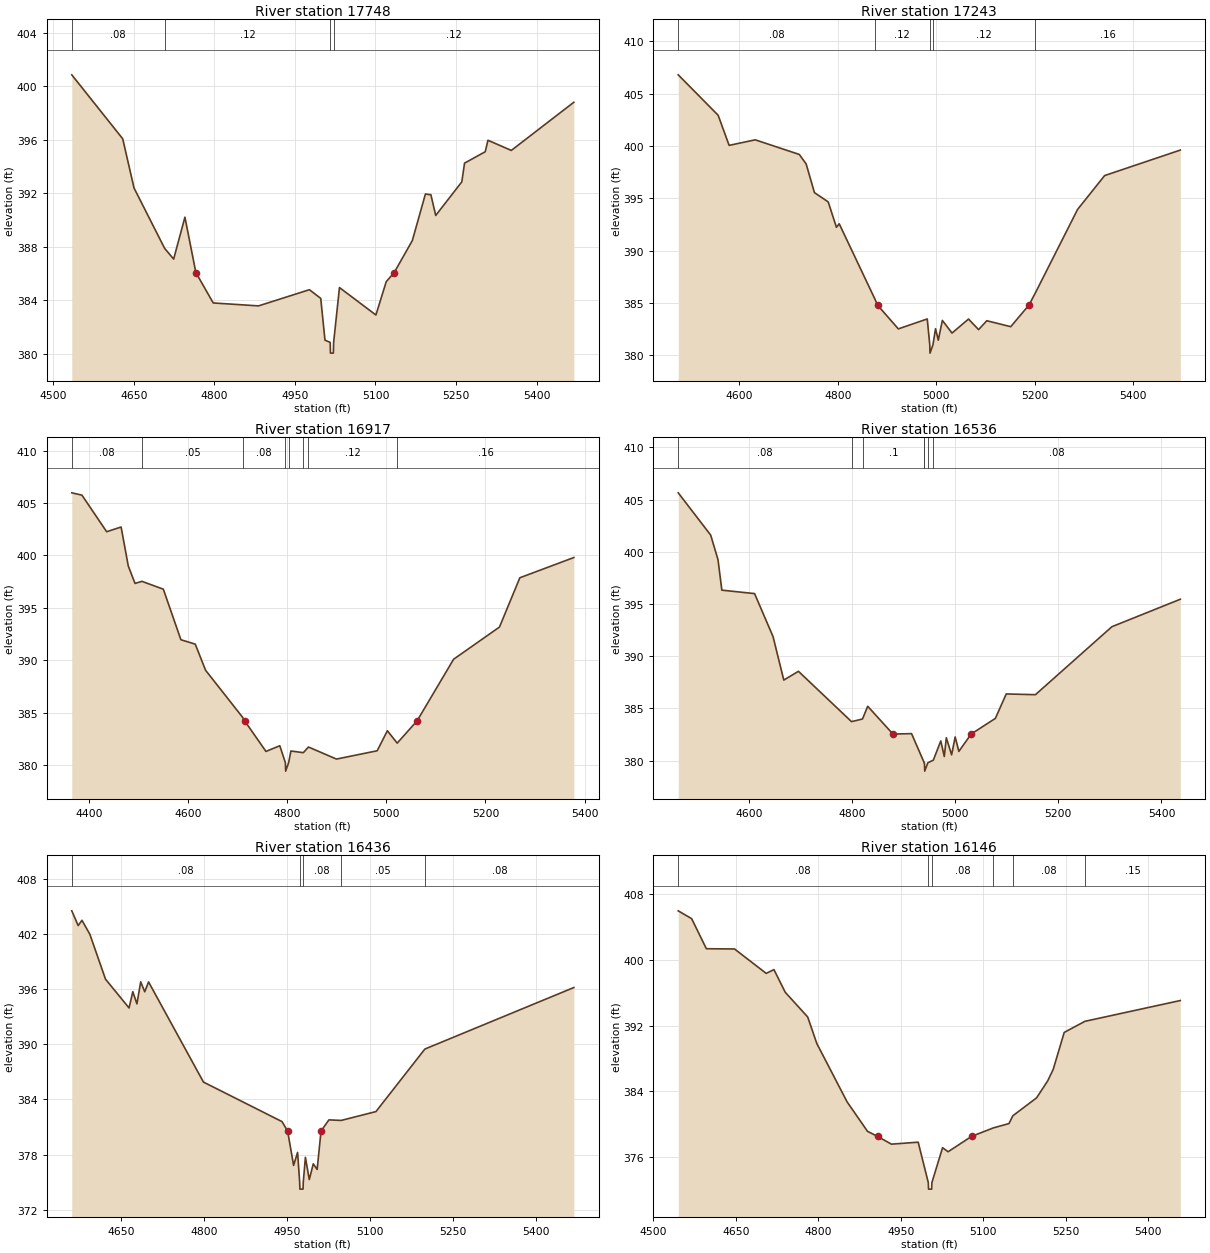
Type RM Length L Ch R = 1,17748,505,505,505
BEGIN DESCRIPTION:
GRAVEYARD BRANCH 28.0
END DESCRIPTION:
XS GIS Cut Line= 3
      2907024.99      6984424.98      2907175.00      6984875.00
      2907075.01      6985324.96
#Sta/Elev= 30
  4534.2  400.85  4629.1  396.07  4650.2  392.39  4707.2  387.88  4724.0  387.08
  4745.0  390.21  4765.4  386.07  4797.7  383.80  4882.1  383.58  4976.9  384.79
  4998.0  384.14  5005.9  381.02  5015.6  380.85  5016.1  380.05  5021.5  380.05
  5022.0  380.85  5032.9  384.95  5100.8  382.90  5120.0  385.39  5134.8  386.07
  5168.6  388.46  5193.0  391.94  5203.2  391.89  5212.2  390.34  5260.8  392.85
  5265.9  394.25  5304.4  395.10  5309.5  395.96  5353.0  395.20  5469.5  398.80
#Mann=4,-1,0
  4534.2    0.08       0  4707.2    0.12       0  5015.6    0.07       0
  5022.0    0.12       0
Bank Sta=4765.4,5134.8
Exp/Cntr=0.3,0.1

Type RM Length L Ch R = 1,17243,326,326,326
BEGIN DESCRIPTION:
GRAVEYARD BRANCH 27.0
END DESCRIPTION:
XS GIS Cut Line= 3
      2906975.00      6984225.01      2906725.00      6984725.00
      2906625.00      6985175.01
#Sta/Elev= 30
  4475.6  406.81  4556.7  402.94  4579.0  400.06  4632.1  400.59  4721.6  399.19
  4735.5  398.28  4752.3  395.54  4780.3  394.65  4797.0  392.22  4802.6  392.56
  4875.3  385.34  4880.5  384.77  4922.8  382.50  4981.5  383.45  4986.6  380.98
  4987.1  380.18  4993.1  380.98  4998.3  382.52  5003.9  381.42  5012.2  383.31
  5031.8  382.10  5065.3  383.44  5085.8  382.43  5102.5  383.28  5151.1  382.71
  5188.0  384.77  5200.8  385.91  5286.9  393.93  5341.9  397.17  5495.6  399.61
#Mann=5,-1,0
  4475.6    0.08       0  4875.3    0.12       0  4986.6    0.07       0
  4993.1    0.12       0  5200.8    0.16       0
Bank Sta=4880.5,5188
Exp/Cntr=0.3,0.1

Type RM Length L Ch R = 1,16917,381,381,381
BEGIN DESCRIPTION:
Mapping XS 4cb7ca9e
END DESCRIPTION:
XS GIS Cut Line= 3
      2906812.30      6984193.52      2906444.26      6984676.15
      2906350.75      6985070.98
#Sta/Elev= 30
  4365.5  405.97  4386.0  405.75  4435.9  402.26  4465.0  402.71  4479.5  398.99
  4493.1  397.33  4507.0  397.53  4550.2  396.78  4585.6  391.96  4614.6  391.54
  4635.4  389.05  4710.3  384.55  4714.1  384.23  4757.2  381.31  4785.1  381.85
  4796.4  380.23  4796.9  379.43  4802.9  380.23  4807.5  381.35  4832.6  381.19
  4842.9  381.73  4899.4  380.58  4981.5  381.37  5002.1  383.28  5021.9  382.10
  5062.1  384.23  5135.7  390.10  5228.2  393.17  5269.3  397.87  5378.2  399.80
#Mann=8,-1,0
  4365.5    0.08       0  4507.0    0.05       0  4710.3    0.08       0
  4796.4    0.07       0  4802.9    0.08       0  4832.6    0.16       0
  4842.9    0.12       0  5021.9    0.16       0
Bank Sta=4714.1,5062.1
Exp/Cntr=0.3,0.1

Type RM Length L Ch R = 1,16536,100,100,100
BEGIN DESCRIPTION:
Mapping XS 392d8e68
END DESCRIPTION:
XS GIS Cut Line= 3
      2906600.52      6984051.14      2906215.10      6984405.31
      2905903.43      6984730.83
#Sta/Elev= 30
  4462.5  405.64  4525.5  401.59  4539.7  399.23  4547.1  396.32  4610.6  395.99
  4646.4  391.88  4667.3  387.71  4695.7  388.55  4798.7  383.73  4820.0  383.98
  4830.1  385.20  4879.1  382.54  4915.2  382.58  4939.8  379.79  4940.2  379.79
  4940.7  378.99  4946.8  379.79  4957.4  380.04  4971.9  381.88  4978.7  380.39
  4982.6  382.19  4992.9  380.55  4999.8  382.26  5007.0  380.88  5030.8  382.54
  5077.8  384.04  5098.9  386.38  5155.5  386.31  5303.9  392.82  5436.6  395.45
#Mann=7,-1,0
  4462.5    0.08       0  4798.7    0.16       0  4820.0     0.1       0
  4939.8    0.16       0  4940.2    0.07       0  4946.8    0.16       0
  4957.4    0.08       0
Bank Sta=4879.1,5030.8
Exp/Cntr=0.3,0.1

Type RM Length L Ch R = 1,16436,290,290,290
BEGIN DESCRIPTION:
Mapping XS ae2960f3
END DESCRIPTION:
XS GIS Cut Line= 3
      2906472.05      6984006.00      2906215.10      6984280.31
      2905843.58      6984658.77
#Sta/Elev= 30
  4561.7  404.51  4573.3  402.91  4580.1  403.48  4594.3  401.97  4622.6  397.08
  4665.1  393.95  4671.9  395.72  4679.3  394.39  4686.1  396.79  4693.4  395.71
  4700.3  396.78  4799.4  385.89  4941.2  381.59  4951.3  380.56  4962.1  376.83
  4969.3  378.24  4973.0  375.05  4973.5  374.25  4979.1  374.25  4979.6  375.05
  4983.4  377.71  4990.4  375.29  4997.6  377.00  5004.6  376.39  5011.6  380.56
  5025.8  381.78  5048.0  381.72  5110.7  382.68  5199.0  389.48  5467.9  396.17
#Mann=5,-1,0
  4561.7    0.08       0  4973.0    0.07       0  4979.6    0.08       0
  5048.0    0.05       0  5199.0    0.08       0
Bank Sta=4951.3,5011.6
Exp/Cntr=0.3,0.1

Type RM Length L Ch R = 1,16146,545,545,545
BEGIN DESCRIPTION:
GRAVEYARD BRANCH 25.0
END DESCRIPTION:
XS GIS Cut Line= 3
      2906475.03      6983974.99      2906025.00      6984075.00
      2905574.97      6984125.00
#Sta/Elev= 30
  4545.1  405.97  4569.5  405.02  4596.3  401.36  4647.6  401.33  4705.2  398.36
  4719.3  398.82  4739.8  396.07  4780.7  393.06  4797.4  389.82  4852.4  382.74
  4889.6  379.15  4908.1  378.53  4933.1  377.59  4981.8  377.83  5000.2  372.92
  5000.7  372.12  5006.3  372.12  5006.8  372.92  5026.2  377.16  5036.3  376.67
  5078.9  378.53  5118.7  379.57  5147.0  380.09  5154.2  381.05  5197.3  383.22
  5217.4  385.27  5227.5  386.67  5247.6  391.18  5285.3  392.53  5458.9  395.06
#Mann=6,-1,0
  4545.1    0.08       0  5000.2    0.07       0  5006.8    0.08       0
  5118.7    0.05       0  5154.2    0.08       0  5285.3    0.15       0
Bank Sta=4908.1,5078.9
Exp/Cntr=0.3,0.1