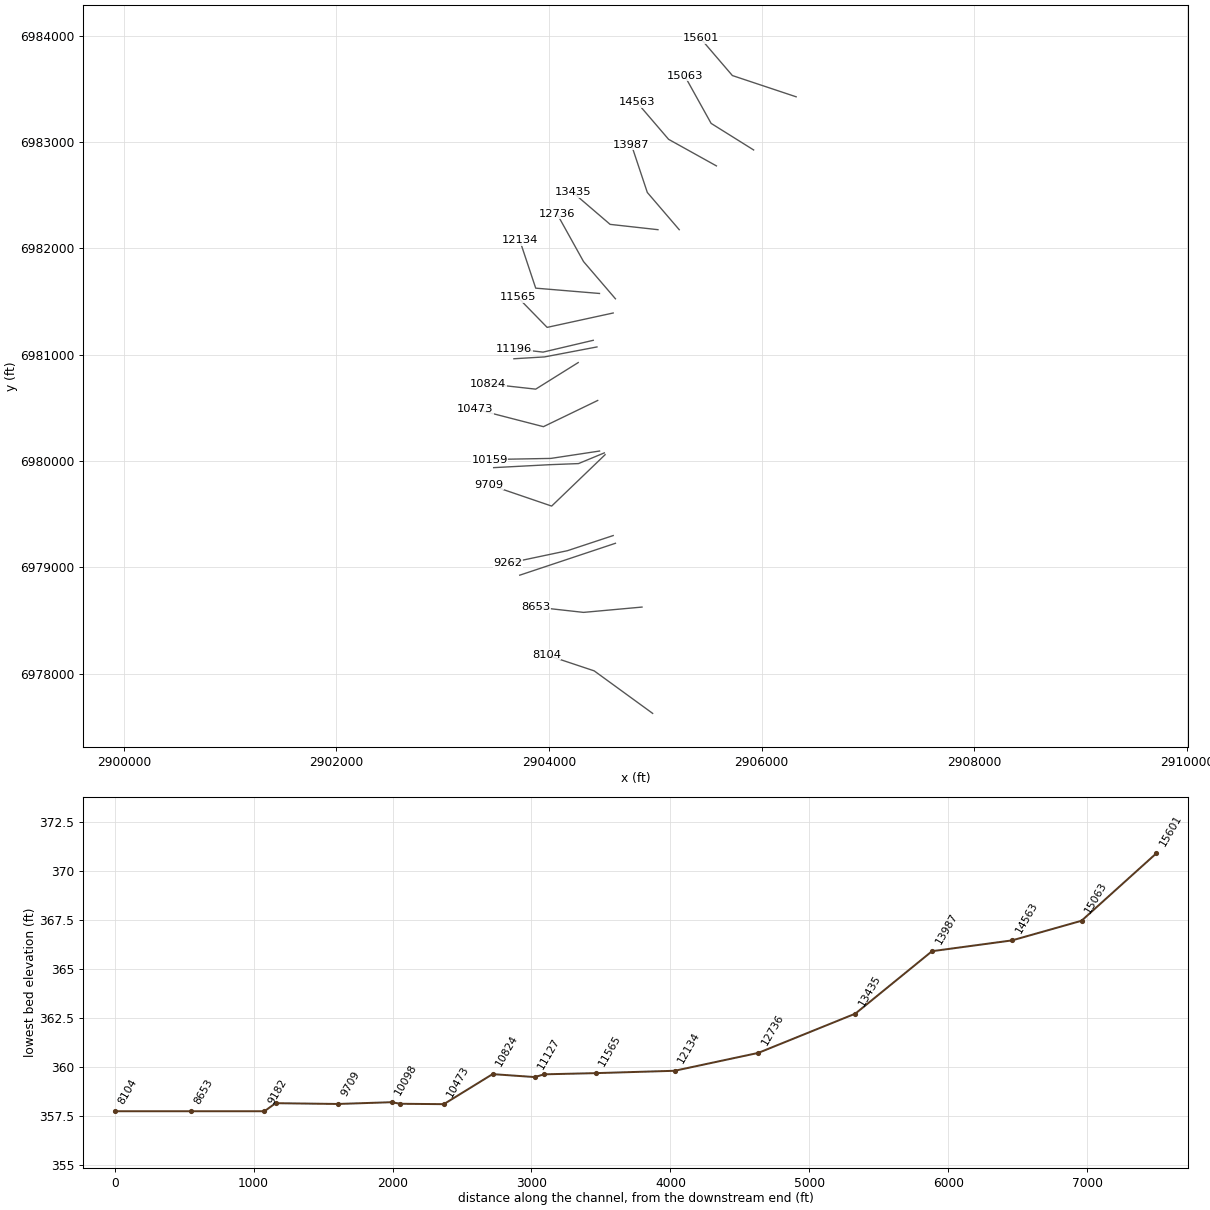
HEC-RAS study GRAVEYARD BRANCH.prj: GRAVEYARD BRANCH Base Level Engineering

--- GRAVEYARD BRANCH.g01 (geometry) --- (continued)

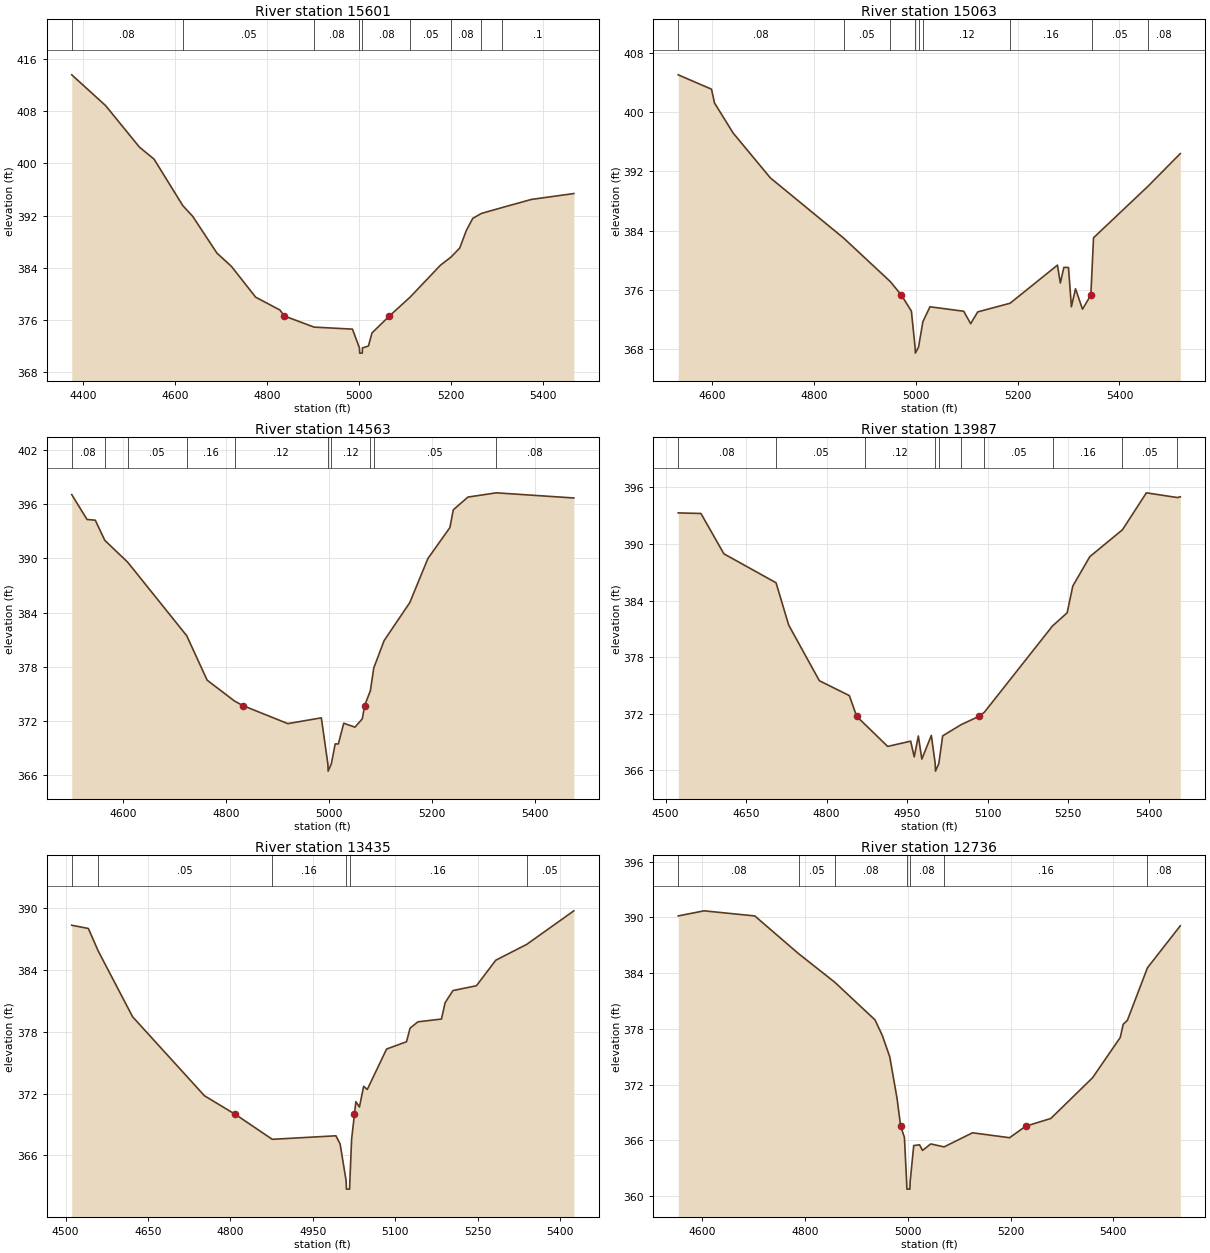
Type RM Length L Ch R = 1,15601,538,538,538
BEGIN DESCRIPTION:
GRAVEYARD BRANCH 24.0
END DESCRIPTION:
XS GIS Cut Line= 3
      2906324.96      6983425.01      2905725.00      6983625.00
      2905424.99      6983975.01
#Sta/Elev= 30
  4374.6  413.58  4448.3  408.86  4522.1  402.48  4553.8  400.65  4616.4  393.52
  4638.1  391.86  4690.8  386.23  4722.4  384.19  4775.1  379.47  4827.8  377.51
  4837.5  376.59  4902.3  374.88  4985.9  374.57  5001.1  371.69  5001.6  370.89
  5007.2  370.89  5007.7  371.69  5020.7  371.98  5028.4  373.99  5066.4  376.59
  5111.7  379.50  5177.7  384.39  5200.4  385.62  5219.4  387.00  5233.7  389.68
  5247.9  391.56  5266.7  392.32  5312.3  393.23  5375.8  394.47  5468.0  395.37
#Mann=9,-1,0
  4374.6    0.08       0  4616.4    0.05       0  4902.3    0.08       0
  5001.1    0.07       0  5007.7    0.08       0  5111.7    0.05       0
  5200.4    0.08       0  5266.7    0.15       0  5312.3     0.1       0
Bank Sta=4837.5,5066.4
Exp/Cntr=0.3,0.1

Type RM Length L Ch R = 1,15063,500,500,500
BEGIN DESCRIPTION:
GRAVEYARD BRANCH 23.0
END DESCRIPTION:
XS GIS Cut Line= 3
      2905924.99      6982925.01      2905525.00      6983175.00
      2905274.98      6983625.03
#Sta/Elev= 30
  4533.0  405.00  4598.4  403.06  4604.3  401.20  4640.9  397.15  4714.0  391.10
  4858.0  382.98  4949.7  377.11  4971.5  375.28  4991.1  373.13  4998.4  368.26
  4998.9  367.46  5005.1  368.26  5013.7  371.70  5027.6  373.71  5093.9  373.11
  5107.6  371.43  5121.4  373.02  5185.1  374.19  5278.1  379.33  5283.8  376.92
  5290.7  379.03  5299.8  379.01  5305.5  373.71  5313.6  376.14  5327.3  373.39
  5343.7  375.28  5345.2  377.47  5349.0  383.02  5455.7  389.95  5519.5  394.38
#Mann=9,-1,0
  4533.0    0.08       0  4858.0    0.05       0  4949.7    0.16       0
  4998.4    0.07       0  5005.1    0.16       0  5013.7    0.12       0
  5185.1    0.16       0  5345.2    0.05       0  5455.7    0.08       0
Bank Sta=4971.5,5343.7
Exp/Cntr=0.3,0.1

Type RM Length L Ch R = 1,14563,576,576,576
BEGIN DESCRIPTION:
GRAVEYARD BRANCH 22.0
END DESCRIPTION:
XS GIS Cut Line= 3
      2905574.98      6982775.01      2905125.00      6983025.00
      2904825.02      6983374.97
#Sta/Elev= 30
  4499.7  397.07  4529.4  394.32  4545.4  394.24  4563.9  392.01  4608.4  389.59
  4723.1  381.45  4762.8  376.53  4816.0  374.22  4832.1  373.72  4919.5  371.72
  4984.7  372.36  4997.4  367.26  4997.9  366.46  5004.1  367.26  5011.6  369.47
  5017.8  369.47  5028.2  371.76  5050.1  371.33  5064.4  372.26  5068.8  373.72
  5080.0  375.36  5086.6  377.88  5106.7  380.91  5156.6  385.12  5191.7  389.99
  5234.5  393.42  5241.1  395.39  5269.6  396.80  5324.9  397.27  5475.4  396.70
#Mann=10,-1,0
  4499.7    0.08       0  4563.9     0.1       0  4608.4    0.05       0
  4723.1    0.16       0  4816.0    0.12       0  4997.4    0.07       0
  5004.1    0.12       0  5080.0    0.16       0  5086.6    0.05       0
  5324.9    0.08       0
Bank Sta=4832.1,5068.8
Exp/Cntr=0.3,0.1

Type RM Length L Ch R = 1,13987,552,552,552
BEGIN DESCRIPTION:
GRAVEYARD BRANCH 21.0
END DESCRIPTION:
XS GIS Cut Line= 3
      2905225.00      6982175.00      2904925.00      6982525.00
      2904775.01      6982974.98
#Sta/Elev= 30
  4523.7  393.30  4566.0  393.24  4608.8  388.96  4705.9  385.89  4729.5  381.40
  4786.6  375.50  4842.5  373.92  4856.2  371.71  4872.1  370.84  4913.9  368.53
  4956.7  369.09  4963.3  367.42  4971.0  369.64  4977.5  367.19  4995.2  369.70
  5002.4  366.71  5002.9  365.91  5009.1  366.71  5016.3  369.65  5050.7  370.84
  5083.5  371.71  5094.0  372.16  5221.1  381.32  5248.2  382.70  5258.7  385.54
  5290.4  388.66  5351.2  391.51  5395.8  395.43  5453.5  394.93  5459.0  395.01
#Mann=10,-1,0
  4523.7    0.08       0  4705.9    0.05       0  4872.1    0.12       0
  5002.4    0.07       0  5009.1    0.12       0  5050.7    0.16       0
  5094.0    0.05       0  5221.1    0.16       0  5351.2    0.05       0
  5453.5    0.08       0
Bank Sta=4856.2,5083.5
Exp/Cntr=0.3,0.1

Type RM Length L Ch R = 1,13435,699,699,699
BEGIN DESCRIPTION:
GRAVEYARD BRANCH 20.0
END DESCRIPTION:
XS GIS Cut Line= 3
      2905024.98      6982175.00      2904575.00      6982225.00
      2904225.02      6982524.98
#Sta/Elev= 30
  4511.2  388.31  4541.4  388.00  4559.3  385.82  4621.9  379.44  4752.7  371.78
  4809.1  369.97  4876.1  367.56  4991.9  367.90  4999.6  367.10  5010.5  363.53
  5011.0  362.73  5016.8  362.73  5017.3  363.53  5020.5  367.59  5025.6  369.97
  5028.2  371.21  5034.7  370.69  5042.4  372.70  5049.0  372.39  5084.1  376.31
  5120.4  377.02  5126.9  378.34  5141.2  378.95  5184.0  379.22  5190.6  380.80
  5204.9  381.98  5247.7  382.45  5282.8  384.92  5339.2  386.46  5424.9  389.71
#Mann=6,-1,0
  4511.2    0.08       0  4559.3    0.05       0  4876.1    0.16       0
  5010.5    0.07       0  5017.3    0.16       0  5339.2    0.05       0
Bank Sta=4809.1,5025.6
Exp/Cntr=0.3,0.1

Type RM Length L Ch R = 1,12736,602,602,602
BEGIN DESCRIPTION:
GRAVEYARD BRANCH 19.0
END DESCRIPTION:
XS GIS Cut Line= 3
      2904625.02      6981524.98      2904325.00      6981875.00
      2904075.00      6982325.01
#Sta/Elev= 30
  4554.2  390.16  4604.2  390.71  4703.0  390.16  4788.0  386.10  4858.4  383.02
  4936.7  378.96  4951.0  377.26  4965.3  374.99  4979.5  370.50  4986.5  367.51
  4993.8  366.31  4998.1  361.53  4998.6  360.73  5004.4  360.73  5004.9  361.53
  5011.9  365.42  5023.2  365.51  5028.9  364.90  5045.0  365.60  5070.9  365.28
  5126.2  366.80  5198.2  366.27  5229.6  367.51  5278.3  368.34  5359.5  372.73
  5413.3  377.07  5419.0  378.49  5427.0  378.90  5466.1  384.57  5530.0  389.10
#Mann=7,-1,0
  4554.2    0.08       0  4788.0    0.05       0  4858.4    0.08       0
  4998.1    0.07       0  5004.9    0.08       0  5070.9    0.16       0
  5466.1    0.08       0
Bank Sta=4986.5,5229.6
Exp/Cntr=0.3,0.1

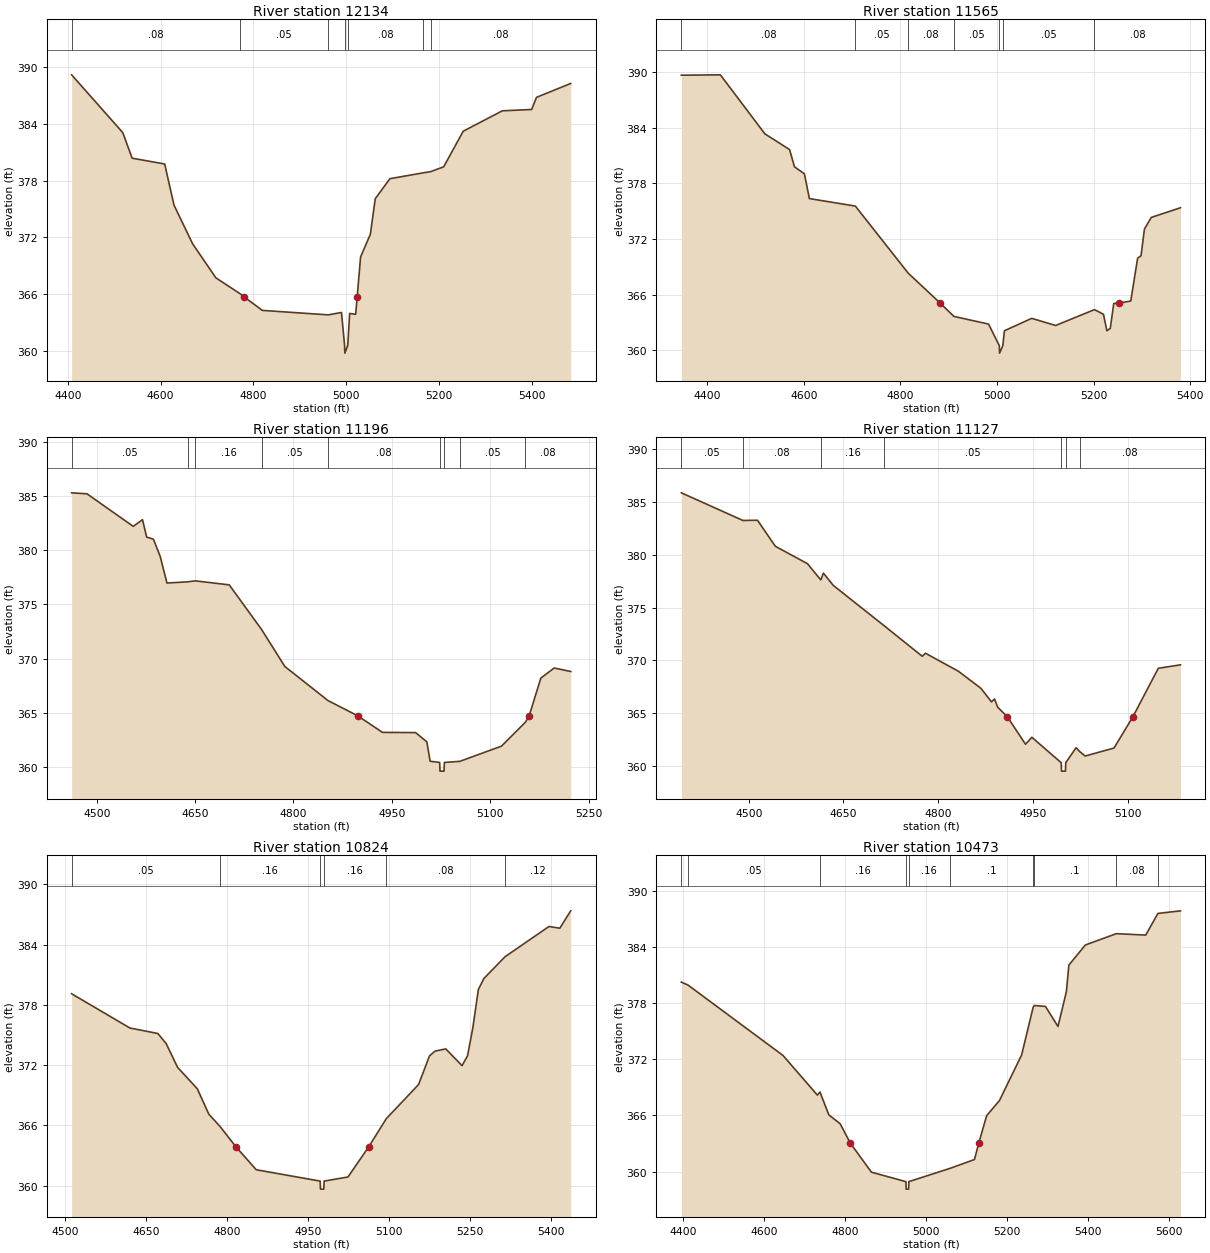
Type RM Length L Ch R = 1,12134,569,569,569
BEGIN DESCRIPTION:
GRAVEYARD BRANCH 18.0
END DESCRIPTION:
XS GIS Cut Line= 3
      2904475.01      6981575.00      2903875.00      6981625.00
      2903725.01      6982074.97
#Sta/Elev= 30
  4408.0  389.13  4518.4  383.04  4538.5  380.35  4608.7  379.74  4628.8  375.41
  4668.9  371.34  4719.1  367.75  4771.8  366.06  4780.6  365.72  4819.4  364.32
  4961.4  363.85  4990.0  364.10  4996.7  360.62  4997.2  359.82  5003.5  360.62
  5007.6  364.00  5020.6  363.91  5023.8  365.72  5031.2  369.95  5052.3  372.34
  5062.8  376.08  5094.4  378.19  5166.5  378.81  5182.1  378.93  5210.4  379.44
  5252.5  383.19  5336.9  385.34  5400.1  385.48  5410.6  386.76  5484.4  388.22
#Mann=7,-1,0
  4408.0    0.08       0  4771.8    0.05       0  4961.4    0.08       0
  4996.7    0.07       0  5003.5    0.08       0  5166.5    0.16       0
  5182.1    0.08       0
Bank Sta=4780.6,5023.8
Exp/Cntr=0.3,0.1

Type RM Length L Ch R = 1,11565,369,369,369
BEGIN DESCRIPTION:
Mapping XS aedba987
END DESCRIPTION:
XS GIS Cut Line= 3
      2904603.98      6981391.42      2903982.46      6981256.01
      2903705.01      6981540.39
#Sta/Elev= 30
  4346.3  389.66  4427.1  389.70  4519.2  383.34  4570.4  381.64  4580.6  379.78
  4601.1  379.03  4611.4  376.36  4706.6  375.55  4816.0  368.32  4882.3  365.09
  4910.6  363.66  4982.4  362.83  5004.7  360.50  5005.2  359.70  5011.9  360.50
  5015.2  362.11  5071.8  363.45  5121.2  362.68  5201.7  364.39  5220.3  363.89
  5227.4  362.11  5234.4  362.37  5241.6  365.05  5252.4  365.09  5276.8  365.32
  5291.0  369.93  5298.1  370.20  5305.1  373.07  5319.3  374.33  5379.7  375.37
#Mann=7,-1,0
  4346.3    0.08       0  4706.6    0.05       0  4816.0    0.08       0
  4910.6    0.05       0  5004.7    0.04       0  5011.9    0.05       0
  5201.7    0.08       0
Bank Sta=4882.3,5252.4
Exp/Cntr=0.3,0.1

Type RM Length L Ch R = 1,11196,69,69,69
BEGIN DESCRIPTION:
Mapping XS 0235c056
END DESCRIPTION:
XS GIS Cut Line= 3
      2904416.50      6981134.48      2903944.26      6981023.37
      2903669.97      6981054.62
#Sta/Elev= 30
  4461.7  385.28  4485.1  385.19  4555.7  382.19  4569.8  382.81  4576.2  381.20
  4586.5  381.01  4596.8  379.42  4607.1  376.97  4639.0  377.08  4650.3  377.17
  4702.1  376.80  4751.5  372.68  4786.9  369.28  4852.7  366.14  4897.7  364.75
  4935.8  363.21  4986.3  363.19  5003.4  362.34  5008.5  360.55  5023.0  360.44
  5023.5  359.64  5029.7  359.64  5030.2  360.44  5053.7  360.54  5117.2  361.94
  5153.7  364.14  5159.6  364.75  5177.3  368.21  5197.7  369.14  5222.9  368.82
#Mann=9,-1,0
  4461.7    0.05       0  4639.0    0.08       0  4650.3    0.16       0
  4751.5    0.05       0  4852.7    0.08       0  5023.0    0.07       0
  5030.2    0.08       0  5053.7    0.05       0  5153.7    0.08       0
Bank Sta=4897.7,5159.6
Exp/Cntr=0.3,0.1

Type RM Length L Ch R = 1,11127,303,303,303
BEGIN DESCRIPTION:
Mapping XS 54bcb161
END DESCRIPTION:
XS GIS Cut Line= 3
      2904451.24      6981071.99      2903958.15      6980978.23
      2903670.00      6980960.87
#Sta/Elev= 30
  4393.2  385.89  4490.7  383.27  4513.8  383.29  4542.1  380.82  4593.0  379.17
  4614.1  377.63  4618.2  378.28  4633.7  377.12  4714.4  373.29  4774.8  370.39
  4779.9  370.68  4832.1  368.97  4867.8  367.35  4884.4  366.07  4889.4  366.34
  4894.2  365.57  4909.6  364.65  4938.4  362.05  4948.4  362.71  4994.9  360.30
  4995.4  359.50  5001.6  359.50  5002.1  360.30  5018.5  361.72  5024.1  361.36
  5032.8  360.93  5078.6  361.69  5108.4  364.65  5148.7  369.25  5183.8  369.58
#Mann=7,-1,0
  4393.2    0.05       0  4490.7    0.08       0  4614.1    0.16       0
  4714.4    0.05       0  4994.9    0.03       0  5002.1    0.05       0
  5024.1    0.08       0
Bank Sta=4909.6,5108.4
Exp/Cntr=0.3,0.1

Type RM Length L Ch R = 1,10824,351,351,351
BEGIN DESCRIPTION:
GRAVEYARD BRANCH 16.0
END DESCRIPTION:
XS GIS Cut Line= 3
      2904274.99      6980924.99      2903875.00      6980675.00
      2903424.96      6980725.00
#Sta/Elev= 30
  4512.2  379.11  4620.1  375.70  4672.0  375.15  4687.3  374.15  4708.5  371.78
  4745.1  369.64  4766.3  367.12  4786.9  365.91  4816.5  363.87  4854.2  361.58
  4972.6  360.45  4973.1  359.65  4979.3  359.65  4979.9  360.45  5024.1  360.86
  5062.6  363.87  5095.1  366.67  5154.9  370.07  5175.1  372.92  5185.1  373.39
  5205.2  373.62  5235.4  371.95  5245.5  372.92  5255.5  375.76  5265.6  379.53
  5275.7  380.62  5315.1  382.80  5396.4  385.81  5416.5  385.64  5436.7  387.37
#Mann=6,-1,0
  4512.2    0.05       0  4786.9    0.16       0  4972.6    0.03       0
  4979.9    0.16       0  5095.1    0.08       0  5315.1    0.12       0
Bank Sta=4816.5,5062.6
Exp/Cntr=0.3,0.1

Type RM Length L Ch R = 1,10473,314,314,314
BEGIN DESCRIPTION:
Mapping XS 3c245013
END DESCRIPTION:
XS GIS Cut Line= 3
      2904458.15      6980568.50      2903947.73      6980321.98
      2903301.92      6980488.64
#Sta/Elev= 30
  4395.5  380.23  4412.1  379.91  4646.9  372.39  4731.8  368.16  4738.3  368.49
  4759.9  366.06  4788.1  365.10  4813.4  363.02  4865.4  359.93  4950.6  358.92
  4951.2  358.12  4957.4  358.12  4957.9  358.92  5059.1  360.33  5120.1  361.28
  5130.6  363.02  5150.2  365.96  5182.0  367.59  5236.7  372.45  5264.9  377.50
  5267.7  377.73  5295.6  377.63  5326.6  375.49  5347.3  379.21  5353.5  382.05
  5394.2  384.19  5470.7  385.40  5543.5  385.25  5573.5  387.56  5629.3  387.84
#Mann=10,-1,0
  4395.5    0.08       0  4412.1    0.05       0  4738.3    0.16       0
  4950.6    0.07       0  4957.9    0.16       0  5059.1     0.1       0
  5264.9    0.08       0  5267.7     0.1       0  5470.7    0.08       0
  5573.5    0.05       0
Bank Sta=4813.4,5130.6
Exp/Cntr=0.3,0.1

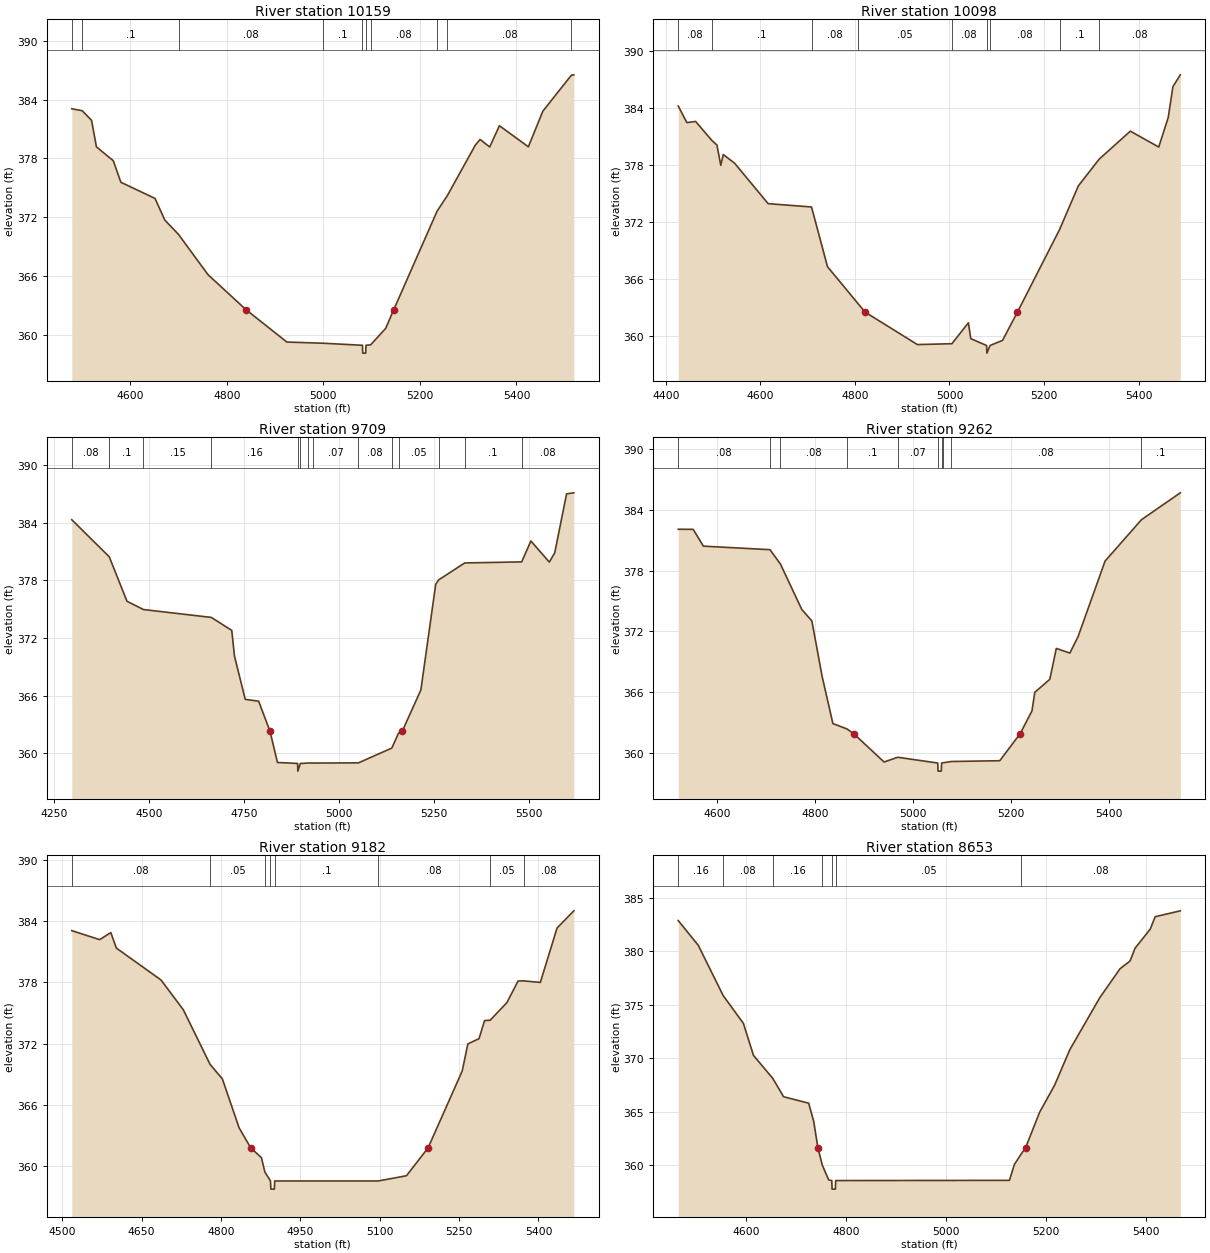
Type RM Length L Ch R = 1,10159,61,61,61
BEGIN DESCRIPTION:
Mapping XS c536e51b
END DESCRIPTION:
XS GIS Cut Line= 3
      2904475.55      6980092.82      2904017.18      6980023.37
      2903440.78      6980012.95
#Sta/Elev= 30
  4478.8  383.07  4500.4  382.87  4519.8  381.89  4529.9  379.18  4564.8  377.77
  4580.5  375.57  4651.3  373.92  4671.5  371.72  4700.1  370.24  4761.1  366.14
  4839.3  362.59  4924.4  359.27  4999.0  359.15  5081.0  358.94  5081.5  358.14
  5087.7  358.14  5088.3  358.94  5098.0  358.99  5129.2  360.67  5146.0  362.59
  5235.6  372.62  5257.0  374.22  5314.6  379.34  5324.6  379.94  5344.6  379.17
  5364.7  381.34  5424.7  379.19  5454.7  382.82  5513.7  386.49  5518.9  386.53
#Mann=10,-1,0
  4478.8    0.08       0  4500.4     0.1       0  4700.1    0.08       0
  4999.0     0.1       0  5081.0    0.07       0  5088.3     0.1       0
  5098.0    0.08       0  5235.6     0.1       0  5257.0    0.08       0
  5513.7    0.16       0
Bank Sta=4839.3,5146
Exp/Cntr=0.3,0.1

Type RM Length L Ch R = 1,10098,389,389,389
BEGIN DESCRIPTION:
Mapping XS 1e688d5f
END DESCRIPTION:
XS GIS Cut Line= 4
      2904520.69      6980075.47      2904277.60      6979974.76
      2904006.76      6979964.34      2903479.46      6979936.59
#Sta/Elev= 30
  4426.2  384.19  4444.5  382.45  4463.0  382.57  4497.2  380.58  4508.1  380.09
  4516.2  377.96  4521.6  379.09  4545.5  378.18  4616.4  373.93  4708.2  373.58
  4742.0  367.30  4807.2  363.39  4821.6  362.53  4932.1  359.12  5005.2  359.21
  5040.1  361.41  5045.1  359.74  5078.6  359.02  5079.2  358.22  5085.9  359.02
  5112.3  359.56  5143.8  362.53  5233.1  371.22  5272.6  375.79  5316.6  378.60
  5382.7  381.55  5442.8  379.88  5462.8  382.98  5472.8  386.23  5488.4  387.47
#Mann=9,-1,0
  4426.2    0.08       0  4497.2     0.1       0  4708.2    0.08       0
  4807.2    0.05       0  5005.2    0.08       0  5078.6    0.04       0
  5085.9    0.08       0  5233.1     0.1       0  5316.6    0.08       0
Bank Sta=4821.6,5143.8
Exp/Cntr=0.3,0.1

Type RM Length L Ch R = 1,9709,447,447,447
BEGIN DESCRIPTION:
GRAVEYARD BRANCH 14.0
END DESCRIPTION:
XS GIS Cut Line= 3
      2904527.63      6980058.12      2904025.00      6979575.00
      2903433.87      6979776.83
#Sta/Elev= 30
  4296.4  384.30  4395.1  380.44  4441.8  375.81  4485.1  374.95  4663.8  374.13
  4717.6  372.78  4724.8  370.10  4753.1  365.60  4788.4  365.41  4818.2  362.29
  4838.0  359.03  4891.0  358.93  4891.5  358.13  4898.3  358.93  4919.3  358.97
  4932.5  358.97  5051.1  358.99  5139.0  360.53  5156.6  362.08  5166.5  362.29
  5215.5  366.58  5254.5  377.57  5262.1  378.03  5330.8  379.80  5480.9  379.91
  5505.1  382.09  5553.6  379.89  5567.8  380.84  5599.1  386.99  5618.2  387.10
#Mann=14,-1,0
  4296.4    0.08       0  4395.1     0.1       0  4485.1    0.15       0
  4663.8    0.16       0  4891.0    0.07       0  4898.3    0.16       0
  4919.3    0.05       0  4932.5    0.07       0  5051.1    0.08       0
  5139.0    0.16       0  5156.6    0.05       0  5262.1    0.08       0
  5330.8     0.1       0  5480.9    0.08       0
Bank Sta=4818.2,5166.5
Exp/Cntr=0.3,0.1

Type RM Length L Ch R = 1,9262,80,80,80
BEGIN DESCRIPTION:
Mapping XS 0a6dac4f
END DESCRIPTION:
XS GIS Cut Line= 3
      2904603.99      6979297.68      2904173.43      6979155.31
      2903614.44      6979037.27
#Sta/Elev= 30
  4521.2  382.08  4551.7  382.07  4572.5  380.41  4708.5  380.06  4729.9  378.63
  4773.4  374.15  4794.0  373.01  4815.0  367.51  4836.9  362.87  4865.6  362.34
  4879.2  361.88  4941.4  359.07  4969.1  359.54  5050.9  358.97  5051.5  358.17
  5058.1  358.17  5058.8  358.97  5061.3  358.99  5078.2  359.12  5177.5  359.20
  5219.2  361.88  5243.2  364.12  5249.0  365.96  5279.7  367.25  5292.9  370.30
  5320.6  369.84  5337.5  371.49  5392.4  378.93  5466.6  383.02  5546.0  385.68
#Mann=10,-1,0
  4521.2    0.08       0  4708.5    0.16       0  4729.9    0.08       0
  4865.6     0.1       0  4969.1    0.07       0  5050.9    0.07       0
  5058.8    0.07       0  5061.3     0.1       0  5078.2    0.08       0
  5466.6     0.1       0
Bank Sta=4879.2,5219.2
Exp/Cntr=0.3,0.1

Type RM Length L Ch R = 1,9182,529,529,529
BEGIN DESCRIPTION:
GRAVEYARD BRANCH 13.0
END DESCRIPTION:
XS GIS Cut Line= 3
      2904624.98      6979224.99      2904175.00      6979075.00
      2903724.97      6978924.99
#Sta/Elev= 30
  4518.1  383.07  4570.8  382.19  4591.9  382.88  4602.4  381.36  4686.7  378.24
  4728.9  375.32  4779.4  369.98  4802.7  368.55  4834.3  363.76  4856.3  361.80
  4876.5  360.84  4883.0  359.43  4893.6  358.56  4894.3  357.76  4900.9  357.76
  4901.5  358.56  5097.2  358.56  5150.5  359.07  5191.4  361.80  5255.9  369.33
  5266.5  371.98  5287.6  372.49  5298.1  374.26  5308.7  374.30  5340.3  376.02
  5361.4  378.14  5371.7  378.15  5403.5  378.00  5435.1  383.33  5466.8  385.01
#Mann=8,-1,0
  4518.1    0.08       0  4779.4    0.05       0  4883.0     0.1       0
  4893.6    0.07       0  4901.5     0.1       0  5097.2    0.08       0
  5308.7    0.05       0  5371.7    0.08       0
Bank Sta=4856.3,5191.4
Exp/Cntr=0.3,0.1

Type RM Length L Ch R = 1,8653,549,549,549
BEGIN DESCRIPTION:
GRAVEYARD BRANCH 12.0
END DESCRIPTION:
XS GIS Cut Line= 3
      2904874.99      6978625.00      2904325.00      6978575.00
      2903875.03      6978625.00
#Sta/Elev= 30
  4463.5  382.88  4503.7  380.56  4553.5  375.86  4594.0  373.26  4614.1  370.27
  4652.7  368.12  4674.4  366.40  4724.6  365.80  4734.6  364.11  4743.1  361.63
  4751.9  360.00  4764.7  358.62  4770.8  358.56  4771.5  357.76  4778.1  357.76
  4778.7  358.56  5126.4  358.58  5136.5  360.08  5149.7  361.02  5158.8  361.63
  5186.8  364.94  5217.0  367.49  5247.2  370.79  5307.5  375.68  5347.8  378.37
  5367.9  379.10  5378.0  380.30  5408.2  382.07  5418.2  383.24  5468.5  383.79
#Mann=7,-1,0
  4463.5    0.16       0  4553.5    0.08       0  4652.7    0.16       0
  4751.9    0.05       0  4770.8   0.033       0  4778.7    0.05       0
  5149.7    0.08       0
Bank Sta=4743.1,5158.8
Exp/Cntr=0.3,0.1

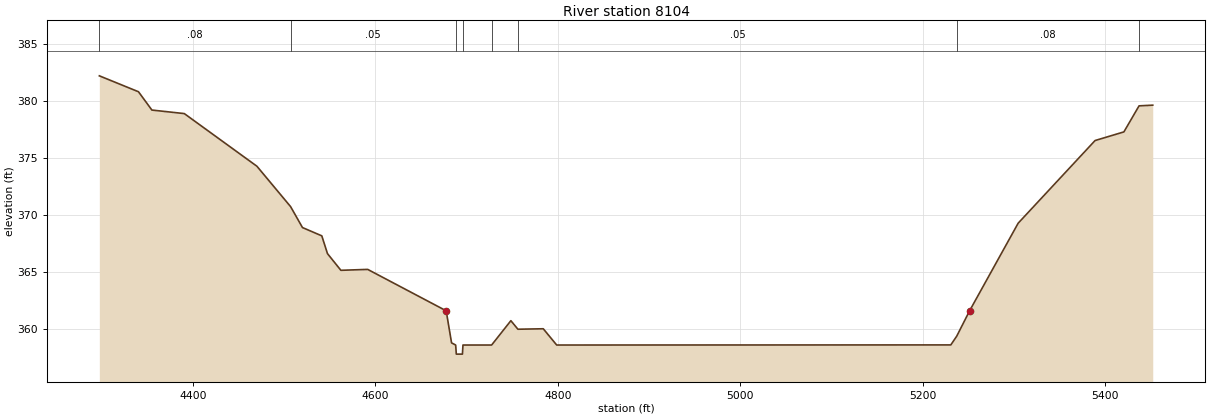
Type RM Length L Ch R = 1,8104,544,544,544
BEGIN DESCRIPTION:
GRAVEYARD BRANCH 11.0
END DESCRIPTION:
XS GIS Cut Line= 3
      2904975.02      6977624.99      2904425.00      6978025.00
      2903975.03      6978174.99
#Sta/Elev= 30
  4297.7  382.23  4340.6  380.83  4355.3  379.22  4390.8  378.91  4470.4  374.28
  4507.3  370.73  4520.3  368.89  4541.5  368.16  4547.7  366.60  4562.4  365.13
  4591.8  365.21  4677.8  361.57  4683.7  358.75  4688.2  358.56  4688.9  357.76
  4695.6  357.76  4696.2  358.56  4727.6  358.56  4748.7  360.70  4756.4  359.95
  4784.2  359.99  4798.9  358.56  5230.8  358.57  5237.3  359.34  5251.4  361.57
  5304.6  369.27  5388.9  376.54  5420.5  377.30  5437.1  379.59  5452.1  379.65
#Mann=8,-1,0
  4297.7    0.08       0  4507.3    0.05       0  4688.2   0.033       0
  4696.2    0.05       0  4727.6     0.1       0  4756.4    0.05       0
  5237.3    0.08       0  5437.1    0.16       0
Bank Sta=4677.8,5251.4
Exp/Cntr=0.3,0.1