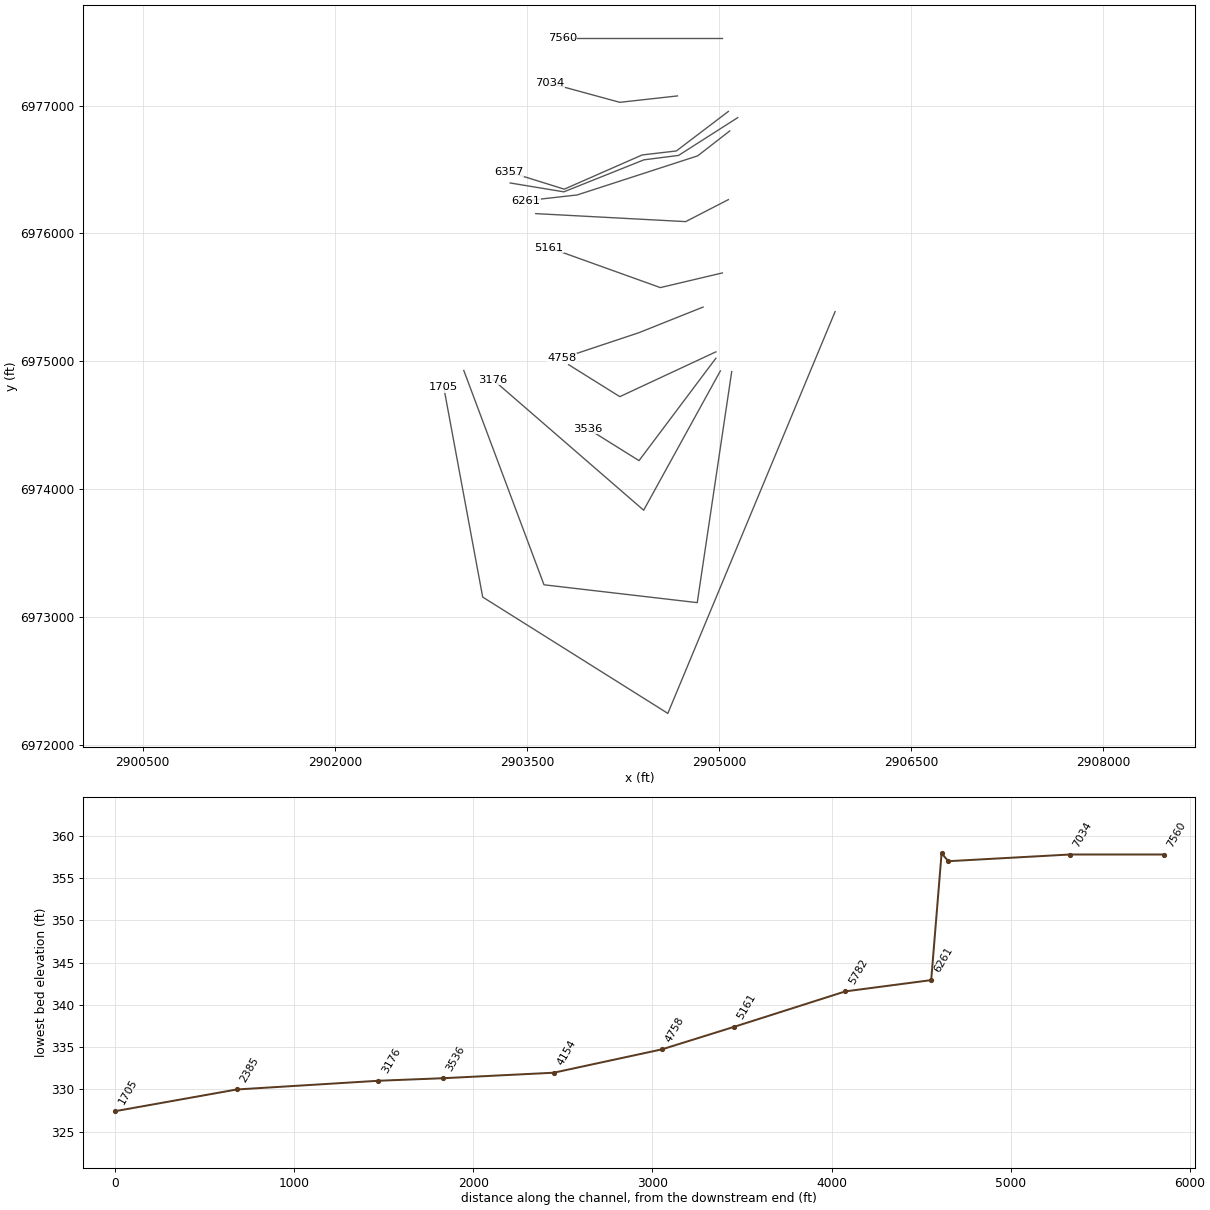
HEC-RAS study GRAVEYARD BRANCH.prj: GRAVEYARD BRANCH Base Level Engineering

--- GRAVEYARD BRANCH.g01 (geometry) --- (continued)

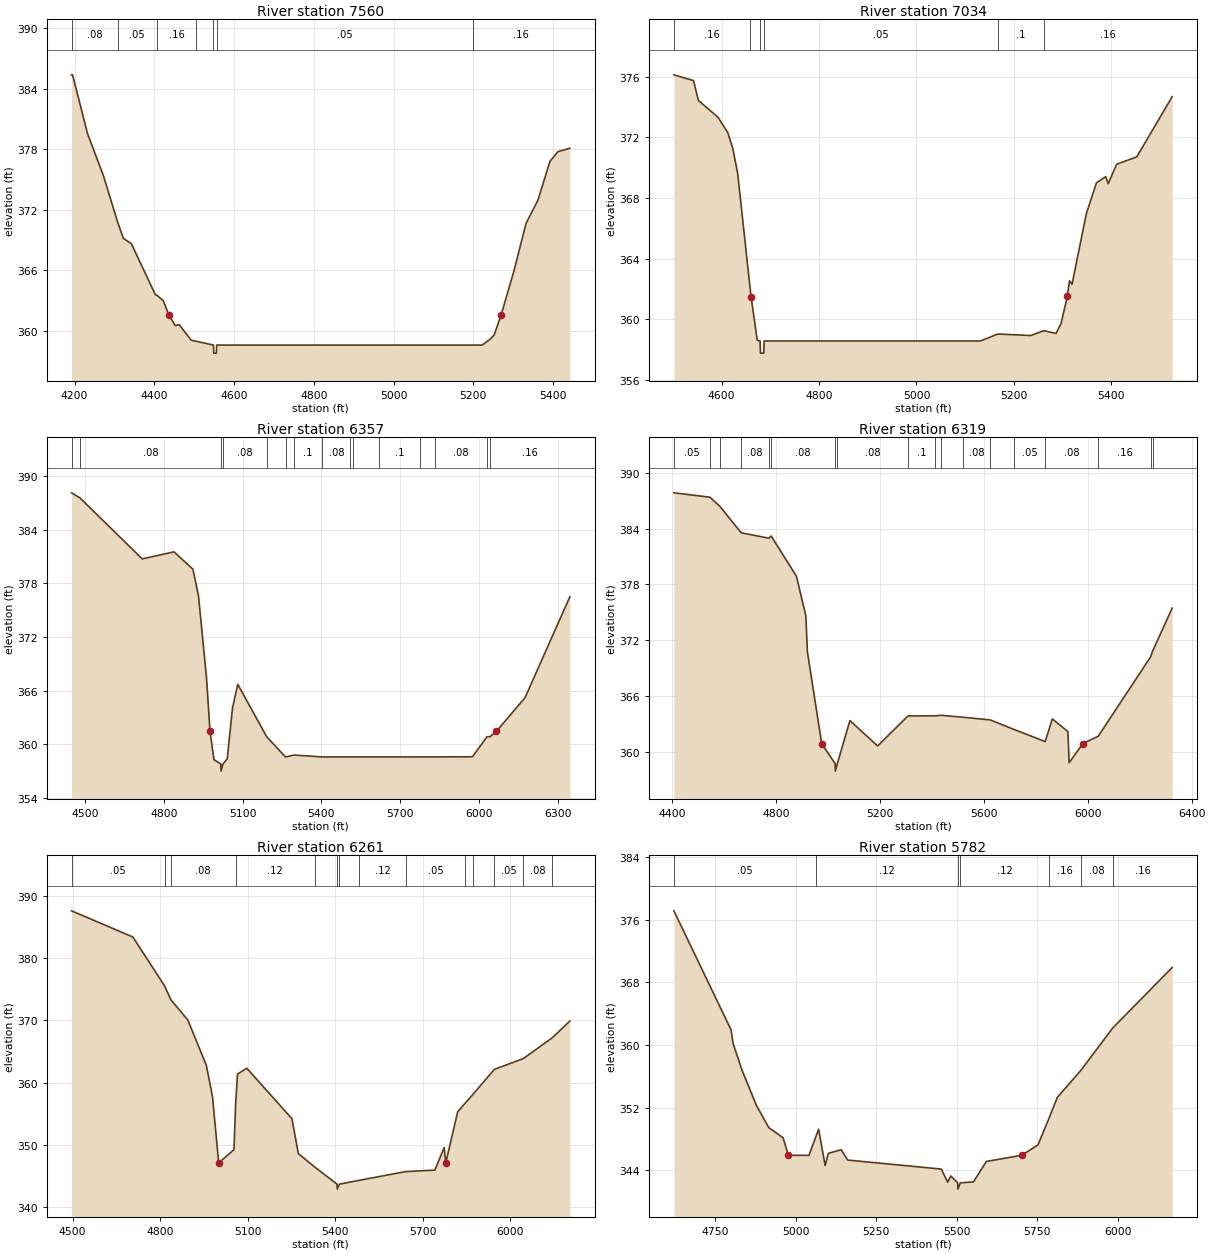
Type RM Length L Ch R = 1,7560,526,526,526
BEGIN DESCRIPTION:
GRAVEYARD BRANCH 10.0
END DESCRIPTION:
XS GIS Cut Line= 3
      2905024.97      6977525.00      2904225.00      6977525.00
      2903774.97      6977525.00
#Sta/Elev= 30
  4192.4  385.39  4194.9  385.39  4232.4  379.56  4272.4  375.36  4307.6  370.81
  4322.4  369.15  4342.4  368.62  4402.4  363.57  4406.7  363.51  4422.4  362.96
  4436.8  361.53  4452.4  360.50  4462.4  360.59  4492.4  359.04  4505.7  358.93
  4548.4  358.56  4549.0  357.76  4555.7  357.76  4556.4  358.56  5198.9  358.56
  5222.4  358.56  5242.4  359.14  5252.4  359.56  5269.8  361.53  5302.4  365.96
  5332.4  370.63  5362.4  372.96  5392.4  376.80  5412.4  377.76  5442.4  378.10
#Mann=7,-1,0
  4192.4    0.08       0  4307.6    0.05       0  4406.7    0.16       0
  4505.7    0.05       0  4548.4   0.033       0  4556.4    0.05       0
  5198.9    0.16       0
Bank Sta=4436.8,5269.8
Exp/Cntr=0.3,0.1

Type RM Length L Ch R = 1,7034,677,677,677
BEGIN DESCRIPTION:
GRAVEYARD BRANCH 9.0
END DESCRIPTION:
XS GIS Cut Line= 3
      2904675.02      6977075.00      2904225.00      6977025.00
      2903674.97      6977175.01
#Sta/Elev= 30
  4502.1  376.12  4542.4  375.74  4552.4  374.43  4592.7  373.32  4612.8  372.30
  4622.9  371.28  4632.9  369.65  4658.1  362.18  4660.5  361.49  4673.2  358.61
  4679.1  358.56  4679.8  357.76  4686.6  357.76  4687.3  358.56  5131.1  358.56
  5167.1  359.02  5234.7  358.92  5261.5  359.24  5286.6  359.06  5296.9  359.72
  5309.7  361.50  5314.2  362.53  5319.4  362.30  5348.8  366.96  5369.5  368.99
  5388.5  369.40  5393.7  368.94  5411.0  370.22  5452.4  370.71  5525.0  374.68
#Mann=6,-1,0
  4502.1    0.16       0  4658.1    0.05       0  4679.1   0.033       0
  4687.3    0.05       0  5167.1     0.1       0  5261.5    0.16       0
Bank Sta=4660.5,5309.7
Exp/Cntr=0.3,0.1

Type RM Length L Ch R = 1,6357,38,38,38
BEGIN DESCRIPTION:
Mapping XS 490e5864
END DESCRIPTION:
XS GIS Cut Line= 5
      2905072.73      6976953.92      2904666.48      6976644.90
      2904399.12      6976613.65      2903791.48      6976346.28
      2903358.72      6976481.31
#Sta/Elev= 30
  4449.1  388.14  4480.6  387.58  4718.1  380.74  4838.8  381.53  4911.1  379.58
  4932.3  376.58  4962.8  367.39  4976.0  361.43  4991.2  358.25  5017.3  357.77
  5018.0  356.97  5025.5  357.77  5041.6  358.35  5061.7  364.05  5081.8  366.69
  5192.0  360.81  5263.4  358.56  5296.2  358.77  5403.3  358.56  5510.4  358.56
  5520.0  358.56  5617.5  358.56  5776.6  358.56  5831.7  358.56  5975.1  358.58
  6030.7  360.83  6042.2  360.83  6066.2  361.43  6175.3  365.20  6345.9  376.50
#Mann=15,-1,0
  4449.1    0.05       0  4480.6    0.08       0  5017.3    0.07       0
  5025.5    0.08       0  5192.0    0.05       0  5263.4    0.08       0
  5296.2     0.1       0  5403.3    0.08       0  5510.4    0.05       0
  5520.0    0.08       0  5617.5     0.1       0  5776.6    0.05       0
  5831.7    0.08       0  6030.7    0.05       0  6042.2    0.16       0
Bank Sta=4976,6066.2
Exp/Cntr=0.3,0.1

Type RM Length L Ch R = 1,6319,58,58,58
BEGIN DESCRIPTION:
Mapping XS f5162f7a
END DESCRIPTION:
XS GIS Cut Line= 5
      2905145.68      6976905.33      2904683.85      6976610.17
      2904413.01      6976575.45      2903788.01      6976325.45
      2903368.90      6976394.73
#Sta/Elev= 30
  4405.9  387.84  4544.5  387.37  4582.8  386.40  4665.0  383.54  4771.4  382.96
  4780.8  383.18  4877.8  378.87  4914.1  374.60  4920.1  370.74  4975.1  360.85
  5027.1  358.69  5027.8  357.89  5035.3  358.69  5083.9  363.33  5190.5  360.60
  5307.6  363.83  5413.2  363.84  5434.6  363.90  5518.9  363.69  5624.6  363.40
  5714.4  362.39  5835.9  361.07  5863.4  363.51  5923.3  362.15  5928.3  358.80
  5980.9  360.85  6040.4  361.65  6242.0  370.19  6249.4  370.79  6325.0  375.44
#Mann=18,-1,0
  4405.9    0.05       0  4544.5    0.08       0  4582.8    0.05       0
  4665.0    0.08       0  4771.4    0.05       0  4780.8    0.08       0
  5027.1    0.07       0  5035.3    0.08       0  5307.6     0.1       0
  5413.2    0.08       0  5434.6    0.05       0  5518.9    0.08       0
  5624.6     0.1       0  5714.4    0.05       0  5835.9    0.08       0
  6040.4    0.16       0  6242.0    0.08       0  6249.4    0.16       0
Bank Sta=4975.1,5980.9
Exp/Cntr=0.3,0.1

Type RM Length L Ch R = 1,6261,479,479,479
BEGIN DESCRIPTION:
Mapping XS 222fec28
END DESCRIPTION:
XS GIS Cut Line= 4
      2905083.12      6976801.12      2904833.15      6976606.70
      2903892.18      6976301.15      2903492.84      6976256.00
#Sta/Elev= 30
  4496.3  387.56  4706.4  383.36  4815.3  375.50  4836.8  373.29  4894.7  370.05
  4958.2  362.78  4979.3  357.73  5000.6  347.12  5052.9  349.26  5058.5  356.49
  5065.0  361.37  5096.9  362.31  5251.5  354.22  5273.6  348.61  5330.9  346.42
  5406.2  343.72  5406.9  342.92  5414.4  343.72  5482.4  344.33  5640.9  345.73
  5741.4  345.97  5773.4  349.59  5778.8  347.12  5819.6  355.30  5845.9  356.74
  5871.2  358.07  5945.3  362.13  6044.7  363.86  6144.1  367.21  6204.2  369.88
#Mann=14,-1,0
  4496.3    0.05       0  4815.3    0.12       0  4836.8    0.08       0
  5058.5    0.12       0  5330.9    0.05       0  5406.2    0.07       0
  5414.4    0.05       0  5482.4    0.12       0  5640.9    0.05       0
  5845.9    0.08       0  5871.2    0.12       0  5945.3    0.05       0
  6044.7    0.08       0  6144.1    0.05       0
Bank Sta=5000.6,5778.8
Exp/Cntr=0.3,0.1

Type RM Length L Ch R = 1,5782,621,621,621
BEGIN DESCRIPTION:
Mapping XS cec3d402
END DESCRIPTION:
XS GIS Cut Line= 3
      2905072.72      6976264.68      2904739.40      6976092.81
      2903568.79      6976155.24
#Sta/Elev= 30
  4621.3  377.11  4798.8  361.92  4805.2  360.17  4833.0  356.76  4877.5  352.28
  4916.0  349.44  4960.4  348.14  4976.8  345.91  5040.8  345.90  5062.3  348.30
  5070.8  349.25  5090.9  344.61  5100.9  346.16  5140.9  346.62  5161.0  345.30
  5451.4  344.15  5471.4  342.49  5481.4  343.27  5502.5  342.39  5503.2  341.59
  5510.7  342.39  5551.5  342.51  5591.6  345.12  5701.4  345.91  5751.8  347.23
  5785.2  350.54  5811.9  353.30  5884.5  356.72  5983.7  362.14  6168.6  369.88
#Mann=7,-1,0
  4621.3    0.05       0  5062.3    0.12       0  5502.5    0.03       0
  5510.7    0.12       0  5785.2    0.16       0  5884.5    0.08       0
  5983.7    0.16       0
Bank Sta=4976.8,5701.4
Exp/Cntr=0.3,0.1

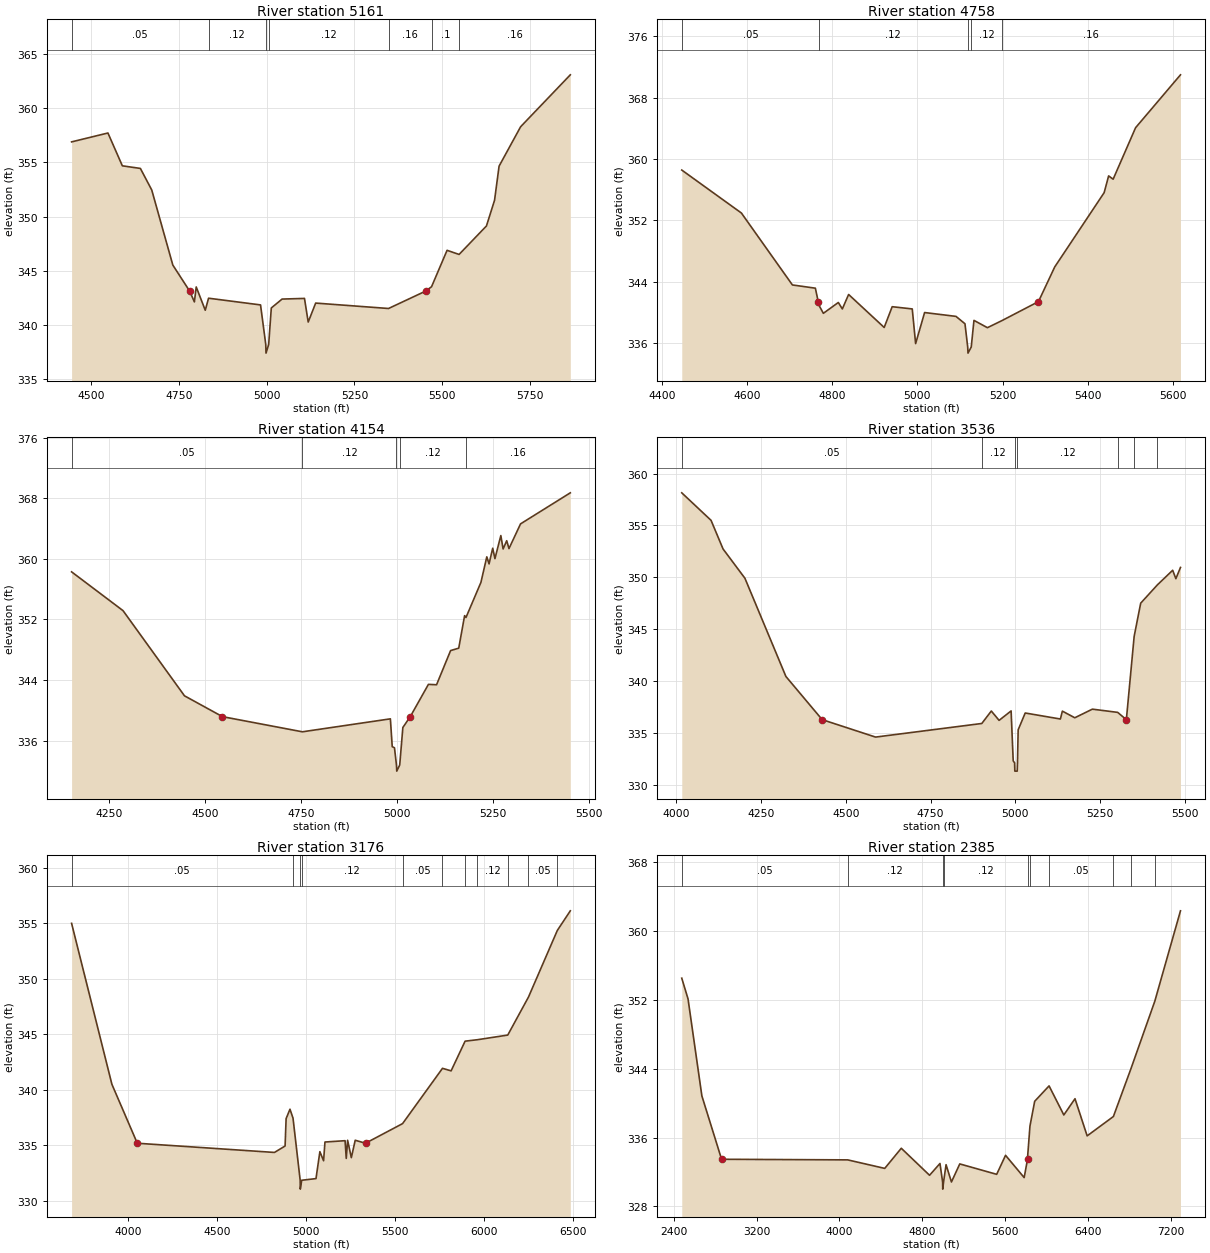
Type RM Length L Ch R = 1,5161,403,403,403
BEGIN DESCRIPTION:
Mapping XS cc3444c3
END DESCRIPTION:
XS GIS Cut Line= 3
      2905025.82      6975691.76      2904541.48      6975577.19
      2903671.72      6975889.68
#Sta/Elev= 30
  4443.6  356.90  4547.2  357.72  4588.3  354.69  4639.7  354.45  4672.1  352.46
  4732.2  345.53  4780.1  343.13  4793.7  342.13  4798.9  343.51  4824.7  341.36
  4834.1  342.47  4982.3  341.85  4997.2  338.20  4997.9  337.40  5005.5  338.20
  5013.0  341.57  5043.8  342.39  5107.6  342.45  5118.2  340.27  5139.5  342.02
  5347.2  341.52  5453.3  343.13  5469.9  343.53  5514.1  346.89  5548.4  346.51
  5626.4  349.14  5649.5  351.51  5662.4  354.66  5723.9  358.30  5865.5  363.09
#Mann=7,-1,0
  4443.6    0.05       0  4834.1    0.12       0  4997.2    0.07       0
  5005.5    0.12       0  5347.2    0.16       0  5469.9     0.1       0
  5548.4    0.16       0
Bank Sta=4780.1,5453.3
Exp/Cntr=0.3,0.1

Type RM Length L Ch R = 1,4758,604,604,604
BEGIN DESCRIPTION:
GRAVEYARD BRANCH 5.0
END DESCRIPTION:
XS GIS Cut Line= 3
      2904875.01      6975425.00      2904375.00      6975225.00
      2903774.99      6975025.00
#Sta/Elev= 30
  4446.7  358.56  4586.7  352.97  4706.5  343.61  4760.4  343.19  4767.1  341.44
  4769.0  340.95  4779.2  339.92  4814.3  341.33  4823.7  340.49  4838.5  342.37
  4922.0  338.08  4940.8  340.78  4987.9  340.49  4995.8  335.98  5016.9  340.02
  5090.6  339.52  5111.7  338.56  5118.1  335.54  5118.8  334.74  5126.4  335.54
  5132.8  339.00  5164.4  338.05  5198.8  338.98  5284.2  341.44  5322.5  345.96
  5438.5  355.62  5449.0  357.80  5459.6  357.37  5512.3  364.07  5617.7  370.95
#Mann=5,-1,0
  4446.7    0.05       0  4769.0    0.12       0  5118.1    0.07       0
  5126.4    0.12       0  5198.8    0.16       0
Bank Sta=4767.1,5284.2
Exp/Cntr=0.3,0.1

Type RM Length L Ch R = 1,4154,618,618,618
BEGIN DESCRIPTION:
GRAVEYARD BRANCH 4.0
END DESCRIPTION:
XS GIS Cut Line= 3
      2904975.04      6975075.02      2904225.00      6974725.00
      2903824.99      6974975.00
#Sta/Elev= 30
  4152.2  358.28  4286.2  353.16  4446.3  341.92  4545.3  339.17  4753.5  337.17
  4982.8  338.88  4987.6  335.21  4993.5  335.06  4998.6  332.78  4999.4  331.98
  5007.1  332.78  5015.3  337.74  5034.6  339.17  5081.9  343.43  5103.1  343.38
  5139.7  347.89  5160.9  348.21  5176.2  352.50  5179.8  352.26  5218.7  356.89
  5234.0  360.26  5239.9  359.33  5249.4  361.40  5255.2  360.02  5270.6  363.07
  5276.5  361.30  5285.9  362.39  5291.8  361.35  5321.9  364.61  5451.6  368.71
#Mann=5,-1,0
  4152.2    0.05       0  4753.5    0.12       0  4998.6    0.07       0
  5007.1    0.12       0  5179.8    0.16       0
Bank Sta=4545.3,5034.6
Exp/Cntr=0.3,0.1

Type RM Length L Ch R = 1,3536,360,360,360
BEGIN DESCRIPTION:
GRAVEYARD BRANCH 3.0
END DESCRIPTION:
XS GIS Cut Line= 3
      2904974.99      6975024.98      2904375.00      6974225.00
      2903974.98      6974475.01
#Sta/Elev= 30
  4015.7  358.14  4102.1  355.49  4137.6  352.73  4202.1  349.91  4323.0  340.45
  4430.0  336.29  4587.6  334.61  4901.1  335.92  4929.2  337.12  4952.1  336.22
  4987.6  337.13  4993.8  332.31  4997.9  332.13  4998.6  331.33  5005.6  331.33
  5006.4  332.13  5008.4  335.31  5029.2  336.93  5133.0  336.35  5138.9  337.11
  5175.5  336.47  5227.4  337.30  5302.1  336.99  5327.7  336.29  5350.7  344.31
  5370.0  347.51  5419.5  349.28  5464.4  350.68  5473.8  349.87  5487.4  350.95
#Mann=7,-1,0
  4015.7    0.05       0  4901.1    0.12       0  4997.9    0.07       0
  5006.4    0.12       0  5302.1    0.16       0  5350.7    0.05       0
  5419.5    0.16       0
Bank Sta=4430,5327.7
Exp/Cntr=0.3,0.1

Type RM Length L Ch R = 1,3176,791,791,791
BEGIN DESCRIPTION:
Mapping XS 0db38745
END DESCRIPTION:
XS GIS Cut Line= 3
      2905010.24      6974926.16      2904411.28      6973837.60
      2903234.16      6974858.47
#Sta/Elev= 30
  3683.4  355.01  3909.7  340.49  4052.3  335.17  4822.6  334.34  4882.3  334.92
  4888.0  337.39  4909.7  338.24  4926.8  337.44  4967.0  331.83  4967.7  331.03
  4975.6  331.83  5055.8  331.98  5077.7  334.41  5098.5  333.59  5106.2  335.28
  5219.1  335.40  5225.8  333.80  5233.4  335.44  5254.3  333.87  5276.1  335.44
  5333.9  335.17  5542.0  336.94  5766.2  341.93  5814.6  341.70  5893.2  344.38
  5962.3  344.51  6132.7  344.93  6249.1  348.36  6411.1  354.37  6484.0  356.14
#Mann=11,-1,0
  3683.4    0.05       0  4926.8    0.12       0  4967.0    0.07       0
  4975.6    0.12       0  5542.0    0.05       0  5766.2    0.12       0
  5893.2    0.16       0  5962.3    0.12       0  6132.7    0.16       0
  6249.1    0.05       0  6411.1    0.16       0
Bank Sta=4052.3,5333.9
Exp/Cntr=0.3,0.1

Type RM Length L Ch R = 1,2385,680,680,680
BEGIN DESCRIPTION:
GRAVEYARD BRANCH 2.0
END DESCRIPTION:
XS GIS Cut Line= 4
      2905098.78      6974920.98      2904829.68      6973115.38
      2903633.01      6973254.74      2903006.77      6974929.59
#Sta/Elev= 30
  2477.7  354.52  2538.3  352.11  2671.9  340.84  2862.4  333.47  4081.0  333.40
  4438.8  332.41  4598.7  334.75  4871.7  331.61  4972.4  332.98  4998.3  330.80
  4999.1  330.00  5006.9  330.80  5031.3  332.84  5083.2  330.83  5163.7  332.93
  5520.4  331.72  5606.0  333.93  5785.9  331.34  5818.4  333.47  5819.4  333.80
  5841.9  337.33  5887.5  340.21  6026.5  342.00  6169.1  338.62  6277.0  340.51
  6394.4  336.19  6648.0  338.44  6815.5  343.93  7047.7  351.83  7296.1  362.35
#Mann=10,-1,0
  2477.7    0.05       0  4081.0    0.12       0  4998.3    0.07       0
  5006.9    0.12       0  5819.4    0.05       0  5841.9    0.12       0
  6026.5    0.05       0  6648.0     0.1       0  6815.5    0.05       0
  7047.7    0.16       0
Bank Sta=2862.4,5818.4
Exp/Cntr=0.3,0.1

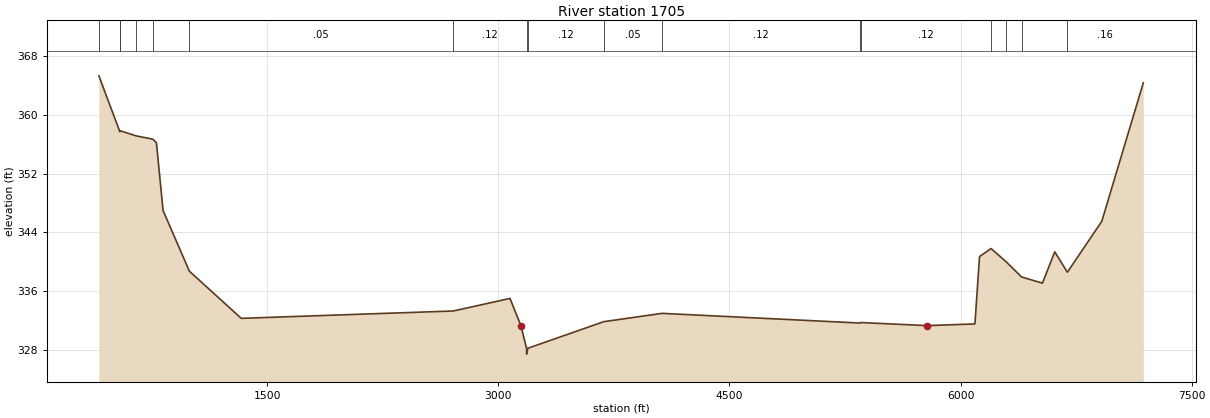
Type RM Length L Ch R = 1,1705,0,0,0
BEGIN DESCRIPTION:
GRAVEYARD BRANCH 1.0
END DESCRIPTION:
XS GIS Cut Line= 4
      2905906.07      6975389.68      2904600.00      6972250.00
      2903154.33      6973158.78      2902850.00      6974800.02
#Sta/Elev= 30
   409.0  365.31   544.8  357.71   546.1  357.84   651.8  357.13   758.8  356.69
   782.3  356.21   825.6  346.97   996.2  338.72  1332.7  332.30  2708.2  333.30
  3076.8  335.01  3147.3  331.31  3184.1  328.23  3184.8  327.43  3192.7  328.23
  3685.9  331.85  4063.7  332.98  5348.7  331.66  5352.6  331.73  5782.0  331.31
  6093.7  331.54  6123.5  340.71  6198.2  341.80  6293.8  340.05  6396.4  337.93
  6531.7  337.09  6611.6  341.35  6693.7  338.58  6916.9  345.51  7186.3  364.36
#Mann=17,-1,0
   409.0    0.05       0   544.8    0.08       0   546.1    0.15       0
   651.8     0.1       0   758.8    0.08       0   996.2    0.05       0
  2708.2    0.12       0  3184.1    0.07       0  3192.7    0.12       0
  3685.9    0.05       0  4063.7    0.12       0  5348.7    0.08       0
  5352.6    0.12       0  6198.2    0.05       0  6293.8    0.12       0
  6396.4     0.1       0  6693.7    0.16       0
Bank Sta=3147.3,5782
Exp/Cntr=0.3,0.1

Chan Stop Cuts=-1