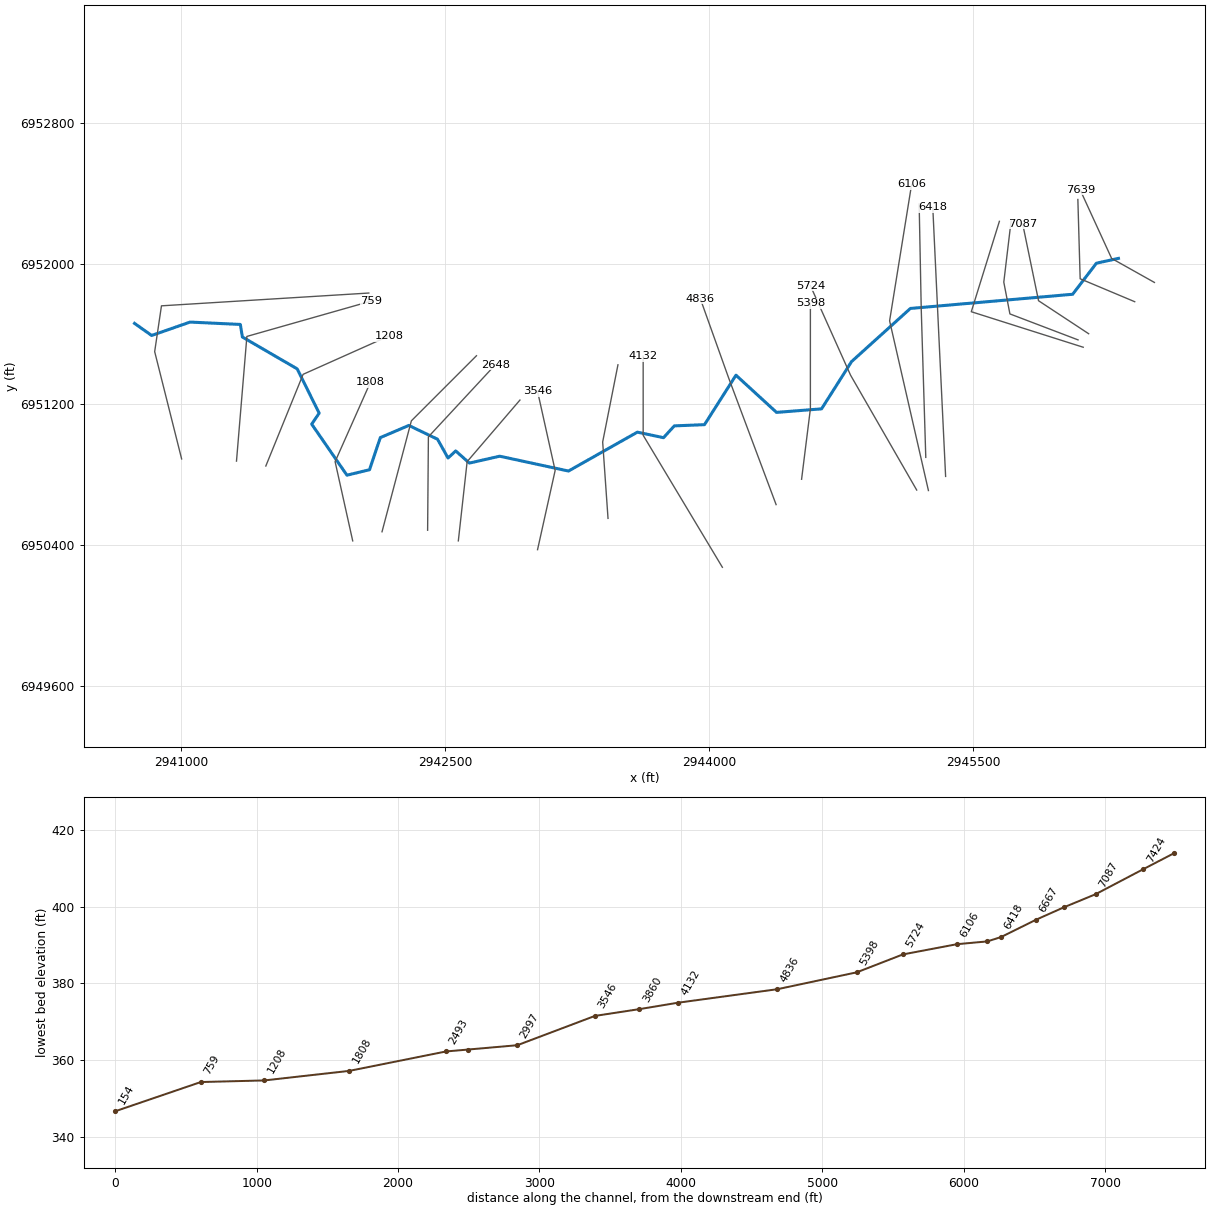
--- JONES BRANCH.prj (project) ---

Proj Title=JONES BRANCH Base Level Engineering
Current Plan=p01
Default Exp/Contr=0.3,0.1
English Units
Geom File=g01
Flow File=f01
Plan File=p01
BEGIN DESCRIPTION:
JONES BRANCH
END DESCRIPTION:

--- JONES BRANCH.p01 (plan) ---

Plan Title=Multiple Run
Short Identifier=Multiple
Geom File=g01
Flow File=f01
Subcritical Flow
K Sum by GR= 0
Std Step Tol= 0.01
Critical Tol= 0.01
Num of Std Step Trials= 20
Max Error Tol= 0.3
Flow Tol Ratio= 0.001
Split Flow NTrial= 30
Split Flow Tol= 0.02
Split Flow Ratio= 0.02
Log Output Level= 0
Friction Slope Method= 1
Unsteady Friction Slope Method= 2
Unsteady Bridges Friction Slope Method= 1
Parabolic Critical Depth
Global Vel Dist=  1 , 1 , 1
Global Log Level= 0
CheckData=True
Encroach Param= -1, 0, 0, 0
BEGIN DESCRIPTION:
Multiple Run
END DESCRIPTION:

--- JONES BRANCH.f01 (steady flow) ---

Flow Title=Multiple
Program Version=5.07
Number of Profiles= 7
Profile Names=10-year,25-year,50-year,1pct_min,100-year,1pct_plu,500-year
River Rch & RM=JONES BRANCH,Reach-1         ,7639
     224     286     335     196     392     782     534
River Rch & RM=JONES BRANCH,Reach-1         ,6418
     843    1164    1435     879    1754    3499    2624
Boundary for River Rch & Prof#=JONES BRANCH,Reach-1         , 1
Up Type= 0
Dn Type= 3
Dn Slope=0.005
Boundary for River Rch & Prof#=JONES BRANCH,Reach-1         , 2
Up Type= 0
Dn Type= 3
Dn Slope=0.005
Boundary for River Rch & Prof#=JONES BRANCH,Reach-1         , 3
Up Type= 0
Dn Type= 3
Dn Slope=0.005
Boundary for River Rch & Prof#=JONES BRANCH,Reach-1         , 4
Up Type= 0
Dn Type= 3
Dn Slope=0.005
Boundary for River Rch & Prof#=JONES BRANCH,Reach-1         , 5
Up Type= 0
Dn Type= 3
Dn Slope=0.005
Boundary for River Rch & Prof#=JONES BRANCH,Reach-1         , 6
Up Type= 0
Dn Type= 3
Dn Slope=0.005
Boundary for River Rch & Prof#=JONES BRANCH,Reach-1         , 7
Up Type= 0
Dn Type= 3
Dn Slope=0.005
DSS Import GetInterval= 0
DSS Import GetPeak= 0
DSS Import FillOption= 0

--- JONES BRANCH.g01 (geometry) ---

Geom Title=Existing Conditions

River Reach=JONES BRANCH,Reach-1
Reach XY= 30
      2946325.01      6952029.85      2946199.87      6952002.52
      2946064.83      6951825.98      2945143.14      6951745.42
      2944809.02      6951443.71      2944638.46      6951175.06
      2944382.70      6951154.93      2944152.18      6951366.19
      2943973.32      6951085.17      2943801.97      6951078.30
      2943740.67      6951011.16      2943592.11      6951042.68
      2943200.70      6950821.79      2942809.95      6950906.07
      2942637.81      6950866.93      2942560.17      6950935.93
      2942516.45      6950895.83      2942456.72      6951002.61
      2942293.71      6951080.78      2942131.84      6951011.79
      2942070.51      6950829.31      2941942.26      6950798.07
      2941741.98      6951088.19      2941784.42      6951150.55
      2941659.63      6951402.15      2941348.17      6951583.16
      2941336.76      6951654.57      2941051.11      6951667.97
      2940832.64      6951591.88      2940735.59      6951660.71

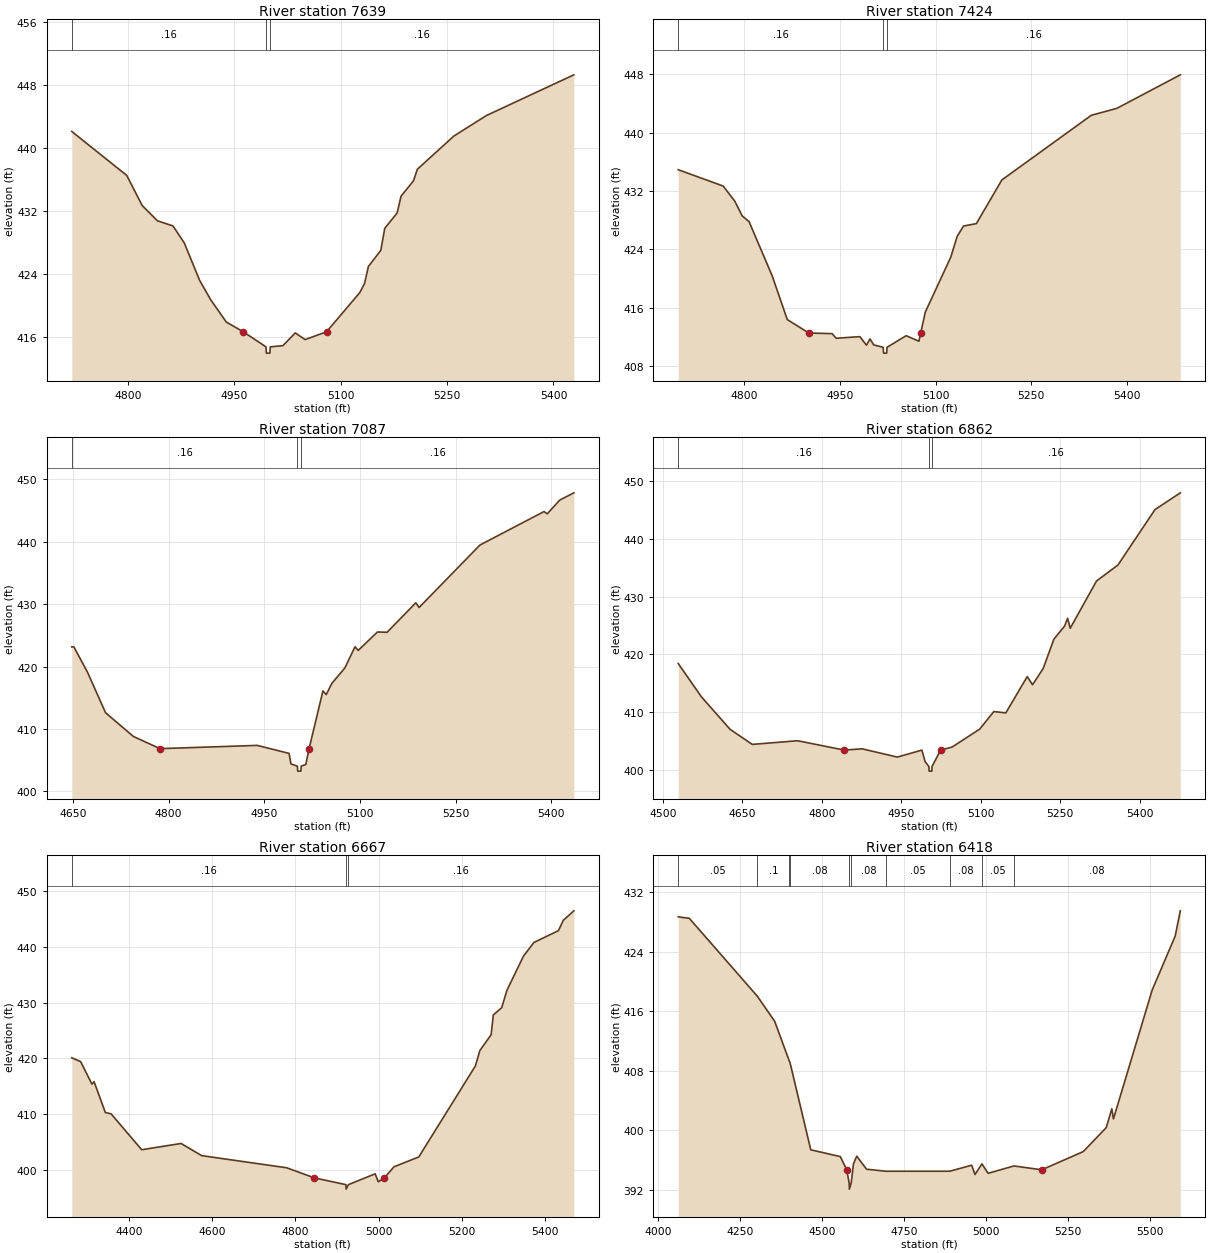
Type RM Length L Ch R = 1,7639,215,215,215
BEGIN DESCRIPTION:
JONES BRANCH 13.0
END DESCRIPTION:
XS GIS Cut Line= 3
      2946529.38      6951893.11      2946286.25      6952029.56
      2946107.47      6952419.20
#Sta/Elev= 30
  4721.2  442.09  4798.7  436.50  4820.4  432.68  4842.0  430.73  4863.8  430.08
  4879.7  427.93  4901.4  423.16  4917.3  420.65  4939.0  417.86  4962.9  416.62
  4994.9  414.71  4995.4  413.91  5000.4  413.91  5000.9  414.71  5018.7  414.86
  5036.2  416.48  5050.0  415.63  5080.2  416.62  5127.0  421.60  5133.7  422.74
  5139.2  424.93  5156.7  426.98  5162.2  429.77  5179.7  431.73  5185.2  433.86
  5202.7  435.81  5208.2  437.29  5259.7  441.51  5305.6  444.12  5428.7  449.29
#Mann=3,-1,0
  4721.2    0.16       0  4994.9    0.07       0  5000.9    0.16       0
Bank Sta=4962.9,5080.2
Exp/Cntr=0.3,0.1

Type RM Length L Ch R = 1,7424,337,337,337
BEGIN DESCRIPTION:
Mapping XS fe2d95bd
END DESCRIPTION:
XS GIS Cut Line= 3
      2946417.36      6951783.75      2946107.48      6951913.96
      2946094.46      6952364.44
#Sta/Elev= 30
  4696.7  434.94  4767.1  432.70  4785.4  430.62  4796.9  428.61  4807.7  427.82
  4843.8  420.42  4867.6  414.39  4901.3  412.55  4937.9  412.46  4944.2  411.83
  4981.3  412.05  4991.7  410.88  4997.2  411.74  5003.0  410.92  5017.9  410.59
  5018.4  409.79  5023.4  409.79  5023.9  410.59  5053.9  412.18  5073.9  411.42
  5076.7  412.55  5083.9  415.42  5123.9  422.97  5133.9  425.82  5143.9  427.22
  5163.9  427.55  5203.9  433.54  5344.0  442.40  5384.0  443.35  5483.5  447.95
#Mann=3,-1,0
  4696.7    0.16       0  5017.9    0.07       0  5023.9    0.16       0
Bank Sta=4901.3,5076.7
Exp/Cntr=0.3,0.1

Type RM Length L Ch R = 1,7087,225,225,225
BEGIN DESCRIPTION:
Mapping XS bd1c94f3
END DESCRIPTION:
XS GIS Cut Line= 3
      2946155.73      6951601.81      2945871.02      6951789.31
      2945780.75      6952226.79
#Sta/Elev= 30
  4648.0  423.15  4651.4  423.15  4672.8  419.07  4701.0  412.61  4744.7  408.81
  4786.4  406.86  4938.9  407.38  4988.9  406.10  4991.8  404.42  5001.9  404.06
  5002.4  403.26  5007.4  403.26  5007.9  404.06  5015.1  404.32  5020.3  406.86
  5042.0  416.10  5047.2  415.51  5056.0  417.31  5076.4  419.78  5092.3  423.17
  5097.4  422.59  5127.5  425.54  5142.6  425.49  5187.7  430.21  5192.9  429.46
  5288.3  439.46  5388.8  444.82  5393.9  444.46  5413.4  446.65  5435.6  447.82
#Mann=3,-1,0
  4648.0    0.16       0  5001.9    0.07       0  5007.9    0.16       0
Bank Sta=4786.4,5020.3
Exp/Cntr=0.3,0.1

Type RM Length L Ch R = 1,6862,195,195,195
BEGIN DESCRIPTION:
Mapping XS 51d74f72
END DESCRIPTION:
XS GIS Cut Line= 4
      2946095.58      6951566.78      2945708.44      6951714.34
      2945673.71      6951894.90      2945715.15      6952241.96
#Sta/Elev= 30
  4529.0  418.43  4572.4  412.71  4626.8  407.06  4668.7  404.45  4754.4  405.08
  4842.2  403.47  4876.2  403.68  4942.5  402.26  4988.9  403.46  4994.9  401.49
  5002.1  400.63  5002.6  399.83  5007.6  399.83  5008.1  400.63  5024.2  403.47
  5045.9  403.99  5097.9  407.08  5124.7  410.12  5147.4  409.90  5187.7  416.16
  5197.8  414.76  5217.9  417.57  5238.1  422.64  5258.2  424.89  5263.9  426.24
  5268.9  424.52  5318.6  432.69  5358.9  435.44  5428.8  445.01  5476.7  447.92
#Mann=3,-1,0
  4529.0    0.16       0  5002.1    0.07       0  5008.1    0.16       0
Bank Sta=4842.2,5024.2
Exp/Cntr=0.3,0.1

Type RM Length L Ch R = 1,6667,249,249,249
BEGIN DESCRIPTION:
JONES BRANCH 12.0
END DESCRIPTION:
XS GIS Cut Line= 3
      2946124.97      6951525.01      2945489.08      6951726.81
      2945648.68      6952240.33
#Sta/Elev= 30
  4263.3  420.12  4284.6  419.44  4311.7  415.41  4316.9  415.84  4343.9  410.33
  4357.7  410.09  4431.1  403.67  4525.6  404.79  4575.1  402.61  4779.1  400.44
  4845.2  398.64  4921.2  397.42  4921.7  396.62  4927.2  397.42  4991.4  399.36
  4998.8  397.93  5013.6  398.64  5036.6  400.62  5096.1  402.38  5231.9  418.66
  5242.7  421.42  5269.7  424.25  5274.9  427.79  5295.1  429.09  5307.5  432.18
  5347.4  438.32  5372.6  440.77  5431.2  442.87  5442.9  444.72  5468.2  446.42
#Mann=3,-1,0
  4263.3    0.16       0  4921.2    0.07       0  4927.2    0.16       0
Bank Sta=4845.2,5013.6
Exp/Cntr=0.3,0.1

Type RM Length L Ch R = 1,6418,97,97,97
BEGIN DESCRIPTION:
double JONES BRANCH 11.0
END DESCRIPTION:
XS GIS Cut Line= 3
      2945343.18      6950791.23      2945303.97      6951606.51
      2945270.24      6952320.69
#Sta/Elev= 30
  4060.3  428.72  4094.1  428.52  4301.5  418.04  4354.4  414.66  4399.3  409.28
  4401.1  409.12  4464.5  397.36  4554.6  396.45  4574.1  394.67  4581.7  392.87
  4582.2  392.07  4587.7  392.87  4594.7  395.48  4604.7  396.50  4634.7  394.75
  4692.9  394.48  4888.7  394.48  4955.1  395.29  4965.4  394.04  4986.5  395.47
  5005.2  394.20  5084.4  395.19  5168.8  394.67  5295.5  397.12  5365.6  400.35
  5382.6  402.88  5387.6  401.52  5505.7  418.87  5575.8  426.12  5591.5  429.53
#Mann=10,-1,0
  4060.3    0.05       0  4301.5     0.1       0  4399.3    0.16       0
  4401.1    0.08       0  4581.7    0.04       0  4587.7    0.08       0
  4692.9    0.05       0  4888.7    0.08       0  4986.5    0.05       0
  5084.4    0.08       0
Bank Sta=4574.1,5168.8
Exp/Cntr=0.3,0.1

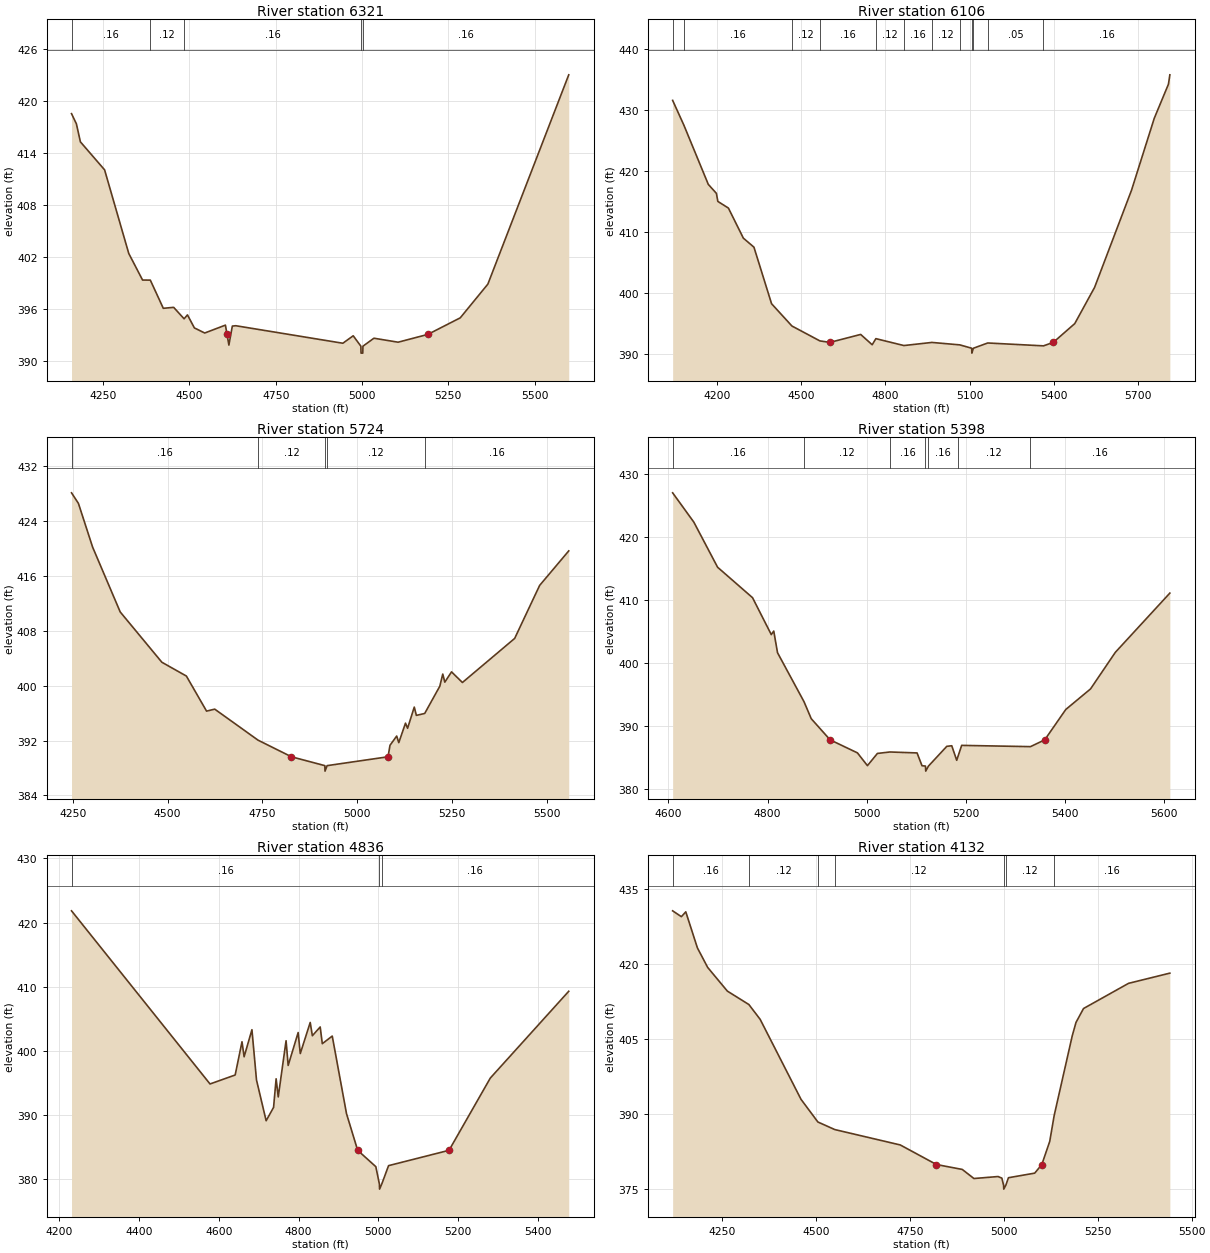
Type RM Length L Ch R = 1,6321,215,215,215
BEGIN DESCRIPTION:
double Mapping XS dbae5270
END DESCRIPTION:
XS GIS Cut Line= 3
      2945230.53      6950899.27      2945204.75      6951740.27
      2945192.85      6952339.26
#Sta/Elev= 30
  4158.4  418.56  4172.5  417.39  4184.1  415.31  4254.2  412.08  4324.2  402.44
  4364.2  399.37  4386.7  399.36  4424.3  396.11  4454.3  396.22  4484.5  394.90
  4494.3  395.35  4514.3  393.85  4544.3  393.26  4604.3  394.17  4608.9  393.10
  4614.3  391.87  4624.3  394.06  4634.4  394.10  4944.5  392.08  4974.5  392.94
  4996.7  391.74  4997.2  390.94  5002.2  390.94  5002.7  391.74  5034.5  392.66
  5104.5  392.20  5190.7  393.10  5284.6  395.01  5364.6  398.90  5598.9  423.04
#Mann=5,-1,0
  4158.4    0.16       0  4386.7    0.12       0  4484.5    0.16       0
  4996.7    0.07       0  5002.7    0.16       0
Bank Sta=4608.9,5190.7
Exp/Cntr=0.3,0.1

Type RM Length L Ch R = 1,6106,382,382,382
BEGIN DESCRIPTION:
double JONES BRANCH 10.0
END DESCRIPTION:
XS GIS Cut Line= 3
      2945245.55      6950710.98      2945025.00      6951675.00
      2945149.99      6952449.96
#Sta/Elev= 30
  4040.7  431.58  4080.9  427.51  4167.9  417.83  4196.8  416.36  4202.0  415.04
  4239.7  413.95  4293.0  409.03  4330.8  407.55  4393.6  398.30  4466.2  394.65
  4566.1  392.21  4602.0  391.97  4711.6  393.27  4752.6  391.58  4765.8  392.58
  4865.7  391.45  4965.5  391.96  5065.3  391.56  5107.7  391.01  5108.2  390.21
  5113.7  391.01  5164.8  391.87  5363.8  391.40  5398.7  391.97  5475.3  395.04
  5546.2  400.98  5677.9  416.88  5758.9  428.64  5809.6  434.23  5814.6  435.76
#Mann=12,-1,0
  4040.7    0.08       0  4080.9    0.16       0  4466.2    0.12       0
  4566.1    0.16       0  4765.8    0.12       0  4865.7    0.16       0
  4965.5    0.12       0  5065.3    0.16       0  5107.7    0.07       0
  5113.7    0.16       0  5164.8    0.05       0  5363.8    0.16       0
Bank Sta=4602,5398.7
Exp/Cntr=0.3,0.1

Type RM Length L Ch R = 1,5724,326,326,326
BEGIN DESCRIPTION:
double JONES BRANCH 9.0
END DESCRIPTION:
XS GIS Cut Line= 3
      2945178.86      6950713.84      2944803.07      6951366.60
      2944575.00      6951874.99
#Sta/Elev= 30
  4246.8  428.08  4265.0  426.54  4302.4  420.17  4375.1  410.73  4484.9  403.40
  4549.5  401.39  4602.7  396.28  4624.2  396.57  4738.4  392.05  4826.4  389.63
  4914.4  388.34  4914.9  387.54  4920.4  388.34  5081.0  389.63  5086.1  391.30
  5103.8  392.65  5109.3  391.69  5127.0  394.53  5132.5  393.78  5150.1  396.87
  5155.6  395.66  5177.6  395.94  5217.4  399.91  5225.2  401.68  5230.6  400.50
  5248.3  402.00  5277.0  400.45  5414.7  406.87  5480.5  414.59  5557.2  419.62
#Mann=5,-1,0
  4246.8    0.16       0  4738.4    0.12       0  4914.4    0.07       0
  4920.4    0.12       0  5177.6    0.16       0
Bank Sta=4826.4,5081
Exp/Cntr=0.3,0.1

Type RM Length L Ch R = 1,5398,562,562,562
BEGIN DESCRIPTION:
JONES BRANCH 8.0
END DESCRIPTION:
XS GIS Cut Line= 3
      2944525.00      6950775.04      2944575.00      6951175.00
      2944575.00      6951775.03
#Sta/Elev= 30
  4608.5  427.08  4651.3  422.42  4699.2  415.26  4769.7  410.42  4807.5  404.56
  4812.5  405.12  4820.1  401.68  4873.6  393.89  4888.1  391.20  4926.2  387.84
  4981.3  385.77  5001.5  383.74  5021.6  385.68  5046.9  385.91  5101.6  385.76
  5111.6  383.73  5118.6  383.67  5119.1  382.87  5124.6  383.67  5161.6  386.81
  5171.6  386.90  5181.6  384.59  5184.2  385.21  5191.6  386.96  5330.4  386.76
  5359.2  387.84  5401.6  392.66  5451.6  395.93  5501.6  401.74  5611.6  411.15
#Mann=7,-1,0
  4608.5    0.16       0  4873.6    0.12       0  5046.9    0.16       0
  5118.6    0.07       0  5124.6    0.16       0  5184.2    0.12       0
  5330.4    0.16       0
Bank Sta=4926.2,5359.2
Exp/Cntr=0.3,0.1

Type RM Length L Ch R = 1,4836,704,704,704
BEGIN DESCRIPTION:
JONES BRANCH 7.0
END DESCRIPTION:
XS GIS Cut Line= 3
      2944380.21      6950631.02      2944110.49      6951350.95
      2943949.99      6951800.03
#Sta/Elev= 30
  4231.2  421.84  4578.2  394.85  4641.2  396.25  4658.3  401.43  4663.6  399.09
  4683.2  403.31  4694.6  395.48  4718.8  389.12  4737.4  391.20  4743.8  395.66
  4749.1  392.83  4768.7  401.59  4774.0  397.74  4799.0  402.87  4804.3  399.59
  4829.2  404.44  4834.6  402.37  4854.2  403.74  4859.5  401.13  4884.4  402.32
  4920.1  390.23  4948.1  384.51  4993.6  381.96  5002.5  379.26  5003.0  378.46
  5008.5  379.26  5025.5  382.12  5177.0  384.51  5280.4  395.77  5476.9  409.30
#Mann=3,-1,0
  4231.2    0.16       0  5002.5    0.07       0  5008.5    0.16       0
Bank Sta=4948.1,5177
Exp/Cntr=0.3,0.1

Type RM Length L Ch R = 1,4132,272,272,272
BEGIN DESCRIPTION:
JONES BRANCH 6.0
END DESCRIPTION:
XS GIS Cut Line= 3
      2944074.98      6950275.03      2943625.00      6951025.00
      2943625.00      6951474.99
#Sta/Elev= 30
  4117.3  430.62  4140.6  429.45  4152.3  430.42  4183.3  423.20  4210.6  419.30
  4263.0  414.56  4320.4  411.87  4350.5  408.90  4459.3  392.90  4504.3  388.36
  4549.2  386.85  4723.7  383.77  4820.2  379.85  4888.9  378.87  4920.0  377.05
  4984.1  377.45  4994.4  377.13  4998.9  375.73  4999.4  374.93  5005.0  375.73
  5011.9  377.21  5081.9  378.13  5100.8  379.85  5121.9  384.48  5133.7  389.65
  5181.9  405.62  5191.9  408.29  5211.9  411.07  5331.9  416.11  5441.9  418.15
#Mann=7,-1,0
  4117.3    0.16       0  4320.4    0.12       0  4504.3    0.16       0
  4549.2    0.12       0  4998.9    0.07       0  5005.0    0.12       0
  5133.7    0.16       0
Bank Sta=4820.2,5100.8
Exp/Cntr=0.3,0.1

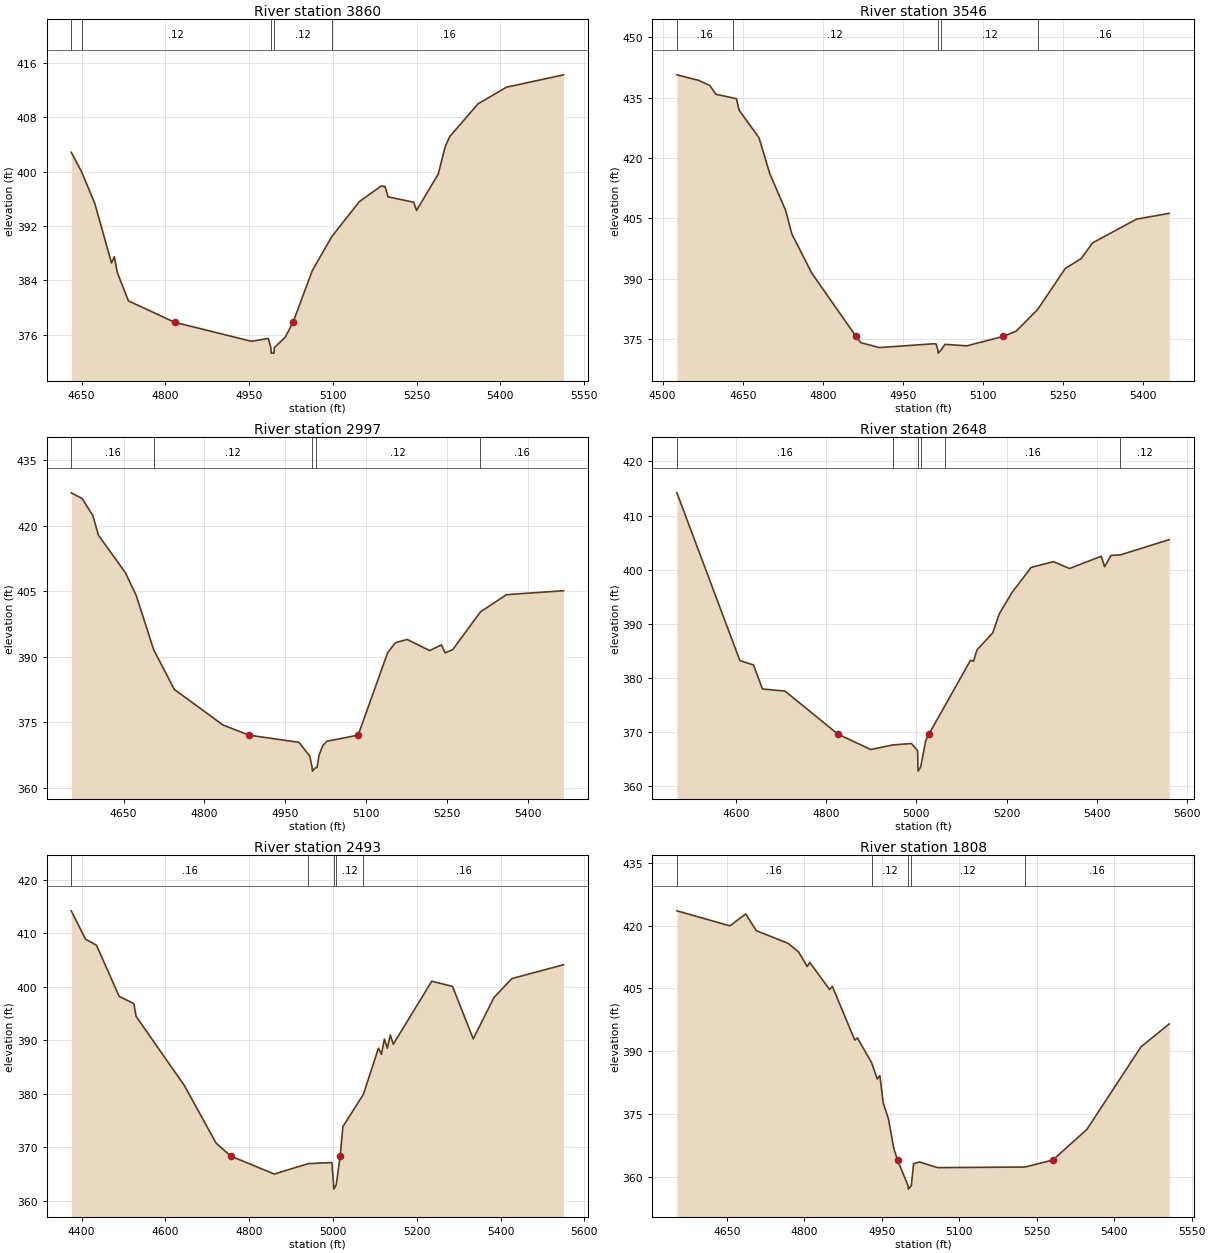
Type RM Length L Ch R = 1,3860,314,314,314
BEGIN DESCRIPTION:
Mapping XS c17939d8
END DESCRIPTION:
XS GIS Cut Line= 3
      2943425.36      6950552.84      2943394.98      6950986.87
      2943481.79      6951425.27
#Sta/Elev= 30
  4631.4  402.85  4649.8  399.99  4673.7  395.27  4703.5  386.54  4708.5  387.47
  4713.8  385.15  4733.8  380.96  4816.4  377.81  4954.3  375.00  4984.4  375.42
  4989.0  374.06  4989.5  373.26  4994.6  373.26  4995.1  374.06  5014.5  375.57
  5028.8  377.81  5063.0  385.38  5098.2  390.43  5147.5  395.58  5186.9  397.89
  5193.7  397.79  5198.8  396.29  5244.9  395.49  5250.0  394.28  5288.9  399.65
  5301.2  403.64  5309.2  405.14  5360.2  409.99  5411.2  412.44  5513.4  414.26
#Mann=5,-1,0
  4631.4    0.16       0  4649.8    0.12       0  4989.0    0.07       0
  4995.1    0.12       0  5098.2    0.16       0
Bank Sta=4816.4,5028.8
Exp/Cntr=0.3,0.1

Type RM Length L Ch R = 1,3546,549,549,549
BEGIN DESCRIPTION:
JONES BRANCH 5.0
END DESCRIPTION:
XS GIS Cut Line= 3
      2943025.00      6950375.01      2943125.00      6950825.00
      2943025.01      6951274.95
#Sta/Elev= 30
  4526.7  440.65  4567.7  439.26  4588.2  438.01  4599.7  435.82  4631.1  434.92
  4638.1  434.71  4643.2  431.86  4680.4  425.02  4700.8  416.03  4730.3  406.96
  4741.8  401.15  4778.9  391.44  4862.1  375.65  4871.1  374.09  4905.7  372.87
  5006.9  373.81  5012.0  373.78  5015.4  372.29  5015.9  371.49  5021.5  372.29
  5028.6  373.67  5069.6  373.30  5138.0  375.65  5161.8  376.93  5202.2  382.33
  5254.0  392.53  5283.5  394.95  5305.2  398.89  5387.2  404.78  5448.6  406.23
#Mann=5,-1,0
  4526.7    0.16       0  4631.1    0.12       0  5015.4    0.07       0
  5021.5    0.12       0  5202.2    0.16       0
Bank Sta=4862.1,5138
Exp/Cntr=0.3,0.1

Type RM Length L Ch R = 1,2997,349,349,349
BEGIN DESCRIPTION:
JONES BRANCH 4.0
END DESCRIPTION:
XS GIS Cut Line= 3
      2942575.00      6950425.01      2942625.00      6950875.00
      2942924.98      6951224.97
#Sta/Elev= 30
  4552.9  427.55  4573.0  426.25  4593.1  422.30  4603.2  417.87  4653.5  409.24
  4673.6  403.98  4705.9  391.62  4744.1  382.55  4834.6  374.39  4883.0  372.07
  4975.5  370.43  4995.6  367.27  5000.0  364.64  5000.5  363.84  5006.2  364.64
  5009.0  364.64  5012.8  367.49  5019.4  369.61  5027.1  370.68  5085.3  372.07
  5140.1  390.95  5154.4  393.23  5176.3  393.99  5218.0  391.43  5240.0  392.75
  5246.6  390.92  5260.8  391.63  5312.3  400.29  5360.7  404.24  5466.6  405.14
#Mann=5,-1,0
  4552.9    0.16       0  4705.9    0.12       0  5000.0    0.07       0
  5006.2    0.12       0  5312.3    0.16       0
Bank Sta=4883,5085.3
Exp/Cntr=0.3,0.1

Type RM Length L Ch R = 1,2648,155,155,155
BEGIN DESCRIPTION:
JONES BRANCH 3.0
END DESCRIPTION:
XS GIS Cut Line= 3
      2942400.54      6950485.47      2942404.95      6951016.05
      2942785.98      6951426.43
#Sta/Elev= 30
  4469.4  414.20  4608.9  383.16  4638.9  382.36  4658.9  377.91  4708.9  377.52
  4826.1  369.55  4898.9  366.71  4948.1  367.56  4989.0  367.82  5002.7  366.48
  5003.3  363.51  5003.8  362.71  5009.5  363.51  5020.6  368.36  5027.5  369.55
  5064.1  374.95  5119.8  383.22  5126.6  383.04  5134.0  385.13  5169.1  388.29
  5183.3  391.76  5211.6  395.74  5254.1  400.40  5303.5  401.46  5339.2  400.20
  5409.5  402.47  5416.9  400.53  5431.0  402.61  5451.9  402.72  5560.0  405.54
#Mann=6,-1,0
  4469.4    0.16       0  4948.1    0.12       0  5003.3    0.07       0
  5009.5    0.12       0  5064.1    0.16       0  5451.9    0.12       0
Bank Sta=4826.1,5027.5
Exp/Cntr=0.3,0.1

Type RM Length L Ch R = 1,2493,685,685,685
BEGIN DESCRIPTION:
Mapping XS b4dc41ef
END DESCRIPTION:
XS GIS Cut Line= 3
      2942141.50      6950476.70      2942308.17      6951106.95
      2942677.98      6951476.76
#Sta/Elev= 30
  4375.4  414.22  4409.3  408.93  4435.7  407.78  4489.7  398.23  4524.8  396.88
  4530.0  394.51  4645.5  381.55  4720.9  370.82  4755.7  368.40  4859.8  365.03
  4940.8  366.97  4997.4  367.18  5001.5  363.01  5002.0  362.21  5007.7  363.01
  5017.2  368.40  5023.7  373.89  5072.5  379.92  5108.5  388.55  5115.6  387.42
  5122.7  390.24  5129.8  388.54  5136.8  391.03  5143.9  389.29  5235.8  401.07
  5285.3  400.09  5334.8  390.29  5384.3  398.03  5426.7  401.55  5550.3  404.15
#Mann=5,-1,0
  4375.4    0.16       0  4940.8    0.12       0  5001.5    0.07       0
  5007.7    0.12       0  5072.5    0.16       0
Bank Sta=4755.7,5017.2
Exp/Cntr=0.3,0.1

Type RM Length L Ch R = 1,1808,600,600,600
BEGIN DESCRIPTION:
JONES BRANCH 2.0
END DESCRIPTION:
XS GIS Cut Line= 3
      2941975.00      6950424.98      2941875.00      6950875.00
      2942074.98      6951324.96
#Sta/Elev= 30
  4553.1  423.52  4655.6  419.94  4686.3  422.78  4706.8  418.79  4768.2  415.78
  4788.7  413.72  4805.4  410.24  4810.5  411.21  4848.9  404.73  4854.0  405.53
  4897.6  392.68  4902.7  393.21  4930.1  387.30  4941.1  383.40  4946.2  384.22
  4952.6  377.72  4962.9  373.82  4973.1  366.85  4980.4  364.09  5000.8  357.94
  5001.3  357.14  5007.0  357.94  5011.5  363.20  5023.0  363.62  5057.9  362.27
  5227.4  362.41  5281.3  364.09  5347.2  371.41  5451.8  391.07  5506.5  396.54
#Mann=5,-1,0
  4553.1    0.16       0  4930.1    0.12       0  5000.8    0.07       0
  5007.0    0.12       0  5227.4    0.16       0
Bank Sta=4980.4,5281.3
Exp/Cntr=0.3,0.1

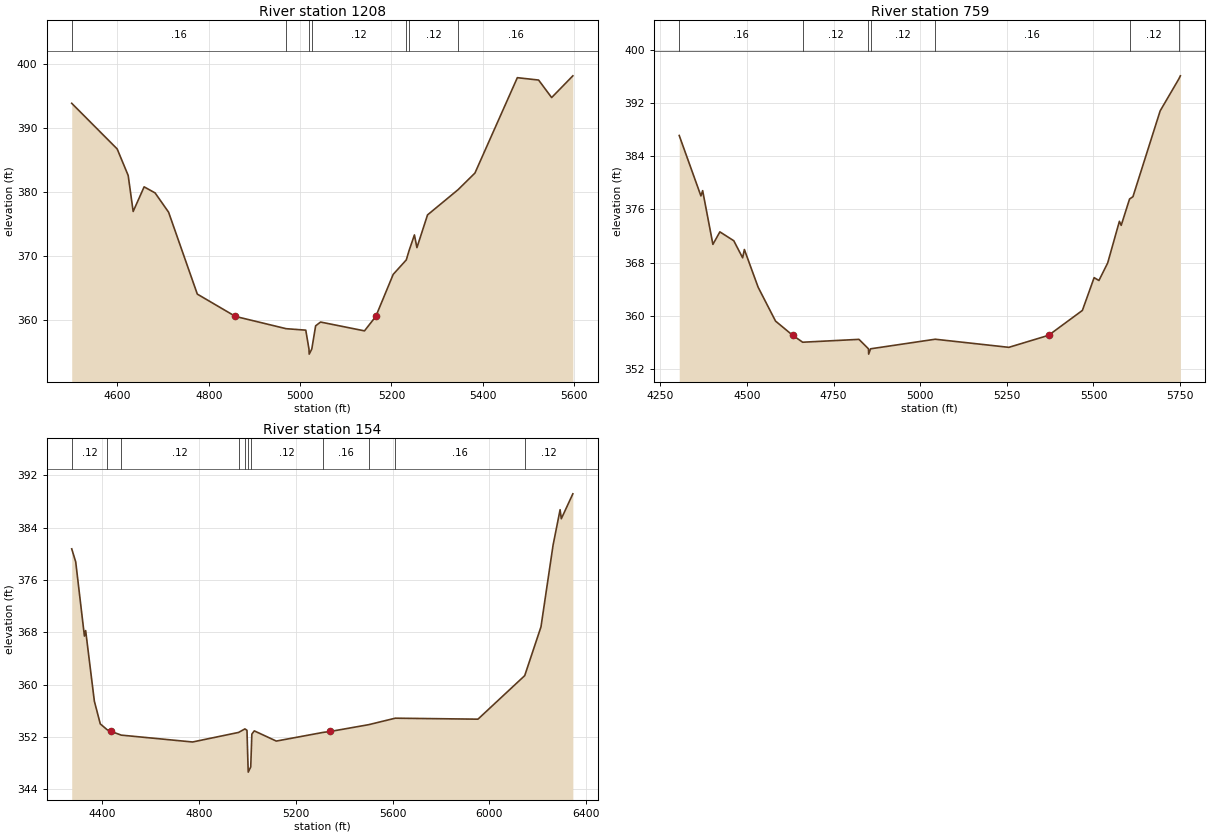
Type RM Length L Ch R = 1,1208,449,449,449
BEGIN DESCRIPTION:
Mapping XS 89373878
END DESCRIPTION:
XS GIS Cut Line= 3
      2941481.45      6950850.39      2941693.24      6951371.19
      2942181.42      6951589.31
#Sta/Elev= 30
  4500.2  393.89  4599.7  386.75  4623.8  382.60  4634.7  376.97  4658.7  380.82
  4682.7  379.87  4712.2  376.86  4775.1  364.04  4858.5  360.55  4969.5  358.63
  5012.5  358.40  5019.5  355.45  5020.0  354.65  5025.7  355.45  5034.1  359.08
  5044.9  359.67  5141.0  358.29  5165.8  360.55  5203.9  367.13  5232.5  369.39
  5238.5  370.82  5250.3  373.30  5255.8  371.31  5279.0  376.43  5345.9  380.38
  5382.8  382.98  5475.6  397.90  5522.1  397.53  5550.7  394.79  5597.1  398.19
#Mann=7,-1,0
  4500.2    0.16       0  4969.5    0.12       0  5019.5    0.07       0
  5025.7    0.12       0  5232.5    0.16       0  5238.5    0.12       0
  5345.9    0.16       0
Bank Sta=4858.5,5165.8
Exp/Cntr=0.3,0.1

Type RM Length L Ch R = 1,759,605,605,605
BEGIN DESCRIPTION:
Mapping XS a11739ed
END DESCRIPTION:
XS GIS Cut Line= 3
      2941314.77      6950878.10      2941373.80      6951586.47
      2942081.05      6951787.55
#Sta/Elev= 30
  4304.6  387.10  4367.2  378.02  4372.2  378.81  4401.8  370.73  4421.9  372.61
  4462.0  371.28  4487.6  368.71  4492.6  369.96  4532.3  364.29  4582.5  359.20
  4632.0  357.06  4660.9  356.02  4823.3  356.45  4850.7  355.03  4851.2  354.23
  4856.9  355.03  5043.2  356.47  5255.8  355.25  5370.5  357.06  5468.0  360.80
  5501.9  365.73  5515.7  365.30  5541.0  367.94  5574.8  374.20  5580.0  373.59
  5604.1  377.55  5613.9  377.90  5692.4  390.80  5746.4  395.61  5750.7  396.07
#Mann=7,-1,0
  4304.6    0.16       0  4660.9    0.12       0  4850.7    0.07       0
  4856.9    0.12       0  5043.2    0.16       0  5604.1    0.12       0
  5746.4    0.16       0
Bank Sta=4632,5370.5
Exp/Cntr=0.3,0.1

Type RM Length L Ch R = 1,154,0,0,0
BEGIN DESCRIPTION:
JONES BRANCH 1.0
END DESCRIPTION:
XS GIS Cut Line= 4
      2941003.14      6950890.51      2940850.00      6951500.00
      2940888.56      6951760.30      2942066.54      6951833.00
#Sta/Elev= 30
  4273.0  380.76  4289.5  378.77  4325.5  367.42  4330.6  368.26  4366.6  357.46
  4391.1  353.99  4419.3  353.10  4436.5  352.83  4477.8  352.27  4772.6  351.22
  4962.6  352.68  4989.0  353.22  4997.5  353.01  5002.0  347.41  5002.8  346.61
  5013.1  347.41  5017.7  352.43  5027.8  352.92  5118.8  351.36  5312.6  352.69
  5342.1  352.83  5500.9  353.87  5610.6  354.86  5952.5  354.71  6145.8  361.37
  6213.0  368.83  6263.1  381.35  6292.1  386.75  6297.1  385.37  6344.8  389.18
#Mann=11,-1,0
  4273.0    0.12       0  4419.3    0.16       0  4477.8    0.12       0
  4962.6    0.16       0  4989.0    0.12       0  5002.0    0.07       0
  5013.1    0.12       0  5312.6    0.16       0  5500.9    0.12       0
  5610.6    0.16       0  6145.8    0.12       0
Bank Sta=4436.5,5342.1
Exp/Cntr=0.3,0.1

Chan Stop Cuts=-1