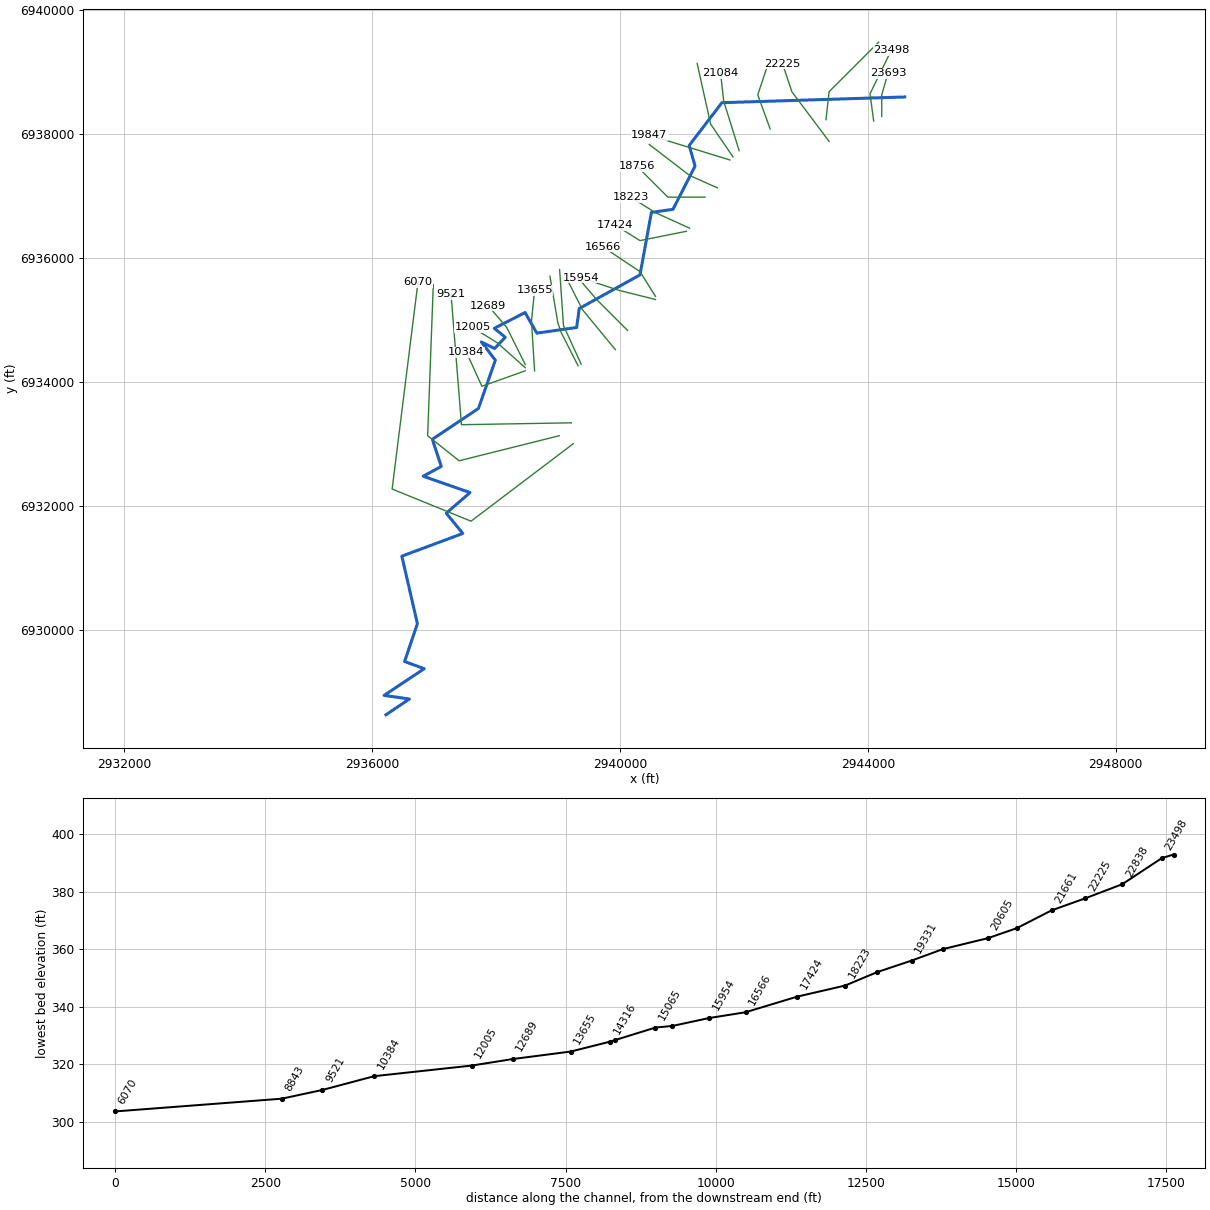
--- LACEY BRANCH.prj (project) ---

Proj Title=LACEY BRANCH Base Level Engineering
Current Plan=p01
Default Exp/Contr=0.3,0.1
English Units
Geom File=g01
Flow File=f01
Plan File=p01
BEGIN DESCRIPTION:
LACEY BRANCH
END DESCRIPTION:

--- LACEY BRANCH.p01 (plan) ---

Plan Title=Multiple Run
Short Identifier=Multiple
Geom File=g01
Flow File=f01
Subcritical Flow
K Sum by GR= 0
Std Step Tol= 0.01
Critical Tol= 0.01
Num of Std Step Trials= 20
Max Error Tol= 0.3
Flow Tol Ratio= 0.001
Split Flow NTrial= 30
Split Flow Tol= 0.02
Split Flow Ratio= 0.02
Log Output Level= 0
Friction Slope Method= 1
Unsteady Friction Slope Method= 2
Unsteady Bridges Friction Slope Method= 1
Parabolic Critical Depth
Global Vel Dist=  1 , 1 , 1
Global Log Level= 0
CheckData=True
Encroach Param= -1, 0, 0, 0
BEGIN DESCRIPTION:
Multiple Run
END DESCRIPTION:

--- LACEY BRANCH.f01 (steady flow) ---

Flow Title=Multiple
Number of Profiles=7
Profile Names=10-year,25-year,50-year,1pct_min,100-year,1pct_plu,500-year
River Rch & RM= LACEY BRANCH,Reach-1,23693
     466     626     756     456     910    1815    1317
River Rch & RM= LACEY BRANCH,Reach-1,22838
     966    1353    1682    1040    2075    4141    3165
River Rch & RM= LACEY BRANCH,Reach-1,19847
    1106    1556    1941    1203    2400    4790    3679
River Rch & RM= LACEY BRANCH,Reach-1,16566
    1511    2157    2716    1698    3387    6758    5279
River Rch & RM= LACEY BRANCH,Reach-1,13655
    1540    2178    2726    1691    3374    6732    5183
Boundary for River Rch & Prof#=LACEY BRANCH,Reach-1,1
Up Type=0
Dn Type=3
Dn Slope=0.005
Boundary for River Rch & Prof#=LACEY BRANCH,Reach-1,2
Up Type=0
Dn Type=3
Dn Slope=0.005
Boundary for River Rch & Prof#=LACEY BRANCH,Reach-1,3
Up Type=0
Dn Type=3
Dn Slope=0.005
Boundary for River Rch & Prof#=LACEY BRANCH,Reach-1,4
Up Type=0
Dn Type=3
Dn Slope=0.005
Boundary for River Rch & Prof#=LACEY BRANCH,Reach-1,5
Up Type=0
Dn Type=3
Dn Slope=0.005
Boundary for River Rch & Prof#=LACEY BRANCH,Reach-1,6
Up Type=0
Dn Type=3
Dn Slope=0.005
Boundary for River Rch & Prof#=LACEY BRANCH,Reach-1,7
Up Type=0
Dn Type=3
Dn Slope=0.005

--- LACEY BRANCH.g01 (geometry) ---

Geom Title=Existing Conditions

River Reach=LACEY BRANCH,Reach-1
Reach XY= 30
      2944595.59      6938590.71      2941646.31      6938498.50
      2941118.90      6937809.00      2941213.69      6937476.59
      2940857.42      6936778.81      2940509.34      6936729.06
      2940325.05      6935721.43      2939345.32      6935179.34
      2939303.53      6934873.34      2938660.92      6934782.69
      2938471.85      6935114.38      2937975.21      6934860.44
      2938152.08      6934715.80      2937979.00      6934535.20
      2937766.23      6934640.81      2937992.33      6934346.40
      2937719.47      6933567.98      2936976.17      6933070.57
      2937119.79      6932632.42      2936827.69      6932474.92
      2937584.20      6932211.11      2937200.09      6931879.08
      2937467.02      6931551.93      2936483.94      6931185.72
      2936734.60      6930097.40      2936528.43      6929487.04
      2936845.27      6929370.94      2936197.49      6928940.71
      2936606.22      6928882.47      2936226.78      6928627.67

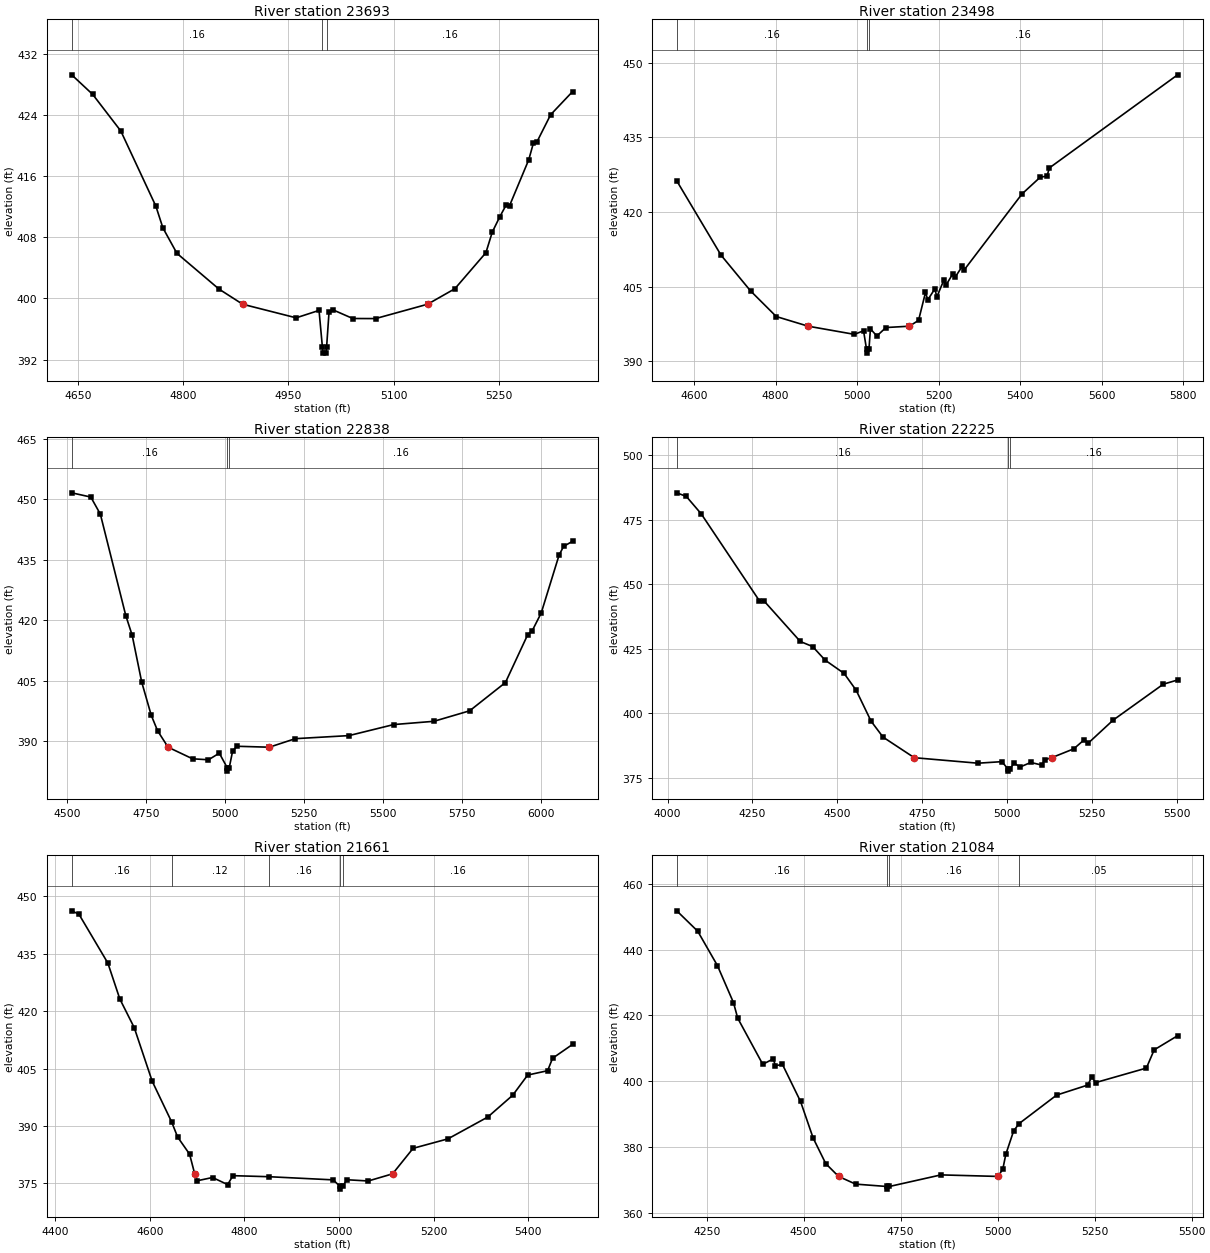
Type RM Length L Ch R = 1,23693,195,195,195
BEGIN DESCRIPTION:
LACEY BRANCH 28.0
END DESCRIPTION:
XS GIS Cut Line= 3
      2944225.00      6938274.97      2944225.00      6938625.00
      2944324.99      6938974.96
#Sta/Elev= 30
  4641.1  429.26  4671.1  426.69  4711.1  421.91  4761.1  412.07  4771.1  409.23
  4791.1  405.90  4851.1  401.22  4884.8  399.24  4961.1  397.46  4993.7  398.43
  4998.5  393.64  4999.0  392.84  5004.0  392.84  5004.5  393.64  5008.0  398.26
  5013.2  398.52  5041.8  397.37  5074.3  397.36  5148.5  399.24  5187.4  401.27
  5231.6  405.98  5240.7  408.68  5251.1  410.63  5260.2  412.18  5265.4  412.15
  5292.7  418.15  5299.2  420.28  5304.4  420.49  5323.9  424.04  5355.1  427.06
#Mann=3,-1,0
  4641.1    0.16       0  4998.5    0.07       0  5004.5    0.16       0
Bank Sta=4884.8,5148.5
Exp/Cntr=0.3,0.1

Type RM Length L Ch R = 1,23498,660,660,660
BEGIN DESCRIPTION:
LACEY BRANCH 27.0
END DESCRIPTION:
XS GIS Cut Line= 3
      2944094.70      6938203.17      2944035.11      6938641.33
      2944380.59      6939347.89
#Sta/Elev= 30
  4557.8  426.22  4666.3  411.31  4738.7  404.13  4801.9  398.97  4880.1  397.03
  4993.6  395.39  5016.0  396.11  5023.3  392.42  5023.8  391.62  5029.3  392.42
  5032.9  396.50  5048.6  395.06  5070.9  396.76  5128.6  397.03  5151.0  398.21
  5168.0  403.82  5173.6  402.32  5190.5  404.48  5196.1  402.97  5213.0  406.28
  5218.6  405.33  5235.5  407.61  5241.1  406.92  5258.0  409.05  5263.6  408.41
  5404.8  423.60  5449.3  426.95  5466.2  427.20  5471.8  428.82  5786.5  447.53
#Mann=3,-1,0
  4557.8    0.16       0  5023.3    0.07       0  5029.3    0.16       0
Bank Sta=4880.1,5128.6
Exp/Cntr=0.3,0.1

Type RM Length L Ch R = 1,22838,613,613,613
BEGIN DESCRIPTION:
LACEY BRANCH 26.0
END DESCRIPTION:
XS GIS Cut Line= 3
      2943325.00      6938224.99      2943375.00      6938675.00
      2944175.03      6939475.03
#Sta/Elev= 30
  4514.9  451.64  4575.3  450.59  4605.5  446.35  4686.0  421.15  4706.1  416.30
  4736.3  404.66  4766.4  396.43  4786.6  392.55  4819.8  388.48  4897.2  385.60
  4947.6  385.36  4981.8  387.00  5007.1  383.34  5007.6  382.54  5013.1  383.34
  5024.2  387.64  5038.4  388.71  5139.9  388.48  5222.2  390.60  5391.9  391.36
  5533.4  394.10  5660.6  394.91  5773.8  397.52  5886.9  404.54  5957.6  416.46
  5971.8  417.43  6000.1  421.81  6056.6  436.18  6070.8  438.33  6099.1  439.61
#Mann=3,-1,0
  4514.9    0.16       0  5007.1    0.07       0  5013.1    0.16       0
Bank Sta=4819.8,5139.9
Exp/Cntr=0.3,0.1

Type RM Length L Ch R = 1,22225,564,564,564
BEGIN DESCRIPTION:
LACEY BRANCH 25.0
END DESCRIPTION:
XS GIS Cut Line= 3
      2943375.01      6937874.99      2942775.00      6938675.00
      2942624.98      6939125.05
#Sta/Elev= 30
  4027.2  485.43  4055.3  484.03  4099.1  477.30  4269.9  443.73  4284.5  443.50
  4390.8  427.87  4427.2  425.90  4463.7  420.67  4519.9  415.49  4555.3  408.98
  4599.1  397.03  4634.5  390.83  4726.4  382.87  4913.7  380.74  4984.5  381.34
  5002.3  378.47  5002.8  377.67  5008.4  378.47  5019.9  380.82  5037.8  379.26
  5069.4  381.03  5101.0  380.04  5111.5  382.11  5130.9  382.87  5195.9  386.30
  5227.5  389.91  5238.0  388.44  5311.8  397.42  5459.4  411.33  5501.6  412.96
#Mann=3,-1,0
  4027.2    0.16       0  5002.3    0.07       0  5008.4    0.16       0
Bank Sta=4726.4,5130.9
Exp/Cntr=0.3,0.1

Type RM Length L Ch R = 1,21661,577,577,577
BEGIN DESCRIPTION:
LACEY BRANCH 24.0
END DESCRIPTION:
XS GIS Cut Line= 3
      2942425.00      6938075.00      2942225.00      6938625.00
      2942375.01      6939075.02
#Sta/Elev= 30
  4434.5  446.24  4449.8  445.35  4511.0  432.57  4536.3  423.19  4566.8  415.69
  4604.8  401.67  4645.8  391.07  4658.6  387.08  4683.9  382.61  4694.7  377.46
  4700.5  375.66  4732.4  376.50  4764.4  374.65  4775.7  376.98  4851.2  376.71
  4987.8  375.88  5001.4  374.26  5001.9  373.46  5007.5  374.26  5017.1  375.91
  5061.9  375.59  5113.4  377.46  5156.8  384.13  5230.6  386.61  5314.9  392.32
  5367.6  398.02  5399.2  403.29  5441.4  404.43  5451.9  407.69  5494.1  411.30
#Mann=5,-1,0
  4434.5    0.16       0  4645.8    0.12       0  4851.2    0.16       0
  5001.4    0.07       0  5007.5    0.16       0
Bank Sta=4694.7,5113.4
Exp/Cntr=0.3,0.1

Type RM Length L Ch R = 1,21084,479,479,479
BEGIN DESCRIPTION:
LACEY BRANCH 23.0
END DESCRIPTION:
XS GIS Cut Line= 3
      2941924.99      6937725.02      2941675.00      6938525.00
      2941625.00      6938975.00
#Sta/Elev= 30
  4172.9  451.76  4226.8  445.58  4277.6  435.16  4319.0  423.91  4330.0  419.17
  4394.5  405.19  4421.7  406.84  4426.9  404.76  4445.3  405.14  4491.9  393.91
  4524.4  382.81  4556.9  375.05  4590.0  371.16  4633.9  368.83  4714.5  368.11
  4715.0  367.31  4720.8  368.11  4853.9  371.63  5001.6  371.16  5013.5  373.52
  5021.1  377.91  5041.2  384.98  5055.2  387.19  5151.9  395.84  5232.4  398.90
  5242.4  401.38  5252.5  399.64  5383.3  404.04  5403.4  409.57  5463.8  413.86
#Mann=4,-1,0
  4172.9    0.16       0  4714.5    0.07       0  4720.8    0.16       0
  5055.2    0.05       0
Bank Sta=4590,5001.6
Exp/Cntr=0.3,0.1

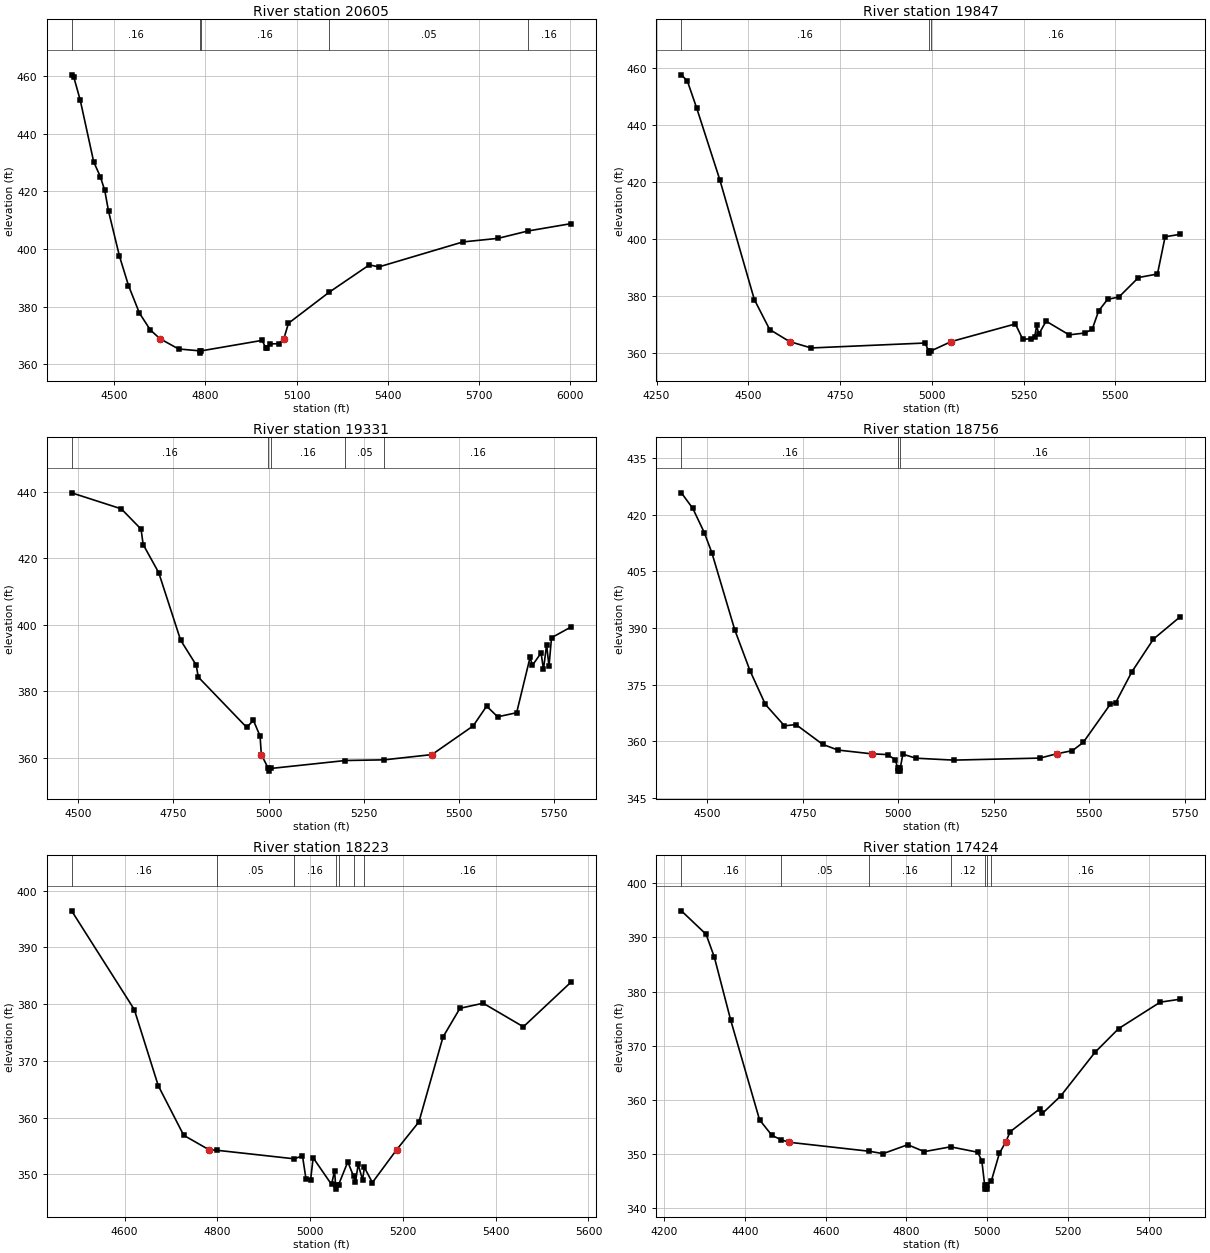
Type RM Length L Ch R = 1,20605,758,758,758
BEGIN DESCRIPTION:
LACEY BRANCH 22.0
END DESCRIPTION:
XS GIS Cut Line= 3
      2941825.03      6937624.96      2941464.51      6938153.40
      2941247.69      6939131.05
#Sta/Elev= 30
  4360.3  460.40  4367.8  459.48  4388.8  451.53  4433.0  430.17  4454.5  425.12
  4469.3  420.27  4481.6  413.12  4517.7  397.45  4547.3  387.29  4583.2  377.74
  4619.1  371.88  4650.7  368.86  4711.9  365.28  4780.9  364.64  4781.4  363.84
  4787.2  364.64  4987.0  368.27  4997.9  365.78  5003.4  365.78  5011.9  367.03
  5042.6  367.12  5058.2  368.86  5073.3  374.20  5206.9  384.95  5339.3  394.46
  5370.4  393.75  5646.9  402.42  5762.3  403.66  5860.9  406.22  6001.4  408.75
#Mann=5,-1,0
  4360.3    0.16       0  4780.9    0.07       0  4787.2    0.16       0
  5206.9    0.05       0  5860.9    0.16       0
Bank Sta=4650.7,5058.2
Exp/Cntr=0.3,0.1

Type RM Length L Ch R = 1,19847,516,516,516
BEGIN DESCRIPTION:
LACEY BRANCH 21.0
END DESCRIPTION:
XS GIS Cut Line= 3
      2941774.99      6937575.00      2941125.00      6937775.00
      2940475.03      6937974.99
#Sta/Elev= 30
  4317.5  457.52  4333.8  455.36  4359.3  445.84  4422.1  420.80  4516.3  378.77
  4558.1  368.27  4612.3  364.04  4671.3  361.80  4981.2  363.53  4991.7  360.79
  4992.2  359.99  4998.1  360.79  5052.9  364.04  5227.7  370.22  5248.0  364.80
  5269.6  365.06  5280.1  365.52  5285.9  369.76  5291.2  366.57  5311.4  371.19
  5374.2  366.39  5416.1  367.03  5437.0  368.31  5454.6  374.79  5478.8  378.80
  5510.2  379.69  5563.2  386.48  5614.9  387.72  5635.8  400.77  5677.6  401.64
#Mann=3,-1,0
  4317.5    0.16       0  4991.7    0.07       0  4998.1    0.16       0
Bank Sta=4612.3,5052.9
Exp/Cntr=0.3,0.1

Type RM Length L Ch R = 1,19331,575,575,575
BEGIN DESCRIPTION:
LACEY BRANCH 20.0
END DESCRIPTION:
XS GIS Cut Line= 3
      2941575.00      6937125.00      2941125.00      6937325.00
      2940475.00      6937825.00
#Sta/Elev= 30
  4482.2  439.62  4612.8  434.81  4664.8  428.72  4670.3  424.10  4711.3  415.63
  4768.8  395.38  4809.8  387.90  4815.3  384.29  4942.5  369.19  4960.3  371.28
  4977.8  366.55  4981.1  361.01  4999.5  356.84  5000.0  356.04  5006.0  356.84
  5202.4  359.23  5304.4  359.43  5429.8  361.01  5538.3  369.63  5573.6  375.56
  5602.6  372.35  5652.5  373.58  5687.8  390.18  5694.1  387.84  5716.8  391.52
  5723.1  386.58  5731.3  394.01  5737.6  387.54  5744.2  396.10  5794.7  399.28
#Mann=5,-1,0
  4482.2    0.16       0  4999.5    0.07       0  5006.0    0.16       0
  5202.4    0.05       0  5304.4    0.16       0
Bank Sta=4981.1,5429.8
Exp/Cntr=0.3,0.1

Type RM Length L Ch R = 1,18756,533,533,533
BEGIN DESCRIPTION:
LACEY BRANCH 19.0
END DESCRIPTION:
XS GIS Cut Line= 3
      2941375.02      6936975.00      2940775.00      6936975.00
      2940275.02      6937474.98
#Sta/Elev= 30
  4431.7  425.86  4461.7  421.71  4491.7  415.31  4511.7  409.91  4571.7  389.45
  4611.7  378.61  4651.7  369.73  4701.7  364.04  4731.7  364.39  4801.7  359.14
  4841.7  357.62  4930.1  356.62  4971.7  356.42  4991.7  355.06  4998.5  352.83
  4999.0  352.03  5004.5  352.03  5005.0  352.83  5011.7  356.53  5045.9  355.46
  5144.9  354.95  5371.1  355.49  5414.2  356.62  5456.0  357.47  5484.3  359.66
  5555.0  369.77  5569.1  370.19  5611.5  378.37  5668.1  387.07  5738.8  393.04
#Mann=3,-1,0
  4431.7    0.16       0  4998.5    0.07       0  5005.0    0.16       0
Bank Sta=4930.1,5414.2
Exp/Cntr=0.3,0.1

Type RM Length L Ch R = 1,18223,799,799,799
BEGIN DESCRIPTION:
LACEY BRANCH 18.0
END DESCRIPTION:
XS GIS Cut Line= 3
      2941124.98      6936475.01      2940575.00      6936725.00
      2940175.02      6936974.99
#Sta/Elev= 30
  4485.9  396.47  4621.0  379.05  4672.6  365.63  4727.5  356.87  4782.0  354.32
  4798.7  354.23  4965.7  352.72  4983.5  353.24  4991.2  349.10  5001.1  349.03
  5006.5  352.91  5046.1  348.20  5052.7  350.57  5054.9  348.17  5055.4  347.37
  5061.5  348.17  5081.2  352.18  5093.9  349.60  5097.7  348.61  5103.6  351.72
  5113.0  349.03  5117.0  351.19  5134.2  348.53  5186.5  354.32  5234.5  359.23
  5286.4  374.20  5322.9  379.27  5373.0  380.17  5459.7  376.01  5561.7  383.84
#Mann=7,-1,0
  4485.9    0.16       0  4798.7    0.05       0  4965.7    0.16       0
  5054.9    0.07       0  5061.5    0.16       0  5093.9    0.12       0
  5117.0    0.16       0
Bank Sta=4782,5186.5
Exp/Cntr=0.3,0.1

Type RM Length L Ch R = 1,17424,858,858,858
BEGIN DESCRIPTION:
LACEY BRANCH 17.0
END DESCRIPTION:
XS GIS Cut Line= 3
      2941075.03      6936425.01      2940325.00      6936275.00
      2939924.99      6936525.01
#Sta/Elev= 30
  4242.4  394.90  4303.6  390.57  4324.0  386.37  4364.8  374.67  4436.2  356.30
  4466.8  353.44  4489.7  352.63  4509.5  352.17  4708.3  350.51  4742.1  350.07
  4803.3  351.72  4844.1  350.44  4909.4  351.33  4976.7  350.33  4986.9  348.70
  4993.8  344.32  4994.3  343.52  4999.9  343.52  5000.4  344.32  5010.3  345.01
  5030.3  350.12  5045.6  352.17  5057.4  354.14  5130.5  358.35  5137.0  357.50
  5182.4  360.73  5267.3  368.78  5325.7  373.15  5428.9  378.04  5479.0  378.59
#Mann=7,-1,0
  4242.4    0.16       0  4489.7    0.05       0  4708.3    0.16       0
  4909.4    0.12       0  4993.8    0.07       0  5000.4    0.12       0
  5010.3    0.16       0
Bank Sta=4509.5,5045.6
Exp/Cntr=0.3,0.1

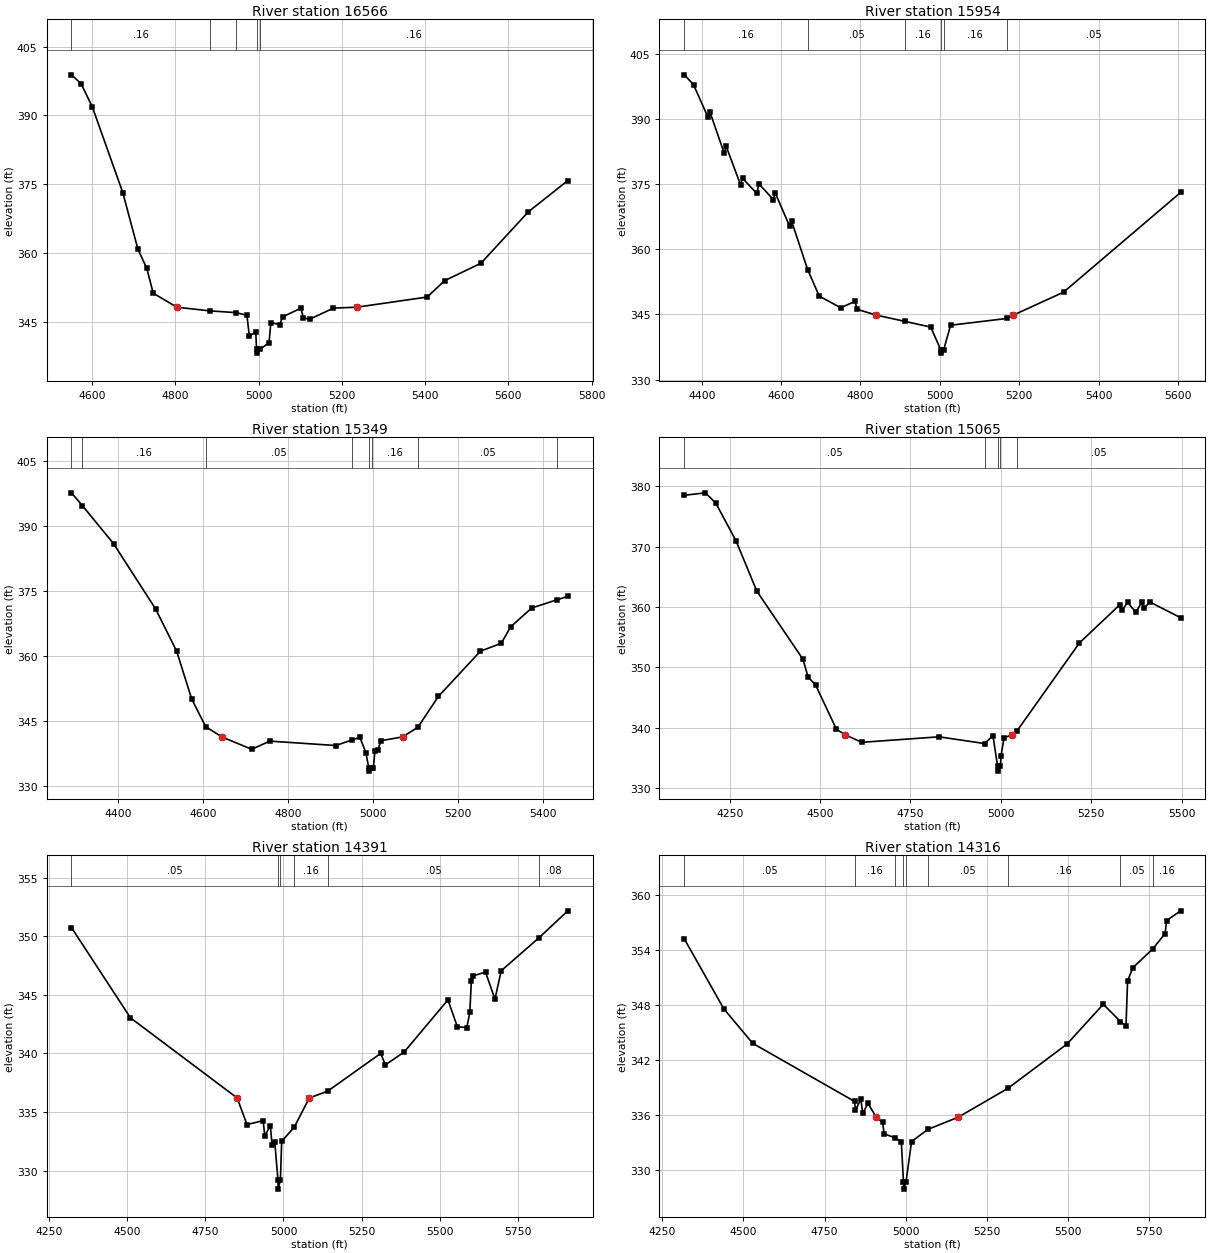
Type RM Length L Ch R = 1,16566,612,612,612
BEGIN DESCRIPTION:
LACEY BRANCH 16.0
END DESCRIPTION:
XS GIS Cut Line= 3
      2940575.01      6935374.98      2940325.00      6935775.00
      2939725.02      6936174.98
#Sta/Elev= 30
  4550.1  398.86  4573.1  396.94  4600.2  391.86  4673.4  373.15  4709.9  360.76
  4731.1  356.61  4746.5  351.20  4803.3  348.14  4882.8  347.33  4944.6  346.96
  4971.7  346.39  4977.6  341.77  4992.9  342.79  4995.0  338.91  4995.6  338.11
  5002.7  338.91  5024.8  340.38  5029.3  344.79  5050.4  344.34  5057.9  346.04
  5101.4  347.92  5107.5  345.80  5122.5  345.50  5179.6  347.93  5235.9  348.14
  5404.9  350.35  5447.0  353.93  5534.1  357.73  5648.3  368.97  5742.9  375.77
#Mann=5,-1,0
  4550.1    0.16       0  4882.8    0.05       0  4944.6    0.16       0
  4995.0    0.07       0  5002.7    0.16       0
Bank Sta=4803.3,5235.9
Exp/Cntr=0.3,0.1

Type RM Length L Ch R = 1,15954,605,605,605
BEGIN DESCRIPTION:
LACEY BRANCH 15.0
END DESCRIPTION:
XS GIS Cut Line= 3
      2940574.98      6935325.00      2939975.00      6935475.00
      2939375.00      6935675.00
#Sta/Elev= 30
  4356.0  400.20  4379.2  397.95  4415.2  390.53  4420.4  391.69  4456.5  382.16
  4461.6  383.73  4497.7  374.87  4502.9  376.37  4538.9  372.86  4544.1  375.09
  4580.2  371.47  4585.3  372.95  4621.4  365.35  4626.6  366.45  4667.0  355.31
  4696.1  349.22  4750.3  346.53  4786.3  348.01  4791.5  346.18  4840.1  344.83
  4913.4  343.37  4977.1  342.08  5002.2  336.88  5002.8  336.08  5009.9  336.88
  5027.2  342.51  5168.5  344.06  5185.0  344.83  5311.8  350.12  5606.9  373.09
#Mann=6,-1,0
  4356.0    0.16       0  4667.0    0.05       0  4913.4    0.16       0
  5002.2    0.07       0  5009.9    0.16       0  5168.5    0.05       0
Bank Sta=4840.1,5185
Exp/Cntr=0.3,0.1

Type RM Length L Ch R = 1,15349,284,284,284
BEGIN DESCRIPTION:
LACEY BRANCH 14.0
END DESCRIPTION:
XS GIS Cut Line= 3
      2940124.98      6934825.02      2939625.00      6935325.00
      2939324.97      6935675.03
#Sta/Elev= 30
  4291.1  397.71  4316.6  394.77  4390.1  385.96  4489.1  370.86  4538.6  361.10
  4573.9  350.07  4607.0  343.63  4645.2  341.27  4715.3  338.40  4757.8  340.30
  4913.3  339.28  4952.1  340.61  4969.9  341.15  4984.0  337.62  4990.7  334.16
  4991.3  333.36  4998.5  334.16  5001.5  334.16  5005.3  337.94  5011.9  338.17
  5019.6  340.40  5070.2  341.27  5106.3  343.49  5154.6  350.63  5253.4  361.08
  5302.8  362.93  5324.7  366.72  5374.1  371.07  5434.5  373.00  5459.2  373.76
#Mann=8,-1,0
  4291.1    0.05       0  4316.6    0.16       0  4607.0    0.05       0
  4952.1    0.16       0  4990.7    0.07       0  4998.5    0.16       0
  5106.3    0.05       0  5434.5    0.16       0
Bank Sta=4645.2,5070.2
Exp/Cntr=0.3,0.1

Type RM Length L Ch R = 1,15065,674,674,674
BEGIN DESCRIPTION:
Mapping XS 418c5492
END DESCRIPTION:
XS GIS Cut Line= 3
      2939927.99      6934515.93      2939396.73      6935161.78
      2939153.93      6935640.44
#Sta/Elev= 30
  4124.4  378.54  4182.8  378.95  4211.5  377.25  4267.5  370.99  4324.9  362.66
  4452.6  351.35  4466.9  348.39  4487.8  347.06  4545.1  339.75  4569.6  338.81
  4615.5  337.57  4829.2  338.48  4955.6  337.36  4978.3  338.69  4991.1  333.59
  4991.7  332.79  4998.9  333.59  5000.6  335.35  5009.1  338.34  5032.2  338.81
  5045.3  339.50  5217.6  354.06  5329.0  360.37  5334.6  359.45  5351.2  360.76
  5373.5  359.13  5390.2  360.85  5395.8  359.78  5412.4  360.84  5497.4  358.24
#Mann=5,-1,0
  4124.4    0.05       0  4955.6    0.16       0  4991.1    0.07       0
  4998.9    0.16       0  5045.3    0.05       0
Bank Sta=4569.6,5032.2
Exp/Cntr=0.3,0.1

Type RM Length L Ch R = 1,14391,75,75,75
BEGIN DESCRIPTION:
Mapping XS d7582a30
END DESCRIPTION:
XS GIS Cut Line= 3
      2939375.89      6934283.33      2939091.17      6934904.83
      2939028.67      6935807.66
#Sta/Elev= 30
  4321.5  350.73  4510.3  343.04  4851.8  336.21  4883.3  333.94  4934.9  334.28
  4940.4  332.98  4957.9  333.86  4963.4  332.23  4972.3  332.43  4982.4  329.24
  4983.1  328.44  4990.3  329.24  4994.3  332.52  5034.6  333.72  5082.6  336.21
  5141.5  336.79  5311.4  340.01  5326.0  339.03  5386.2  340.12  5526.5  344.57
  5556.6  342.28  5586.7  342.21  5596.5  343.50  5601.5  346.20  5606.7  346.61
  5646.8  346.94  5676.9  344.63  5696.9  347.05  5818.2  349.87  5910.1  352.16
#Mann=6,-1,0
  4321.5    0.05       0  4982.4    0.04       0  4990.3    0.05       0
  5034.6    0.16       0  5141.5    0.05       0  5818.2    0.08       0
Bank Sta=4851.8,5082.6
Exp/Cntr=0.3,0.1

Type RM Length L Ch R = 1,14316,661,661,661
BEGIN DESCRIPTION:
LACEY BRANCH 13.0
END DESCRIPTION:
XS GIS Cut Line= 4
      2939327.29      6934255.52      2939050.00      6934800.00
      2939000.00      6934950.00      2938872.42      6935699.99
#Sta/Elev= 30
  4317.8  355.19  4439.5  347.58  4528.5  343.82  4842.6  337.49  4845.5  336.56
  4862.1  337.73  4867.7  336.20  4884.3  337.27  4909.4  335.77  4928.8  335.23
  4934.1  333.94  4966.0  333.56  4986.8  333.10  4993.4  328.74  4994.0  327.94
  5001.3  328.74  5018.4  333.12  5068.3  334.44  5162.2  335.77  5315.7  338.92
  5497.8  343.74  5609.3  348.07  5662.3  346.19  5679.3  345.65  5684.3  350.61
  5700.6  352.05  5761.2  354.07  5799.8  355.76  5804.8  357.18  5847.7  358.24
#Mann=9,-1,0
  4317.8    0.05       0  4842.6    0.16       0  4966.0    0.08       0
  4993.4    0.07       0  5001.3    0.08       0  5068.3    0.05       0
  5315.7    0.16       0  5662.3    0.05       0  5761.2    0.16       0
Bank Sta=4909.4,5162.2
Exp/Cntr=0.3,0.1

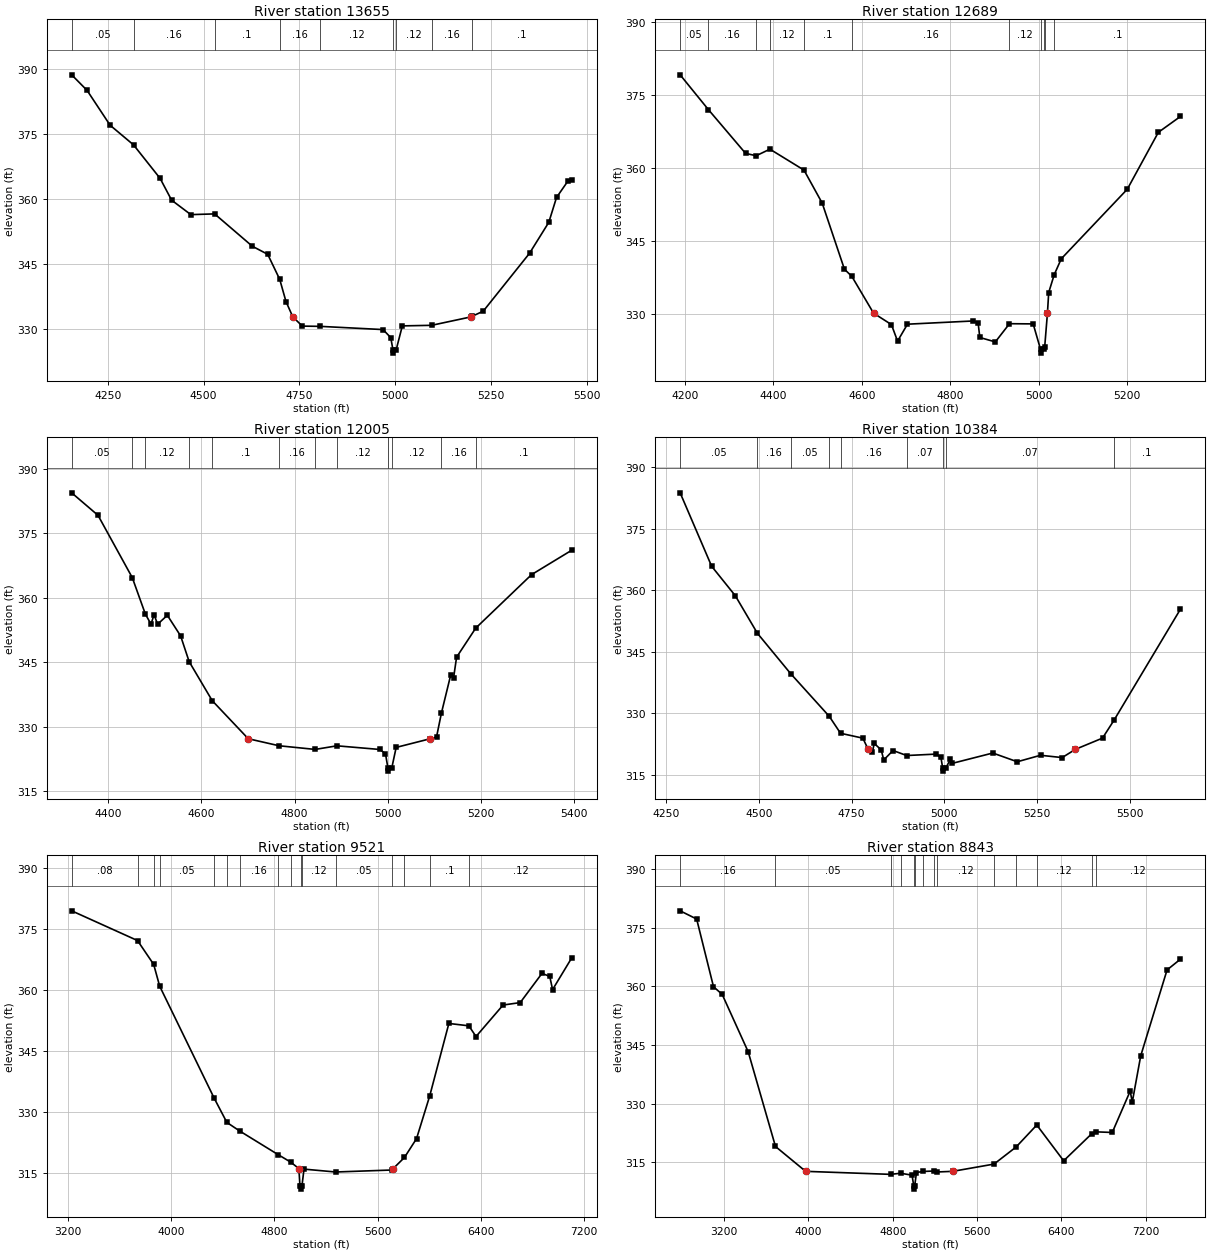
Type RM Length L Ch R = 1,13655,966,966,966
BEGIN DESCRIPTION:
LACEY BRANCH 11.0
END DESCRIPTION:
XS GIS Cut Line= 3
      2938625.00      6934174.99      2938575.00      6934975.00
      2938625.00      6935475.04
#Sta/Elev= 30
  4156.2  388.73  4196.3  385.14  4256.4  377.09  4317.5  372.55  4386.7  364.82
  4416.7  359.79  4466.8  356.45  4528.8  356.62  4627.1  349.15  4667.2  347.29
  4698.6  341.49  4714.8  336.39  4732.6  332.85  4757.4  330.71  4803.9  330.65
  4967.8  329.91  4987.9  328.06  4993.7  325.27  4994.5  324.47  5002.2  325.27
  5018.1  330.76  5094.4  330.89  5197.8  332.85  5200.5  332.99  5229.1  334.16
  5349.7  347.52  5400.0  354.68  5420.1  360.41  5450.2  364.25  5460.3  364.40
#Mann=9,-1,0
  4156.2    0.05       0  4317.5    0.16       0  4528.8     0.1       0
  4698.6    0.16       0  4803.9    0.12       0  4993.7    0.07       0
  5002.2    0.12       0  5094.4    0.16       0  5200.5     0.1       0
Bank Sta=4732.6,5197.8
Exp/Cntr=0.3,0.1

Type RM Length L Ch R = 1,12689,684,684,684
BEGIN DESCRIPTION:
LACEY BRANCH 10.0
END DESCRIPTION:
XS GIS Cut Line= 3
      2938475.00      6934275.00      2938175.00      6934875.00
      2937875.00      6935225.00
#Sta/Elev= 30
  4189.0  379.18  4252.8  372.03  4337.1  363.00  4361.0  362.52  4392.1  363.87
  4469.2  359.56  4510.4  352.76  4560.7  339.15  4577.4  337.68  4626.6  330.10
  4667.0  327.75  4680.9  324.34  4703.3  327.83  4851.4  328.49  4863.1  328.16
  4867.0  325.09  4902.1  324.18  4934.1  327.93  4987.7  327.89  5004.3  322.67
  5005.0  321.87  5012.8  322.67  5013.8  323.18  5020.0  330.10  5022.8  334.34
  5035.3  338.02  5051.3  341.30  5200.6  355.62  5270.9  367.34  5320.8  370.60
#Mann=11,-1,0
  4189.0    0.05       0  4252.8    0.16       0  4361.0     0.1       0
  4392.1    0.12       0  4469.2     0.1       0  4577.4    0.16       0
  4934.1    0.12       0  5004.3    0.07       0  5012.8    0.12       0
  5013.8    0.16       0  5035.3     0.1       0
Bank Sta=4626.6,5020
Exp/Cntr=0.3,0.1

Type RM Length L Ch R = 1,12005,1621,1621,1621
BEGIN DESCRIPTION:
LACEY BRANCH 9.0
END DESCRIPTION:
XS GIS Cut Line= 3
      2938475.03      6934224.97      2938025.00      6934625.00
      2937625.02      6934874.99
#Sta/Elev= 30
  4321.4  384.47  4377.9  379.23  4451.5  364.70  4479.5  356.22  4491.6  353.86
  4498.3  356.07  4505.8  353.83  4526.7  355.93  4555.2  351.13  4573.5  345.13
  4623.1  336.02  4700.4  327.15  4766.7  325.51  4844.0  324.66  4890.8  325.50
  4982.5  324.65  4994.9  323.69  5000.1  320.40  5000.8  319.60  5008.6  320.40
  5017.9  325.13  5091.1  327.15  5104.5  327.53  5115.0  333.12  5135.2  342.11
  5141.1  341.33  5147.6  346.16  5188.7  352.94  5308.5  365.40  5395.2  371.12
#Mann=12,-1,0
  4321.4    0.05       0  4451.5    0.16       0  4479.5    0.12       0
  4573.5    0.16       0  4623.1     0.1       0  4766.7    0.16       0
  4844.0     0.1       0  4890.8    0.12       0  5000.1    0.07       0
  5008.6    0.12       0  5115.0    0.16       0  5188.7     0.1       0
Bank Sta=4700.4,5091.1
Exp/Cntr=0.3,0.1

Type RM Length L Ch R = 1,10384,863,863,863
BEGIN DESCRIPTION:
LACEY BRANCH 8.0
END DESCRIPTION:
XS GIS Cut Line= 3
      2938474.96      6934174.99      2937775.00      6933925.00
      2937525.01      6934474.98
#Sta/Elev= 30
  4288.4  383.71  4373.3  365.82  4437.0  358.65  4496.5  349.50  4585.8  339.70
  4690.0  329.28  4720.4  325.15  4780.5  323.96  4794.8  321.24  4806.0  320.60
  4811.3  322.66  4829.9  321.11  4836.8  318.65  4861.8  320.95  4898.6  319.73
  4978.6  320.08  4990.8  319.25  4995.5  316.73  4996.3  315.93  5004.1  316.73
  5016.3  318.77  5021.6  317.83  5130.5  320.34  5196.4  318.21  5259.0  319.79
  5317.3  319.23  5353.1  321.24  5426.0  323.97  5457.2  328.36  5635.8  355.36
#Mann=9,-1,0
  4288.4    0.05       0  4496.5    0.16       0  4585.8    0.05       0
  4690.0    0.07       0  4720.4    0.16       0  4898.6    0.07       0
  4995.5    0.07       0  5004.1    0.07       0  5457.2     0.1       0
Bank Sta=4794.8,5353.1
Exp/Cntr=0.3,0.1

Type RM Length L Ch R = 1,9521,678,678,678
BEGIN DESCRIPTION:
LACEY BRANCH 7.0
END DESCRIPTION:
XS GIS Cut Line= 3
      2939217.89      6933336.26      2937445.66      6933305.70
      2937277.80      6935406.61
#Sta/Elev= 30
  3227.5  379.57  3738.2  372.26  3863.5  366.40  3909.8  361.06  4332.2  333.54
  4431.1  327.55  4530.1  325.45  4827.1  319.66  4926.1  317.79  4989.8  316.20
  4997.8  311.98  5005.0  311.95  5005.8  311.15  5013.6  311.95  5029.4  316.07
  5274.5  315.36  5710.5  315.85  5721.2  316.20  5808.5  318.93  5902.2  323.56
  6004.5  334.07  6153.0  351.88  6307.9  351.30  6363.6  348.67  6573.5  356.41
  6706.5  357.01  6875.3  364.19  6935.4  363.45  6957.5  360.21  7107.6  368.09
#Mann=16,-1,0
  3227.5    0.08       0  3738.2    0.05       0  3863.5    0.08       0
  3909.8    0.05       0  4332.2    0.08       0  4431.1    0.05       0
  4530.1    0.16       0  4827.1    0.08       0  4926.1    0.12       0
  5005.0    0.07       0  5013.6    0.12       0  5274.5    0.05       0
  5710.5     0.1       0  5808.5    0.16       0  6004.5     0.1       0
  6307.9    0.12       0
Bank Sta=4989.8,5721.2
Exp/Cntr=0.3,0.1

Type RM Length L Ch R = 1,8843,2773,2773,2773
BEGIN DESCRIPTION:
Mapping XS 369e3fa5
END DESCRIPTION:
XS GIS Cut Line= 4
      2939022.58      6933127.92      2937408.01      6932724.28
      2936900.20      6933127.92      2936991.29      6935561.37
#Sta/Elev= 30
  2782.2  379.33  2939.0  377.23  3098.8  359.91  3181.2  357.95  3428.6  343.22
  3687.2  319.02  3973.4  312.66  4779.4  311.89  4874.1  312.17  4983.2  311.69
  4999.7  308.91  5000.5  308.11  5008.3  308.91  5025.2  312.36  5085.4  312.63
  5186.9  312.74  5221.9  312.50  5368.8  312.66  5761.4  314.52  5971.2  318.90
  6167.2  324.52  6422.3  315.36  6690.5  322.33  6728.3  322.77  6883.5  322.61
  7053.6  333.19  7073.6  330.40  7153.7  342.23  7403.8  364.21  7530.3  366.95
#Mann=14,-1,0
  2782.2    0.16       0  3687.2    0.05       0  4779.4    0.12       0
  4874.1    0.05       0  4999.7    0.03       0  5008.3    0.05       0
  5085.4    0.08       0  5186.9    0.16       0  5221.9    0.12       0
  5761.4    0.05       0  5971.2    0.16       0  6167.2    0.12       0
  6690.5     0.1       0  6728.3    0.12       0
Bank Sta=3973.4,5368.8
Exp/Cntr=0.3,0.1

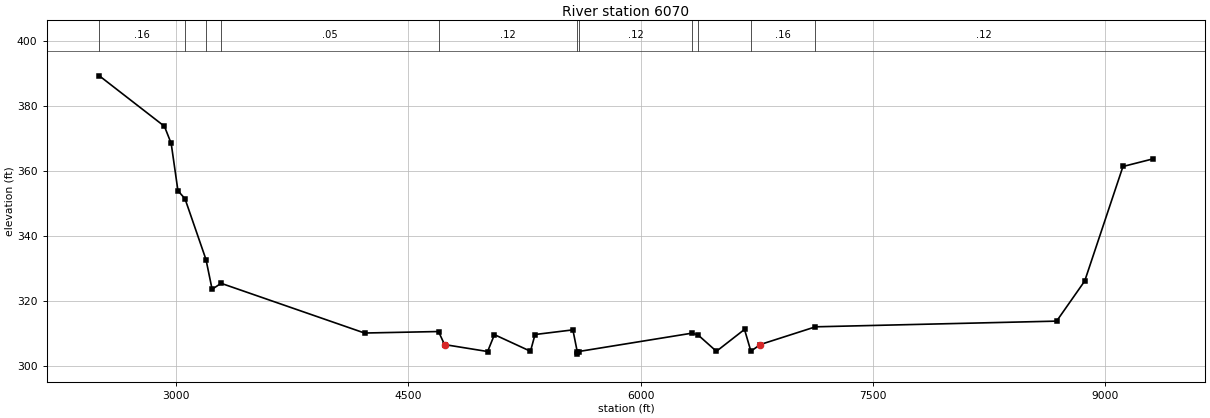
Type RM Length L Ch R = 1,6070,0,0,0
BEGIN DESCRIPTION:
LACEY BRANCH 6.0
END DESCRIPTION:
XS GIS Cut Line= 4
      2939250.03      6933000.02      2937600.00      6931750.00
      2936327.29      6932268.55      2936743.84      6935600.96
#Sta/Elev= 30
  2504.7  389.28  2925.0  373.76  2968.7  368.49  3012.3  353.94  3057.9  351.48
  3193.5  332.77  3232.9  323.64  3291.1  325.47  4217.2  310.18  4695.0  310.64
  4733.9  306.63  5012.1  304.49  5056.2  309.68  5288.9  304.57  5318.3  309.72
  5562.8  311.15  5590.8  304.49  5591.6  303.69  5599.6  304.49  6333.6  310.15
  6373.4  309.49  6489.7  304.56  6671.1  311.29  6712.3  304.57  6772.2  306.63
  7129.5  312.09  8686.6  313.84  8868.0  326.17  9115.1  361.40  9307.4  363.72
#Mann=11,-1,0
  2504.7    0.16       0  3057.9    0.05       0  3193.5    0.16       0
  3291.1    0.05       0  4695.0    0.12       0  5590.8    0.07       0
  5599.6    0.12       0  6333.6    0.05       0  6373.4    0.12       0
  6712.3    0.16       0  7129.5    0.12       0
Bank Sta=4733.9,6772.2
Exp/Cntr=0.3,0.1

Chan Stop Cuts=-1