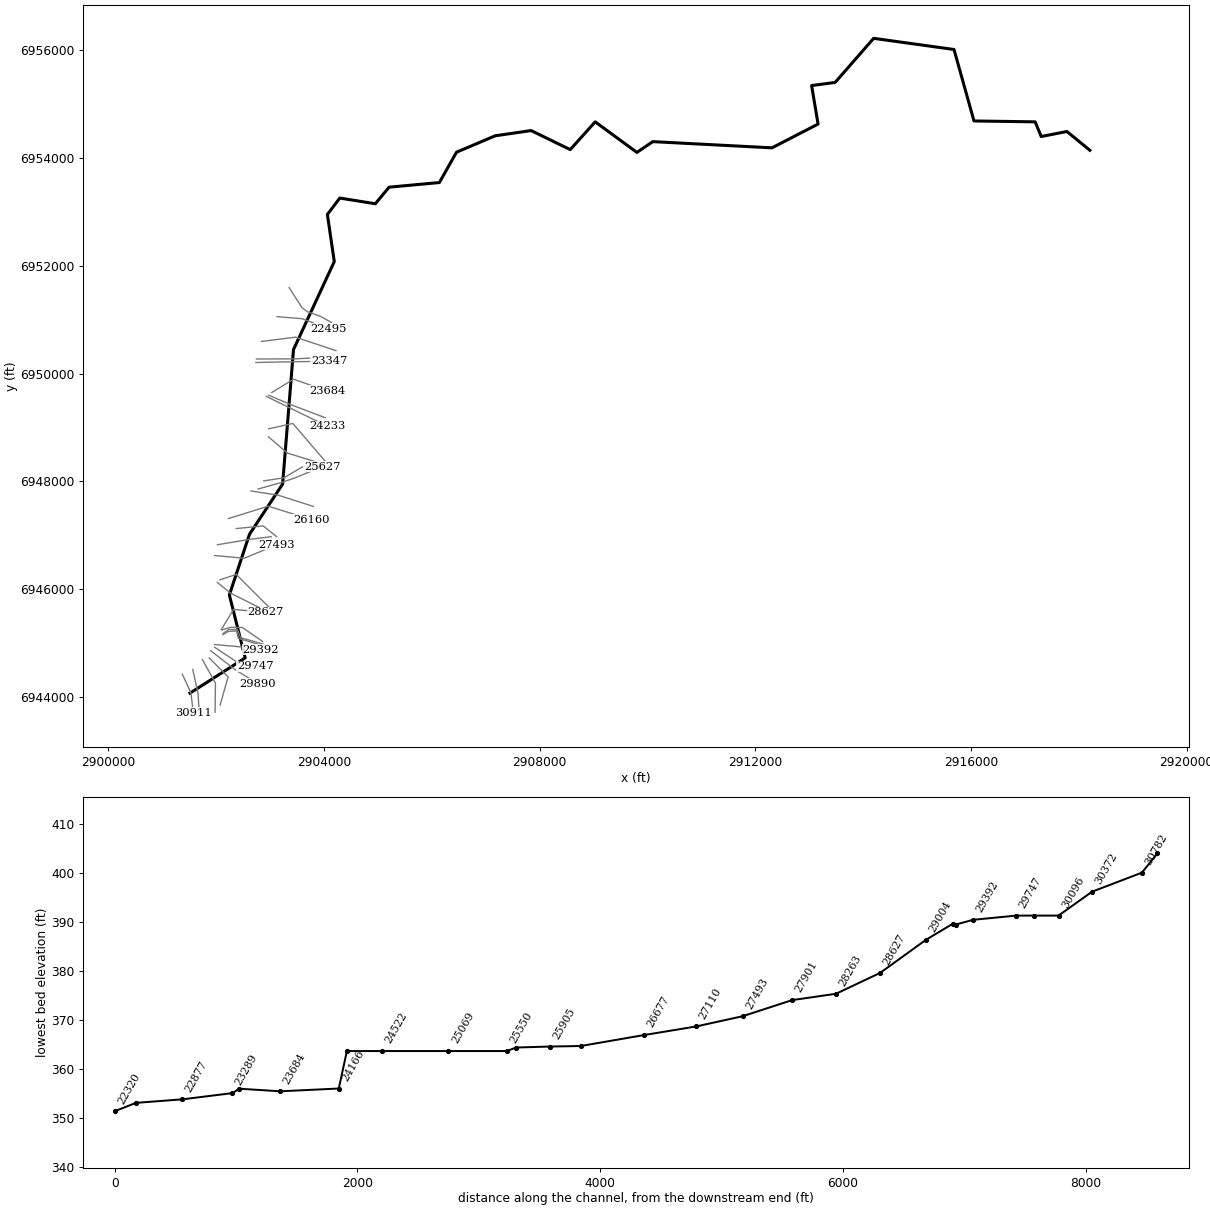
--- LEWELLYN CREEK.prj (project) ---

Proj Title=LEWELLYN CREEK Base Level Engineering
Current Plan=p01
Default Exp/Contr=0.3,0.1
English Units
Geom File=g01
Flow File=f01
Plan File=p01
BEGIN DESCRIPTION:
LEWELLYN CREEK
END DESCRIPTION:

--- LEWELLYN CREEK.p01 (plan) ---

Plan Title=Multiple Run
Short Identifier=Multiple
Geom File=g01
Flow File=f01
Subcritical Flow
K Sum by GR= 0
Std Step Tol= 0.01
Critical Tol= 0.01
Num of Std Step Trials= 20
Max Error Tol= 0.3
Flow Tol Ratio= 0.001
Split Flow NTrial= 30
Split Flow Tol= 0.02
Split Flow Ratio= 0.02
Log Output Level= 0
Friction Slope Method= 1
Unsteady Friction Slope Method= 2
Unsteady Bridges Friction Slope Method= 1
Parabolic Critical Depth
Global Vel Dist=  1 , 1 , 1
Global Log Level= 0
CheckData=True
Encroach Param= -1, 0, 0, 0
BEGIN DESCRIPTION:
Multiple Run
END DESCRIPTION:

--- LEWELLYN CREEK.f01 (steady flow) ---

Flow Title=Multiple
Program Version=5.07
Number of Profiles= 7
Profile Names=10-year,25-year,50-year,1pct_min,100-year,1pct_plu,500-year
River Rch & RM=LEWELLYN CREEK,Reach-1         ,30911
     381     505     604     361     720    1437    1023
River Rch & RM=LEWELLYN CREEK,Reach-1         ,28263
     732    1004    1231     750    1497    2987    2220
River Rch & RM=LEWELLYN CREEK,Reach-1         ,23347
     765    1049    1285     783    1562    3116    2310
River Rch & RM=LEWELLYN CREEK,Reach-1         ,20678
    3197    4683    5998    3802    7585   15134   12165
River Rch & RM=LEWELLYN CREEK,Reach-1         ,14259
    3203    4674    5971    3773    7528   15021   12003
River Rch & RM=LEWELLYN CREEK,Reach-1         ,9312
    3349    4890    6249    3950    7881   15725   12572
River Rch & RM=LEWELLYN CREEK,Reach-1         ,7729
    3374    4913    6265    3951    7883   15728   12515
River Rch & RM=LEWELLYN CREEK,Reach-1         ,1511
    3386    4926    6277    3956    7893   15748   12513
Boundary for River Rch & Prof#=LEWELLYN CREEK,Reach-1         , 1
Up Type= 0
Dn Type= 3
Dn Slope=0.0011
Boundary for River Rch & Prof#=LEWELLYN CREEK,Reach-1         , 2
Up Type= 0
Dn Type= 3
Dn Slope=0.0011
Boundary for River Rch & Prof#=LEWELLYN CREEK,Reach-1         , 3
Up Type= 0
Dn Type= 3
Dn Slope=0.0011
Boundary for River Rch & Prof#=LEWELLYN CREEK,Reach-1         , 4
Up Type= 0
Dn Type= 3
Dn Slope=0.0011
Boundary for River Rch & Prof#=LEWELLYN CREEK,Reach-1         , 5
Up Type= 0
Dn Type= 3
Dn Slope=0.0011
Boundary for River Rch & Prof#=LEWELLYN CREEK,Reach-1         , 6
Up Type= 0
Dn Type= 3
Dn Slope=0.0011
Boundary for River Rch & Prof#=LEWELLYN CREEK,Reach-1         , 7
Up Type= 0
Dn Type= 3
Dn Slope=0.0011
DSS Import GetInterval= 0
DSS Import GetPeak= 0
DSS Import FillOption= 0

--- LEWELLYN CREEK.g01 (geometry) ---

Geom Title=Existing Conditions

River Reach=LEWELLYN CREEK,Reach-1
Reach XY= 30
      2901517.83      6944072.88      2902541.48      6944727.51
      2902247.78      6945894.60      2902621.12      6947019.41
      2903235.49      6947950.76      2903437.16      6950444.89
      2904193.45      6952076.42      2904065.59      6952950.71
      2904296.04      6953254.43      2904954.89      6953148.96
      2905210.10      6953456.26      2906142.39      6953542.19
      2906460.10      6954104.69      2907178.85      6954409.38
      2907843.65      6954505.99      2908569.23      6954153.01
      2909031.95      6954668.11      2909805.30      6954101.22
      2910100.49      6954300.94      2912310.34      6954185.72
      2913165.19      6954627.00      2913045.59      6955340.71
      2913482.01      6955398.75      2914196.05      6956216.50
      2915686.02      6956009.74      2916056.66      6954684.13
      2917190.94      6954668.04      2917303.05      6954395.71
      2917779.92      6954488.89      2918205.59      6954140.71

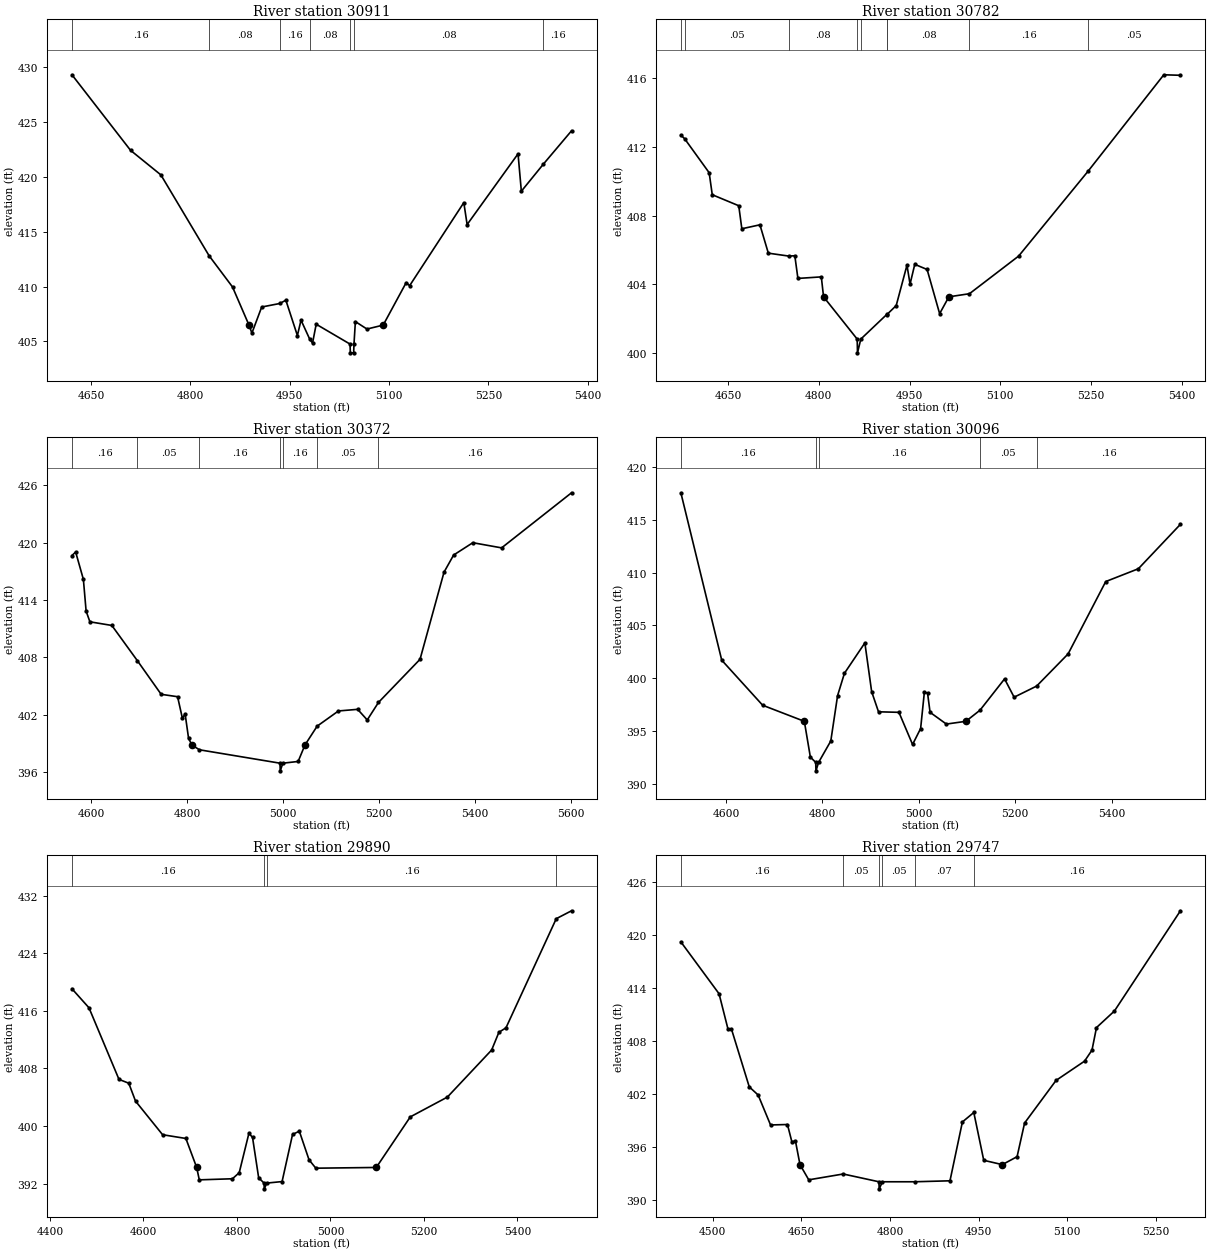
Type RM Length L Ch R = 1,30911,129,129,129
BEGIN DESCRIPTION:
LEWELLYN CREEK 42.0
END DESCRIPTION:
XS GIS Cut Line= 3
      2901374.99      6944425.01      2901534.40      6944081.16
      2901579.53      6943708.28
#Sta/Elev= 30
  4621.0  429.32  4709.5  422.43  4755.3  420.19  4828.1  412.82  4863.5  409.97
  4888.4  406.49  4892.8  405.76  4907.6  408.14  4934.9  408.46  4944.1  408.76
  4961.5  405.54  4967.0  406.94  4980.1  405.21  4984.4  404.85  4989.9  406.57
  5041.0  404.76  5041.5  403.96  5046.5  403.96  5047.0  404.76  5049.1  406.81
  5066.6  406.13  5091.1  406.49  5125.9  410.37  5131.0  410.08  5212.9  417.66
  5217.9  415.66  5294.8  422.11  5299.8  418.70  5333.2  421.18  5375.6  424.21
#Mann=7,-1,0
  4621.0    0.16       0  4828.1    0.08       0  4934.9    0.16       0
  4980.1    0.08       0  5041.0    0.07       0  5047.0    0.08       0
  5333.2    0.16       0
Bank Sta=4888.4,5091.1
Exp/Cntr=0.3,0.1

Type RM Length L Ch R = 1,30782,410,410,410
BEGIN DESCRIPTION:
Mapping XS e4f1c670
END DESCRIPTION:
XS GIS Cut Line= 3
      2901569.30      6944512.67      2901665.67      6944073.82
      2901691.58      6943698.12
#Sta/Elev= 30
  4571.9  412.69  4578.1  412.48  4618.7  410.50  4623.8  409.22  4667.6  408.58
  4672.7  407.24  4702.6  407.47  4716.5  405.82  4750.4  405.65  4760.3  405.67
  4765.4  404.35  4804.1  404.44  4807.8  403.28  4863.4  400.82  4863.9  400.02
  4869.4  400.82  4912.2  402.25  4913.5  402.28  4927.9  402.77  4945.7  405.12
  4950.8  404.02  4958.6  405.17  4979.0  404.87  4999.7  402.30  5015.0  403.28
  5049.0  403.46  5130.3  405.65  5244.9  410.58  5370.3  416.20  5397.8  416.17
#Mann=9,-1,0
  4571.9    0.16       0  4578.1    0.05       0  4750.4    0.08       0
  4863.4    0.07       0  4869.4    0.08       0  4912.2    0.16       0
  4913.5    0.08       0  5049.0    0.16       0  5244.9    0.05       0
Bank Sta=4807.8,5015
Exp/Cntr=0.3,0.1

Type RM Length L Ch R = 1,30372,276,276,276
BEGIN DESCRIPTION:
Mapping XS ccc00f5b
END DESCRIPTION:
XS GIS Cut Line= 3
      2901746.85      6944697.77      2901989.89      6944256.84
      2901982.95      6943719.36
#Sta/Elev= 30
  4560.4  418.65  4568.1  419.02  4584.2  416.16  4589.9  412.84  4597.8  411.72
  4643.5  411.34  4696.8  407.65  4746.3  404.14  4780.5  403.89  4790.5  401.64
  4796.2  402.09  4803.4  399.54  4810.3  398.84  4826.1  398.34  4993.9  396.94
  4994.4  396.14  4999.9  396.94  5031.7  397.12  5045.9  398.84  5071.3  400.81
  5115.7  402.40  5155.7  402.57  5175.7  401.46  5199.1  403.29  5285.7  407.80
  5335.7  416.91  5355.7  418.70  5395.7  419.99  5455.7  419.45  5601.4  425.21
#Mann=7,-1,0
  4560.4    0.16       0  4696.8    0.05       0  4826.1    0.16       0
  4993.9    0.07       0  4999.9    0.16       0  5071.3    0.05       0
  5199.1    0.16       0
Bank Sta=4810.3,5045.9
Exp/Cntr=0.3,0.1

Type RM Length L Ch R = 1,30096,206,206,206
BEGIN DESCRIPTION:
LEWELLYN CREEK 41.0
END DESCRIPTION:
XS GIS Cut Line= 3
      2901875.03      6944724.97      2902225.00      6944375.00
      2902076.69      6943854.03
#Sta/Elev= 30
  4506.3  417.54  4591.1  401.72  4676.0  397.46  4762.5  395.94  4775.0  392.56
  4786.1  392.06  4786.6  391.26  4792.1  392.06  4817.4  394.08  4831.5  398.37
  4845.7  400.48  4888.1  403.35  4902.2  398.74  4916.4  396.84  4958.8  396.79
  4987.1  393.75  5003.8  395.26  5011.6  398.71  5018.2  398.60  5023.4  396.79
  5057.2  395.68  5097.7  395.94  5127.0  396.99  5178.0  399.95  5197.8  398.22
  5244.5  399.27  5309.8  402.31  5387.9  409.15  5455.6  410.36  5542.9  414.56
#Mann=5,-1,0
  4506.3    0.16       0  4786.1    0.07       0  4792.1    0.16       0
  5127.0    0.05       0  5244.5    0.16       0
Bank Sta=4762.5,5097.7
Exp/Cntr=0.3,0.1

Type RM Length L Ch R = 1,29890,143,143,143
BEGIN DESCRIPTION:
Mapping XS e96de6cb
END DESCRIPTION:
XS GIS Cut Line= 3
      2901899.62      6944861.00      2902361.42      6944503.37
      2902774.50      6944249.96
#Sta/Elev= 30
  4447.0  419.06  4483.4  416.42  4547.6  406.47  4568.5  405.94  4583.0  403.45
  4640.9  398.78  4690.7  398.26  4713.8  394.23  4719.4  392.51  4790.3  392.66
  4804.8  393.50  4825.6  398.99  4833.3  398.40  4846.4  392.80  4857.9  392.06
  4858.4  391.26  4863.9  392.06  4896.5  392.27  4918.9  398.82  4933.4  399.27
  4954.2  395.29  4968.7  394.13  5098.0  394.23  5170.8  401.26  5250.1  404.01
  5344.8  410.55  5360.3  413.01  5375.5  413.64  5483.0  428.80  5515.7  429.90
#Mann=4,-1,0
  4447.0    0.16       0  4857.9    0.07       0  4863.9    0.16       0
  5483.0    0.05       0
Bank Sta=4713.8,5098
Exp/Cntr=0.3,0.1

Type RM Length L Ch R = 1,29747,355,355,355
BEGIN DESCRIPTION:
LEWELLYN CREEK 40.0
END DESCRIPTION:
XS GIS Cut Line= 3
      2901975.01      6944924.99      2902425.00      6944625.00
      2902725.04      6944574.99
#Sta/Elev= 30
  4446.4  419.21  4511.0  413.34  4526.0  409.37  4532.0  409.34  4562.1  402.80
  4577.1  401.88  4598.1  398.49  4626.7  398.54  4634.2  396.57  4640.2  396.68
  4647.9  394.00  4662.7  392.28  4721.0  392.94  4781.4  392.06  4781.9  391.26
  4787.4  392.06  4841.9  392.06  4901.6  392.17  4922.6  398.83  4941.9  399.90
  4958.7  394.49  4990.1  394.00  5015.1  394.90  5027.8  398.71  5081.0  403.53
  5129.2  405.71  5141.8  406.96  5149.4  409.51  5179.8  411.39  5291.4  422.73
#Mann=6,-1,0
  4446.4    0.16       0  4721.0    0.05       0  4781.4    0.07       0
  4787.4    0.05       0  4841.9    0.07       0  4941.9    0.16       0
Bank Sta=4647.9,4990.1
Exp/Cntr=0.3,0.1

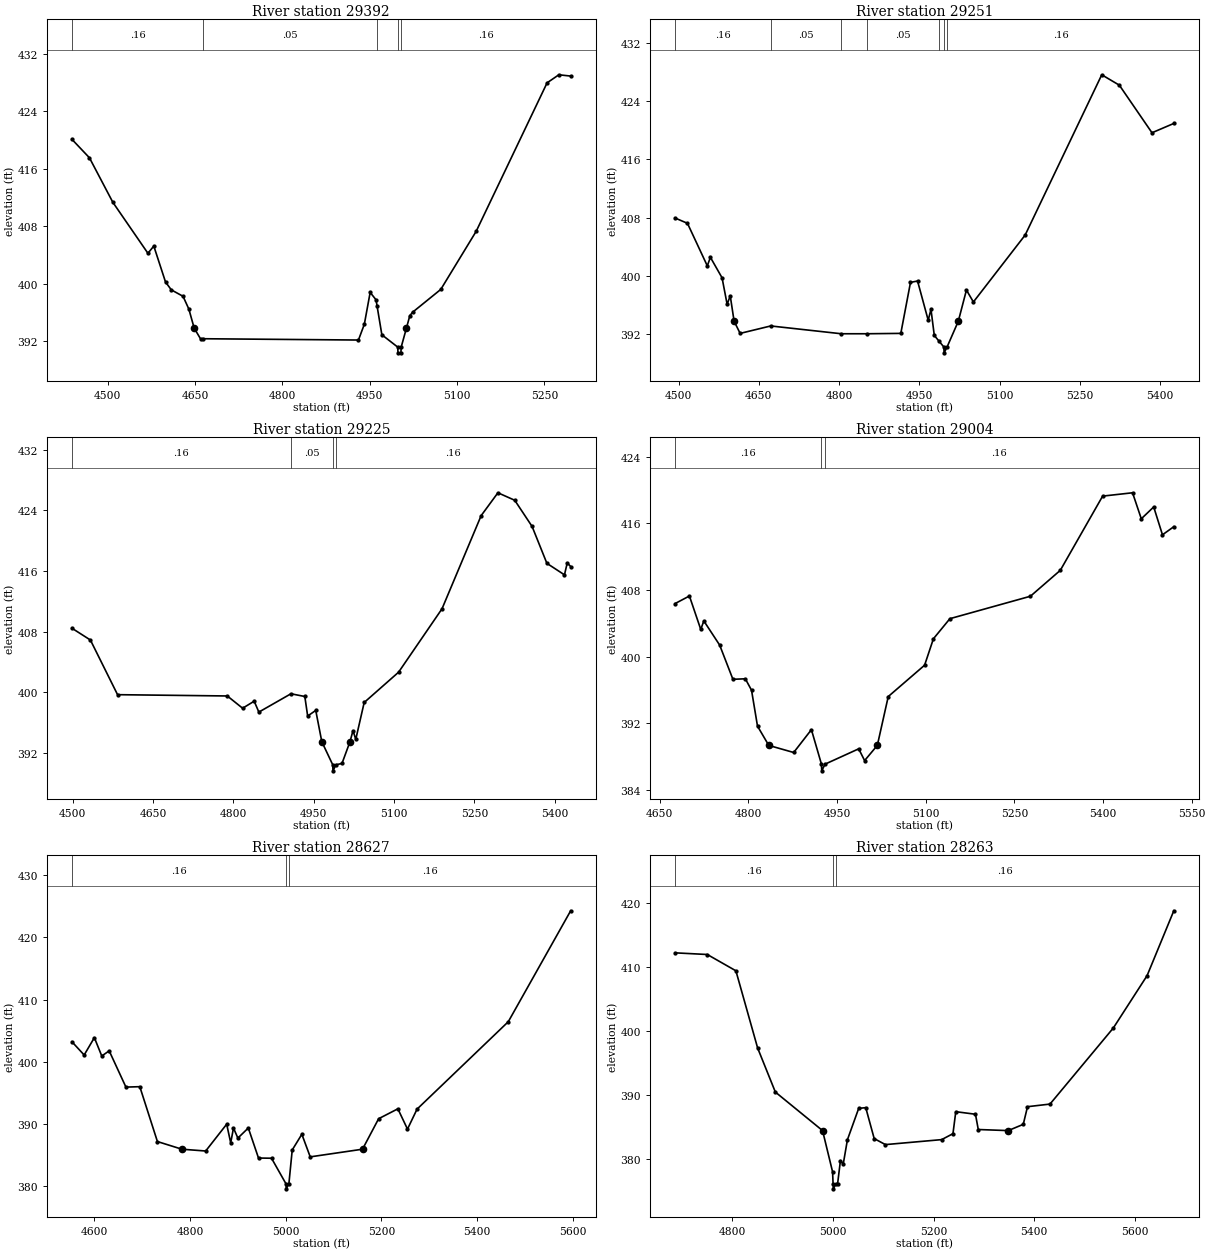
Type RM Length L Ch R = 1,29392,141,141,141
BEGIN DESCRIPTION:
LEWELLYN CREEK 39.0
END DESCRIPTION:
XS GIS Cut Line= 3
      2901974.99      6944975.00      2902525.00      6944925.00
      2902824.98      6944875.00
#Sta/Elev= 30
  4438.8  420.08  4468.9  417.51  4509.1  411.32  4569.3  404.24  4579.4  405.24
  4599.5  400.25  4609.5  399.15  4629.6  398.26  4639.6  396.48  4648.7  393.84
  4659.7  392.34  4664.0  392.36  4930.8  392.18  4940.9  394.37  4950.9  398.80
  4961.0  397.77  4962.9  396.85  4971.0  392.91  4998.2  391.20  4998.7  390.40
  5003.7  390.40  5004.2  391.20  5013.2  393.84  5019.0  395.57  5024.0  396.06
  5072.2  399.22  5133.0  407.30  5254.7  427.93  5274.9  429.05  5295.2  428.87
#Mann=5,-1,0
  4438.8    0.16       0  4664.0    0.05       0  4962.9    0.16       0
  4998.2    0.07       0  5004.2    0.16       0
Bank Sta=4648.7,5013.2
Exp/Cntr=0.3,0.1

Type RM Length L Ch R = 1,29251,26,26,26
BEGIN DESCRIPTION:
Mapping XS 6fa999f6
END DESCRIPTION:
XS GIS Cut Line= 5
      2902129.22      6945158.76      2902229.04      6945217.34
      2902383.12      6945226.02      2902413.50      6945089.30
      2902914.03      6944939.79
#Sta/Elev= 30
  4493.3  407.95  4516.5  407.22  4553.6  401.38  4559.4  402.55  4581.2  399.74
  4590.7  396.10  4596.5  397.27  4603.7  393.78  4615.0  392.11  4672.2  393.13
  4804.1  392.06  4851.7  392.06  4915.4  392.11  4933.5  399.11  4946.7  399.30
  4966.6  393.92  4971.8  395.40  4978.0  391.83  4987.2  391.01  4995.9  390.24
  4996.4  389.44  5001.9  390.24  5022.9  393.78  5038.1  398.06  5051.1  396.42
  5147.9  405.61  5291.1  427.61  5324.0  426.18  5385.0  419.65  5425.8  420.93
#Mann=7,-1,0
  4493.3    0.16       0  4672.2    0.05       0  4804.1    0.16       0
  4851.7    0.05       0  4987.2    0.16       0  4995.9    0.07       0
  5001.9    0.16       0
Bank Sta=4603.7,5022.9
Exp/Cntr=0.3,0.1

Type RM Length L Ch R = 1,29225,221,221,221
BEGIN DESCRIPTION:
Mapping XS 609ce864
END DESCRIPTION:
XS GIS Cut Line= 6
      2902131.41      6945180.47      2902237.72      6945254.23
      2902398.31      6945252.06      2902454.73      6945100.16
      2902680.43      6945039.39      2902914.85      6944967.76
#Sta/Elev= 30
  4498.8  408.44  4533.3  406.88  4584.0  399.66  4788.8  399.49  4817.4  397.87
  4839.0  398.80  4847.7  397.36  4907.6  399.78  4933.5  399.42  4938.8  396.84
  4953.9  397.58  4965.2  393.45  4985.6  390.40  4986.1  389.60  4991.6  390.40
  5002.9  390.58  5017.8  393.45  5023.4  394.91  5028.6  393.76  5044.3  398.63
  5108.5  402.63  5189.6  411.01  5262.6  423.31  5293.9  426.33  5325.3  425.34
  5357.7  421.88  5385.3  417.01  5418.1  415.49  5423.3  417.06  5429.7  416.59
#Mann=4,-1,0
  4498.8    0.16       0  4907.6    0.05       0  4985.6    0.07       0
  4991.6    0.16       0
Bank Sta=4965.2,5017.8
Exp/Cntr=0.3,0.1

Type RM Length L Ch R = 1,29004,377,377,377
BEGIN DESCRIPTION:
Mapping XS 0ced6bad
END DESCRIPTION:
XS GIS Cut Line= 4
      2902111.87      6945245.56      2902259.42      6945293.30
      2902489.45      6945291.13      2902866.03      6945029.25
#Sta/Elev= 30
  4676.0  406.38  4700.3  407.29  4719.5  403.28  4724.7  404.30  4751.5  401.40
  4773.9  397.30  4794.9  397.36  4805.4  395.99  4815.5  391.68  4834.6  389.37
  4876.7  388.52  4906.7  391.26  4923.7  387.12  4924.2  386.32  4929.7  387.12
  4986.7  388.96  4996.7  387.55  5018.2  389.37  5036.7  395.23  5098.2  398.99
  5113.1  402.16  5141.0  404.57  5277.2  407.26  5327.8  410.37  5399.4  419.27
  5450.0  419.67  5464.8  416.55  5485.8  417.97  5500.6  414.63  5519.8  415.60
#Mann=3,-1,0
  4676.0    0.16       0  4923.7    0.07       0  4929.7    0.16       0
Bank Sta=4834.6,5018.2
Exp/Cntr=0.3,0.1

Type RM Length L Ch R = 1,28627,364,364,364
BEGIN DESCRIPTION:
LEWELLYN CREEK 37.0
END DESCRIPTION:
XS GIS Cut Line= 3
      2902096.54      6945248.43      2902325.00      6945625.00
      2902924.97      6945575.00
#Sta/Elev= 30
  4553.2  403.21  4578.8  401.08  4600.1  403.87  4615.6  400.92  4631.1  401.75
  4666.1  395.92  4695.1  395.99  4731.9  387.17  4783.1  385.94  4832.8  385.65
  4876.7  389.96  4885.1  386.96  4890.9  389.34  4900.1  387.73  4921.9  389.35
  4943.2  384.52  4970.4  384.49  5000.7  380.37  5001.2  379.57  5006.7  380.37
  5013.7  385.82  5033.8  388.34  5051.3  384.71  5160.6  385.94  5194.3  390.84
  5234.5  392.43  5254.6  389.17  5274.6  392.38  5465.3  406.43  5595.7  424.26
#Mann=3,-1,0
  4553.2    0.16       0  5000.7    0.07       0  5006.7    0.16       0
Bank Sta=4783.1,5160.6
Exp/Cntr=0.3,0.1

Type RM Length L Ch R = 1,28263,362,362,362
BEGIN DESCRIPTION:
LEWELLYN CREEK 36.0
END DESCRIPTION:
XS GIS Cut Line= 3
      2902024.98      6946125.02      2902275.00      6945925.00
      2902875.00      6945625.00
#Sta/Elev= 30
  4686.4  412.22  4750.5  411.96  4807.3  409.41  4850.5  397.33  4885.7  390.44
  4979.5  384.41  4999.4  377.96  5000.4  376.10  5000.9  375.30  5006.4  376.10
  5009.4  376.10  5015.0  379.72  5020.6  379.18  5028.9  382.98  5051.3  387.89
  5065.3  388.00  5082.1  383.16  5104.4  382.22  5216.2  383.00  5238.6  383.93
  5244.2  387.37  5283.3  386.97  5288.9  384.58  5348.4  384.41  5378.3  385.39
  5386.7  388.15  5431.4  388.56  5557.2  400.46  5624.3  408.65  5677.4  418.80
#Mann=3,-1,0
  4686.4    0.16       0  5000.4    0.07       0  5006.4    0.16       0
Bank Sta=4979.5,5348.4
Exp/Cntr=0.3,0.1

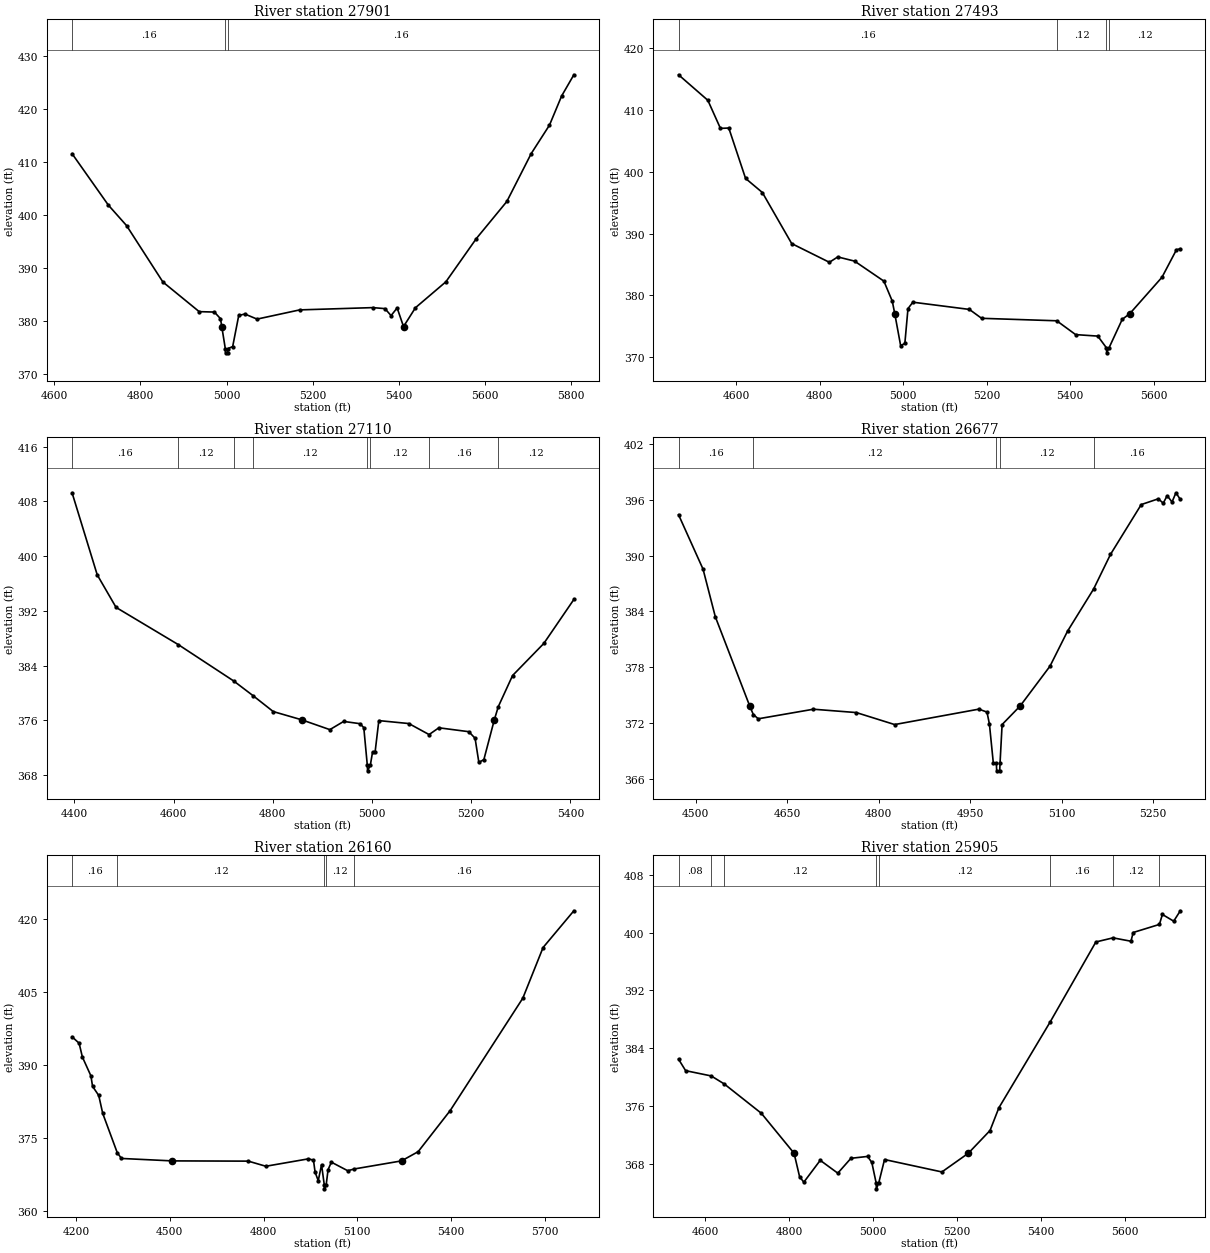
Type RM Length L Ch R = 1,27901,408,408,408
BEGIN DESCRIPTION:
LEWELLYN CREEK 35.0
END DESCRIPTION:
XS GIS Cut Line= 3
      2902075.00      6946175.00      2902375.00      6946275.00
      2902975.03      6945674.97
#Sta/Elev= 30
  4641.3  411.61  4725.6  401.89  4767.8  398.03  4852.1  387.38  4936.4  381.78
  4971.7  381.70  4985.8  380.45  4988.8  378.96  4997.0  374.80  4997.5  374.00
  5002.5  374.00  5003.0  374.80  5014.1  375.18  5028.2  381.06  5042.4  381.33
  5070.7  380.37  5169.7  382.11  5339.4  382.54  5367.6  382.35  5381.8  381.03
  5395.9  382.48  5410.7  378.96  5438.4  382.52  5509.1  387.42  5579.8  395.59
  5650.5  402.58  5707.1  411.63  5749.5  417.00  5777.8  422.52  5806.1  426.51
#Mann=3,-1,0
  4641.3    0.16       0  4997.0    0.07       0  5003.0    0.16       0
Bank Sta=4988.8,5410.7
Exp/Cntr=0.3,0.1

Type RM Length L Ch R = 1,27493,383,383,383
BEGIN DESCRIPTION:
LEWELLYN CREEK 34.0
END DESCRIPTION:
XS GIS Cut Line= 3
      2901975.05      6946625.00      2902525.00      6946575.00
      2903124.98      6946824.99
#Sta/Elev= 30
  4461.6  415.73  4531.8  411.60  4562.0  407.05  4582.0  407.11  4622.2  398.95
  4662.4  396.67  4732.7  388.40  4823.0  385.37  4843.1  386.24  4883.3  385.56
  4953.6  382.32  4973.7  379.08  4979.6  377.06  4993.7  371.89  5003.8  372.23
  5011.3  377.87  5023.0  378.91  5158.4  377.74  5187.7  376.30  5367.7  375.90
  5413.0  373.66  5466.1  373.42  5486.9  371.51  5487.4  370.71  5492.9  371.51
  5524.6  376.13  5542.8  377.06  5619.9  382.95  5654.6  387.41  5663.8  387.55
#Mann=4,-1,0
  4461.6    0.16       0  5367.7    0.12       0  5486.9    0.07       0
  5492.9    0.12       0
Bank Sta=4979.6,5542.8
Exp/Cntr=0.3,0.1

Type RM Length L Ch R = 1,27110,433,433,433
BEGIN DESCRIPTION:
LEWELLYN CREEK 33.0
END DESCRIPTION:
XS GIS Cut Line= 3
      2902025.01      6946825.00      2902625.00      6946925.00
      2903025.02      6946975.00
#Sta/Elev= 30
  4395.5  409.25  4446.2  397.26  4484.2  392.50  4609.7  387.06  4721.5  381.74
  4760.7  379.58  4801.0  377.28  4858.2  376.08  4915.1  374.64  4942.9  375.84
  4975.9  375.51  4983.5  374.93  4990.6  369.42  4991.1  368.62  4996.6  369.42
  5001.2  371.38  5006.3  371.38  5013.8  375.96  5074.3  375.53  5115.1  373.92
  5134.8  374.91  5195.2  374.34  5207.8  373.38  5215.4  369.86  5225.5  370.26
  5246.6  376.08  5254.6  378.00  5283.4  382.55  5346.4  387.24  5406.9  393.66
#Mann=8,-1,0
  4395.5    0.16       0  4609.7    0.12       0  4721.5    0.16       0
  4760.7    0.12       0  4990.6    0.07       0  4996.6    0.12       0
  5115.1    0.16       0  5254.6    0.12       0
Bank Sta=4858.2,5246.6
Exp/Cntr=0.3,0.1

Type RM Length L Ch R = 1,26677,517,517,517
BEGIN DESCRIPTION:
LEWELLYN CREEK 32.0
END DESCRIPTION:
XS GIS Cut Line= 3
      2902374.98      6947125.00      2902875.00      6947175.00
      2903125.03      6946974.98
#Sta/Elev= 30
  4472.0  394.41  4512.2  388.55  4532.3  383.43  4588.7  373.83  4594.6  372.91
  4602.7  372.45  4693.1  373.48  4763.5  373.12  4826.3  371.83  4964.5  373.49
  4977.7  373.17  4981.7  371.89  4988.1  367.69  4993.1  367.65  4993.6  366.85
  4998.6  366.85  4999.1  367.65  5002.5  371.83  5032.1  373.83  5081.0  378.11
  5109.8  381.88  5152.5  386.41  5180.2  390.14  5230.6  395.50  5258.6  396.12
  5266.7  395.65  5273.1  396.46  5281.1  395.78  5287.5  396.77  5294.7  396.05
#Mann=5,-1,0
  4472.0    0.16       0  4594.6    0.12       0  4993.1    0.07       0
  4999.1    0.12       0  5152.5    0.16       0
Bank Sta=4588.7,5032.1
Exp/Cntr=0.3,0.1

Type RM Length L Ch R = 1,26160,255,255,255
BEGIN DESCRIPTION:
Mapping XS 39ecc61b
END DESCRIPTION:
XS GIS Cut Line= 3
      2902233.54      6947311.69      2902967.94      6947540.86
      2903764.82      6947290.86
#Sta/Elev= 30
  4187.8  395.80  4210.3  394.49  4220.8  391.65  4248.1  387.79  4253.3  385.65
  4273.1  383.77  4285.8  380.10  4332.1  372.07  4345.6  370.86  4507.7  370.36
  4751.3  370.31  4807.4  369.26  4943.6  370.78  4959.7  370.51  4964.9  368.04
  4975.0  366.30  4985.5  369.59  4994.3  365.43  4994.8  364.63  5000.3  365.43
  5006.4  368.56  5016.9  370.10  5069.3  368.34  5090.6  368.71  5241.2  370.36
  5294.4  372.25  5396.9  380.68  5629.1  403.72  5693.9  414.11  5792.3  421.64
#Mann=5,-1,0
  4187.8    0.16       0  4332.1    0.12       0  4994.3    0.07       0
  5000.3    0.12       0  5090.6    0.16       0
Bank Sta=4507.7,5241.2
Exp/Cntr=0.3,0.1

Type RM Length L Ch R = 1,25905,278,278,278
BEGIN DESCRIPTION:
Mapping XS 41cbe7db
END DESCRIPTION:
XS GIS Cut Line= 3
      2902650.23      6947822.12      2903155.44      6947743.99
      2903806.50      6947535.65
#Sta/Elev= 30
  4536.9  382.48  4553.8  380.89  4614.7  380.16  4645.5  379.06  4734.0  374.99
  4812.0  369.45  4825.1  366.21  4835.2  365.44  4874.3  368.47  4916.1  366.69
  4947.4  368.75  4987.0  369.01  4997.1  368.18  5007.5  365.32  5008.0  364.52
  5013.5  365.32  5027.4  368.58  5164.0  366.86  5226.9  369.45  5278.6  372.60
  5299.6  375.74  5422.1  387.67  5530.6  398.72  5571.5  399.29  5614.2  398.82
  5619.4  400.03  5681.9  401.15  5689.0  402.53  5715.9  401.60  5731.7  403.04
#Mann=8,-1,0
  4536.9    0.08       0  4614.7    0.05       0  4645.5    0.12       0
  5007.5    0.07       0  5013.5    0.12       0  5422.1    0.16       0
  5571.5    0.12       0  5681.9    0.16       0
Bank Sta=4812,5226.9
Exp/Cntr=0.3,0.1

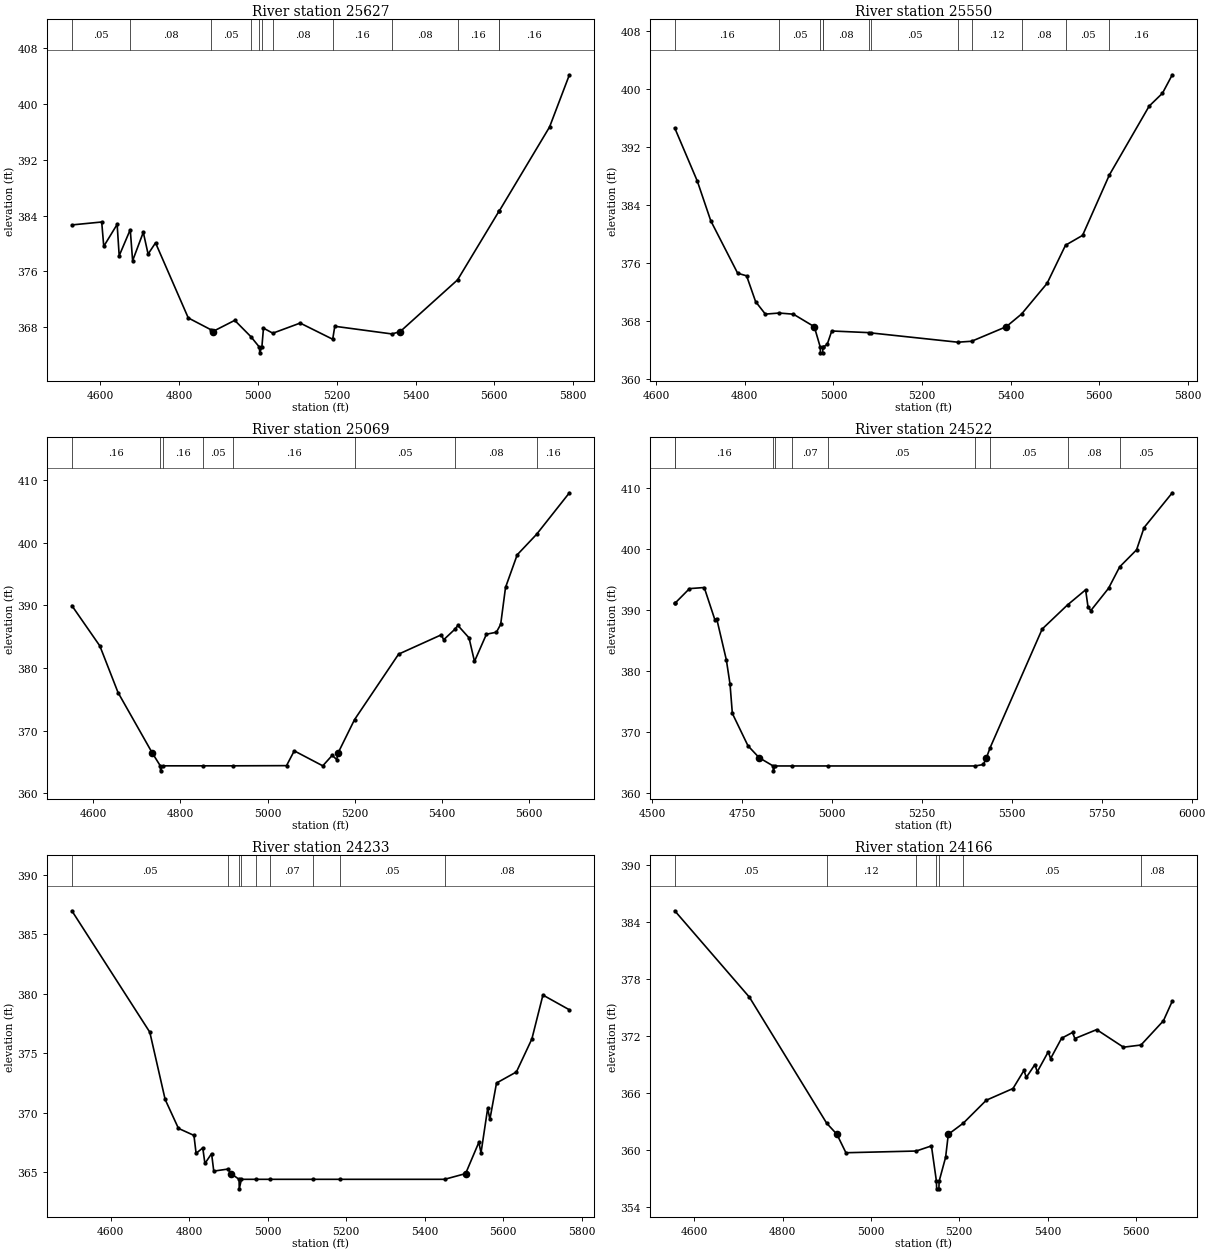
Type RM Length L Ch R = 1,25627,77,77,77
BEGIN DESCRIPTION:
Mapping XS fe41b5f6
END DESCRIPTION:
XS GIS Cut Line= 4
      2902780.41      6947858.56      2903243.99      6947988.78
      2903467.94      6948066.91      2903971.59      6948274.59
#Sta/Elev= 30
  4527.3  382.67  4603.1  383.09  4608.3  379.60  4642.3  382.75  4647.5  378.25
  4675.6  381.99  4681.6  377.54  4708.7  381.61  4720.9  378.49  4739.8  380.10
  4822.9  369.33  4879.9  367.65  4885.0  367.37  4940.9  368.98  4982.1  366.63
  5003.8  365.12  5004.3  364.32  5009.8  365.12  5013.9  367.86  5037.7  367.14
  5107.1  368.59  5189.7  366.27  5195.0  368.13  5340.1  367.03  5361.1  367.37
  5506.8  374.79  5612.2  384.66  5612.9  384.69  5740.4  396.72  5790.8  404.21
#Mann=12,-1,0
  4527.3    0.05       0  4675.6    0.08       0  4879.9    0.05       0
  4982.1    0.12       0  5003.8    0.07       0  5009.8    0.12       0
  5037.7    0.08       0  5189.7    0.16       0  5340.1    0.08       0
  5506.8    0.16       0  5612.2    0.05       0  5612.9    0.16       0
Bank Sta=4885,5361.1
Exp/Cntr=0.3,0.1

Type RM Length L Ch R = 1,25550,481,481,481
BEGIN DESCRIPTION:
Mapping XS 457f632b
END DESCRIPTION:
XS GIS Cut Line= 4
      2902884.63      6948009.62      2903259.61      6948066.91
      2903603.36      6948270.03      2903947.12      6948290.87
#Sta/Elev= 30
  4641.7  394.67  4692.7  387.32  4723.0  381.85  4783.7  374.60  4803.9  374.24
  4824.2  370.68  4846.2  368.95  4877.5  369.10  4909.6  368.94  4956.7  367.21
  4970.1  364.40  4970.6  363.60  4975.6  363.60  4976.1  364.40  4977.4  364.40
  4986.0  364.80  4996.1  366.62  5080.4  366.39  5084.8  366.35  5280.6  365.07
  5311.8  365.20  5389.9  367.21  5424.6  368.97  5482.1  373.20  5523.7  378.47
  5562.2  379.83  5622.7  388.18  5712.5  397.69  5742.5  399.47  5764.7  402.02
#Mann=12,-1,0
  4641.7    0.16       0  4877.5    0.05       0  4970.1    0.07       0
  4976.1    0.05       0  4977.4    0.08       0  5080.4    0.16       0
  5084.8    0.05       0  5280.6    0.16       0  5311.8    0.12       0
  5424.6    0.08       0  5523.7    0.05       0  5622.7    0.16       0
Bank Sta=4956.7,5389.9
Exp/Cntr=0.3,0.1

Type RM Length L Ch R = 1,25069,547,547,547
BEGIN DESCRIPTION:
LEWELLYN CREEK 29.0
END DESCRIPTION:
XS GIS Cut Line= 3
      2902975.03      6948824.97      2903325.00      6948525.00
      2903974.99      6948325.00
#Sta/Elev= 30
  4551.0  389.98  4615.2  383.54  4656.9  376.10  4735.5  366.44  4753.8  364.40
  4754.3  363.60  4759.8  364.40  4851.6  364.40  4919.5  364.40  5043.3  364.43
  5061.0  366.79  5126.4  364.40  5148.0  366.07  5158.4  365.40  5161.4  366.44
  5199.2  371.77  5300.3  382.23  5398.4  385.32  5403.6  384.52  5429.4  386.21
  5436.3  386.81  5461.8  384.83  5474.3  381.07  5501.7  385.41  5524.6  385.73
  5534.4  386.99  5545.5  392.88  5572.3  398.09  5616.6  401.35  5692.0  407.99
#Mann=8,-1,0
  4551.0    0.16       0  4753.8    0.07       0  4759.8    0.16       0
  4851.6    0.05       0  4919.5    0.16       0  5199.2    0.05       0
  5429.4    0.08       0  5616.6    0.16       0
Bank Sta=4735.5,5161.4
Exp/Cntr=0.3,0.1

Type RM Length L Ch R = 1,24522,289,289,289
BEGIN DESCRIPTION:
LEWELLYN CREEK 28.0
END DESCRIPTION:
XS GIS Cut Line= 3
      2902974.99      6948975.00      2903425.00      6949075.00
      2904024.97      6948375.03
#Sta/Elev= 30
  4563.3  391.02  4563.4  391.02  4604.3  393.45  4645.3  393.63  4674.7  388.38
  4679.8  388.55  4706.7  381.79  4717.0  377.79  4723.4  373.01  4766.9  367.70
  4798.0  365.75  4836.8  364.40  4837.3  363.60  4842.9  364.40  4888.7  364.40
  4989.6  364.40  5399.0  364.40  5421.1  364.64  5429.7  365.75  5439.6  367.35
  5584.6  386.83  5655.0  390.78  5705.3  393.25  5711.9  390.48  5719.6  389.84
  5769.0  393.50  5799.9  397.01  5846.9  399.80  5867.8  403.45  5946.2  409.15
#Mann=10,-1,0
  4563.3    0.05       0  4563.4    0.16       0  4836.8   0.033       0
  4842.9    0.16       0  4888.7    0.07       0  4989.6    0.05       0
  5399.0    0.16       0  5439.6    0.05       0  5655.0    0.08       0
  5799.9    0.05       0
Bank Sta=4798,5429.7
Exp/Cntr=0.3,0.1

Type RM Length L Ch R = 1,24233,67,67,67
BEGIN DESCRIPTION:
Mapping XS 37ba0ce8
END DESCRIPTION:
XS GIS Cut Line= 3
      2902931.47      6949577.33      2903441.90      6949327.32
      2904071.03      6949020.56
#Sta/Elev= 30
  4500.7  386.96  4699.4  376.76  4738.5  371.11  4772.4  368.68  4811.9  368.09
  4817.4  366.58  4834.4  367.04  4839.9  365.73  4856.9  366.56  4862.4  365.09
  4898.4  365.26  4906.5  364.88  4926.9  364.40  4927.4  363.60  4933.0  364.40
  4971.2  364.40  5005.1  364.40  5116.6  364.40  5183.9  364.40  5450.8  364.40
  5504.4  364.88  5538.2  367.51  5543.7  366.62  5560.7  370.37  5566.3  369.44
  5583.2  372.49  5633.9  373.42  5673.3  376.19  5701.5  379.88  5769.0  378.64
#Mann=9,-1,0
  4500.7    0.05       0  4898.4    0.12       0  4926.9   0.033       0
  4933.0    0.12       0  4971.2    0.05       0  5005.1    0.07       0
  5116.6    0.16       0  5183.9    0.05       0  5450.8    0.08       0
Bank Sta=4906.5,5504.4
Exp/Cntr=0.3,0.1

Type RM Length L Ch R = 1,24166,482,482,482
BEGIN DESCRIPTION:
Mapping XS 79b5689f
END DESCRIPTION:
XS GIS Cut Line= 3
      2902978.40      6949598.14      2903405.44      6949415.86
      2904025.20      6949181.50
#Sta/Elev= 30
  4555.5  385.22  4724.7  376.12  4899.6  362.86  4922.8  361.69  4943.2  359.75
  5102.4  359.93  5136.9  360.47  5148.2  356.75  5148.7  355.95  5153.8  355.95
  5154.3  356.75  5169.0  359.27  5175.1  361.69  5209.2  362.87  5261.2  365.28
  5321.6  366.51  5346.4  368.41  5351.8  367.68  5371.2  369.03  5376.6  368.27
  5401.4  370.37  5406.8  369.66  5431.6  371.80  5456.4  372.41  5461.8  371.77
  5511.1  372.71  5571.8  370.86  5611.5  371.09  5662.3  373.64  5682.4  375.71
#Mann=7,-1,0
  4555.5    0.05       0  4899.6    0.12       0  5102.4    0.16       0
  5148.2    0.07       0  5154.3    0.16       0  5209.2    0.05       0
  5611.5    0.08       0
Bank Sta=4922.8,5175.1
Exp/Cntr=0.3,0.1

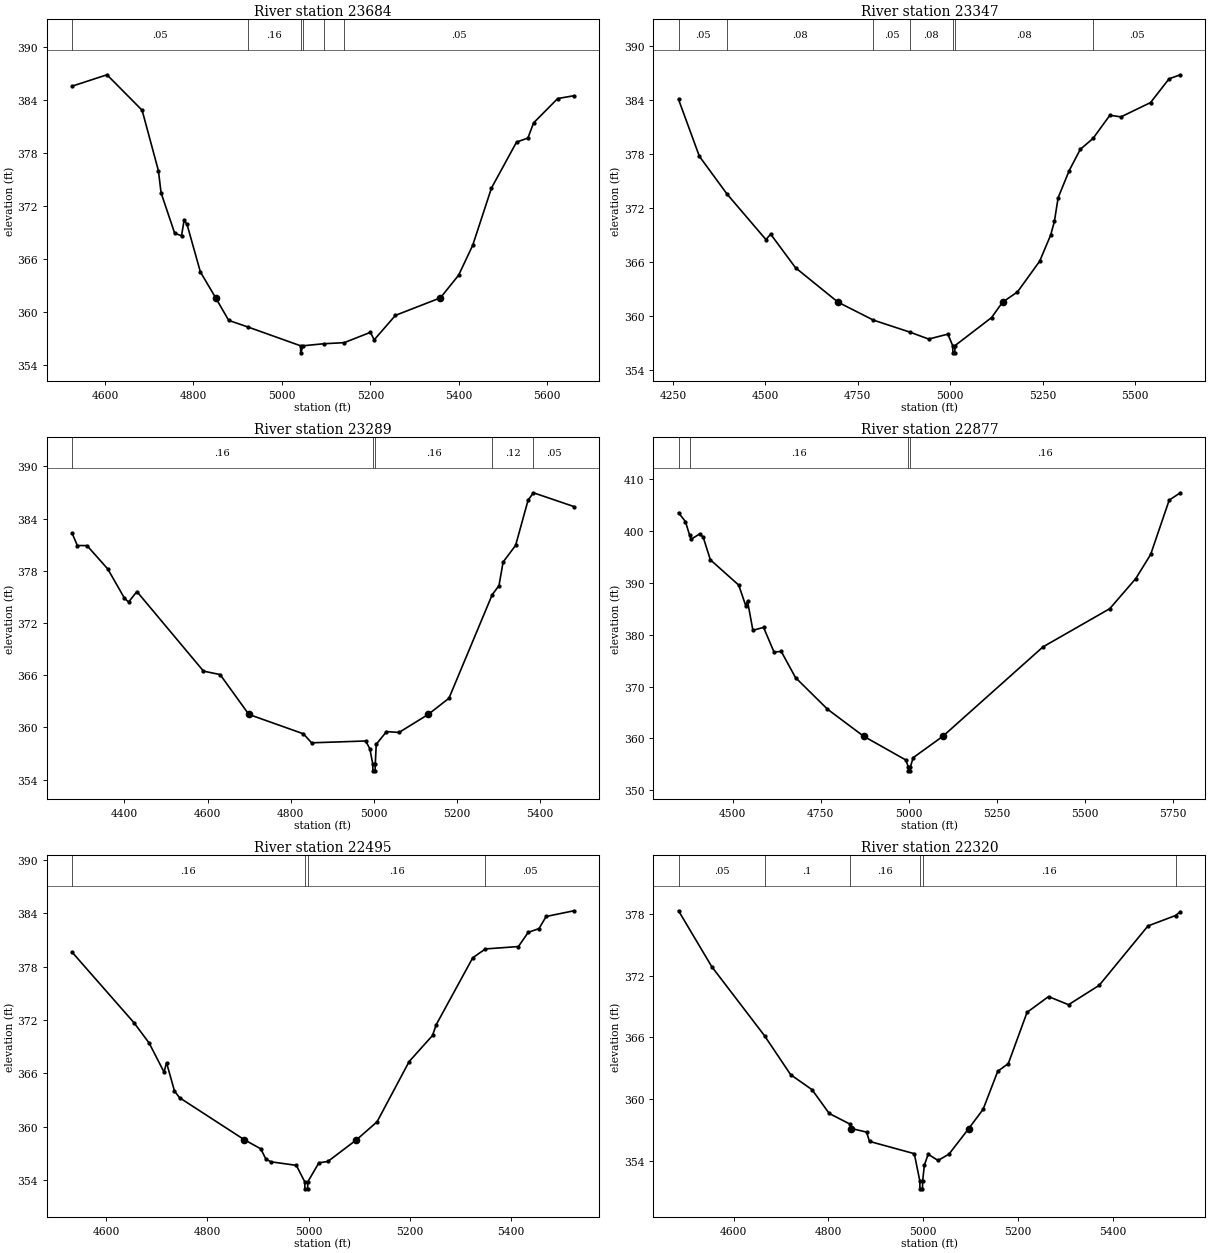
Type RM Length L Ch R = 1,23684,337,337,337
BEGIN DESCRIPTION:
LEWELLYN CREEK 27.0
END DESCRIPTION:
XS GIS Cut Line= 3
      2903033.08      6949648.71      2903438.18      6949895.20
      2904060.82      6949676.59
#Sta/Elev= 30
  4525.8  385.54  4604.7  386.83  4684.1  382.82  4720.9  375.99  4727.0  373.47
  4757.7  368.91  4773.2  368.62  4779.0  370.38  4785.6  369.91  4815.8  364.53
  4850.4  361.60  4879.8  359.05  4923.5  358.30  5042.1  356.18  5042.6  355.38
  5048.2  356.18  5094.9  356.41  5140.8  356.53  5200.1  357.70  5208.6  356.85
  5256.7  359.62  5358.3  361.60  5399.4  364.16  5431.2  367.53  5473.7  374.02
  5530.4  379.22  5556.0  379.67  5568.9  381.39  5623.3  384.14  5659.9  384.46
#Mann=6,-1,0
  4525.8    0.05       0  4923.5    0.16       0  5042.1    0.07       0
  5048.2    0.16       0  5094.9    0.12       0  5140.8    0.05       0
Bank Sta=4850.4,5358.3
Exp/Cntr=0.3,0.1

Type RM Length L Ch R = 1,23347,58,58,58
BEGIN DESCRIPTION:
Mapping XS 9b8d58fb
END DESCRIPTION:
XS GIS Cut Line= 3
      2902738.67      6950204.84      2903486.10      6950220.47
      2904095.48      6950225.68
#Sta/Elev= 30
  4265.1  384.09  4321.4  377.77  4396.0  373.58  4501.5  368.50  4514.2  369.11
  4581.5  365.37  4696.5  361.54  4792.0  359.55  4891.0  358.21  4941.6  357.44
  4993.4  357.99  5006.5  356.71  5007.0  355.91  5012.2  355.91  5012.7  356.71
  5111.6  359.83  5141.3  361.54  5181.6  362.68  5241.6  366.09  5271.6  369.02
  5281.6  370.54  5291.6  373.15  5321.6  376.18  5351.6  378.54  5386.0  379.75
  5431.6  382.33  5461.6  382.15  5541.6  383.74  5591.6  386.38  5622.1  386.83
#Mann=7,-1,0
  4265.1    0.05       0  4396.0    0.08       0  4792.0    0.05       0
  4891.0    0.08       0  5006.5    0.07       0  5012.7    0.08       0
  5386.0    0.05       0
Bank Sta=4696.5,5141.3
Exp/Cntr=0.3,0.1

Type RM Length L Ch R = 1,23289,412,412,412
BEGIN DESCRIPTION:
Mapping XS cfecd85c
END DESCRIPTION:
XS GIS Cut Line= 3
      2902749.13      6950269.95      2903480.89      6950272.55
      2903954.81      6950298.59
#Sta/Elev= 30
  4274.3  382.32  4287.0  380.90  4310.2  380.89  4360.2  378.20  4400.2  374.85
  4410.2  374.41  4430.2  375.61  4590.2  366.47  4630.2  366.07  4699.4  361.49
  4830.2  359.27  4850.2  358.23  4980.2  358.44  4990.2  357.55  4997.1  355.81
  4997.6  355.01  5002.8  355.01  5003.3  355.81  5005.6  358.06  5030.2  359.52
  5060.3  359.42  5130.5  361.49  5180.4  363.35  5284.5  375.26  5300.6  376.28
  5310.6  379.00  5340.7  380.92  5370.7  386.12  5383.5  386.96  5480.7  385.38
#Mann=5,-1,0
  4274.3    0.16       0  4997.1    0.07       0  5003.3    0.16       0
  5284.5    0.12       0  5383.5    0.05       0
Bank Sta=4699.4,5130.5
Exp/Cntr=0.3,0.1

Type RM Length L Ch R = 1,22877,382,382,382
BEGIN DESCRIPTION:
LEWELLYN CREEK 25.0
END DESCRIPTION:
XS GIS Cut Line= 3
      2902845.45      6950595.47      2903475.00      6950675.00
      2904224.98      6950425.01
#Sta/Elev= 30
  4346.6  403.57  4366.3  401.85  4378.0  399.24  4382.1  398.45  4406.6  399.47
  4416.7  398.84  4436.9  394.49  4517.5  389.60  4537.5  385.62  4542.5  386.52
  4557.8  380.87  4588.1  381.43  4617.7  376.69  4638.4  376.78  4678.8  371.74
  4769.5  365.65  4872.1  360.43  4991.7  355.85  4999.1  354.54  4999.6  353.74
  5004.8  353.74  5005.3  354.54  5012.8  356.27  5097.6  360.43  5381.7  377.67
  5571.4  385.05  5645.2  390.86  5687.4  395.51  5740.1  406.00  5771.7  407.42
#Mann=4,-1,0
  4346.6    0.05       0  4378.0    0.16       0  4999.1    0.07       0
  5005.3    0.16       0
Bank Sta=4872.1,5097.6
Exp/Cntr=0.3,0.1

Type RM Length L Ch R = 1,22495,175,175,175
BEGIN DESCRIPTION:
Mapping XS 82128e75
END DESCRIPTION:
XS GIS Cut Line= 3
      2903133.19      6951055.54      2903599.38      6951016.48
      2904089.40      6950829.80
#Sta/Elev= 30
  4532.5  379.63  4654.7  371.71  4684.8  369.42  4714.3  366.15  4719.3  367.20
  4735.0  364.02  4745.1  363.26  4873.4  358.53  4905.6  357.52  4915.6  356.38
  4925.7  356.06  4975.9  355.66  4992.5  353.82  4993.0  353.02  4998.2  353.02
  4998.7  353.82  5020.5  355.94  5038.4  356.10  5094.8  358.53  5135.5  360.55
  5199.0  367.33  5245.2  370.26  5252.5  371.47  5324.8  379.00  5349.9  379.99
  5415.1  380.26  5434.4  381.85  5455.8  382.28  5469.9  383.64  5524.7  384.28
#Mann=4,-1,0
  4532.5    0.16       0  4992.5    0.07       0  4998.7    0.16       0
  5349.9    0.05       0
Bank Sta=4873.4,5094.8
Exp/Cntr=0.3,0.1

Type RM Length L Ch R = 1,22320,40,40,40
BEGIN DESCRIPTION:
Mapping XS 0c6bdb70
END DESCRIPTION:
XS GIS Cut Line= 6
      2903355.87      6951593.77      2903559.88      6951276.89
      2903594.61      6951220.47      2903694.43      6951146.68
      2903939.66      6951059.88      2904140.76      6950947.43
#Sta/Elev= 30
  4484.0  378.28  4553.9  372.87  4665.3  366.16  4720.4  362.38  4765.4  360.93
  4801.7  358.62  4844.5  357.61  4848.6  357.16  4880.4  356.81  4886.6  355.91
  4981.0  354.72  4992.5  352.11  4993.0  351.31  4998.2  351.31  4998.7  352.11
  5002.2  353.60  5010.2  354.67  5031.1  354.06  5054.2  354.68  5095.8  357.16
  5126.0  359.02  5156.9  362.71  5179.2  363.46  5218.7  368.43  5264.0  369.96
  5306.1  369.17  5370.8  371.05  5473.6  376.81  5531.7  377.82  5541.8  378.19
#Mann=6,-1,0
  4484.0    0.05       0  4665.3     0.1       0  4844.5    0.16       0
  4992.5    0.07       0  4998.7    0.16       0  5531.7    0.05       0
Bank Sta=4848.6,5095.8
Exp/Cntr=0.3,0.1