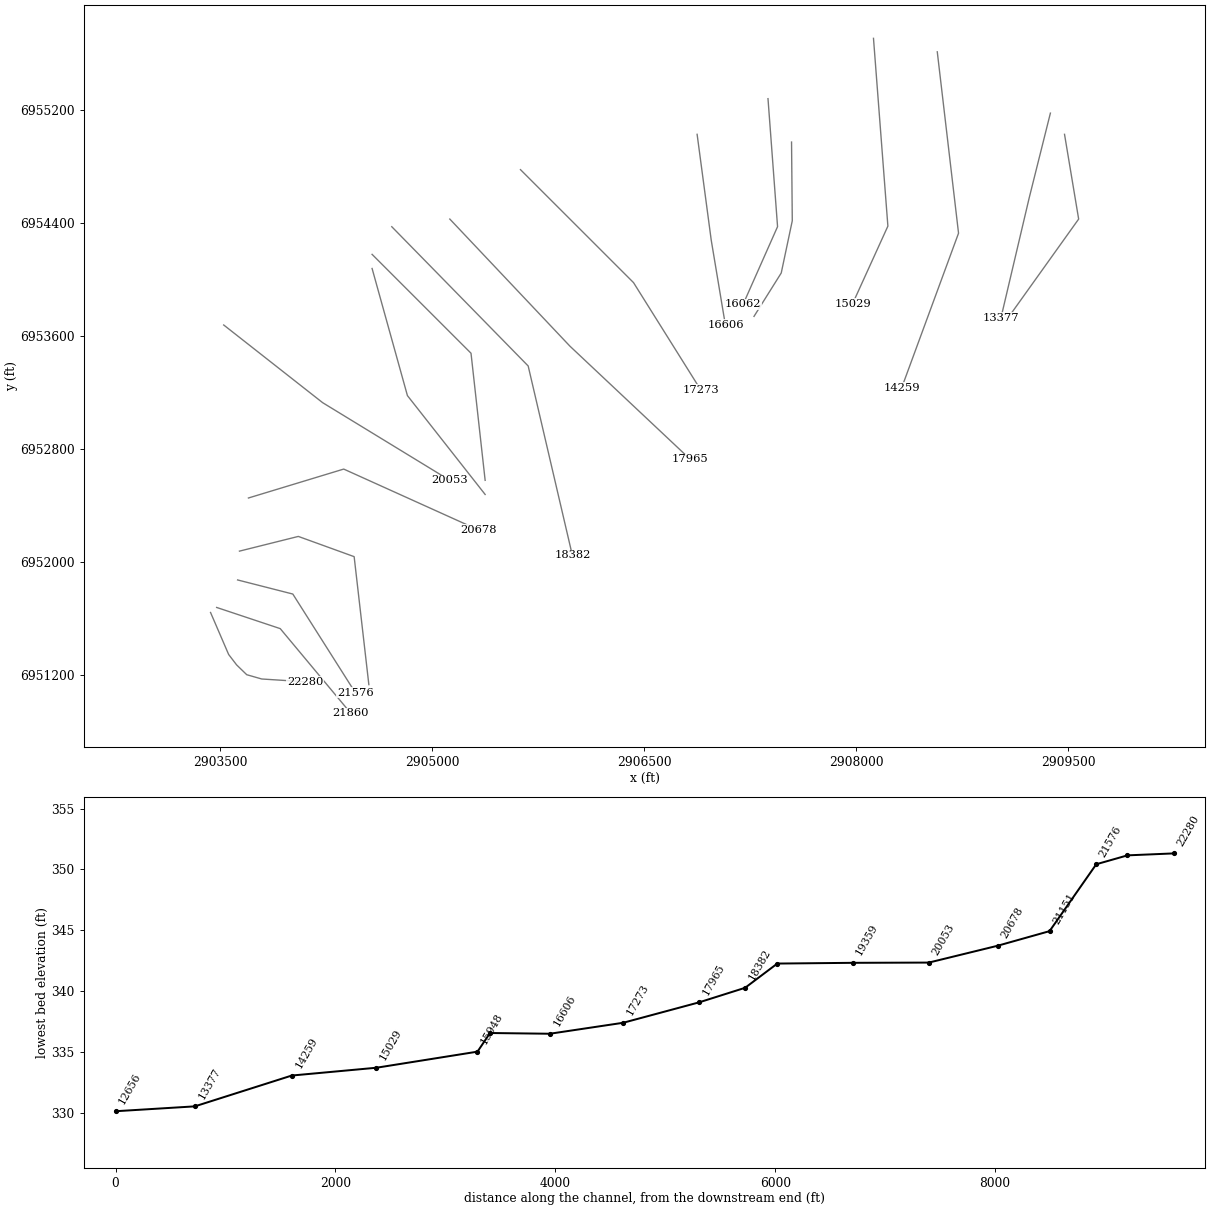
HEC-RAS study LEWELLYN CREEK.prj: LEWELLYN CREEK Base Level Engineering

--- LEWELLYN CREEK.g01 (geometry) --- (continued)

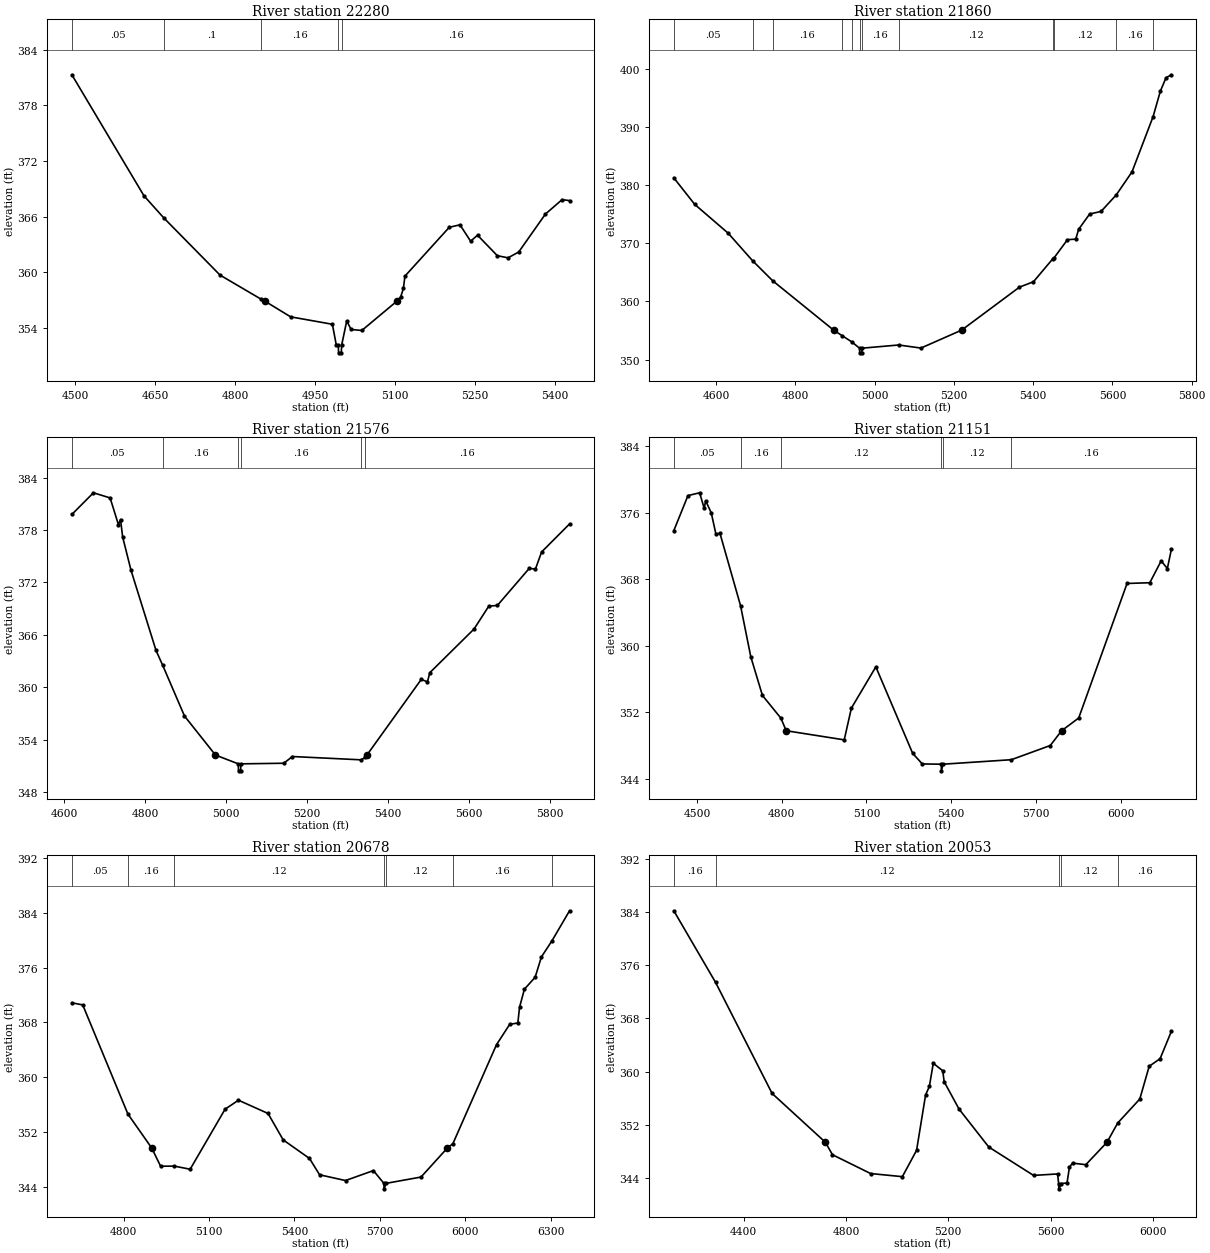
Type RM Length L Ch R = 1,22280,420,420,420
BEGIN DESCRIPTION:
Mapping XS 30179ec8
END DESCRIPTION:
XS GIS Cut Line= 6
      2903431.85      6951639.30      2903559.88      6951342.00
      2903616.31      6951268.21      2903687.92      6951198.77
      2903794.26      6951168.39      2904100.10      6951148.86
#Sta/Elev= 30
  4494.0  381.29  4629.3  368.24  4666.3  365.87  4771.9  359.70  4848.1  357.13
  4856.1  356.89  4904.3  355.20  4982.6  354.40  4989.8  352.20  4993.7  352.12
  4994.2  351.32  4999.4  351.32  4999.9  352.12  5009.5  354.76  5017.7  353.84
  5037.8  353.73  5103.6  356.89  5110.6  357.32  5115.8  358.27  5118.7  359.59
  5201.8  364.85  5221.9  365.12  5241.9  363.35  5254.8  364.00  5292.0  361.79
  5312.1  361.56  5332.1  362.19  5382.2  366.28  5413.4  367.83  5427.4  367.73
#Mann=5,-1,0
  4494.0    0.05       0  4666.3     0.1       0  4848.1    0.16       0
  4993.7    0.07       0  4999.9    0.16       0
Bank Sta=4856.1,5103.6
Exp/Cntr=0.3,0.1

Type RM Length L Ch R = 1,21860,284,284,284
BEGIN DESCRIPTION:
LEWELLYN CREEK 23.0
END DESCRIPTION:
XS GIS Cut Line= 3
      2903475.01      6951675.00      2903925.00      6951525.00
      2904425.03      6950924.97
#Sta/Elev= 30
  4493.7  381.25  4546.4  376.69  4630.7  371.74  4693.2  366.94  4743.0  363.56
  4896.8  355.07  4917.9  354.13  4942.9  353.03  4962.2  351.96  4962.7  351.16
  4968.0  351.16  4968.5  351.96  5061.0  352.51  5117.1  351.98  5219.9  355.07
  5365.7  362.46  5400.9  363.38  5450.1  367.36  5452.9  367.49  5486.8  370.62
  5507.6  370.71  5514.8  372.39  5542.7  375.03  5571.4  375.47  5609.6  378.30
  5649.5  382.27  5702.8  391.79  5721.1  396.17  5735.4  398.47  5749.1  398.97
#Mann=12,-1,0
  4493.7    0.05       0  4693.2     0.1       0  4743.0    0.16       0
  4917.9    0.12       0  4942.9    0.16       0  4962.2    0.07       0
  4968.5    0.16       0  5061.0    0.12       0  5450.1    0.16       0
  5452.9    0.12       0  5609.6    0.16       0  5702.8    0.05       0
Bank Sta=4896.8,5219.9
Exp/Cntr=0.3,0.1

Type RM Length L Ch R = 1,21576,425,425,425
BEGIN DESCRIPTION:
Mapping XS 80532c1b
END DESCRIPTION:
XS GIS Cut Line= 3
      2903623.35      6951869.74      2904013.97      6951769.92
      2904456.68      6951071.13
#Sta/Elev= 30
  4618.8  379.79  4672.1  382.27  4713.4  381.68  4733.9  378.62  4739.1  379.21
  4744.4  377.20  4765.0  373.40  4826.9  364.21  4843.4  362.51  4897.2  356.71
  4973.8  352.24  5030.3  351.23  5030.8  350.43  5036.1  350.43  5036.6  351.23
  5142.8  351.30  5164.0  352.07  5334.2  351.69  5343.3  351.96  5348.3  352.24
  5482.6  360.90  5497.9  360.62  5503.8  361.67  5613.1  366.67  5649.6  369.29
  5670.8  369.37  5749.9  373.63  5764.8  373.52  5780.1  375.49  5849.2  378.70
#Mann=6,-1,0
  4618.8    0.05       0  4843.4    0.16       0  5030.3    0.07       0
  5036.6    0.16       0  5334.2    0.12       0  5343.3    0.16       0
Bank Sta=4973.8,5348.3
Exp/Cntr=0.3,0.1

Type RM Length L Ch R = 1,21151,473,473,473
BEGIN DESCRIPTION:
LEWELLYN CREEK 22.0
END DESCRIPTION:
XS GIS Cut Line= 4
      2903636.36      6952073.73      2904053.04      6952177.90
      2904448.00      6952034.67      2904552.03      6951128.76
#Sta/Elev= 30
  4418.2  373.86  4468.3  378.08  4509.6  378.42  4525.8  376.54  4530.9  377.46
  4550.8  376.00  4567.0  373.48  4581.7  373.52  4654.4  364.83  4690.7  358.67
  4731.9  354.02  4797.5  351.27  4815.9  349.77  5021.4  348.67  5046.7  352.49
  5133.3  357.46  5263.6  347.05  5297.7  345.77  5364.9  345.74  5365.4  344.94
  5371.2  345.74  5612.8  346.28  5750.7  347.99  5790.8  349.77  5851.3  351.30
  6022.4  367.50  6103.0  367.59  6143.2  370.22  6165.1  369.30  6179.7  371.67
#Mann=6,-1,0
  4418.2    0.05       0  4654.4    0.16       0  4797.5    0.12       0
  5364.9    0.07       0  5371.2    0.12       0  5612.8    0.16       0
Bank Sta=4815.9,5790.8
Exp/Cntr=0.3,0.1

Type RM Length L Ch R = 1,20678,625,625,625
BEGIN DESCRIPTION:
double LEWELLYN CREEK 21.0
END DESCRIPTION:
XS GIS Cut Line= 3
      2903699.96      6952449.99      2904374.22      6952654.75
      2905325.04      6952224.98
#Sta/Elev= 30
  4618.0  370.86  4656.1  370.56  4814.9  354.64  4898.7  349.68  4929.7  347.04
  4978.2  347.05  5033.5  346.60  5156.3  355.36  5203.2  356.66  5307.1  354.73
  5360.2  350.88  5452.7  348.17  5488.1  345.79  5579.2  344.95  5677.1  346.40
  5714.0  344.54  5714.7  343.74  5721.7  344.54  5844.4  345.46  5936.7  349.68
  5956.3  350.32  6109.6  364.76  6155.9  367.72  6184.5  367.92  6190.5  370.22
  6207.6  372.85  6245.3  374.59  6267.3  377.55  6304.2  379.89  6366.1  384.28
#Mann=7,-1,0
  4618.0    0.05       0  4814.9    0.16       0  4978.2    0.12       0
  5714.0    0.07       0  5721.7    0.12       0  5956.3    0.16       0
  6304.2    0.05       0
Bank Sta=4898.7,5936.7
Exp/Cntr=0.3,0.1

Type RM Length L Ch R = 1,20053,694,694,694
BEGIN DESCRIPTION:
double LEWELLYN CREEK 20.0
END DESCRIPTION:
XS GIS Cut Line= 3
      2903524.98      6953675.01      2904225.00      6953125.00
      2905125.00      6952575.00
#Sta/Elev= 30
  4127.5  384.17  4290.9  373.39  4511.7  356.70  4719.7  349.37  4747.5  347.49
  4896.6  344.66  5020.7  344.19  5076.3  348.15  5111.5  356.48  5126.2  357.75
  5141.6  361.24  5178.4  360.12  5184.2  358.46  5242.3  354.35  5358.4  348.65
  5533.4  344.38  5627.4  344.60  5631.5  343.16  5632.3  342.36  5642.5  343.16
  5664.2  343.24  5673.8  345.62  5685.8  346.23  5737.7  345.99  5820.6  349.37
  5862.4  352.26  5948.6  355.86  5985.4  360.79  6028.0  361.93  6072.5  366.08
#Mann=5,-1,0
  4127.5    0.16       0  4290.9    0.12       0  5631.5    0.07       0
  5642.5    0.12       0  5862.4    0.16       0
Bank Sta=4719.7,5820.6
Exp/Cntr=0.3,0.1

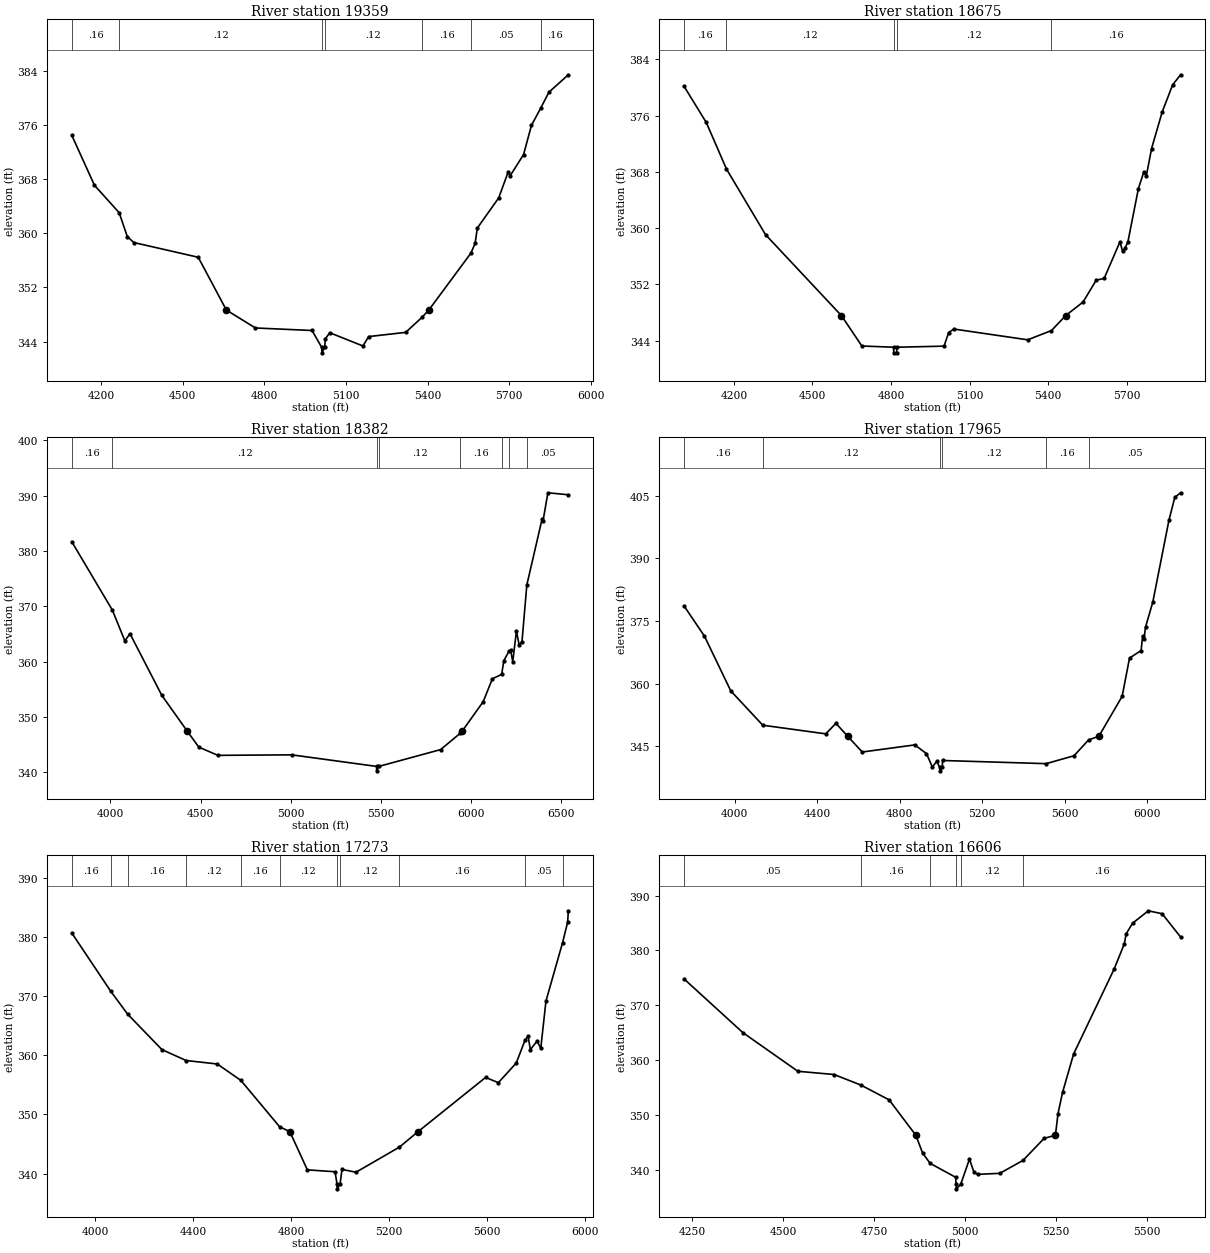
Type RM Length L Ch R = 1,19359,684,684,684
BEGIN DESCRIPTION:
double LEWELLYN CREEK 19.0
END DESCRIPTION:
XS GIS Cut Line= 3
      2904575.00      6954075.02      2904825.00      6953175.00
      2905374.99      6952475.02
#Sta/Elev= 30
  4092.5  374.45  4175.5  367.09  4266.6  363.02  4296.5  359.49  4320.8  358.62
  4557.0  356.45  4660.3  348.66  4767.1  346.01  4975.2  345.64  5010.7  343.14
  5011.5  342.34  5021.7  343.14  5024.0  344.41  5040.2  345.31  5162.2  343.35
  5183.0  344.74  5319.1  345.36  5379.4  347.59  5404.2  348.66  5558.7  357.05
  5574.3  358.50  5582.4  360.76  5661.0  365.22  5696.3  369.10  5702.6  368.45
  5752.4  371.62  5781.3  375.93  5815.9  378.51  5845.4  380.82  5916.8  383.39
#Mann=7,-1,0
  4092.5    0.16       0  4266.6    0.12       0  5010.7    0.07       0
  5021.7    0.12       0  5379.4    0.16       0  5558.7    0.05       0
  5815.9    0.16       0
Bank Sta=4660.3,5404.2
Exp/Cntr=0.3,0.1

Type RM Length L Ch R = 1,18675,293,293,293
BEGIN DESCRIPTION:
LEWELLYN CREEK 18.0
END DESCRIPTION:
XS GIS Cut Line= 3
      2904575.00      6954175.00      2905275.00      6953475.00
      2905375.00      6952574.99
#Sta/Elev= 30
  4009.7  380.15  4094.6  375.01  4171.6  368.40  4320.8  359.07  4610.5  347.57
  4688.5  343.25  4809.7  343.08  4810.2  342.28  4821.5  342.28  4822.0  343.08
  5002.2  343.23  5019.8  345.17  5039.9  345.66  5321.6  344.13  5412.4  345.45
  5466.4  347.57  5532.9  349.50  5583.2  352.61  5613.4  352.85  5673.8  358.06
  5683.8  356.69  5693.9  357.22  5704.0  358.03  5744.2  365.63  5764.3  367.93
  5774.4  367.42  5794.5  371.31  5834.8  376.49  5875.0  380.37  5905.2  381.79
#Mann=5,-1,0
  4009.7    0.16       0  4171.6    0.12       0  4809.7    0.07       0
  4822.0    0.12       0  5412.4    0.16       0
Bank Sta=4610.5,5466.4
Exp/Cntr=0.3,0.1

Type RM Length L Ch R = 1,18382,417,417,417
BEGIN DESCRIPTION:
Mapping XS 97cd643f
END DESCRIPTION:
XS GIS Cut Line= 3
      2904714.29      6954370.85      2905679.54      6953384.76
      2905992.04      6952044.49
#Sta/Elev= 30
  3785.5  381.69  4010.7  369.33  4080.1  363.77  4108.3  365.08  4285.1  353.93
  4425.9  347.48  4490.3  344.58  4596.3  343.09  5006.5  343.18  5477.3  341.09
  5477.8  340.29  5489.6  341.09  5832.8  344.13  5942.7  347.11  5952.5  347.48
  6068.7  352.77  6120.1  356.93  6171.4  357.72  6183.6  360.19  6211.3  361.87
  6221.0  362.13  6233.0  360.03  6253.6  365.55  6268.7  363.02  6284.4  363.66
  6311.2  373.88  6396.3  385.85  6401.5  385.53  6428.1  390.54  6541.6  390.18
#Mann=8,-1,0
  3785.5    0.16       0  4010.7    0.12       0  5477.3    0.07       0
  5489.6    0.12       0  5942.7    0.16       0  6171.4    0.05       0
  6211.3    0.08       0  6311.2    0.05       0
Bank Sta=4425.9,5952.5
Exp/Cntr=0.3,0.1

Type RM Length L Ch R = 1,17965,692,692,692
BEGIN DESCRIPTION:
LEWELLYN CREEK 17.0
END DESCRIPTION:
XS GIS Cut Line= 3
      2905125.00      6954425.00      2905975.00      6953525.00
      2906825.00      6952725.00
#Sta/Elev= 30
  3755.4  378.60  3854.3  371.35  3981.7  358.25  4136.6  350.03  4441.7  347.96
  4491.1  350.48  4547.6  347.40  4618.5  343.61  4873.0  345.31  4929.6  343.23
  4957.9  340.02  4979.4  341.36  4994.2  339.90  4994.7  339.10  5006.6  339.90
  5007.3  341.58  5509.2  340.82  5644.1  342.71  5714.8  346.49  5764.9  347.40
  5877.6  356.95  5913.2  366.11  5969.4  367.92  5976.7  371.43  5983.6  370.74
  5990.9  373.56  6026.1  379.54  6104.2  399.13  6132.5  404.60  6160.6  405.70
#Mann=6,-1,0
  3755.4    0.16       0  4136.6    0.12       0  4994.2    0.07       0
  5006.6    0.12       0  5509.2    0.16       0  5714.8    0.05       0
Bank Sta=4547.6,5764.9
Exp/Cntr=0.3,0.1

Type RM Length L Ch R = 1,17273,667,667,667
BEGIN DESCRIPTION:
LEWELLYN CREEK 16.0
END DESCRIPTION:
XS GIS Cut Line= 3
      2905625.00      6954775.00      2906425.00      6953975.00
      2906900.46      6953215.76
#Sta/Elev= 30
  3903.9  380.68  4062.0  370.88  4131.6  366.97  4271.6  360.97  4370.5  359.12
  4497.9  358.53  4594.3  355.75  4752.4  347.91  4793.9  347.10  4865.6  340.63
  4978.7  340.31  4986.7  338.22  4987.2  337.42  4999.1  338.22  5007.0  340.70
  5064.2  340.23  5241.2  344.47  5317.8  347.10  5593.4  356.26  5645.3  355.37
  5718.4  358.69  5754.9  362.62  5766.8  363.23  5776.1  360.95  5803.2  362.40
  5818.6  361.21  5839.8  369.19  5907.6  379.05  5928.2  382.51  5931.1  384.44
#Mann=11,-1,0
  3903.9    0.16       0  4062.0    0.12       0  4131.6    0.16       0
  4370.5    0.12       0  4594.3    0.16       0  4752.4    0.12       0
  4986.7    0.07       0  4999.1    0.12       0  5241.2    0.16       0
  5754.9    0.05       0  5907.6    0.16       0
Bank Sta=4793.9,5317.8
Exp/Cntr=0.3,0.1

Type RM Length L Ch R = 1,16606,544,544,544
BEGIN DESCRIPTION:
LEWELLYN CREEK 15.0
END DESCRIPTION:
XS GIS Cut Line= 3
      2906874.99      6955025.04      2906975.00      6954275.00
      2907075.01      6953674.96
#Sta/Elev= 30
  4227.7  374.80  4389.2  365.02  4540.5  357.96  4640.1  357.37  4714.0  355.44
  4791.4  352.75  4864.9  346.29  4883.5  343.05  4904.3  341.16  4974.3  338.63
  4975.7  337.32  4976.2  336.52  4988.1  337.32  5012.3  341.94  5024.9  339.51
  5035.1  339.16  5095.9  339.35  5159.6  341.71  5217.6  345.73  5248.6  346.29
  5255.6  350.19  5268.2  354.10  5298.7  361.13  5410.2  376.63  5438.1  381.22
  5443.1  383.04  5460.9  384.97  5504.0  387.23  5542.0  386.69  5592.7  382.45
#Mann=6,-1,0
  4227.7    0.05       0  4714.0    0.16       0  4904.3    0.12       0
  4975.7    0.07       0  4988.1    0.12       0  5159.6    0.16       0
Bank Sta=4864.9,5248.6
Exp/Cntr=0.3,0.1

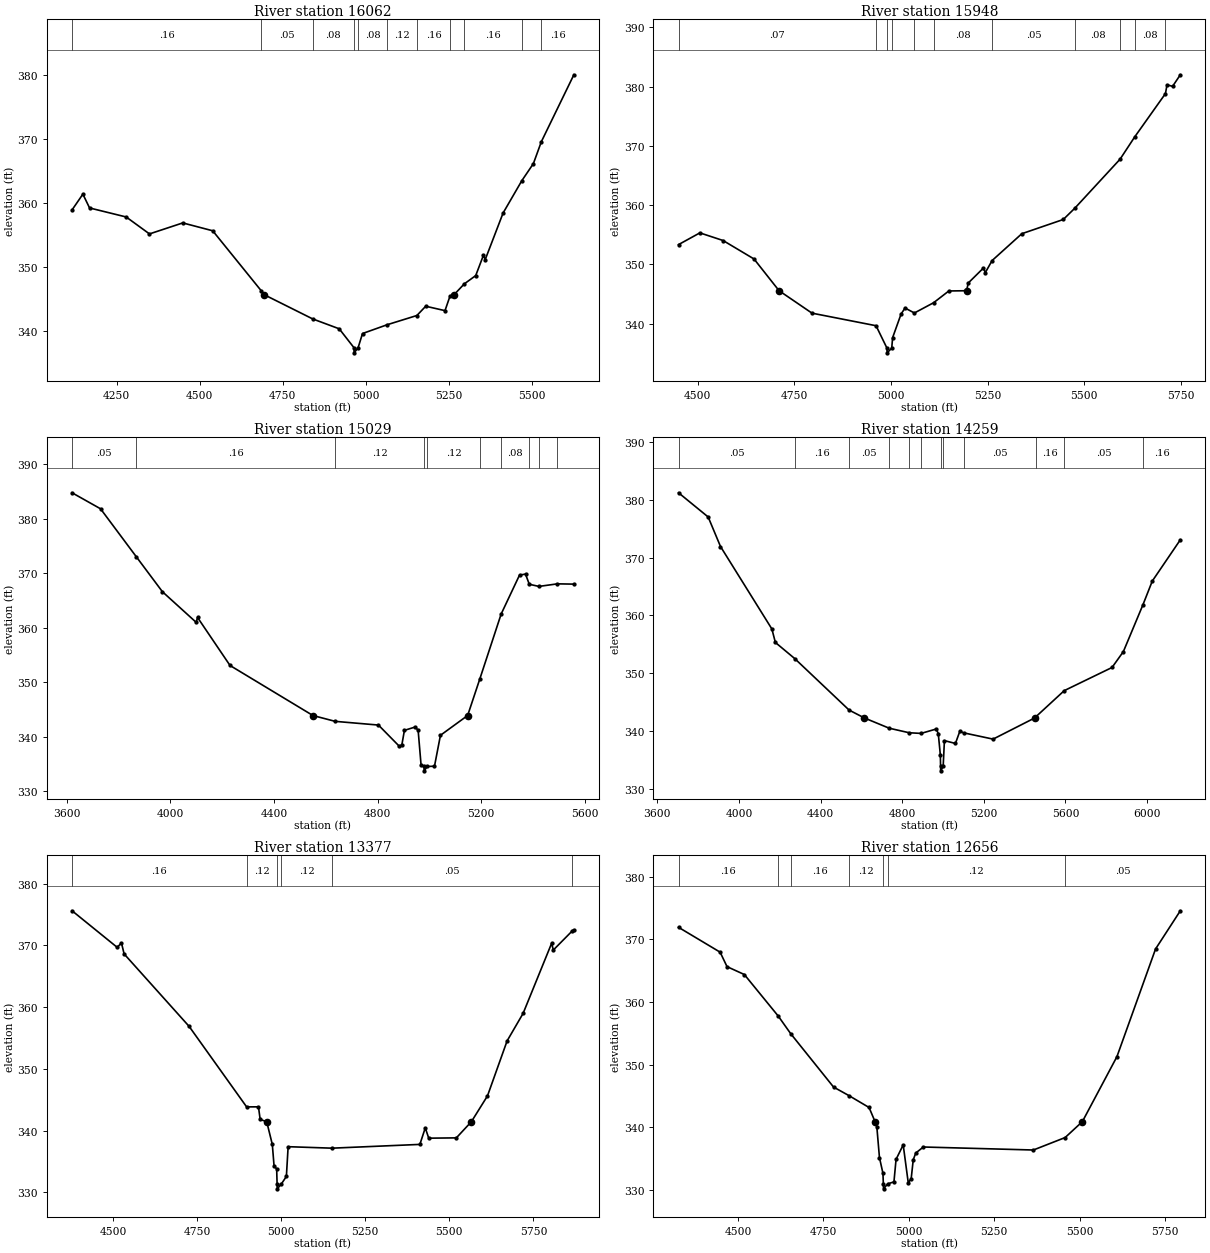
Type RM Length L Ch R = 1,16062,114,114,114
BEGIN DESCRIPTION:
Mapping XS ee33c576
END DESCRIPTION:
XS GIS Cut Line= 3
      2907376.59      6955277.56      2907444.30      6954371.31
      2907199.91      6953820.14
#Sta/Elev= 30
  4115.7  358.94  4148.3  361.40  4168.4  359.24  4278.7  357.83  4348.9  355.18
  4449.2  356.90  4539.4  355.67  4686.2  346.25  4694.2  345.68  4840.8  341.88
  4920.5  340.34  4965.0  337.38  4965.5  336.58  4977.4  337.38  4990.7  339.60
  5065.2  340.98  5154.5  342.42  5181.1  343.87  5239.2  343.18  5254.3  345.46
  5266.6  345.68  5297.4  347.37  5331.7  348.66  5354.9  351.83  5360.4  351.17
  5414.2  358.45  5470.7  363.51  5505.5  366.18  5529.5  369.61  5627.4  380.07
#Mann=11,-1,0
  4115.7    0.16       0  4686.2    0.05       0  4840.8    0.08       0
  4965.0    0.07       0  4977.4    0.08       0  5065.2    0.12       0
  5154.5    0.16       0  5254.3    0.05       0  5297.4    0.16       0
  5470.7    0.08       0  5529.5    0.16       0
Bank Sta=4694.2,5266.6
Exp/Cntr=0.3,0.1

Type RM Length L Ch R = 1,15948,919,919,919
BEGIN DESCRIPTION:
Mapping XS 6426f719
END DESCRIPTION:
XS GIS Cut Line= 4
      2907543.26      6954970.24      2907548.47      6954412.97
      2907470.34      6954043.18      2907277.61      6953735.86
#Sta/Elev= 30
  4450.4  353.33  4505.6  355.31  4565.6  354.02  4645.7  350.90  4710.5  345.54
  4795.7  341.75  4961.3  339.63  4989.5  335.85  4990.0  335.05  5001.9  335.85
  5004.2  337.62  5026.1  341.61  5036.3  342.62  5060.5  341.78  5110.1  343.51
  5149.6  345.50  5195.5  345.54  5199.8  346.84  5238.9  349.36  5244.0  348.61
  5261.6  350.64  5338.4  355.17  5445.6  357.57  5475.4  359.47  5592.6  367.76
  5630.4  371.52  5709.9  378.83  5714.0  380.31  5728.4  380.06  5748.4  382.01
#Mann=11,-1,0
  4450.4    0.07       0  4961.3    0.12       0  4989.5    0.07       0
  5001.9    0.12       0  5060.5    0.05       0  5110.1    0.08       0
  5261.6    0.05       0  5475.4    0.08       0  5592.6    0.16       0
  5630.4    0.08       0  5709.9    0.05       0
Bank Sta=4710.5,5195.5
Exp/Cntr=0.3,0.1

Type RM Length L Ch R = 1,15029,770,770,770
BEGIN DESCRIPTION:
LEWELLYN CREEK 13.0
END DESCRIPTION:
XS GIS Cut Line= 3
      2908123.12      6955704.65      2908225.00      6954375.00
      2907975.00      6953825.00
#Sta/Elev= 30
  3620.3  384.75  3730.3  381.81  3867.9  373.04  3969.1  366.60  4099.7  360.97
  4104.7  361.88  4230.3  353.06  4550.4  343.88  4636.3  342.81  4803.4  342.13
  4883.5  338.26  4893.7  338.47  4903.7  341.16  4943.8  341.75  4956.6  341.22
  4968.1  334.73  4979.4  334.53  4979.9  333.73  4992.1  334.53  5019.8  334.58
  5042.8  340.25  5147.8  343.88  5195.4  350.67  5277.3  362.51  5348.2  369.65
  5371.3  369.83  5385.9  367.96  5423.1  367.57  5494.6  368.04  5558.0  367.99
#Mann=10,-1,0
  3620.3    0.05       0  3867.9    0.16       0  4636.3    0.12       0
  4979.4    0.07       0  4992.1    0.12       0  5195.4    0.16       0
  5277.3    0.08       0  5385.9    0.05       0  5423.1     0.1       0
  5494.6    0.16       0
Bank Sta=4550.4,5147.8
Exp/Cntr=0.3,0.1

Type RM Length L Ch R = 1,14259,882,882,882
BEGIN DESCRIPTION:
LEWELLYN CREEK 12.0
END DESCRIPTION:
XS GIS Cut Line= 3
      2908574.50      6955609.19      2908725.00      6954325.00
      2908322.76      6953230.66
#Sta/Elev= 30
  3703.8  381.22  3849.0  377.03  3909.4  371.92  4161.1  357.65  4178.4  355.31
  4273.2  352.52  4539.5  343.61  4614.8  342.24  4736.0  340.47  4834.3  339.68
  4892.2  339.57  4966.6  340.33  4976.6  339.54  4986.7  335.85  4987.9  333.89
  4988.4  333.09  5000.6  333.89  5006.7  338.32  5060.7  337.83  5082.0  339.92
  5101.7  339.66  5245.2  338.58  5448.9  342.24  5453.9  342.42  5593.8  346.97
  5828.0  350.98  5883.6  353.73  5979.7  361.85  6025.3  365.94  6162.7  373.08
#Mann=12,-1,0
  3703.8    0.05       0  4273.2    0.16       0  4539.5    0.05       0
  4736.0    0.07       0  4834.3    0.05       0  4892.2    0.12       0
  4987.9    0.07       0  5000.6    0.12       0  5101.7    0.05       0
  5453.9    0.16       0  5593.8    0.05       0  5979.7    0.16       0
Bank Sta=4614.8,5448.9
Exp/Cntr=0.3,0.1

Type RM Length L Ch R = 1,13377,721,721,721
BEGIN DESCRIPTION:
LEWELLYN CREEK 11.0
END DESCRIPTION:
XS GIS Cut Line= 3
      2909375.01      6955175.04      2909225.00      6954575.00
      2909025.01      6953725.02
#Sta/Elev= 30
  4378.4  375.62  4512.4  369.70  4525.3  370.40  4533.1  368.63  4726.3  356.89
  4897.3  343.84  4932.5  343.85  4937.6  341.80  4957.0  341.45  4973.7  337.75
  4978.9  334.25  4986.6  333.80  4987.9  331.36  4988.4  330.56  5000.7  331.36
  5015.5  332.57  5020.7  337.39  5151.2  337.15  5412.3  337.76  5428.4  340.44
  5438.7  338.77  5520.8  338.82  5565.6  341.45  5613.3  345.62  5671.7  354.54
  5719.2  358.99  5804.0  370.35  5809.1  369.26  5865.4  372.36  5870.1  372.50
#Mann=6,-1,0
  4378.4    0.16       0  4897.3    0.12       0  4987.9    0.07       0
  5000.7    0.12       0  5151.2    0.05       0  5865.4    0.08       0
Bank Sta=4957,5565.6
Exp/Cntr=0.3,0.1

Type RM Length L Ch R = 1,12656,868,868,868
BEGIN DESCRIPTION:
LEWELLYN CREEK 10.0
END DESCRIPTION:
XS GIS Cut Line= 3
      2909475.00      6955025.02      2909575.00      6954425.00
      2909075.02      6953725.02
#Sta/Elev= 30
  4325.9  371.92  4447.6  367.95  4467.8  365.64  4518.5  364.38  4617.8  357.74
  4654.1  354.94  4779.6  346.41  4824.2  345.06  4883.5  343.15  4901.0  340.89
  4906.3  340.01  4913.9  335.15  4924.1  332.65  4925.3  330.96  4925.8  330.16
  4938.1  330.96  4956.3  331.27  4962.5  334.87  4983.4  337.18  4998.1  331.15
  5006.7  331.75  5012.8  334.81  5020.2  335.88  5042.3  336.84  5364.3  336.36
  5457.3  338.35  5507.7  340.89  5608.9  351.27  5721.9  368.46  5794.4  374.56
#Mann=7,-1,0
  4325.9    0.16       0  4617.8    0.05       0  4654.1    0.16       0
  4824.2    0.12       0  4925.3    0.07       0  4938.1    0.12       0
  5457.3    0.05       0
Bank Sta=4901,5507.7
Exp/Cntr=0.3,0.1