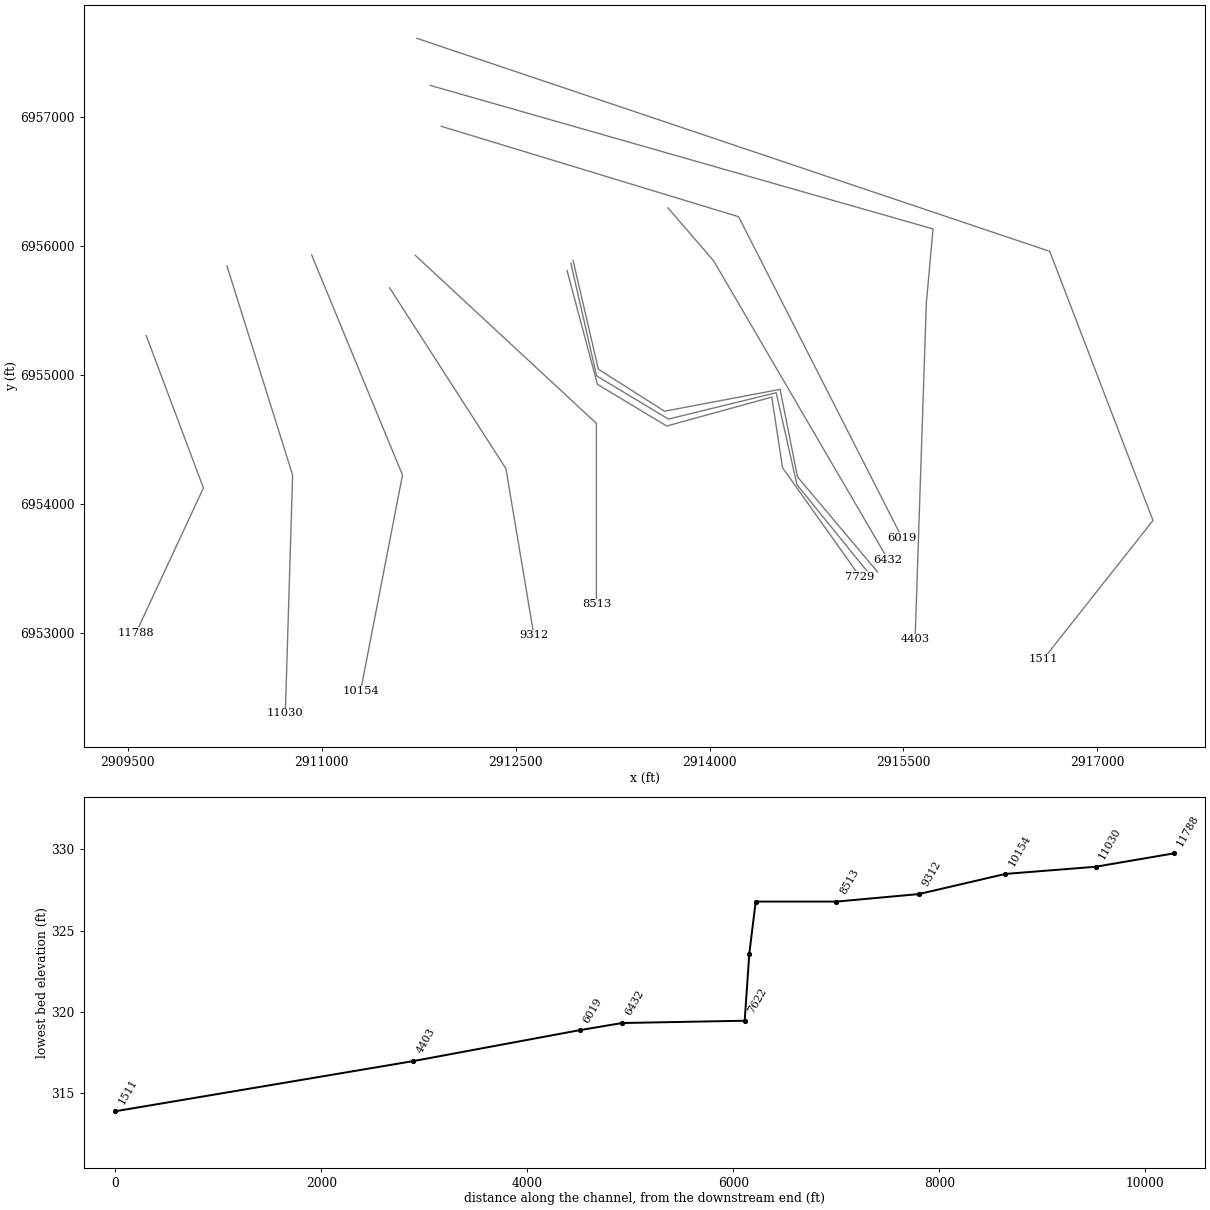
HEC-RAS study LEWELLYN CREEK.prj: LEWELLYN CREEK Base Level Engineering

--- LEWELLYN CREEK.g01 (geometry) --- (continued)

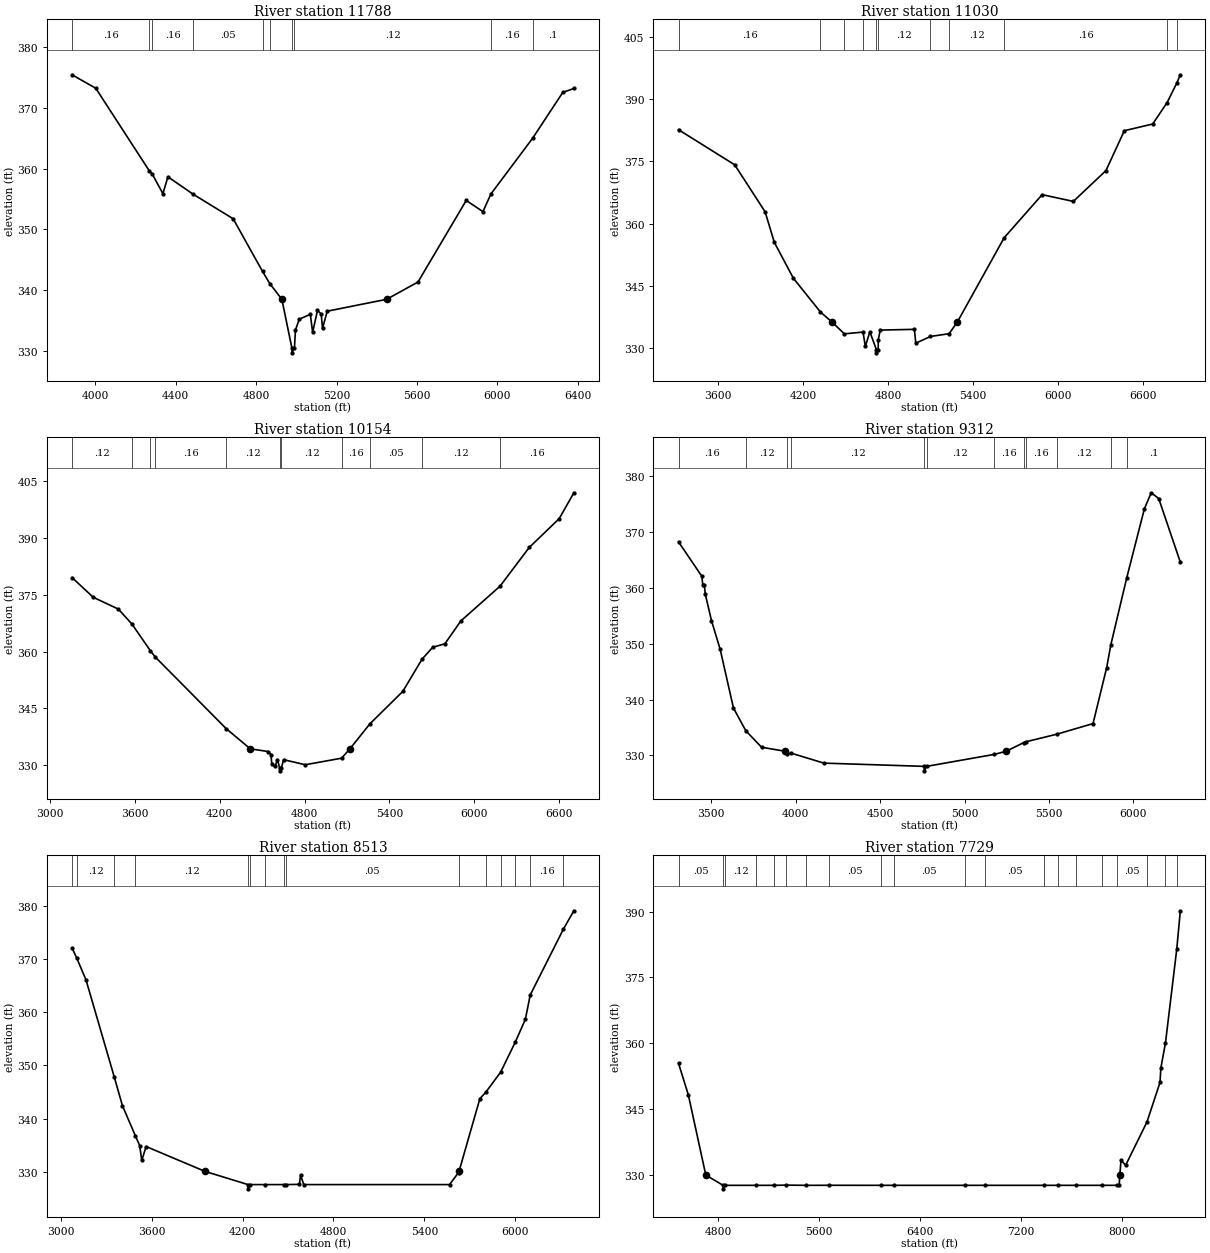
Type RM Length L Ch R = 1,11788,758,758,758
BEGIN DESCRIPTION:
LEWELLYN CREEK 9.0
END DESCRIPTION:
XS GIS Cut Line= 3
      2909642.23      6955305.29      2910084.92      6954124.78
      2909564.08      6953004.96
#Sta/Elev= 30
  3884.7  375.40  4002.5  373.19  4269.4  359.60  4282.6  359.16  4336.5  355.88
  4361.4  358.65  4485.5  355.82  4686.0  351.76  4832.2  343.11  4868.4  341.11
  4928.1  338.54  4978.0  330.55  4978.5  329.75  4990.8  330.55  4995.7  333.47
  5014.6  335.27  5069.8  336.08  5081.2  333.11  5105.4  336.71  5123.9  336.12
  5130.3  333.78  5154.0  336.59  5449.5  338.54  5605.3  341.38  5845.2  354.77
  5928.3  352.93  5967.9  355.83  6175.4  364.98  6325.3  372.50  6380.5  373.15
#Mann=10,-1,0
  3884.7    0.16       0  4269.4    0.12       0  4282.6    0.16       0
  4485.5    0.05       0  4832.2    0.16       0  4868.4    0.12       0
  4978.0    0.07       0  4990.8    0.12       0  5967.9    0.16       0
  6175.4     0.1       0
Bank Sta=4928.1,5449.5
Exp/Cntr=0.3,0.1

Type RM Length L Ch R = 1,11030,876,876,876
BEGIN DESCRIPTION:
LEWELLYN CREEK 8.0
END DESCRIPTION:
XS GIS Cut Line= 3
      2910267.21      6955843.56      2910775.00      6954225.00
      2910718.61      6952380.00
#Sta/Elev= 30
  3319.4  382.59  3716.1  374.14  3930.5  362.85  3995.4  355.51  4130.3  346.85
  4321.5  338.74  4400.9  336.39  4490.0  333.50  4621.3  333.92  4638.4  330.51
  4670.0  333.98  4715.8  329.73  4716.3  328.93  4728.8  329.73  4729.7  332.11
  4743.2  334.40  4984.3  334.58  4994.3  331.25  5097.7  332.87  5229.3  333.53
  5288.4  336.39  5618.2  356.62  5886.1  366.97  6106.3  365.35  6336.4  372.75
  6466.4  382.35  6666.5  383.96  6768.1  389.10  6836.4  393.80  6861.6  395.80
#Mann=11,-1,0
  3319.4    0.16       0  4321.5    0.05       0  4490.0    0.16       0
  4621.3    0.12       0  4715.8    0.07       0  4728.8    0.12       0
  5097.7    0.07       0  5229.3    0.12       0  5618.2    0.16       0
  6768.1    0.12       0  6836.4    0.16       0
Bank Sta=4400.9,5288.4
Exp/Cntr=0.3,0.1

Type RM Length L Ch R = 1,10154,842,842,842
BEGIN DESCRIPTION:
LEWELLYN CREEK 7.0
END DESCRIPTION:
XS GIS Cut Line= 3
      2910922.58      6955927.76      2911625.00      6954225.00
      2911300.00      6952549.99
#Sta/Elev= 30
  3156.2  379.52  3306.0  374.32  3483.7  371.20  3579.8  367.24  3710.1  360.20
  3743.4  358.59  4245.3  339.66  4416.5  334.30  4544.2  333.58  4562.8  332.80
  4568.2  330.30  4592.1  329.69  4608.7  331.45  4623.8  329.29  4624.4  328.49
  4636.9  329.29  4652.0  331.44  4805.2  330.10  5061.6  331.83  5121.0  334.30
  5261.9  340.89  5494.5  349.45  5630.9  357.98  5706.5  361.12  5792.7  362.05
  5904.8  368.06  6182.1  377.24  6389.0  387.49  6601.0  395.10  6704.4  401.92
#Mann=11,-1,0
  3156.2    0.12       0  3579.8    0.16       0  3710.1    0.12       0
  3743.4    0.16       0  4245.3    0.12       0  4623.8    0.07       0
  4636.9    0.12       0  5061.6    0.16       0  5261.9    0.05       0
  5630.9    0.12       0  6182.1    0.16       0
Bank Sta=4416.5,5121
Exp/Cntr=0.3,0.1

Type RM Length L Ch R = 1,9312,799,799,799
BEGIN DESCRIPTION:
LEWELLYN CREEK 6.0
END DESCRIPTION:
XS GIS Cut Line= 3
      2911524.97      6955675.04      2912425.00      6954275.00
      2912641.35      6952985.00
#Sta/Elev= 30
  3305.9  368.20  3443.7  362.06  3449.6  360.53  3458.8  360.47  3464.8  358.79
  3501.1  354.11  3552.6  348.97  3631.2  338.49  3704.2  334.43  3797.7  331.47
  3937.6  330.75  3949.4  330.31  3974.4  330.40  4166.8  328.63  4761.3  328.05
  4762.1  327.25  4775.1  328.05  5176.0  330.19  5246.8  330.75  5350.0  332.29
  5361.2  332.43  5545.0  333.79  5761.2  335.70  5842.1  345.72  5867.0  349.84
  5960.3  361.70  6065.4  374.12  6105.9  376.98  6150.4  375.95  6278.3  364.57
#Mann=12,-1,0
  3305.9    0.16       0  3704.2    0.12       0  3949.4    0.16       0
  3974.4    0.12       0  4761.3    0.07       0  4775.1    0.12       0
  5176.0    0.16       0  5350.0    0.05       0  5361.2    0.16       0
  5545.0    0.12       0  5867.0    0.16       0  5960.3     0.1       0
Bank Sta=3937.6,5246.8
Exp/Cntr=0.3,0.1

Type RM Length L Ch R = 1,8513,784,784,784
BEGIN DESCRIPTION:
LEWELLYN CREEK 5.0
END DESCRIPTION:
XS GIS Cut Line= 3
      2911725.02      6955924.98      2913125.00      6954625.00
      2913125.00      6953224.97
#Sta/Elev= 30
  3075.4  372.05  3107.1  370.09  3167.5  366.03  3353.3  347.85  3407.9  342.39
  3493.6  336.72  3521.2  334.93  3535.4  332.12  3563.8  334.74  3951.4  330.08
  4236.0  327.59  4236.8  326.79  4249.8  327.59  4350.0  327.59  4475.8  327.59
  4488.1  327.59  4575.7  327.63  4582.5  329.39  4603.8  327.59  5565.9  327.59
  5624.9  329.85  5628.5  330.08  5765.9  343.74  5804.4  344.92  5902.3  348.68
  6000.2  354.40  6065.9  358.64  6098.0  363.21  6317.2  375.60  6385.9  379.03
#Mann=15,-1,0
  3075.4    0.16       0  3107.1    0.12       0  3353.3    0.16       0
  3493.6    0.12       0  4236.0   0.033       0  4249.8    0.12       0
  4350.0    0.05       0  4475.8    0.07       0  4488.1    0.05       0
  5624.9    0.12       0  5804.4    0.05       0  5902.3    0.08       0
  6000.2    0.05       0  6098.0    0.16       0  6317.2     0.1       0
Bank Sta=3951.4,5628.5
Exp/Cntr=0.3,0.1

Type RM Length L Ch R = 1,7729,62,62,62
BEGIN DESCRIPTION:
Mapping XS 2e641e84
END DESCRIPTION:
XS GIS Cut Line= 6
      2912898.41      6955807.67      2913132.77      6954927.50
      2913669.23      6954604.58      2914481.73      6954828.54
      2914565.06      6954281.66      2915163.27      6953438.97
#Sta/Elev= 30
  4484.7  355.39  4562.2  348.23  4700.7  329.93  4837.7  327.59  4838.7  326.79
  4852.1  327.59  5101.2  327.59  5238.7  327.59  5340.0  327.64  5492.6  327.59
  5679.8  327.60  6089.9  327.59  6189.7  327.59  6752.1  327.59  6913.9  327.59
  7379.9  327.59  7488.3  327.59  7637.9  327.59  7842.5  327.59  7960.6  327.59
  7976.7  327.60  7981.6  329.93  7991.5  333.38  8027.2  332.13  8196.7  342.03
  8300.3  351.06  8306.6  354.28  8343.7  360.10  8432.9  381.43  8461.2  390.18
#Mann=20,-1,0
  4484.7    0.05       0  4837.7   0.033       0  4852.1    0.12       0
  5101.2    0.12       0  5238.7    0.07       0  5340.0    0.05       0
  5492.6    0.12       0  5679.8    0.05       0  6089.9    0.12       0
  6189.7    0.05       0  6752.1    0.12       0  6913.9    0.05       0
  7379.9    0.16       0  7488.3    0.05       0  7637.9    0.16       0
  7842.5    0.12       0  7960.6    0.05       0  8196.7    0.16       0
  8343.7    0.12       0  8432.9    0.16       0
Bank Sta=4700.7,7981.6
Exp/Cntr=0.3,0.1

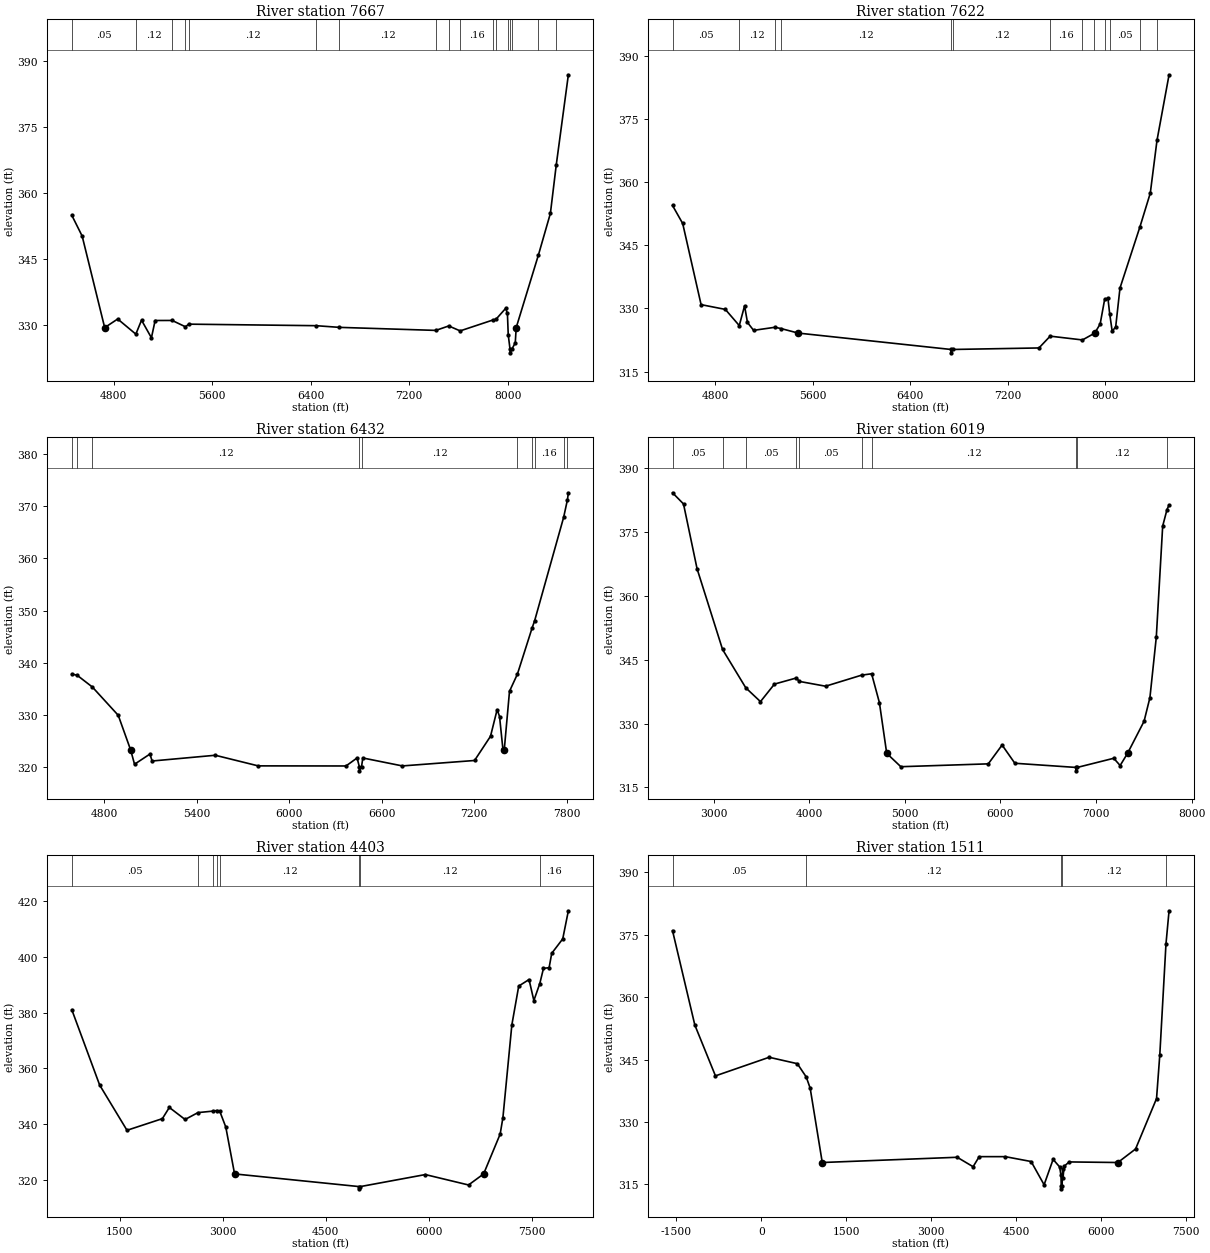
Type RM Length L Ch R = 1,7667,45,45,45
BEGIN DESCRIPTION:
Mapping XS 311f940a
END DESCRIPTION:
XS GIS Cut Line= 6
      2912927.25      6955865.02      2913126.91      6954992.60
      2913682.47      6954658.40      2914515.80      6954862.39
      2914676.39      6954150.59      2915230.97      6953466.06
#Sta/Elev= 30
  4459.7  354.86  4543.8  350.14  4726.7  329.33  4832.4  331.29  4979.7  327.85
  5026.0  331.02  5106.3  327.02  5136.4  330.95  5274.7  330.96  5382.8  329.52
  5408.8  330.12  6444.5  329.77  6632.9  329.39  7415.8  328.70  7520.8  329.71
  7613.6  328.59  7879.3  331.06  7904.3  331.22  7982.9  333.70  7997.3  332.58
  8004.1  327.68  8018.7  324.40  8019.8  323.60  8033.1  324.40  8061.2  325.89
  8068.7  329.33  8249.6  345.88  8346.4  355.30  8394.0  366.31  8492.3  386.80
#Mann=17,-1,0
  4459.7    0.05       0  4979.7    0.12       0  5274.7    0.07       0
  5382.8    0.05       0  5408.8    0.12       0  6444.5    0.05       0
  6632.9    0.12       0  7415.8    0.16       0  7520.8    0.05       0
  7613.6    0.16       0  7879.3    0.12       0  7904.3    0.16       0
  8004.1    0.05       0  8018.7    0.07       0  8033.1    0.05       0
  8249.6    0.16       0  8394.0    0.12       0
Bank Sta=4726.7,8068.7
Exp/Cntr=0.3,0.1

Type RM Length L Ch R = 1,7622,1190,1190,1190
BEGIN DESCRIPTION:
Mapping XS 167830b8
END DESCRIPTION:
XS GIS Cut Line= 6
      2912944.60      6955886.73      2913139.93      6955044.69
      2913652.08      6954719.16      2914546.18      6954888.44
      2914680.73      6954211.35      2915300.70      6953474.34
#Sta/Elev= 30
  4449.0  354.45  4532.6  350.17  4683.6  330.91  4882.6  329.78  4996.9  325.94
  5040.4  330.62  5064.3  326.68  5114.4  324.81  5290.9  325.54  5342.7  325.21
  5480.2  324.16  6734.8  320.27  6735.9  319.47  6749.2  320.27  7456.9  320.63
  7548.8  323.43  7813.7  322.53  7912.7  324.12  7914.7  324.16  7959.1  326.31
  7996.0  332.16  8022.9  332.44  8037.3  328.75  8058.0  324.58  8086.7  325.65
  8121.9  334.85  8286.5  349.45  8370.7  357.39  8425.7  369.91  8524.7  385.47
#Mann=13,-1,0
  4449.0    0.05       0  4996.9    0.12       0  5290.9    0.07       0
  5342.7    0.12       0  6734.8    0.07       0  6749.2    0.12       0
  7548.8    0.16       0  7813.7    0.12       0  7912.7    0.16       0
  7996.0    0.12       0  8037.3    0.05       0  8286.5    0.16       0
  8425.7    0.12       0
Bank Sta=5480.2,7914.7
Exp/Cntr=0.3,0.1

Type RM Length L Ch R = 1,6432,413,413,413
BEGIN DESCRIPTION:
Mapping XS 645081ce
END DESCRIPTION:
XS GIS Cut Line= 3
      2913679.01      6956293.23      2914033.16      6955881.78
      2915381.88      6953569.68
#Sta/Elev= 30
  4590.5  337.86  4625.7  337.60  4723.9  335.36  4891.6  329.95  4971.9  323.33
  4997.2  320.59  5097.0  322.54  5111.3  321.21  5520.8  322.31  5798.6  320.28
  6368.4  320.26  6440.3  321.80  6454.6  320.13  6455.7  319.33  6469.1  320.13
  6477.5  321.79  6733.9  320.27  7201.9  321.31  7305.3  325.94  7348.3  331.04
  7364.0  329.72  7385.5  323.51  7394.4  323.33  7428.5  334.55  7479.6  337.82
  7574.7  346.63  7591.4  348.04  7779.4  367.81  7804.4  371.22  7810.1  372.52
#Mann=10,-1,0
  4590.5    0.05       0  4625.7    0.16       0  4723.9    0.12       0
  6454.6    0.07       0  6469.1    0.12       0  7479.6    0.05       0
  7574.7    0.12       0  7591.4    0.16       0  7779.4    0.12       0
  7804.4    0.16       0
Bank Sta=4971.9,7394.4
Exp/Cntr=0.3,0.1

Type RM Length L Ch R = 1,6019,1616,1616,1616
BEGIN DESCRIPTION:
LEWELLYN CREEK 2.0
END DESCRIPTION:
XS GIS Cut Line= 3
      2911924.98      6956925.01      2914225.00      6956225.00
      2915489.65      6953739.30
#Sta/Elev= 30
  2570.5  384.18  2685.5  381.56  2827.4  366.34  3093.9  347.39  3337.0  338.38
  3490.4  335.14  3636.7  339.26  3865.2  340.69  3896.7  339.89  4171.3  338.76
  4548.6  341.36  4652.8  341.68  4734.3  334.90  4810.7  323.00  4958.3  319.86
  5872.9  320.53  6017.4  324.95  6150.8  320.67  6788.7  319.69  6789.8  318.89
  6803.2  319.69  7185.0  321.84  7251.9  320.14  7329.5  323.00  7502.2  330.53
  7563.4  336.08  7630.1  350.27  7696.9  376.37  7742.1  380.24  7763.6  381.32
#Mann=10,-1,0
  2570.5    0.05       0  3093.9    0.16       0  3337.0    0.05       0
  3865.2    0.12       0  3896.7    0.05       0  4548.6    0.16       0
  4652.8    0.12       0  6788.7    0.07       0  6803.2    0.12       0
  7742.1    0.16       0
Bank Sta=4810.7,7329.5
Exp/Cntr=0.3,0.1

Type RM Length L Ch R = 1,4403,2892,2892,2892
BEGIN DESCRIPTION:
Mapping XS fb34a407
END DESCRIPTION:
XS GIS Cut Line= 4
      2911840.54      6957241.40      2915729.46      6956130.28
      2915677.37      6955557.36      2915590.57      6952953.22
#Sta/Elev= 30
   805.6  380.99  1210.9  354.07  1608.7  337.91  2123.5  342.07  2224.7  346.07
  2453.7  341.77  2641.4  344.23  2853.6  344.75  2915.1  344.98  2957.3  344.79
  3046.3  339.07  3174.1  322.32  4988.7  317.79  4989.9  316.99  5003.4  317.79
  5950.0  322.09  6578.4  318.37  6797.9  322.32  7038.7  336.56  7078.7  342.43
  7208.8  375.57  7308.8  389.45  7458.9  391.78  7528.9  384.27  7615.3  390.34
  7669.0  395.76  7751.0  396.03  7789.1  401.15  7949.2  406.31  8031.0  416.35
#Mann=8,-1,0
   805.6    0.05       0  2641.4    0.16       0  2853.6    0.12       0
  2915.1    0.16       0  2957.3    0.12       0  4988.7    0.07       0
  5003.4    0.12       0  7615.3    0.16       0
Bank Sta=3174.1,6797.9
Exp/Cntr=0.3,0.1

Type RM Length L Ch R = 1,1511,0,0,0
BEGIN DESCRIPTION:
LEWELLYN CREEK 1.0
END DESCRIPTION:
XS GIS Cut Line= 4
      2911736.38      6957605.98      2916632.23      6955956.67
      2917430.84      6953873.33      2916581.34      6952798.45
#Sta/Elev= 30
 -1568.9  375.99 -1174.5  353.28  -810.6  341.07   137.6  345.54   635.0  344.00
   792.1  340.81   861.8  338.11  1075.3  320.24  3457.8  321.50  3738.3  319.23
  3846.6  321.65  4305.9  321.65  4762.8  320.48  4992.3  314.89  5151.1  320.99
  5265.9  319.19  5290.6  317.14  5294.4  314.71  5295.7  313.91  5309.4  314.71
  5320.6  318.61  5325.9  316.46  5344.7  319.33  5435.4  320.38  6294.5  320.24
  6607.1  323.49  6977.4  335.61  7035.1  346.16  7143.9  372.78  7198.5  380.76
#Mann=5,-1,0
 -1568.9    0.05       0   792.1    0.12       0  5294.4    0.07       0
  5309.4    0.12       0  7143.9    0.16       0
Bank Sta=1075.3,6294.5
Exp/Cntr=0.3,0.1

Chan Stop Cuts=-1