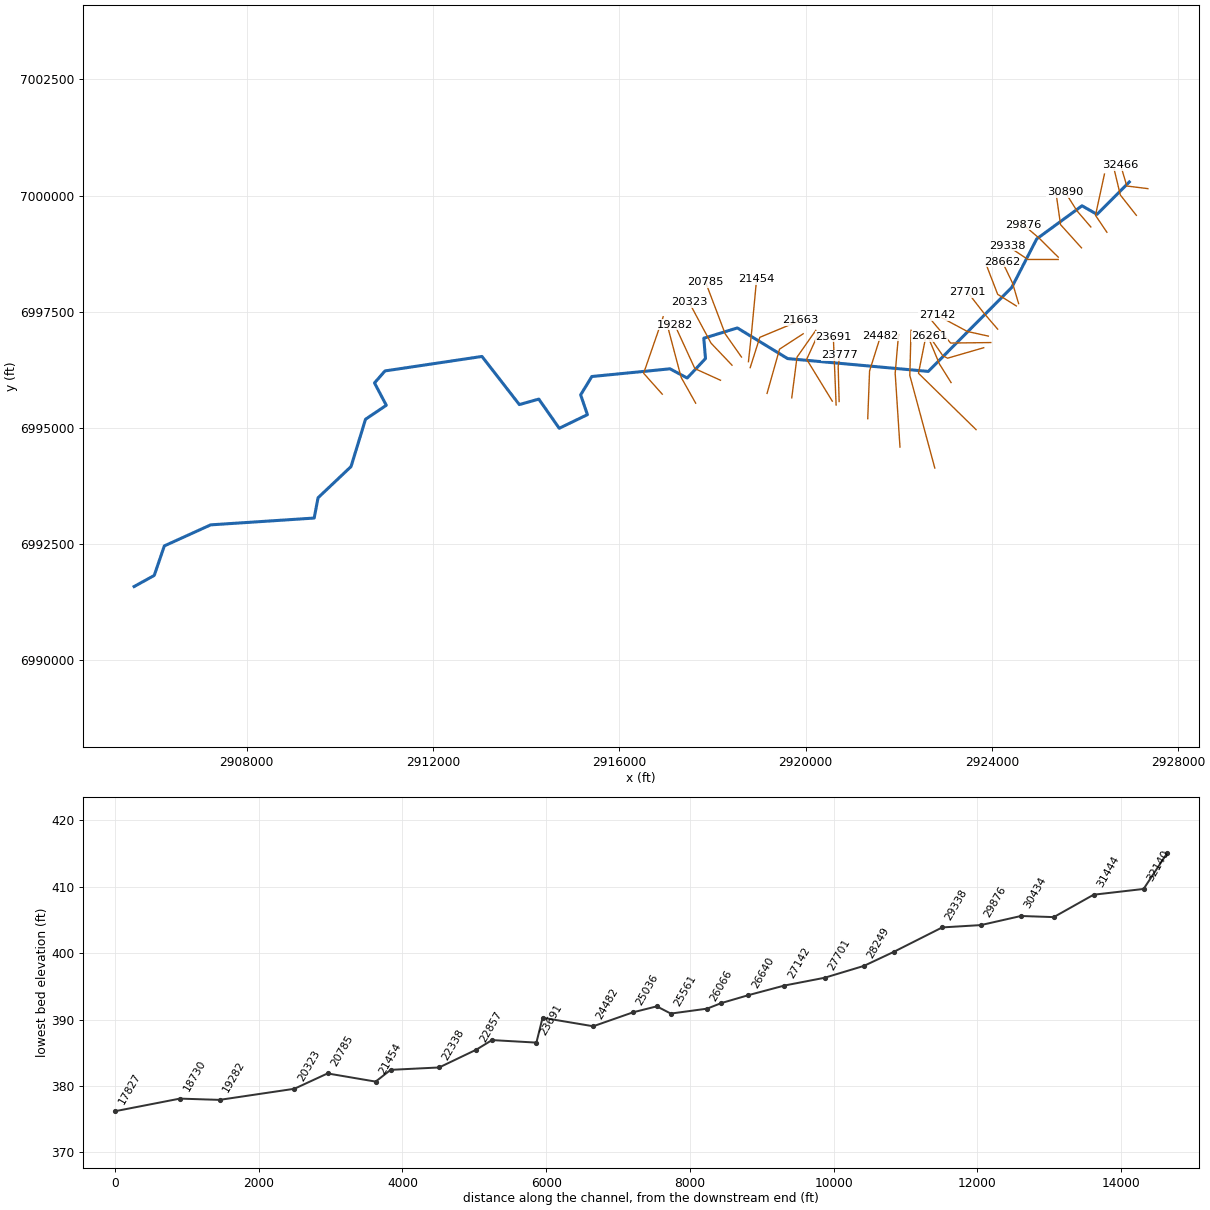
--- LITTLE DRY CREEK.prj (project) ---

Proj Title=LITTLE DRY CREEK Base Level Engineering
Current Plan=p01
Default Exp/Contr=0.3,0.1
English Units
Geom File=g01
Flow File=f01
Plan File=p01
BEGIN DESCRIPTION:
LITTLE DRY CREEK
END DESCRIPTION:

--- LITTLE DRY CREEK.p01 (plan) ---

Plan Title=Multiple Run
Short Identifier=Multiple
Geom File=g01
Flow File=f01
Subcritical Flow
K Sum by GR= 0
Std Step Tol= 0.01
Critical Tol= 0.01
Num of Std Step Trials= 20
Max Error Tol= 0.3
Flow Tol Ratio= 0.001
Split Flow NTrial= 30
Split Flow Tol= 0.02
Split Flow Ratio= 0.02
Log Output Level= 0
Friction Slope Method= 1
Unsteady Friction Slope Method= 2
Unsteady Bridges Friction Slope Method= 1
Parabolic Critical Depth
Global Vel Dist=  1 , 1 , 1
Global Log Level= 0
CheckData=True
Encroach Param= -1, 0, 0, 0
BEGIN DESCRIPTION:
Multiple Run
END DESCRIPTION:

--- LITTLE DRY CREEK.f01 (steady flow) ---

Flow Title=Multiple
Program Version=5.07
Number of Profiles= 7
Profile Names=10-year,25-year,50-year,1pct_min,100-year,1pct_plu,500-year
River Rch & RM=LITTLE DRY CREEK,Reach-1         ,32466
     387     503     595     350     698    1393     962
River Rch & RM=LITTLE DRY CREEK,Reach-1         ,32140
     628     840    1011     605    1207    2408    1722
River Rch & RM=LITTLE DRY CREEK,Reach-1         ,30890
     855    1163    1416     856    1707    3407    2487
River Rch & RM=LITTLE DRY CREEK,Reach-1         ,29876
    1031    1413    1729    1049    2093    4177    3075
River Rch & RM=LITTLE DRY CREEK,Reach-1         ,26066
    1813    2565    3208    1986    3963    7908    6067
River Rch & RM=LITTLE DRY CREEK,Reach-1         ,21454
    2171    3089    3878    2409    4806    9590    7405
River Rch & RM=LITTLE DRY CREEK,Reach-1         ,15252
    2512    3588    4516    2811    5608   11190    8675
River Rch & RM=LITTLE DRY CREEK,Reach-1         ,10785
    2484    3535    4438    2755    5496   10966    8454
River Rch & RM=LITTLE DRY CREEK,Reach-1         ,6668
    2630    3750    4713    2928    5843   11657    9005
River Rch & RM=LITTLE DRY CREEK,Reach-1         ,4039
    2614    3720    4668    2896    5778   11529    8878
Boundary for River Rch & Prof#=LITTLE DRY CREEK,Reach-1         , 1
Up Type= 0
Dn Type= 3
Dn Slope=0.00188
Boundary for River Rch & Prof#=LITTLE DRY CREEK,Reach-1         , 2
Up Type= 0
Dn Type= 3
Dn Slope=0.00188
Boundary for River Rch & Prof#=LITTLE DRY CREEK,Reach-1         , 3
Up Type= 0
Dn Type= 3
Dn Slope=0.00188
Boundary for River Rch & Prof#=LITTLE DRY CREEK,Reach-1         , 4
Up Type= 0
Dn Type= 3
Dn Slope=0.00188
Boundary for River Rch & Prof#=LITTLE DRY CREEK,Reach-1         , 5
Up Type= 0
Dn Type= 3
Dn Slope=0.00188
Boundary for River Rch & Prof#=LITTLE DRY CREEK,Reach-1         , 6
Up Type= 0
Dn Type= 3
Dn Slope=0.00188
Boundary for River Rch & Prof#=LITTLE DRY CREEK,Reach-1         , 7
Up Type= 0
Dn Type= 3
Dn Slope=0.00188
DSS Import GetInterval= 0
DSS Import GetPeak= 0
DSS Import FillOption= 0

--- LITTLE DRY CREEK.g01 (geometry) ---

Geom Title=Existing Conditions

River Reach=LITTLE DRY CREEK,Reach-1
Reach XY= 30
      2926950.61      7000293.32      2926258.17      6999596.28
      2925935.59      6999780.71      2924962.49      6999066.95
      2924427.68      6998024.00      2922634.90      6996215.00
      2919615.19      6996491.58      2918536.62      6997150.95
      2917816.18      6996929.58      2917852.60      6996492.22
      2917460.05      6996072.80      2917090.71      6996270.99
      2915412.96      6996105.27      2915172.71      6995710.38
      2915318.37      6995284.50      2914712.98      6994990.78
      2914274.72      6995618.93      2913856.52      6995501.25
      2913054.27      6996537.33      2910972.72      6996225.62
      2910747.02      6995966.94      2911000.49      6995486.03
      2910554.31      6995184.82      2910243.55      6994166.59
      2909535.22      6993494.71      2909452.54      6993058.07
      2907230.28      6992911.49      2906235.49      6992458.37
      2906018.82      6991822.95      2905586.53      6991583.37

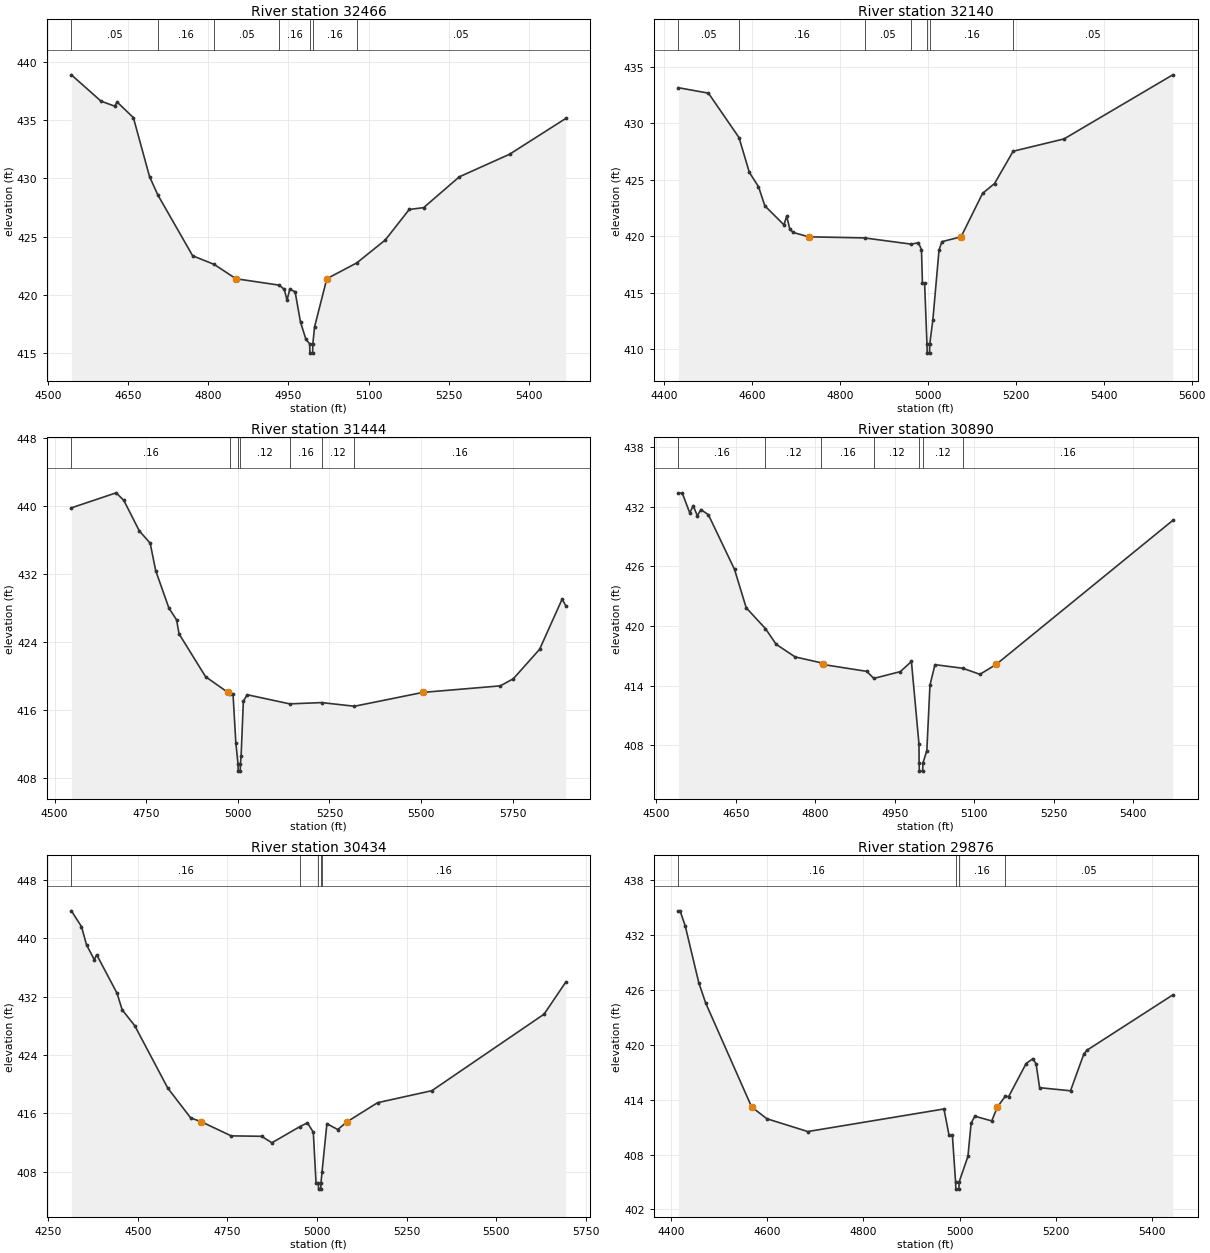
Type RM Length L Ch R = 1,32466,326,326,326
BEGIN DESCRIPTION:
LITTLE DRY CREEK 42.0
END DESCRIPTION:
XS GIS Cut Line= 3
      2927349.98      7000150.00      2926897.70      7000206.53
      2926765.01      7000655.74
#Sta/Elev= 30
  4544.2  438.88  4599.6  436.62  4624.8  436.20  4629.8  436.54  4660.1  435.21
  4690.3  430.15  4705.9  428.57  4770.9  423.36  4811.1  422.62  4851.9  421.39
  4932.9  420.84  4942.3  420.47  4947.3  419.55  4952.4  420.48  4962.4  420.28
  4972.5  417.67  4982.6  416.20  4989.6  415.81  4990.1  415.01  4995.1  415.01
  4995.6  415.81  4998.8  417.26  5021.7  421.39  5077.7  422.75  5130.9  424.71
  5175.7  427.33  5202.7  427.49  5269.3  430.13  5363.4  432.07  5468.4  435.14
#Mann=7,-1,0
  4544.2    0.05       0  4705.9    0.16       0  4811.1    0.05       0
  4932.9    0.16       0  4989.6    0.07       0  4995.6    0.16       0
  5077.7    0.05       0
Bank Sta=4851.9,5021.7
Exp/Cntr=0.3,0.1

Type RM Length L Ch R = 1,32140,696,696,696
BEGIN DESCRIPTION:
Mapping XS d1349152
END DESCRIPTION:
XS GIS Cut Line= 3
      2927101.84      6999575.88      2926758.06      7000013.41
      2926626.11      7000565.53
#Sta/Elev= 30
  4433.0  433.14  4501.3  432.66  4570.8  428.73  4594.3  425.65  4615.1  424.39
  4629.6  422.69  4673.0  421.01  4679.3  421.78  4686.2  420.65  4693.8  420.34
  4728.9  419.95  4856.4  419.85  4962.7  419.30  4978.7  419.43  4985.7  418.82
  4987.9  415.86  4992.8  415.86  4998.2  410.46  4998.7  409.66  5004.0  409.66
  5004.5  410.46  5011.6  412.61  5025.6  418.78  5032.2  419.52  5075.7  419.95
  5124.7  423.80  5151.8  424.66  5194.1  427.52  5309.8  428.61  5557.1  434.28
#Mann=7,-1,0
  4433.0    0.05       0  4570.8    0.16       0  4856.4    0.05       0
  4962.7    0.16       0  4998.2    0.07       0  5004.5    0.16       0
  5194.1    0.05       0
Bank Sta=4728.9,5075.7
Exp/Cntr=0.3,0.1

Type RM Length L Ch R = 1,31444,554,554,554
BEGIN DESCRIPTION:
LITTLE DRY CREEK 41.0
END DESCRIPTION:
XS GIS Cut Line= 3
      2926469.89      6999211.29      2926225.00      6999575.00
      2926417.78      7000464.79
#Sta/Elev= 30
  4545.8  439.79  4667.9  441.56  4688.9  440.67  4731.1  437.08  4760.8  435.63
  4775.8  432.40  4811.8  428.00  4832.8  426.60  4839.6  424.95  4911.9  419.91
  4972.9  418.06  4978.2  417.93  4986.8  417.89  4994.5  412.12  5000.5  409.59
  5001.0  408.79  5006.4  408.79  5006.9  409.59  5008.9  410.62  5015.0  417.01
  5025.2  417.79  5141.4  416.71  5228.8  416.86  5318.1  416.43  5504.7  418.06
  5716.1  418.83  5751.7  419.67  5823.3  423.14  5884.7  429.04  5894.7  428.27
#Mann=7,-1,0
  4545.8    0.16       0  4978.2    0.12       0  5000.5    0.07       0
  5006.9    0.12       0  5141.4    0.16       0  5228.8    0.12       0
  5318.1    0.16       0
Bank Sta=4972.9,5504.7
Exp/Cntr=0.3,0.1

Type RM Length L Ch R = 1,30890,456,456,456
BEGIN DESCRIPTION:
LITTLE DRY CREEK 40.0
END DESCRIPTION:
XS GIS Cut Line= 3
      2926125.02      6999324.98      2925825.00      6999675.00
      2925575.00      7000075.00
#Sta/Elev= 30
  4541.9  433.33  4549.1  433.39  4563.3  431.37  4569.9  432.10  4577.6  431.08
  4584.2  431.71  4598.5  431.19  4647.8  425.69  4669.8  421.84  4706.2  419.74
  4726.3  418.17  4762.0  416.90  4811.8  416.30  4814.5  416.14  4897.0  415.45
  4910.6  414.74  4960.6  415.42  4981.5  416.44  4995.8  408.12  4996.0  406.22
  4996.6  405.42  5002.7  405.42  5003.2  406.22  5010.6  407.49  5016.5  414.06
  5025.9  416.12  5078.2  415.76  5110.8  415.15  5141.3  416.14  5474.6  430.62
#Mann=7,-1,0
  4541.9    0.16       0  4706.2    0.12       0  4811.8    0.16       0
  4910.6    0.12       0  4996.0    0.07       0  5003.2    0.12       0
  5078.2    0.16       0
Bank Sta=4814.5,5141.3
Exp/Cntr=0.3,0.1

Type RM Length L Ch R = 1,30434,558,558,558
BEGIN DESCRIPTION:
LITTLE DRY CREEK 39.0
END DESCRIPTION:
XS GIS Cut Line= 3
      2925925.02      6998874.98      2925475.00      6999375.00
      2925375.00      7000074.98
#Sta/Elev= 30
  4314.5  443.78  4342.6  441.62  4356.8  439.11  4378.4  437.08  4385.2  437.75
  4442.0  432.46  4456.2  430.20  4491.3  428.02  4583.6  419.45  4647.5  415.36
  4677.0  414.84  4760.4  412.90  4845.6  412.84  4874.0  411.95  4952.3  414.17
  4973.4  414.69  4989.7  413.39  4997.3  406.43  5003.8  406.39  5004.4  405.59
  5010.5  405.59  5011.0  406.39  5013.9  407.89  5027.6  414.57  5057.9  413.77
  5084.2  414.84  5169.0  417.45  5320.6  419.10  5633.7  429.60  5694.3  434.00
#Mann=5,-1,0
  4314.5    0.16       0  4952.3    0.12       0  5003.8    0.07       0
  5011.0    0.12       0  5013.9    0.16       0
Bank Sta=4677,5084.2
Exp/Cntr=0.3,0.1

Type RM Length L Ch R = 1,29876,538,538,538
BEGIN DESCRIPTION:
LITTLE DRY CREEK 38.0
END DESCRIPTION:
XS GIS Cut Line= 3
      2925424.99      6998675.01      2925025.00      6999075.00
      2924674.96      6999375.03
#Sta/Elev= 30
  4416.0  434.67  4419.5  434.67  4430.1  433.03  4458.4  426.80  4472.6  424.59
  4568.1  413.21  4599.8  411.92  4684.7  410.52  4967.5  412.99  4978.1  410.11
  4985.0  410.11  4991.6  405.02  4992.2  404.22  4998.5  404.22  4999.1  405.02
  5017.3  407.81  5023.9  411.45  5031.6  412.20  5066.7  411.68  5078.5  413.21
  5094.7  414.37  5101.9  414.35  5138.1  417.96  5152.3  418.50  5158.9  417.90
  5166.1  415.32  5230.3  414.98  5258.3  419.05  5265.4  419.45  5442.7  425.47
#Mann=4,-1,0
  4416.0    0.16       0  4991.6    0.07       0  4999.1    0.16       0
  5094.7    0.05       0
Bank Sta=4568.1,5078.5
Exp/Cntr=0.3,0.1

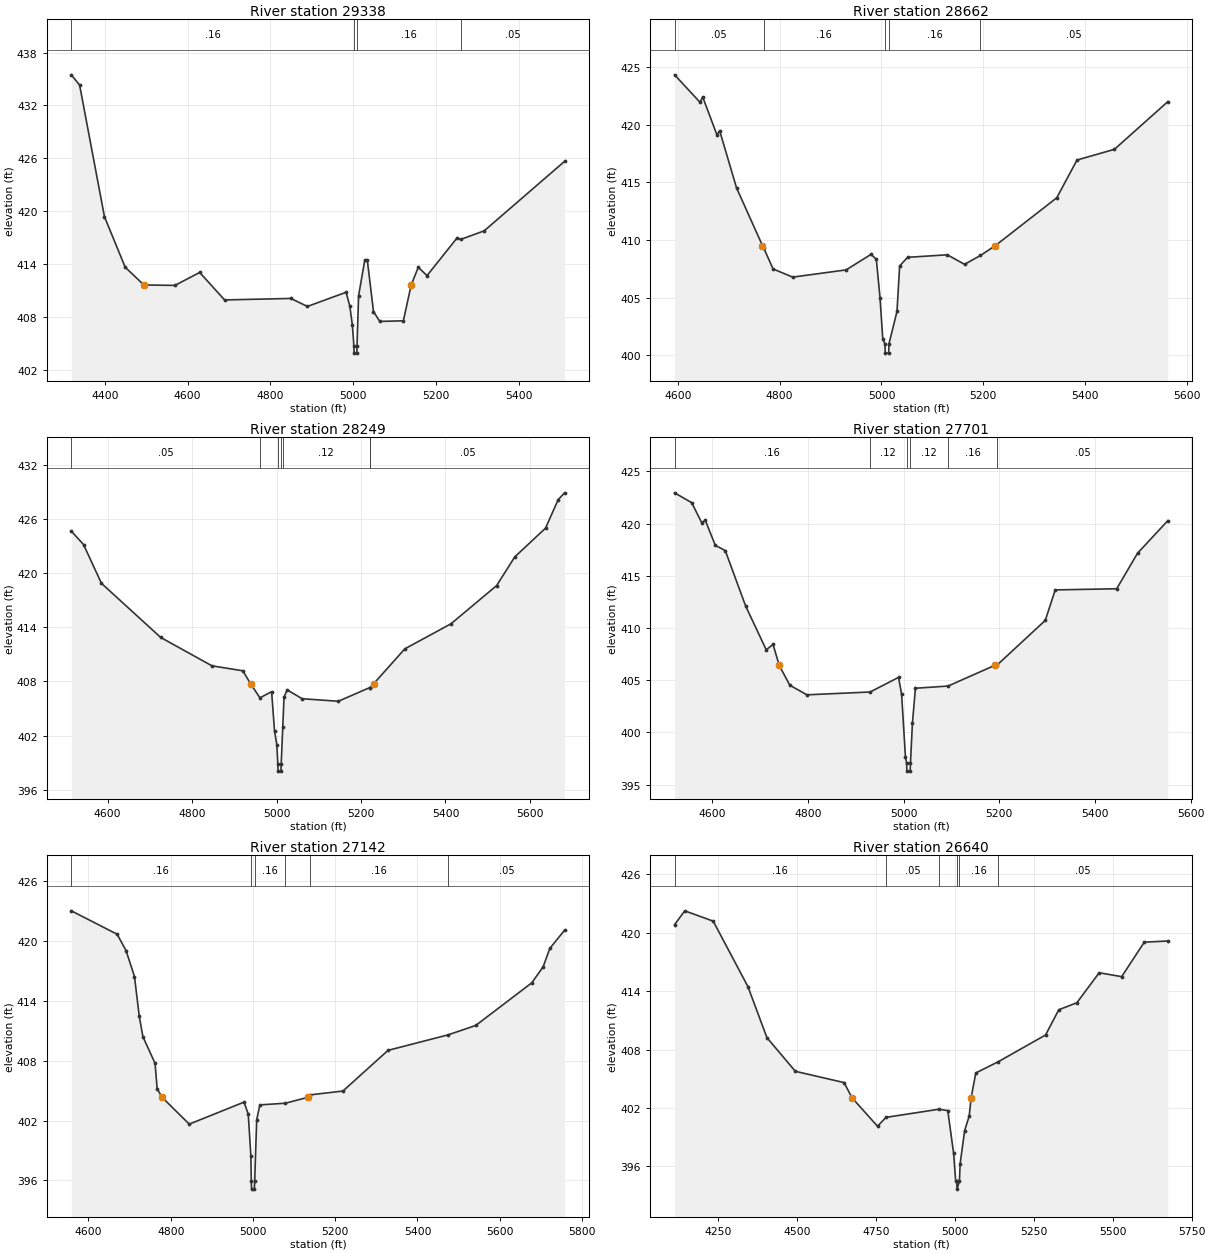
Type RM Length L Ch R = 1,29338,676,676,676
BEGIN DESCRIPTION:
LITTLE DRY CREEK 37.0
END DESCRIPTION:
XS GIS Cut Line= 3
      2925425.01      6998625.00      2924775.00      6998625.00
      2924325.04      6998924.98
#Sta/Elev= 30
  4319.2  435.47  4339.2  434.31  4399.2  419.36  4449.2  413.63  4494.4  411.61
  4569.2  411.56  4629.2  413.03  4689.2  409.91  4849.2  410.08  4889.2  409.17
  4982.7  410.78  4991.7  409.19  4997.8  407.04  5001.5  404.67  5002.1  403.87
  5008.4  403.87  5009.0  404.67  5012.8  410.39  5027.8  414.44  5033.8  414.46
  5048.8  408.59  5063.9  407.47  5120.9  407.54  5139.8  411.61  5157.0  413.62
  5178.0  412.67  5250.1  416.92  5259.9  416.79  5316.2  417.76  5510.0  425.64
#Mann=4,-1,0
  4319.2    0.16       0  5001.5    0.07       0  5009.0    0.16       0
  5259.9    0.05       0
Bank Sta=4494.4,5139.8
Exp/Cntr=0.3,0.1

Type RM Length L Ch R = 1,28662,413,413,413
BEGIN DESCRIPTION:
LITTLE DRY CREEK 36.0
END DESCRIPTION:
XS GIS Cut Line= 3
      2924575.01      6997674.96      2924444.18      6998117.64
      2924224.99      6998575.02
#Sta/Elev= 30
  4593.6  424.35  4643.6  421.96  4648.8  422.43  4676.8  419.13  4682.1  419.50
  4715.3  414.53  4766.2  409.52  4768.3  409.34  4787.1  407.49  4825.6  406.78
  4930.7  407.41  4979.5  408.76  4989.9  408.33  4997.2  404.96  5002.5  401.44
  5006.7  400.98  5007.4  400.18  5014.1  400.18  5014.7  400.98  5030.5  403.81
  5035.7  407.75  5051.2  408.50  5129.3  408.72  5163.2  407.89  5194.5  408.66
  5223.8  409.52  5344.3  413.67  5384.1  416.95  5457.6  417.88  5562.4  422.02
#Mann=5,-1,0
  4593.6    0.05       0  4768.3    0.16       0  5006.7    0.07       0
  5014.7    0.16       0  5194.5    0.05       0
Bank Sta=4766.2,5223.8
Exp/Cntr=0.3,0.1

Type RM Length L Ch R = 1,28249,548,548,548
BEGIN DESCRIPTION:
LITTLE DRY CREEK 35.0
END DESCRIPTION:
XS GIS Cut Line= 3
      2924525.00      6997625.00      2924125.00      6997875.00
      2923875.00      6998524.99
#Sta/Elev= 30
  4513.9  424.63  4542.8  423.15  4585.2  418.86  4725.6  412.87  4847.0  409.73
  4920.1  409.18  4938.3  407.76  4960.6  406.19  4988.3  406.87  4995.2  402.52
  5000.6  401.00  5003.0  398.88  5003.7  398.08  5010.4  398.08  5011.0  398.88
  5014.7  402.96  5017.7  406.27  5025.2  407.07  5060.6  406.09  5146.3  405.81
  5220.6  407.32  5222.1  407.33  5230.2  407.76  5303.8  411.61  5413.1  414.38
  5521.3  418.61  5564.2  421.78  5637.0  424.96  5667.0  428.11  5682.0  428.87
#Mann=7,-1,0
  4513.9    0.05       0  4960.6    0.16       0  5003.0    0.07       0
  5011.0    0.16       0  5014.7    0.12       0  5220.6    0.16       0
  5222.1    0.05       0
Bank Sta=4938.3,5230.2
Exp/Cntr=0.3,0.1

Type RM Length L Ch R = 1,27701,559,559,559
BEGIN DESCRIPTION:
LITTLE DRY CREEK 34.0
END DESCRIPTION:
XS GIS Cut Line= 3
      2924125.02      6997124.98      2923825.00      6997475.00
      2923475.00      6997925.00
#Sta/Elev= 30
  4521.1  422.95  4556.8  422.01  4577.7  420.10  4585.3  420.32  4606.2  417.92
  4627.0  417.42  4669.8  412.09  4712.7  407.91  4726.9  408.43  4739.8  406.42
  4762.0  404.52  4797.7  403.60  4929.9  403.87  4989.3  405.27  4995.7  403.67
  5003.8  397.62  5006.1  397.09  5006.8  396.29  5013.6  396.29  5014.3  397.09
  5018.3  400.88  5024.6  404.23  5092.8  404.44  5190.4  406.42  5196.0  406.48
  5296.1  410.73  5316.9  413.65  5445.4  413.76  5488.9  417.16  5552.2  420.28
#Mann=6,-1,0
  4521.1    0.16       0  4929.9    0.12       0  5006.1    0.07       0
  5014.3    0.12       0  5092.8    0.16       0  5196.0    0.05       0
Bank Sta=4739.8,5190.4
Exp/Cntr=0.3,0.1

Type RM Length L Ch R = 1,27142,502,502,502
BEGIN DESCRIPTION:
LITTLE DRY CREEK 33.0
END DESCRIPTION:
XS GIS Cut Line= 3
      2923924.96      6996975.01      2923475.00      6997075.00
      2922824.98      6997425.01
#Sta/Elev= 30
  4558.3  423.04  4669.7  420.69  4691.4  419.05  4711.9  416.44  4723.4  412.48
  4732.4  410.41  4761.9  407.74  4767.0  405.19  4779.0  404.33  4845.1  401.64
  4978.3  403.85  4988.5  402.64  4994.9  398.47  4995.9  395.92  4996.6  395.12
  5003.4  395.12  5004.2  395.92  5009.0  402.07  5016.7  403.57  5078.9  403.74
  5133.5  404.33  5137.5  404.57  5218.8  404.96  5328.3  409.04  5474.6  410.60
  5541.7  411.54  5678.0  415.82  5705.6  417.43  5721.8  419.27  5757.5  421.09
#Mann=6,-1,0
  4558.3    0.16       0  4995.9    0.07       0  5004.2    0.16       0
  5078.9    0.12       0  5137.5    0.16       0  5474.6    0.05       0
Bank Sta=4779,5133.5
Exp/Cntr=0.3,0.1

Type RM Length L Ch R = 1,26640,379,379,379
BEGIN DESCRIPTION:
Mapping XS fbac839e
END DESCRIPTION:
XS GIS Cut Line= 3
      2923977.20      6996836.47      2923115.23      6996826.06
      2922665.79      6997361.23
#Sta/Elev= 30
  4113.5  420.83  4145.7  422.25  4235.7  421.19  4345.7  414.46  4405.7  409.23
  4495.7  405.77  4649.9  404.61  4674.9  403.06  4755.7  400.13  4782.7  401.04
  4949.1  401.87  4978.1  401.74  4996.5  397.37  5003.0  394.55  5006.6  394.47
  5007.3  393.67  5014.9  394.47  5017.3  396.30  5031.6  399.69  5045.9  401.17
  5052.0  403.06  5066.8  405.60  5138.3  406.76  5287.6  409.50  5329.5  412.09
  5386.7  412.81  5457.3  415.89  5528.5  415.49  5600.0  419.03  5674.4  419.15
#Mann=6,-1,0
  4113.5    0.16       0  4782.7    0.05       0  4949.1    0.16       0
  5006.6    0.07       0  5014.9    0.16       0  5138.3    0.05       0
Bank Sta=4674.9,5052
Exp/Cntr=0.3,0.1

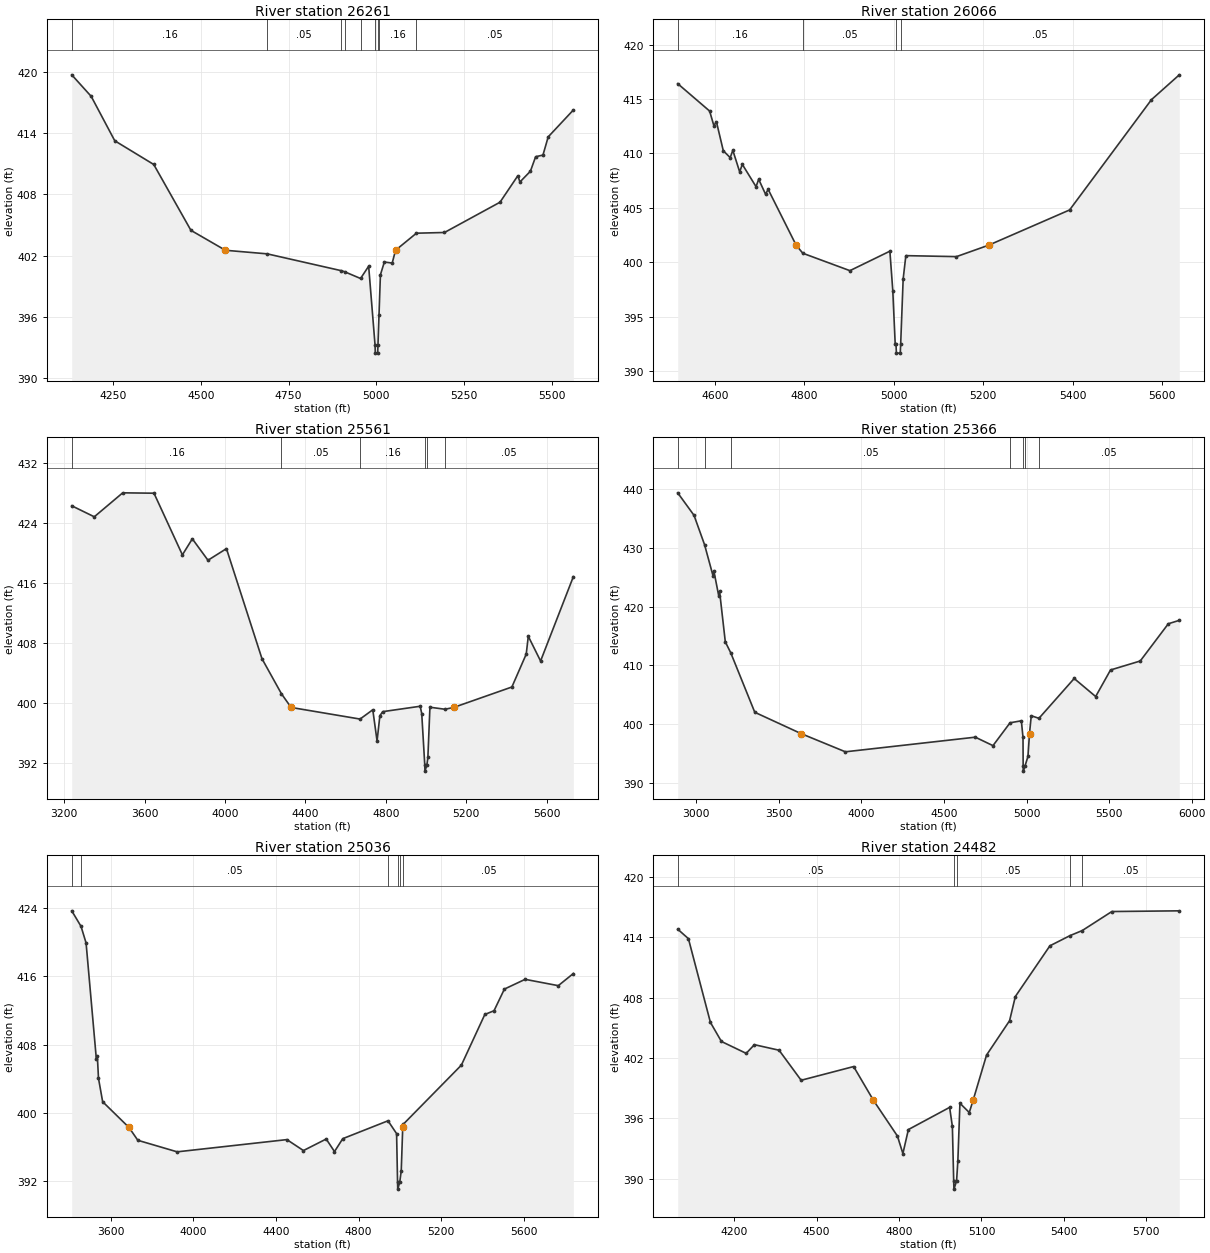
Type RM Length L Ch R = 1,26261,195,195,195
BEGIN DESCRIPTION:
LITTLE DRY CREEK 32.0
END DESCRIPTION:
XS GIS Cut Line= 4
      2923824.98      6996724.99      2923050.00      6996500.00
      2922950.00      6996550.00      2922660.41      6996970.56
#Sta/Elev= 30
  4132.1  419.69  4187.6  417.58  4254.7  413.24  4365.8  410.92  4471.7  404.48
  4570.0  402.53  4689.1  402.18  4899.4  400.54  4909.7  400.43  4955.1  399.77
  4978.2  400.97  4996.4  393.27  4997.1  392.47  5004.0  392.47  5004.7  393.27
  5007.7  396.21  5011.7  400.13  5022.9  401.38  5045.3  401.28  5054.8  402.53
  5114.3  404.20  5194.3  404.27  5352.5  407.23  5403.3  409.82  5409.3  409.21
  5439.1  410.26  5454.0  411.68  5474.9  411.84  5489.8  413.62  5561.5  416.25
#Mann=9,-1,0
  4132.1    0.16       0  4689.1    0.05       0  4899.4    0.07       0
  4909.7    0.16       0  4955.1    0.07       0  4996.4    0.07       0
  5004.7    0.07       0  5007.7    0.16       0  5114.3    0.05       0
Bank Sta=4570,5054.8
Exp/Cntr=0.3,0.1

Type RM Length L Ch R = 1,26066,505,505,505
BEGIN DESCRIPTION:
LITTLE DRY CREEK 31.0
END DESCRIPTION:
XS GIS Cut Line= 3
      2923125.02      6995974.96      2922875.00      6996375.00
      2922625.02      6996974.96
#Sta/Elev= 30
  4516.5  416.41  4587.9  413.89  4597.3  412.56  4603.2  412.89  4618.5  410.24
  4633.9  409.61  4639.8  410.28  4655.1  408.30  4661.0  408.99  4691.7  406.94
  4697.6  407.62  4712.9  406.25  4718.8  406.69  4781.4  401.56  4796.3  400.82
  4901.6  399.22  4991.0  401.01  4997.5  397.39  5002.9  392.46  5004.7  392.44
  5005.6  391.64  5014.2  391.64  5015.1  392.44  5020.7  398.46  5026.7  400.60
  5139.9  400.51  5211.8  401.56  5392.9  404.80  5576.0  414.94  5638.2  417.22
#Mann=4,-1,0
  4516.5    0.16       0  4796.3    0.05       0  5004.7    0.03       0
  5015.1    0.05       0
Bank Sta=4781.4,5211.8
Exp/Cntr=0.3,0.1

Type RM Length L Ch R = 1,25561,195,195,195
BEGIN DESCRIPTION:
LITTLE DRY CREEK 30.0
END DESCRIPTION:
XS GIS Cut Line= 3
      2923660.99      6994962.25      2922425.00      6996175.00
      2922574.99      6996924.95
#Sta/Elev= 30
  3236.8  426.32  3349.0  424.85  3490.5  428.05  3646.1  428.00  3787.5  419.77
  3836.9  421.91  3914.8  419.05  4006.7  420.60  4183.5  405.91  4280.6  401.22
  4328.5  399.40  4671.7  397.85  4735.0  399.09  4756.3  394.93  4770.4  398.31
  4784.6  398.84  4970.9  399.56  4978.6  398.59  4993.8  391.70  4994.6  390.90
  5004.2  391.70  5009.2  392.72  5019.4  399.43  5094.4  399.16  5137.5  399.40
  5427.3  402.13  5498.7  406.52  5508.9  408.90  5570.1  405.60  5733.2  416.86
#Mann=6,-1,0
  3236.8    0.16       0  4280.6    0.05       0  4671.7    0.16       0
  4993.8    0.07       0  5004.2    0.16       0  5094.4    0.05       0
Bank Sta=4328.5,5137.5
Exp/Cntr=0.3,0.1

Type RM Length L Ch R = 1,25366,330,330,330
BEGIN DESCRIPTION:
Mapping XS fdd41505
END DESCRIPTION:
XS GIS Cut Line= 3
      2922775.58      6994134.09      2922239.11      6996128.92
      2922265.11      6997101.47
#Sta/Elev= 30
  2886.7  439.37  2985.6  435.54  3049.3  430.55  3100.3  425.29  3105.5  426.11
  3135.1  421.86  3140.3  422.62  3175.1  414.00  3208.0  412.14  3353.6  402.01
  3633.2  398.39  3902.5  395.28  4689.5  397.77  4796.6  396.33  4900.1  400.22
  4968.5  400.56  4978.5  397.72  4979.4  392.79  4980.3  391.99  4989.8  392.79
  5008.5  394.49  5017.9  398.39  5028.5  401.42  5075.0  400.98  5288.6  407.76
  5418.6  404.69  5508.7  409.21  5688.7  410.74  5858.8  417.08  5925.3  417.66
#Mann=7,-1,0
  2886.7    0.05       0  3049.3    0.16       0  3208.0    0.05       0
  4900.1    0.16       0  4979.4    0.07       0  4989.8    0.16       0
  5075.0    0.05       0
Bank Sta=3633.2,5017.9
Exp/Cntr=0.3,0.1

Type RM Length L Ch R = 1,25036,554,554,554
BEGIN DESCRIPTION:
LITTLE DRY CREEK 29.0
END DESCRIPTION:
XS GIS Cut Line= 3
      2922027.99      6994585.72      2921925.00      6996175.00
      2921996.73      6997007.60
#Sta/Elev= 30
  3411.5  423.63  3456.5  421.81  3480.9  419.87  3530.5  406.33  3535.5  406.60
  3541.0  404.04  3561.1  401.31  3688.6  398.30  3731.4  396.80  3921.8  395.45
  4453.0  396.88  4533.1  395.60  4643.4  396.95  4683.4  395.48  4723.5  396.99
  4942.5  399.08  4984.1  397.58  4988.8  391.89  4989.7  391.09  4999.3  391.89
  5006.6  393.24  5013.8  398.30  5017.0  398.69  5297.8  405.59  5411.2  411.51
  5455.8  411.95  5506.0  414.48  5606.3  415.62  5766.9  414.88  5839.8  416.30
#Mann=6,-1,0
  3411.5    0.16       0  3456.5    0.05       0  4942.5    0.16       0
  4988.8    0.07       0  4999.3    0.16       0  5017.0    0.05       0
Bank Sta=3688.6,5013.8
Exp/Cntr=0.3,0.1

Type RM Length L Ch R = 1,24482,705,705,705
BEGIN DESCRIPTION:
LITTLE DRY CREEK 28.0
END DESCRIPTION:
XS GIS Cut Line= 3
      2921335.75      6995196.02      2921375.00      6996225.00
      2921613.54      6996984.28
#Sta/Elev= 30
  3994.5  414.78  4033.5  413.84  4113.6  405.53  4153.6  403.64  4243.7  402.46
  4273.7  403.32  4363.5  402.77  4443.8  399.79  4634.8  401.15  4706.9  397.80
  4794.1  394.26  4814.1  392.52  4834.1  394.90  4984.2  397.10  4994.2  395.21
  4999.0  389.79  4999.9  388.99  5009.5  389.79  5014.2  391.82  5021.7  397.51
  5055.7  396.59  5069.6  397.80  5118.6  402.29  5202.4  405.70  5223.4  408.10
  5349.2  413.13  5422.3  414.14  5466.7  414.64  5574.6  416.53  5820.1  416.60
#Mann=5,-1,0
  3994.5    0.05       0  4999.0    0.03       0  5009.5    0.05       0
  5422.3    0.16       0  5466.7    0.05       0
Bank Sta=4706.9,5069.6
Exp/Cntr=0.3,0.1

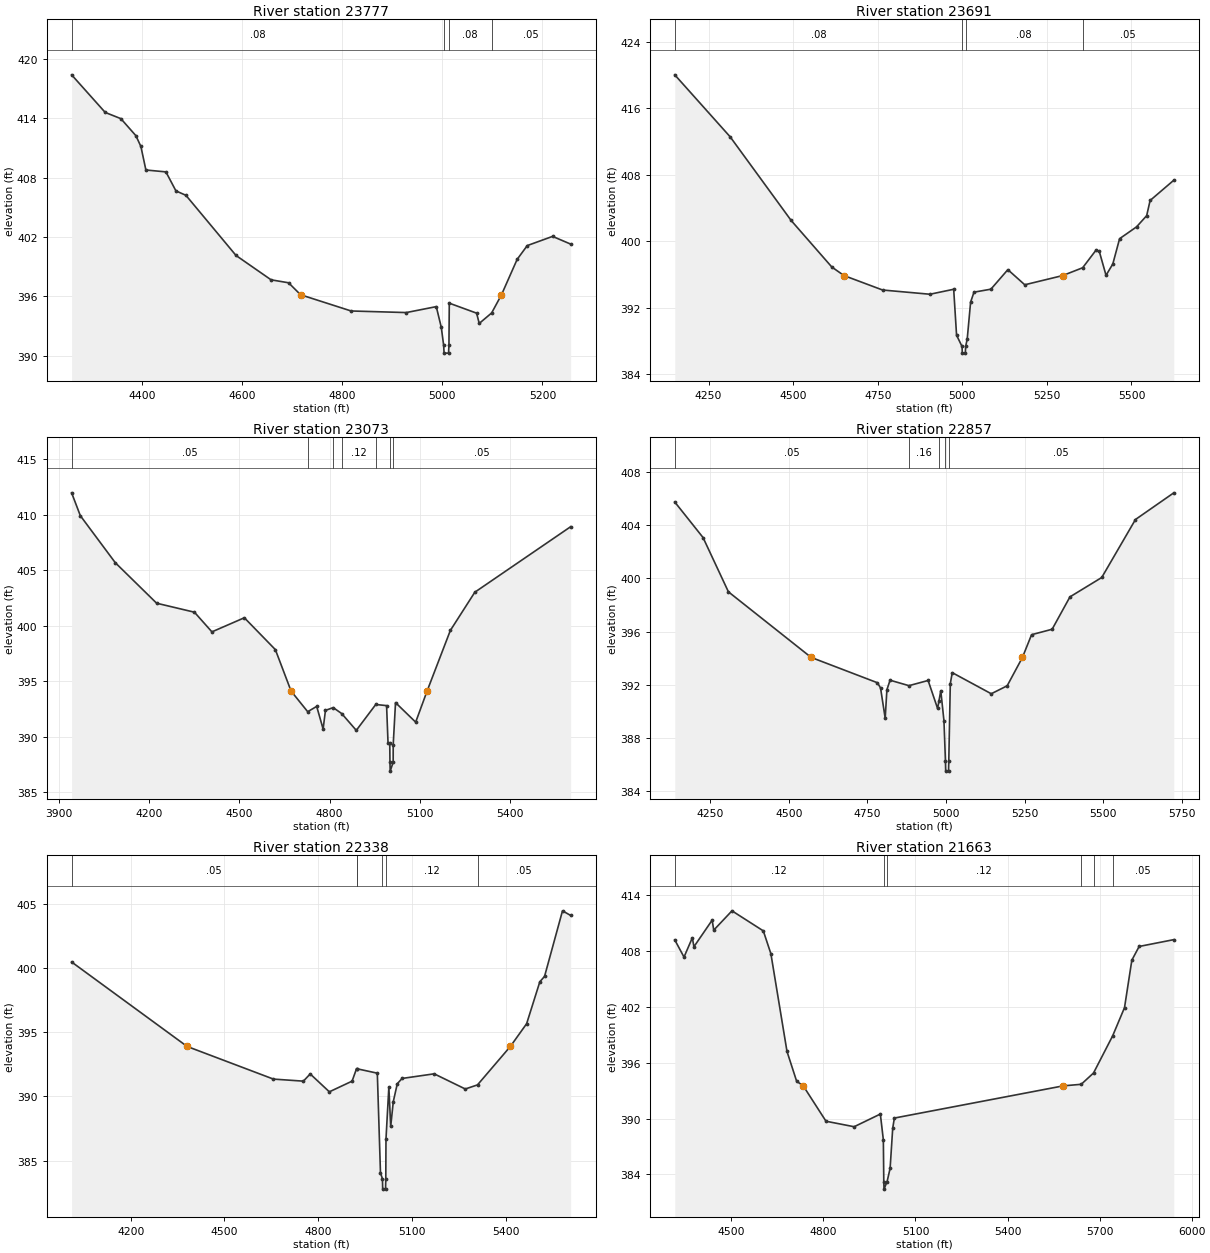
Type RM Length L Ch R = 1,23777,86,86,86
BEGIN DESCRIPTION:
Mapping XS b2600188
END DESCRIPTION:
XS GIS Cut Line= 3
      2920721.95      6995566.67      2920701.12      6996321.92
      2920737.46      6996560.73
#Sta/Elev= 30
  4259.4  418.40  4326.5  414.60  4357.8  413.97  4387.8  412.25  4397.8  411.16
  4407.8  408.78  4447.8  408.59  4467.8  406.67  4487.8  406.22  4587.9  400.14
  4657.9  397.68  4692.9  397.38  4716.9  396.17  4817.9  394.53  4928.0  394.37
  4988.0  394.97  4998.0  392.88  5002.7  391.07  5003.6  390.27  5012.5  390.27
  5013.3  391.07  5014.0  395.32  5068.6  394.31  5073.8  393.27  5098.6  394.33
  5118.3  396.17  5149.6  399.75  5169.8  401.14  5220.4  402.07  5256.5  401.29
#Mann=4,-1,0
  4259.4    0.08       0  5002.7    0.07       0  5013.3    0.08       0
  5098.6    0.05       0
Bank Sta=4716.9,5118.3
Exp/Cntr=0.3,0.1

Type RM Length L Ch R = 1,23691,618,618,618
BEGIN DESCRIPTION:
Mapping XS cd137807
END DESCRIPTION:
XS GIS Cut Line= 3
      2920656.84      6995491.22      2920622.99      6996327.13
      2920596.95      6996965.10
#Sta/Elev= 30
  4150.0  420.04  4313.9  412.57  4494.1  402.50  4614.2  396.90  4650.2  395.87
  4764.3  394.13  4904.4  393.62  4974.5  394.22  4983.0  388.69  4999.2  387.33
  5000.0  386.53  5008.9  386.53  5009.8  387.33  5014.5  388.23  5024.5  392.67
  5034.5  393.87  5084.5  394.23  5134.6  396.58  5184.6  394.76  5296.8  395.87
  5355.7  396.81  5394.8  398.91  5404.8  398.79  5424.8  395.90  5444.8  397.26
  5464.9  400.31  5514.9  401.73  5544.9  403.08  5555.1  404.91  5625.1  407.35
#Mann=4,-1,0
  4150.0    0.08       0  4999.2    0.07       0  5009.8    0.08       0
  5355.7    0.05       0
Bank Sta=4650.2,5296.8
Exp/Cntr=0.3,0.1

Type RM Length L Ch R = 1,23073,216,216,216
BEGIN DESCRIPTION:
LITTLE DRY CREEK 26.0
END DESCRIPTION:
XS GIS Cut Line= 3
      2920574.98      6995575.03      2920025.00      6996475.00
      2920275.01      6997025.02
#Sta/Elev= 30
  3942.2  411.97  3971.2  409.91  4087.3  405.68  4224.8  402.03  4350.5  401.22
  4408.6  399.45  4516.4  400.72  4619.5  397.85  4671.7  394.12  4727.0  392.26
  4756.9  392.74  4778.2  390.70  4786.0  392.38  4811.8  392.63  4840.1  392.09
  4888.5  390.58  4953.2  392.91  4989.2  392.81  4994.0  389.45  4999.7  389.45
  5000.4  387.71  5001.2  386.91  5011.1  387.71  5011.2  389.28  5018.9  393.08
  5085.9  391.32  5123.8  394.12  5201.2  399.58  5282.5  403.02  5601.1  408.92
#Mann=7,-1,0
  3942.2    0.05       0  4727.0    0.16       0  4811.8    0.05       0
  4840.1    0.12       0  4953.2    0.05       0  5000.4    0.03       0
  5011.1    0.05       0
Bank Sta=4671.7,5123.8
Exp/Cntr=0.3,0.1

Type RM Length L Ch R = 1,22857,519,519,519
BEGIN DESCRIPTION:
Mapping XS be732c1b
END DESCRIPTION:
XS GIS Cut Line= 3
      2919704.59      6995645.72      2919817.44      6996522.44
      2920220.54      6997098.93
#Sta/Elev= 30
  4137.1  405.76  4227.1  403.08  4307.8  398.99  4570.9  394.05  4781.7  392.14
  4791.7  391.75  4806.5  389.46  4811.9  391.61  4822.0  392.33  4882.0  391.92
  4943.0  392.31  4973.2  390.20  4977.4  390.76  4983.3  391.54  4993.4  389.28
  4998.1  386.28  4998.9  385.48  5008.0  385.48  5008.8  386.28  5013.6  392.07
  5019.8  392.90  5143.9  391.31  5194.5  391.91  5243.1  394.05  5272.1  395.76
  5337.5  396.17  5394.2  398.61  5495.3  400.07  5602.6  404.44  5724.5  406.45
#Mann=5,-1,0
  4137.1    0.05       0  4882.0    0.16       0  4977.4    0.05       0
  4998.1    0.03       0  5008.8    0.05       0
Bank Sta=4570.9,5243.1
Exp/Cntr=0.3,0.1

Type RM Length L Ch R = 1,22338,675,675,675
BEGIN DESCRIPTION:
Mapping XS 15542f11
END DESCRIPTION:
XS GIS Cut Line= 3
      2919174.43      6995741.63      2919442.65      6996694.75
      2919950.25      6997025.34
#Sta/Elev= 30
  4011.2  400.46  4380.5  393.89  4656.5  391.35  4752.3  391.19  4774.2  391.75
  4835.4  390.36  4908.1  391.19  4922.4  392.16  4922.5  392.16  4988.8  391.81
  4998.9  384.06  5005.2  383.59  5006.0  382.79  5015.1  382.79  5015.9  383.59
  5016.5  386.68  5025.7  390.73  5031.6  387.67  5039.9  389.60  5052.7  390.99
  5067.9  391.40  5170.6  391.76  5270.1  390.58  5309.2  390.90  5414.3  393.89
  5466.3  395.66  5508.5  398.92  5523.6  399.34  5581.0  404.44  5607.1  404.08
#Mann=6,-1,0
  4011.2    0.05       0  4922.4    0.16       0  4922.5    0.12       0
  5005.2    0.07       0  5015.9    0.12       0  5309.2    0.05       0
Bank Sta=4380.5,5414.3
Exp/Cntr=0.3,0.1

Type RM Length L Ch R = 1,21663,209,209,209
BEGIN DESCRIPTION:
LITTLE DRY CREEK 25.0
END DESCRIPTION:
XS GIS Cut Line= 3
      2918812.44      6996296.28      2919019.01      6996948.87
      2919888.01      6997311.95
#Sta/Elev= 30
  4315.5  409.16  4345.7  407.31  4372.8  409.38  4378.0  408.42  4437.4  411.27
  4442.6  410.20  4502.0  412.27  4604.1  410.12  4628.8  407.67  4681.3  397.19
  4712.7  394.00  4734.3  393.50  4808.4  389.71  4900.1  389.12  4985.5  390.48
  4995.3  387.71  4996.7  383.23  4997.5  382.43  5007.4  383.23  5017.3  384.65
  5025.8  388.96  5031.2  390.05  5581.1  393.50  5640.1  393.67  5680.2  394.88
  5742.5  398.86  5781.2  401.89  5805.1  406.98  5828.9  408.45  5941.8  409.18
#Mann=6,-1,0
  4315.5    0.12       0  4996.7    0.07       0  5007.4    0.12       0
  5640.1    0.05       0  5680.2    0.16       0  5742.5    0.05       0
Bank Sta=4734.3,5581.1
Exp/Cntr=0.3,0.1

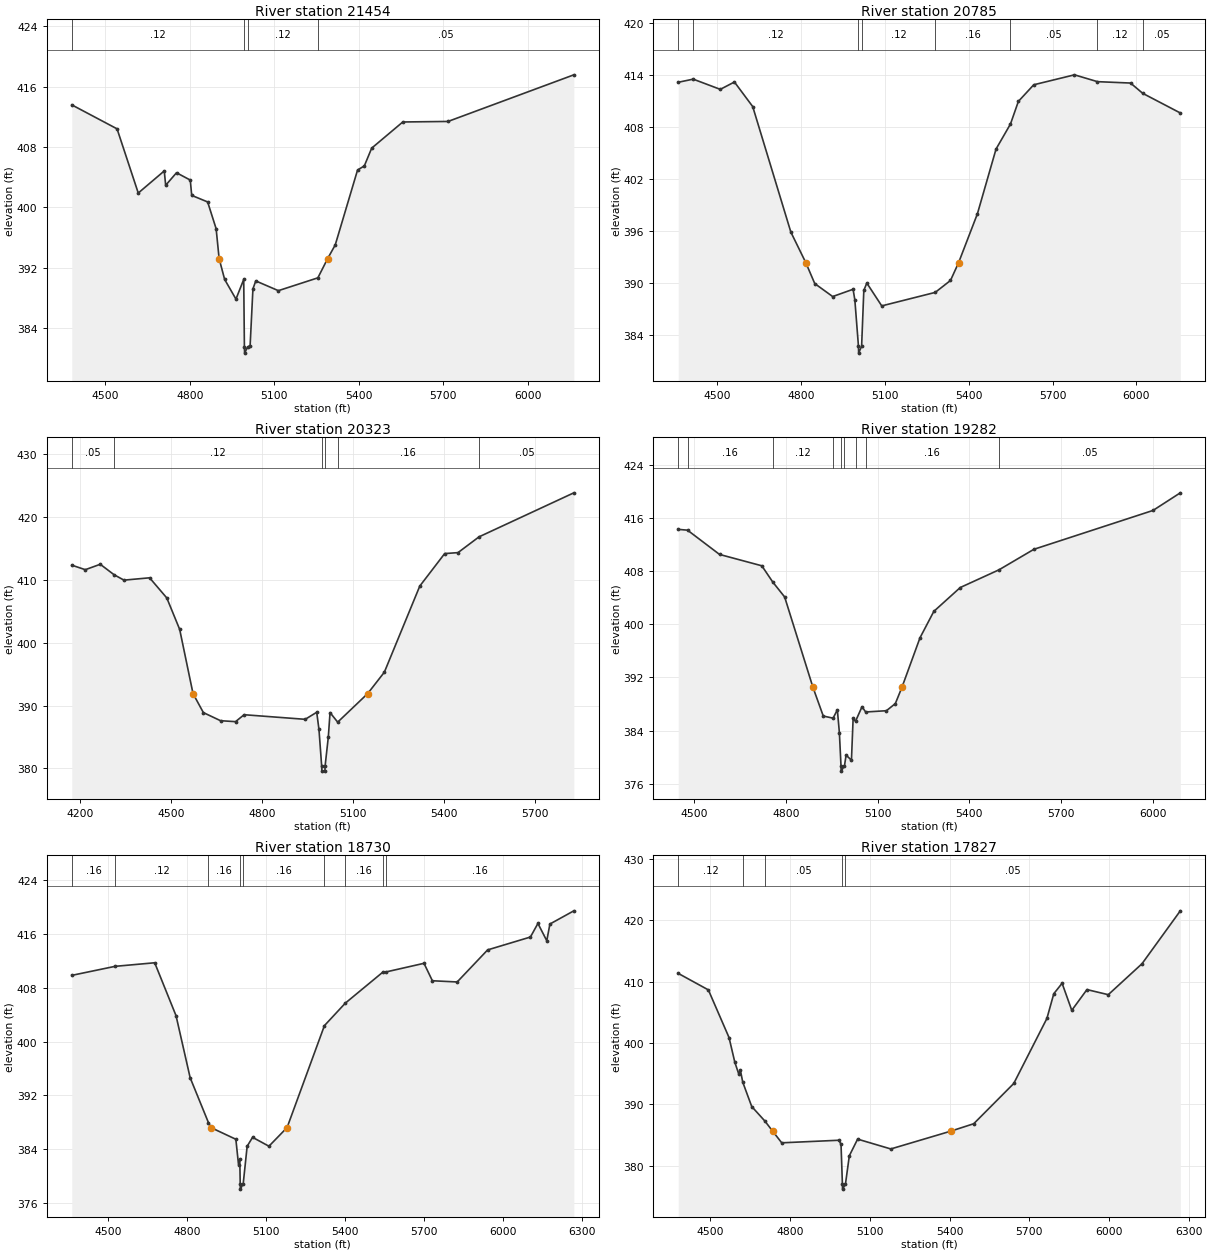
Type RM Length L Ch R = 1,21454,669,669,669
BEGIN DESCRIPTION:
LITTLE DRY CREEK 24.0
END DESCRIPTION:
XS GIS Cut Line= 3
      2918775.00      6996424.97      2918840.62      6997040.79
      2918950.00      6998200.04
#Sta/Elev= 30
  4380.7  413.57  4541.6  410.39  4616.9  401.88  4709.3  404.81  4714.3  402.91
  4752.8  404.57  4801.7  403.60  4806.8  401.57  4863.4  400.70  4893.6  397.15
  4904.2  393.19  4923.8  390.43  4964.0  387.82  4991.6  390.43  4994.0  381.46
  4994.7  380.66  5005.2  381.46  5014.3  381.64  5024.3  389.18  5034.4  390.23
  5114.7  388.94  5255.0  390.64  5289.7  393.19  5316.7  395.00  5396.0  404.93
  5420.1  405.48  5446.2  407.83  5556.7  411.30  5717.4  411.37  6164.4  417.55
#Mann=4,-1,0
  4380.7    0.12       0  4994.0    0.07       0  5005.2    0.12       0
  5255.0    0.05       0
Bank Sta=4904.2,5289.7
Exp/Cntr=0.3,0.1

Type RM Length L Ch R = 1,20785,462,462,462
BEGIN DESCRIPTION:
LITTLE DRY CREEK 23.0
END DESCRIPTION:
XS GIS Cut Line= 3
      2918625.00      6996525.00      2918275.00      6997025.00
      2917856.15      6998134.01
#Sta/Elev= 30
  4361.3  413.20  4414.9  413.56  4511.7  412.38  4562.3  413.23  4627.7  410.39
  4764.1  395.88  4817.7  392.34  4849.6  389.93  4913.7  388.43  4986.7  389.27
  4993.0  388.04  5005.9  382.69  5006.6  381.89  5017.2  382.69  5025.1  389.14
  5035.8  389.99  5089.2  387.35  5280.5  388.91  5335.1  390.29  5364.0  392.34
  5431.3  397.99  5498.0  405.48  5549.7  408.38  5577.9  410.99  5632.9  412.91
  5778.5  414.06  5860.8  413.27  5979.1  413.11  6022.7  411.92  6157.1  409.65
#Mann=8,-1,0
  4361.3    0.05       0  4414.9    0.12       0  5005.9    0.07       0
  5017.2    0.12       0  5280.5    0.16       0  5549.7    0.05       0
  5860.8    0.12       0  6022.7    0.05       0
Bank Sta=4817.7,5364
Exp/Cntr=0.3,0.1

Type RM Length L Ch R = 1,20323,1041,1041,1041
BEGIN DESCRIPTION:
LITTLE DRY CREEK 22.0
END DESCRIPTION:
XS GIS Cut Line= 3
      2918422.16      6996349.24      2917970.74      6996824.97
      2917499.24      6997705.57
#Sta/Elev= 30
  4173.2  412.30  4217.8  411.58  4267.1  412.44  4312.6  410.78  4345.2  409.92
  4429.7  410.29  4486.4  407.09  4528.8  402.10  4572.8  391.90  4606.9  388.88
  4663.5  387.59  4712.9  387.44  4741.2  388.54  4942.5  387.81  4980.5  388.93
  4987.9  386.20  4996.8  380.38  4997.5  379.58  5007.5  379.58  5008.1  380.38
  5018.7  385.00  5024.4  388.88  5049.6  387.36  5148.5  391.90  5203.4  395.30
  5320.2  408.98  5402.2  414.14  5446.1  414.29  5515.5  416.80  5827.9  423.79
#Mann=6,-1,0
  4173.2    0.05       0  4312.6    0.12       0  4996.8    0.07       0
  5008.1    0.12       0  5049.6    0.16       0  5515.5    0.05       0
Bank Sta=4572.8,5148.5
Exp/Cntr=0.3,0.1

Type RM Length L Ch R = 1,19282,552,552,552
BEGIN DESCRIPTION:
LITTLE DRY CREEK 21.0
END DESCRIPTION:
XS GIS Cut Line= 3
      2918175.02      6996024.99      2917625.00      6996275.00
      2917191.93      6997219.25
#Sta/Elev= 30
  4447.3  414.29  4477.7  414.17  4582.4  410.52  4720.8  408.81  4756.7  406.36
  4795.5  404.12  4888.0  390.54  4921.9  386.20  4954.0  385.88  4968.0  387.13
  4974.6  383.72  4979.9  378.71  4980.5  377.91  4991.3  378.71  4996.6  380.32
  5014.1  379.55  5019.6  385.83  5027.5  385.42  5048.7  387.60  5060.6  386.81
  5128.5  387.00  5157.7  388.07  5179.5  390.54  5238.5  397.98  5283.7  401.95
  5370.2  405.54  5497.2  408.21  5611.1  411.29  6001.0  417.14  6090.3  419.79
#Mann=9,-1,0
  4447.3    0.05       0  4477.7    0.16       0  4756.7    0.12       0
  4954.0    0.16       0  4979.9    0.07       0  4991.3    0.16       0
  5027.5    0.12       0  5060.6    0.16       0  5497.2    0.05       0
Bank Sta=4888,5179.5
Exp/Cntr=0.3,0.1

Type RM Length L Ch R = 1,18730,903,903,903
BEGIN DESCRIPTION:
LITTLE DRY CREEK 20.0
END DESCRIPTION:
XS GIS Cut Line= 3
      2917641.97      6995531.61      2917329.58      6996088.35
      2917005.87      6997314.44
#Sta/Elev= 30
  4361.6  409.83  4526.1  411.17  4676.5  411.70  4757.5  403.85  4811.1  394.64
  4880.7  387.96  4889.8  387.24  4984.7  385.50  4994.8  381.73  4999.6  382.54
  5001.2  378.90  5001.8  378.10  5012.6  378.90  5027.6  384.47  5048.2  385.79
  5110.3  384.47  5179.2  387.24  5321.0  402.37  5400.4  405.71  5541.9  410.28
  5556.3  410.35  5699.1  411.62  5730.9  409.03  5825.1  408.85  5940.7  413.61
  6103.2  415.52  6131.7  417.54  6165.3  414.97  6177.2  417.45  6268.1  419.41
#Mann=9,-1,0
  4361.6    0.16       0  4526.1    0.12       0  4880.7    0.16       0
  5001.2    0.07       0  5012.6    0.16       0  5321.0    0.05       0
  5400.4    0.16       0  5541.9    0.05       0  5556.3    0.16       0
Bank Sta=4889.8,5179.2
Exp/Cntr=0.3,0.1

Type RM Length L Ch R = 1,17827,673,673,673
BEGIN DESCRIPTION:
LITTLE DRY CREEK 19.0
END DESCRIPTION:
XS GIS Cut Line= 3
      2916925.03      6995724.97      2916525.00      6996175.00
      2916944.89      6997391.13
#Sta/Elev= 30
  4379.0  411.37  4492.3  408.68  4570.1  400.91  4591.9  396.88  4606.1  395.04
  4612.8  395.59  4621.6  393.65  4655.4  389.67  4704.9  387.30  4734.3  385.64
  4768.3  383.75  4983.8  384.17  4991.4  383.48  4996.6  377.00  4997.2  376.20
  5008.0  377.00  5022.6  381.64  5053.8  384.35  5178.6  382.75  5403.4  385.64
  5490.5  386.86  5641.1  393.42  5765.9  404.03  5791.8  408.06  5823.0  409.76
  5859.4  405.35  5916.5  408.73  5996.7  407.90  6123.7  412.95  6267.7  421.57
#Mann=5,-1,0
  4379.0    0.12       0  4621.6    0.16       0  4704.9    0.05       0
  4996.6    0.03       0  5008.0    0.05       0
Bank Sta=4734.3,5403.4
Exp/Cntr=0.3,0.1