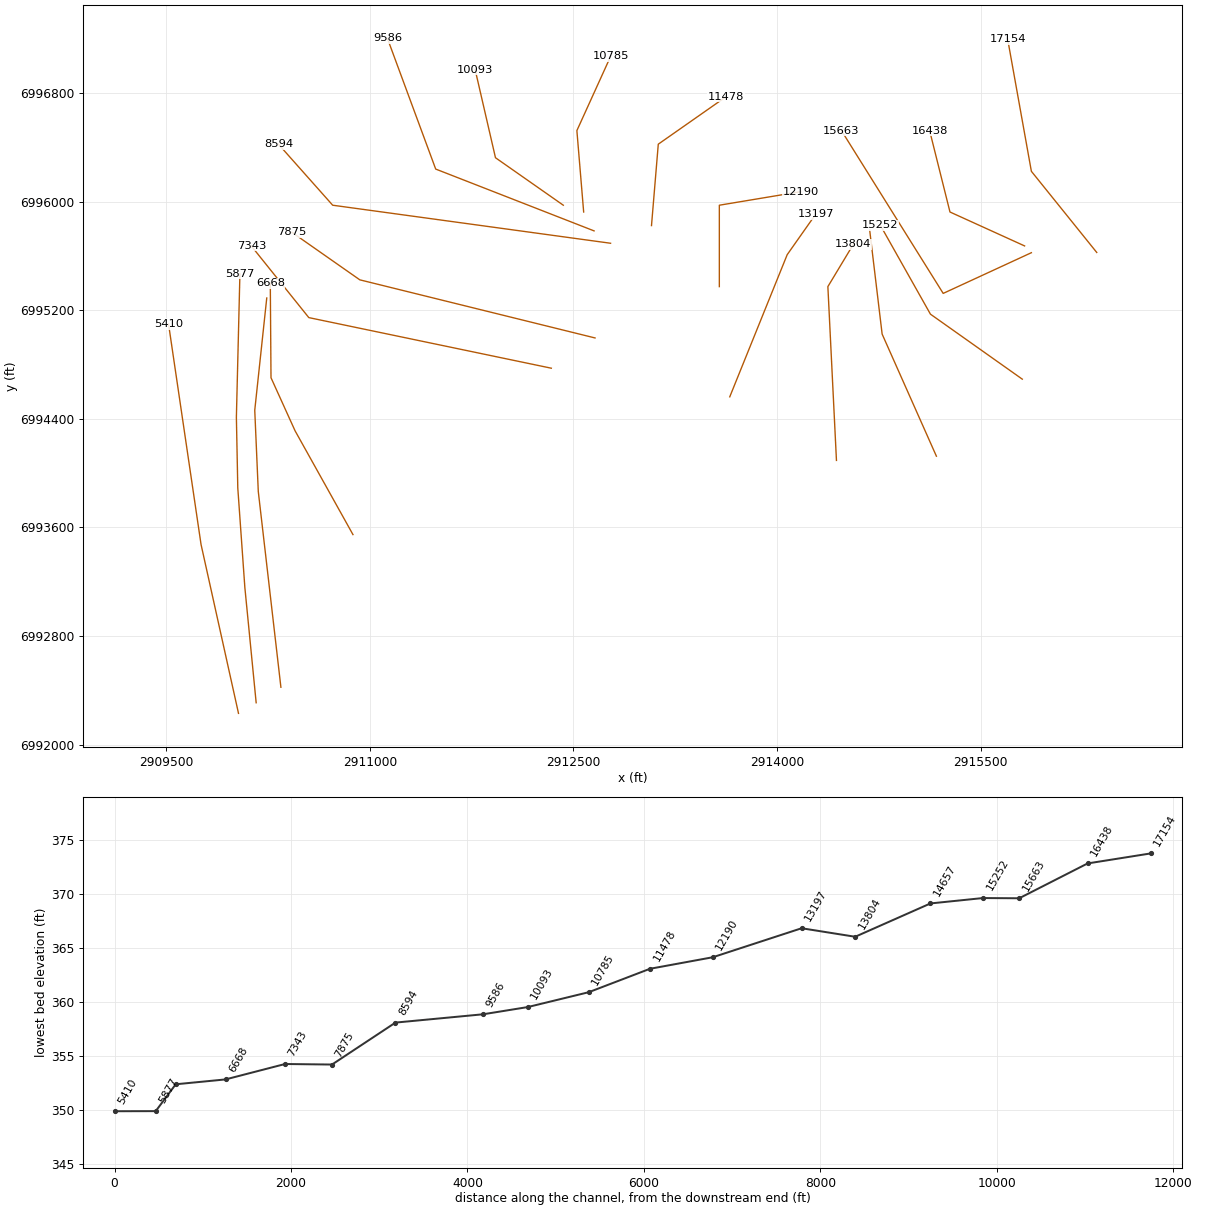
HEC-RAS study LITTLE DRY CREEK.prj: LITTLE DRY CREEK Base Level Engineering

--- LITTLE DRY CREEK.g01 (geometry) --- (continued)

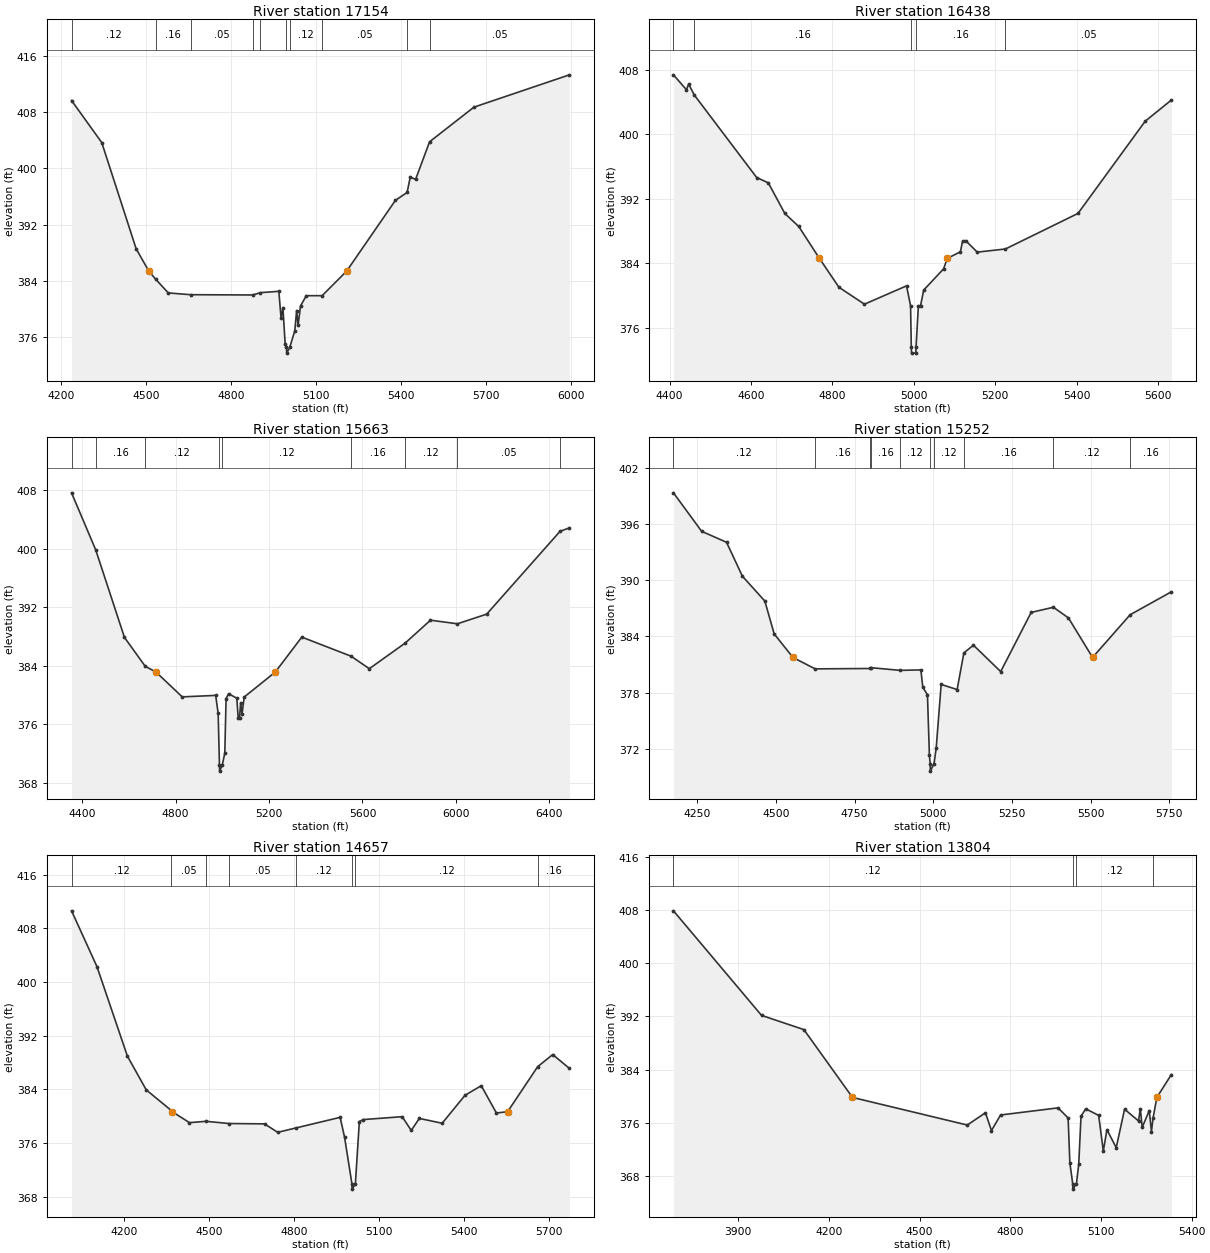
Type RM Length L Ch R = 1,17154,716,716,716
BEGIN DESCRIPTION:
LITTLE DRY CREEK 18.0
END DESCRIPTION:
XS GIS Cut Line= 3
      2916356.77      6995626.83      2915875.00      6996225.00
      2915700.01      6997199.97
#Sta/Elev= 30
  4237.1  409.64  4343.7  403.67  4465.3  388.57  4510.3  385.39  4534.1  384.26
  4578.8  382.31  4657.4  382.06  4876.7  382.02  4904.1  382.35  4969.2  382.54
  4977.1  378.70  4983.6  380.23  4991.5  375.08  4996.2  374.56  4996.9  373.76
  5007.6  374.56  5025.5  376.93  5032.0  379.81  5037.1  377.71  5045.8  380.46
  5066.1  381.92  5122.0  381.92  5208.3  385.39  5381.1  395.47  5422.2  396.58
  5433.3  398.76  5452.2  398.44  5501.6  403.78  5658.3  408.70  5995.7  413.29
#Mann=10,-1,0
  4237.1    0.12       0  4534.1    0.16       0  4657.4    0.05       0
  4876.7    0.16       0  4904.1    0.12       0  4996.2    0.07       0
  5007.6    0.12       0  5122.0    0.05       0  5422.2    0.16       0
  5501.6    0.05       0
Bank Sta=4510.3,5208.3
Exp/Cntr=0.3,0.1

Type RM Length L Ch R = 1,16438,775,775,775
BEGIN DESCRIPTION:
LITTLE DRY CREEK 17.0
END DESCRIPTION:
XS GIS Cut Line= 3
      2915824.99      6995675.01      2915275.00      6995925.00
      2915125.00      6996525.00
#Sta/Elev= 30
  4409.7  407.41  4441.5  405.56  4447.0  406.25  4460.9  404.90  4614.0  394.65
  4642.6  393.99  4683.2  390.18  4717.3  388.57  4768.1  384.60  4816.1  381.01
  4878.7  378.91  4982.0  381.19  4991.9  378.71  4993.7  373.63  4994.3  372.83
  5004.8  372.83  5005.4  373.63  5011.1  378.72  5016.4  378.72  5024.1  380.66
  5073.1  383.31  5081.9  384.60  5114.3  385.42  5119.5  386.73  5127.2  386.81
  5155.6  385.38  5224.8  385.77  5403.0  390.19  5567.9  401.64  5632.3  404.28
#Mann=5,-1,0
  4409.7    0.12       0  4460.9    0.16       0  4993.7    0.07       0
  5005.4    0.16       0  5224.8    0.05       0
Bank Sta=4768.1,5081.9
Exp/Cntr=0.3,0.1

Type RM Length L Ch R = 1,15663,411,411,411
BEGIN DESCRIPTION:
LITTLE DRY CREEK 16.0
END DESCRIPTION:
XS GIS Cut Line= 3
      2915875.03      6995625.02      2915225.00      6995325.00
      2914475.01      6996524.98
#Sta/Elev= 30
  4355.0  407.64  4458.5  399.83  4581.3  387.88  4670.5  383.92  4716.6  383.14
  4828.6  379.75  4971.8  379.95  4982.4  377.48  4988.0  370.40  4988.6  369.60
  4999.7  370.40  5010.8  372.05  5016.3  379.52  5026.9  380.18  5062.2  379.57
  5068.2  376.88  5073.9  376.88  5078.6  378.96  5084.5  377.40  5093.9  379.73
  5226.9  383.14  5340.4  387.92  5551.3  385.31  5629.3  383.60  5782.3  387.09
  5891.1  390.23  6006.2  389.74  6131.7  391.06  6445.9  402.39  6486.0  402.85
#Mann=9,-1,0
  4355.0    0.12       0  4458.5    0.16       0  4670.5    0.12       0
  4988.0    0.07       0  4999.7    0.12       0  5551.3    0.16       0
  5782.3    0.12       0  6006.2    0.05       0  6445.9    0.16       0
Bank Sta=4716.6,5226.9
Exp/Cntr=0.3,0.1

Type RM Length L Ch R = 1,15252,595,595,595
BEGIN DESCRIPTION:
Mapping XS 34d23e10
END DESCRIPTION:
XS GIS Cut Line= 3
      2915808.10      6994692.88      2915131.01      6995172.05
      2914761.19      6995828.34
#Sta/Elev= 30
  4174.2  399.34  4263.8  395.23  4342.9  394.06  4393.3  390.44  4464.7  387.78
  4494.3  384.28  4554.0  381.76  4624.6  380.54  4799.0  380.58  4801.0  380.67
  4894.8  380.38  4960.7  380.43  4966.8  378.58  4981.6  377.77  4987.8  371.29
  4990.3  370.42  4990.8  369.62  5002.5  370.42  5009.3  372.04  5025.2  378.88
  5075.9  378.33  5097.4  382.25  5127.8  383.07  5214.4  380.25  5311.3  386.57
  5382.0  387.12  5429.8  385.98  5506.5  381.76  5625.9  386.32  5757.0  388.77
#Mann=10,-1,0
  4174.2    0.12       0  4624.6    0.16       0  4799.0    0.05       0
  4801.0    0.16       0  4894.8    0.12       0  4990.3    0.07       0
  5002.5    0.12       0  5097.4    0.16       0  5382.0    0.12       0
  5625.9    0.16       0
Bank Sta=4554,5506.5
Exp/Cntr=0.3,0.1

Type RM Length L Ch R = 1,14657,853,853,853
BEGIN DESCRIPTION:
LITTLE DRY CREEK 15.0
END DESCRIPTION:
XS GIS Cut Line= 3
      2915175.01      6994124.97      2914775.00      6995025.00
      2914683.20      6995790.90
#Sta/Elev= 30
  4014.8  410.61  4104.4  402.29  4211.8  388.94  4278.2  383.92  4366.7  380.84
  4370.0  380.66  4430.7  379.03  4489.1  379.23  4570.3  378.90  4695.4  378.85
  4741.9  377.59  4807.1  378.25  4962.1  379.82  4977.8  376.85  5003.7  369.92
  5004.2  369.12  5015.9  369.92  5029.9  379.19  5043.4  379.49  5181.0  379.92
  5213.0  377.87  5241.4  379.66  5322.0  378.94  5402.6  383.11  5459.9  384.54
  5513.4  380.47  5552.8  380.66  5659.0  387.38  5711.9  389.18  5771.1  387.11
#Mann=8,-1,0
  4014.8    0.12       0  4366.7    0.05       0  4489.1    0.16       0
  4570.3    0.05       0  4807.1    0.12       0  5003.7    0.07       0
  5015.9    0.12       0  5659.0    0.16       0
Bank Sta=4370,5552.8
Exp/Cntr=0.3,0.1

Type RM Length L Ch R = 1,13804,607,607,607
BEGIN DESCRIPTION:
LITTLE DRY CREEK 14.0
END DESCRIPTION:
XS GIS Cut Line= 3
      2914438.29      6994093.97      2914375.00      6995375.00
      2914563.30      6995687.68
#Sta/Elev= 30
  3685.3  407.85  3976.7  392.14  4116.9  390.00  4277.7  379.81  4657.5  375.66
  4717.6  377.50  4737.6  374.83  4767.7  377.17  4957.9  378.24  4991.2  376.72
  4997.0  369.97  5006.4  366.83  5006.9  366.03  5018.7  366.83  5026.3  369.75
  5033.9  376.99  5049.4  378.10  5092.2  377.11  5107.7  371.76  5119.6  374.96
  5150.4  372.26  5178.0  378.04  5224.2  376.28  5230.1  378.13  5236.4  375.31
  5259.7  377.84  5267.0  374.66  5272.1  376.66  5284.8  379.81  5332.9  383.25
#Mann=4,-1,0
  3685.3    0.12       0  5006.4    0.07       0  5018.7    0.12       0
  5272.1    0.16       0
Bank Sta=4277.7,5284.8
Exp/Cntr=0.3,0.1

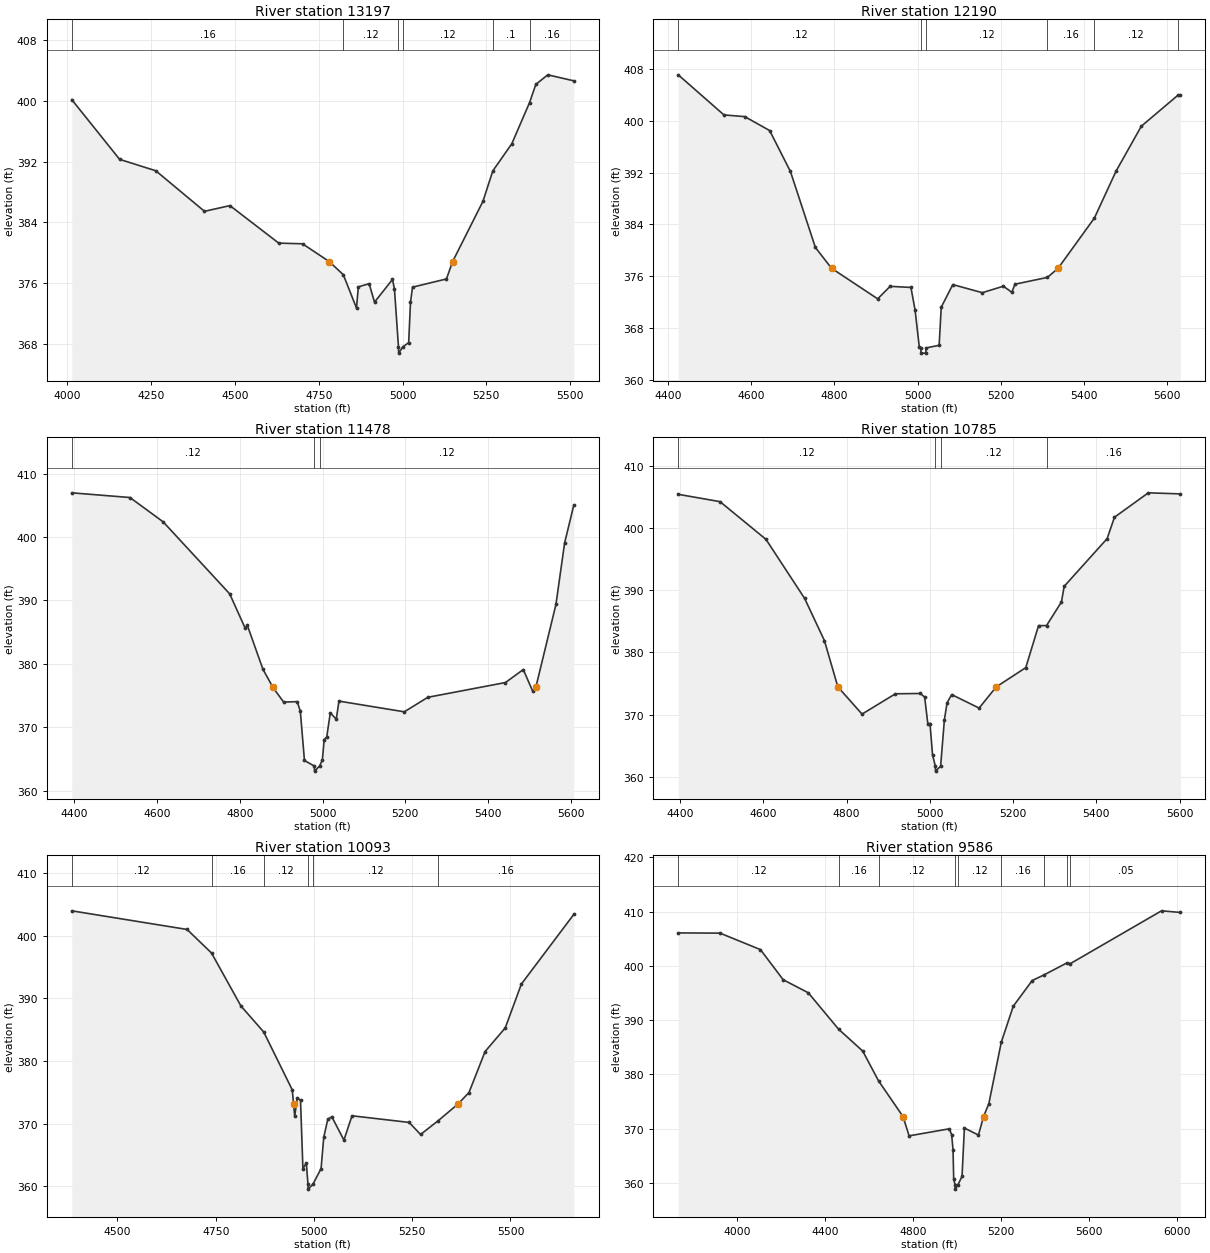
Type RM Length L Ch R = 1,13197,1007,1007,1007
BEGIN DESCRIPTION:
LITTLE DRY CREEK 13.0
END DESCRIPTION:
XS GIS Cut Line= 3
      2913651.84      6994562.68      2914075.21      6995610.51
      2914286.67      6995910.80
#Sta/Elev= 30
  4013.5  400.14  4156.2  392.29  4264.1  390.79  4409.3  385.46  4485.2  386.21
  4630.8  381.28  4701.7  381.19  4781.6  378.85  4823.4  377.12  4862.7  372.74
  4868.1  375.53  4900.4  375.95  4916.4  373.52  4970.0  376.50  4975.9  375.26
  4987.9  367.62  4988.4  366.82  5000.5  367.62  5018.3  368.21  5023.7  373.49
  5029.8  375.49  5131.0  376.57  5149.3  378.85  5239.8  386.77  5269.2  390.77
  5326.0  394.35  5378.9  399.76  5397.5  402.14  5433.2  403.40  5510.9  402.61
#Mann=6,-1,0
  4013.5    0.16       0  4823.4    0.12       0  4987.9    0.07       0
  5000.5    0.12       0  5269.2     0.1       0  5378.9    0.16       0
Bank Sta=4781.6,5149.3
Exp/Cntr=0.3,0.1

Type RM Length L Ch R = 1,12190,712,712,712
BEGIN DESCRIPTION:
LITTLE DRY CREEK 12.0
END DESCRIPTION:
XS GIS Cut Line= 3
      2913575.00      6995374.98      2913575.00      6995975.00
      2914175.00      6996075.00
#Sta/Elev= 30
  4424.0  407.09  4534.0  400.90  4584.0  400.64  4644.0  398.49  4694.0  392.17
  4754.0  380.45  4792.9  377.23  4904.0  372.51  4934.0  374.44  4984.0  374.27
  4994.0  370.77  5004.0  365.14  5007.7  364.93  5008.2  364.13  5019.8  364.13
  5020.3  364.93  5051.9  365.34  5057.0  371.23  5084.8  374.71  5155.8  373.46
  5206.5  374.46  5226.8  373.52  5234.4  374.77  5312.5  375.82  5338.2  377.23
  5425.6  384.99  5477.7  392.23  5538.5  399.16  5625.8  403.90  5632.3  403.92
#Mann=6,-1,0
  4424.0    0.12       0  5007.7    0.07       0  5020.3    0.12       0
  5312.5    0.16       0  5425.6    0.12       0  5625.8    0.16       0
Bank Sta=4792.9,5338.2
Exp/Cntr=0.3,0.1

Type RM Length L Ch R = 1,11478,693,693,693
BEGIN DESCRIPTION:
LITTLE DRY CREEK 11.0
END DESCRIPTION:
XS GIS Cut Line= 3
      2913075.00      6995825.03      2913125.00      6996425.00
      2913625.01      6996775.01
#Sta/Elev= 30
  4394.5  406.98  4535.0  406.24  4615.2  402.40  4775.8  391.04  4813.4  385.59
  4818.4  386.08  4856.1  379.14  4880.4  376.26  4906.2  373.95  4938.9  374.03
  4946.4  372.52  4956.4  364.74  4980.2  363.86  4980.7  363.06  4992.8  363.86
  4999.6  364.79  5004.0  368.05  5010.1  368.41  5018.8  372.26  5033.2  371.26
  5039.7  374.11  5197.5  372.42  5254.2  374.71  5441.7  377.04  5484.8  379.09
  5507.1  375.74  5515.0  376.26  5563.7  389.37  5584.6  399.07  5606.9  405.07
#Mann=3,-1,0
  4394.5    0.12       0  4980.2    0.07       0  4992.8    0.12       0
Bank Sta=4880.4,5515
Exp/Cntr=0.3,0.1

Type RM Length L Ch R = 1,10785,692,692,692
BEGIN DESCRIPTION:
LITTLE DRY CREEK 10.0
END DESCRIPTION:
XS GIS Cut Line= 3
      2912575.00      6995924.97      2912525.00      6996525.00
      2912775.02      6997075.03
#Sta/Elev= 30
  4395.6  405.45  4496.0  404.27  4606.4  398.20  4699.2  388.70  4746.8  381.91
  4779.1  374.45  4837.2  370.07  4917.4  373.34  4977.6  373.39  4987.7  372.80
  4995.2  368.55  5000.5  368.55  5006.5  363.56  5013.3  361.69  5013.8  360.89
  5026.0  361.69  5035.1  369.19  5041.6  371.90  5052.6  373.21  5118.5  371.04
  5159.6  374.45  5230.6  377.55  5261.3  384.31  5280.5  384.32  5316.3  388.12
  5322.9  390.64  5426.1  398.32  5443.7  401.76  5525.0  405.69  5601.9  405.52
#Mann=4,-1,0
  4395.6    0.12       0  5013.3    0.07       0  5026.0    0.12       0
  5280.5    0.16       0
Bank Sta=4779.1,5159.6
Exp/Cntr=0.3,0.1

Type RM Length L Ch R = 1,10093,507,507,507
BEGIN DESCRIPTION:
LITTLE DRY CREEK 9.0
END DESCRIPTION:
XS GIS Cut Line= 3
      2912425.00      6995975.00      2911925.00      6996325.00
      2911775.00      6996974.99
#Sta/Elev= 30
  4383.8  404.02  4677.2  401.04  4739.4  397.27  4814.1  388.81  4872.2  384.64
  4944.9  375.37  4948.1  373.13  4951.0  371.15  4957.5  374.10  4965.8  373.71
  4971.9  362.76  4980.6  363.70  4984.7  360.31  4985.2  359.51  4997.5  360.31
  5018.1  362.80  5024.9  367.80  5035.2  370.68  5045.4  371.09  5076.2  367.35
  5096.8  371.24  5242.1  370.18  5271.2  368.25  5315.6  370.43  5366.6  373.13
  5394.4  374.96  5435.4  381.52  5486.7  385.30  5527.8  392.32  5661.2  403.46
#Mann=6,-1,0
  4383.8    0.12       0  4739.4    0.16       0  4872.2    0.12       0
  4984.7    0.07       0  4997.5    0.12       0  5315.6    0.16       0
Bank Sta=4948.1,5366.6
Exp/Cntr=0.3,0.1

Type RM Length L Ch R = 1,9586,992,992,992
BEGIN DESCRIPTION:
Mapping XS 9817bf3c
END DESCRIPTION:
XS GIS Cut Line= 3
      2912651.81      6995785.78      2911484.30      6996241.50
      2911128.39      6997205.07
#Sta/Elev= 30
  3734.5  406.07  3924.3  406.03  4107.9  402.99  4211.2  397.44  4325.3  395.03
  4462.9  388.32  4572.5  384.29  4644.2  378.81  4755.5  372.22  4783.1  368.66
  4965.6  369.96  4976.3  368.88  4982.7  366.13  4985.7  360.64  4992.1  359.64
  4992.6  358.84  5004.9  359.64  5023.5  361.18  5034.3  370.10  5098.1  368.81
  5121.4  372.22  5145.3  374.59  5201.9  385.93  5256.3  392.56  5342.3  397.29
  5398.0  398.37  5501.4  400.57  5516.0  400.42  5929.6  410.14  6015.0  409.84
#Mann=9,-1,0
  3734.5    0.12       0  4462.9    0.16       0  4644.2    0.12       0
  4992.1    0.07       0  5004.9    0.12       0  5201.9    0.16       0
  5398.0    0.12       0  5501.4    0.16       0  5516.0    0.05       0
Bank Sta=4755.5,5121.4
Exp/Cntr=0.3,0.1

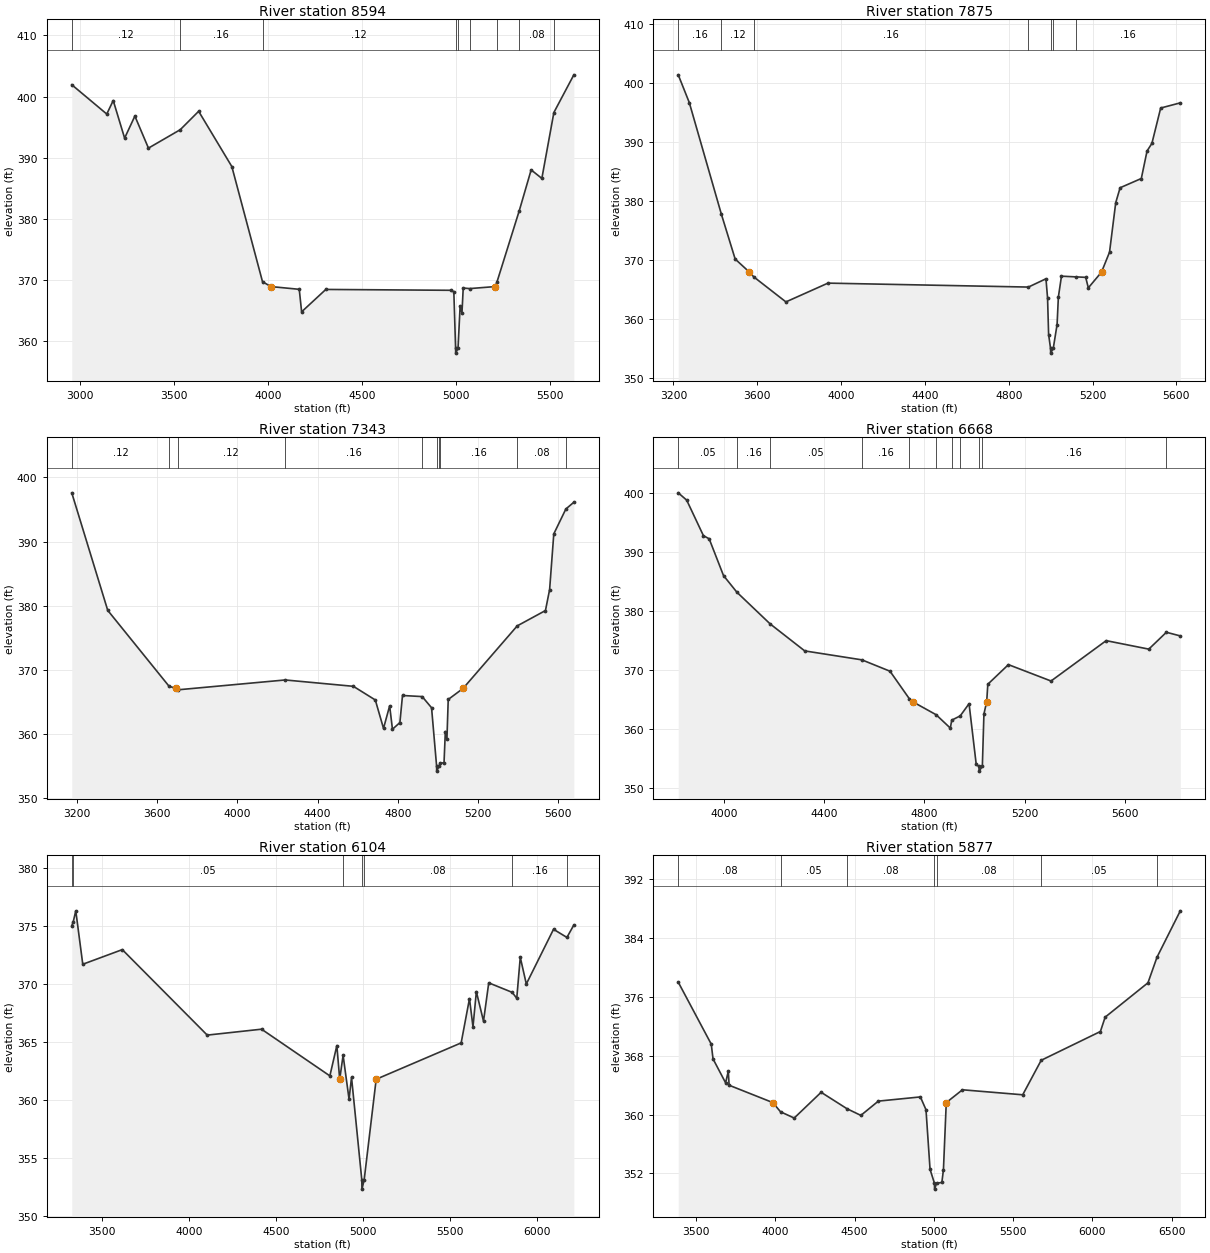
Type RM Length L Ch R = 1,8594,719,719,719
BEGIN DESCRIPTION:
LITTLE DRY CREEK 8.0
END DESCRIPTION:
XS GIS Cut Line= 3
      2912773.36      6995694.62      2910725.00      6995975.00
      2910325.03      6996424.97
#Sta/Elev= 30
  2955.1  401.94  3141.2  397.15  3175.5  399.36  3236.1  393.21  3290.6  396.82
  3362.8  391.58  3531.8  394.59  3629.7  397.60  3806.1  388.57  3969.2  369.75
  4013.4  368.95  4164.6  368.50  4177.2  364.82  4305.9  368.48  4972.1  368.34
  4986.5  368.11  4995.9  358.87  4996.4  358.07  5008.8  358.87  5020.0  365.79
  5029.7  364.62  5036.4  368.71  5071.0  368.62  5207.6  368.95  5216.1  369.72
  5334.6  381.37  5397.6  388.02  5454.5  386.63  5518.4  397.40  5624.6  403.56
#Mann=9,-1,0
  2955.1    0.12       0  3531.8    0.16       0  3969.2    0.12       0
  4995.9    0.07       0  5008.8    0.12       0  5071.0    0.16       0
  5216.1    0.12       0  5334.6    0.08       0  5518.4    0.05       0
Bank Sta=4013.4,5207.6
Exp/Cntr=0.3,0.1

Type RM Length L Ch R = 1,7875,532,532,532
BEGIN DESCRIPTION:
LITTLE DRY CREEK 7.0
END DESCRIPTION:
XS GIS Cut Line= 3
      2912658.77      6994996.71      2910925.00      6995425.00
      2910425.01      6995774.99
#Sta/Elev= 30
  3222.7  401.45  3275.5  396.73  3428.7  377.76  3494.4  370.16  3562.4  367.94
  3583.5  367.12  3736.6  362.88  3937.3  366.07  4894.0  365.40  4977.7  366.81
  4985.3  363.56  4990.4  357.33  4999.6  354.98  5000.1  354.18  5012.5  354.98
  5030.8  359.04  5036.9  363.70  5051.7  367.25  5122.1  367.13  5167.3  367.05
  5179.9  365.27  5242.8  367.94  5281.1  371.33  5310.7  379.74  5331.6  382.27
  5432.8  383.84  5460.2  388.52  5483.3  389.80  5525.2  395.81  5618.9  396.69
#Mann=7,-1,0
  3222.7    0.16       0  3428.7    0.12       0  3583.5    0.16       0
  4894.0    0.12       0  4999.6    0.07       0  5012.5    0.12       0
  5122.1    0.16       0
Bank Sta=3562.4,5242.8
Exp/Cntr=0.3,0.1

Type RM Length L Ch R = 1,7343,675,675,675
BEGIN DESCRIPTION:
LITTLE DRY CREEK 6.0
END DESCRIPTION:
XS GIS Cut Line= 3
      2912336.70      6994773.62      2910549.10      6995146.62
      2910125.02      6995674.98
#Sta/Elev= 30
  3173.9  397.61  3353.2  379.29  3659.0  367.46  3694.3  367.12  3701.4  366.90
  4238.0  368.44  4578.1  367.45  4687.5  365.32  4728.4  360.89  4759.0  364.41
  4773.0  360.76  4810.1  361.80  4823.1  366.02  4921.2  365.85  4968.0  364.11
  4993.1  355.03  4993.6  354.23  5006.0  355.03  5009.7  355.43  5030.2  355.55
  5036.7  360.40  5044.6  359.21  5051.1  365.40  5125.1  367.12  5395.2  376.87
  5535.9  379.26  5556.7  382.53  5577.5  391.21  5637.7  395.09  5677.5  396.14
#Mann=10,-1,0
  3173.9    0.12       0  3659.0    0.16       0  3701.4    0.12       0
  4238.0    0.16       0  4921.2    0.12       0  4993.1    0.07       0
  5006.0    0.12       0  5009.7    0.16       0  5395.2    0.08       0
  5637.7    0.05       0
Bank Sta=3694.3,5125.1
Exp/Cntr=0.3,0.1

Type RM Length L Ch R = 1,6668,564,564,564
BEGIN DESCRIPTION:
Mapping XS 8bf24bc1
END DESCRIPTION:
XS GIS Cut Line= 4
      2910874.57      6993547.24      2910447.51      6994312.83
      2910270.43      6994703.45      2910265.22      6995400.70
#Sta/Elev= 30
  3817.9  400.02  3851.6  398.78  3918.4  392.75  3941.3  392.22  3998.5  385.98
  4052.0  383.15  4184.5  377.78  4322.4  373.20  4550.5  371.68  4662.7  369.75
  4740.3  365.05  4752.5  364.59  4846.6  362.37  4903.3  360.10  4908.9  361.45
  4942.7  362.17  4978.0  364.24  5006.6  353.94  5017.4  353.60  5018.2  352.80
  5031.0  353.60  5037.3  362.49  5048.4  364.59  5052.8  367.54  5135.0  370.87
  5305.0  368.09  5525.0  374.94  5695.0  373.50  5765.1  376.36  5820.7  375.74
#Mann=11,-1,0
  3817.9    0.05       0  4052.0    0.16       0  4184.5    0.05       0
  4550.5    0.16       0  4740.3    0.05       0  4846.6    0.16       0
  4908.9    0.12       0  4942.7    0.16       0  5017.4    0.07       0
  5031.0    0.16       0  5765.1    0.08       0
Bank Sta=4752.5,5048.4
Exp/Cntr=0.3,0.1

Type RM Length L Ch R = 1,6104,227,227,227
BEGIN DESCRIPTION:
Mapping XS 14cfb677
END DESCRIPTION:
XS GIS Cut Line= 4
      2910343.35      6992422.18      2910176.68      6993864.91
      2910150.63      6994463.87      2910239.07      6995291.00
#Sta/Elev= 30
  3325.6  375.03  3333.3  375.32  3348.6  376.31  3388.8  371.71  3615.8  372.97
  4103.6  365.61  4415.6  366.12  4808.0  362.10  4848.1  364.71  4864.5  361.81
  4884.0  363.87  4918.2  360.09  4932.4  361.97  4991.4  353.15  4992.2  352.35
  5005.0  353.15  5074.0  361.81  5562.1  364.94  5609.9  368.75  5630.0  366.32
  5649.4  369.35  5690.4  366.81  5720.5  370.11  5855.3  369.29  5881.4  368.78
  5901.6  372.31  5936.3  370.01  6092.6  374.72  6169.5  374.02  6209.3  375.09
#Mann=7,-1,0
  3325.6    0.16       0  3333.3    0.05       0  4884.0    0.08       0
  4991.4    0.07       0  5005.0    0.08       0  5855.3    0.16       0
  6169.5    0.08       0
Bank Sta=4864.5,5074
Exp/Cntr=0.3,0.1

Type RM Length L Ch R = 1,5877,467,467,467
BEGIN DESCRIPTION:
Mapping XS 2f7d5077
END DESCRIPTION:
XS GIS Cut Line= 5
      2910161.05      6992307.63      2910077.72      6993156.58
      2910025.63      6993890.95      2910015.22      6994411.79
      2910041.26      6995469.08
#Sta/Elev= 30
  3387.6  377.99  3596.0  369.56  3607.1  367.56  3686.4  364.31  3703.5  365.88
  3708.5  363.98  3984.5  361.62  4033.0  360.37  4119.2  359.52  4289.2  363.02
  4452.1  360.79  4539.8  359.88  4650.1  361.82  4915.4  362.39  4950.8  360.65
  4976.4  352.55  5004.1  350.66  5004.9  349.86  5017.8  350.66  5050.9  350.77
  5060.9  352.50  5078.7  361.62  5180.9  363.36  5561.0  362.68  5677.7  367.37
  6051.2  371.28  6081.2  373.23  6351.3  377.90  6408.6  381.39  6555.4  387.68
#Mann=7,-1,0
  3387.6    0.08       0  4033.0    0.05       0  4452.1    0.08       0
  5004.1    0.07       0  5017.8    0.08       0  5677.7    0.05       0
  6408.6    0.16       0
Bank Sta=3984.5,5078.7
Exp/Cntr=0.3,0.1

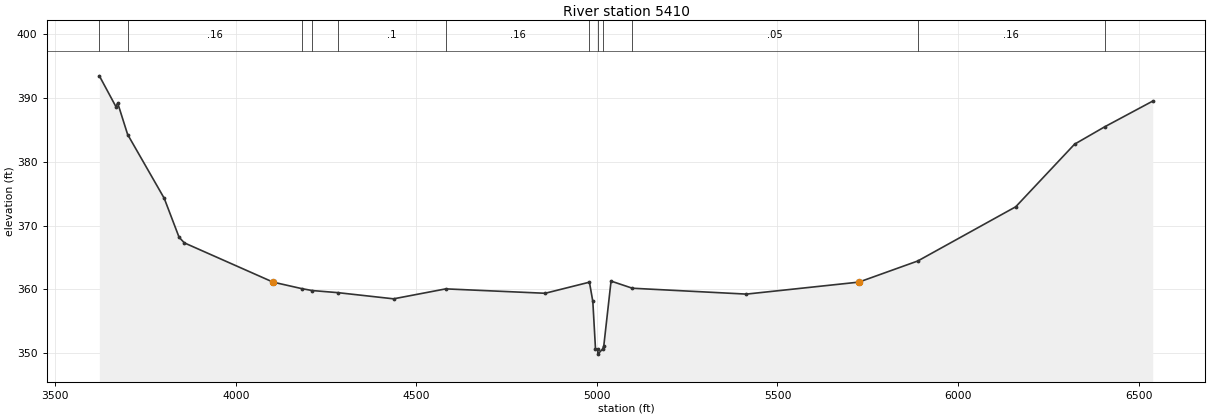
Type RM Length L Ch R = 1,5410,593,593,593
BEGIN DESCRIPTION:
Mapping XS 0c61c477
END DESCRIPTION:
XS GIS Cut Line= 3
      2910030.85      6992229.46      2909754.80      6993474.29
      2909515.22      6995099.25
#Sta/Elev= 30
  3621.8  393.48  3667.6  388.66  3672.7  389.20  3700.2  384.28  3801.6  374.27
  3842.6  368.18  3857.3  367.29  4102.9  361.14  4182.4  360.12  4211.0  359.82
  4282.1  359.49  4436.7  358.52  4581.3  360.08  4856.6  359.39  4979.2  361.13
  4988.6  358.11  4996.0  350.68  5001.9  350.65  5002.7  349.85  5015.6  350.65
  5018.9  351.10  5039.1  361.30  5098.1  360.18  5413.9  359.26  5725.4  361.14
  5888.5  364.45  6159.9  372.95  6322.8  382.76  6406.4  385.49  6539.4  389.52
#Mann=12,-1,0
  3621.8    0.05       0  3700.2    0.16       0  4182.4    0.05       0
  4211.0    0.16       0  4282.1     0.1       0  4581.3    0.16       0
  4979.2    0.12       0  5001.9    0.07       0  5015.6    0.12       0
  5098.1    0.05       0  5888.5    0.16       0  6406.4    0.05       0
Bank Sta=4102.9,5725.4
Exp/Cntr=0.3,0.1