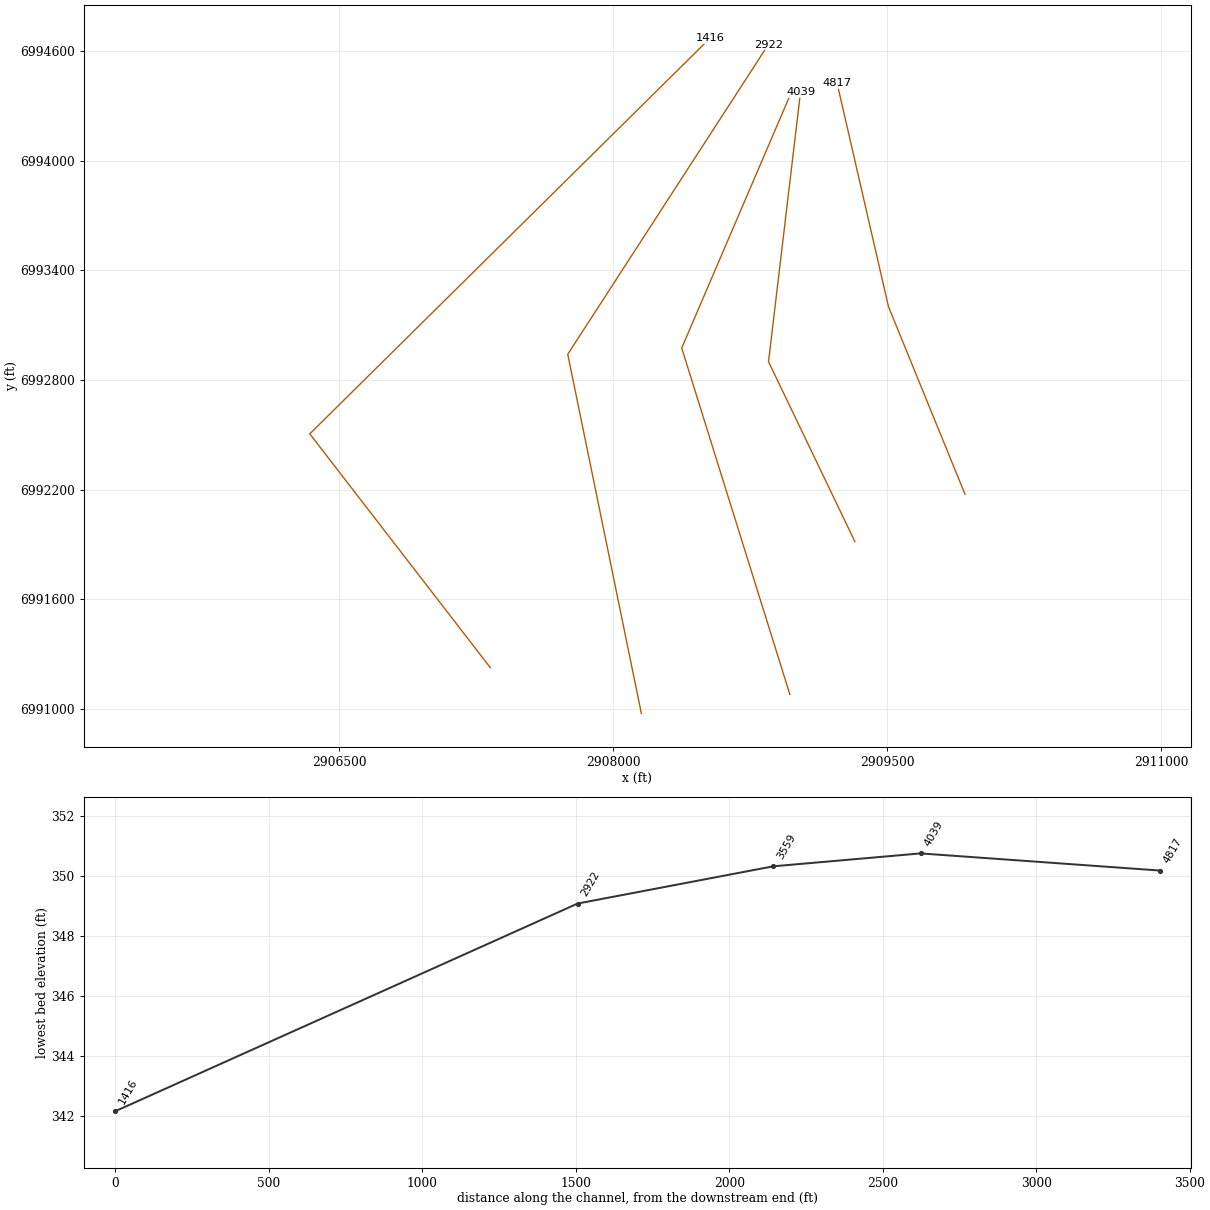
HEC-RAS study LITTLE DRY CREEK.prj: LITTLE DRY CREEK Base Level Engineering

--- LITTLE DRY CREEK.g01 (geometry) --- (continued)

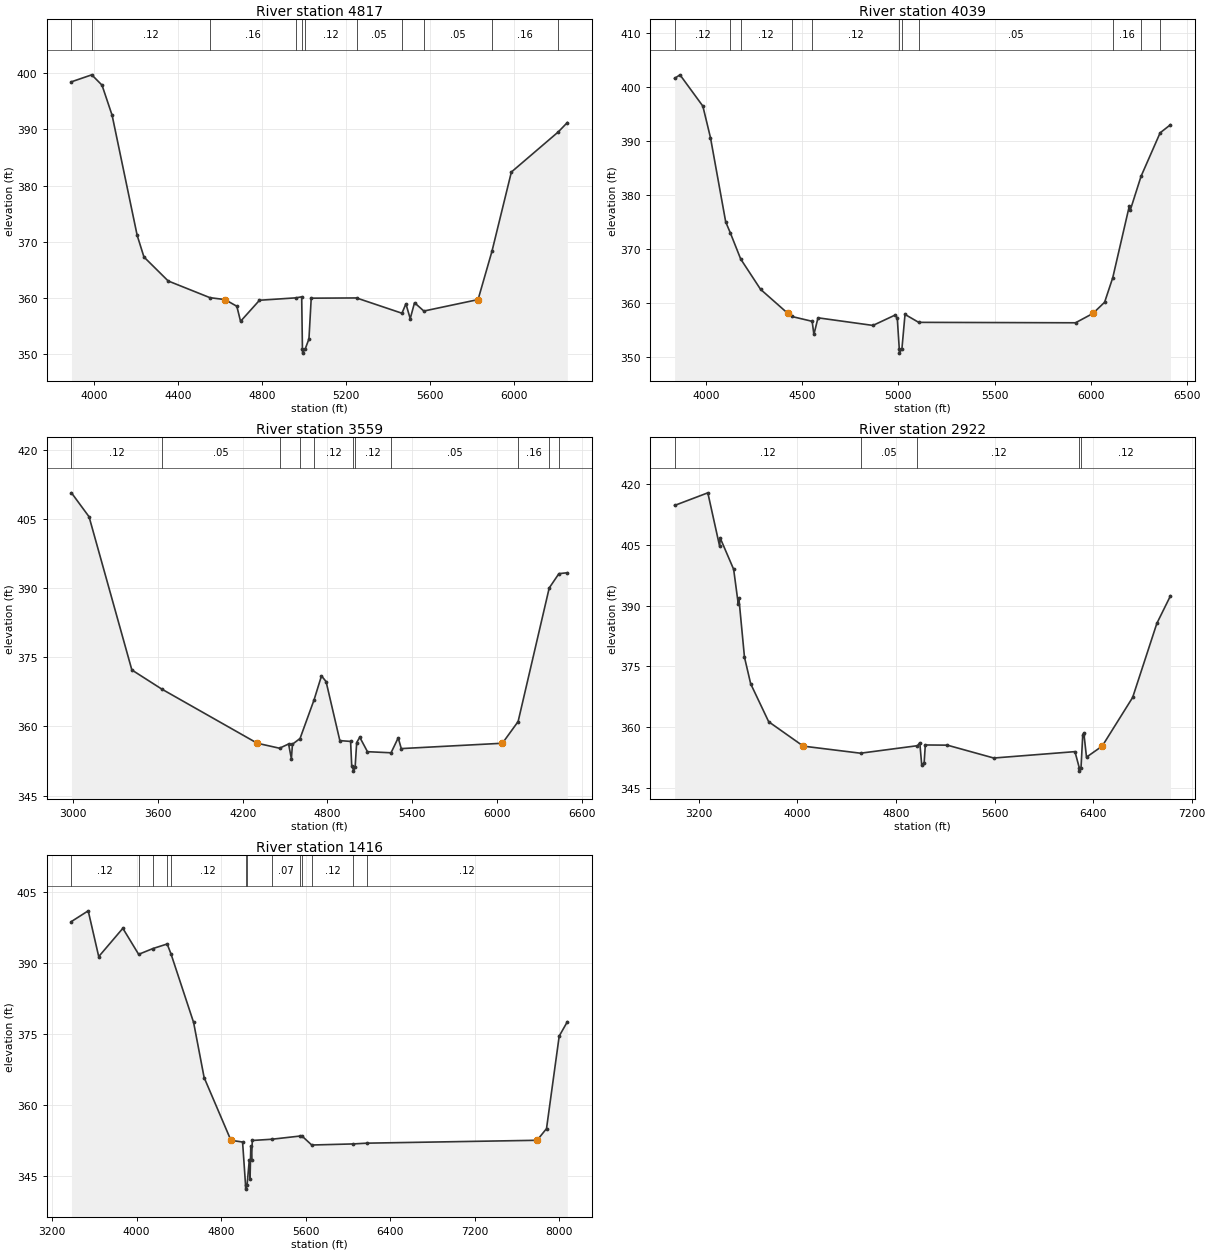
Type RM Length L Ch R = 1,4817,778,778,778
BEGIN DESCRIPTION:
LITTLE DRY CREEK 4.0
END DESCRIPTION:
XS GIS Cut Line= 3
      2909925.00      6992175.00      2909506.24      6993201.90
      2909225.00      6994424.99
#Sta/Elev= 30
  3891.0  398.46  3987.8  399.70  4036.7  397.86  4084.8  392.50  4204.2  371.14
  4236.6  367.28  4352.2  363.01  4551.2  360.04  4623.1  359.70  4679.4  358.51
  4697.1  355.83  4787.4  359.58  4961.5  360.01  4988.6  360.19  4992.1  350.97
  4992.9  350.17  5005.8  350.97  5023.2  352.70  5034.0  359.95  5250.0  359.99
  5466.6  357.27  5485.4  358.95  5506.0  356.30  5526.5  359.14  5571.0  357.66
  5829.4  359.70  5895.6  368.29  5988.2  382.40  6211.8  389.54  6255.0  391.21
#Mann=11,-1,0
  3891.0    0.05       0  3987.8    0.12       0  4551.2    0.16       0
  4961.5    0.12       0  4992.1    0.07       0  5005.8    0.12       0
  5250.0    0.05       0  5466.6    0.16       0  5571.0    0.05       0
  5895.6    0.16       0  6211.8    0.05       0
Bank Sta=4623.1,5829.4
Exp/Cntr=0.3,0.1

Type RM Length L Ch R = 1,4039,480,480,480
BEGIN DESCRIPTION:
double LITTLE DRY CREEK 3.0
END DESCRIPTION:
XS GIS Cut Line= 3
      2909322.55      6991915.65      2908850.00      6992900.00
      2909025.01      6994375.05
#Sta/Elev= 30
  3836.9  401.62  3864.9  402.28  3983.7  396.49  4023.4  390.64  4102.5  375.05
  4126.3  373.03  4180.3  368.18  4283.6  362.56  4426.0  358.08  4444.5  357.54
  4551.9  356.63  4560.9  354.19  4582.2  357.28  4867.8  355.87  4984.2  357.81
  4994.3  357.19  5004.6  351.54  5005.4  350.74  5018.4  351.54  5034.5  357.91
  5105.4  356.44  5920.7  356.36  6010.7  358.08  6071.8  360.16  6114.3  364.72
  6199.8  377.91  6204.8  377.17  6261.3  383.49  6360.4  391.54  6414.2  393.04
#Mann=11,-1,0
  3836.9    0.12       0  4126.3    0.16       0  4180.3    0.12       0
  4444.5    0.16       0  4551.9    0.12       0  5004.6    0.07       0
  5018.4    0.12       0  5105.4    0.05       0  6114.3    0.16       0
  6261.3    0.12       0  6360.4    0.05       0
Bank Sta=4426,6010.7
Exp/Cntr=0.3,0.1

Type RM Length L Ch R = 1,3559,637,637,637
BEGIN DESCRIPTION:
LITTLE DRY CREEK 2.0
END DESCRIPTION:
XS GIS Cut Line= 3
      2908966.59      6991079.60      2908375.00      6992975.00
      2908974.99      6994374.97
#Sta/Elev= 30
  2988.7  410.70  3113.2  405.51  3416.1  372.26  3626.8  368.13  4303.5  356.36
  4460.9  355.28  4525.1  356.20  4544.8  352.99  4552.4  356.15  4606.1  357.39
  4705.4  365.79  4757.8  370.98  4790.3  369.74  4887.8  356.93  4963.8  356.76
  4971.7  351.47  4981.8  351.11  4982.7  350.31  4995.7  351.11  5006.9  356.52
  5028.7  357.66  5083.1  354.53  5250.0  354.29  5300.7  357.54  5322.4  355.20
  6037.9  356.36  6149.1  361.07  6369.2  390.06  6437.7  393.16  6497.4  393.36
#Mann=11,-1,0
  2988.7    0.12       0  3626.8    0.05       0  4460.9    0.12       0
  4606.1    0.16       0  4705.4    0.12       0  4981.8    0.07       0
  4995.7    0.12       0  5250.0    0.05       0  6149.1    0.16       0
  6369.2    0.12       0  6437.7    0.16       0
Bank Sta=4303.5,6037.9
Exp/Cntr=0.3,0.1

Type RM Length L Ch R = 1,2922,1506,1506,1506
BEGIN DESCRIPTION:
Mapping XS 9d70ba60
END DESCRIPTION:
XS GIS Cut Line= 3
      2908154.08      6990975.46      2907751.31      6992940.70
      2908848.55      6994635.17
#Sta/Elev= 30
  3002.8  414.76  3272.5  417.88  3368.3  404.67  3373.4  406.67  3482.1  398.97
  3519.5  390.41  3524.6  391.79  3569.9  377.25  3620.4  370.66  3766.5  361.28
  4047.2  355.25  4511.7  353.50  4974.3  355.36  4992.9  356.09  5008.5  350.63
  5028.4  351.16  5037.6  355.54  5216.5  355.49  5593.5  352.31  6252.3  353.89
  6287.6  349.87  6288.4  349.07  6301.5  349.87  6315.6  358.07  6324.5  358.46
  6346.0  352.53  6473.4  355.25  6720.6  367.29  6917.0  385.60  7027.6  392.42
#Mann=5,-1,0
  3002.8    0.12       0  4511.7    0.05       0  4974.3    0.12       0
  6287.6    0.07       0  6301.5    0.12       0
Bank Sta=4047.2,6473.4
Exp/Cntr=0.3,0.1

Type RM Length L Ch R = 1,1416,0,0,0
BEGIN DESCRIPTION:
LITTLE DRY CREEK 1.0
END DESCRIPTION:
XS GIS Cut Line= 3
      2907327.68      6991225.46      2906339.66      6992505.24
      2908529.06      6994669.85
#Sta/Elev= 30
  3383.2  398.81  3541.8  401.07  3641.4  391.38  3869.7  397.37  4019.4  391.86
  4155.5  393.09  4289.6  394.05  4327.2  391.85  4539.9  377.43  4639.5  365.77
  4893.1  352.49  5003.6  352.12  5031.9  342.95  5032.8  342.15  5046.0  342.95
  5067.2  348.33  5074.3  344.27  5081.4  351.27  5088.5  348.24  5095.5  352.45
  5279.7  352.71  5552.0  353.40  5564.6  353.42  5658.4  351.49  6051.3  351.72
  6177.9  351.88  7792.1  352.49  7881.6  354.96  8001.8  374.55  8078.8  377.59
#Mann=13,-1,0
  3383.2    0.12       0  4019.4    0.16       0  4155.5    0.12       0
  4289.6    0.16       0  4327.2    0.12       0  5031.9    0.07       0
  5046.0    0.12       0  5279.7    0.07       0  5552.0    0.12       0
  5564.6    0.07       0  5658.4    0.12       0  6051.3    0.07       0
  6177.9    0.12       0
Bank Sta=4893.1,7792.1
Exp/Cntr=0.3,0.1

Chan Stop Cuts=-1