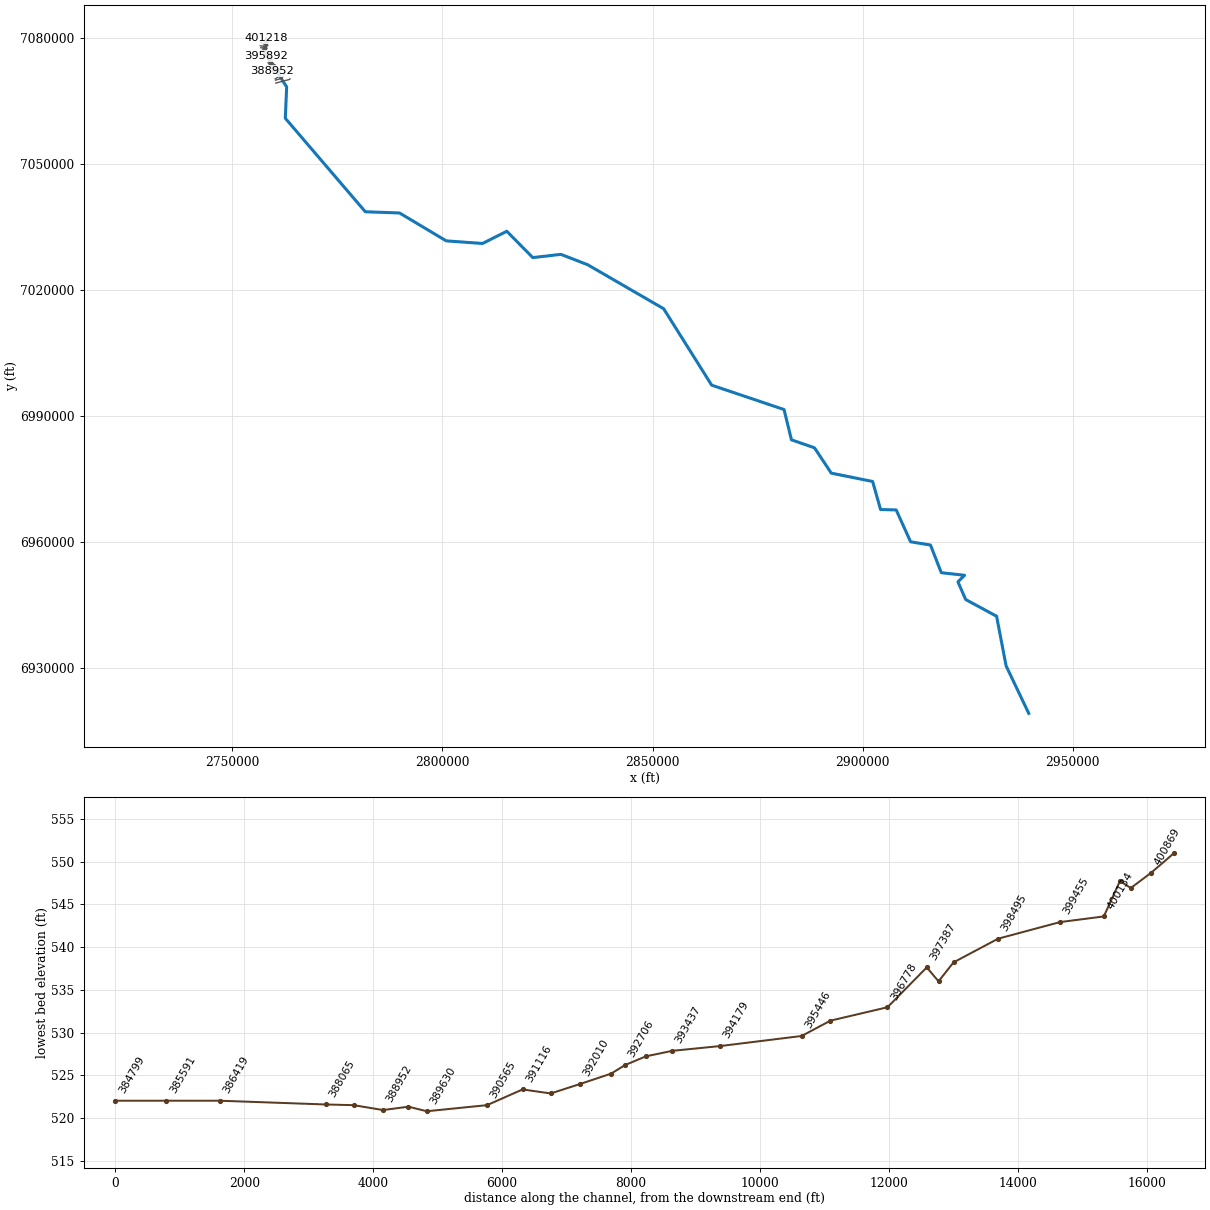
--- Lake Fork Creek.prj (project) ---

Proj Title=Lake Fork Creek Base Level Engineering
Current Plan=p01
Default Exp/Contr=0.3,0.1
English Units
Geom File=g01
Flow File=f01
Plan File=p01
Y Axis Title=Elevation
X Axis Title(PF)=Main Channel Distance
X Axis Title(XS)=Station
BEGIN DESCRIPTION:
Lake Fork Creek
END DESCRIPTION:
DSS Export Rating Curves= 0
DSS Export Rating Curve Sorted= 0
DSS Export Volume Flow Curves= 0
DXF OffsetX= 0
DXF OffsetY= 0
DXF ScaleX= 1
DXF ScaleY= 10

--- Lake Fork Creek.p01 (plan) ---

Plan Title=Multiple Run
Short Identifier=Multiple
Geom File=g01
Flow File=f01
Subcritical Flow
K Sum by GR= 0
Std Step Tol= 0.01
Critical Tol= 0.01
Num of Std Step Trials= 20
Max Error Tol= 0.3
Flow Tol Ratio= 0.001
Split Flow NTrial= 30
Split Flow Tol= 0.02
Split Flow Ratio= 0.02
Log Output Level= 0
Friction Slope Method= 1
Unsteady Friction Slope Method= 2
Unsteady Bridges Friction Slope Method= 1
Parabolic Critical Depth
Global Vel Dist=  1 , 1 , 1
Global Log Level= 0
CheckData=True
Encroach Param= -1, 0, 0, 0
BEGIN DESCRIPTION:
Multiple Run
END DESCRIPTION:

--- Lake Fork Creek.f01 (steady flow) ---

Flow Title=Multiple
Program Version=5.07
Number of Profiles= 7
Profile Names=10-year,25-year,50-year,1pct_min,100-year,1pct_plu,500-year
River Rch & RM=Lake Fork Creek,Reach-1         ,401218
     637     843    1010     598    1190    2380    1660
River Rch & RM=Lake Fork Creek,Reach-1         ,400385
    1110    1530    1870    1130    2250    4500    3280
River Rch & RM=Lake Fork Creek,Reach-1         ,397387
    1190    1630    2000    1210    2410    4800    3500
River Rch & RM=Lake Fork Creek,Reach-1         ,392491
    1810    2510    3090    1880    3750    7480    5500
River Rch & RM=Lake Fork Creek,Reach-1         ,384529
    2090    2930    3630    2220    4440    8850    6610
River Rch & RM=Lake Fork Creek,Reach-1         ,372747
    2990    4240    5310    3280    6540   13100    9920
River Rch & RM=Lake Fork Creek,Reach-1         ,368938
    3520    5020    6310    3900    7790   15500   11900
River Rch & RM=Lake Fork Creek,Reach-1         ,358102
    3700    5280    6620    4090    8160   16300   12400
River Rch & RM=Lake Fork Creek,Reach-1         ,351037
    4330    6210    7830    4860    9700   19400   14900
River Rch & RM=Lake Fork Creek,Reach-1         ,347923
    4610    6620    8350    5190   10400   20700   15900
River Rch & RM=Lake Fork Creek,Reach-1         ,343165
    4880    7010    8860    5510   11000   21900   16900
River Rch & RM=Lake Fork Creek,Reach-1         ,338132
    5240    7510    9470    5880   11700   23400   18000
River Rch & RM=Lake Fork Creek,Reach-1         ,323858
    5490    7880    9940    6180   12300   24600   18900
River Rch & RM=Lake Fork Creek,Reach-1         ,313641
    5510    7880    9920    6150   12300   24500   18700
River Rch & RM=Lake Fork Creek,Reach-1         ,302099
    5890    8440   10600    6600   13200   26300   20200
River Rch & RM=Lake Fork Creek,Reach-1         ,301224
   10900   15800   20200   12600   25200   50200   39100
River Rch & RM=Lake Fork Creek,Reach-1         ,292078
   11300   16400   20900   13100   26100   52000   40500
River Rch & RM=Lake Fork Creek,Reach-1         ,279536
   11600   16800   21400   13300   26600   53100   41200
River Rch & RM=Lake Fork Creek,Reach-1         ,254556
   11500   16600   21000   13100   26100   52000   40200
River Rch & RM=Lake Fork Creek,Reach-1         ,238076
   17400   25100   31800   19900   39600   79000   61200
River Rch & RM=Lake Fork Creek,Reach-1         ,219208
   20400   29400   37400   23300   46500   92700   71800
River Rch & RM=Lake Fork Creek,Reach-1         ,214250
   20500   29500   37300   23200   46300   92400   71100
River Rch & RM=Lake Fork Creek,Reach-1         ,191298
   27600   39800   50600   31600   63100  126000   97800
River Rch & RM=Lake Fork Creek,Reach-1         ,172074
   12200   15900   18000   15900   19500   26100   21100
River Rch & RM=Lake Fork Creek,Reach-1         ,164210
   17200   22700   26200   23700   29100   38800   33700
River Rch & RM=Lake Fork Creek,Reach-1         ,124744
   22100   29600   34600   31900   39100   52200   47800
River Rch & RM=Lake Fork Creek,Reach-1         ,124337
   25900   34700   40900   38100   46800   62400   59000
River Rch & RM=Lake Fork Creek,Reach-1         ,71541
   29100   39300   46700   43900   53900   71900   69800
River Rch & RM=Lake Fork Creek,Reach-1         ,32770
   30000   40600   48300   45500   55900   74500   72700
Boundary for River Rch & Prof#=Lake Fork Creek,Reach-1         , 1
Up Type= 0
Dn Type= 3
Dn Slope=0.00049
Boundary for River Rch & Prof#=Lake Fork Creek,Reach-1         , 2
Up Type= 0
Dn Type= 3
Dn Slope=0.00049
Boundary for River Rch & Prof#=Lake Fork Creek,Reach-1         , 3
Up Type= 0
Dn Type= 3
Dn Slope=0.00049
Boundary for River Rch & Prof#=Lake Fork Creek,Reach-1         , 4
Up Type= 0
Dn Type= 3
Dn Slope=0.00049
Boundary for River Rch & Prof#=Lake Fork Creek,Reach-1         , 5
Up Type= 0
Dn Type= 3
Dn Slope=0.00049
Boundary for River Rch & Prof#=Lake Fork Creek,Reach-1         , 6
Up Type= 0
Dn Type= 3
Dn Slope=0.00049
Boundary for River Rch & Prof#=Lake Fork Creek,Reach-1         , 7
Up Type= 0
Dn Type= 3
Dn Slope=0.00049
DSS Import GetInterval= 0
DSS Import GetPeak= 0
DSS Import FillOption= 0

--- Lake Fork Creek.g01 (geometry) ---

Geom Title=Existing Conditions
Program Version=5.07

River Reach=Lake Fork Creek ,Reach-1
Reach XY= 30
      2758142.81      7079447.15      2757361.81      7076843.64
      2762903.77      7068254.67      2762587.61      7060780.74
       2781632.9      7038525.59      2789774.38       7038237.6
      2800895.42      7031597.69      2809532.95      7030976.26
       2815311.8      7033885.09      2821496.68      7027618.36
      2828185.05      7028383.01      2834561.94      7025916.48
      2852645.84      7015448.75      2864084.43      6997244.17
      2881309.75      6991446.46      2883073.57      6984234.25
      2888555.52      6982340.57       2892552.6      6976305.63
      2902394.81      6974320.27      2904290.84      6967637.65
      2908002.68      6967547.69      2911435.59      6959960.71
      2916163.37       6959190.8      2918749.32      6952598.46
      2924280.94      6951994.32      2922705.29      6950435.58
      2924540.15      6946219.59      2931906.31      6942239.96
      2934175.59      6930410.71        2939562.        6919116.

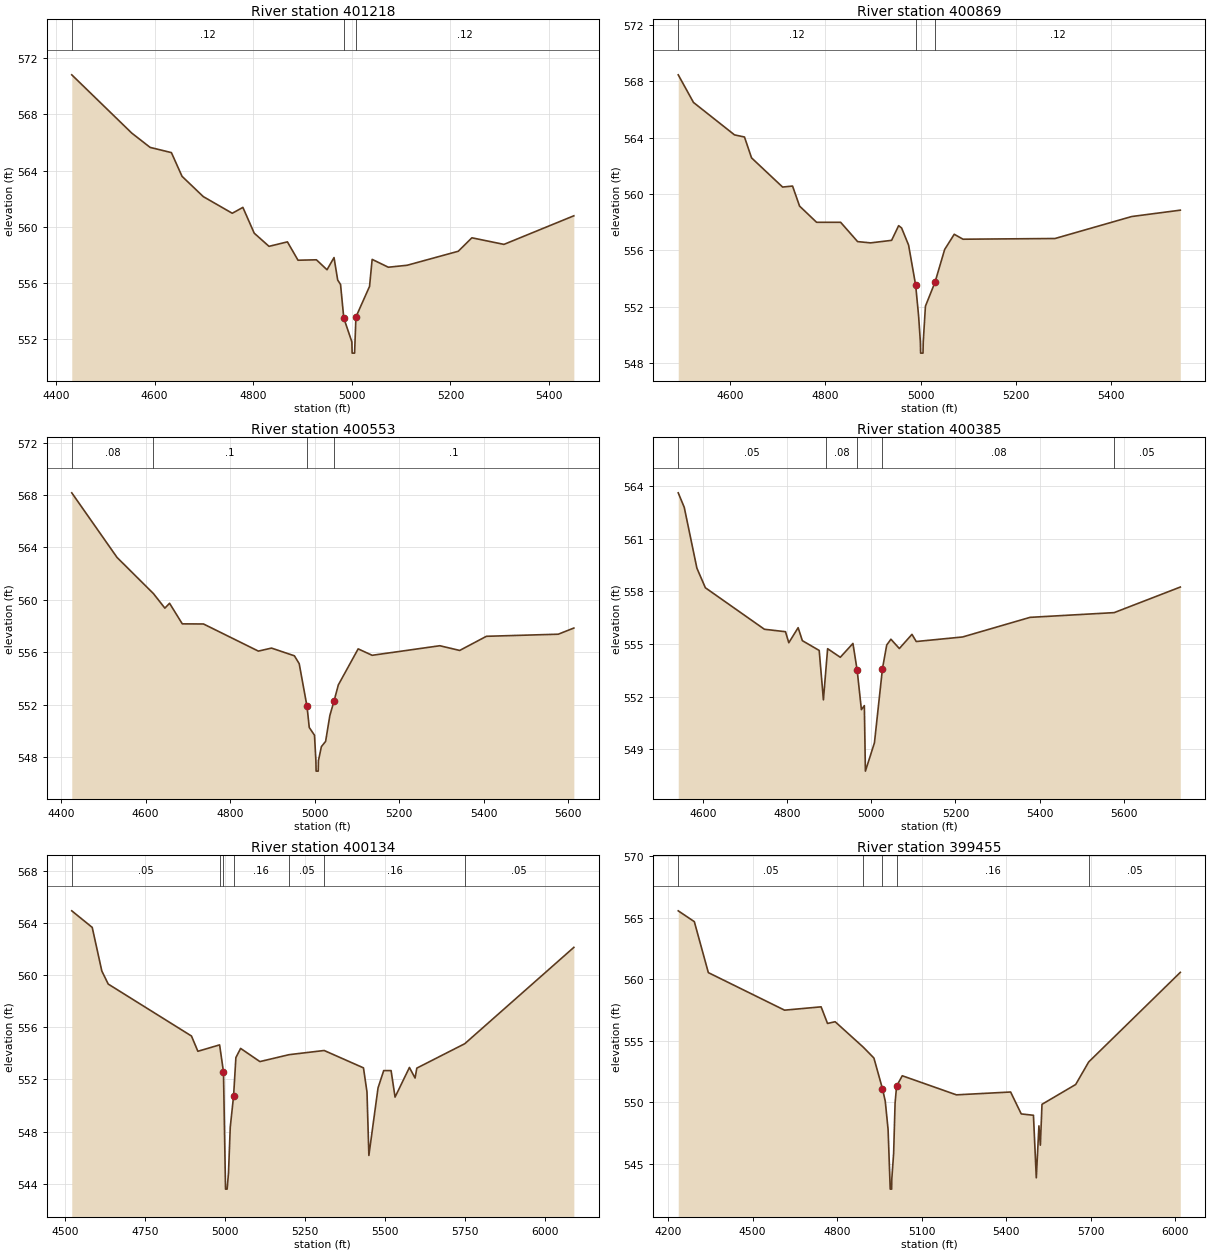
Type RM Length L Ch R = 1 ,401218  ,349,349,349
BEGIN DESCRIPTION:
LFC193
END DESCRIPTION:
XS GIS Cut Line= 3
      2758605.02      7079088.85      2758125.86      7079366.62
      2757990.61      7079810.52
#Sta/Elev= 30
  4432.2  570.83  4553.9  566.67  4591.1  565.65  4634.2  565.28  4655.7  563.59
  4698.8  562.14  4757.6  560.95  4779.1  561.37  4802.1  559.53  4832.1  558.59
  4869.4  558.91  4890.9   557.6  4928.2  557.63  4949.7  556.92  4963.9  557.79
  4971.3  556.19  4977.1  555.87  4983.7  553.47  5000.1  551.77  5000.6  550.97
  5005.6  550.97  5008.3  553.55  5035.9  555.73  5041.2  557.66    5074   557.1
  5112.1  557.24  5215.8  558.24  5243.4   559.2  5308.4  558.73  5450.1  560.77
#Mann= 3 ,-1 , 0
  4432.2     .12       0  4983.7     .05       0  5008.3     .12       0
Bank Sta=4983.7,5008.3
XS Rating Curve= 0 ,0
Exp/Cntr=0.3,0.1

Type RM Length L Ch R = 1 ,400869  ,316,316,316
BEGIN DESCRIPTION:
LFC192
END DESCRIPTION:
XS GIS Cut Line= 3
      2758393.24      7078769.38      2757980.03      7079064.54
        2757921.      7079606.23
#Sta/Elev= 30
    4492  568.45    4524  566.49    4610  564.19  4630.9  564.04  4645.7  562.56
  4710.8  560.49  4731.7  560.56  4746.4  559.14  4782.1  557.99  4832.5  557.99
  4868.1  556.62  4895.4  556.53  4939.4  556.71  4954.1  557.75  4960.3  557.59
    4975  556.37  4989.8  553.53  4995.9  551.38  4999.7  549.51  5000.2  548.71
  5005.2  548.71  5005.7  549.51  5010.3  552.04  5030.4  553.74  5050.6  556.06
  5070.7  557.14  5089.1  556.79    5282  556.84  5442.9   558.4  5544.7  558.85
#Mann= 3 ,-1 , 0
    4492     .12       0  4989.8     .05       0  5030.4     .12       0
Bank Sta=4989.8,5030.4
XS Rating Curve= 0 ,0
Exp/Cntr=0.3,0.1

Type RM Length L Ch R = 1 ,400553  ,168,168,168
BEGIN DESCRIPTION:
LFC0
END DESCRIPTION:
XS GIS Cut Line= 4
      2758365.51      7078610.67      2757921.36      7078649.11
      2757874.38      7078768.68      2757848.84      7079381.76
#Sta/Elev= 30
  4425.4  568.16  4532.5  563.23  4618.6  560.47  4645.7  559.36  4656.8  559.73
  4686.9  558.16  4737.1  558.15  4866.9  556.08    4898  556.31  4952.2  555.72
  4963.5  555.12    4982  551.86  4987.3  550.25  4999.7  549.66    5003  547.72
  5003.5  546.92  5008.5  546.92    5009  547.72    5016  548.79    5026  549.19
    5036  551.16    5046  552.28  5056.1   553.5    5103  556.25  5136.1  555.76
  5296.3  556.49  5343.2  556.13  5406.4  557.21  5576.5  557.37  5613.3  557.84
#Mann= 4 ,-1 , 0
  4425.4     .08       0  4618.6      .1       0    4982     .05       0
    5046      .1       0
Bank Sta=4982,5046
XS Rating Curve= 0 ,0
Exp/Cntr=0.3,0.1

Type RM Length L Ch R = 1 ,400385  ,251,251,251
BEGIN DESCRIPTION:
LFC6
END DESCRIPTION:
XS GIS Cut Line= 4
      2758109.28      7078465.48      2757797.52      7078482.56
      2757788.98      7078632.02       2757750.6      7079361.18
#Sta/Elev= 30
  4541.8  563.63  4556.1   562.8  4586.1  559.33  4606.2  558.21  4746.4  555.84
  4796.5   555.7  4804.3  555.07  4826.5  555.93  4836.5  555.19  4876.5  554.63
  4886.5  551.81  4892.1  553.45  4896.5  554.73  4926.6  554.24  4956.6  555.03
  4966.7  553.49  4976.7  551.25  4983.7  551.48  4986.2  547.74  5007.7  549.36
  5026.7  553.59  5036.8  554.94  5046.8  555.27  5066.8  554.74  5096.8  555.55
  5106.9  555.14    5217   555.4  5377.2  556.52  5576.9  556.79  5733.9  558.25
#Mann= 5 ,-1 , 0
  4541.8     .05       0  4892.1     .08       0  4966.7     .07       0
  5026.7     .08       0  5576.9     .05       0
Bank Sta=4966.7,5026.7
XS Rating Curve= 0 ,0
Exp/Cntr=0.3,0.1

Type RM Length L Ch R = 1 ,400134  ,679,679,679
BEGIN DESCRIPTION:
LFC1
END DESCRIPTION:
XS GIS Cut Line= 3
      2758198.94      7078384.34      2757712.11      7078388.61
      2756725.63      7078832.74
#Sta/Elev= 30
  4521.6  564.92  4585.5  563.65  4615.5  560.31  4635.5  559.31  4895.6  555.33
  4915.6  554.16  4983.5  554.65  4995.6  552.59    5002   543.6    5007   543.6
  5011.3  544.85  5016.8  548.35  5027.2  550.74  5034.4  553.68  5049.2  554.38
  5109.4  553.37  5200.4   553.9  5310.2  554.22    5433  552.89    5444  551.04
  5449.9  546.18  5478.5  551.35  5496.2  552.68  5519.3  552.68  5531.7  550.65
  5576.6  552.92  5594.2  552.11  5599.7  552.87  5749.5  554.74  6090.3  562.12
#Mann= 7 ,-1 , 0
  4521.6     .05       0  4983.5     .16       0  4995.6     .07       0
  5027.2     .16       0  5200.4     .05       0  5310.2     .16       0
  5749.5     .05       0
Bank Sta=4995.6,5027.2
XS Rating Curve= 0 ,0
Exp/Cntr=0.3,0.1

Type RM Length L Ch R = 1 ,399455  ,960,960,960
BEGIN DESCRIPTION:
LFC2
END DESCRIPTION:
XS GIS Cut Line= 4
      2758305.73      7078281.88      2757720.65      7077918.87
      2757566.92      7077901.79      2756640.24      7078046.98
#Sta/Elev= 30
  4235.9  565.55    4293  564.67  4342.7  560.53  4613.1  557.48  4742.8  557.75
  4765.5   556.4  4792.6  556.54  4892.5  554.47  4930.1  553.59  4960.3  551.11
  4970.4  550.08  4980.4  547.78    4988  542.94    4993  542.94  4993.5  543.74
  5000.1  545.85  5005.2  549.93  5010.6  551.31  5030.7  552.15  5222.8   550.6
  5415.1  550.83  5452.8  549.05  5496.1  548.94  5506.2  543.86  5515.5  548.08
  5520.6  546.51  5526.4  549.83  5645.9  551.44    5692  553.27  6017.1  560.55
#Mann= 5 ,-1 , 0
  4235.9     .05       0  4892.5     .16       0  4960.3     .07       0
  5010.6     .16       0    5692     .05       0
Bank Sta=4960.3,5010.6
XS Rating Curve= 0 ,0
Exp/Cntr=0.3,0.1

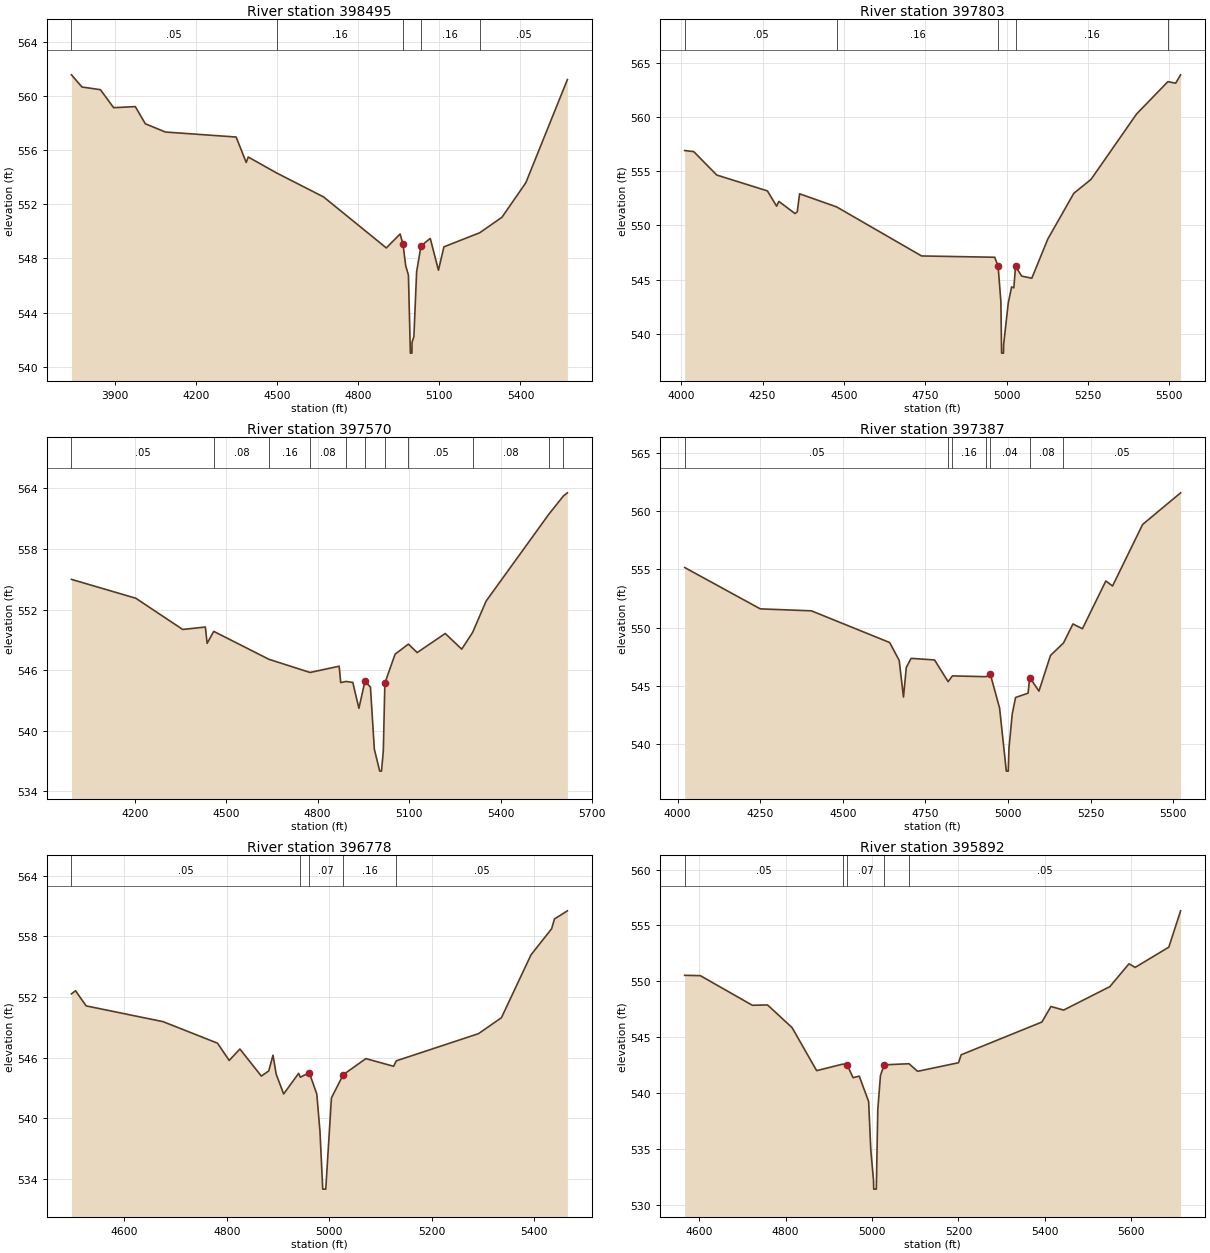
Type RM Length L Ch R = 1 ,398495  ,692,692,692
BEGIN DESCRIPTION:
LFC3
END DESCRIPTION:
XS GIS Cut Line= 3
      2758408.19      7078076.88      2757400.37      7077483.29
      2756742.69      7077572.98
#Sta/Elev= 30
  3740.2  561.58    3779  560.68  3847.4  560.48  3896.1  559.15  3976.2  559.23
  4013.3  557.96  4087.5  557.35    4349  556.98  4386.2   555.1  4393.8   555.5
  4499.9  554.31  4672.3  552.55  4904.2  548.78    4955  549.81  4965.7  549.08
  4975.8  547.46  4985.9  546.77  4993.1     541  4998.8     541  4999.3   541.8
  5006.1  542.22  5016.2  547.02  5032.4  548.93  5066.6  549.48  5096.9  547.13
  5117.1  548.86  5249.3   549.9  5331.8  551.05  5419.9   553.6  5573.6  561.23
#Mann= 5 ,-1 , 0
  3740.2     .05       0  4499.9     .16       0  4965.7     .07       0
  5032.4     .16       0  5249.3     .05       0
Bank Sta=4965.7,5032.4
XS Rating Curve= 0 ,0
Exp/Cntr=0.3,0.1

Type RM Length L Ch R = 1 ,397803  ,233,233,233
BEGIN DESCRIPTION:
LFC4
END DESCRIPTION:
XS GIS Cut Line= 4
      2758079.34      7077590.03      2757430.26      7076958.04
      2757225.28      7076902.52      2756819.79      7076889.72
#Sta/Elev= 30
  4010.6  556.91  4038.5  556.81  4109.2  554.65  4264.8  553.19  4293.1  551.78
  4300.1  552.22  4349.7   551.1  4356.6  551.26  4363.8  552.92  4477.7  551.71
  4738.6  547.19  4963.4  547.07  4973.8  546.23  4982.3  542.98  4984.5  538.23
  4990.3  538.23  4990.8  539.03  5004.9  542.84  5015.2  544.33  5022.1  544.25
  5027.3  546.23  5046.3  545.33  5077.4  545.14  5126.5  548.75  5206.5  552.97
  5259.3  554.25  5399.3  560.28  5495.5  563.26  5519.4  563.12  5534.6  563.89
#Mann= 5 ,-1 , 0
  4010.6     .05       0  4477.7     .16       0  4973.8     .07       0
  5027.3     .16       0  5495.5     .05       0
Bank Sta=4973.8,5027.3
XS Rating Curve= 0 ,0
Exp/Cntr=0.3,0.1

Type RM Length L Ch R = 1 ,397570  ,183,183,183
BEGIN DESCRIPTION:
LFC5
END DESCRIPTION:
XS GIS Cut Line= 6
      2758092.16      7077504.63      2757793.25      7076962.31
      2757592.54      7076787.22      2757417.45       7076761.6
      2757267.99      7076829.92      2756868.31      7076838.43
#Sta/Elev= 30
  3992.1     555  4203.3  553.13  4357.1  550.04  4431.5  550.28  4437.2  548.66
    4459  549.85  4640.4  547.08  4775.1  545.78  4870.6   546.4  4875.6  544.78
  4893.3  544.89  4915.3  544.79  4935.3  542.23  4955.3  544.93  4973.2  544.32
    4986  538.18  5003.6  536.01  5009.4  536.01  5015.4     538  5020.5  544.73
  5054.1  547.59  5097.7  548.59  5126.6  547.75  5218.6  549.64  5272.7  548.09
  5308.2  549.73  5352.8  552.85  5557.8  561.42  5606.4  563.26  5619.5  563.57
#Mann= 11 ,-1 , 0
  3992.1     .05       0    4459     .08       0  4640.4     .16       0
  4775.1     .08       0  4893.3     .16       0  4955.3     .07       0
  5020.5     .16       0  5097.7     .05       0  5308.2     .08       0
  5557.8     .16       0  5606.4     .05       0
Bank Sta=4955.3,5020.5
XS Rating Curve= 0 ,0
Exp/Cntr=0.3,0.1

Type RM Length L Ch R = 1 ,397387  ,609,609,609
BEGIN DESCRIPTION:
LFC7
END DESCRIPTION:
XS GIS Cut Line= 5
      2758207.46      7077419.22      2757925.63       7076876.9
      2757733.46      7076735.98      2757622.43      7076680.46
      2757101.43      7076599.32
#Sta/Elev= 30
  4021.5  555.17  4250.3  551.61  4405.1  551.44    4642  548.71  4670.7  547.17
  4683.7  544.02  4692.2  546.57  4706.8  547.35  4777.8  547.21  4818.8  545.34
  4831.8  545.84  4933.2  545.77  4946.7  545.97  4974.6  543.06  4994.9  537.64
  5000.7  537.64  5002.9   539.6  5012.8  542.55  5022.9  543.98  5060.7  544.35
  5065.8   545.7  5093.7  544.53  5128.6   547.6  5167.9  548.67  5196.5  550.31
  5225.3   549.9  5296.1  554.01  5316.4  553.58  5407.5  558.88  5522.4   561.6
#Mann= 7 ,-1 , 0
  4021.5     .05       0  4818.8     .08       0  4831.8     .16       0
  4933.2     .05       0  4946.7     .04       0  5065.8     .08       0
  5167.9     .05       0
Bank Sta=4946.7,5065.8
XS Rating Curve= 0 ,0
Exp/Cntr=0.3,0.1

Type RM Length L Ch R = 1 ,396778  ,886,886,886
BEGIN DESCRIPTION:
LFC8
END DESCRIPTION:
XS GIS Cut Line= 3
        2758422.      7076747.92      2758010.57      7076440.64
      2757598.25      7076248.75
#Sta/Elev= 30
  4496.5  552.31  4504.4  552.62  4525.2  551.12  4675.3  549.56  4781.6  547.43
  4804.5  545.72  4825.4  546.85  4867.2  544.17  4881.7  544.68    4890  546.24
  4896.2  544.36  4910.8   542.4    4940  544.44  4943.4  544.06  4960.9   544.5
  4975.5  542.39  4981.7   538.7  4987.1  532.98    4993  532.98  5004.1  542.02
  5027.2  544.31  5071.3   545.9  5125.5  545.14  5130.7  545.68  5291.2  548.37
    5336  549.95  5393.7  556.17    5434  558.76  5439.5  559.72  5464.8  560.53
#Mann= 5 ,-1 , 0
  4496.5     .05       0  4943.4     .16       0  4960.9     .07       0
  5027.2     .16       0  5130.7     .05       0
Bank Sta=4960.9,5027.2
XS Rating Curve= 0 ,0
Exp/Cntr=0.3,0.1

Type RM Length L Ch R = 1 ,395892  ,446,446,446
BEGIN DESCRIPTION:
LFC9
END DESCRIPTION:
XS GIS Cut Line= 3
      2758812.65      7076318.24      2758492.34      7076029.19
       2757909.5      7075612.87
#Sta/Elev= 30
  4566.4  550.54  4602.7  550.51    4723  547.86  4758.2  547.89    4815  545.86
  4871.8  542.01  4931.7  542.59    4942  542.56  4956.2  541.38  4970.4  541.52
  4992.1  539.25  4997.2  534.89  5003.4  532.21  5003.9  531.41  5009.9  531.41
  5013.3  538.52  5019.5  541.58  5028.1  542.53  5085.5  542.63  5105.5  541.95
  5200.1  542.72  5206.3  543.43  5393.1  546.36    5414  547.75  5443.4  547.43
  5550.4  549.53  5594.6  551.57    5609  551.25  5686.8  553.06  5714.1  556.31
#Mann= 5 ,-1 , 0
  4566.4     .05       0  4931.7     .16       0    4942     .07       0
  5028.1     .16       0  5085.5     .05       0
Bank Sta=4942,5028.1
XS Rating Curve= 0 ,0
Exp/Cntr=0.3,0.1

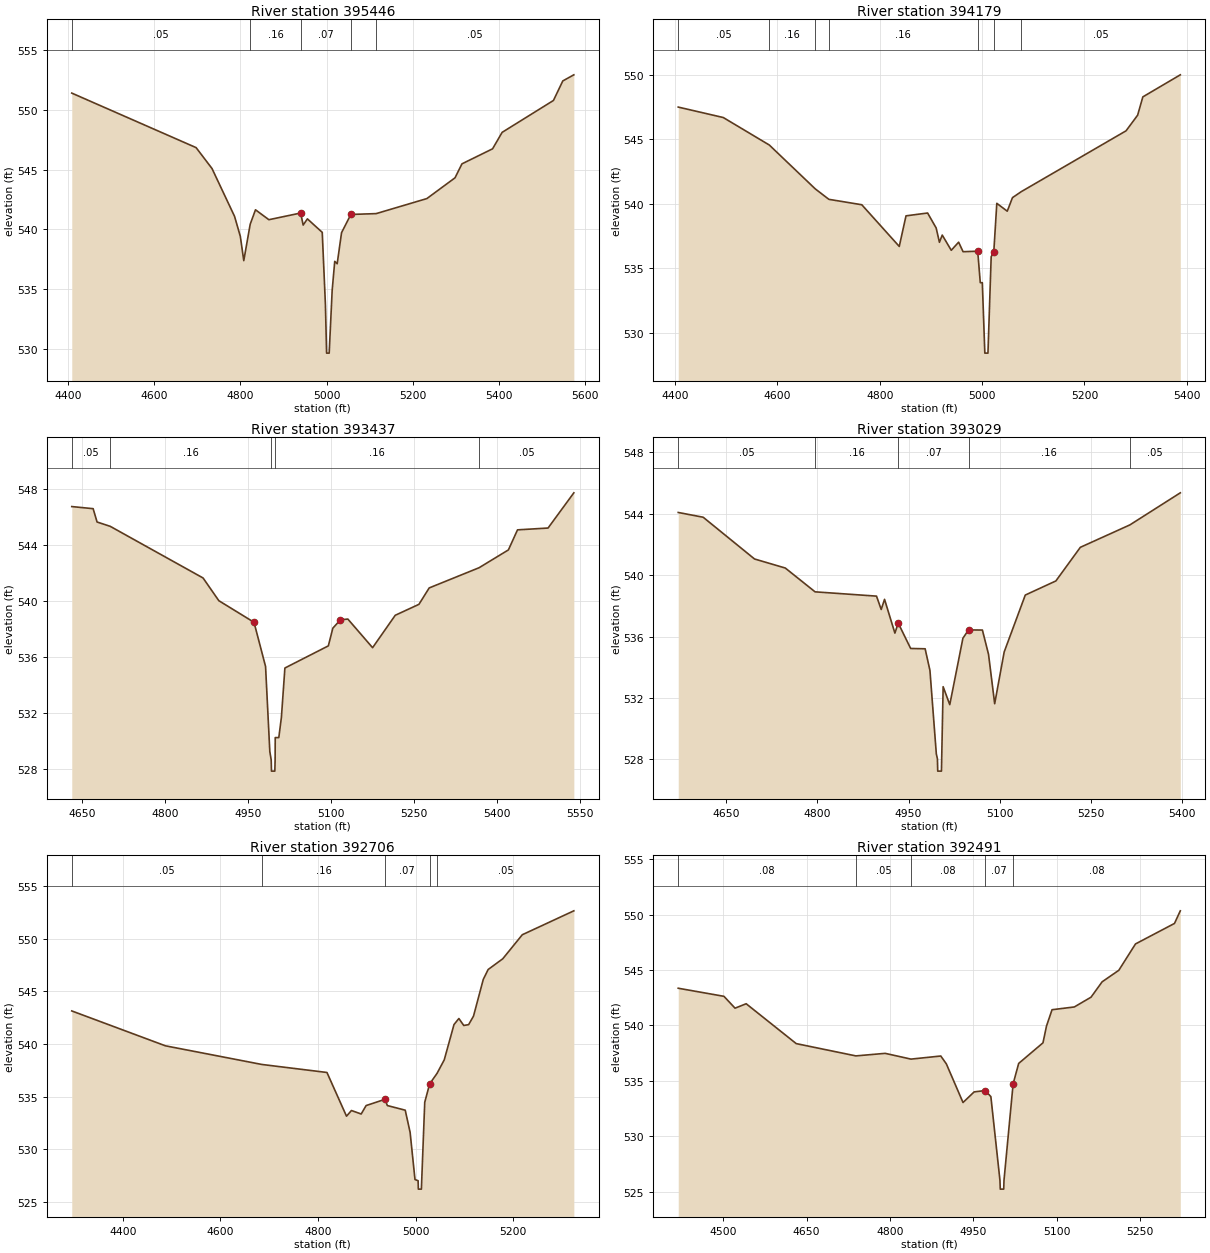
Type RM Length L Ch R = 1 ,395446  ,1267,1267,1267
BEGIN DESCRIPTION:
LFC10
END DESCRIPTION:
XS GIS Cut Line= 4
      2759150.36      7076017.05      2758681.58      7075734.92
       2758629.5      7075643.77      2758179.03      7075396.88
#Sta/Elev= 30
  4408.4  551.41  4697.1  546.84    4734  545.09  4786.4  541.08  4799.8   539.4
  4807.8  537.37  4822.7  540.42    4835  541.63  4866.1   540.8  4939.9  541.36
  4945.7  540.35  4955.5  540.87    4990  539.74  4997.4  533.65  5000.1  529.62
  5006.1  529.62    5013  534.86    5019  537.31  5024.7  537.11  5034.8  539.71
  5056.4  541.24  5115.1  541.31  5232.9  542.57  5298.3  544.31  5314.4  545.48
  5385.5  546.74  5407.7  548.12  5526.8  550.79  5548.6  552.43  5574.2  552.94
#Mann= 5 ,-1 , 0
  4408.4     .05       0  4822.7     .16       0  4939.9     .07       0
  5056.4     .16       0  5115.1     .05       0
Bank Sta=4939.9,5056.4
XS Rating Curve= 0 ,0
Exp/Cntr=0.3,0.1

Type RM Length L Ch R = 1 ,394179  ,742,742,742
BEGIN DESCRIPTION:
LFC11
END DESCRIPTION:
XS GIS Cut Line= 4
      2759238.83      7075458.64       2758837.4      7075263.34
      2758702.85      7075324.11       2758323.1      7075250.33
#Sta/Elev= 30
  4406.4  547.51  4494.4   546.7  4584.3  544.57  4674.1  541.17  4700.7  540.36
    4765  539.94  4838.2  536.71  4851.4  539.08  4893.6   539.3  4910.3  538.14
  4916.7  537.03  4922.2  537.59  4939.8  536.41  4954.2  537.04  4962.9   536.3
  4991.5  536.34  4996.5   533.9  5000.5   533.9  5005.4  528.44  5011.5  528.44
  5017.8  535.91  5022.9  536.28  5028.8  540.05  5049.2  539.44  5059.4  540.49
  5076.8  540.96  5281.3  545.67  5303.9  546.88  5314.1   548.3  5387.3  550.01
#Mann= 7 ,-1 , 0
  4406.4     .05       0  4584.3     .16       0  4674.1     .12       0
  4700.7     .16       0  4991.5     .07       0  5022.9     .16       0
  5076.8     .05       0
Bank Sta=4991.5,5022.9
XS Rating Curve= 0 ,0
Exp/Cntr=0.3,0.1

Type RM Length L Ch R = 1 ,393437  ,408,408,408
BEGIN DESCRIPTION:
LFC12
END DESCRIPTION:
XS GIS Cut Line= 4
      2759234.51      7075400.04      2758995.82      7075115.77
      2758876.46      7075022.46      2758499.41      7074937.95
#Sta/Elev= 30
  4630.6  546.74  4669.3  546.59  4676.4  545.64  4700.3  545.33  4868.3  541.65
  4896.9  540.03  4960.6  538.49  4981.5  535.34  4989.2  529.28  4991.7  528.68
  4992.2  527.88  4998.3  527.88  4998.8  528.68    4999  530.27  5005.5  530.27
  5010.2  531.72  5016.5  535.23  5095.2  536.81  5103.3  538.07  5117.1  538.67
  5130.5  538.72  5175.3  536.68  5216.3  538.99  5259.2  539.77  5277.8  540.94
  5368.1  542.38  5421.2  543.65  5437.7  545.08    5493  545.21  5539.7  547.72
#Mann= 5 ,-1 , 0
  4630.6     .05       0  4700.3     .16       0  4991.7     .07       0
  4998.8     .16       0  5368.1     .05       0
Bank Sta=4960.6,5117.1
XS Rating Curve= 0 ,0
Exp/Cntr=0.3,0.1

Type RM Length L Ch R = 1 ,393029  ,323,323,323
BEGIN DESCRIPTION:
LFC15
END DESCRIPTION:
XS GIS Cut Line= 4
      2759367.75      7074917.56      2759037.92      7074756.11
       2758921.6      7074804.72      2758591.71      7074768.26
#Sta/Elev= 30
  4571.5  544.09  4612.5  543.78  4696.9  541.06  4747.5  540.47  4796.4  538.92
  4897.4  538.64  4905.1  537.77  4910.6  538.43  4927.6  536.23  4933.1  536.88
  4953.5  535.23  4977.3  535.21  4985.2   533.8  4995.7  528.36  4997.5  528.04
    4998  527.24  5004.1  527.24  5006.9  532.74  5017.8  531.57  5039.4   535.9
  5048.7  536.44  5071.4  536.43  5081.5  534.85  5091.6  531.63  5107.2     535
  5141.9  538.71  5192.2  539.63  5232.4  541.82  5313.8  543.28  5396.7  545.37
#Mann= 5 ,-1 , 0
  4571.5     .05       0  4796.4     .16       0  4933.1     .07       0
  5048.7     .16       0  5313.8     .05       0
Bank Sta=4933.1,5048.7
XS Rating Curve= 0 ,0
Exp/Cntr=0.3,0.1

Type RM Length L Ch R = 1 ,392706  ,215,215,215
BEGIN DESCRIPTION:
LFC13
END DESCRIPTION:
XS GIS Cut Line= 3
      2759456.27        7074645.      2758786.18      7074587.71
      2758429.32      7074585.98
#Sta/Elev= 30
  4295.1  543.13  4487.1  539.82  4684.9  538.05  4818.3  537.29  4858.4  533.14
  4868.5  533.68  4888.5  533.35  4898.6  534.15  4937.2  534.74  4942.2  534.15
  4978.8  533.71  4988.8  531.61  4998.8  527.13  5005.2  527.02  5005.7  526.22
  5011.9  526.22  5018.8  534.46  5028.8   536.2  5044.1  537.21  5058.8  538.49
  5078.8  541.84  5088.8  542.41  5098.8  541.75  5108.8  541.83  5118.8  542.64
  5138.8  546.12  5148.8  547.06  5178.8  548.08  5218.8  550.36  5324.5  552.63
#Mann= 5 ,-1 , 0
  4295.1     .05       0  4684.9     .16       0  4937.2     .07       0
  5028.8     .16       0  5044.1     .05       0
Bank Sta=4937.2,5028.8
XS Rating Curve= 0 ,0
Exp/Cntr=0.3,0.1

Type RM Length L Ch R = 1 ,392491  ,481,481,481
BEGIN DESCRIPTION:
LFC14
END DESCRIPTION:
XS GIS Cut Line= 3
      2759437.18       7074481.8      2758916.39      7074474.86
      2758534.48      7074460.97
#Sta/Elev= 30
  4419.2  543.36  4501.4  542.63  4521.4  541.56  4541.4  541.96  4631.4  538.36
  4738.7  537.25  4791.4  537.48  4837.8  536.96  4891.4  537.24  4901.4  536.53
  4931.4  533.04  4951.4     534  4971.4  534.12  4981.5  533.57  4997.8  526.02
  4998.4  525.22  5004.6  525.22  5005.1  526.02  5021.5  534.72  5031.5  536.57
  5075.2  538.43  5081.5  539.94  5091.5  541.42  5131.6  541.67  5161.6  542.55
  5181.6  543.94  5211.6  544.98  5241.6  547.36  5311.7  549.21  5322.2  550.35
#Mann= 5 ,-1 , 0
  4419.2     .08       0  4738.7     .05       0  4837.8     .08       0
  4971.4     .07       0  5021.5     .08       0
Bank Sta=4971.4,5021.5
XS Rating Curve= 0 ,0
Exp/Cntr=0.3,0.1

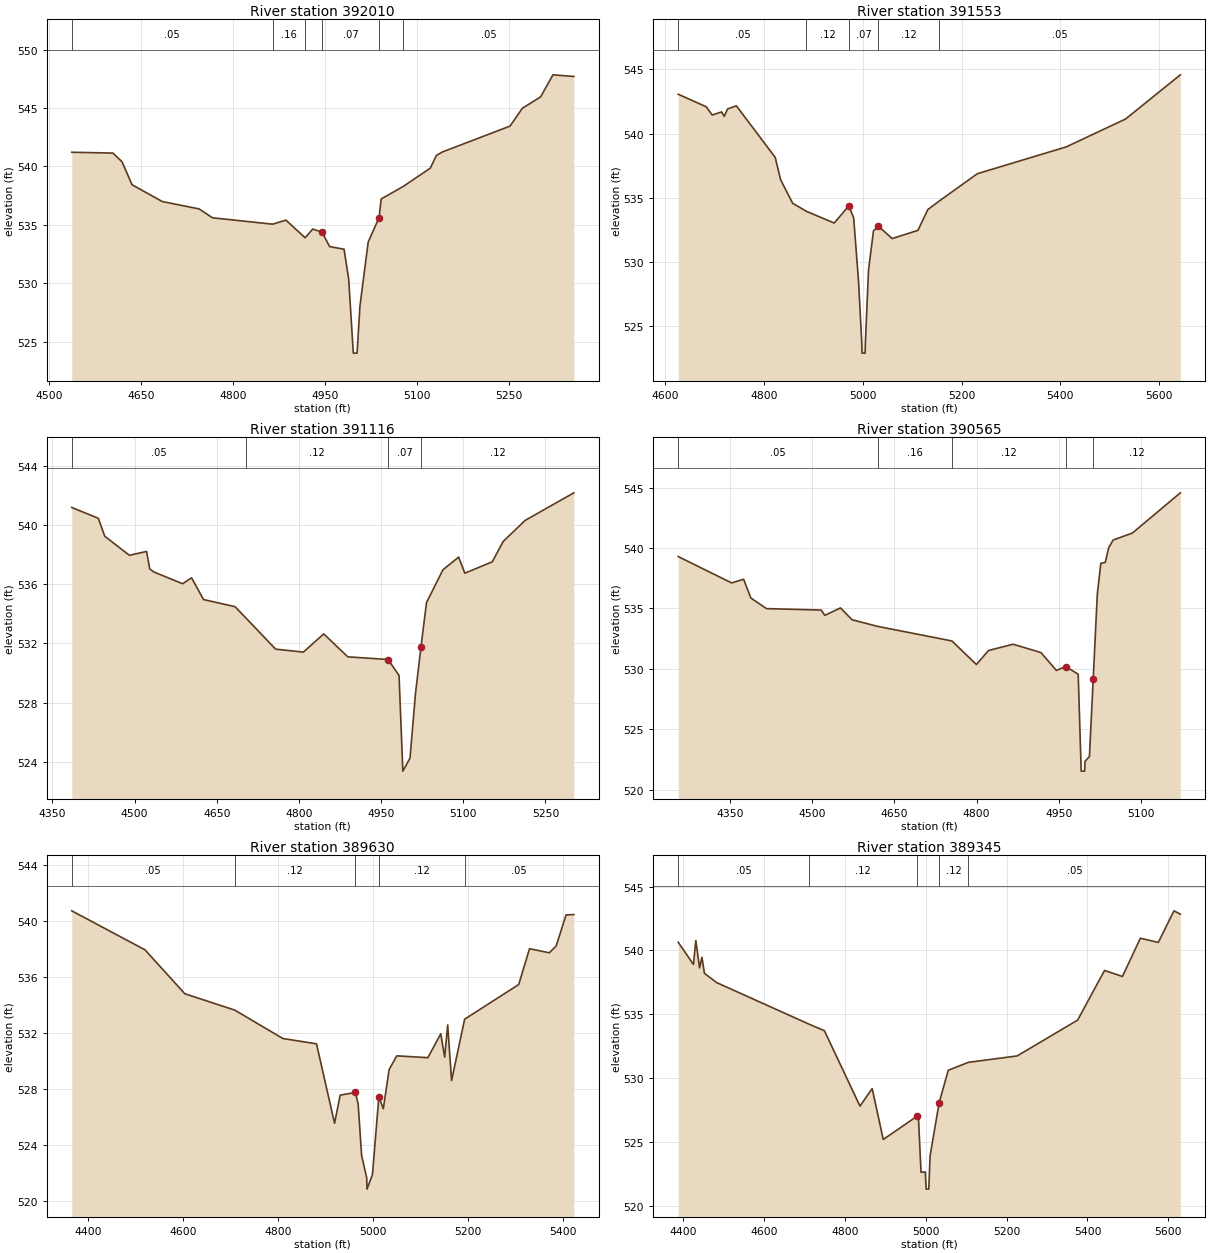
Type RM Length L Ch R = 1 ,392010  ,457,457,457
BEGIN DESCRIPTION:
LFC16
END DESCRIPTION:
XS GIS Cut Line= 4
      2759313.96      7074328.16      2758938.96      7074125.03
      2758863.44      7074098.99      2758550.98      7074085.97
#Sta/Elev= 30
  4537.4  541.21  4604.5  541.14  4619.5  540.39  4635.7  538.43  4685.1  536.99
  4745.1  536.36  4766.9   535.6  4865.1  535.05  4886.8   535.4  4918.1  533.89
  4930.5  534.63  4945.6  534.37  4958.1  533.13  4981.6  532.91  4989.2  530.34
  4996.7  524.01  5002.9  524.01  5007.5  528.02    5021  533.52  5038.8  535.62
  5042.2  537.21  5077.8  538.27  5122.3  539.85  5132.3  540.94  5142.3  541.24
  5252.4  543.45  5272.4  544.97  5302.4  545.96  5322.4  547.84  5356.5   547.7
#Mann= 6 ,-1 , 0
  4537.4     .05       0  4865.1     .16       0  4918.1     .12       0
  4945.6     .07       0  5038.8     .12       0  5077.8     .05       0
Bank Sta=4945.6,5038.8
XS Rating Curve= 0 ,0
Exp/Cntr=0.3,0.1

Type RM Length L Ch R = 1 ,391553  ,437,437,437
BEGIN DESCRIPTION:
LFC17
END DESCRIPTION:
XS GIS Cut Line= 4
      2759537.91      7074023.47      2759238.44      7073906.28
      2758759.27      7073921.91      2758544.34      7073927.04
#Sta/Elev= 30
  4626.6  543.06  4683.4  542.08  4695.3  541.44  4714.4  541.68  4719.7  541.34
  4726.4  541.91  4744.2  542.16  4822.9  538.14  4833.8   536.4  4858.1  534.57
  4886.1  533.94  4942.2  533.03  4971.6  534.35  4981.6  533.45  4991.6  528.42
    4998   523.7  4998.6   522.9  5004.8   522.9  5005.3   523.7  5011.7  529.38
  5021.7  532.42  5031.7  532.79  5059.4  531.82  5111.7  532.46  5131.7  534.08
  5154.7  534.74  5231.8  536.87  5411.9  538.96  5531.9  541.13  5642.6  544.57
#Mann= 5 ,-1 , 0
  4626.6     .05       0  4886.1     .12       0  4971.6     .07       0
  5031.7     .12       0  5154.7     .05       0
Bank Sta=4971.6,5031.7
XS Rating Curve= 0 ,0
Exp/Cntr=0.3,0.1

Type RM Length L Ch R = 1 ,391116  ,551,551,551
BEGIN DESCRIPTION:
LFC18
END DESCRIPTION:
XS GIS Cut Line= 3
      2759597.79      7073895.86      2759116.04      7073638.05
      2758746.28      7073619.83
#Sta/Elev= 30
  4385.3  541.18  4433.8  540.45  4445.5  539.24  4490.5  537.95  4521.9  538.21
  4527.6  537.03  4535.9  536.81  4587.7  536.03    4604  536.43  4625.9  534.96
  4683.4  534.48  4703.6   533.7  4757.5  531.61  4808.1  531.41  4845.3  532.64
  4889.2  531.09  4962.8  530.91  4982.8  529.83  4989.7  523.37  5002.8  524.25
  5012.8  528.61  5022.8  531.75  5032.9  534.75  5062.9  536.97  5091.6  537.83
  5102.9  536.74    5153  537.51    5173  538.89  5213.1  540.31  5301.9  542.17
#Mann= 4 ,-1 , 0
  4385.3     .05       0  4703.6     .12       0  4962.8     .07       0
  5022.8     .12       0
Bank Sta=4962.8,5022.8
XS Rating Curve= 0 ,0
Exp/Cntr=0.3,0.1

Type RM Length L Ch R = 1 ,390565  ,935,935,935
BEGIN DESCRIPTION:
LFC19
END DESCRIPTION:
XS GIS Cut Line= 4
      2759665.48      7073802.09      2759204.58      7073406.28
      2759147.29      7073286.49       2759009.6      7073177.38
#Sta/Elev= 30
  4255.5   539.3  4352.9  537.12  4374.8  537.42    4388  535.87  4416.5  534.99
  4516.4  534.87    4523  534.43  4551.5  535.05  4572.5  534.07  4619.2  533.52
  4754.9  532.31  4799.5  530.36  4821.5  531.52  4866.5  532.04  4917.2  531.35
  4945.4  529.87  4962.5  530.19  4985.2  529.56  4990.7  521.53    4997  521.53
  4997.6  522.33  5005.7  522.74  5012.6  529.17  5020.1   536.2  5026.5  538.74
  5034.6  538.82  5040.9  540.04    5049  540.67  5084.2  541.25  5171.5  544.58
#Mann= 5 ,-1 , 0
  4255.5     .05       0  4619.2     .16       0  4754.9     .12       0
  4962.5     .07       0  5012.6     .12       0
Bank Sta=4962.5,5012.6
XS Rating Curve= 0 ,0
Exp/Cntr=0.3,0.1

Type RM Length L Ch R = 1 ,389630  ,285,285,285
BEGIN DESCRIPTION:
LFC20
END DESCRIPTION:
XS GIS Cut Line= 5
      2760006.67      7073572.97      2759889.48      7073179.72
      2759813.96      7073098.99       2759652.5      7073010.45
      2759371.22      7072796.88
#Sta/Elev= 30
  4365.6  540.72    4520  537.93  4603.9  534.79  4709.2  533.62  4810.5  531.59
  4881.4  531.21  4919.5  525.53  4931.3  527.54  4963.5  527.73  4969.2  526.91
  4976.5  523.23  4987.3  521.62  4987.8  520.82  4999.3  521.85  5012.8   527.4
  5022.2  526.57  5034.6  529.38  5050.7  530.35  5116.2  530.22  5143.3  531.93
  5151.6  530.26  5157.9  532.56  5166.1  528.58  5193.6  532.97  5307.6  535.45
  5330.4  538.01  5372.1  537.72  5386.6  538.21  5407.4  540.43  5423.8  540.45
#Mann= 5 ,-1 , 0
  4365.6     .05       0  4709.2     .12       0  4963.5     .07       0
  5012.8     .12       0  5193.6     .05       0
Bank Sta=4963.5,5012.8
XS Rating Curve= 0 ,0
Exp/Cntr=0.3,0.1

Type RM Length L Ch R = 1 ,389345  ,393,393,393
BEGIN DESCRIPTION:
LFC21
END DESCRIPTION:
XS GIS Cut Line= 3
      2760271.49      7073399.65      2759954.05      7072901.64
      2759374.29      7072603.74
#Sta/Elev= 30
  4387.4  540.64    4425  538.91  4430.9  540.78  4440.2  538.64  4446.1  539.47
  4452.2  538.22  4482.5  537.49    4712  534.23  4749.1  533.73  4837.1  527.84
  4867.3  529.21  4894.7  525.23    4978  527.04    4982  526.83  4988.2  522.67
  4998.6  522.69    5001  521.35  5007.4  521.35  5010.6  523.95  5033.1  528.11
  5055.6  530.64  5105.6  531.26  5226.1  531.76  5375.7  534.56  5442.3  538.44
  5486.6  537.97    5531  540.96  5575.4  540.63  5614.1   543.1  5629.8  542.84
#Mann= 5 ,-1 , 0
  4387.4     .05       0    4712     .12       0    4978     .07       0
  5033.1     .12       0  5105.6     .05       0
Bank Sta=4978,5033.1
XS Rating Curve= 0 ,0
Exp/Cntr=0.3,0.1

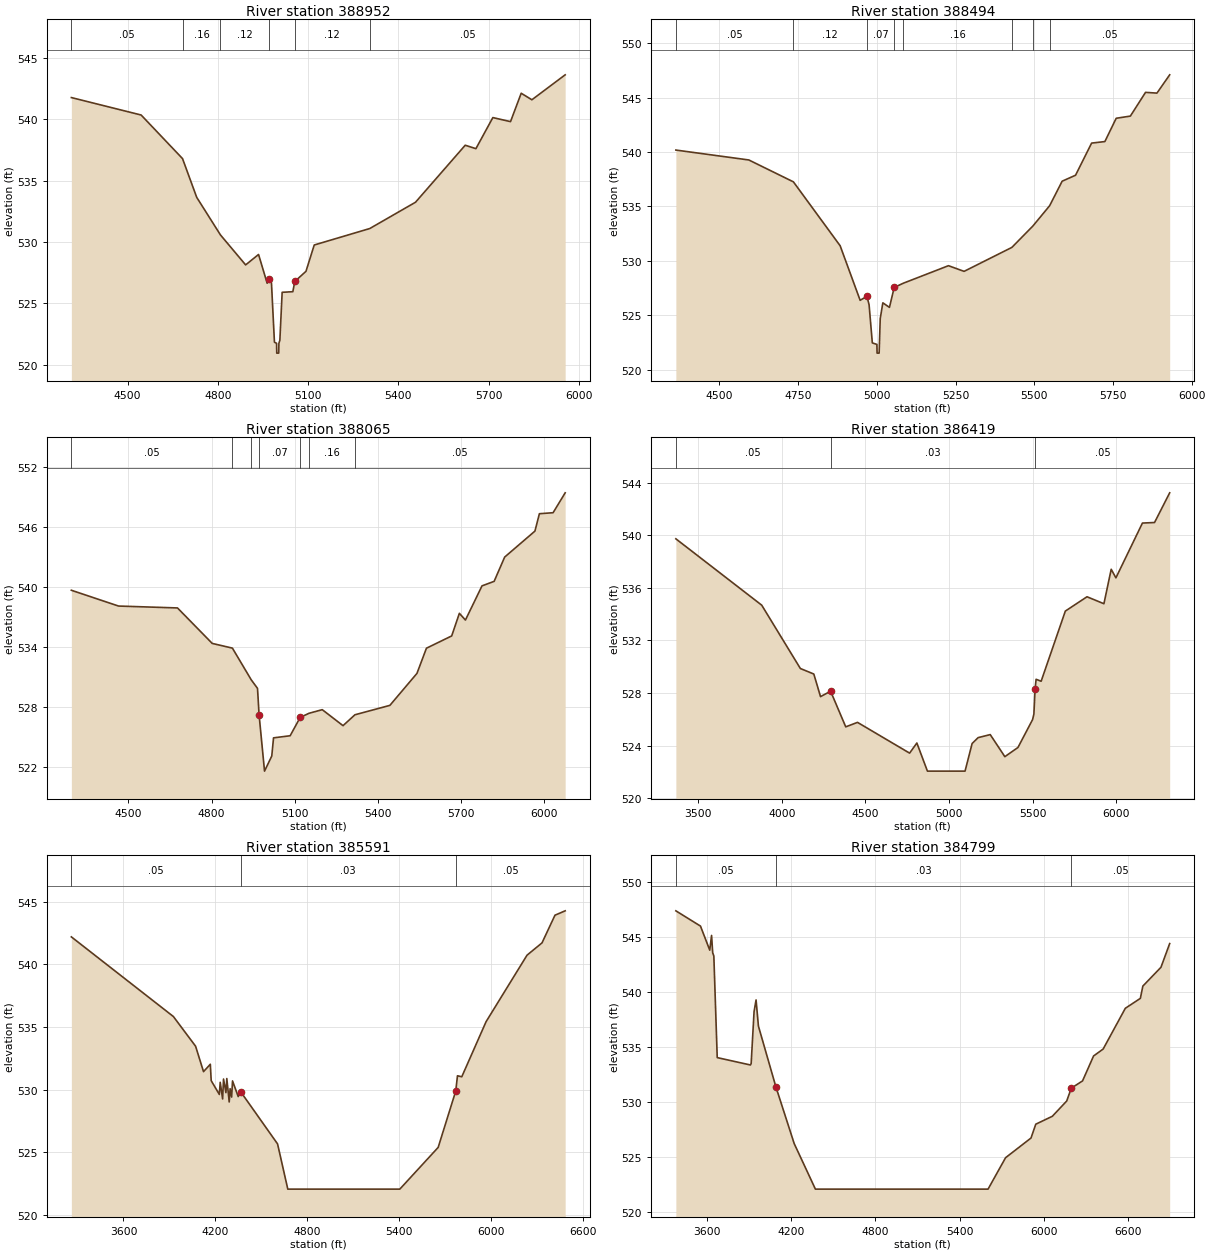
Type RM Length L Ch R = 1 ,388952  ,458,458,458
BEGIN DESCRIPTION:
LFC22
END DESCRIPTION:
XS GIS Cut Line= 3
      2760705.68      7073030.67        2760189.       7072595.6
      2759410.45      7072024.87
#Sta/Elev= 30
  4313.4  541.76  4545.2  540.34  4682.8  536.79  4729.9  533.64  4808.8  530.58
  4892.5  528.14  4935.4  528.99    4964  526.65  4970.5  527.03  4978.3  526.67
  4988.2  521.85  4995.3  521.76  4995.9  520.96  5002.4  520.96    5003  521.76
  5006.2     522  5013.8  525.91  5049.3  525.96  5055.8  526.79    5093  527.62
  5120.4  529.76  5304.9   531.1  5456.9  533.24  5622.1  537.88  5657.6   537.6
  5713.9  540.13  5772.6   539.8  5808.1  542.11  5843.6  541.58  5954.2  543.61
#Mann= 6 ,-1 , 0
  4313.4     .05       0  4682.8     .16       0  4808.8     .12       0
  4970.5     .07       0  5055.8     .12       0  5304.9     .05       0
Bank Sta=4970.5,5055.8
XS Rating Curve= 0 ,0
Exp/Cntr=0.3,0.1

Type RM Length L Ch R = 1 ,388494  ,429,429,429
BEGIN DESCRIPTION:
LFC23
END DESCRIPTION:
XS GIS Cut Line= 3
      2760835.87      7072661.59      2760375.63       7072239.7
      2759591.32      7071713.72
#Sta/Elev= 30
  4361.5  540.18  4593.3  539.27  4734.9  537.26  4883.4  531.39  4946.9  526.38
  4968.5  526.75  4975.3  525.97  4985.6  522.47  5000.1  522.33  5000.7  521.53
  5007.2  521.53  5010.7   524.7    5019  526.15    5040  525.73    5055  527.56
    5084  527.95  5227.4  529.56  5277.1  529.04  5428.9  531.24  5495.5   533.2
  5548.9  535.07  5588.6  537.32  5631.2  537.87  5682.2  540.82  5724.3  540.96
  5760.3   543.1  5805.3   543.3  5853.5  545.48  5889.7  545.41  5930.2  547.09
#Mann= 8 ,-1 , 0
  4361.5     .05       0  4734.9     .12       0  4968.5     .07       0
    5055     .12       0    5084     .16       0  5428.9     .05       0
  5495.5     .16       0  5548.9     .05       0
Bank Sta=4968.5,5055
XS Rating Curve= 0 ,0
Exp/Cntr=0.3,0.1

Type RM Length L Ch R = 1 ,388065  ,1646,1646,1646
BEGIN DESCRIPTION:
LFC24
END DESCRIPTION:
XS GIS Cut Line= 3
      2760973.36      7072545.82      2760642.56      7071938.48
      2759685.44      7071417.09
#Sta/Elev= 30
  4294.1  539.71  4464.3  538.13    4677  537.94  4802.3  534.39  4875.1  533.92
    4943  530.75  4965.7  529.89  4971.3  527.26    4991  521.61  5017.1  523.12
  5023.5  524.94  5083.4  525.15  5119.5  526.98  5151.6   527.4  5199.3  527.76
  5274.2  526.16  5317.2  527.25  5443.2  528.19  5540.9  531.39  5575.1  533.91
  5666.2  535.14  5693.9   537.4  5715.8  536.73  5775.6  540.15  5819.3   540.6
  5857.3  543.03  5966.5  545.63  5982.6  547.37    6032  547.47  6075.6  549.46
#Mann= 7 ,-1 , 0
  4294.1     .05       0  4875.1     .16       0    4943     .12       0
  4971.3     .07       0  5119.5     .12       0  5151.6     .16       0
  5317.2     .05       0
Bank Sta=4971.3,5119.5
XS Rating Curve= 0 ,0
Exp/Cntr=0.3,0.1

Type RM Length L Ch R = 1 ,386419  ,828,828,828
BEGIN DESCRIPTION:
LFC25
END DESCRIPTION:
XS GIS Cut Line= 4
      2761118.09      7072545.88      2761273.63      7070975.81
      2761155.58      7070795.26      2760186.19      7070159.03
#Sta/Elev= 30
    3367  539.73  3880.4  534.68  4111.5  529.86  4191.9  529.44  4232.1  527.72
  4292.4  528.13  4382.8  525.42  4453.2  525.76  4764.7  523.42  4808.2  524.19
  4871.3  522.05  5096.3  522.05  5138.5  524.15  5174.6   524.6  5246.9  524.83
  5334.3  523.15  5412.7  523.85  5500.1  525.97    5508   526.4  5515.2  528.33
  5521.2  529.04  5551.3  528.89    5696  534.23  5825.6  535.32  5926.7  534.79
  5970.3  537.41  5998.5  536.76  6157.1  540.93  6229.4  540.97    6320  543.23
#Mann= 3 ,-1 , 0
    3367     .05       0  4292.4     .03       0  5515.2     .05       0
Bank Sta=4292.4,5515.2
XS Rating Curve= 0 ,0
Exp/Cntr=0.3,0.1

Type RM Length L Ch R = 1 ,385591  ,792,792,792
BEGIN DESCRIPTION:
LFC173
END DESCRIPTION:
XS GIS Cut Line= 3
      2762586.97        7071721.      2761759.82      7070295.25
      2760250.02      7069850.01
#Sta/Elev= 30
  3259.8  542.19  3925.6  535.83  4070.5  533.46  4122.2  531.43  4166.6  532.02
  4172.4  530.71  4225.4  529.61  4231.1  530.58  4246.9  529.25  4252.7  530.84
  4268.4  529.75  4274.2  530.88  4289.9  529.01  4295.7  530.07  4305.7   529.4
  4311.5  530.69  4348.7  529.44  4364.5  529.83  4605.4  525.66  4672.2  522.05
  5403.2  522.05  5653.4  525.38  5768.1  529.88  5779.4   531.1  5807.5  531.02
  5966.1  535.42  6233.4  540.73    6331  541.71  6415.6  543.92  6482.2  544.27
#Mann= 3 ,-1 , 0
  3259.8     .05       0  4364.5     .03       0  5768.1     .05       0
Bank Sta=4364.5,5768.1
XS Rating Curve= 0 ,0
Exp/Cntr=0.3,0.1

Type RM Length L Ch R = 1 ,384799  ,127,127,127
BEGIN DESCRIPTION:
LFC26
END DESCRIPTION:
XS GIS Cut Line= 5
      2763695.47      7070147.66      2763471.55      7069996.64
      2762784.05      7069814.35       2762065.3      7069637.27
      2760341.34      7069152.89
#Sta/Elev= 30
  3381.1  547.38  3556.2  545.99  3622.1   543.8    3635  545.14  3643.1  543.56
  3651.2  543.27  3675.3  534.02  3911.3  533.35  3916.6  533.48  3937.3  538.21
  3951.5  539.27  3968.3  536.89  4092.5  531.36  4222.6   526.2  4373.6  522.05
  5601.6  522.05  5726.2  524.91    5907   526.7    5941  527.96  6058.8  528.68
    6161  530.07  6193.7  531.24  6273.6   531.9  6352.1  534.17  6420.2   534.8
    6578  538.51  6684.7  539.41  6702.6  540.53  6831.3  542.24  6893.4   544.4
#Mann= 3 ,-1 , 0
  3381.1     .05       0  4092.5     .03       0  6193.7     .05       0
Bank Sta=4092.5,6193.7
XS Rating Curve= 0 ,0
Exp/Cntr=0.3,0.1