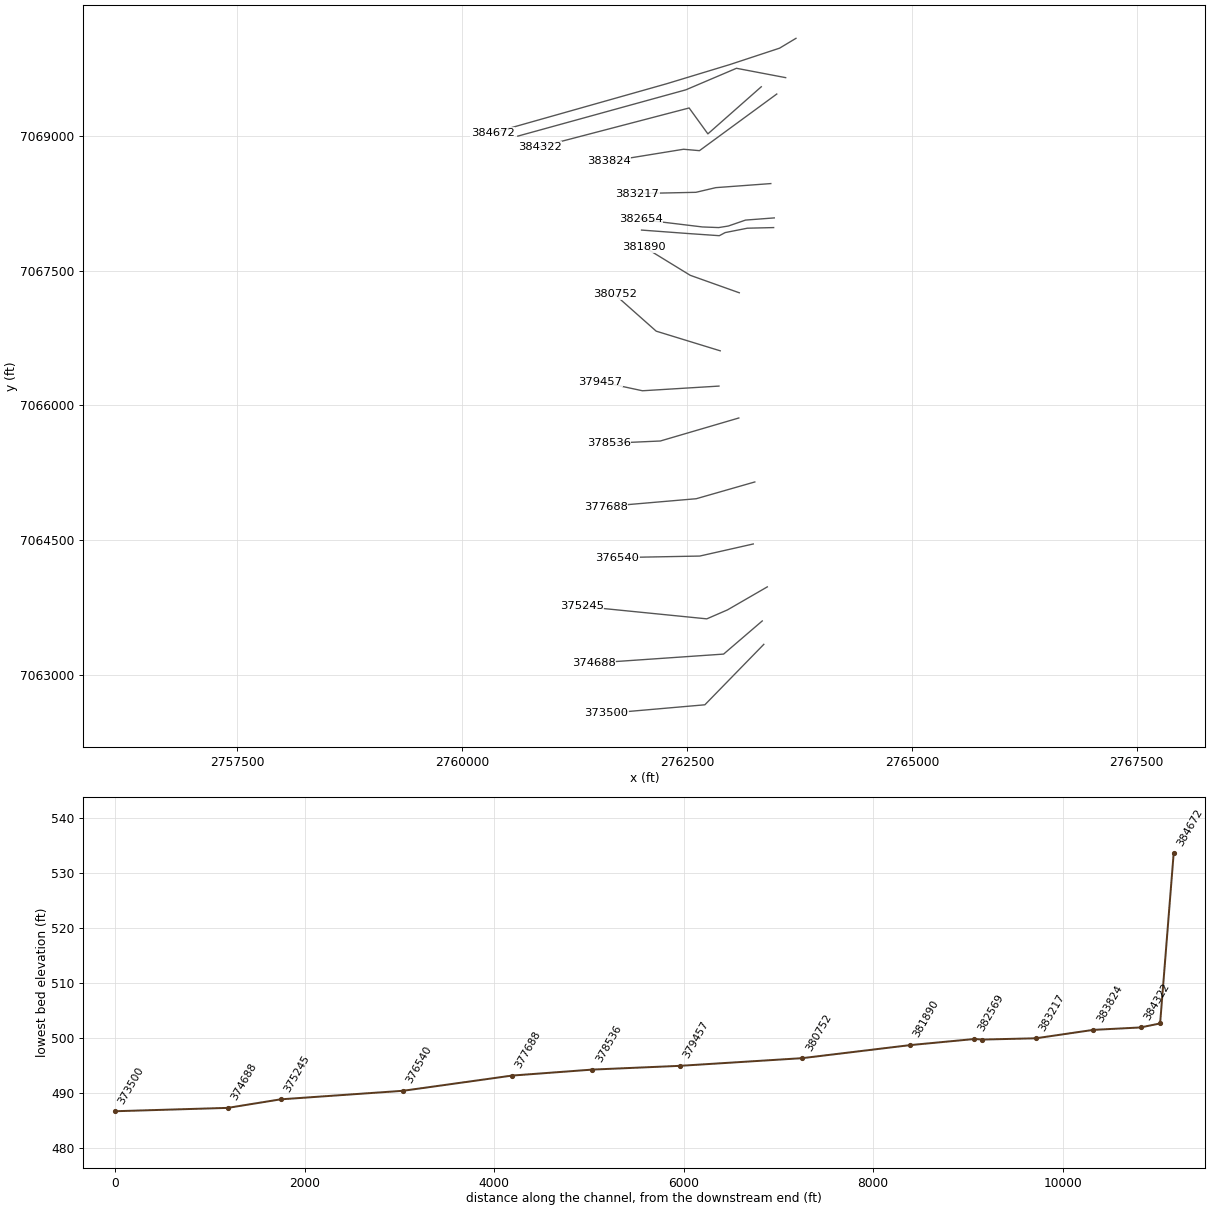
HEC-RAS study Lake Fork Creek.prj: Lake Fork Creek Base Level Engineering

--- Lake Fork Creek.g01 (geometry) --- (continued)

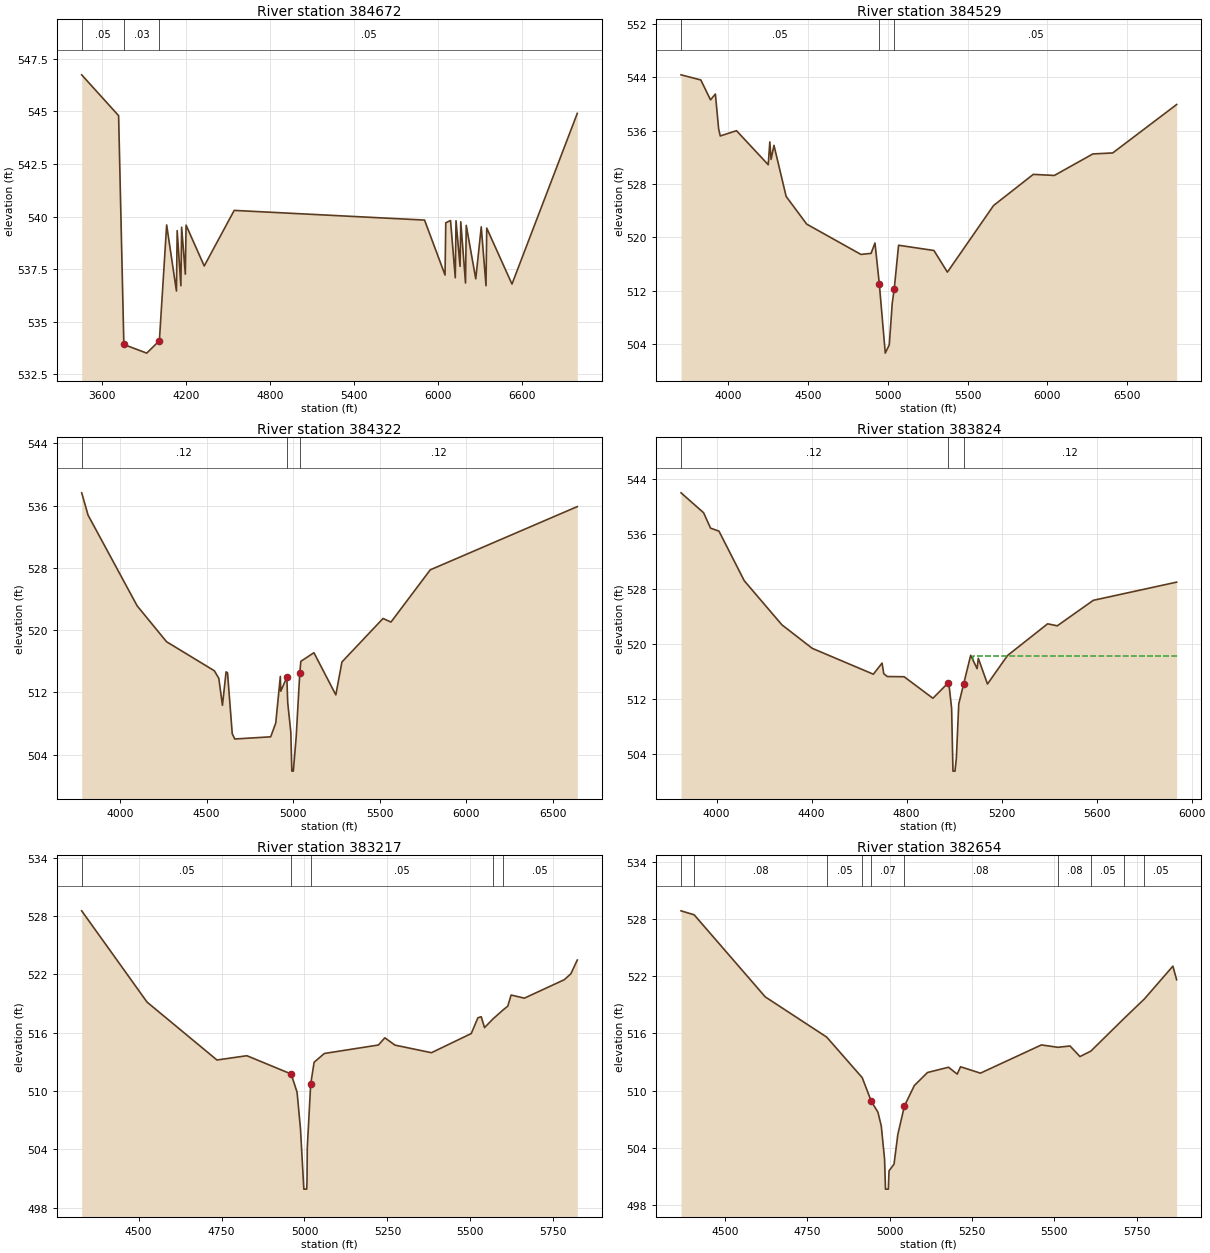
Type RM Length L Ch R = 1 ,384672  ,143,143,143
BEGIN DESCRIPTION:
LFC27
END DESCRIPTION:
XS GIS Cut Line= 5
      2763711.12      7070085.18      2763528.84      7069975.81
      2762976.76      7069793.52      2762273.63      7069579.98
      2760341.34       7069033.1
#Sta/Elev= 30
  3454.9  546.73  3718.4  544.79  3755.8  533.92  3919.1  533.51  4009.4   534.1
  4061.2   539.6  4131.1  536.46  4136.3  539.33  4162.8  536.71  4168.1  539.49
  4194.6  537.26  4199.8  539.59  4329.4  537.65  4543.3  540.29  5901.9  539.83
    6048  537.22  6053.2   539.7  6087.2  539.81  6121.1  537.09  6126.3   539.8
  6155.1  537.63  6160.3  539.75  6194.2  536.84  6199.4  539.58  6267.3  537.04
  6306.5  539.51  6340.4  536.71  6345.6  539.45  6525.8  536.79  6991.9   544.9
#Mann= 3 ,-1 , 0
  3454.9     .05       0  3755.8     .03       0  4009.4     .05       0
Bank Sta=3755.8,4009.4
XS Rating Curve= 0 ,0
Exp/Cntr=0.3,0.1

Type RM Length L Ch R = 1 ,384529  ,207,207,207
BEGIN DESCRIPTION:
LFC28
END DESCRIPTION:
XS GIS Cut Line= 4
      2763596.54      7069647.69      2763049.67      7069751.85
      2762487.17      7069512.27      2760618.71      7068997.01
#Sta/Elev= 30
  3703.1  544.39  3827.1  543.62  3887.9  540.63  3918.4  541.51  3938.8  536.27
    3949  535.21  4050.8     536  4249.6  530.89  4259.6  534.32  4267.4  531.69
  4285.6   533.8  4361.9  526.13  4490.9  521.97  4830.7  517.42  4894.2  517.58
  4918.7  519.14  4946.1  512.94  4983.2   502.6  5008.3  503.85    5027  510.12
  5039.4  512.24  5066.6   518.8  5288.3  518.01  5372.6  514.76  5661.8  524.76
  5910.8  529.44  6043.1  529.28  6284.2  532.51  6408.7  532.66  6809.4  539.93
#Mann= 3 ,-1 , 0
  3703.1     .05       0  4946.1     .03       0  5039.4     .05       0
Bank Sta=4946.1,5039.4
XS Rating Curve= 0 ,0
Exp/Cntr=0.3,0.1

Type RM Length L Ch R = 1 ,384322  ,498,498,498
BEGIN DESCRIPTION:
Mapping XS 9fe71427
END DESCRIPTION:
XS GIS Cut Line= 4
      2763325.49      7069546.32      2762731.75      7069022.02
      2762523.42      7069310.22      2760863.74       7068876.2
#Sta/Elev= 30
  3778.5  537.64  3815.4  534.77    4099  523.11  4268.8   518.5  4544.8  514.77
  4570.6   513.8  4591.7  510.33  4612.6  514.63  4621.1   514.5  4648.3  506.68
  4662.9     506  4870.4  506.28  4899.6  508.05  4926.1  514.04  4928.4  512.14
  4963.7  513.92  4968.8  510.68  4986.6  506.89  4992.6  501.87  5001.2  501.87
  5017.6  506.24  5038.3  514.42  5044.5  515.98  5120.2  517.09  5246.7  511.67
    5282   515.9  5519.4  521.49  5565.4  521.03  5792.1  527.74  6641.7  535.87
#Mann= 3 ,-1 , 0
  3778.5     .12       0  4963.7     .07       0  5038.3     .12       0
Bank Sta=4963.7,5038.3
XS Rating Curve= 0 ,0
Exp/Cntr=0.3,0.1

Type RM Length L Ch R = 1 ,383824  ,607,607,607
BEGIN DESCRIPTION:
LFC29
END DESCRIPTION:
XS GIS Cut Line= 4
      2763497.57      7069465.38      2762638.21      7068835.19
      2762461.13      7068850.81      2761628.88      7068715.57
#Sta/Elev= 30
  3850.2  542.03  3945.1  539.13  3974.4  536.88  4009.9  536.44  4116.5   529.2
    4275  522.77  4402.8  519.34  4659.8  515.57  4696.6  517.19  4703.8  515.64
  4718.5  515.23  4789.5   515.2  4910.7  512.06  4972.5  514.22  4979.3  513.76
  4989.4  510.59  4995.1  501.43  5003.7  501.43  5009.4  503.32  5019.5  511.24
  5039.6  514.08  5069.7  518.33  5096.7  516.38  5101.8  517.89  5140.4  514.14
  5224.9   518.3  5393.6  522.92  5434.2  522.63  5586.1  526.35  5936.8     529
#Mann= 3 ,-1 , 0
  3850.2     .12       0  4972.5     .07       0  5039.6     .12       0
#XS Ineff= 2 , 0
       0                  5079.5       0  518.25
Permanent Ineff=
       F       F
Bank Sta=4972.5,5039.6
XS Rating Curve= 0 ,0
Exp/Cntr=0.3,0.1

Type RM Length L Ch R = 1 ,383217  ,563,563,563
BEGIN DESCRIPTION:
LFC30
END DESCRIPTION:
XS GIS Cut Line= 4
      2763431.58      7068468.86      2762820.51      7068423.73
      2762598.28      7068371.64      2761945.51      7068357.76
#Sta/Elev= 30
  4328.5  528.52  4525.6  519.13  4736.2  513.18  4826.4  513.62  4959.9  511.74
  4977.7  509.87    4988  506.12  4998.1   499.9  5006.7   499.9  5007.6   500.7
  5008.5  504.17  5018.8  510.71  5029.1  512.95  5059.9  513.85  5222.8  514.72
  5242.3  515.46  5272.8  514.71  5382.8  513.93  5502.8   515.9  5522.8  517.52
  5532.8  517.63  5542.8  516.51  5568.1   517.4  5597.5  518.29  5612.9  518.72
  5622.9  519.86  5662.9  519.54  5782.9  521.43  5802.9  522.04  5822.4  523.46
#Mann= 5 ,-1 , 0
  4328.5     .05       0  4959.9     .03       0  5018.8     .05       0
  5568.1     .08       0  5597.5     .05       0
Bank Sta=4959.9,5018.8
XS Rating Curve= 0 ,0
Exp/Cntr=0.3,0.1

Type RM Length L Ch R = 1 ,382654  ,85,85,85
BEGIN DESCRIPTION:
LFC31
END DESCRIPTION:
XS GIS Cut Line= 6
      2763469.82      7068086.92      2763150.37      7068062.62
       2762959.4      7067996.64      2762851.76      7067979.28
       2762671.2      7067986.23      2761983.68      7068069.56
#Sta/Elev= 30
  4366.6  528.85  4406.6  528.43  4622.2  519.83  4808.9  515.61  4916.7  511.36
  4944.1  508.89  4964.4  507.74  4974.5   506.3  4984.6   502.8  4987.3  499.67
    4996  499.67  4998.1  501.59  5013.3  502.29  5024.8   505.4  5044.8  508.39
  5074.9  510.53  5114.9   511.9  5178.7  512.45  5205.1  511.73  5215.2   512.5
  5275.6  511.83  5460.7  514.79  5510.7  514.54  5547.6  514.68  5577.8  513.57
  5610.8  514.14  5710.9  517.54  5773.7  519.62  5859.9  523.05  5871.3  521.63
#Mann= 10 ,-1 , 0
  4366.6     .05       0  4406.6     .08       0  4808.9     .05       0
  4916.7     .08       0  4944.1     .07       0  5044.8     .08       0
  5510.7     .08       0  5610.8     .05       0  5710.9     .08       0
  5773.7     .05       0
Bank Sta=4944.1,5044.8
XS Rating Curve= 0 ,0
Exp/Cntr=0.3,0.1

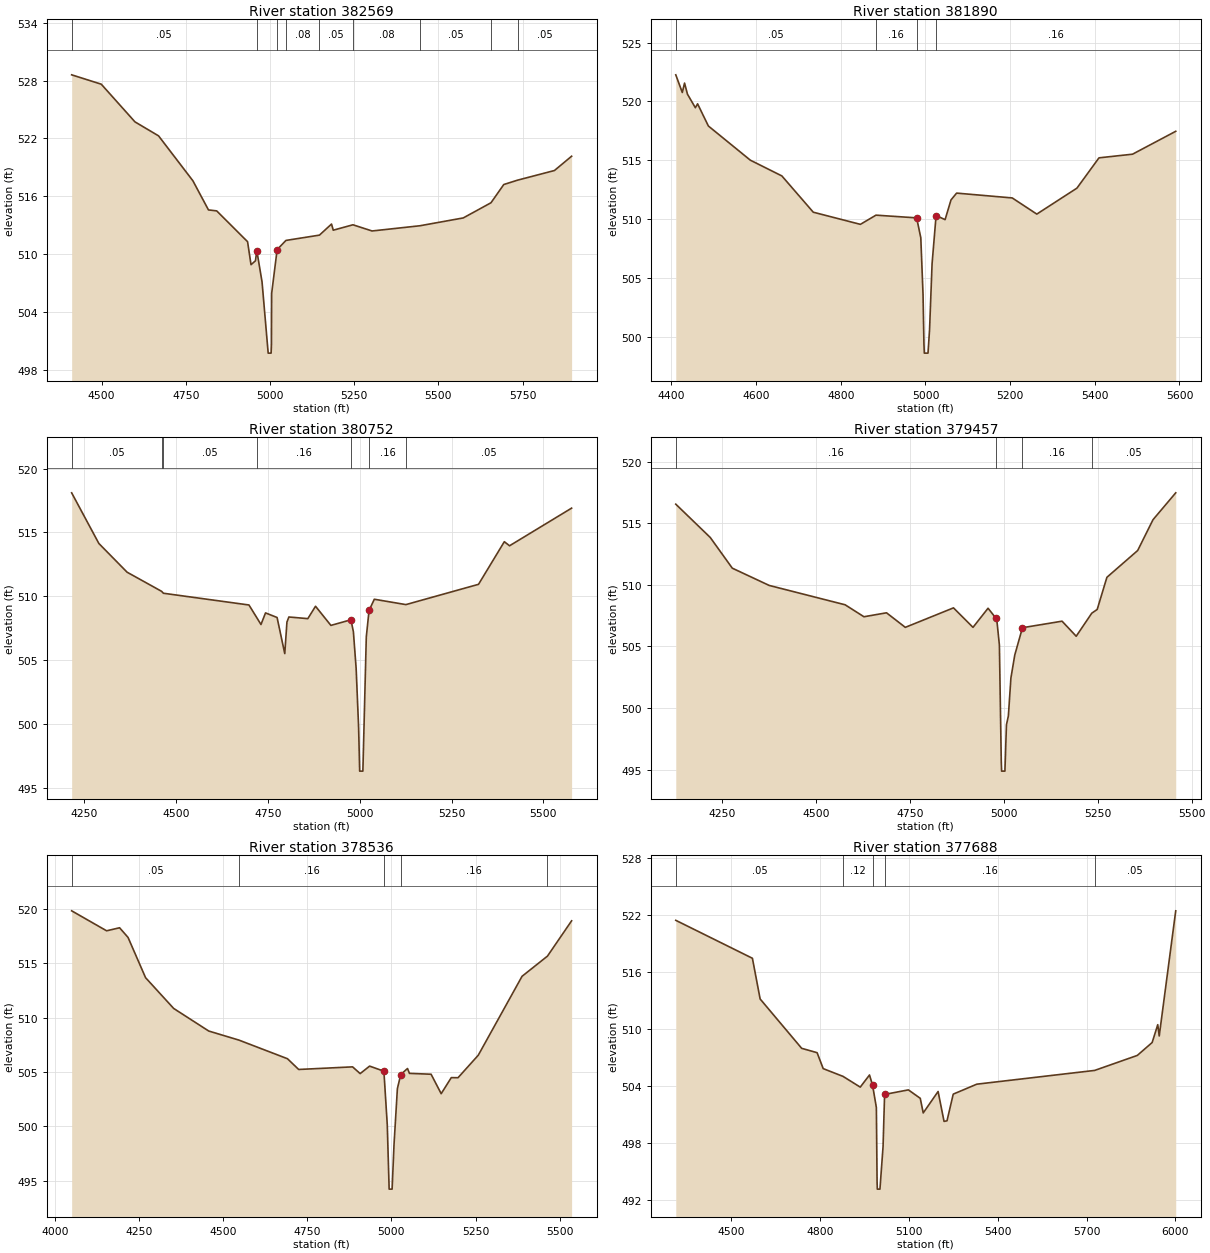
Type RM Length L Ch R = 1 ,382569  ,679,679,679
BEGIN DESCRIPTION:
LFC32
END DESCRIPTION:
XS GIS Cut Line= 6
      2763462.89      7067979.28       2763171.2      7067972.34
      2762924.67      7067923.73       2762858.7      7067889.01
      2762508.01      7067913.31      2761994.16       7067951.5
#Sta/Elev= 30
  4411.3  528.59  4499.2  527.62  4599.2  523.72  4669.3  522.27  4771.2  517.62
  4817.5   514.6  4841.9   514.5  4933.6  511.31  4943.8  508.93    4957  509.33
    4961  510.39  4976.6  507.14  4994.8  499.77  5003.5  499.77  5004.4  500.57
  5005.1  505.95  5021.4  510.49  5047.5  511.44    5147  511.99  5182.9  513.14
    5188   512.5  5246.4  513.06  5303.3  512.42  5445.4  512.96    5574  513.77
  5656.3  515.34  5694.3  517.23  5735.1  517.68  5844.7  518.68  5895.7  520.16
#Mann= 9 ,-1 , 0
  4411.3     .05       0    4961     .04       0  5021.4     .05       0
  5047.5     .08       0    5147     .05       0  5246.4     .08       0
  5445.4     .05       0  5656.3     .08       0  5735.1     .05       0
Bank Sta=4961,5021.4
XS Rating Curve= 0 ,0
Exp/Cntr=0.3,0.1

Type RM Length L Ch R = 1 ,381890  ,1138,1138,1138
BEGIN DESCRIPTION:
LFC33
END DESCRIPTION:
XS GIS Cut Line= 3
      2763080.96      7067253.58      2762535.78      7067448.03
      2762022.54      7067763.01
#Sta/Elev= 30
  4410.2  522.26  4425.6  520.76  4430.9  521.56  4437.8  520.62  4456.4  519.47
  4461.7   519.8  4487.2  517.92  4586.4  515.02  4660.7  513.69    4735  510.61
  4846.3  509.58  4883.1  510.36  4979.2  510.13    4989  508.44  4994.3  503.61
  4996.4  499.46  4997.3  498.66    5006  498.66  5009.7  500.66  5015.6  506.22
  5025.1  510.33  5046.4  509.98  5060.3  511.65  5073.6  512.23    5205  511.82
    5263  510.45  5357.8  512.65  5409.9  515.22  5489.2  515.53  5591.2  517.47
#Mann= 4 ,-1 , 0
  4410.2     .05       0  4883.1     .16       0  4979.2     .07       0
  5025.1     .16       0
Bank Sta=4979.2,5025.1
XS Rating Curve= 0 ,0
Exp/Cntr=0.3,0.1

Type RM Length L Ch R = 1 ,380752  ,1295,1295,1295
BEGIN DESCRIPTION:
LFC34
END DESCRIPTION:
XS GIS Cut Line= 3
       2762869.1      7066607.76      2762157.31      7066826.51
      2761696.93      7067234.81
#Sta/Elev= 30
  4216.7   518.1  4290.7  514.13  4367.5  511.88  4461.4  510.38  4466.3  510.23
    4699  509.31  4719.8  508.34  4731.7  507.78  4744.1  508.69  4775.5  508.33
  4796.4   505.5  4802.3  507.97  4807.6  508.37  4859.1  508.24  4880.1  509.21
  4921.9  507.71  4976.4  508.15  4983.1  507.21  4990.6  504.33  4997.3  499.71
  5000.2  496.29  5008.9  496.29  5018.2  506.81  5025.7  508.88    5040  509.76
  5125.9  509.34  5323.5  510.93  5393.7  514.27  5407.9  513.95  5576.7   516.9
#Mann= 7 ,-1 , 0
  4216.7     .05       0  4461.4     .16       0  4466.3     .05       0
  4719.8     .16       0  4976.4     .07       0  5025.7     .16       0
  5125.9     .05       0
Bank Sta=4976.4,5025.7
XS Rating Curve= 0 ,0
Exp/Cntr=0.3,0.1

Type RM Length L Ch R = 1 ,379457  ,921,921,921
BEGIN DESCRIPTION:
LFC35
END DESCRIPTION:
XS GIS Cut Line= 3
      2762855.24      7066215.39      2762004.53      7066163.31
      2761535.82        7066264.
#Sta/Elev= 30
  4125.9  516.54  4217.7  513.84  4276.4  511.35  4374.7  509.95    4577  508.38
  4627.1  507.41  4687.2  507.73  4737.3  506.55  4865.6  508.13  4917.6  506.55
  4957.7   508.1  4978.2  507.31  4980.5  507.31  4987.9  505.11  4992.9  495.69
  4993.8  494.89  5002.6  494.89  5006.7  498.65  5011.8  499.36  5018.6  502.45
  5028.9  504.31  5049.3  506.52  5154.8  507.05  5192.5  505.83    5234   507.7
  5248.4     508  5274.3  510.61  5356.2  512.78  5397.1  515.28  5457.6  517.46
#Mann= 4 ,-1 , 0
  4125.9     .16       0  4978.2     .07       0  5049.3     .16       0
    5234     .05       0
Bank Sta=4978.2,5049.3
XS Rating Curve= 0 ,0
Exp/Cntr=0.3,0.1

Type RM Length L Ch R = 1 ,378536  ,848,848,848
BEGIN DESCRIPTION:
LFC36
END DESCRIPTION:
XS GIS Cut Line= 3
       2763075.7      7065860.35      2762203.32      7065604.28
      2761627.99      7065578.33
#Sta/Elev= 30
  4050.2  519.84    4154     518  4192.6  518.28  4217.7  517.39  4269.8  513.68
  4353.2  510.85  4457.4  508.77  4547.5  507.93  4691.2  506.22  4724.6  505.23
  4884.7  505.47  4907.2  504.85  4935.3  505.54  4977.7  505.07  4987.7  500.15
  4993.3  494.21  5002.1  494.21  5007.8  498.33  5017.8  503.47  5027.8  504.76
  5047.8  505.32  5053.6  504.87  5117.9  504.79  5147.9     503  5177.9  504.48
  5197.9  504.47    5258  506.54  5388.1  513.81  5463.6  515.67  5535.3  518.92
#Mann= 5 ,-1 , 0
  4050.2     .05       0  4547.5     .16       0  4977.7     .07       0
  5027.8     .16       0  5463.6     .05       0
Bank Sta=4977.7,5027.8
XS Rating Curve= 0 ,0
Exp/Cntr=0.3,0.1

Type RM Length L Ch R = 1 ,377688  ,1148,1148,1148
BEGIN DESCRIPTION:
LFC37
END DESCRIPTION:
XS GIS Cut Line= 3
      2763253.64      7065148.55      2762602.62      7064961.92
      2761595.69      7064875.12
#Sta/Elev= 30
  4312.9  521.45  4571.6  517.45  4597.7  513.16  4737.9  507.96    4790   507.5
  4810.6  505.82  4877.7     505  4935.7  503.87  4966.9  505.15  4977.3  504.07
  4990.1  501.72  4992.5  493.92  4993.3  493.12  5002.2  493.12  5012.7  497.61
  5017.9   503.1  5098.2  503.58  5138.3  502.69  5148.3  501.15  5198.5  503.41
  5218.6  500.26  5228.6  500.32  5249.6  503.13    5329  504.18  5727.1  505.63
    5871  507.21  5921.2  508.57  5940.1  510.45  5945.1  509.26  6000.8  522.45
#Mann= 5 ,-1 , 0
  4312.9     .05       0  4877.7     .12       0  4977.3     .07       0
  5017.9     .16       0  5727.1     .05       0
Bank Sta=4977.3,5017.9
XS Rating Curve= 0 ,0
Exp/Cntr=0.3,0.1

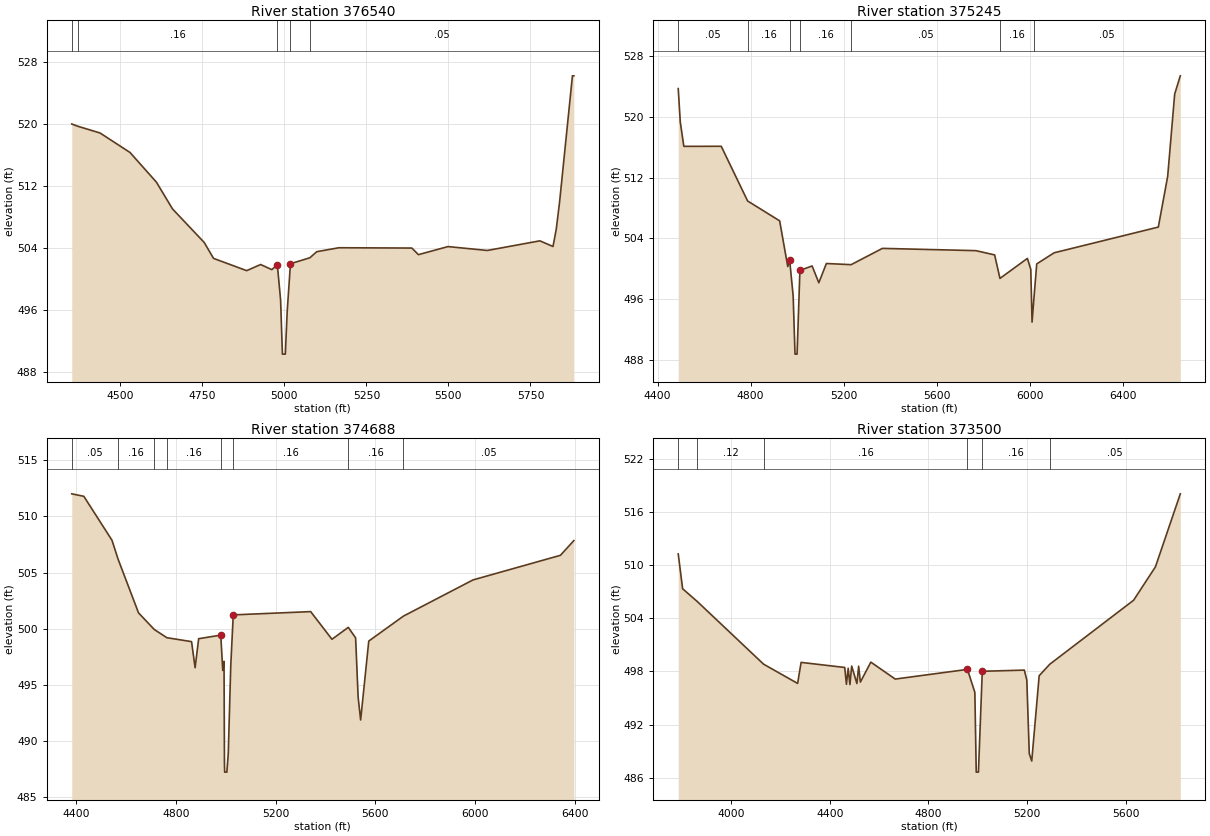
Type RM Length L Ch R = 1 ,376540  ,1295,1295,1295
BEGIN DESCRIPTION:
LFC38
END DESCRIPTION:
XS GIS Cut Line= 3
      2763236.32      7064458.45      2762641.69       7064323.9
      2761721.51      7064306.54
#Sta/Elev= 30
  4352.2     520  4370.2  519.71  4438.3  518.84  4529.7  516.33  4609.9  512.52
  4659.2  509.06  4755.8  504.74  4784.2  502.69  4885.2  501.11  4927.7   501.9
  4961.9  501.24  4978.6  501.88  4988.6  497.32  4994.1  490.36    5003  490.36
  5008.6   495.8  5018.6     502  5077.9  502.77  5098.6  503.55  5166.1  504.06
  5388.6  504.02  5408.6  503.17  5498.6  504.21  5618.7  503.71  5778.7  504.95
  5818.7  504.22  5828.7  506.48  5838.7  509.93  5877.9   526.2  5882.2   526.2
#Mann= 5 ,-1 , 0
  4352.2     .08       0  4370.2     .16       0  4978.6     .07       0
  5018.6     .16       0  5077.9     .05       0
Bank Sta=4978.6,5018.6
XS Rating Curve= 0 ,0
Exp/Cntr=0.3,0.1

Type RM Length L Ch R = 1 ,375245  ,557,557,557
BEGIN DESCRIPTION:
LFC39
END DESCRIPTION:
XS GIS Cut Line= 4
      2763392.57      7063981.03      2762949.85      7063724.94
      2762719.81      7063625.12      2761330.96        7063764.
#Sta/Elev= 30
  4488.8   523.7  4497.6  519.31  4512.9  516.11  4673.6  516.12    4787  508.93
  4924.7  506.32  4959.6  500.31  4967.8  501.13  4982.8  496.43  4990.7   488.8
  4999.6   488.8  5011.8   499.8  5064.2  500.39  5093.1  498.18  5125.5  500.71
  5232.1  500.56  5366.4   502.7  5768.4   502.4  5848.8  501.84  5871.6  498.75
  5989.5  501.38  6004.1  499.95  6009.6  493.01  6017.4  496.05  6029.7  500.66
  6104.6  502.12  6552.3   505.5  6592.5  512.16  6622.6  522.98  6646.8  525.38
#Mann= 7 ,-1 , 0
  4488.8     .05       0    4787     .16       0  4967.8     .07       0
  5011.8     .16       0  5232.1     .05       0  5871.6     .16       0
  6017.4     .05       0
Bank Sta=4967.8,5011.8
XS Rating Curve= 0 ,0
Exp/Cntr=0.3,0.1

Type RM Length L Ch R = 1 ,374688  ,1188,1188,1188
BEGIN DESCRIPTION:
LFC190
END DESCRIPTION:
XS GIS Cut Line= 3
       2763336.3      7063601.88      2762906.59      7063232.94
      2761461.29      7063133.12
#Sta/Elev= 30
  4382.2  512.01  4430.6  511.79  4543.6  507.88  4568.1   506.2  4650.1  501.42
  4713.3  499.94  4763.9  499.21    4863  498.86  4877.2  496.54  4891.5  499.12
  4980.2  499.44  4988.2   496.3  4993.3  497.11    4995  488.05  4995.8  487.25
  5004.7  487.25  5010.3  488.91  5020.3  496.71  5030.3  501.24  5341.1  501.53
  5426.5  499.07    5492  500.13  5521.5  499.19  5531.5  493.93  5541.6  491.89
  5574.2  498.91  5713.4  501.13  5992.6  504.35  6343.5  506.54  6397.3  507.85
#Mann= 8 ,-1 , 0
  4382.2     .05       0  4568.1     .16       0  4713.3     .12       0
  4763.9     .16       0  4980.2     .07       0  5030.3     .16       0
    5492     .16       0  5713.4     .05       0
Bank Sta=4980.2,5030.3
XS Rating Curve= 0 ,0
Exp/Cntr=0.3,0.1

Type RM Length L Ch R = 1 ,373500  ,753,753,753
BEGIN DESCRIPTION:
LFC191
END DESCRIPTION:
XS GIS Cut Line= 3
      2763353.64      7063341.45      2762698.26      7062668.71
      2761604.52      7062573.22
#Sta/Elev= 30
  3785.1  511.26  3802.9  507.33  3862.7  505.88  4131.4  498.82  4269.5  496.65
  4283.6  499.02  4460.6  498.45  4467.5  496.55  4474.7  498.36  4481.7  496.52
  4488.8  498.61    4510  496.64  4517.1  498.59  4524.1   496.8  4566.6  499.05
  4665.6  497.14  4958.5  498.23  4988.6  495.64  4994.2  486.64  5003.1  486.64
  5018.7  498.02  5189.3  498.15  5199.4  497.04  5209.4  488.74  5219.4  487.89
  5249.6  497.52  5292.8  498.82  5632.6  506.03  5721.3   509.8  5822.2  518.04
#Mann= 6 ,-1 , 0
  3785.1     .16       0  3862.7     .12       0  4131.4     .16       0
  4958.5     .07       0  5018.7     .16       0  5292.8     .05       0
Bank Sta=4958.5,5018.7
XS Rating Curve= 0 ,0
Exp/Cntr=0.3,0.1