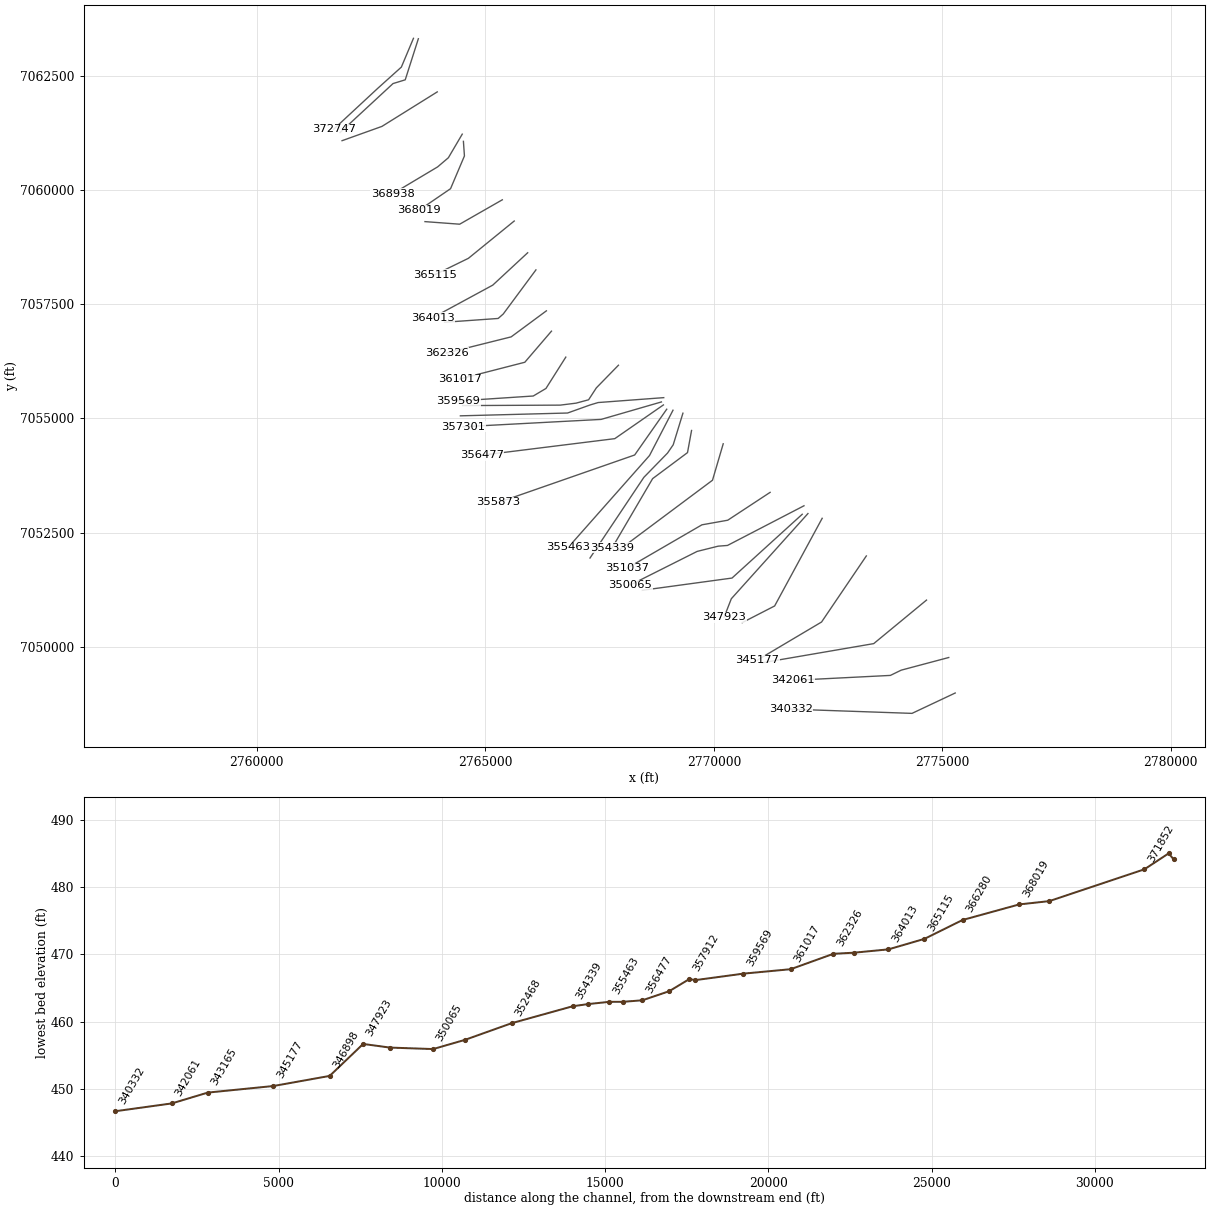
HEC-RAS study Lake Fork Creek.prj: Lake Fork Creek Base Level Engineering

--- Lake Fork Creek.g01 (geometry) --- (continued)

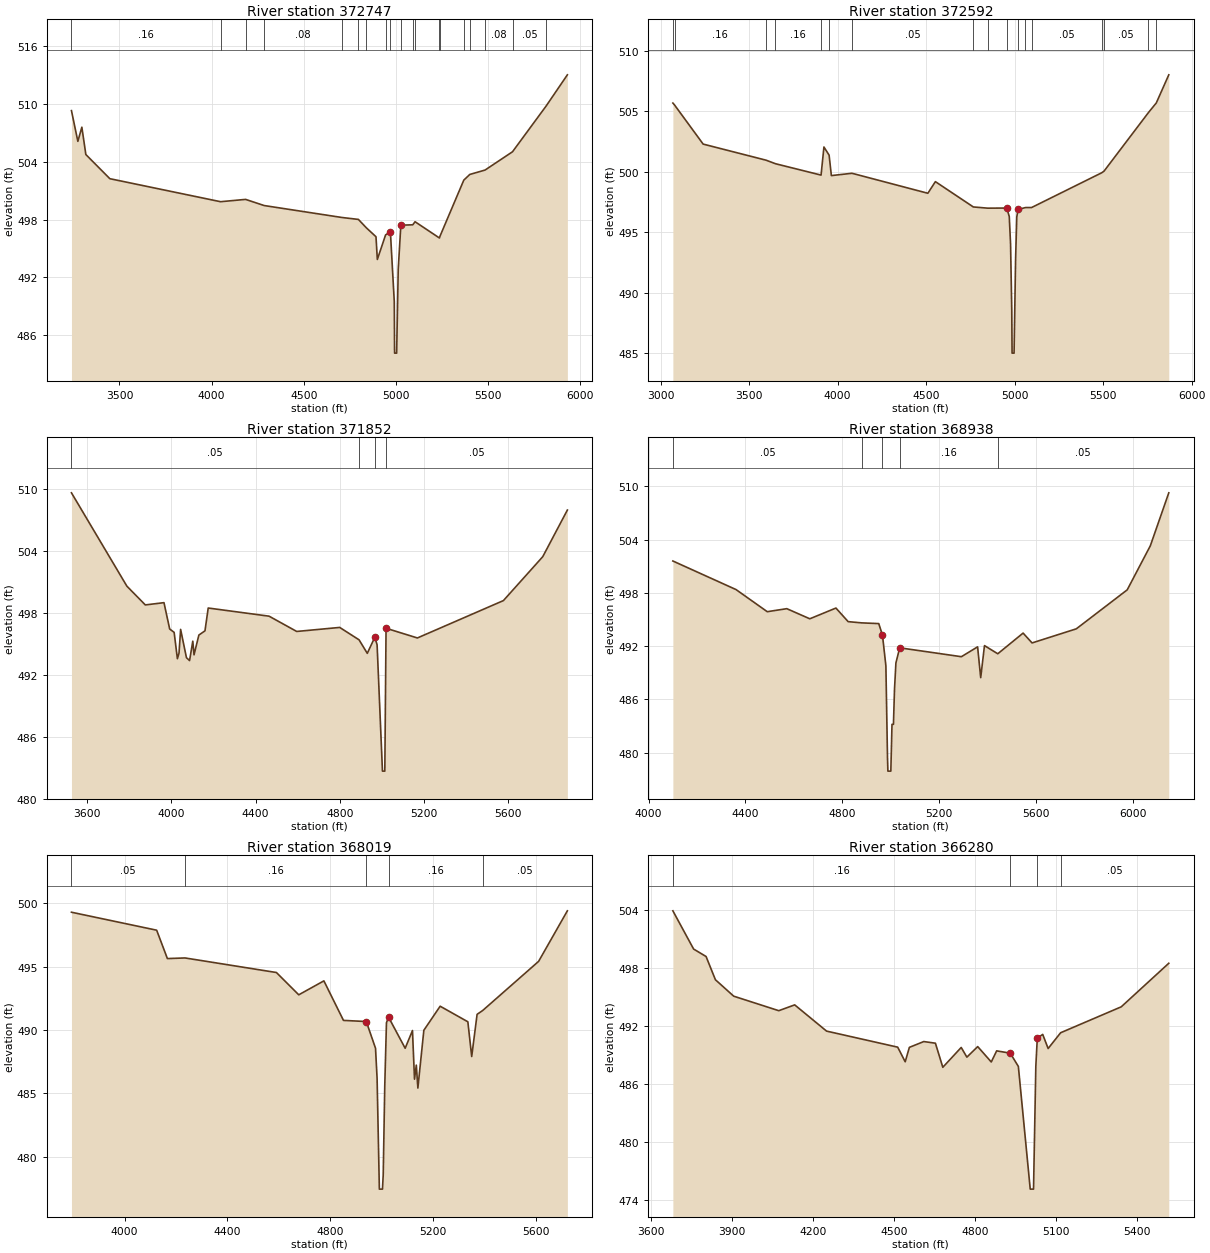
Type RM Length L Ch R = 1 ,372747  ,155,155,155
BEGIN DESCRIPTION:
LFC40
END DESCRIPTION:
XS GIS Cut Line= 4
      2763427.29      7063316.99      2763162.52      7062687.62
      2762646.03      7062223.21      2761682.96      7061329.55
#Sta/Elev= 30
  3239.7  509.33  3274.4  506.14  3296.1  507.61  3317.8  504.77    3448  502.26
  4048.7  499.87  4184.6  500.11  4285.7  499.47  4707.6  498.23  4796.8  498.03
  4839.9  497.16  4892.3  496.23  4899.6  493.87  4944.4  496.42  4970.5  496.74
  4991.5   489.5  4993.2  484.14  5004.4  484.14    5013  492.86  5027.2  497.43
  5091.9  497.47  5104.3  497.79  5236.6   496.1  5239.5  496.28  5368.8  502.11
  5401.3   502.7  5484.4  503.16  5633.3  505.06    5816  509.82  5930.9  513.05
#Mann= 19 ,-1 , 0
  3239.7     .16       0  4048.7     .08       0  4184.6     .16       0
  4285.7     .08       0  4707.6     .16       0  4796.8     .08       0
  4839.9     .16       0  4944.4     .08       0  4970.5     .03       0
  5027.2     .05       0  5091.9     .08       0  5104.3     .05       0
  5236.6     .08       0  5239.5     .05       0  5368.8     .08       0
  5401.3     .05       0  5484.4     .08       0  5633.3     .05       0
    5816     .08       0
Bank Sta=4970.5,5027.2
XS Rating Curve= 0 ,0
Exp/Cntr=0.3,0.1

Type RM Length L Ch R = 1 ,372592  ,740,740,740
BEGIN DESCRIPTION:
LFC41
END DESCRIPTION:
XS GIS Cut Line= 4
      2763534.37      7063307.97      2763247.31      7062409.13
      2762980.23      7062327.37      2761821.34       7061255.3
#Sta/Elev= 30
  3069.2  505.67  3078.6  505.51  3240.3  502.28    3596  500.95  3648.7  500.66
  3906.4  499.72  3922.6  502.04  3951.8  501.37  3964.6  499.68  4081.2  499.87
  4509.7  498.22  4552.2  499.18  4766.6  497.09  4847.7  496.99  4955.4     497
  4969.6   496.3  4976.9  494.04  4983.7  488.59  4985.5  485.02  4996.7  485.02
  5005.3  492.74  5012.1  496.27  5019.4  496.88  5061.1  497.04  5095.4  497.04
  5491.6  499.91  5504.6  500.04  5755.7  504.88  5800.3  505.68  5870.8     508
#Mann= 17 ,-1 , 0
  3069.2     .08       0  3078.6     .16       0    3596     .08       0
  3648.7     .16       0  3906.4     .05       0  3951.8     .08       0
  4081.2     .05       0  4766.6     .08       0  4847.7     .05       0
  4955.4     .03       0  5019.4     .05       0  5061.1     .16       0
  5095.4     .05       0  5491.6     .08       0  5504.6     .05       0
  5755.7     .08       0  5800.3     .05       0
Bank Sta=4955.4,5019.4
XS Rating Curve= 0 ,0
Exp/Cntr=0.3,0.1

Type RM Length L Ch R = 1 ,371852  ,2914,2914,2914
BEGIN DESCRIPTION:
LFC42
END DESCRIPTION:
XS GIS Cut Line= 3
      2763948.13      7062145.09      2762737.17      7061389.87
      2761864.81      7061077.38
#Sta/Elev= 30
  3526.2  509.62  3789.2  500.58  3876.8  498.76  3965.3  498.98  3992.4  496.43
  4013.6   496.1    4029  493.55  4036.7  494.09  4044.3  496.39    4072  493.65
  4086.8  493.37  4102.1  495.25    4108  493.93  4130.9  495.84  4159.9  496.25
  4175.3  498.46  4464.3  497.67  4595.3  496.19  4799.4  496.58  4891.2  495.38
  4930.3  494.07  4966.3  495.64  4976.9  494.89  5002.3  482.66  5013.5  482.66
  5019.4   496.5  5168.1  495.56  5576.4  499.18    5763  503.43    5880  507.95
#Mann= 4 ,-1 , 0
  3526.2     .05       0  4891.2     .16       0  4966.3     .03       0
  5019.4     .05       0
Bank Sta=4966.3,5019.4
XS Rating Curve= 0 ,0
Exp/Cntr=0.3,0.1

Type RM Length L Ch R = 1 ,368938  ,919,919,919
BEGIN DESCRIPTION:
LFC43
END DESCRIPTION:
XS GIS Cut Line= 4
      2764494.96      7061220.56      2764191.17      7060704.11
      2763956.79      7060504.46      2762977.13      7059919.26
#Sta/Elev= 30
  4100.5   501.6  4361.5  498.38  4490.3  495.89    4571  496.23  4666.1  495.09
  4773.9   496.3  4824.4  494.77  4880.6  494.63  4950.8  494.55  4966.1  493.26
  4980.3  489.79  4986.9  479.51  4988.6  477.93  5000.7  477.93  5005.5   483.2
  5011.5   483.2  5015.9  487.17  5021.7  490.12  5037.3  491.82  5292.1  490.82
  5359.1  491.93  5371.9  488.46  5387.5  492.07  5442.4  491.15    5547  493.48
    5584  492.37  5766.8  493.96    5977  498.35  6072.4  503.31  6148.7  509.28
#Mann= 5 ,-1 , 0
  4100.5     .05       0  4880.6     .16       0  4966.1     .07       0
  5037.3     .16       0  5442.4     .05       0
Bank Sta=4966.1,5037.3
XS Rating Curve= 0 ,0
Exp/Cntr=0.3,0.1

Type RM Length L Ch R = 1 ,368019  ,1739,1739,1739
BEGIN DESCRIPTION:
LFC44
END DESCRIPTION:
XS GIS Cut Line= 4
       2764520.4      7061062.98      2764542.73      7060743.17
      2764238.91      7060027.03      2763554.45      7059559.17
#Sta/Elev= 30
  3793.7   499.3  4124.9  497.88  4166.6  495.64  4235.1  495.69  4590.3  494.54
  4677.2  492.78  4774.9  493.88    4851  490.76  4939.7  490.67  4975.6  488.56
  4981.7  486.17  4990.5  477.44  5002.6  477.44  5005.5  478.57  5011.5   485.6
  5018.1  490.58  5026.4  491.01  5090.8  488.56  5119.2  489.96  5127.1  486.12
  5134.1  487.23  5140.2  485.42  5163.4  489.98  5226.8  491.88  5334.5  490.65
  5349.4  487.91  5370.4  491.24  5392.1  491.54  5609.5  495.42  5721.3  499.41
#Mann= 5 ,-1 , 0
  3793.7     .05       0  4235.1     .16       0  4939.7     .07       0
  5026.4     .16       0  5392.1     .05       0
Bank Sta=4939.7,5026.4
XS Rating Curve= 0 ,0
Exp/Cntr=0.3,0.1

Type RM Length L Ch R = 1 ,366280  ,1165,1165,1165
BEGIN DESCRIPTION:
LFC45
END DESCRIPTION:
XS GIS Cut Line= 3
      2765371.68      7059783.95      2764438.56      7059250.12
      2763679.48       7059306.5
#Sta/Elev= 30
  3680.1  503.88  3756.9  499.93    3803  499.16  3837.6  496.76  3905.3  495.06
  4072.2  493.56  4131.2  494.16  4249.2  491.45  4512.6  489.79  4540.3  488.28
  4555.8  489.77  4609.1  490.37  4652.2   490.2  4679.6  487.71  4747.7  489.76
  4768.7  488.76  4808.8  489.85    4859  488.26    4879  489.41  4929.2  489.17
  4959.3   487.8  5003.3  475.12  5015.5  475.12    5024  487.82  5029.4  490.71
  5049.5  491.11  5069.6  489.65  5115.8  491.28  5340.3  493.96  5516.3  498.46
#Mann= 4 ,-1 , 0
  3680.1     .16       0  4929.2     .07       0  5029.4     .16       0
  5115.8     .05       0
Bank Sta=4929.2,5029.4
XS Rating Curve= 0 ,0
Exp/Cntr=0.3,0.1

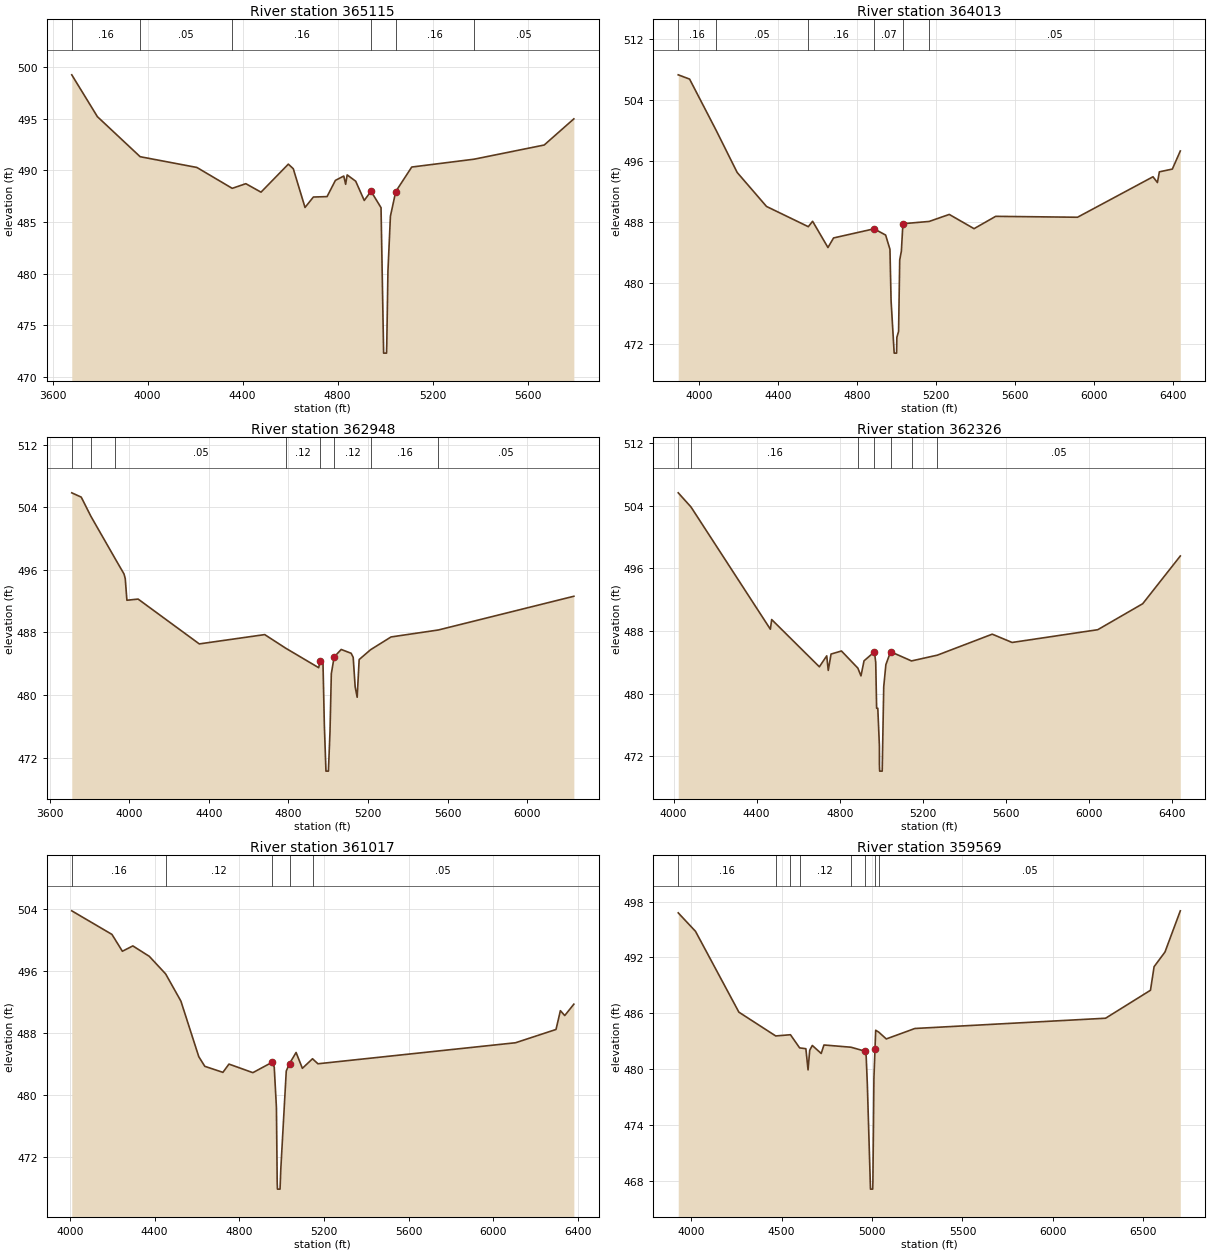
Type RM Length L Ch R = 1 ,365115  ,1102,1102,1102
BEGIN DESCRIPTION:
LFC46
END DESCRIPTION:
XS GIS Cut Line= 3
       2765632.1      7059319.53      2764629.53      7058503.59
      2763891.72      7058143.36
#Sta/Elev= 30
  3680.7  499.24  3788.7  495.19  3968.6  491.32  4207.4  490.28  4356.2  488.26
  4413.5  488.71  4477.4  487.89  4592.4   490.6  4613.2  490.16  4662.7  486.41
  4697.9  487.42  4755.4  487.46  4790.6  489.03  4825.8  489.45  4833.7  488.65
  4840.1  489.56    4876  488.95    4912  487.09  4940.5  487.98  4982.7  486.39
  4993.6  472.32  5005.8  472.32  5006.8  473.12  5011.8  480.26  5022.2  485.57
  5044.7  487.95  5111.9  490.32  5374.7  491.08  5669.6  492.45  5794.4  494.98
#Mann= 6 ,-1 , 0
  3680.7     .16       0  3968.6     .05       0  4356.2     .16       0
  4940.5     .07       0  5044.7     .16       0  5374.7     .05       0
Bank Sta=4940.5,5044.7
XS Rating Curve= 0 ,0
Exp/Cntr=0.3,0.1

Type RM Length L Ch R = 1 ,364013  ,1065,1065,1065
BEGIN DESCRIPTION:
LFC47
END DESCRIPTION:
XS GIS Cut Line= 3
      2765926.42      7058625.13      2765162.52      7057916.78
       2763843.1      7057201.52
#Sta/Elev= 30
  3895.9  507.34  3953.4  506.78    4088  500.04  4194.3  494.51  4342.9  490.04
  4554.6  487.38  4576.4  488.09  4654.1  484.64  4682.5   485.9  4887.7   487.1
  4946.2  486.28  4968.1   484.4  4973.8  477.65  4989.5  470.76  5001.7  470.76
  5003.1  472.83  5011.8  473.62  5017.5  483.01  5025.9  484.16  5033.7  487.77
  5166.7  488.07  5268.5  488.99    5394  487.12  5503.6  488.74    5918  488.62
  6300.2  493.94  6322.6  493.18  6332.5  494.59  6398.1  494.95  6438.5  497.33
#Mann= 6 ,-1 , 0
  3895.9     .16       0    4088     .05       0  4554.6     .16       0
  4887.7     .07       0  5033.7     .16       0  5166.7     .05       0
Bank Sta=4887.7,5033.7
XS Rating Curve= 0 ,0
Exp/Cntr=0.3,0.1

Type RM Length L Ch R = 1 ,362948  ,622,622,622
BEGIN DESCRIPTION:
LFC48
END DESCRIPTION:
XS GIS Cut Line= 4
      2766106.95       7058250.1      2765391.69      7057284.84
      2765280.58      7057187.62      2764108.45      7057104.39
#Sta/Elev= 30
  3710.6  505.83  3758.2  505.28  3806.8  502.83  3927.7  497.46  3973.2  495.46
  3979.4  494.88  3987.8   492.1  4044.1  492.25  4351.7  486.52  4680.6  487.71
  4786.3  485.97  4951.9  483.48  4959.5  484.39  4973.7  483.94  4980.4  476.14
  4988.5  470.26  5000.8  470.26  5008.8  475.28  5015.5  482.72  5029.7  484.85
  5065.2  485.81  5115.3  485.32  5125.4   484.8  5135.4  481.01  5145.4   479.7
  5155.4  484.52  5212.9  485.78  5315.8  487.41  5553.6   488.3  6234.7  492.61
#Mann= 8 ,-1 , 0
  3710.6     .05       0  3806.8     .16       0  3927.7     .05       0
  4786.3     .12       0  4959.5     .07       0  5029.7     .12       0
  5212.9     .16       0  5553.6     .05       0
Bank Sta=4959.5,5029.7
XS Rating Curve= 0 ,0
Exp/Cntr=0.3,0.1

Type RM Length L Ch R = 1 ,362326  ,1309,1309,1309
BEGIN DESCRIPTION:
LFC49
END DESCRIPTION:
XS GIS Cut Line= 3
      2766336.11      7057354.27       2765565.3      7056784.84
      2764149.31      7056430.84
#Sta/Elev= 30
  4022.4  505.66  4083.9  503.85  4466.1  488.23  4472.4  489.47  4702.1  483.43
  4737.5  484.83  4744.9  482.97  4758.4  485.06  4808.5  485.45  4887.5  483.26
  4902.5  482.27  4917.1  484.19  4967.2  485.34  4973.5  483.99  4977.8  478.13
  4983.5  478.13  4991.3  473.23  4991.4   470.9  4992.4   470.1  5004.7   470.1
    5012  480.87  5022.3   483.7    5045  485.36  5145.8  484.18  5270.4  484.92
  5534.6   487.6  5630.4  486.54  6042.7  488.17  6259.2  491.49  6440.3  497.59
#Mann= 7 ,-1 , 0
  4022.4     .05       0  4083.9     .16       0  4887.5     .12       0
  4967.2     .07       0    5045     .12       0  5145.8     .16       0
  5270.4     .05       0
Bank Sta=4967.2,5045
XS Rating Curve= 0 ,0
Exp/Cntr=0.3,0.1

Type RM Length L Ch R = 1 ,361017  ,1448,1448,1448
BEGIN DESCRIPTION:
LFC50
END DESCRIPTION:
XS GIS Cut Line= 3
      2766447.27      7056909.87      2765863.91      7056229.28
      2764433.39      7055861.24
#Sta/Elev= 30
  4008.1  503.82    4198  500.77  4247.4  498.59  4296.8  499.28  4374.7  497.93
  4451.8  495.66    4524  492.14  4608.5  484.95    4637   483.7  4722.6  482.92
  4751.2  483.99  4864.2  482.88    4955  484.22  4965.3  483.59  4975.6  478.36
  4979.3  468.61  4980.4  467.81  4992.7  467.81  4996.3  470.41  5022.1   483.1
  5037.6  484.06  5068.6  485.49  5098.3  483.44  5146.2  484.68  5171.8  484.03
    6106  486.75  6297.3  488.47    6318   490.9  6338.6  490.27  6381.6  491.74
#Mann= 5 ,-1 , 0
  4008.1     .16       0  4451.8     .12       0    4955     .07       0
  5037.6     .16       0  5146.2     .05       0
Bank Sta=4955,5037.6
XS Rating Curve= 0 ,0
Exp/Cntr=0.3,0.1

Type RM Length L Ch R = 1 ,359569  ,1467,1467,1467
BEGIN DESCRIPTION:
LFC51
END DESCRIPTION:
XS GIS Cut Line= 4
      2766760.63      7056341.58      2766326.58      7055655.79
      2766048.81      7055490.86      2764410.34      7055382.57
#Sta/Elev= 30
  3928.1  496.78  4023.7   494.8  4263.6  486.13  4467.2  483.58  4548.8  483.71
  4599.4   482.3    4634  482.21    4646  479.94  4655.2  482.04  4669.6  482.56
  4718.8   481.7    4734  482.61  4883.9  482.37  4961.6  481.94  4967.4  481.44
  4974.1   478.3  4991.3  467.15  5003.6  467.15  5004.7  467.95  5010.3  479.02
  5016.2482.1327  5020.1  484.19    5037  483.99  5078.7  483.26  5236.9  484.38
  6291.5  485.48  6539.8  488.48  6559.8  491.01    6620  492.58  6704.8     497
#Mann= 8 ,-1 , 0
  3928.1     .16       0  4467.2     .12       0  4548.8     .16       0
  4599.4     .12       0  4883.9     .16       0  4961.6     .07       0
  5016.2     .16       0    5037     .05       0
Bank Sta=4961.6,5016.2
XS Rating Curve= 0 ,0
Exp/Cntr=0.3,0.1

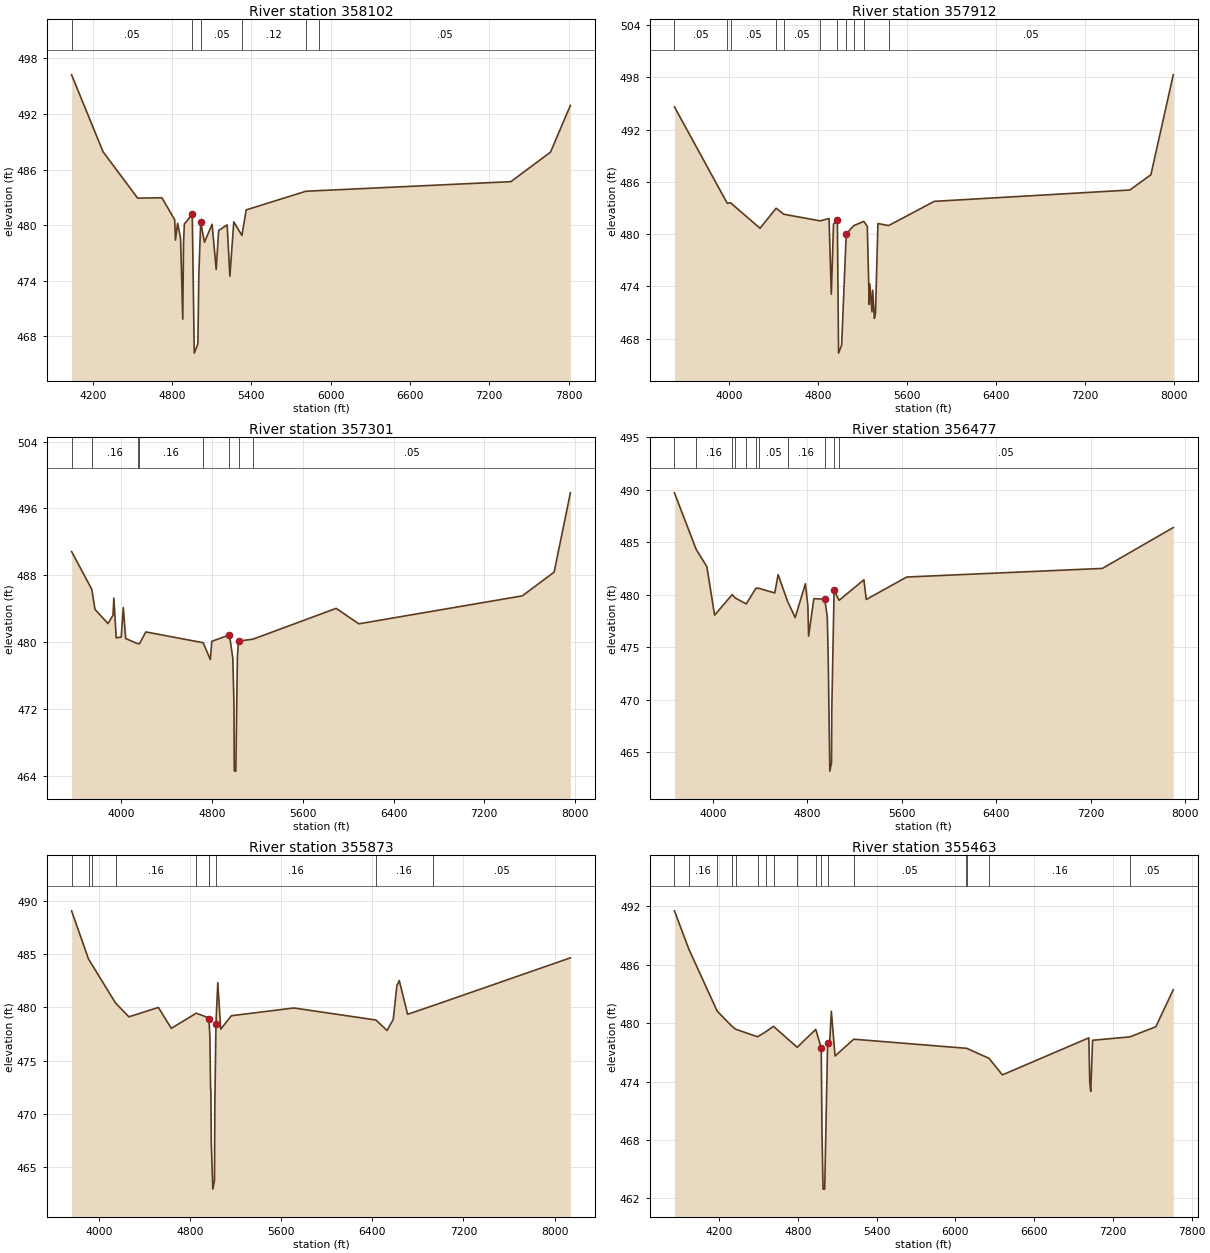
Type RM Length L Ch R = 1 ,358102  ,190,190,190
BEGIN DESCRIPTION:
LFC52
END DESCRIPTION:
XS GIS Cut Line= 6
      2767912.47      7056164.02      2767429.01      7055668.81
      2767259.74      7055408.39      2766986.31      7055334.61
      2766639.08       7055291.2      2764504.41      7055281.27
#Sta/Elev= 30
  4039.7  496.23  4277.6  487.93  4539.4  482.92  4723.1  482.96  4819.4   480.6
  4825.5  478.39  4841.8   480.2  4864.2   478.6  4880.9  469.86  4886.5  477.93
  4892.6  480.12  4952.8  481.19  4967.7  466.19  4995.2  467.18  5002.3   474.6
  5016.5  480.33  5044.7  478.16  5102.8   480.1  5133.8  475.22  5152.2  479.42
  5216.7  480.03  5237.4  474.49  5266.8  480.36  5328.6  478.89  5360.8  481.65
  5811.6  483.66  5910.6  483.73  7363.3   484.7  7663.3  487.88  7813.9  492.93
#Mann= 6 ,-1 , 0
  4039.7     .05       0  4952.8     .04       0  5016.5     .05       0
  5328.6     .12       0  5811.6     .16       0  5910.6     .05       0
Bank Sta=4952.8,5016.5
XS Rating Curve= 0 ,0
Exp/Cntr=0.3,0.1

Type RM Length L Ch R = 1 ,357912  ,611,611,611
BEGIN DESCRIPTION:
LFC53
END DESCRIPTION:
XS GIS Cut Line= 5
      2768903.83      7055454.93      2767468.08      7055347.63
      2767294.46      7055295.54      2766799.46      7055118.52
      2764453.79      7055056.96
#Sta/Elev= 30
  3504.3   494.6  3979.7  483.54  4010.1  483.59  4275.3  480.67  4420.4  482.97
    4489  482.28    4817  481.52    4897  481.79  4917.2   473.1  4937.1  481.15
  4966.8   481.6    4972  481.62  4982.7  466.34  5010.3  467.26  5051.7  480.02
  5120.5  480.98  5210.2481.4604  5241.6  480.89    5259  471.93  5264.3  474.29
  5284.1  471.08  5289.8  473.56  5305.3  470.32  5315.3  470.92  5337.2  481.21
  5433.4  480.98  5845.5  483.76  7606.2  485.06  7796.2  486.81  7997.5  498.28
#Mann= 11 ,-1 , 0
  3504.3     .05       0  3979.7     .16       0  4010.1     .05       0
  4420.4     .08       0    4489     .05       0    4817     .12       0
  4966.8     .07       0  5051.7     .12       0  5120.5     .05       0
  5210.2     .16       0  5433.4     .05       0
Bank Sta=4966.8,5051.7
XS Rating Curve= 0 ,0
Exp/Cntr=0.3,0.1

Type RM Length L Ch R = 1 ,357301  ,824,824,824
BEGIN DESCRIPTION:
LFC54
END DESCRIPTION:
XS GIS Cut Line= 3
      2768853.13      7055360.86      2767533.18       7054978.7
       2764511.7      7054818.18
#Sta/Elev= 30
  3559.9  490.83  3738.1  486.31  3766.2  483.91  3880.7  482.21  3925.1  483.21
  3932.7  485.27  3953.4   480.5  3997.4   480.6    4016  484.13  4036.8  480.42
  4141.8  479.81  4158.7   479.8  4214.6  481.21  4720.7479.9189  4783.4  477.91
  4796.8  480.09  4952.3  480.85  4982.3  478.05  4992.3  472.35  4994.2  465.35
    4996  464.55  5008.7  464.55  5022.4  478.28  5032.4  480.12  5158.9  480.34
  5893.6  484.03  6093.9  482.18  7535.9  485.53  7816.3  488.37  7959.8  497.86
#Mann= 8 ,-1 , 0
  3559.9     .05       0  3738.1     .16       0  4141.8     .05       0
  4158.7     .16       0  4720.7     .12       0  4952.3     .07       0
  5032.4     .16       0  5158.9     .05       0
Bank Sta=4952.3,5032.4
XS Rating Curve= 0 ,0
Exp/Cntr=0.3,0.1

Type RM Length L Ch R = 1 ,356477  ,604,604,604
BEGIN DESCRIPTION:
LFC55
END DESCRIPTION:
XS GIS Cut Line= 3
      2768896.55      7055295.74      2767832.66       7054557.7
       2764924.1       7054195.9
#Sta/Elev= 30
  3675.1   489.7  3859.3  484.31  3949.6  482.67  4015.1  478.05  4164.6  480.01
  4188.1   479.7  4283.2  479.12  4365.8  480.62  4394.3  480.59  4525.1  480.16
  4553.3  481.91  4633.3  479.37    4698  477.82  4784.4  481.04  4805.4  478.96
  4811.5  476.05    4856  479.62  4948.6  479.57  4969.9  477.89  4977.6   474.1
  4991.4  463.19  5005.9  463.99  5007.9  468.97  5027.6  480.44  5070.2479.4612
  5280.2  481.42  5300.1  479.54  5642.7  481.68  7300.5   482.5  7900.9  486.39
#Mann= 11 ,-1 , 0
  3675.1     .05       0  3859.3     .16       0  4164.6     .05       0
  4188.1     .16       0  4283.2     .05       0  4365.8     .16       0
  4394.3     .05       0  4633.3     .16       0  4948.6     .07       0
  5027.6     .16       0  5070.2     .05       0
Bank Sta=4948.6,5027.6
XS Rating Curve= 0 ,0
Exp/Cntr=0.3,0.1

Type RM Length L Ch R = 1 ,355873  ,410,410,410
BEGIN DESCRIPTION:
LFC56
END DESCRIPTION:
XS GIS Cut Line= 3
      2768968.92      7055201.68      2768267.56      7054200.06
      2765285.92      7053161.19
#Sta/Elev= 30
    3759  489.06  3907.6  484.54  3935.3  484.06  4144.5  480.42  4262.1  479.12
  4521.1     480  4634.4  478.04  4854.1  479.46  4962.2479.0225  4964.8  478.95
  4973.6   477.2  4979.6   472.3  4981.8   472.3  4985.9  467.24  4999.3  462.96
  5013.8  463.76  5016.9  470.97  5026.8  478.48  5042.7  482.32  5068.5  477.96
  5161.7  479.22  5710.6  479.95  6431.3  478.82  6528.6  477.84  6583.5  478.87
  6615.3  482.04  6636.4  482.52  6709.8  479.36  6930.5  480.16  8139.2  484.65
#Mann= 10 ,-1 , 0
    3759     .05       0  3907.6     .16       0  3935.3     .05       0
  4144.5     .16       0  4854.1     .12       0  4962.2     .16       0
  4964.8     .07       0  5026.8     .16       0  6431.3     .16       0
  6930.5     .05       0
Bank Sta=4964.8,5026.8
XS Rating Curve= 0 ,0
Exp/Cntr=0.3,0.1

Type RM Length L Ch R = 1 ,355463  ,644,644,644
BEGIN DESCRIPTION:
LFC58
END DESCRIPTION:
XS GIS Cut Line= 3
      2769106.39      7055179.95      2768592.66      7054188.67
      2766813.92      7052178.55
#Sta/Elev= 30
  3859.1  491.51  3969.4  487.56  4184.7  481.22  4294.6   479.7  4324.4  479.37
  4492.3  478.59  4555.7479.1105  4613.8  479.66  4794.4  477.51  4935.8  479.35
  4977.6  477.43  4983.4  468.82  4991.3  462.96    5004  462.96    5026   477.9
  5040.3  477.62  5054.5  481.21  5082.9  476.62  5225.1  478.34  6080.9  477.41
  6084.9  477.41  6255.9  476.38  6357.7  474.68  7016.8  478.48  7023.5  473.96
    7031  472.99  7045.2  478.23  7329.7  478.58    7527  479.62  7659.7  483.41
#Mann= 17 ,-1 , 0
  3859.1     .05       0  3969.4     .16       0  4184.7     .05       0
  4294.6     .16       0  4324.4     .05       0  4492.3     .16       0
  4555.7     .05       0  4613.8     .16       0  4794.4     .12       0
  4935.8     .16       0  4977.6     .07       0    5026     .16       0
  5225.1     .05       0  6080.9     .16       0  6084.9     .05       0
  6255.9     .16       0  7329.7     .05       0
Bank Sta=4977.6,5026
XS Rating Curve= 0 ,0
Exp/Cntr=0.3,0.1

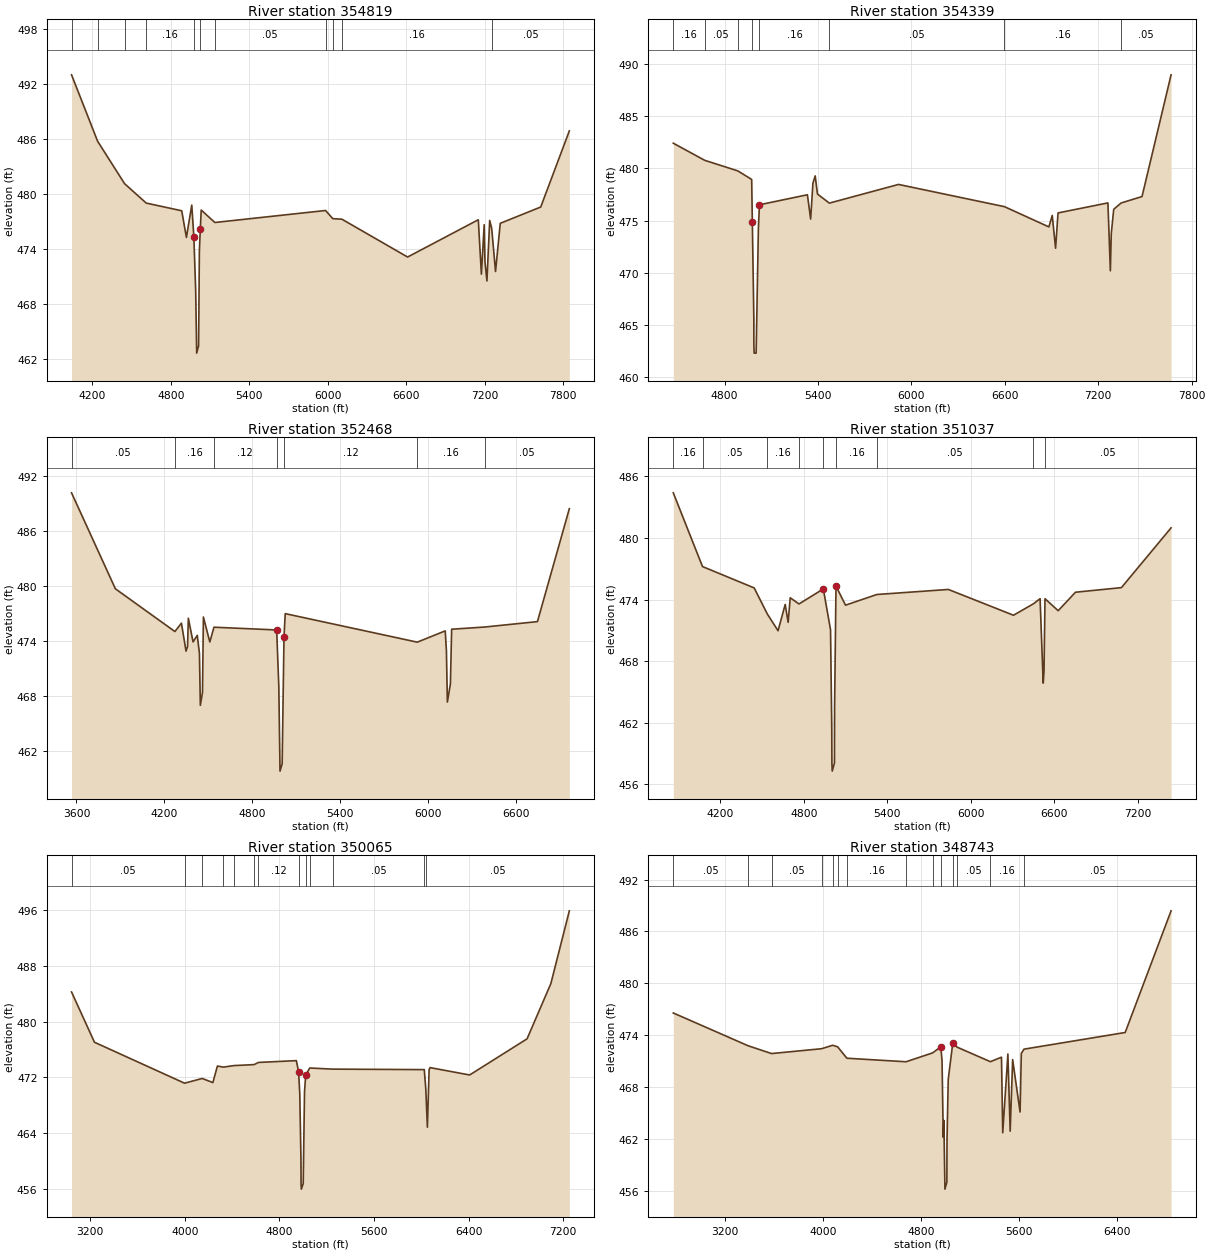
Type RM Length L Ch R = 1 ,354819  ,480,480,480
BEGIN DESCRIPTION:
LFC57
END DESCRIPTION:
XS GIS Cut Line= 5
      2769323.47      7055114.83      2769111.31      7054424.02
      2768986.31      7054241.72      2768469.27      7053711.65
      2767290.19      7051945.54
#Sta/Elev= 30
  4040.7  493.01  4240.1  485.76  4446.2  481.13  4611.8  479.01  4883.4  478.17
  4919.3  475.26  4960.2  478.79  4976.1  475.35  4990.1  469.55  4997.9  462.63
  5012.5  463.43  5018.4  473.72  5025.4  476.13  5032.5  478.25  5136.9  476.89
  5983.9   478.2  6038.6477.3111  6108.8  477.25  6611.3  473.12    7152  477.19
  7175.7  471.25  7197.1  476.65  7203.1  472.58  7218.1  470.51  7239.1  477.11
  7254.3476.2708  7283.9  471.54    7320   476.8  7629.6  478.58  7848.4  486.89
#Mann= 11 ,-1 , 0
  4040.7     .05       0  4240.1     .16       0  4446.2     .05       0
  4611.8     .16       0  4976.1     .07       0  5025.4     .16       0
  5136.9     .05       0  5983.9     .16       0  6038.6     .05       0
  6108.8     .16       0  7254.3     .05       0
Bank Sta=4976.1,5025.4
XS Rating Curve= 0 ,0
Exp/Cntr=0.3,0.1

Type RM Length L Ch R = 1 ,354339  ,1871,1871,1871
BEGIN DESCRIPTION:
LFC59
END DESCRIPTION:
XS GIS Cut Line= 4
      2769512.35      7054736.54      2769423.81      7054252.14
      2768660.76      7053683.09      2767775.05      7052169.95
#Sta/Elev= 30
  4470.2  482.41  4672.1  480.77  4884.2  479.76  4973.6  478.94    4978  474.85
  4987.6  465.63  4987.8   463.1  4989.6   462.3  5002.3   462.3  5016.8  474.24
  5023.5  476.51  5331.7  477.47  5352.5  475.14  5367.1  478.58  5381.7  479.28
  5396.3  477.54  5472.6  476.67    5917  478.46  6597.6  476.33  6882.9  474.39
  6904.4  475.49  6925.9  472.35  6941.6  475.73  7262.1  476.69  7277.8  470.19
  7283.6  473.74  7299.3  476.08  7346.6  476.68  7481.1   477.3  7667.8  488.96
#Mann= 8 ,-1 , 0
  4470.2     .16       0  4672.1     .05       0  4884.2     .16       0
    4978     .07       0  5023.5     .16       0  5472.6     .05       0
  6597.6     .16       0  7346.6     .05       0
Bank Sta=4978,5023.5
XS Rating Curve= 0 ,0
Exp/Cntr=0.3,0.1

Type RM Length L Ch R = 1 ,352468  ,1431,1431,1431
BEGIN DESCRIPTION:
LFC60
END DESCRIPTION:
XS GIS Cut Line= 3
      2770205.05      7054444.83      2769970.68      7053647.97
      2767912.46      7052111.97
#Sta/Elev= 30
  3566.7  490.12  3865.9  479.66  4272.3     475    4317  475.91  4348.3  472.86
  4358.7  473.36  4364.1  476.45  4396.3  473.87  4425.2  474.58  4439.8  472.63
  4446.1  466.95  4460.7  468.37  4466.9  476.58  4510.7  473.86  4539.1  475.47
  4967.3  475.17  4981.9  468.98  4990.1  459.78  5004.7  460.58  5017.3  474.44
  5025.7  476.95  5927.2  473.84  6118.1  475.07  6126.3  472.88  6132.7  467.31
  6153.5  469.29  6161.9  475.25  6387.7  475.49  6747.7  476.08  6965.5  488.39
#Mann= 7 ,-1 , 0
  3566.7     .05       0  4272.3     .16       0  4539.1     .12       0
  4967.3     .03       0  5017.3     .12       0  5927.2     .16       0
  6387.7     .05       0
Bank Sta=4967.3,5017.3
XS Rating Curve= 0 ,0
Exp/Cntr=0.3,0.1

Type RM Length L Ch R = 1 ,351037  ,972,972,972
BEGIN DESCRIPTION:
LFC61
END DESCRIPTION:
XS GIS Cut Line= 4
      2771231.08      7053382.34      2770304.01      7052772.97
      2769739.26      7052672.13      2768100.65      7051721.28
#Sta/Elev= 30
  3861.6   484.4  4071.5  477.22  4442.9  475.14  4537.9  472.59  4614.5  470.97
  4665.8  473.53  4686.9  471.79  4701.9  474.18  4764.9  473.58    4940  475.04
  4991.7  471.06  5000.5  461.47  5001.5   458.1    5004   457.3  5019.8   458.1
  5020.8  463.45  5030.9  475.32  5099.3  473.46  5324.7   474.5  5838.7  474.99
  6306.5  472.48  6449.3473.5891  6497.7  474.09  6520.1  465.87  6525.9  466.99
    6533  474.09  6627.7  472.92    6752  474.72  7082.3  475.17  7439.2  480.99
#Mann= 9 ,-1 , 0
  3861.6     .16       0  4071.5     .05       0  4537.9     .16       0
  4764.9     .12       0    4940     .07       0  5030.9     .16       0
  5324.7     .05       0  6449.3     .16       0    6533     .05       0
Bank Sta=4940,5030.9
XS Rating Curve= 0 ,0
Exp/Cntr=0.3,0.1

Type RM Length L Ch R = 1 ,350065  ,1322,1322,1322
BEGIN DESCRIPTION:
LFC62
END DESCRIPTION:
XS GIS Cut Line= 5
      2771972.38      7053088.95      2770298.81      7052220.89
      2770095.68      7052205.27      2769634.61      7052090.29
      2768165.73      7051352.23
#Sta/Elev= 30
  3043.1  484.25  3236.8  477.03  3998.4  471.15  4147.6471.8304  4237.6  471.24
  4276.2  473.61  4327.4  473.46  4417.5  473.68  4586.9  473.82  4622.8  474.13
  4943.6  474.39  4962.3   472.8  4972.3  469.67  4982.4  460.22  4983.2  456.74
  4985.7  455.94  5001.5  456.74  5012.5  469.92  5022.5   472.3  5056.3473.3302
  5250.7  473.17  6024.9   473.1  6037.7  470.33  6051.2  464.83  6065.7  473.08
  6073.5  473.39  6408.4  472.33  6893.9  477.52    7095  485.45  7251.2   495.9
#Mann= 13 ,-1 , 0
  3043.1     .05       0  3998.4     .16       0  4147.6     .05       0
  4327.4     .16       0  4417.5     .12       0  4586.9     .16       0
  4622.8     .12       0  4962.3     .07       0  5022.5     .12       0
  5056.3     .16       0  5250.7     .05       0  6024.9     .16       0
  6037.7     .05       0
Bank Sta=4962.3,5022.5
XS Rating Curve= 0 ,0
Exp/Cntr=0.3,0.1

Type RM Length L Ch R = 1 ,348743  ,820,820,820
BEGIN DESCRIPTION:
LFC63
END DESCRIPTION:
XS GIS Cut Line= 3
      2771934.21      7052903.17      2770397.76      7051507.35
        2768436.      7051239.99
#Sta/Elev= 30
  2780.9  476.56  3390.8  472.76  3581.4  471.86  3988.9  472.42  4079.5472.8202
  4119.9  472.64  4195.3  471.32    4677  470.91  4894.2  471.94  4960.4  472.64
  4970.5  471.05  4980.4  462.17  4985.4  464.11  4994.1  456.16  5009.9  456.96
  5010.9  461.81    5021  468.87  5057.8  473.07  5093.5   472.6  5364.2  470.92
  5454.9  471.44    5465  462.69    5507  471.81  5525.6  462.87  5545.8  471.16
  5606.3  465.09  5616.4  471.88  5638.5472.3698  6462.7   474.3  6836.6  488.39
#Mann= 14 ,-1 , 0
  2780.9     .05       0  3390.8     .16       0  3581.4     .05       0
  3988.9     .12       0  4079.5     .16       0  4119.9     .12       0
  4195.3     .16       0    4677     .05       0  4894.2     .12       0
  4960.4     .07       0  5057.8     .12       0  5093.5     .05       0
  5364.2     .16       0  5638.5     .05       0
Bank Sta=4960.4,5057.8
XS Rating Curve= 0 ,0
Exp/Cntr=0.3,0.1

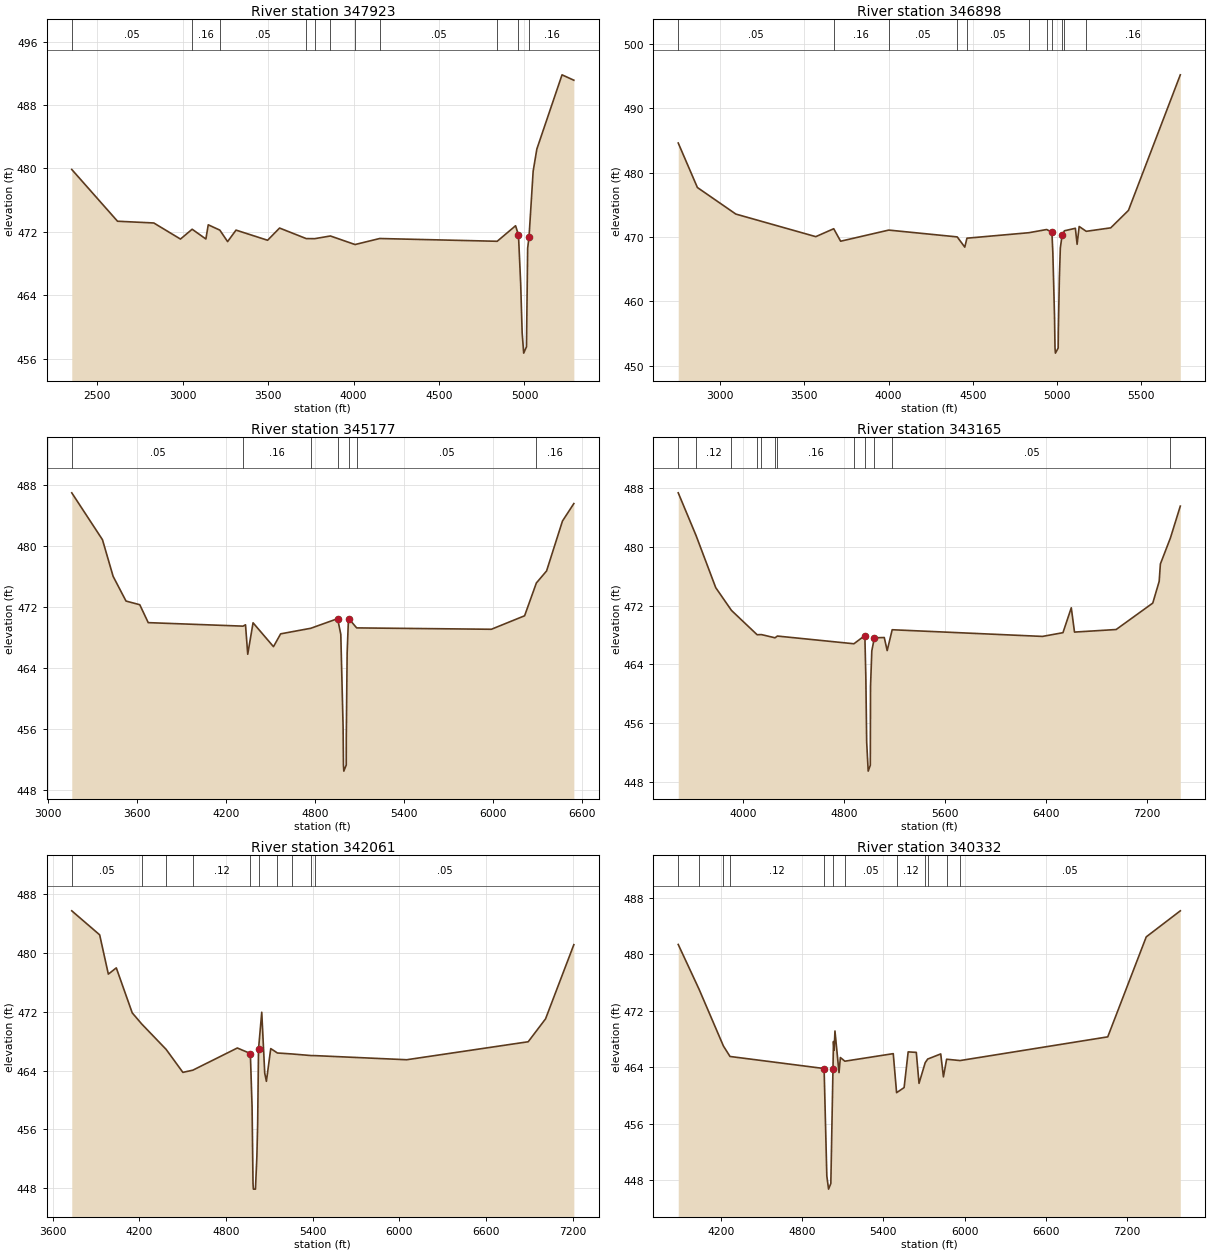
Type RM Length L Ch R = 1 ,347923  ,1025,1025,1025
BEGIN DESCRIPTION:
LFC64
END DESCRIPTION:
XS GIS Cut Line= 3
      2772059.23      7052918.81      2770382.14      7051054.22
      2770225.87      7050653.14
#Sta/Elev= 30
  2350.8  479.87  2618.5  473.34  2830.8  473.12    2987  471.09  3055.3  472.33
  3135.7   471.1  3149.5  472.89  3217.2  472.22  3262.8  470.77  3312.1  472.22
  3496.8  470.94    3567  472.48  3722.8  471.15  3772.5  471.14  3864.2  471.48
  4008.6   470.4  4152.9  471.16  4840.6  470.81  4948.1  472.77  4965.1  471.59
    4978  465.46  4986.6  459.28  4995.6   456.7  5011.9   457.5  5018.8  469.93
    5027  471.41    5051  479.66  5072.5  482.44    5220  491.81  5289.1  491.13
#Mann= 11 ,-1 , 0
  2350.8     .05       0  3055.3     .16       0  3217.2     .05       0
  3722.8     .16       0  3772.5     .05       0  3864.2     .12       0
  4008.6     .16       0  4152.9     .05       0  4840.6     .12       0
  4965.1     .07       0    5027     .16       0
Bank Sta=4965.1,5027
XS Rating Curve= 0 ,0
Exp/Cntr=0.3,0.1

Type RM Length L Ch R = 1 ,346898  ,1721,1721,1721
BEGIN DESCRIPTION:
LFC65
END DESCRIPTION:
XS GIS Cut Line= 3
      2772370.57      7052814.96      2771330.44      7050896.79
      2770621.25      7050532.07
#Sta/Elev= 30
  2751.8  484.62  2865.5   477.7  3093.7  473.57  3568.1  470.06  3674.5  471.29
  3715.5  469.35  4001.2  471.08  4407.4  470.02  4452.3  468.43  4465.1  469.82
  4832.2  470.67  4938.3  471.17  4969.3  470.75  4974.9  467.57  4984.9   457.6
  4987.7  452.75  4990.2  451.95  5006.5  452.75  5007.4  455.39  5013.7  463.73
  5019.3  468.29  5029.9   470.3  5043.5  470.97  5108.6  471.36  5118.9  468.87
  5131.1  471.64  5173.1  470.89  5318.5  471.43  5423.5  474.14  5731.3  495.22
#Mann= 11 ,-1 , 0
  2751.8     .05       0  3674.5     .16       0  4001.2     .05       0
  4407.4     .16       0  4465.1     .05       0  4832.2     .12       0
  4938.3     .05       0  4969.3     .03       0  5029.9     .05       0
  5043.5     .12       0  5173.1     .16       0
Bank Sta=4969.3,5029.9
XS Rating Curve= 0 ,0
Exp/Cntr=0.3,0.1

Type RM Length L Ch R = 1 ,345177  ,2012,2012,2012
BEGIN DESCRIPTION:
LFC66
END DESCRIPTION:
XS GIS Cut Line= 3
      2773336.41      7051990.97      2772357.06      7050545.58
      2770947.08      7049709.04
#Sta/Elev= 30
  3161.8  486.96  3368.8  480.81  3440.7     476  3527.6  472.76  3620.4  472.28
  3677.4  469.93  4316.6  469.47  4333.3  469.65  4348.3  465.78  4384.2  469.91
  4521.9  466.78  4570.2  468.46  4773.4  469.19  4954.3  470.45  4975.8   468.4
  4991.4  456.23  4993.7  451.25  4996.2  450.45  5012.5  451.25  5012.8  454.82
  5018.6  465.94  5026.4  469.89  5034.2  470.35  5082.8  469.24  5991.1  469.06
 6215.23470.8306  6294.4  475.13  6363.3  476.71  6470.5  483.26  6547.2  485.55
#Mann= 7 ,-1 , 0
  3161.8     .05       0  4316.6     .16       0  4773.4     .12       0
  4954.3     .07       0  5034.2     .12       0  5082.8     .05       0
  6294.4     .16       0
Bank Sta=4954.3,5034.2
XS Rating Curve= 0 ,0
Exp/Cntr=0.3,0.1

Type RM Length L Ch R = 1 ,343165  ,1104,1104,1104
BEGIN DESCRIPTION:
LFC67
END DESCRIPTION:
XS GIS Cut Line= 3
      2774653.42       7051025.1      2773498.49       7050072.8
       2771060.3      7049654.05
#Sta/Elev= 30
  3490.1  487.38  3631.2  481.56  3786.8  474.46  3911.2  471.36  4114.1  468.05
  4147.8  468.07  4255.9  467.63  4273.7  467.87  4879.5466.8194    4966  467.94
  4973.9  462.25  4980.4  453.45  4992.5  449.47  5009.2  450.27  5010.8  460.96
    5021  465.85  5041.3  467.63  5119.5  467.67  5142.7  465.89  5182.2468.7294
  6370.5  467.82  6532.8  468.33  6598.7  471.72  6624.1  468.41  6953.5  468.76
  7243.1  472.36  7293.8  475.32  7303.2  477.68  7382.8  481.24  7460.9  485.57
#Mann= 12 ,-1 , 0
  3490.1     .16       0  3631.2     .12       0  3911.2     .16       0
  4114.1     .12       0  4147.8     .16       0  4255.9     .12       0
  4273.7     .16       0  4879.5     .12       0    4966     .07       0
  5041.3     .12       0  5182.2     .05       0  7382.8     .16       0
Bank Sta=4966,5041.3
XS Rating Curve= 0 ,0
Exp/Cntr=0.3,0.1

Type RM Length L Ch R = 1 ,342061  ,1729,1729,1729
BEGIN DESCRIPTION:
LFC68
END DESCRIPTION:
XS GIS Cut Line= 4
      2775139.69      7049768.85      2774099.61      7049491.95
      2773863.21      7049377.13      2771729.46      7049269.09
#Sta/Elev= 30
    3732  485.76  3925.1  482.49  3985.2  477.14  4040.3  477.99  4150.4  471.87
  4215.3  470.37  4385.7  466.88  4501.2  463.76  4570.3  464.06    4878  467.08
  4968.3  466.33  4980.2  459.03  4986.7  448.66  4989.2  447.86  5003.5  447.86
  5013.4  452.29  5018.9  456.83  5024.7   466.9  5047.1  471.95  5067.8  463.65
  5079.3  462.54  5109.4     467  5155.5   466.4  5254.6  466.27  5388.6  466.05
  5417.4  466.04  6050.6  465.48  6891.7  467.93  7011.8  471.05  7207.6  481.15
#Mann= 10 ,-1 , 0
    3732     .05       0  4215.3     .12       0  4385.7     .16       0
  4570.3     .12       0  4968.3     .07       0  5024.7     .12       0
  5155.5     .07       0  5254.6     .05       0  5388.6     .07       0
  5417.4     .05       0
Bank Sta=4968.3,5024.7
XS Rating Curve= 0 ,0
Exp/Cntr=0.3,0.1

Type RM Length L Ch R = 1 ,340332  ,2200,2200,2200
BEGIN DESCRIPTION:
LFC69
END DESCRIPTION:
XS GIS Cut Line= 3
      2775281.61      7048992.17        2774336.      7048546.38
      2771678.02      7048638.69
#Sta/Elev= 30
  3886.2  481.37  4039.4  475.05  4219.7  466.98  4268.3   465.5  4962.6  463.79
  4982.7  448.57  4995.5   446.7  5012.3   447.5 5028.07 463.718  5031.8  467.62
  5036.8  466.38  5042.7  469.11  5072.7  463.21  5082.7  465.35  5115.7  464.83
  5472.9   465.9  5497.5  460.37    5553  461.09    5583  466.15    5643  466.08
  5663.1  461.69  5708.5  464.61  5726.8  465.13  5823.2  465.86  5843.2  462.61
  5866.7  465.11  5965.9  464.92  7055.8  468.28  7339.9  482.45  7591.2  486.14
#Mann= 12 ,-1 , 0
  3886.2     .16       0  4039.4     .05       0  4219.7     .16       0
  4268.3     .12       0  4962.6     .07       0 5028.07     .12       0
  5115.7     .05       0  5497.5     .12       0  5708.5     .07       0
  5726.8     .12       0  5866.7     .16       0  5965.9     .05       0
Bank Sta=4962.6,5028.07
XS Rating Curve= 0 ,0
Exp/Cntr=0.3,0.1