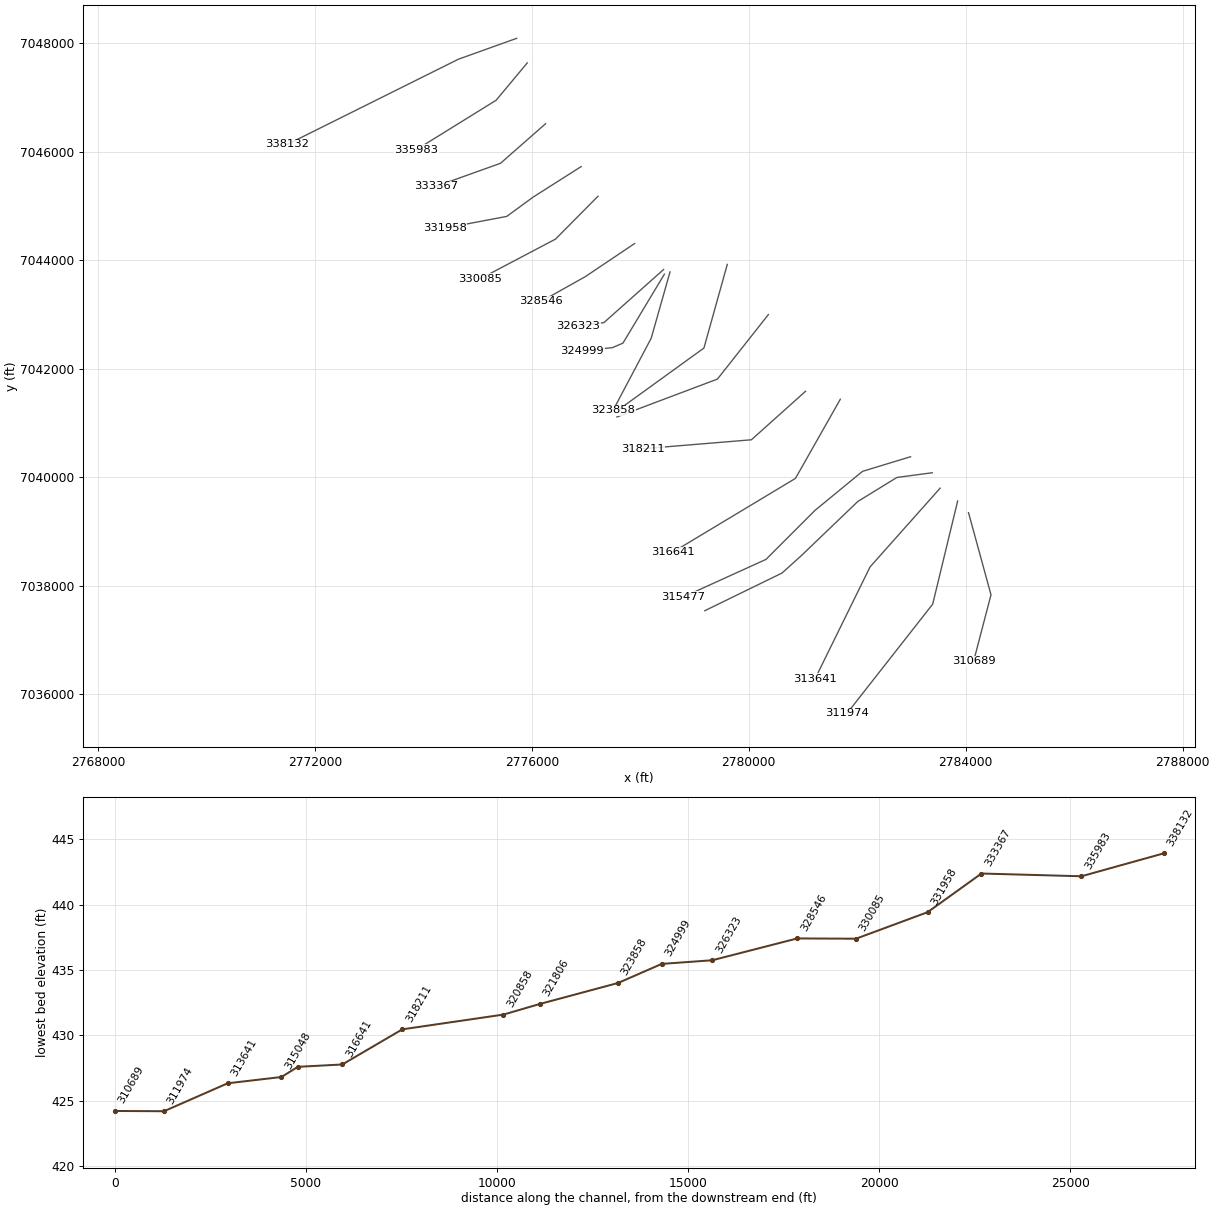
HEC-RAS study Lake Fork Creek.prj: Lake Fork Creek Base Level Engineering

--- Lake Fork Creek.g01 (geometry) --- (continued)

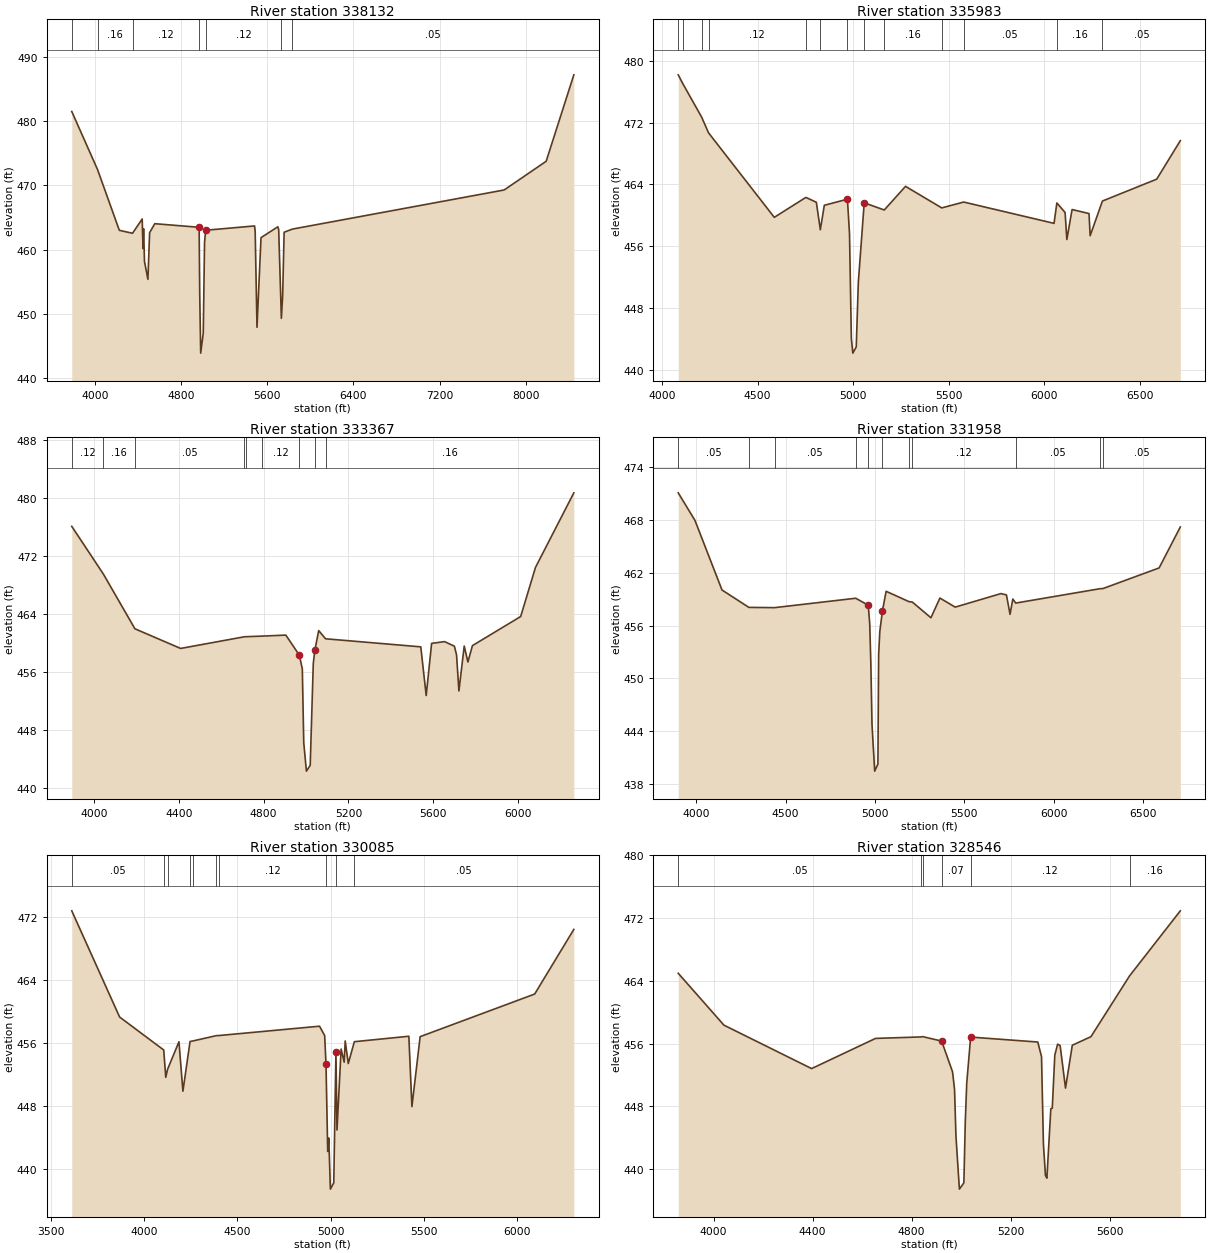
Type RM Length L Ch R = 1 ,338132  ,2149,2149,2149
BEGIN DESCRIPTION:
LFC70
END DESCRIPTION:
XS GIS Cut Line= 3
      2775720.56      7048093.85      2774646.69      7047708.88
      2771495.06      7046139.37
#Sta/Elev= 30
  3785.3  481.49  4024.8  472.46  4226.8  463.02  4349.6462.5638  4439.2  464.78
  4446.6   460.2  4451.9  463.28  4460.5  458.17  4492.3   455.4  4508.1  462.65
  4556.1  464.05  4967.8  463.49  4973.3  453.17  4982.4  443.93  5006.2  447.06
  5018.1  461.14  5028.5  463.03  5482.7   463.7  5488.3  462.78  5505.1  447.95
  5542.4  461.88  5698.8  463.57  5706.5  463.14  5731.4449.3329  5743.5  452.88
  5756.9  462.72  5833.9  463.21  7799.8  469.29    8190  473.75  8446.9  487.19
#Mann= 7 ,-1 , 0
  3785.3     .05       0  4024.8     .16       0  4349.6     .12       0
  4967.8     .07       0  5028.5     .12       0  5731.4     .16       0
  5833.9     .05       0
Bank Sta=4967.8,5028.5
XS Rating Curve= 0 ,0
Exp/Cntr=0.3,0.1

Type RM Length L Ch R = 1 ,335983  ,2616,2616,2616
BEGIN DESCRIPTION:
LFC71
END DESCRIPTION:
XS GIS Cut Line= 3
      2775916.42       7047641.3      2775342.35      7046952.42
      2773870.03      7046040.66
#Sta/Elev= 30
  4084.9  478.19  4109.7  477.01  4207.2  472.73  4243.7  470.68  4587.7  459.75
  4753.2  462.33    4808   461.7  4828.8  458.15  4849.7  461.31  4970.7   462.1
  4981.6   457.6  4991.2  444.09  4998.9  442.18  5016.8  442.98  5027.8  451.37
  5058.6  461.63  5163.5   460.7  5274.8  463.76  5464.5  460.97  5579.3  461.73
  6052.3  458.97  6067.2  461.61  6110.2  460.38  6119.4  456.88  6146.8  460.76
  6235.5  460.24  6241.4  457.37  6305.7  461.86  6589.9  464.69  6713.4  469.67
#Mann= 13 ,-1 , 0
  4084.9     .16       0  4109.7     .12       0  4207.2     .16       0
  4243.7     .12       0  4753.2     .16       0  4828.8     .12       0
  4970.7     .07       0  5058.6     .12       0  5163.5     .16       0
  5464.5     .12       0  5579.3     .05       0  6067.2     .16       0
  6305.7     .05       0
Bank Sta=4970.7,5058.6
XS Rating Curve= 0 ,0
Exp/Cntr=0.3,0.1

Type RM Length L Ch R = 1 ,333367  ,1409,1409,1409
BEGIN DESCRIPTION:
LFC72
END DESCRIPTION:
XS GIS Cut Line= 3
      2776254.18      7046520.18       2775423.4      7045790.72
      2774234.64       7045365.2
#Sta/Elev= 30
  3895.1  476.13  4044.2  469.55    4193  462.01  4408.5   459.3  4709.6  460.91
  4717.9  460.92    4792     461  4904.8  461.14  4968.4  458.38  4982.6  456.48
  4989.3  446.31  5001.9  442.39  5019.8  443.19  5034.3  457.23  5041.5  459.02
  5059.8  461.76  5092.3  460.63  5541.4  459.52  5566.9  452.81  5592.4     460
  5653.9  460.24    5700  459.61  5710.1   458.4  5721.2  453.44  5746.2  459.63
  5763.7  457.43    5785  459.69  6012.5   463.7  6082.4  470.47  6263.3  480.75
#Mann= 9 ,-1 , 0
  3895.1     .12       0  4044.2     .16       0    4193     .05       0
  4709.6     .12       0  4717.9     .05       0    4792     .12       0
  4968.4     .07       0  5041.5     .12       0  5092.3     .16       0
Bank Sta=4968.4,5041.5
XS Rating Curve= 0 ,0
Exp/Cntr=0.3,0.1

Type RM Length L Ch R = 1 ,331958  ,1873,1873,1873
BEGIN DESCRIPTION:
LFC73
END DESCRIPTION:
XS GIS Cut Line= 4
      2776909.33      7045729.95      2776017.76      7045162.59
      2775538.22      7044811.38      2774398.35      7044595.55
#Sta/Elev= 30
  3898.5  471.11    3992  467.98  4143.6  460.05    4294  458.07  4437.9  458.04
  4892.3  459.11  4962.3  458.32  4970.7  456.24  4976.9  451.77  4983.5  444.76
  4998.5  439.43  5016.5  440.23  5020.7  452.71  5027.1  455.31  5041.8  457.67
  5062.6   459.9    5191  458.72    5209  458.68  5313.5  456.89  5363.7  459.13
  5449.4   458.1  5705.6  459.64  5736.2  459.49  5756.5  457.28  5771.9  459.02
  5788.1  458.56  6261.5   460.2  6276.4  460.21  6591.1  462.56  6709.8  467.22
#Mann= 11 ,-1 , 0
  3898.5     .05       0    4294     .12       0  4437.9     .05       0
  4892.3     .12       0  4962.3     .07       0  5041.8     .12       0
    5191     .07       0    5209     .12       0  5788.1     .05       0
  6261.5     .07       0  6276.4     .05       0
Bank Sta=4962.3,5041.8
XS Rating Curve= 0 ,0
Exp/Cntr=0.3,0.1

Type RM Length L Ch R = 1 ,330085  ,1539,1539,1539
BEGIN DESCRIPTION:
LFC74
END DESCRIPTION:
XS GIS Cut Line= 3
      2777219.95      7045182.82      2776436.51      7044392.63
      2775039.23      7043656.86
#Sta/Elev= 30
  3612.2  472.81  3868.7   459.3  4105.3   455.1  4116.2  451.62  4125.8  452.64
  4186.9  456.15  4208.1  449.86  4246.4  456.18  4263.2  456.26  4387.5  456.93
  4400.6  456.94  4940.5  458.13  4968.1  456.94  4975.3  453.29  4984.5   442.2
  4990.2   443.9  4998.8   437.4  5016.9   438.2  5028.6  454.86  5034.2  444.92
  5056.3  455.22  5072.7  453.55  5078.3  456.25  5094.7  453.38  5127.4  456.16
  5419.5  456.85  5435.9   447.9    5480   456.8  6094.1  462.22  6304.1  470.45
#Mann= 10 ,-1 , 0
  3612.2     .05       0  4105.3     .07       0  4125.8     .12       0
  4246.4     .05       0  4263.2     .12       0  4387.5     .07       0
  4400.6     .12       0  4975.3     .07       0  5028.6     .16       0
  5127.4     .05       0
Bank Sta=4975.3,5028.6
XS Rating Curve= 0 ,0
Exp/Cntr=0.3,0.1

Type RM Length L Ch R = 1 ,328546  ,2223,2223,2223
BEGIN DESCRIPTION:
LFC75
END DESCRIPTION:
XS GIS Cut Line= 3
       2777895.4      7044311.59      2776990.35      7043703.72
       2776173.1      7043244.44
#Sta/Elev= 30
  3857.3  464.96    4042  458.34    4396   452.8  4654.1  456.65  4837.9  456.84
  4844.2  456.88  4921.1  456.31  4965.1  452.39  4973.2  450.16  4978.9  444.21
  4992.8  437.42  5010.9  438.22  5016.6  446.04  5022.5  450.96  5038.2  456.82
  5309.3  456.19  5324.5  454.33  5332.2  443.13  5340.4  439.16  5346.2  438.82
  5362.1  447.68  5367.9  447.75  5378.1  454.52  5389.6  455.92  5399.7  455.73
  5421.4  450.31  5448.8  455.78  5524.1  456.87  5679.9  464.62    5885  472.93
#Mann= 6 ,-1 , 0
  3857.3     .05       0  4837.9     .07       0  4844.2     .12       0
  4921.1     .07       0  5038.2     .12       0  5679.9     .16       0
Bank Sta=4921.1,5038.2
XS Rating Curve= 0 ,0
Exp/Cntr=0.3,0.1

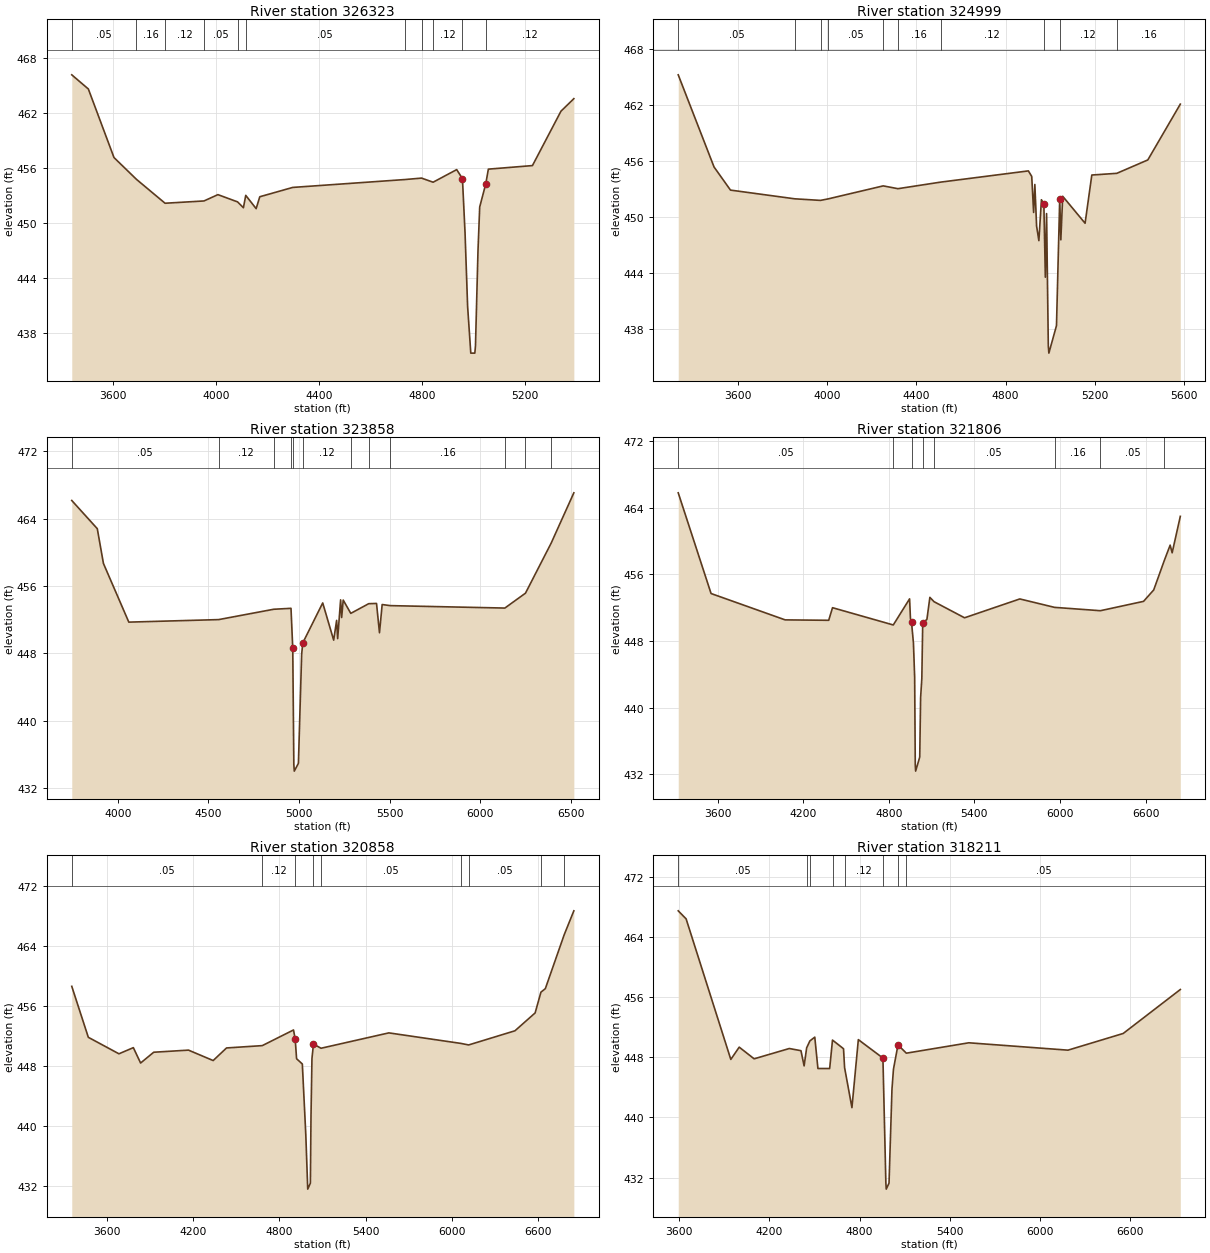
Type RM Length L Ch R = 1 ,326323  ,1324,1324,1324
BEGIN DESCRIPTION:
LFC76
END DESCRIPTION:
XS GIS Cut Line= 3
      2778428.96      7043832.04      2777328.05       7042852.7
      2776855.29      7042798.67
#Sta/Elev= 30
  3439.3   466.2  3503.7  464.65  3603.2  457.15  3690.6  454.76  3801.5  452.15
  3952.7   452.4  4006.7  453.09  4082.9   452.3  4105.7  451.66  4114.8  453.01
  4155.1  451.56  4169.3  452.86  4297.2  453.88  4731.5  454.74  4797.3   454.9
  4842.2  454.45  4933.8  455.83  4956.1  454.84  4966.2   448.9  4976.2  440.85
  4988.5  435.75  5004.2  435.75  5006.7  436.55  5016.5  446.99  5023.1  451.74
  5046.7  454.28  5056.7  455.88  5227.9  456.27  5338.6  462.22  5388.6  463.59
#Mann= 11 ,-1 , 0
  3439.3     .05       0  3690.6     .16       0  3801.5     .12       0
  3952.7     .05       0  4082.9     .16       0  4114.8     .05       0
  4731.5     .07       0  4797.3     .05       0  4842.2     .12       0
  4956.1     .07       0  5046.7     .12       0
Bank Sta=4956.1,5046.7
XS Rating Curve= 0 ,0
Exp/Cntr=0.3,0.1

Type RM Length L Ch R = 1 ,324999  ,1141,1141,1141
BEGIN DESCRIPTION:
LFC175
END DESCRIPTION:
XS GIS Cut Line= 4
       2778443.7      7043746.06      2777679.81      7042475.22
      2777485.37      7042391.89      2776929.94      7042336.35
#Sta/Elev= 30
  3331.5  465.19  3492.1  455.35  3565.9  452.88    3854  451.95  3969.8  451.78
  4003.8  451.94  4251.2  453.33  4317.2  453.03  4508.2  453.73  4902.4  454.93
  4917.4  454.34  4925.9  450.49  4931.4  453.48  4939.2  449.04  4949.5  447.48
  4960.9  451.85  4971.8  451.42  4978.5  443.58    4984  450.37  4991.8  436.27
  4994.3  435.47  5028.5  438.41    5043  451.96    5048  447.57  5056.3  452.22
  5156.8  449.34    5187  454.49    5299  454.67  5438.2   456.1    5584  462.06
#Mann= 10 ,-1 , 0
  3331.5     .05       0    3854     .12       0  3969.8      .1       0
  4003.8     .05       0  4251.2     .07       0  4317.2     .16       0
  4508.2     .12       0  4971.8     .07       0    5043     .12       0
    5299     .16       0
Bank Sta=4971.8,5043
XS Rating Curve= 0 ,0
Exp/Cntr=0.3,0.1

Type RM Length L Ch R = 1 ,323858  ,2052,2052,2052
BEGIN DESCRIPTION:
LFC77
END DESCRIPTION:
XS GIS Cut Line= 3
      2778547.85      7043787.68      2778200.64       7042565.5
      2777499.85      7041240.23
#Sta/Elev= 30
  3746.2  466.16    3887  462.81  3920.9  458.68  4060.9  451.71  4556.4  452.01
  4860.7  453.24  4955.6  453.35  4965.3  448.59  4971.2  434.81  4973.7  434.01
  4996.5  434.94  5014.4  447.89  5020.5  449.24  5130.6  453.99    5191  449.57
  5207.3  451.92    5213  449.75  5229.3  454.36    5235  452.26  5243.6  454.33
  5285.4  452.75  5384.3   453.9  5427.4  453.93  5443.7  450.45  5458.5   453.8
  5503.3  453.67  6135.3  453.38  6249.1  455.15  6390.7  461.09  6515.9  467.07
#Mann= 12 ,-1 , 0
  3746.2     .05       0  4556.4     .12       0  4860.7     .16       0
  4955.6     .12       0  4965.3     .07       0  5020.5     .12       0
  5285.4     .16       0  5384.3     .12       0  5503.3     .16       0
  6135.3     .05       0  6249.1     .16       0  6390.7     .05       0
Bank Sta=4965.3,5020.5
XS Rating Curve= 0 ,0
Exp/Cntr=0.3,0.1

Type RM Length L Ch R = 1 ,321806  ,948,948,948
BEGIN DESCRIPTION:
LFC174
END DESCRIPTION:
XS GIS Cut Line= 3
      2779603.42      7043926.59      2779172.87      7042384.94
      2777618.67      7041260.92
#Sta/Elev= 30
  3324.3  465.76  3554.4  453.69  4073.5  450.53  4378.9  450.48  4405.7  451.99
  4831.4  449.92  4945.6  453.05  4951.8  450.67  4959.3  450.26  4972.7  447.75
  4981.2  443.68  4985.5   433.2    4988   432.4  5016.8  434.09    5023  441.23
  5031.5  443.52  5037.7  450.14  5067.1  450.59  5087.9  453.23  5117.1  452.71
  5330.8  450.78  5718.3  453.04  5961.5  452.03    6283  451.63  6585.4  452.75
  6656.6  454.12  6731.1  457.66  6771.8  459.49  6785.8  458.57    6843  462.94
#Mann= 8 ,-1 , 0
  3324.3     .05       0  4831.4     .12       0  4959.3     .07       0
  5037.7     .12       0  5117.1     .05       0  5961.5     .16       0
    6283     .05       0  6731.1     .16       0
Bank Sta=4959.3,5037.7
XS Rating Curve= 0 ,0
Exp/Cntr=0.3,0.1

Type RM Length L Ch R = 1 ,320858  ,2647,2647,2647
BEGIN DESCRIPTION:
LFC78
END DESCRIPTION:
XS GIS Cut Line= 3
      2780360.65      7043001.32      2779421.81      7041812.58
      2777569.39      7041114.37
#Sta/Elev= 30
  3354.8  458.64    3470  451.84  3683.2  449.64  3783.4  450.46  3833.9  448.41
  3925.2  449.85  4167.3  450.13  4338.9  448.74  4431.9  450.42  4680.6  450.73
  4898.2  452.82  4909.7  451.61  4919.6  448.98  4959.5  448.28  4983.7  438.83
  4997.1  431.59  5015.5  432.39  5019.9   441.4  5026.5  449.02  5037.1  450.94
  5089.7  450.38  5561.7  452.43  6061.8  451.03  6116.9  450.82  6439.4  452.71
  6579.7  455.09  6620.1  457.86  6650.8  458.33  6782.1  465.52  6849.2  468.71
#Mann= 9 ,-1 , 0
  3354.8     .05       0  4680.6     .12       0  4909.7     .07       0
  5037.1     .12       0  5089.7     .05       0  6061.8     .16       0
  6116.9     .05       0  6620.1     .16       0  6782.1     .05       0
Bank Sta=4909.7,5037.1
XS Rating Curve= 0 ,0
Exp/Cntr=0.3,0.1

Type RM Length L Ch R = 1 ,318211  ,1570,1570,1570
BEGIN DESCRIPTION:
LFC79
END DESCRIPTION:
XS GIS Cut Line= 3
      2781046.14      7041587.69      2780047.88       7040693.6
      2778051.39      7040528.67
#Sta/Elev= 30
  3592.6  467.45  3645.1  466.38  3942.7   447.7  3998.7  449.33  4098.1  447.78
  4332.2  449.15  4409.9  448.86  4430.8  446.84  4447.8  449.24  4469.3  450.16
  4501.9  450.66  4522.8  446.49    4601  446.49  4619.9  450.27  4693.3  449.12
  4700.3  446.62  4749.3  441.29  4791.9  450.33  4955.7  447.88  4975.3  431.26
  4977.8  430.46  4996.3  431.26  5015.9  443.75  5025.9  446.41    5056  449.63
  5111.5  448.53  5527.6  449.91    6188  448.93  6555.8  451.15    6936  456.99
#Mann= 8 ,-1 , 0
  3592.6     .05       0  4447.8     .07       0  4469.3     .12       0
  4619.9     .07       0  4700.3     .12       0  4955.7     .07       0
    5056     .12       0  5111.5     .05       0
Bank Sta=4955.7,5056
XS Rating Curve= 0 ,0
Exp/Cntr=0.3,0.1

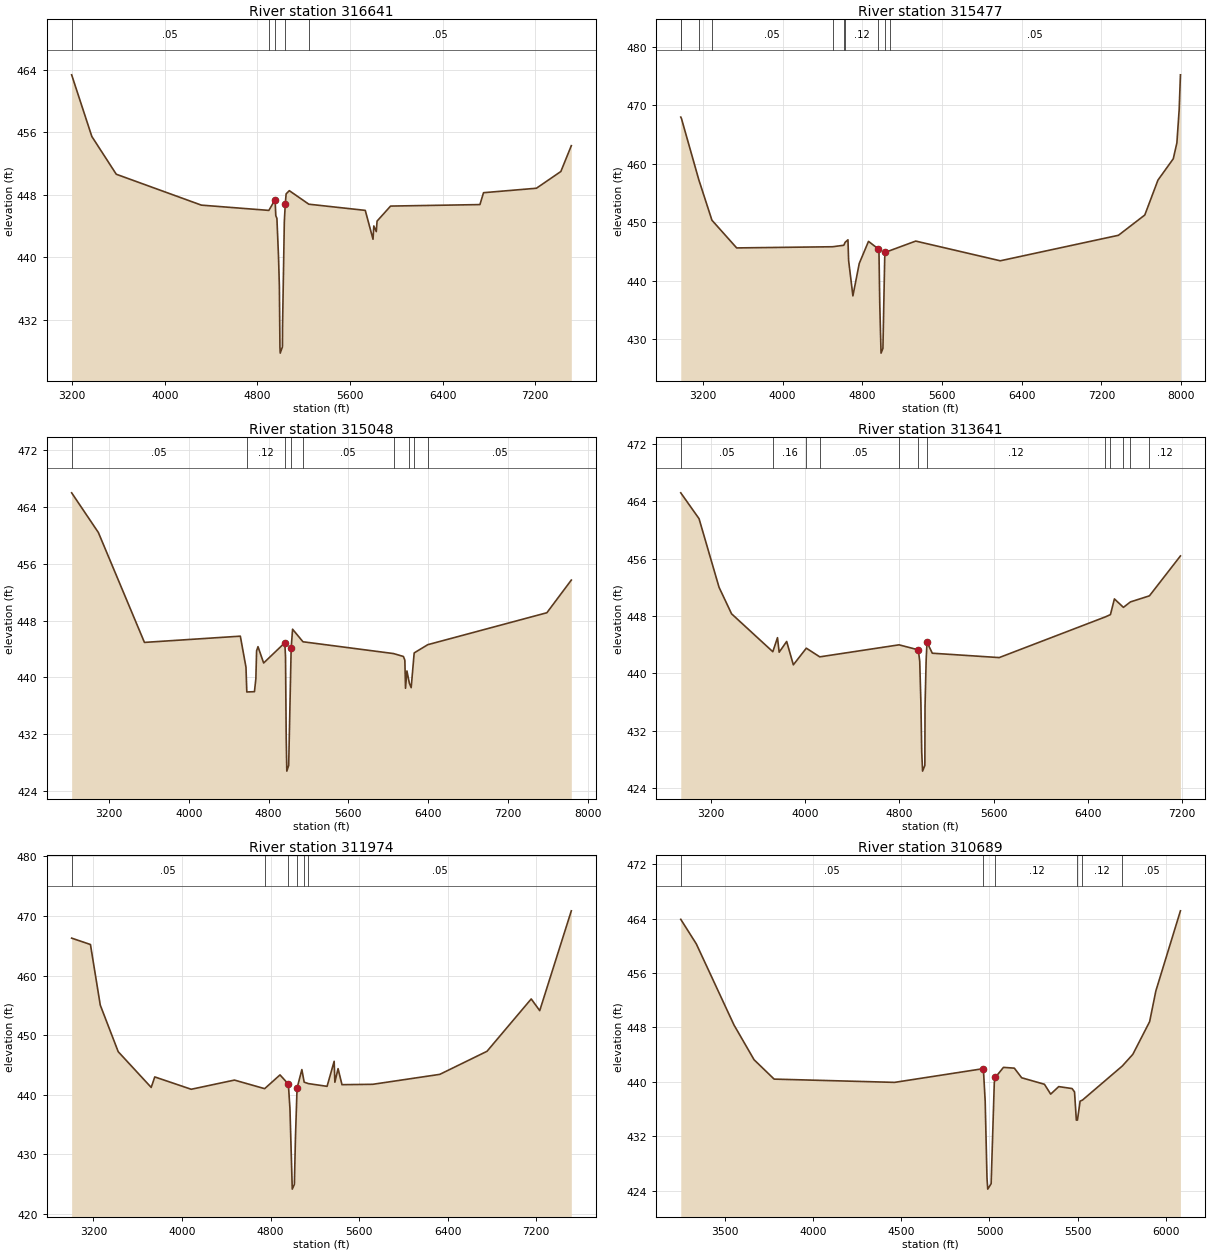
Type RM Length L Ch R = 1 ,316641  ,1164,1164,1164
BEGIN DESCRIPTION:
LFC176
END DESCRIPTION:
XS GIS Cut Line= 3
      2781686.73      7041440.46      2780860.37      7039982.17
      2778596.49      7038621.06
#Sta/Elev= 30
  3195.3  463.35  3369.7  455.47  3580.9  450.64  4316.5  446.69  4899.3446.0177
  4953.4  447.38  4959.4  445.34    4969     445  4982.7  440.18  4990.3  436.33
  4995.2  428.57  4997.8  427.77  5016.6  428.57  5017.7  431.16  5033.1  444.59
  5041.1  446.78  5048.6  448.13  5076.1  448.54  5244.8  446.81  5732.5  446.02
  5799.5  442.33  5806.3  444.03  5827.7  443.31  5834.5  444.65  5951.2  446.57
  6723.3  446.76  6754.3  448.28  7211.4  448.85  7422.6  450.99    7513  454.29
#Mann= 5 ,-1 , 0
  3195.3     .05       0  4899.3     .12       0  4953.4     .07       0
  5041.1     .12       0  5244.8     .05       0
Bank Sta=4953.4,5041.1
XS Rating Curve= 0 ,0
Exp/Cntr=0.3,0.1

Type RM Length L Ch R = 1 ,315477  ,429,429,429
BEGIN DESCRIPTION:
LFC80
END DESCRIPTION:
XS GIS Cut Line= 5
      2782981.89       7040381.1       2782096.5        7040112.
      2781219.76      7039391.52      2780316.98      7038488.74
      2778789.57      7037794.46
#Sta/Elev= 30
  2978.8  467.95  2985.7  467.71  3159.9  457.24  3291.6  450.32  3539.9  445.58
  4502.7445.7811  4615.4446.0373  4628.4  446.54  4656.8  446.97  4663.3  443.44
  4706.4  437.38  4770.2  442.93  4862.8   446.7  4961.8  445.41  4968.3  444.66
  4976.2  435.86  4988.9  427.59  5007.7  428.39  5025.7  443.92  5032.2  444.81
  5076.2  445.11  5336.9  446.75  6185.4  443.38  7371.4  447.74    7636  451.21
    7768  457.18  7921.6  460.82    7958  463.55  7981.1   469.3  7993.5  475.18
#Mann= 10 ,-1 , 0
  2978.8     .16       0  2985.7     .05       0  3159.9     .16       0
  3291.6     .05       0  4502.7     .07       0  4615.4     .08       0
  4628.4     .12       0  4961.8     .07       0  5032.2     .12       0
  5076.2     .05       0
Bank Sta=4961.8,5032.2
XS Rating Curve= 0 ,0
Exp/Cntr=0.3,0.1

Type RM Length L Ch R = 1 ,315048  ,1407,1407,1407
BEGIN DESCRIPTION:
LFC81
END DESCRIPTION:
XS GIS Cut Line= 6
      2783381.27      7040085.97      2782730.18      7039999.16
      2782009.69      7039556.45      2780959.34       7038549.5
      2780612.12        7038237.      2779189.25      7037542.92
#Sta/Elev= 30
  2826.7  466.01  3094.6  460.42  3556.3  444.94  4517.3  445.82  4573.9  441.45
  4582.2437.9597  4658.8     438    4673  439.84  4680.2  443.75  4694.3  444.34
  4750.9  442.04  4962.9  444.89  4970.1  442.95  4977.1  431.54  4983.2  426.81
  5001.9  427.61  5026.8  444.14  5040.9   446.8  5145.1  445.03  6052.5  443.37
  6151.9  442.96  6166.1  442.44  6172.8  438.48    6187  440.92  6211.4439.1905
  6229.6  438.57  6259.6  443.46  6395.8  444.62  7589.6  449.12  7834.5  453.72
#Mann= 9 ,-1 , 0
  2826.7     .05       0  4582.2     .12       0  4962.9     .07       0
  5026.8     .12       0  5145.1     .05       0  6052.5     .12       0
  6211.4     .16       0  6259.6     .12       0  6395.8     .05       0
Bank Sta=4962.9,5026.8
XS Rating Curve= 0 ,0
Exp/Cntr=0.3,0.1

Type RM Length L Ch R = 1 ,313641  ,1667,1667,1667
BEGIN DESCRIPTION:
LFC177
END DESCRIPTION:
XS GIS Cut Line= 3
      2783527.05      7039801.63      2782235.37      7038350.22
      2781222.04      7036288.87
#Sta/Elev= 30
  2945.4  465.18  3100.6  461.57  3270.4  451.99  3376.6  448.29  3726.4     443
  3766.2  444.96  3780.4  442.93    3844  444.43  3900.8  441.17  4010.8443.4922
    4125442.2824  4797.6  443.96    4961  443.26  4973.1  441.69  4983.3  435.73
    4990  429.02  4997.4  426.33  5016.6  427.13  5018.1  435.33  5027.9  441.97
    5035  444.31  5079.9  442.79  5647.4  442.18  6546.6  447.85  6591.4  448.18
  6625.1  450.37  6701.7  449.19  6760.8  449.95  6922.3   450.8  7185.3  456.37
#Mann= 12 ,-1 , 0
  2945.4     .05       0  3726.4     .16       0  4010.8     .07       0
    4125     .05       0  4797.6     .12       0    4961     .07       0
    5035     .12       0  6546.6     .16       0  6591.4     .07       0
  6701.7     .05       0  6760.8     .16       0  6922.3     .12       0
Bank Sta=4961,5035
XS Rating Curve= 0 ,0
Exp/Cntr=0.3,0.1

Type RM Length L Ch R = 1 ,311974  ,1285,1285,1285
BEGIN DESCRIPTION:
LFC82
END DESCRIPTION:
XS GIS Cut Line= 3
      2783849.97      7039565.16       2783389.9      7037664.09
      2781810.02      7035650.18
#Sta/Elev= 30
  3002.8  466.29  3172.7  465.22  3261.5  455.06  3423.7  447.24  3721.7  441.25
    3754  443.01  4083.3  440.94  4474.2  442.48  4746.9  441.04  4885.8  443.35
  4961.3  441.81  4975.7  437.67  4996.5  424.19  5015.7  424.99  5025.4  432.85
  5039.9  441.12  5083.3  444.24  5104.2  442.13  5142.2  441.89  5311.1  441.43
  5375.2  445.63  5381.6  442.12  5410.5   444.4  5445.8  441.71  5723.3  441.77
  6329.8  443.44  6756.5  447.31    7156  456.09  7232.9  454.13  7518.4  470.87
#Mann= 6 ,-1 , 0
  3002.8     .05       0  4746.9     .12       0  4961.3     .07       0
  5039.9     .12       0  5104.2     .16       0  5142.2     .05       0
Bank Sta=4961.3,5039.9
XS Rating Curve= 0 ,0
Exp/Cntr=0.3,0.1

Type RM Length L Ch R = 1 ,310689  ,1757,1757,1757
BEGIN DESCRIPTION:
LFC178
END DESCRIPTION:
XS GIS Cut Line= 3
      2784050.01      7039349.98      2784464.53      7037836.33
      2784145.08      7036614.07
#Sta/Elev= 30
  3249.8  463.89  3337.9  460.28  3551.6  448.35  3665.4  443.24  3779.2  440.39
  4462.1  439.91  4965.3  441.93  4975.6  437.15  4985.9  425.84  4990.2  424.21
  5009.4  425.01  5027.3  439.89  5033.6  440.65  5079.2  442.12    5141     442
  5182.3  440.59  5311.6  439.63  5346.9  438.18  5392.5  439.29  5468.2     439
  5482.1  438.51  5492.4  434.36  5498.7  434.37  5513.8  437.15  5526.8   437.3
  5753.1  442.32  5812.8  444.04  5907.9  448.84  5943.2  453.36  6082.5  465.14
#Mann= 6 ,-1 , 0
  3249.8     .05       0  4965.3     .03       0  5033.6     .12       0
  5498.7     .16       0  5526.8     .12       0  5753.1     .05       0
Bank Sta=4965.3,5033.6
XS Rating Curve= 0 ,0
Exp/Cntr=0.3,0.1