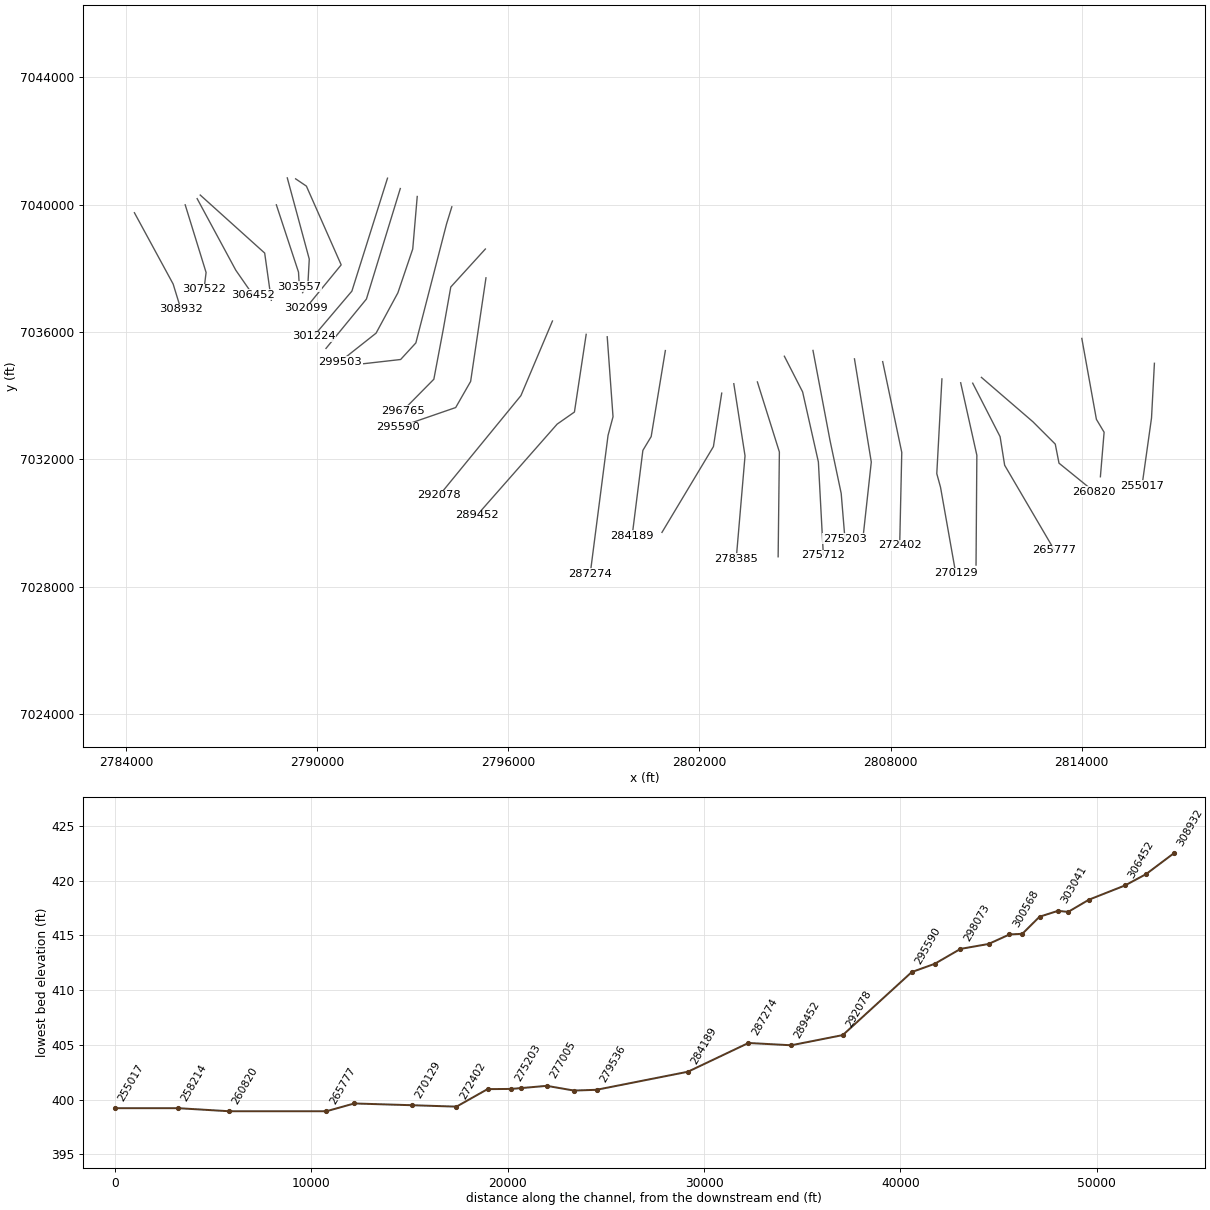
HEC-RAS study Lake Fork Creek.prj: Lake Fork Creek Base Level Engineering

--- Lake Fork Creek.g01 (geometry) --- (continued)

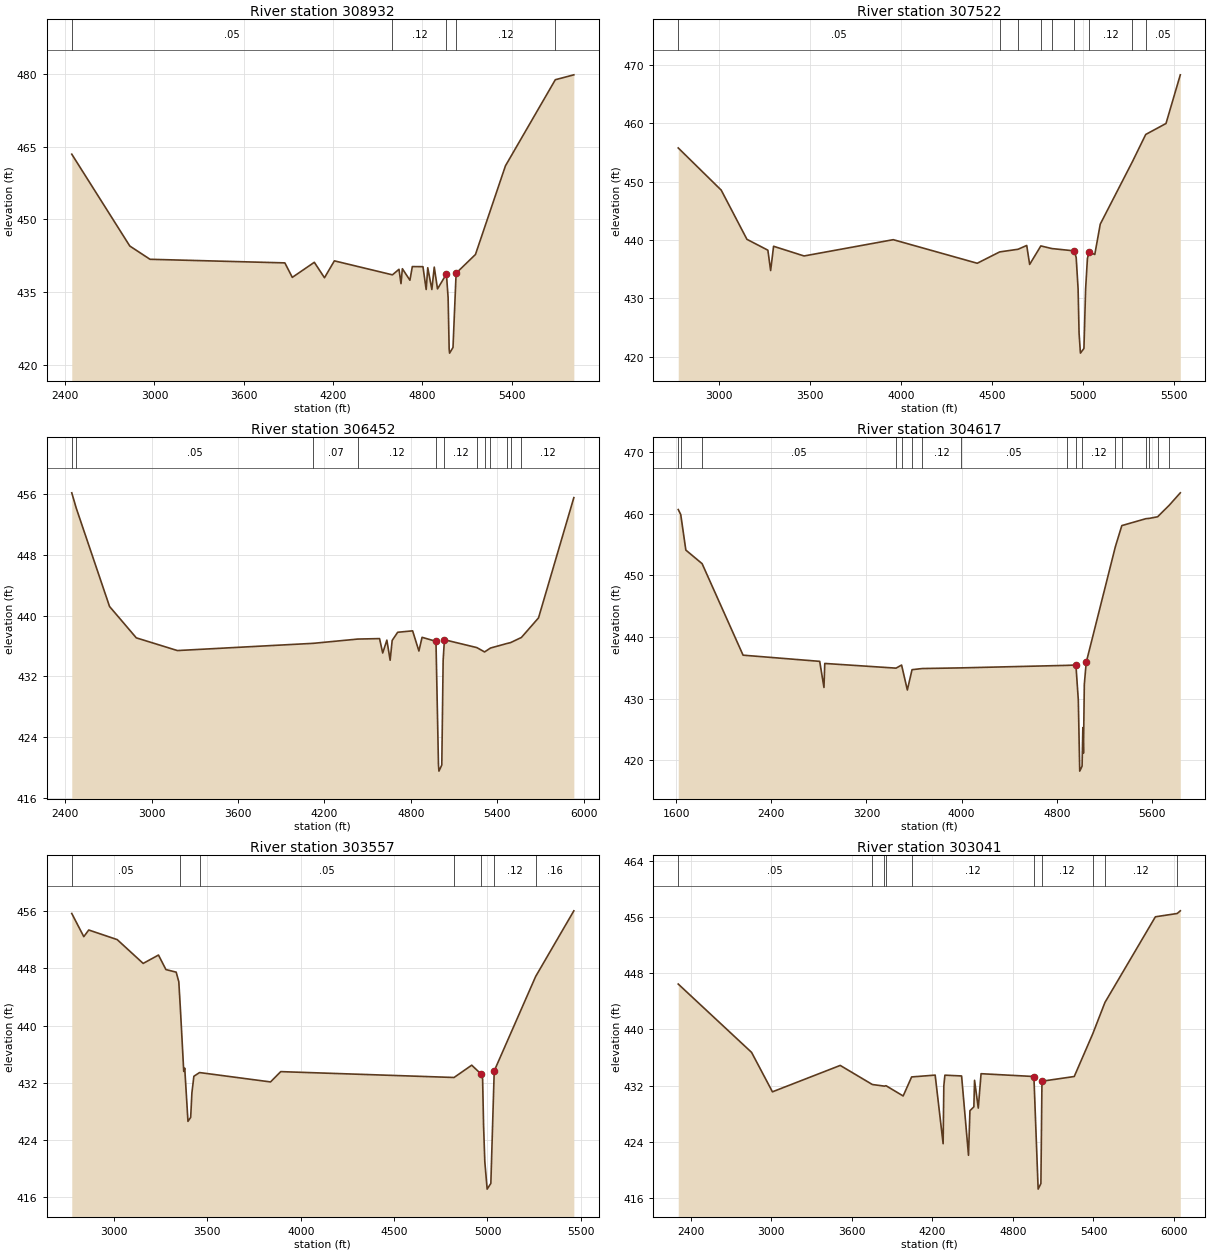
Type RM Length L Ch R = 1 ,308932  ,1410,1410,1410
BEGIN DESCRIPTION:
LFC83
END DESCRIPTION:
XS GIS Cut Line= 3
      2784266.63      7039747.42      2785481.91      7037507.84
      2785724.63        7036719.
#Sta/Elev= 30
  2444.3  463.44  2834.2  444.54  2970.1  441.81    3876  441.07  3926.1  438.09
    4074  441.19  4142.3  438.01  4208.7  441.49  4598.8  438.61  4642.9  439.75
  4656.4   436.8  4665.6  439.87  4716.3   437.5  4732.5  440.31  4803.8  440.29
  4825.6  435.59  4836.1  440.07  4863.7  435.59  4879.8   440.2  4901.7  435.72
  4961.5  438.78    4973   433.9    4980   423.3    4983   422.5  5005.8  423.67
  5026.7  438.95  5156.7   442.8  5358.1  461.04  5693.2  478.76  5817.7  479.77
#Mann= 5 ,-1 , 0
  2444.3     .05       0  4598.8     .12       0  4961.5     .07       0
  5026.7     .12       0  5693.2     .05       0
Bank Sta=4961.5,5026.7
XS Rating Curve= 0 ,0
Exp/Cntr=0.3,0.1

Type RM Length L Ch R = 1 ,307522  ,1070,1070,1070
BEGIN DESCRIPTION:
LFC179
END DESCRIPTION:
XS GIS Cut Line= 3
      2785860.37      7039996.04      2786516.14      7037869.97
      2786450.87      7037338.17
#Sta/Elev= 30
  2775.1  455.76  3011.5  448.53  3152.9   440.1    3268  438.24  3283.2  434.75
  3299.4  438.91  3466.9  437.25  3957.4  440.04  4419.2     436  4542.2  437.94
  4643.9   438.4  4691.3  439.05  4707.4   435.8  4768.9  438.97  4829.3  438.52
  4952.9  438.12  4963.3  436.97  4973.8   431.6  4979.1  424.05  4986.6   420.6
  5005.9   421.4  5015.1   431.6  5025.2  436.87  5035.2  437.93  5065.5   437.5
  5095.7  442.71  5272.6  453.42  5345.6  458.07  5457.1  459.95  5535.8  468.29
#Mann= 9 ,-1 , 0
  2775.1     .05       0  4542.2     .07       0  4643.9     .12       0
  4768.9     .07       0  4829.3     .12       0  4952.9     .07       0
  5035.2     .12       0  5272.6     .16       0  5345.6     .05       0
Bank Sta=4952.9,5035.2
XS Rating Curve= 0 ,0
Exp/Cntr=0.3,0.1

Type RM Length L Ch R = 1 ,306452  ,1835,1835,1835
BEGIN DESCRIPTION:
LFC180
END DESCRIPTION:
XS GIS Cut Line= 3
      2786235.38      7040190.47      2787447.95      7037942.56
      2787978.42      7037176.62
#Sta/Elev= 30
  2445.9  456.11    2477   454.1  2708.1  441.19  2893.8  437.07  3179.3   435.4
  4123.4  436.35  4432.4  436.91  4582.8  436.97  4604.7  435.08  4633.6  436.77
  4656.4  434.13  4670.4  436.73  4708.5   437.8  4812.3  437.99    4856  435.34
  4877.9  437.14  4974.5  436.61  4991.9  420.37  4995.1  419.57  5014.9  420.37
  5024.3  434.12  5033.1  436.82  5258.1  435.79    5312  435.22  5352.8  435.73
  5467.5  436.33  5492.1  436.44  5567.7  437.12  5686.4  439.69  5931.7  455.48
#Mann= 12 ,-1 , 0
  2445.9     .08       0    2477     .05       0  4123.4     .07       0
  4432.4     .12       0  4974.5     .07       0  5033.1     .12       0
  5258.1     .16       0    5312     .05       0  5352.8     .16       0
  5467.5     .12       0  5492.1     .16       0  5567.7     .12       0
Bank Sta=4974.5,5033.1
XS Rating Curve= 0 ,0
Exp/Cntr=0.3,0.1

Type RM Length L Ch R = 1 ,304617  ,1060,1060,1060
BEGIN DESCRIPTION:
LFC84
END DESCRIPTION:
XS GIS Cut Line= 3
      2786332.59      7040302.99      2788355.18      7038480.06
      2788563.51      7036995.66
#Sta/Elev= 30
  1617.4  460.66  1638.5  459.85  1681.4  454.09  1818.2  451.89  2162.7  437.06
    2807  436.06  2842.8  431.83  2849.6  435.72    3449  434.96  3495.5435.4596
  3543.9  431.42  3583.4  434.71  3669.3434.8951  3992.1     435  4890.2  435.41
  4961.3  435.47  4981.5  429.82  4993.5  418.27  5013.2  419.07  5019.7  425.32
  5024.7  421.18    5032  432.32 5048.03435.8792  5293.5  454.67  5347.5  458.06
  5550.1  459.18  5578.2  459.23  5648.6  459.49  5747.1  461.38  5839.2  463.37
#Mann= 17 ,-1 , 0
  1617.4     .05       0  1638.5     .08       0  1818.2     .05       0
    3449     .12       0  3495.5     .05       0  3583.4     .07       0
  3669.3     .12       0  3992.1     .05       0  4890.2     .12       0
  4961.3     .07       0  5013.2     .12       0  5293.5     .05       0
  5347.5     .12       0  5550.1     .16       0  5578.2     .12       0
  5648.6     .05       0  5747.1     .12       0
Bank Sta=4961.3,5048.03
XS Rating Curve= 0 ,0
Exp/Cntr=0.3,0.1

Type RM Length L Ch R = 1 ,303557  ,516,516,516
BEGIN DESCRIPTION:
LFC181
END DESCRIPTION:
XS GIS Cut Line= 3
      2788721.49      7039996.03      2789416.94      7037881.45
      2789443.69      7037419.83
#Sta/Elev= 30
    2774  455.67  2838.4  452.43  2864.9  453.36  3017.2  452.02  3156.3  448.69
  3238.3  449.86  3278.2  447.83    3333  447.47  3347.1  446.14    3356  442.19
  3373.6   433.6  3378.9  434.05  3396.2  426.62  3410.7  427.18  3417.2  430.58
  3427.8  432.92  3458.2  433.44  3838.3  432.13  3892.9  433.57  4820.9  432.75
  4915.5  434.47  4964.7  433.26  4973.9  432.54  4979.1     426  4985.7  420.98
  4998.2  417.15    5018  417.95 5036.06433.6646    5258  446.87  5462.4  456.04
#Mann= 7 ,-1 , 0
    2774     .05       0    3356     .16       0  3458.2     .05       0
  4820.9     .12       0  4964.7     .07       0 5036.06     .12       0
    5258     .16       0
Bank Sta=4964.7,5036.06
XS Rating Curve= 0 ,0
Exp/Cntr=0.3,0.1

Type RM Length L Ch R = 1 ,303041  ,942,942,942
BEGIN DESCRIPTION:
Mapping XS 687375a1
END DESCRIPTION:
XS GIS Cut Line= 4
      2789064.41      7040842.26      2789754.51       7038290.2
      2789715.44      7037574.05      2789546.19      7037235.54
#Sta/Elev= 30
  2307.3  446.46  2853.5  436.73  3008.9  431.11  3513.8  434.87  3753.1  432.15
  3843.1  431.92  3854.7  431.98  3982.6  430.52  4045.6  433.23  4220.9  433.49
  4280.2  423.72  4285.4  431.97  4293.4  433.48  4417.7  433.37  4469.2  422.07
  4479.9  428.42  4509.1  428.97  4514.2  432.75    4542  428.79  4562.8  433.69
  4956.2  433.29  4987.9  417.25  5008.4  418.05  5016.3  432.62  5256.7  433.29
  5393.9  439.34  5485.4  443.84  5861.1  456.04  6023.6  456.51  6046.7  456.89
#Mann= 10 ,-1 , 0
  2307.3     .05       0  3753.1     .12       0  3843.1     .05       0
  3854.7     .16       0  4045.6     .12       0  4956.2     .07       0
  5016.3     .12       0  5393.9     .16       0  5485.4     .12       0
  6023.6     .16       0
Bank Sta=4956.2,5016.3
XS Rating Curve= 0 ,0
Exp/Cntr=0.3,0.1

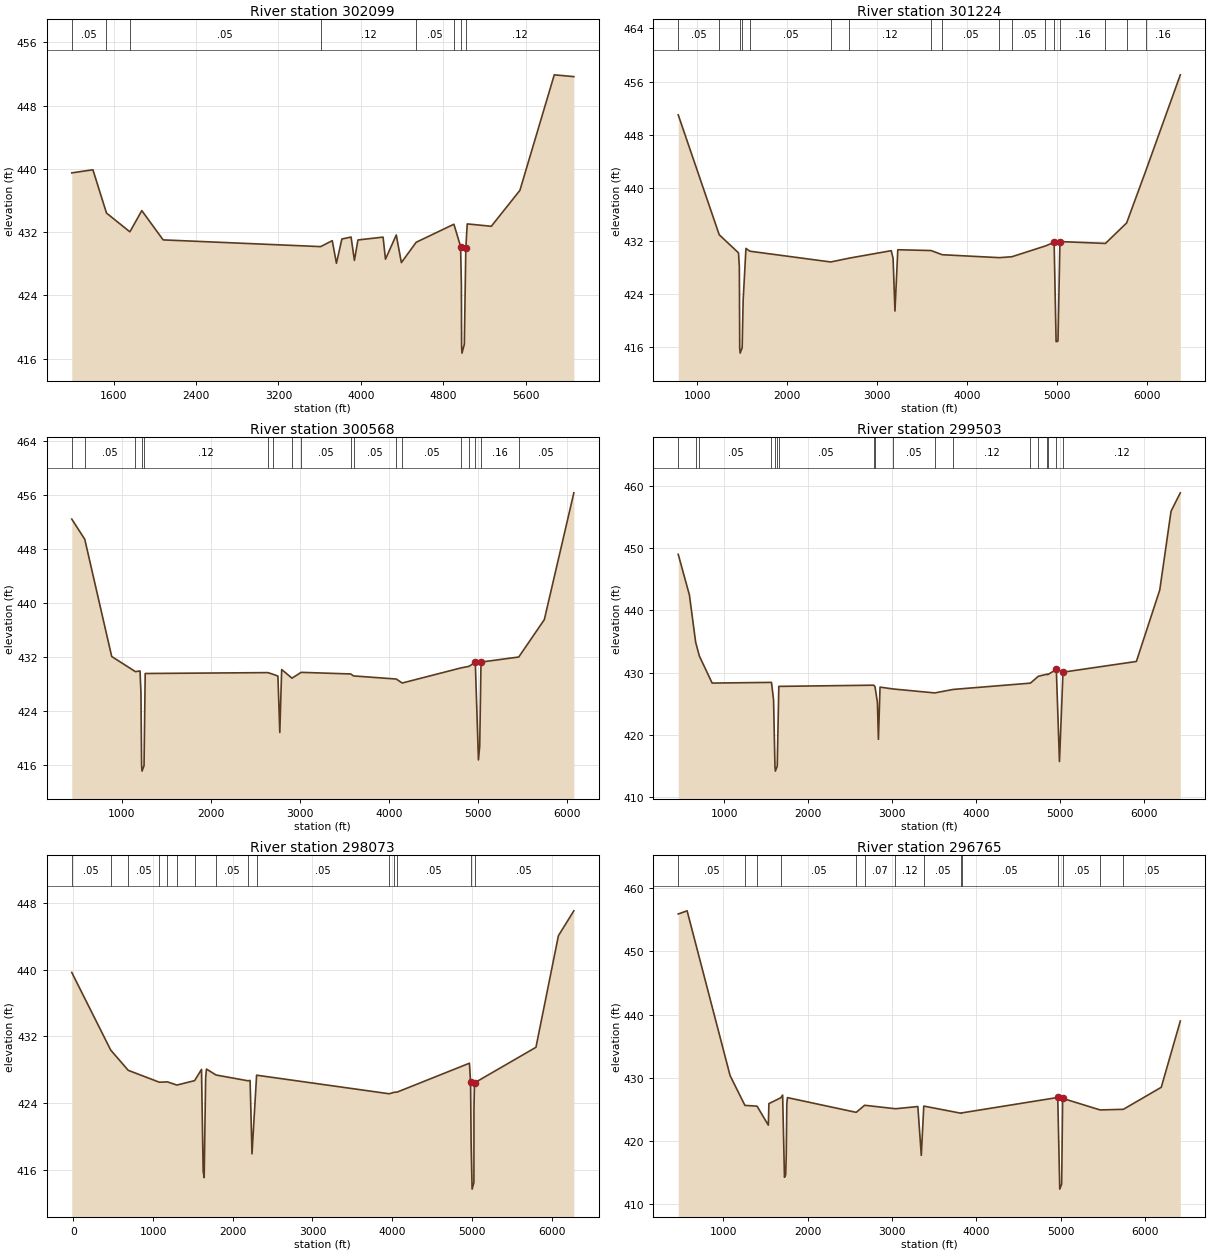
Type RM Length L Ch R = 1 ,302099  ,875,875,875
BEGIN DESCRIPTION:
LFC85
END DESCRIPTION:
XS GIS Cut Line= 4
      2789326.04       7040812.6       2789664.6      7040583.41
      2790756.04      7038109.49      2789639.23       7036743.3
#Sta/Elev= 30
  1191.8  439.49  1397.3  439.88  1529.1  434.41  1756.3  432.04  1872.2  434.72
  2079.5  431.02  3609.1  430.17  3722.3  430.92    3763  428.07  3815.6  431.13
  3905.1  431.38  3937.6  428.43  3971.9  431.01    4216  431.37  4239.3  428.58
  4344.2  431.64  4393.8  428.15  4537.6  430.72  4904.2     433  4969.1  430.18
  4976.7  425.33  4978.9  417.51  4982.6  416.71  5005.4  417.83  5019.8     430
  5033.7  433.04  5267.4  432.74  5545.2  437.28  5879.1  451.88  6069.2  451.65
#Mann= 8 ,-1 , 0
  1191.8     .05       0  1529.1     .12       0  1756.3     .05       0
  3609.1     .12       0  4537.6     .05       0  4904.2     .12       0
  4969.1     .07       0  5019.8     .12       0
Bank Sta=4969.1,5019.8
XS Rating Curve= 0 ,0
Exp/Cntr=0.3,0.1

Type RM Length L Ch R = 1 ,301224  ,656,656,656
BEGIN DESCRIPTION:
LFC182
END DESCRIPTION:
XS GIS Cut Line= 3
      2792210.04      7040833.06      2791092.41      7037284.84
        2789889.       7035864.6
#Sta/Elev= 30
   789.6  450.99  1245.1  432.96  1459.6  430.23    1469  428.14  1473.2  415.95
  1477.9  415.15  1500.4  415.95    1511  423.04  1542.4   430.9  1586.2  430.48
  2485.1  428.86  2691.8  429.44  3157.6  430.56    3178  429.42    3199  421.48
  3230.4   430.7  3599.5  430.58  3725.2  429.95  4359.4  429.51  4499.2  429.65
  4871.4  431.27  4968.4  431.81  4990.4  416.88    4997  416.88  5011.2  416.96
  5033.3  431.93  5538.9  431.65  5774.3  434.73  5988.2   442.6  6371.2  457.01
#Mann= 17 ,-1 , 0
   789.6     .05       0  1245.1     .12       0  1473.2     .07       0
  1500.4     .12       0  1586.2     .05       0  2485.1     .05       0
  2691.8     .12       0  3599.5     .07       0  3725.2     .05       0
  4359.4     .12       0  4499.2     .05       0  4871.4     .12       0
  4968.4     .07       0  5033.3     .16       0  5538.9     .16       0
  5774.3     .05       0  5988.2     .16       0
Bank Sta=4968.4,5033.3
XS Rating Curve= 0 ,0
Exp/Cntr=0.3,0.1

Type RM Length L Ch R = 1 ,300568  ,1065,1065,1065
BEGIN DESCRIPTION:
LFC86
END DESCRIPTION:
XS GIS Cut Line= 3
      2792611.51       7040507.5      2791548.14      7037035.27
      2790279.32       7035484.5
#Sta/Elev= 30
     439  452.39   584.8  449.41   887.1  432.06    1154  429.81  1205.1  429.92
  1215.5  426.71  1222.9  415.89  1227.6  415.09  1250.1  415.89  1263.2  429.54
  2640.2  429.67  2697.3  429.43  2752.9  429.16  2773.8  420.81  2794.8  430.13
  2910.7  428.85  3013.8  429.71  3570.3  429.47  3601.5  429.18  4080.7  428.72
  4148.2  428.13  4811.3  430.38  4898.4   430.6  4968.2   431.2  5003.3  416.75
  5017.7  418.81  5032.1  431.23  5455.8  431.98  5742.7  437.51  6074.1  456.28
#Mann= 18 ,-1 , 0
     439     .08       0   584.8     .05       0    1154     .12       0
  1222.9     .07       0  1250.1     .12       0  2640.2     .07       0
  2697.3     .12       0  2910.7     .16       0  3013.8     .05       0
  3570.3     .16       0  3601.5     .05       0  4080.7     .12       0
  4148.2     .05       0  4811.3     .07       0  4898.4     .16       0
  4968.2     .07       0  5032.1     .16       0  5455.8     .05       0
Bank Sta=4968.2,5032.1
XS Rating Curve= 0 ,0
Exp/Cntr=0.3,0.1

Type RM Length L Ch R = 1 ,299503  ,1430,1430,1430
BEGIN DESCRIPTION:
LFC183
END DESCRIPTION:
XS GIS Cut Line= 5
      2793143.19       7040257.9      2793002.13      7038608.62
      2792535.55      7037230.59       2791850.7       7035963.4
       2790723.5      7035071.31
#Sta/Elev= 30
   449.4  449.01   582.8  442.48   657.4  434.89   701.5  432.69   853.8  428.35
  1561.5  428.46  1586.4  425.64  1602.9  415.02  1607.7  414.22  1630.1  415.02
    1649  427.82  2779.3  428.01    2796   427.8  2824.8  425.27    2837  419.32
  2856.3   427.7  3015.8   427.4  3508.1  426.77  3729.2  427.33  4649.7  428.34
    4743  429.43  4849.4  429.78  4855.6   429.7  4958.9  430.53  4996.2  415.76
  5038.4   430.1  5913.5  431.82  6192.4  443.29    6327  455.93  6437.5  458.88
#Mann= 18 ,-1 , 0
   449.4     .05       0   657.4     .16       0   701.5     .05       0
  1561.5     .12       0  1602.9     .07       0  1630.1     .12       0
    1649     .05       0  2779.3     .12       0    2796     .16       0
  3015.8     .05       0  3508.1     .16       0  3729.2     .12       0
  4649.7     .05       0    4743     .12       0  4849.4     .16       0
  4855.6     .12       0  4958.9     .07       0  5038.4     .12       0
Bank Sta=4958.9,5038.4
XS Rating Curve= 0 ,0
Exp/Cntr=0.3,0.1

Type RM Length L Ch R = 1 ,298073  ,1308,1308,1308
BEGIN DESCRIPTION:
LFC87
END DESCRIPTION:
XS GIS Cut Line= 5
       2794228.9      7039933.73      2794061.95      7039390.83
      2793099.79      7035657.24      2792622.36       7035136.4
      2791462.86      7035004.37
#Sta/Elev= 30
     -19  439.65   469.5  430.38   689.2  427.96  1079.4  426.54    1181  426.58
  1299.3   426.2  1521.9  426.73  1608.3  428.07    1629  415.92  1641.6  415.15
    1660  427.05  1670.3  428.11  1790.9   427.4    2191  426.71  2217.6  426.75
  2241.6  417.99  2299.2  427.38    3962  425.16  4027.2  425.34  4062.1  425.36
  4968.6  428.81  4982.8  426.55  4990.2  418.99  5002.2  413.77  5024.9  414.57
  5025.3  423.39  5032.1  426.46  5802.9  430.71  6084.7  444.04  6278.1  447.01
#Mann= 15 ,-1 , 0
     -19     .05       0   469.5     .16       0   689.2     .05       0
  1079.4     .07       0    1181     .16       0  1299.3     .07       0
  1521.9     .16       0  1790.9     .05       0    2191     .12       0
  2299.2     .05       0    3962     .16       0  4027.2     .12       0
  4062.1     .05       0  4982.8     .03       0  5032.1     .05       0
Bank Sta=4982.8,5032.1
XS Rating Curve= 0 ,0
Exp/Cntr=0.3,0.1

Type RM Length L Ch R = 1 ,296765  ,1175,1175,1175
BEGIN DESCRIPTION:
LFC184
END DESCRIPTION:
XS GIS Cut Line= 5
      2795281.22      7038607.34      2794196.14      7037413.75
      2793957.43      7036068.26      2793664.46      7034516.61
      2792686.78      7033523.86
#Sta/Elev= 30
   467.3  455.88   572.5  456.38    1082  430.35  1257.9  425.64  1401.5  425.52
  1535.4  422.52  1542.2  425.92  1682.8  426.84    1705  427.27  1726.6  414.28
  1740.8  414.65  1747.6  417.63  1754.4  425.84  1761.8  426.87    2577  424.54
  2676.7  425.66  3042.6  425.11    3308  425.46  3348.6  417.74  3378.2  425.53
  3823.5  424.39  3826.4  424.45  4966.5  426.89  4990.2  412.41  5012.9  413.21
  5024.2  426.75  5468.8  424.92  5744.5  425.02  6193.4   428.5  6419.3  438.97
#Mann= 14 ,-1 , 0
   467.3     .05       0  1257.9     .16       0  1401.5     .12       0
  1682.8     .05       0    2577     .12       0  2676.7     .07       0
  3042.6     .12       0  3378.2     .05       0  3823.5     .07       0
  3826.4     .05       0  4966.5     .03       0  5024.2     .05       0
  5468.8     .07       0  5744.5     .05       0
Bank Sta=4966.5,5024.2
XS Rating Curve= 0 ,0
Exp/Cntr=0.3,0.1

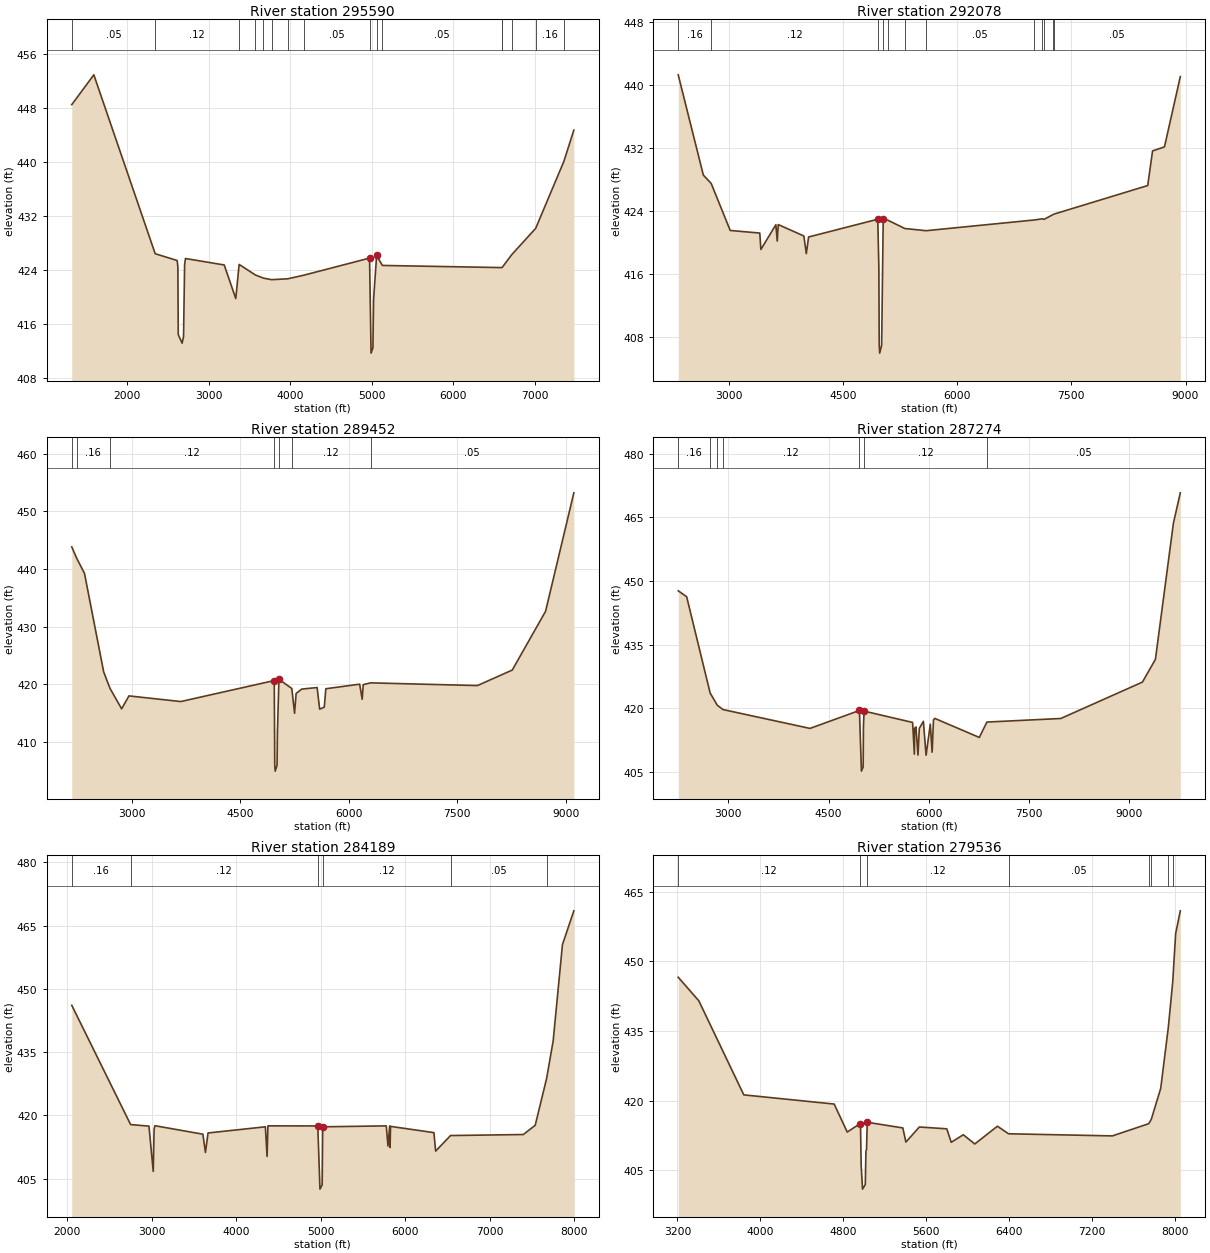
Type RM Length L Ch R = 1 ,295590  ,3512,3512,3512
BEGIN DESCRIPTION:
Mapping XS 4ba24c33
END DESCRIPTION:
XS GIS Cut Line= 4
      2795300.74      7037702.37      2794818.97      7034447.17
      2794350.22      7033626.85      2792540.35      7033001.86
#Sta/Elev= 30
  1325.1  448.49  1595.4  452.91  2346.9  426.39  2616.4  425.38  2624.7  424.42
  2629.7  414.39    2677  413.13  2694.2   414.1  2707.4  424.72  2717.5  425.68
  3192.6  424.72  3334.1  419.74  3375.2   424.8    3574  423.24  3673.2  422.77
  3772.5  422.54    3971  422.67  4169.5  423.21    4973  425.74  4991.4  411.65
  5014.2  412.45    5022  419.58  5059.4  426.13  5130.1  424.65  6592.1  424.33
  6600.3   424.4  6714.7  426.25  7007.8  430.15    7353  440.07  7475.3  444.71
#Mann= 16 ,-1 , 0
  1325.1     .05       0  2346.9     .12       0  3375.2     .07       0
    3574     .12       0  3673.2     .07       0  3772.5     .05       0
    3971     .16       0  4169.5     .05       0    4973     .07       0
  5059.4     .16       0  5130.1     .05       0  6592.1     .07       0
  6600.3     .05       0  6714.7     .07       0  7007.8     .16       0
    7353     .05       0
Bank Sta=4973,5059.4
XS Rating Curve= 0 ,0
Exp/Cntr=0.3,0.1

Type RM Length L Ch R = 1 ,292078  ,2626,2626,2626
BEGIN DESCRIPTION:
LFC88
END DESCRIPTION:
XS GIS Cut Line= 3
      2797387.31      7036345.55      2796397.71      7034001.76
      2793832.58      7030863.71
#Sta/Elev= 30
  2334.1  441.33  2663.6  428.57  2767.5  427.49  3017.2  421.51  3405.4  421.18
  3420.2  419.09  3616.8  422.24  3635.1  420.16  3648.1  422.26  3984.6  420.81
  4017.2  418.56    4047  420.68  4955.8  422.94  4970.2  416.84  4975.1  406.89
  4981.2  405.89  5006.8  406.89  5027.6  422.93  5087.8  422.82  5310.7  421.76
  5590.8  421.48  7013.2422.8457    7112  422.99    7142422.9295  7264.1  423.56
  7270.9  423.59  8502.9  427.23  8566.7  431.64    8723  432.15  8931.3   441.1
#Mann= 12 ,-1 , 0
  2334.1     .16       0  2767.5     .12       0  4955.8     .07       0
  5027.6     .12       0  5087.8     .05       0  5310.7     .12       0
  5590.8     .05       0  7013.2     .07       0    7112     .12       0
    7142     .16       0  7264.1     .12       0  7270.9     .05       0
Bank Sta=4955.8,5027.6
XS Rating Curve= 0 ,0
Exp/Cntr=0.3,0.1

Type RM Length L Ch R = 1 ,289452  ,2178,2178,2178
BEGIN DESCRIPTION:
LFC185
END DESCRIPTION:
XS GIS Cut Line= 4
      2798445.87      7035927.02      2798076.95      7033485.64
      2797534.41      7033105.86      2795017.03      7030241.26
#Sta/Elev= 30
  2168.2  443.83  2235.7  441.88  2344.3  439.23  2609.6  422.16  2696.7  419.31
    2858  415.76  2959.1     418    3676  417.02  4969.2  420.66  4975.9  405.96
  4981.9  404.96  5007.6  405.96  5012.6  411.45  5033.6  420.88  5212.3  419.28
    5250  414.99  5271.6  418.43  5349.5  419.18    5562  419.45  5597.1   415.7
  5660.7  416.04  5682.5  419.24  6150.3  420.03  6185.4  417.42  6199.7  419.95
  6300.5 420.259  7779.5  419.79  8261.5  422.48    8722  432.66  9113.1   453.2
#Mann= 7 ,-1 , 0
  2168.2     .12       0  2235.7     .16       0  2696.7     .12       0
  4969.2     .07       0  5033.6     .12       0  5212.3     .12       0
  6300.5     .05       0
Bank Sta=4969.2,5033.6
XS Rating Curve= 0 ,0
Exp/Cntr=0.3,0.1

Type RM Length L Ch R = 1 ,287274  ,3085,3085,3085
BEGIN DESCRIPTION:
LFC89
END DESCRIPTION:
XS GIS Cut Line= 4
      2799106.05      7035850.69      2799288.34       7033337.7
      2799132.09      7032751.76      2798572.19      7028402.77
#Sta/Elev= 30
  2250.1  447.69  2376.1  446.29  2727.4  423.59  2834.9   420.7  2919.1  419.69
    4221  415.24  4960.6  419.47  4990.9  405.17  5016.6  406.17  5020.9  415.78
  5030.5  419.32    5756  416.65  5782.6  409.18  5787.6  415.27  5806.4  415.59
  5836.6  408.95  5856.8  415.25  5917.3  416.92  5957.6  408.93  6021.1  416.24
  6048.4  409.63  6068.5  417.26  6088.7   417.6  6754.2  413.11  6867.7  416.74
    7973  417.58  9194.1  426.16  9388.6  431.52  9657.9  463.65    9761  470.79
#Mann= 7 ,-1 , 0
  2250.1     .16       0  2727.4     .12       0  2834.9     .16       0
  2919.1     .12       0  4960.6     .07       0  5030.5     .12       0
  6867.7     .05       0
Bank Sta=4960.6,5030.5
XS Rating Curve= 0 ,0
Exp/Cntr=0.3,0.1

Type RM Length L Ch R = 1 ,284189  ,4653,4653,4653
BEGIN DESCRIPTION:
LFC186
END DESCRIPTION:
XS GIS Cut Line= 4
      2800930.68      7035417.07       2800485.8      7032715.24
      2800225.38      7032281.21      2799889.01      7029601.11
#Sta/Elev= 30
  2052.2  446.11    2749  417.84  2966.4  417.47  3017.1  406.74  3027.2  416.71
  3036.7  417.57  3604.9  415.56  3635.3  411.23  3665.7  415.85  4344.7  417.31
    4365  410.28  4375.1  417.54  4965.6  417.51  4991.3  402.54  5017.4  403.54
  5023.9  417.31  5776.5  417.53  5796.7  412.77  5816.7  417.52  5821.7   412.4
  5826.9  417.41  6340.9  415.93  6361.1  411.55  6537.6415.2397  7399.2  415.48
  7540.3  417.67  7675.9  428.83  7752.9  437.68  7862.8  460.49  7997.7   468.5
#Mann= 6 ,-1 , 0
  2052.2     .16       0    2749     .12       0  4965.6     .07       0
  5023.9     .12       0  6537.6     .05       0  7675.9     .16       0
Bank Sta=4965.6,5023.9
XS Rating Curve= 0 ,0
Exp/Cntr=0.3,0.1

Type RM Length L Ch R = 1 ,279536  ,1151,1151,1151
BEGIN DESCRIPTION:
LFC90
END DESCRIPTION:
XS GIS Cut Line= 3
      2802699.79      7034079.86      2802439.38       7032400.2
      2800824.81      7029704.91
#Sta/Elev= 30
  3208.4  446.59  3406.7  441.52  3840.7  421.22  4712.2  419.24  4838.1   413.2
  4960.1  414.99    4966  414.81  4972.5  405.93  4985.8  400.89  5012.3  401.89
  5018.5   409.1  5024.3  409.43  5030.8  415.31  5374.3  414.09  5403.8  411.04
  5533.7  414.29  5798.2   413.9  5840.9  410.99  5957.6  412.62  6068.2  410.63
  6286.2  414.46  6393.6412.8289  7394.5  412.37  7745.4415.0025  7770.1  415.94
  7861.2  422.64  7934.3  435.76  7977.1  445.63    8005  455.99    8050  460.92
#Mann= 8 ,-1 , 0
  3208.4     .12       0  4960.1     .07       0  5030.8     .12       0
  6393.6     .05       0  7745.4     .12       0  7770.1     .16       0
  7934.3     .12       0  7977.1     .16       0
Bank Sta=4960.1,5030.8
XS Rating Curve= 0 ,0
Exp/Cntr=0.3,0.1

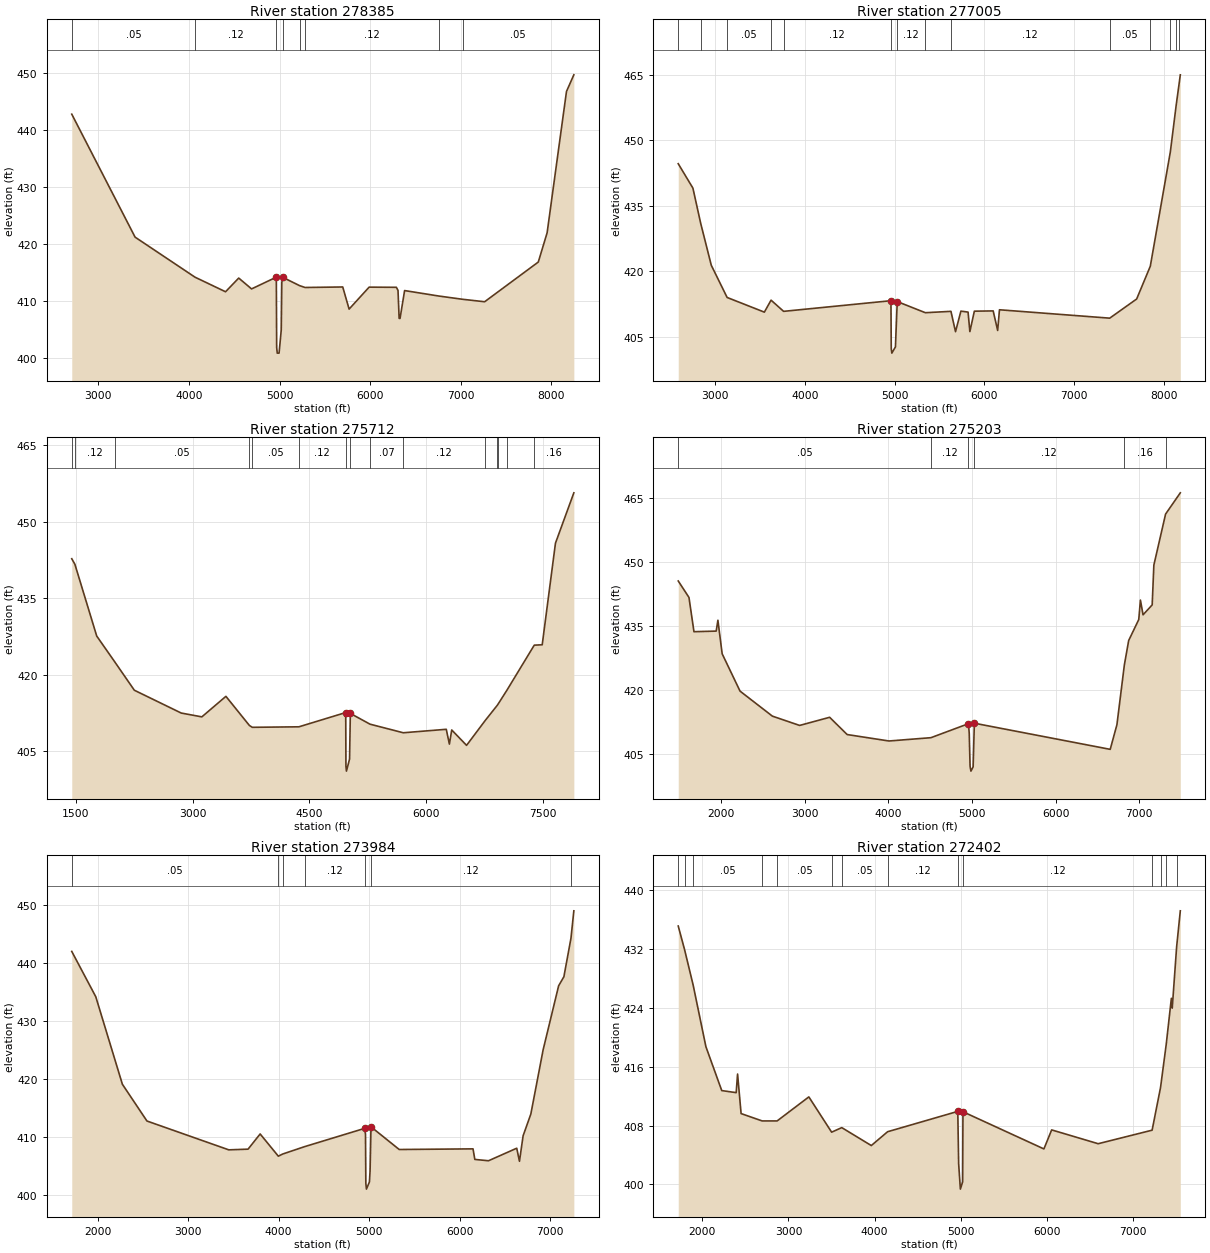
Type RM Length L Ch R = 1 ,278385  ,1380,1380,1380
BEGIN DESCRIPTION:
LFC187
END DESCRIPTION:
XS GIS Cut Line= 3
      2803079.11      7034375.43      2803431.45      7032109.05
      2803155.07      7028874.14
#Sta/Elev= 30
  2706.4  442.72  3405.1  421.16  4066.1  414.14  4403.3  411.58  4548.7  413.98
  4690.4  412.08  4963.6  414.14  4967.4  401.82  4973.9  400.82  4993.9  400.82
  5018.1  404.89  5024.1  413.17  5034.2  414.11  5220.8412.6512  5280.7  412.33
  5696.6  412.42  5766.8  408.54  5987.6  412.39  6288.7  412.36  6306.5  411.81
  6318.8  406.92  6328.9   406.9  6379.1  411.79  6757.7  410.83  7019.4410.2594
  7262.3  409.83  7854.4  416.79  7951.8  421.92  8165.5   446.7  8246.7  449.62
#Mann= 8 ,-1 , 0
  2706.4     .05       0  4066.1     .12       0  4963.6     .07       0
  5034.2     .12       0  5220.8     .07       0  5280.7     .12       0
  6757.7     .07       0  7019.4     .05       0
Bank Sta=4963.6,5034.2
XS Rating Curve= 0 ,0
Exp/Cntr=0.3,0.1

Type RM Length L Ch R = 1 ,277005  ,1293,1293,1293
BEGIN DESCRIPTION:
LFC93
END DESCRIPTION:
XS GIS Cut Line= 3
      2803819.58      7034431.47      2804509.69      7032230.93
      2804470.65      7028938.37
#Sta/Elev= 30
  2586.3  444.64  2749.9  439.05    2837  430.96    2955  421.37  3131.5     414
  3546.8  410.64  3621.4413.3848  3761.4  410.82  4958.4  413.26  4961.9  402.25
  4968.4  401.25  5008.5  402.68  5028.5  413.06    5342  410.51  5627.6  410.82
  5678.5  406.16  5738.5  410.87  5818.5  410.65  5838.5  406.18  5888.5  410.86
  6098.5  410.92  6148.5  406.44  6168.5  411.18  7398.2  409.26  7698.6  413.65
  7850.8  421.16  8074.3  447.36  8139.9  458.14  8171.9  462.95  8185.3     465
#Mann= 14 ,-1 , 0
  2586.3     .05       0    2837     .16       0  3131.5     .05       0
  3621.4     .16       0  3761.4     .12       0  4958.4     .07       0
  5028.5     .12       0    5342     .07       0  5627.6     .12       0
  7398.2     .05       0  7850.8     .16       0  8074.3     .12       0
  8139.9     .16       0  8171.9     .12       0
Bank Sta=4958.4,5028.5
XS Rating Curve= 0 ,0
Exp/Cntr=0.3,0.1

Type RM Length L Ch R = 1 ,275712  ,509,509,509
BEGIN DESCRIPTION:
LFC91
END DESCRIPTION:
XS GIS Cut Line= 4
      2804665.95      7035238.72      2805238.86      7034118.95
      2805733.65      7031918.43      2805889.86      7028989.38
#Sta/Elev= 30
    1448  442.74  1487.8  441.67  1768.3  427.57  1996.7  422.57  2251.3  416.93
  2853.4  412.45    3118   411.7  3427.3  415.73  3729.1410.0063  3766.4  409.65
  4364.9  409.75  4965.5  412.55  4968.2  402.05  4974.7  401.05  5014.8  403.41
  5024.8  412.38    5277  410.27  5704.5  408.58  6256.6  409.26  6296.6  406.35
  6326.7  409.13  6516.9  406.11  6751.5  410.89  6913.4  414.01  6921.6   414.2
  7034.7  416.92  7386.4  425.78  7488.3  425.85  7658.5   445.8  7894.5  455.68
#Mann= 15 ,-1 , 0
    1448     .05       0  1487.8     .12       0  1996.7     .05       0
  3729.1     .08       0  3766.4     .05       0  4364.9     .12       0
  4965.5     .07       0  5024.8     .12       0    5277     .07       0
  5704.5     .12       0  6751.5     .07       0  6913.4     .12       0
  6921.6     .16       0  7034.7     .12       0  7386.4     .16       0
Bank Sta=4965.5,5024.8
XS Rating Curve= 0 ,0
Exp/Cntr=0.3,0.1

Type RM Length L Ch R = 1 ,275203  ,1219,1219,1219
BEGIN DESCRIPTION:
LFC92
END DESCRIPTION:
XS GIS Cut Line= 4
      2805564.38      7035421.04      2806098.23      7032595.51
      2806449.79      7030928.85      2806566.96      7029509.84
#Sta/Elev= 30
  1487.5  445.58  1615.8  441.72  1675.6  433.68  1941.4  433.82  1961.8  436.37
  2012.7   428.5  2226.4  419.74  2613.1  413.87  2938.8  411.69  3297.7   413.6
  3507.2  409.55  4007.3  408.04  4509.3408.8167  4957.2   412.1  4966.5  409.87
  4976.7  402.12  4986.8  400.97  5013.3  401.97  5027.8  412.21  6652.2  406.08
  6732.5  411.87  6821.2  425.87  6872.9  431.61  6993.4  436.53  7013.4   441.1
  7044.8  437.64  7153.9  439.97    7174  449.31    7314  461.27  7490.2  466.26
#Mann= 6 ,-1 , 0
  1487.5     .05       0  4509.3     .12       0  4957.2     .07       0
  5027.8     .12       0  6821.2     .16       0    7314     .05       0
Bank Sta=4957.2,5027.8
XS Rating Curve= 0 ,0
Exp/Cntr=0.3,0.1

Type RM Length L Ch R = 1 ,273984  ,1582,1582,1582
BEGIN DESCRIPTION:
LFC188
END DESCRIPTION:
XS GIS Cut Line= 3
      2806866.02       7035156.6       2807394.2      7031914.44
      2807148.33      7029668.06
#Sta/Elev= 30
  1715.1  441.92  1980.1  434.12    2274  419.03  2545.4  412.69  3449.3  407.72
    3662  407.84  3795.5  410.46  3996.3  406.63  4046.1  407.01    4288  408.28
  4948.8  411.42  4958.9  410.42  4962.7  401.95  4969.2  400.95  5002.2  402.19
  5009.5  404.11  5019.6  411.69  5331.4  407.78  6146.4  407.89  6166.4  406.07
  6317.3  405.84  6629.1     408  6659.3  405.75  6699.5  410.14    6785   413.9
  6920.8  424.98  7091.9     436  7149.9  437.56    7228  444.19  7259.8  448.92
#Mann= 7 ,-1 , 0
  1715.1     .05       0  3996.3     .16       0  4046.1     .05       0
    4288     .12       0  4948.8     .07       0  5019.6     .12       0
    7228     .05       0
Bank Sta=4948.8,5019.6
XS Rating Curve= 0 ,0
Exp/Cntr=0.3,0.1

Type RM Length L Ch R = 1 ,272402  ,2273,2273,2273
BEGIN DESCRIPTION:
LFC95
END DESCRIPTION:
XS GIS Cut Line= 3
      2807751.87      7035069.51      2808350.84      7032217.91
      2808285.73      7029301.26
#Sta/Elev= 30
  1720.2  435.15  1794.1  431.93  1893.6  427.11  2041.6  418.73  2225.5  412.76
  2393.1  412.48  2409.4  415.01  2450.3  409.63  2694.7  408.63  2868.9  408.63
  3237.1   411.9  3501.8   407.1  3619.5  407.72  3962.6  405.28  4151.7  407.16
    4967  409.93    4977  402.82    4997  399.35  5023.5  400.35    5027  409.88
  5967.3  404.82  6057.3  407.41  6597.4  405.53  7223.9  407.37  7321.8  413.18
  7387.7  419.04  7447.6  425.32  7457.6  423.98  7508.7  432.32  7551.4  437.22
#Mann= 14 ,-1 , 0
  1720.2     .05       0  1794.1     .08       0  1893.6     .05       0
  2694.7     .16       0  2868.9     .05       0  3501.8     .07       0
  3619.5     .05       0  4151.7     .12       0    4967     .07       0
    5027     .12       0  7223.9     .16       0  7321.8     .12       0
  7387.7     .16       0  7508.7     .12       0
Bank Sta=4967,5027
XS Rating Curve= 0 ,0
Exp/Cntr=0.3,0.1

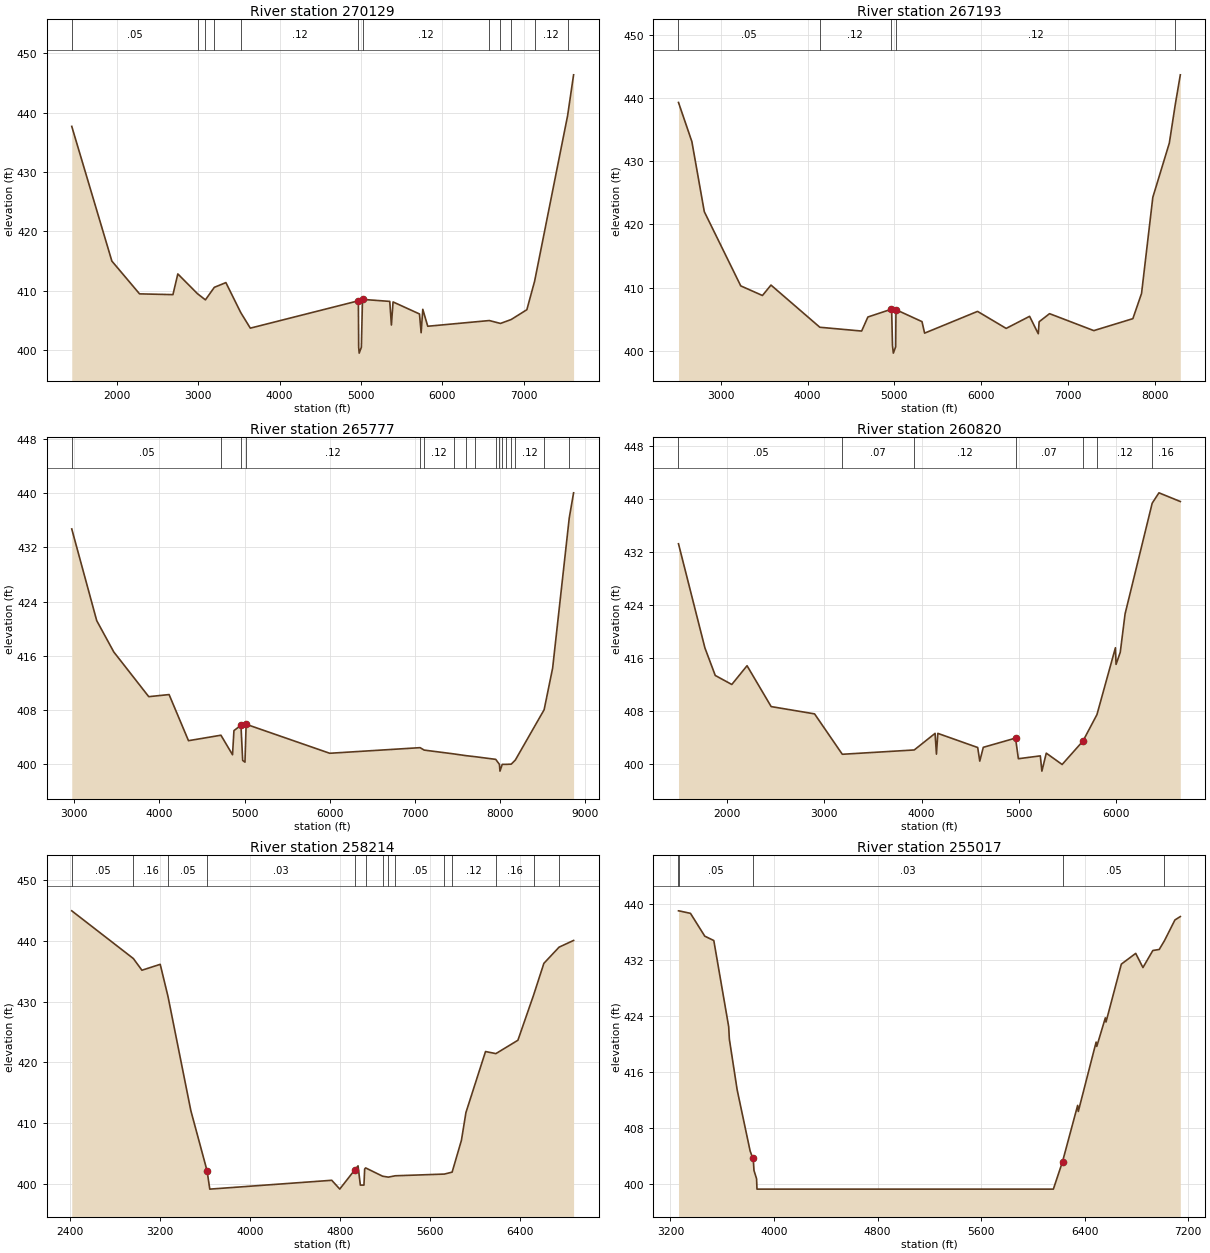
Type RM Length L Ch R = 1 ,270129  ,2936,2936,2936
BEGIN DESCRIPTION:
LFC189
END DESCRIPTION:
XS GIS Cut Line= 4
      2809611.23       7034527.3        2809450.        7031550.
      2809567.83      7031120.19      2810045.12      7028419.17
#Sta/Elev= 30
  1444.8   437.7  1937.8     415  2278.3  409.47  2688.9  409.34    2749  412.83
  2991.2  409.49  3088.2  408.46  3197.7  410.57  3339.9  411.37  3522.4  406.32
  3640.3  403.69  4968.8   408.3  4972.6  400.48  4979.1  399.48  5005.7  400.48
  5019.6  408.54  5354.7   408.2    5375  404.22  5395.3  408.11  5720.3  406.08
  5740.6  402.92  5760.9  406.87  5821.8  404.01  6578.9404.9716  6715.9404.4835
  6847.2  405.14  7040.4   406.8  7135.9  411.61  7541.4   439.5    7615  446.39
#Mann= 12 ,-1 , 0
  1444.8     .05       0  2991.2     .07       0  3088.2     .12       0
  3197.7     .05       0  3522.4     .12       0  4968.8     .07       0
  5019.6     .12       0  6578.9     .16       0  6715.9     .07       0
  6847.2     .16       0  7135.9     .12       0  7541.4     .16       0
Bank Sta=4968.8,5019.6
XS Rating Curve= 0 ,0
Exp/Cntr=0.3,0.1

Type RM Length L Ch R = 1 ,267193  ,1416,1416,1416
BEGIN DESCRIPTION:
LFC94
END DESCRIPTION:
XS GIS Cut Line= 3
       2810199.8      7034405.38      2810707.61      7032126.76
      2810681.58      7028678.07
#Sta/Elev= 30
  2512.3  439.27  2666.4  433.09  2809.8     422  3229.9  410.27  3479.8  408.75
  3578.2   410.4  4141.1  403.73    4623  403.13  4694.9  405.35  4958.6  406.55
  4968.6  406.56  4978.6  400.82  4988.5  399.64  5015.2  400.64  5018.6  406.51
  5318.6  404.62  5348.6   402.8  5958.6  406.24  6288.6  403.55  6558.6  405.46
  6658.6   402.7  6668.6   404.6  6788.6  405.88  7298.6   403.2  7748.7  405.09
  7848.7  409.07  7978.7  424.28  8168.7  432.84  8237.5  438.95  8295.6  443.64
#Mann= 5 ,-1 , 0
  2512.3     .05       0  4141.1     .12       0  4958.6     .07       0
  5018.6     .12       0  8237.5     .16       0
Bank Sta=4958.6,5018.6
XS Rating Curve= 0 ,0
Exp/Cntr=0.3,0.1

Type RM Length L Ch R = 1 ,265777  ,4957,4957,4957
BEGIN DESCRIPTION:
LFC97
END DESCRIPTION:
XS GIS Cut Line= 4
      2810577.38      7034392.42      2811436.77       7032712.7
        2811580.      7031814.26      2813142.48      7029145.03
#Sta/Elev= 30
  2970.8  434.74  3263.8  421.18  3463.7  416.56  3874.4  409.94  4113.1  410.25
  4340.8  403.43  4721.6  404.24  4857.6  401.35  4874.3  404.92  4956.5  405.71
  4976.8  400.51  5003.6  400.26  5017.3  405.86  5998.3  401.57  7058.5402.3996
  7106.8  402.04  7452.4  401.48  7602.6  401.21  7700.9  401.07  7946.6  400.67
  7989.8  399.93  7996.4  398.93    8023  399.93  8064.9  399.93  8128.1  399.96
  8176.7  400.57  8514.6  408.01  8614.5  414.17  8809.3  436.36  8860.3  440.08
#Mann= 17 ,-1 , 0
  2970.8     .05       0  4721.6     .12       0  4956.5     .05       0
  5017.3     .12       0  7058.5     .07       0  7106.8     .12       0
  7452.4     .07       0  7602.6     .05       0  7700.9     .07       0
  7946.6     .05       0  7989.8     .07       0    8023     .05       0
  8064.9     .12       0  8128.1     .07       0  8176.7     .12       0
  8514.6     .16       0  8809.3     .05       0
Bank Sta=4956.5,5017.3
XS Rating Curve= 0 ,0
Exp/Cntr=0.3,0.1

Type RM Length L Ch R = 1 ,260820  ,2606,2606,2606
BEGIN DESCRIPTION:
LFC96
END DESCRIPTION:
XS GIS Cut Line= 5
      2810850.85      7034574.67      2812465.42      7033181.45
      2813168.54      7032478.32      2813285.73      7031879.37
      2814391.27      7030981.93
#Sta/Elev= 30
  1500.3   433.2  1772.1   417.5  1878.5  413.35  2048.6  411.99  2205.4  414.82
  2453.3  408.66  2899.8  407.56  3185.1  401.47    3925  402.12  4139.2  404.62
  4153.3  401.49  4167.5  404.62  4577.6  402.49  4598.8  400.44  4635.3  402.52
  4966.9  403.91  4995.9   400.8  5221.6  401.23  5237.7  398.93  5282.9  401.64
    5446  399.93  5660.1  403.46    5804  407.45  5994.1  417.53  6000.6  415.02
  6043.7  416.84  6093.3  422.63  6372.2  439.32  6441.7  440.88  6661.5  439.57
#Mann= 7 ,-1 , 0
  1500.3     .05       0  3185.1     .07       0    3925     .12       0
  4966.9     .07       0  5660.1     .16       0    5804     .12       0
  6372.2     .16       0
Bank Sta=4966.9,5660.1
XS Rating Curve= 0 ,0
Exp/Cntr=0.3,0.1

Type RM Length L Ch R = 1 ,258214  ,3197,3197,3197
BEGIN DESCRIPTION:
LFC172
END DESCRIPTION:
XS GIS Cut Line= 4
      2814001.99      7035798.59      2814459.96      7033256.01
      2814701.45      7032850.85      2814584.87      7031451.87
#Sta/Elev= 30
  2416.5  444.88  2963.9  437.05    3040  435.13  3202.5   436.1  3271.8  430.81
  3474.5   412.1  3619.1   402.2  3642.9  399.21  4726.7  400.66  4797.8  399.22
  4929.9  402.34  4960.4  403.03  4980.7  399.87  5012.8  399.87  5019.1  402.51
  5027.9  402.69  5178.5  401.33  5229.3  401.18  5290.8   401.4  5727.8  401.68
  5796.3     402  5878.9  407.22  5919.1  411.79    6093  421.79  6185.2  421.45
  6380.7  423.64  6520.3  431.06  6611.5  436.26  6746.6  438.92  6875.5  440.02
#Mann= 14 ,-1 , 0
  2416.5     .05       0  2963.9     .16       0  3271.8     .05       0
  3619.1     .03       0  4929.9     .12       0  5027.9     .07       0
  5178.5     .16       0  5229.3      .1       0  5290.8     .05       0
  5727.8     .16       0  5796.3     .12       0  6185.2     .16       0
  6520.3     .12       0  6746.6     .16       0
Bank Sta=3619.1,4929.9
XS Rating Curve= 0 ,0
Exp/Cntr=0.3,0.1

Type RM Length L Ch R = 1 ,255017  ,461,461,461
BEGIN DESCRIPTION:
LFC98
END DESCRIPTION:
XS GIS Cut Line= 3
      2816280.52      7035017.39      2816189.38      7033298.64
      2815889.95       7031163.6
#Sta/Elev= 30
    3262  439.05  3264.3  439.05  3354.5  438.69  3465.2  435.42  3534.8   434.8
  3649.8  422.47  3654.9  420.69    3715  413.45  3815.2  404.69  3834.3  403.72
  3839.3  403.62  3845.2  401.88  3865.2   400.7  3868.4  399.21  6158.2  399.21
  6228.9  403.14  6345.9   411.2  6350.9  410.33  6488.6  420.26  6493.6  419.64
  6559.9  423.73  6564.9  423.13  6683.3  431.42  6794.4  432.96  6850.3  430.93
  6926.7  433.37  6976.1  433.52  7016.7  434.78  7097.3  437.74  7139.1  438.23
#Mann= 5 ,-1 , 0
    3262     .16       0  3264.3     .05       0  3834.3     .03       0
  6228.9     .05       0  7016.7     .12       0
Bank Sta=3834.3,6228.9
XS Rating Curve= 0 ,0
Exp/Cntr=0.3,0.1