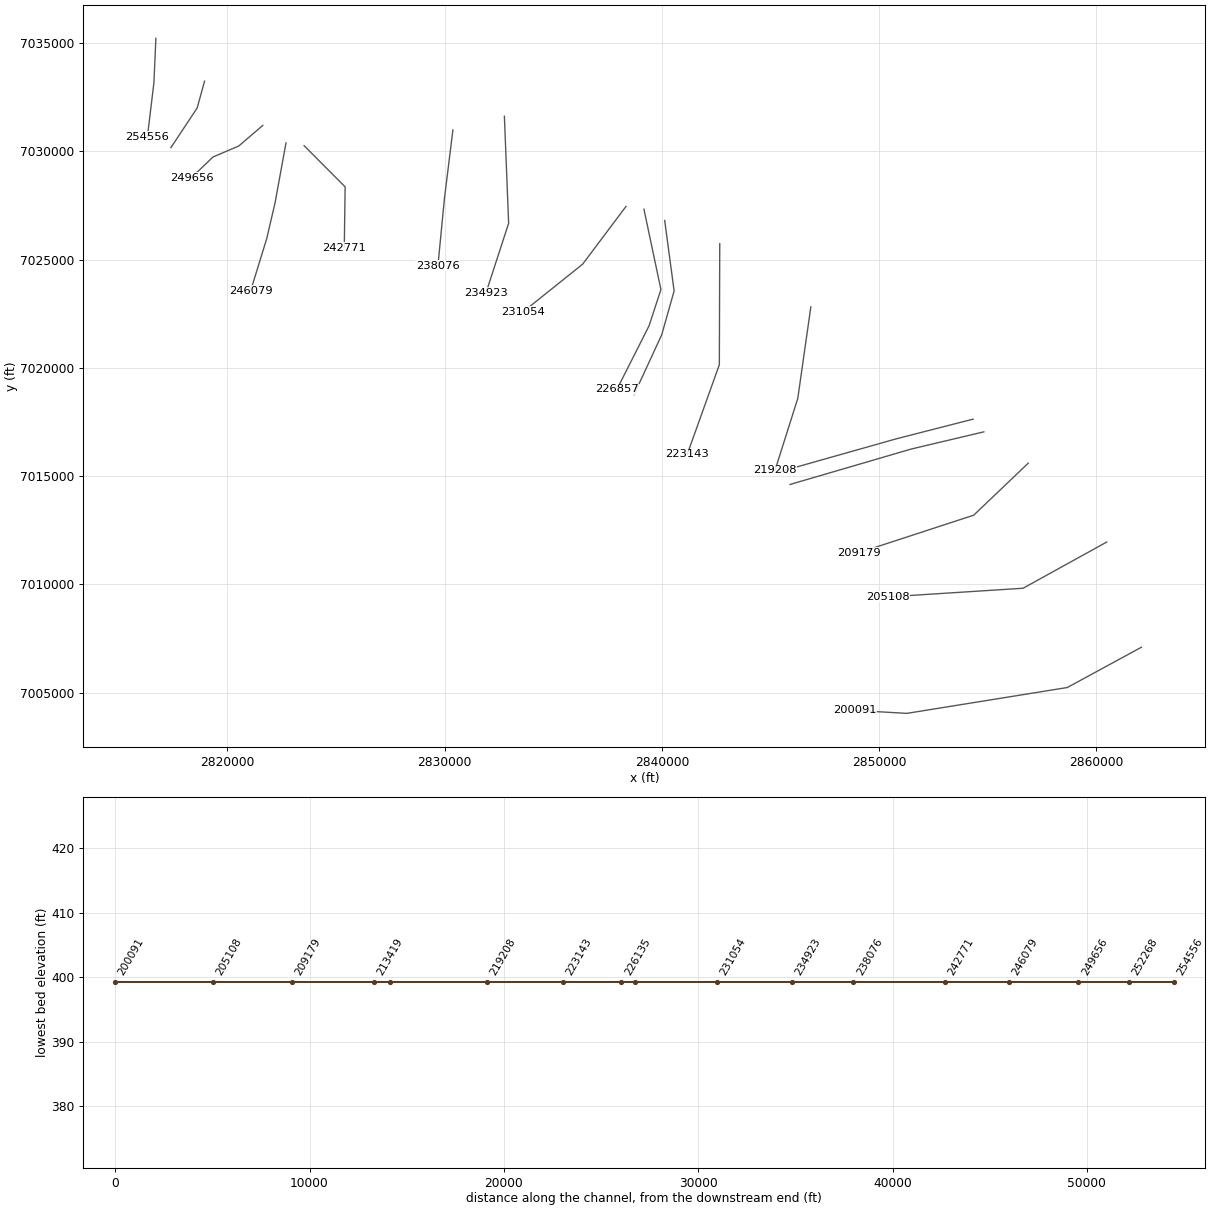
HEC-RAS study Lake Fork Creek.prj: Lake Fork Creek Base Level Engineering

--- Lake Fork Creek.g01 (geometry) --- (continued)

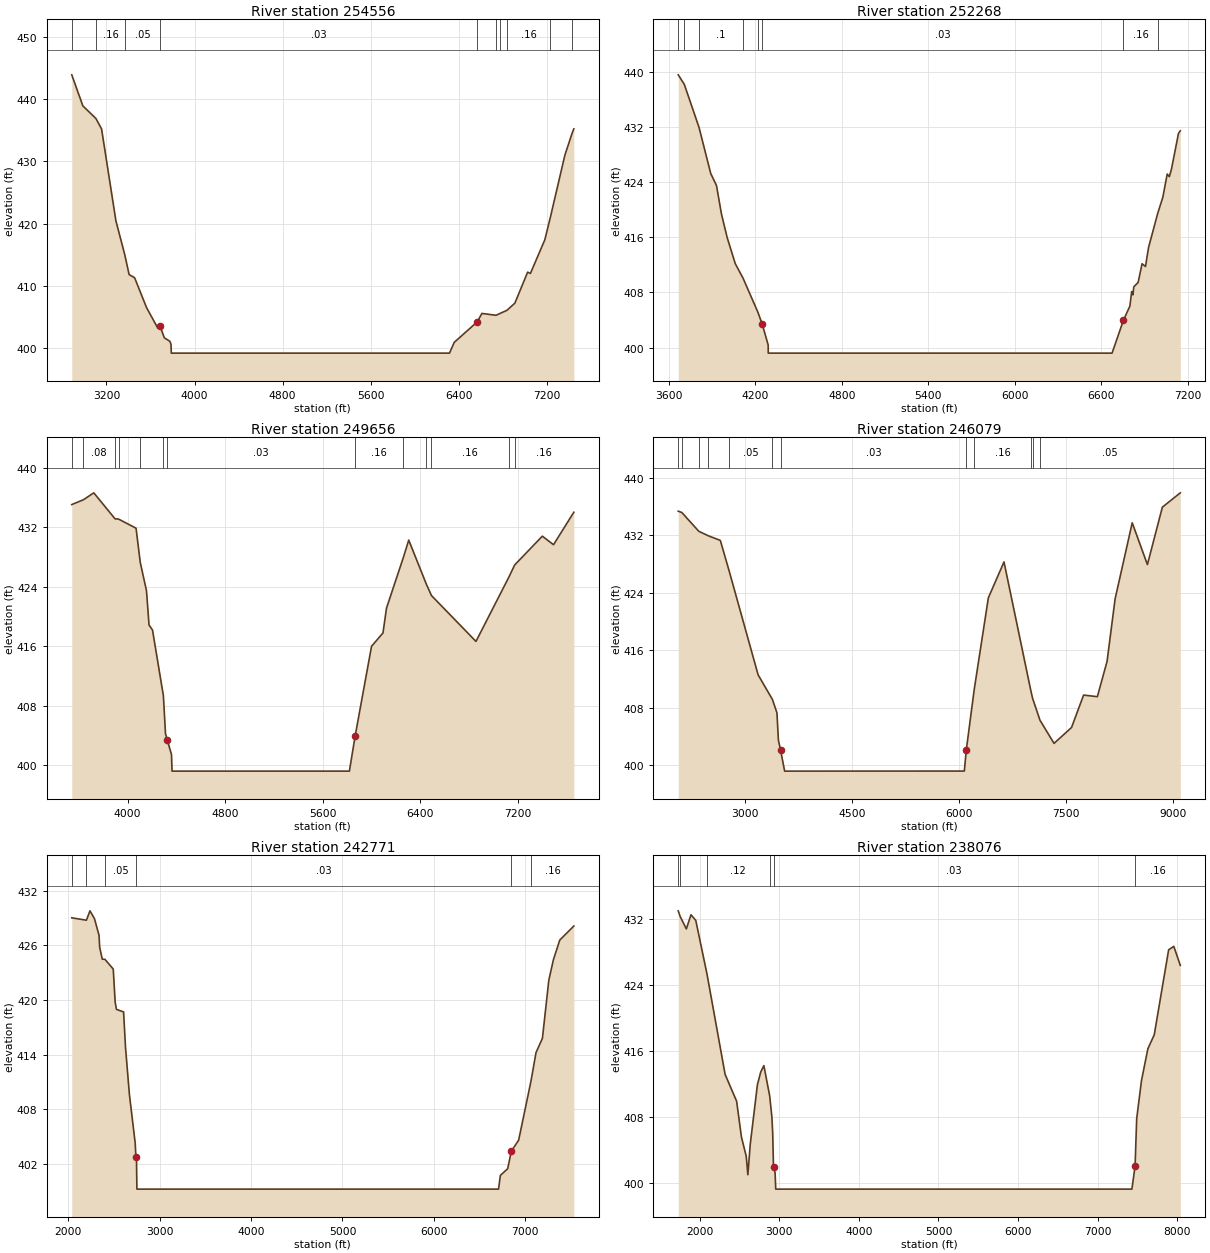
Type RM Length L Ch R = 1 ,254556  ,2288,2288,2288
BEGIN DESCRIPTION:
LFC99
END DESCRIPTION:
XS GIS Cut Line= 3
      2816710.21      7035225.69      2816619.07      7033168.43
      2816319.79      7030683.16
#Sta/Elev= 30
  2884.5  443.92  2985.3  438.93  3103.8  436.91  3155.5  435.22  3285.6  420.47
  3366.9  414.97  3405.7  411.83  3455.7  411.32  3563.9  406.53    3666  403.24
    3686  403.55    3726  401.67  3776.1  401.11  3786.1  400.64  3789.2  399.21
  6317.1  399.21  6360.1  400.94  6568.9  404.23  6611.5  405.59  6739.7  405.29
    6773  405.56  6838.5  406.08  6911.3  407.24  7027.1  412.22  7052.3  412.01
  7183.3  417.42  7233.8  421.04  7365.6  431.02  7431.5  434.55    7447  435.24
#Mann= 10 ,-1 , 0
  2884.5     .05       0  3103.8     .16       0  3366.9     .05       0
    3686     .03       0  6568.9     .12       0  6739.7     .16       0
    6773     .12       0  6838.5     .16       0  7233.8     .12       0
  7431.5     .05       0
Bank Sta=3686,6568.9
XS Rating Curve= 0 ,0
Exp/Cntr=0.3,0.1

Type RM Length L Ch R = 1 ,252268  ,2612,2612,2612
BEGIN DESCRIPTION:
LFC100
END DESCRIPTION:
XS GIS Cut Line= 3
       2818949.8      7033246.56      2818611.25      7032009.57
      2817400.32      7030173.64
#Sta/Elev= 30
  3665.8  439.52  3707.7  438.15  3809.8  431.92  3891.3  425.22    3931   423.5
  3965.5  419.37  4005.2  415.95  4061.4  412.17  4116.1  410.03  4218.2  405.14
    4248  403.43  4289.5  400.39  4290.1  399.21  6674.4  399.21  6752.6  403.94
  6797.8  406.02  6810.5  408.13  6818.9  407.65  6824.9  408.81    6855  409.44
  6882.4  412.16  6906.2  411.76  6927.3  414.51  6991.7  419.51  7026.6   421.8
  7056.7  425.15  7071.8  424.77  7086.1  425.85    7135  431.04  7147.6  431.41
#Mann= 8 ,-1 , 0
  3665.8     .05       0  3707.7     .16       0  3809.8      .1       0
  4116.1     .16       0  4218.2     .05       0    4248     .03       0
  6752.6     .16       0  6991.7     .12       0
Bank Sta=4248,6752.6
XS Rating Curve= 0 ,0
Exp/Cntr=0.3,0.1

Type RM Length L Ch R = 1 ,249656  ,3577,3577,3577
BEGIN DESCRIPTION:
LFC101
END DESCRIPTION:
XS GIS Cut Line= 4
      2821632.05      7031202.25      2820525.32      7030251.76
      2819340.42      7029743.95      2818350.86      7028793.45
#Sta/Elev= 30
    3542  435.07  3637.9  435.72  3722.7  436.65  3897.3  433.15  3925.7  433.12
  4069.6  431.89  4104.2  427.27  4155.2  423.48  4176.1  418.87  4204.6  418.19
  4293.8  409.36  4311.1  404.27  4325.3  403.43  4360.4  401.44  4364.8  399.21
  5820.2  399.21  5867.3  403.92  6002.1  416.01  6095.8   417.8  6124.8  421.14
  6262.6  427.93  6307.3  430.29  6450.8   424.4  6493.8  422.83  6858.9  416.66
  7129.3  425.32  7176.4  426.94  7403.5  430.82  7495.4  429.67  7662.1  434.04
#Mann= 13 ,-1 , 0
    3542     .05       0  3637.9     .08       0  3897.3      .1       0
  3925.7     .08       0  4104.2     .16       0  4293.8     .05       0
  4325.3     .03       0  5867.3     .16       0  6262.6     .16       0
  6450.8     .12       0  6493.8     .16       0  7129.3     .12       0
  7176.4     .16       0
Bank Sta=4325.3,5867.3
XS Rating Curve= 0 ,0
Exp/Cntr=0.3,0.1

Type RM Length L Ch R = 1 ,246079  ,3308,3308,3308
BEGIN DESCRIPTION:
LFC102
END DESCRIPTION:
XS GIS Cut Line= 4
      2822699.79      7030394.99      2822191.98      7027608.53
      2821814.38      7025980.93      2821072.84      7023564.64
#Sta/Elev= 30
  2066.4  435.38  2117.1  435.19  2354.5  432.58  2488.5  431.95  2655.9  431.31
  2783.7  426.91  3185.2   412.6  3385.5  409.18  3448.8  407.31  3469.1  403.51
  3499.6  402.15  3556.5  399.21  6072.7  399.22  6100.3  402.16  6211.8  410.61
  6409.1  423.32  6628.1  428.32  7004.3  410.39    7029  409.33  7132.1  406.29
  7328.9  403.07  7573.9  405.28  7742.8  409.79  7935.6  409.57  8071.6  414.49
    8184  423.17  8423.6  433.76  8636.5  427.95  8845.7  435.93  9097.1  437.93
#Mann= 12 ,-1 , 0
  2066.4     .05       0  2117.1     .08       0  2354.5     .05       0
  2488.5     .08       0  2783.7     .05       0  3385.5     .16       0
  3499.6     .03       0  6100.3     .05       0  6211.8     .16       0
  7004.3     .07       0    7029     .16       0  7132.1     .05       0
Bank Sta=3499.6,6100.3
XS Rating Curve= 0 ,0
Exp/Cntr=0.3,0.1

Type RM Length L Ch R = 1 ,242771  ,4695,4695,4695
BEGIN DESCRIPTION:
LFC103
END DESCRIPTION:
XS GIS Cut Line= 3
       2823533.1      7030264.81      2825421.15      7028363.74
      2825382.09      7025551.24
#Sta/Elev= 30
  2039.2  429.02  2199.4  428.76  2238.4  429.79  2287.9  428.92  2337.4   427.1
  2344.5  425.79  2372.8  424.48    2402  424.46  2492.9  423.39  2514.2  419.74
  2528.3  418.96  2606.1  418.68  2627.3  414.76  2669.7  409.61  2733.4  404.24
  2740.5  402.71  2747.5  402.34  2751.7  399.21  6707.5  399.21  6727.5  400.72
  6807.5  401.45  6847.5  403.38  6927.5  404.59  7062.1  411.06  7117.5  414.21
  7187.5  415.78  7257.5  422.16  7307.5  424.41  7377.5  426.58  7531.3  428.12
#Mann= 6 ,-1 , 0
  2039.2     .05       0  2199.4     .08       0    2402     .05       0
  2740.5     .03       0  6847.5     .12       0  7062.1     .16       0
Bank Sta=2740.5,6847.5
XS Rating Curve= 0 ,0
Exp/Cntr=0.3,0.1

Type RM Length L Ch R = 1 ,238076  ,3153,3153,3153
BEGIN DESCRIPTION:
LFC104
END DESCRIPTION:
XS GIS Cut Line= 3
      2830382.09      7030993.99      2829991.46      7027816.87
      2829692.08      7024718.94
#Sta/Elev= 30
  1727.7  433.05  1751.8  432.37  1829.6  430.85  1887.9  432.57  1948.3  431.89
  2088.7   425.4  2317.3  413.16  2462.2  409.89  2522.6  405.54  2583.1  403.19
  2603.2  400.96  2633.5  404.69  2723.6  411.92  2764.4  413.43  2804.7  414.23
  2877.9  410.53  2905.5  407.96  2915.6  406.04  2925.6  401.88  2945.8  401.19
  2953.8  399.21  7432.2  399.21  7472.4  402.01  7492.5  407.77  7552.8   412.4
  7633.2  416.28  7713.5  417.98  7894.4  428.31  7959.2  428.73  8041.1  426.42
#Mann= 6 ,-1 , 0
  1727.7     .12       0  1751.8     .16       0  2088.7     .12       0
  2877.9     .05       0  2925.6     .03       0  7472.4     .16       0
Bank Sta=2925.6,7472.4
XS Rating Curve= 0 ,0
Exp/Cntr=0.3,0.1

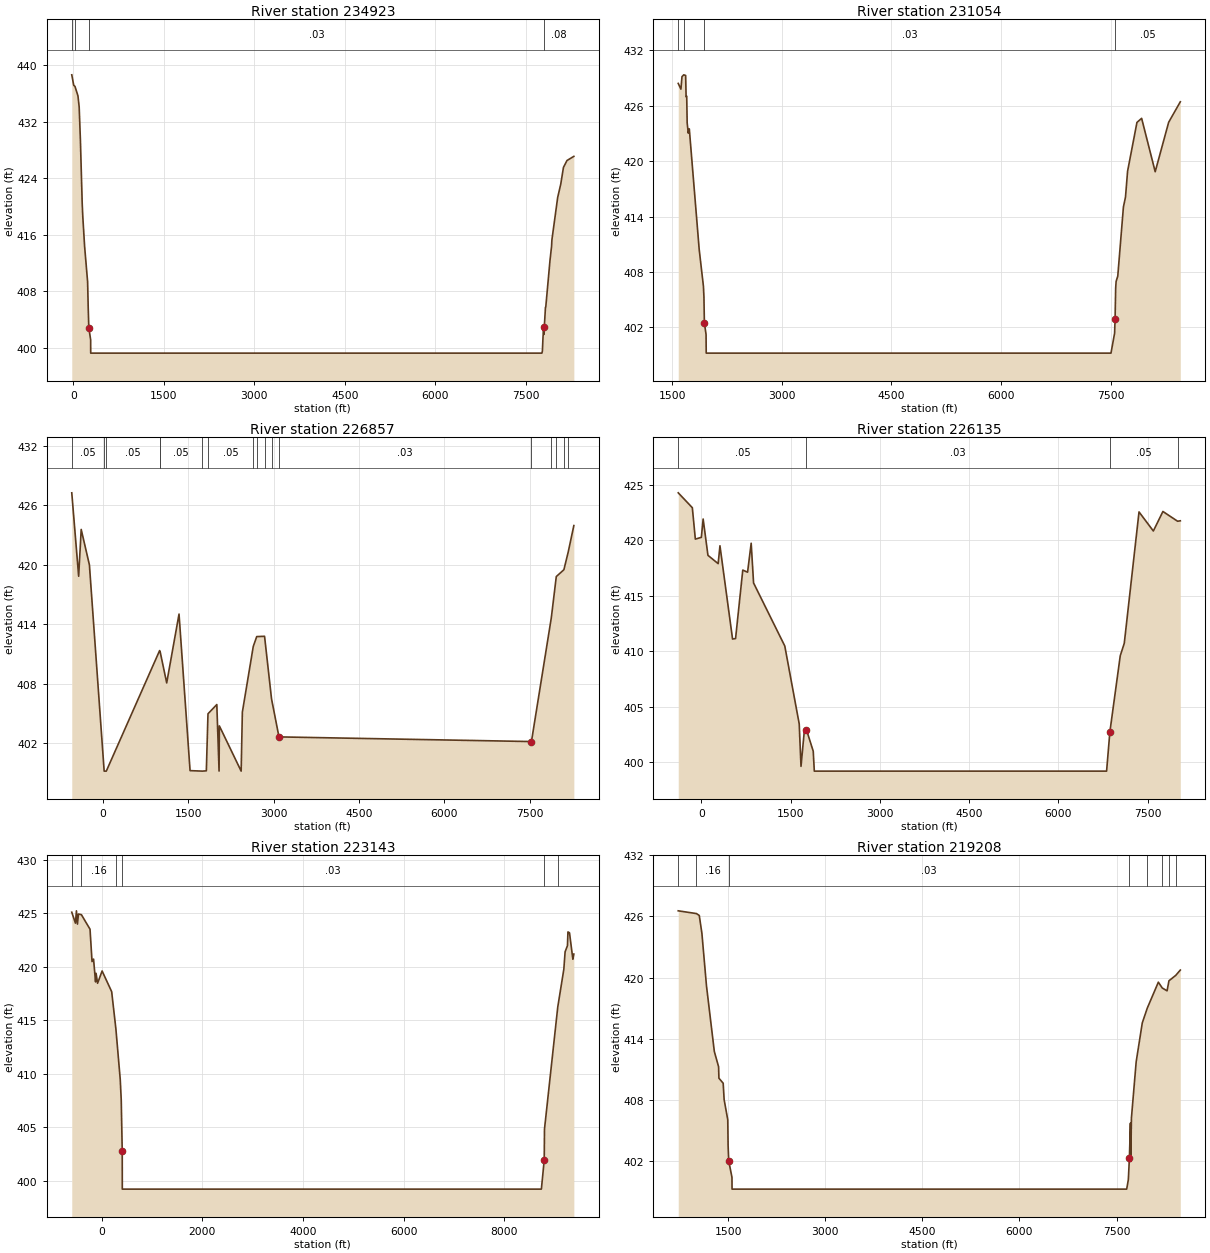
Type RM Length L Ch R = 1 ,234923  ,3869,3869,3869
BEGIN DESCRIPTION:
LFC106
END DESCRIPTION:
XS GIS Cut Line= 3
      2832751.88      7031627.62      2832947.19      7026679.71
      2831905.85      7023468.92
#Sta/Elev= 30
   -27.6  438.67       5  437.18    25.4  437.03    75.1  435.69    95.1  434.12
   115.1  429.55   145.2   420.5   155.2  418.58   185.2  414.37   235.2  409.31
   245.2  405.63   255.2   402.8   285.3  401.12   286.6  399.21  7770.2  399.21
  7778.1  399.53  7788.6  401.56  7796.9  402.48  7802.1  401.86  7809.6   402.9
  7828.9  405.71  7834.1  405.76  7904.2  412.38  7930.1  414.35  7935.8  415.27
  8031.2  421.27  8082.9  423.19  8127.2  425.54  8185.9  426.52  8299.6  427.11
#Mann= 4 ,-1 , 0
   -27.6     .08       0    25.4     .05       0   255.2     .03       0
  7809.6     .08       0
Bank Sta=255.2,7809.6
XS Rating Curve= 0 ,0
Exp/Cntr=0.3,0.1

Type RM Length L Ch R = 1 ,231054  ,4197,4197,4197
BEGIN DESCRIPTION:
LFC105
END DESCRIPTION:
XS GIS Cut Line= 3
      2838350.84      7027460.97      2836354.31      7024791.69
      2833598.22      7022578.14
#Sta/Elev= 30
  1584.4  428.41  1621.1  427.79  1635.7  429.14  1659.9  429.34  1685.8  429.27
    1692  426.97  1700.3  427.03  1706.6  424.14  1721.2  423.03  1735.8  423.49
  1871.2  410.43    1929  406.45  1935.8  405.34  1942.1   402.5    1965  401.23
  1967.2  399.21  7504.4  399.21    7554  401.38  7560.4  402.93  7568.4  406.24
  7574.8  406.98  7597.2  407.55  7674.4  415.03  7702.8   416.1  7731.6  418.91
  7859.6  424.19  7923.6  424.63  8109.2  418.85  8293.3   424.2  8452.7  426.42
#Mann= 4 ,-1 , 0
  1584.4     .08       0  1659.9     .05       0  1942.1     .03       0
  7560.4     .05       0
Bank Sta=1942.1,7560.4
XS Rating Curve= 0 ,0
Exp/Cntr=0.3,0.1

Type RM Length L Ch R = 1 ,226857  ,722,722,722
BEGIN DESCRIPTION:
LFC107
END DESCRIPTION:
XS GIS Cut Line= 4
      2839175.49      7027330.75      2839956.74      7023619.82
      2839413.16      7021947.73      2837938.52      7019019.15
#Sta/Elev= 30
  -550.5  427.26  -429.3  418.85  -384.6  423.57  -240.3     420    19.2  399.21
    56.6  399.21   994.5  411.36  1004.9  411.21  1118.9   408.1  1335.7  415.04
  1529.9  399.26  1745.5  399.21    1816  399.24    1845  404.99  2000.3  405.92
  2039.9  399.22    2045  403.77  2428.2  399.21  2449.6  405.16  2640.9  411.77
  2702.1  412.77  2839.9   412.8  2962.6  406.49  3093.4  402.66  7533.4  402.19
  7882.3  414.65  7970.2  418.82    8104  419.51  8180.6  421.31  8278.9  423.96
#Mann= 17 ,-1 , 0
  -550.5     .05       0    19.2    .033       0    56.6     .05       0
   994.5      .1       0  1004.9     .05       0  1745.5     .16       0
    1845     .05       0  2640.9      .1       0  2702.1     .15       0
  2839.9     .08       0  2962.6     .05       0  3093.4     .03       0
  7533.4     .05       0  7882.3      .1       0  7970.2     .08       0
    8104      .1       0  8180.6     .08       0
Bank Sta=3093.4,7533.4
XS Rating Curve= 0 ,0
Exp/Cntr=0.3,0.1

Type RM Length L Ch R = 1 ,226135  ,2992,2992,2992
BEGIN DESCRIPTION:
LFC108
END DESCRIPTION:
XS GIS Cut Line= 4
      2840130.35      7026809.94      2840564.38      7023554.71
      2839994.26      7021530.19      2838720.17       7018759.6
#Sta/Elev= 30
  -387.3  424.28  -150.3  422.94   -99.8  420.11       1  420.27    31.3  421.92
     112  418.65   283.5   417.9   313.8  419.51   525.6  411.11   576.1  411.15
   697.2  417.32   777.9  417.13   838.4  419.74   878.7  416.16  1403.3  410.48
  1645.5  403.47  1675.7  399.64  1729.9  402.74  1766.5  402.95  1881.3     401
  1899.2  399.21  6810.8  399.21  6865.8  402.74  7040.5  409.61    7108  410.73
  7355.7  422.56  7596.5  420.84  7757.3   422.6    8004  421.72  8049.5  421.76
#Mann= 4 ,-1 , 0
  -387.3     .05       0  1766.5     .03       0  6865.8     .05       0
    8004     .16       0
Bank Sta=1766.5,6865.8
XS Rating Curve= 0 ,0
Exp/Cntr=0.3,0.1

Type RM Length L Ch R = 1 ,223143  ,3935,3935,3935
BEGIN DESCRIPTION:
LFC112
END DESCRIPTION:
XS GIS Cut Line= 3
      2842665.07      7025737.85      2842646.16      7020145.18
        2841172.      7016015.62
#Sta/Elev= 30
  -592.7  425.08  -519.8  424.06  -499.8  425.21  -479.8  423.97  -459.8  424.91
  -401.1  424.85  -229.8  423.49  -189.8  420.47  -159.8   420.7  -119.8  418.57
  -109.8  419.37   -79.8  418.44    10.2  419.59   200.2  417.66   283.9  414.19
   370.2  409.48   390.2  407.56   410.2  402.73   411.5  399.21  8739.7  399.21
    8796  401.92  8801.5  404.82    9065  416.22  9185.8  419.75  9211.3  421.39
    9258  421.95  9267.6  423.24  9298.4  423.16  9365.3  420.69  9384.8  421.17
#Mann= 6 ,-1 , 0
  -592.7     .05       0  -401.1     .16       0   283.9     .05       0
   410.2     .03       0    8796     .05       0    9065     .05       0
Bank Sta=410.2,8796
XS Rating Curve= 0 ,0
Exp/Cntr=0.3,0.1

Type RM Length L Ch R = 1 ,219208  ,4958,4958,4958
BEGIN DESCRIPTION:
LFC109
END DESCRIPTION:
XS GIS Cut Line= 3
      2846857.78      7022816.89      2846256.91      7018589.07
      2845208.48      7015264.78
#Sta/Elev= 30
   729.7  426.55  1011.7  426.28  1054.8  426.09  1095.2  424.35  1165.9  419.19
  1287.3  412.73  1353.2  411.23  1358.2  410.11  1424.1  409.61  1438.6  408.01
  1494.9  406.02    1500  403.51  1509.3  401.99  1559.8  400.37  1560.9  399.21
  7657.1  399.21    7683  400.14  7699.1  402.25  7715.4  405.69  7720.6  401.92
  7730.5  406.19  7803.9  411.72  7898.3  415.54  7974.2  416.97  8146.4  419.54
    8207  418.97  8281.1  418.69  8310.4  419.68  8413.7   420.2  8485.7  420.73
#Mann= 8 ,-1 , 0
   729.7     .05       0  1011.7     .16       0  1509.3     .03       0
  7699.1     .16       0  7974.2     .05       0    8207     .08       0
  8310.4     .05       0  8413.7     .16       0
Bank Sta=1509.3,7699.1
XS Rating Curve= 0 ,0
Exp/Cntr=0.3,0.1

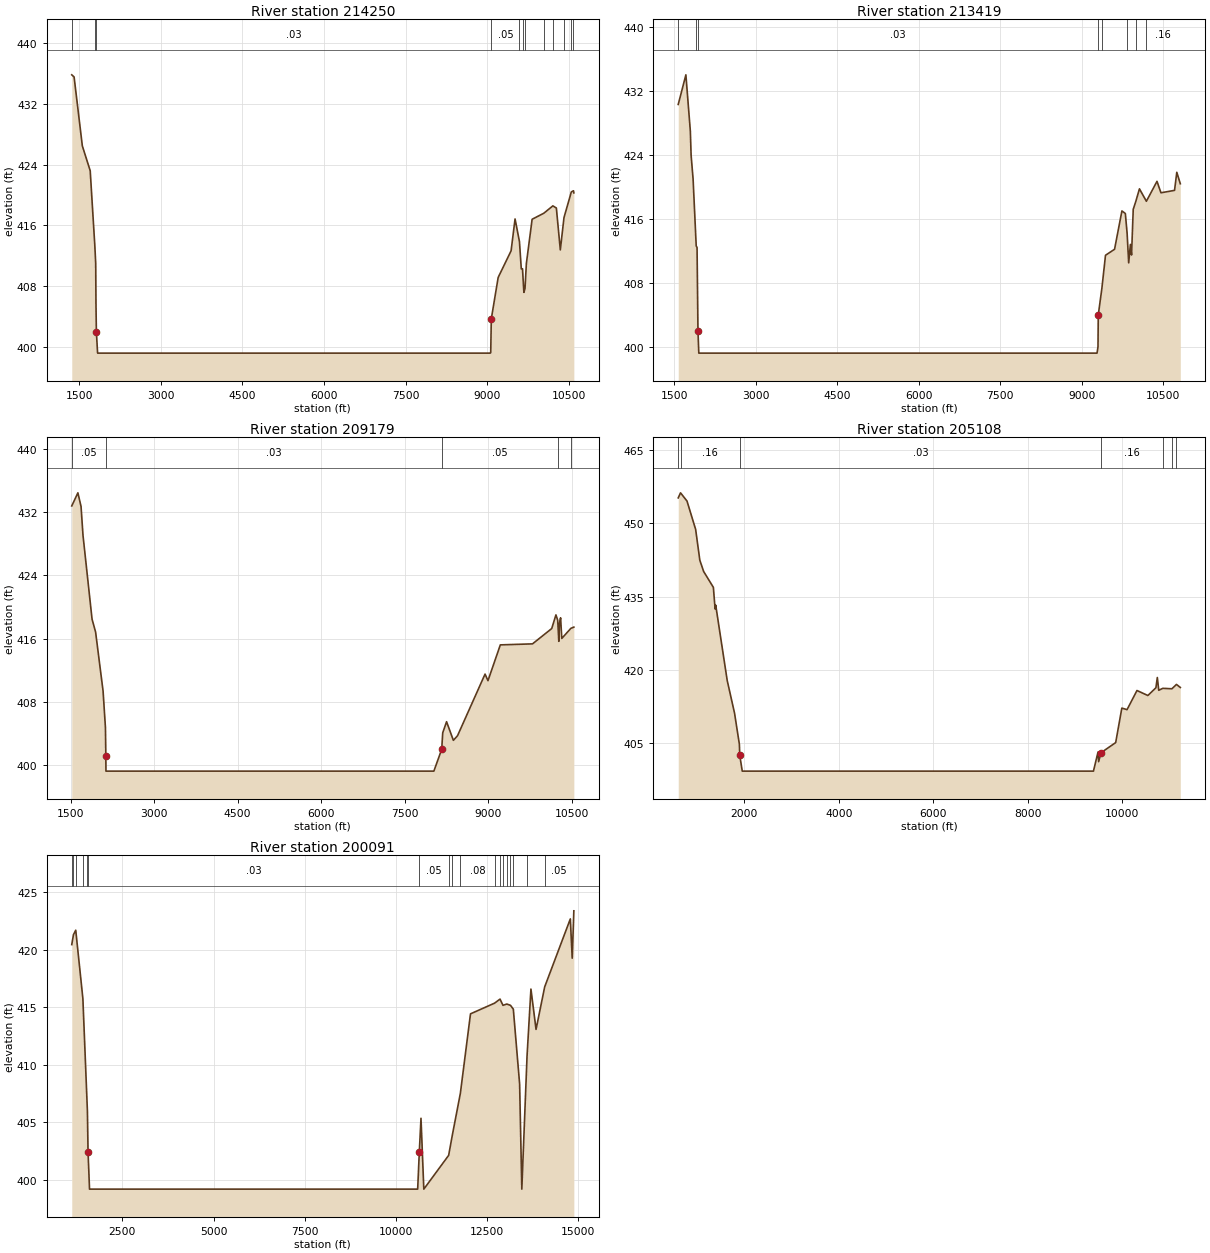
Type RM Length L Ch R = 1 ,214250  ,831,831,831
BEGIN DESCRIPTION:
LFC110
END DESCRIPTION:
XS GIS Cut Line= 3
      2854323.09      7017630.24      2850802.66       7016724.8
      2845426.04      7015199.84
#Sta/Elev= 30
    1365  435.82  1407.8  435.54  1559.2  426.47  1703.8   423.2  1789.5  413.24
  1804.7  411.02  1809.9  405.56  1817.3  401.96  1839.5  399.21  9052.7  399.21
  9061.8  399.27  9072.2  403.71  9198.8  409.17    9436  412.67  9508.8  416.86
  9589.4  413.89  9623.1  410.29  9645.6  410.31  9670.9   407.2  9691.6   407.7
  9716.6     411  9822.1  416.82 10036.6  417.61   10203  418.58 10267.6   418.3
 10340.3  412.79 10407.5  417.04 10542.1  420.41 10582.1  420.57 10588.7  420.29
#Mann= 12 ,-1 , 0
    1365     .16       0  1789.5     .05       0  1817.3     .03       0
  9072.2     .05       0  9589.4     .16       0  9645.6     .08       0
  9691.6     .05       0 10036.6     .08       0   10203      .1       0
 10407.5     .05       0 10542.1     .16       0 10582.1     .05       0
Bank Sta=1817.3,9072.2
XS Rating Curve= 0 ,0
Exp/Cntr=0.3,0.1

Type RM Length L Ch R = 1 ,213419  ,4240,4240,4240
BEGIN DESCRIPTION:
LFC111
END DESCRIPTION:
XS GIS Cut Line= 3
      2854822.17      7017044.29      2851485.79      7016251.86
      2845902.95      7014613.75
#Sta/Elev= 30
  1570.8  430.29  1711.8  433.99    1794  426.94  1807.6  423.97  1844.6  420.95
  1901.9   412.6  1917.4  412.41  1934.2  402.02  1949.6  399.21  9284.1  399.21
    9302  399.99  9307.2  403.97  9373.3  407.29  9440.4  411.44  9607.2  412.19
  9742.6  416.98  9805.9  416.66  9838.5  414.18  9867.5  410.49    9899   412.8
  9919.8  411.47  9951.1  417.18  9998.5  418.17 10065.7  419.74 10193.4  418.19
 10388.8  420.68 10461.7  419.25 10711.9  419.55 10753.5  421.81 10818.2  420.38
#Mann= 8 ,-1 , 0
  1570.8     .16       0  1901.9     .05       0  1934.2     .03       0
  9307.2     .16       0  9373.3     .05       0  9838.5      .1       0
  9998.5     .15       0 10193.4     .16       0
Bank Sta=1934.2,9307.2
XS Rating Curve= 0 ,0
Exp/Cntr=0.3,0.1

Type RM Length L Ch R = 1 ,209179  ,4071,4071,4071
BEGIN DESCRIPTION:
LFC113
END DESCRIPTION:
XS GIS Cut Line= 3
      2856866.43      7015598.95      2854355.04      7013193.41
      2849089.35      7011467.26
#Sta/Elev= 30
  1522.4   432.8  1632.4  434.46    1689  432.73  1724.2  429.07  1886.8  418.46
  1950.7  416.82  2084.9  409.34  2127.4  404.71  2134.3  401.17  2136.5  399.21
  8027.1  399.21  8167.6  401.97  8186.3  404.07  8255.2  405.47  8377.3  403.11
  8451.8  403.69  8946.4   411.5    8999  410.67  9220.8   415.2  9799.2  415.33
 10144.1  417.27 10219.7     419 10251.3  418.33 10265.7  416.46 10271.4  415.65
 10282.9   417.9 10303.3  418.63   10325  416.02 10488.8   417.3 10541.4  417.45
#Mann= 5 ,-1 , 0
  1522.4     .05       0  2134.3     .03       0  8167.6     .05       0
 10265.7     .08       0 10488.8     .05       0
Bank Sta=2134.3,8167.6
XS Rating Curve= 0 ,0
Exp/Cntr=0.3,0.1

Type RM Length L Ch R = 1 ,205108  ,5017,5017,5017
BEGIN DESCRIPTION:
LFC114
END DESCRIPTION:
XS GIS Cut Line= 3
      2860477.58      7011953.15      2856628.38      7009817.84
      2850409.09      7009418.49
#Sta/Elev= 30
   598.2  455.21   646.7  456.25   784.1  454.56   967.1  448.75  1055.5  442.44
  1136.8  440.12  1342.8  436.87  1378.8  432.45    1392  433.23  1635.7  417.78
  1790.5  411.11  1893.4  404.71  1901.2  402.45  1954.2  399.21  9392.4  399.21
  9489.8  403.13  9502.6  401.15  9552.7  402.98  9863.4  405.06  9993.6  412.13
 10103.9  411.81 10314.3  415.73 10544.8  414.71 10715.1  416.29 10745.3   418.4
 10775.3  415.78 10861.4  416.18 11054.8  416.09 11150.4  416.98 11232.1  416.36
#Mann= 7 ,-1 , 0
   598.2     .05       0   646.7     .16       0  1901.2     .03       0
  9552.7     .16       0 10861.4     .16       0 11054.8     .08       0
 11150.4      .1       0
Bank Sta=1901.2,9552.7
XS Rating Curve= 0 ,0
Exp/Cntr=0.3,0.1

Type RM Length L Ch R = 1 ,200091  ,4704,4704,4704
BEGIN DESCRIPTION:
LFC115
END DESCRIPTION:
XS GIS Cut Line= 4
      2862074.83      7007092.06      2858661.13      7005231.09
      2851276.18      7004036.48      2848880.35      7004175.37
#Sta/Elev= 30
    1112  420.43  1158.3  421.29  1220.9  421.68  1416.7  415.75  1541.3  405.95
  1558.4  402.45    1599  399.21   10598  399.21 10643.2  402.44 10689.1  405.36
 10766.6  399.21 11447.5  402.14 11547.5  403.88 11768.7  407.52 12046.6  414.42
 12707.9  415.35 12856.6   415.7 12937.7  415.16 13043.3  415.27 13142.6  415.16
 13221.1  414.83 13393.7  408.34 13453.8  399.21 13597.4  410.75 13704.2  416.57
 13844.4  413.07 14081.1  416.76 14784.5  422.66 14836.1  419.25 14880.8  423.36
#Mann= 18 ,-1 , 0
    1112     .05       0  1158.3     .16       0  1220.9     .12       0
  1416.7     .16       0  1541.3     .05       0  1558.4     .03       0
 10643.2     .05       0 11447.5      .1       0 11547.5     .08       0
 11768.7     .08       0 12707.9      .1       0 12856.6     .08       0
 12937.7     .16       0 13043.3     .08       0 13142.6      .1       0
 13221.1     .08       0 13597.4     .08       0 14081.1     .05       0
Bank Sta=1558.4,10643.2
XS Rating Curve= 0 ,0
Exp/Cntr=0.3,0.1