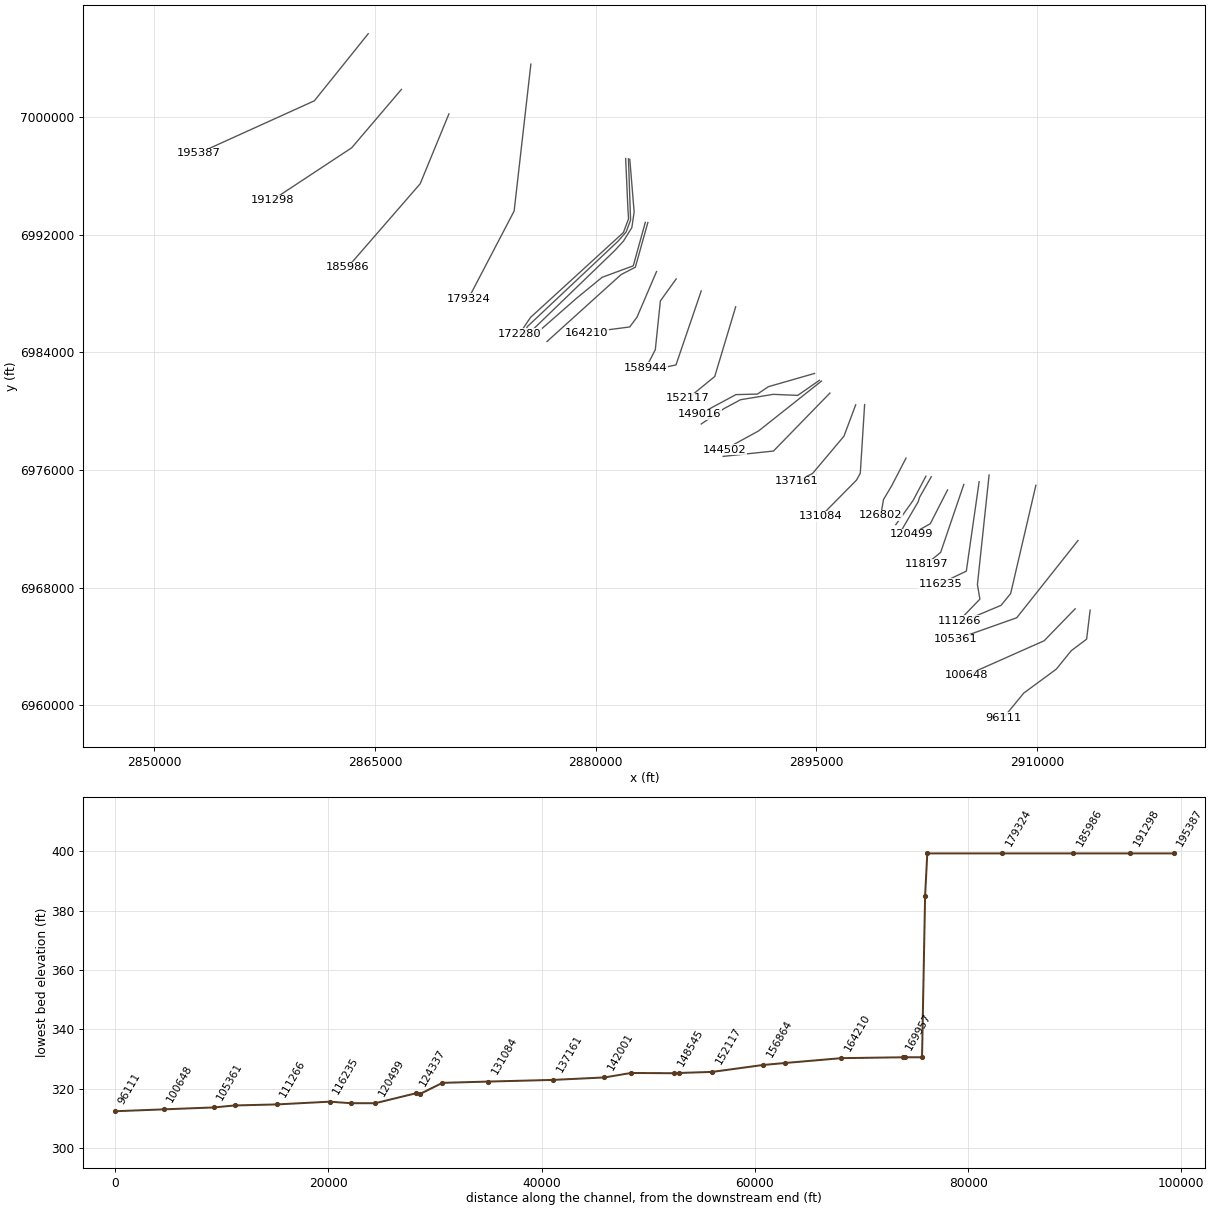
HEC-RAS study Lake Fork Creek.prj: Lake Fork Creek Base Level Engineering

--- Lake Fork Creek.g01 (geometry) --- (continued)

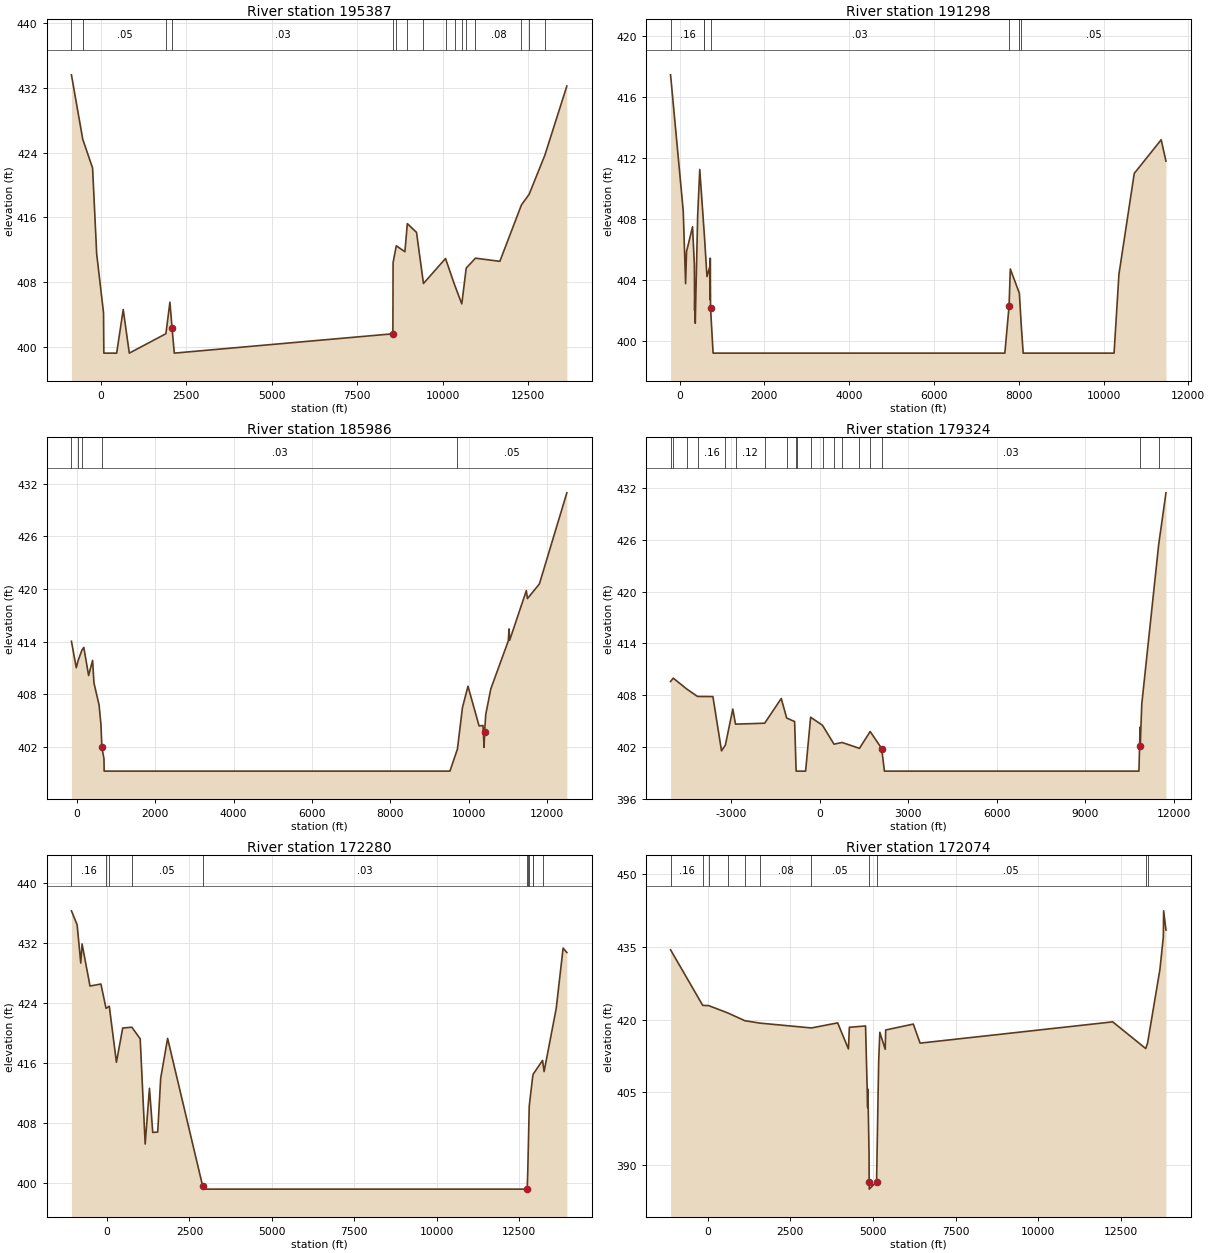
Type RM Length L Ch R = 1 ,195387  ,4089,4089,4089
BEGIN DESCRIPTION:
LFC116
END DESCRIPTION:
XS GIS Cut Line= 3
       2864540.1      7005668.46      2860875.53      7001107.32
      2853012.28      6997543.42
#Sta/Elev= 30
  -850.9  433.62  -519.7  425.65  -232.6   422.1  -112.6  411.47    87.4   404.2
    96.4  399.21   471.4  399.21   663.4   404.6     841  399.21  1910.8  401.61
  2028.3  405.51  2092.3  402.28  2156.3  399.21    8547 401.602  8553.4  410.41
    8647  412.48  8898.6  411.75  8969.8  415.22  9238.5  414.14  9441.5  407.82
   10086  410.91 10353.9  407.63 10562.2   405.3 10691.3  409.73 10961.8  410.95
 11674.9  410.56 12305.3  417.53 12532.6  418.86 12993.7  423.72 13633.2  432.23
#Mann= 16 ,-1 , 0
  -850.9     .16       0  -519.7     .05       0  1910.8     .07       0
  2092.3     .03       0    8547     .05       0    8647     .15       0
  8969.8      .1       0  9441.5     .16       0   10086     .05       0
 10353.9     .16       0 10562.2     .12       0 10691.3     .16       0
 10961.8     .08       0 12305.3     .05       0 12532.6     .16       0
 12993.7     .05       0
Bank Sta=2092.3,8547
XS Rating Curve= 0 ,0
Exp/Cntr=0.3,0.1

Type RM Length L Ch R = 1 ,191298  ,5312,5312,5312
BEGIN DESCRIPTION:
LFC117
END DESCRIPTION:
XS GIS Cut Line= 3
      2866797.01       7001883.7      2863416.77      6997913.84
      2858013.04      6994349.48
#Sta/Elev= 30
    -214  417.47    84.8  408.55   140.8  403.77   162.8  405.87   304.5   407.5
   347.3  405.05   353.9     402   361.6  403.37   368.1  401.17   425.3  408.22
   474.7  411.26   584.3  406.92   584.5  406.91   644.9  404.23   708.6  404.85
   716.3  402.72   722.8  405.44   729.9  402.16   789.2  399.21  7672.1  399.21
  7771.4  402.28  7801.6  404.73  8014.8  403.14  8059.5  401.03  8104.8  399.21
 10249.1  399.21 10363.8  404.38 10725.1     411 11360.4  413.21 11473.4  411.81
#Mann= 7 ,-1 , 0
    -214     .16       0   584.3     .05       0   584.5     .16       0
   729.9     .03       0  7771.4     .05       0  8014.8     .16       0
  8059.5     .05       0
Bank Sta=729.9,7771.4
XS Rating Curve= 0 ,0
Exp/Cntr=0.3,0.1

Type RM Length L Ch R = 1 ,185986  ,6662,6662,6662
BEGIN DESCRIPTION:
LFC118
END DESCRIPTION:
XS GIS Cut Line= 3
      2870026.18      7000217.02      2868072.38      6995465.43
      2863151.16      6989800.35
#Sta/Elev= 30
  -137.6  414.03   -13.6  411.01    29.1  411.77   129.1  413.01   178.1  413.33
   300.9  410.12   402.2  411.85   437.6  409.26   567.6  406.77   615.5  404.54
   639.4  401.93   692.8  400.61   697.4  399.21  9520.7  399.21  9712.5  401.73
  9839.7  406.45  9981.2   408.9 10265.1  404.37 10364.9  404.42 10392.4  401.92
10405.49403.6794 10435.1  405.68 10563.3  408.59 11009.6  414.07 11030.5  415.44
 11044.7  414.14 11470.2  419.81 11498.7   418.9 11803.5  420.57 12504.1  430.97
#Mann= 5 ,-1 , 0
  -137.6     .05       0    29.1     .08       0   129.1     .05       0
   639.4     .03       0  9712.5     .05       0
Bank Sta=639.4,10405.49
XS Rating Curve= 0 ,0
Exp/Cntr=0.3,0.1

Type RM Length L Ch R = 1 ,179324  ,7044,7044,7044
BEGIN DESCRIPTION:
LFC119
END DESCRIPTION:
XS GIS Cut Line= 3
      2875599.08      7003600.21      2874462.33      6993614.81
      2871346.24      6987648.77
#Sta/Elev= 30
 -5049.9  409.59 -4958.9  409.98 -4498.9  408.71 -4137.1  407.86 -3615.5  407.84
 -3323.6  401.56 -3193.2  402.23 -2941.2   406.4 -2849.9  404.65 -1862.5  404.76
 -1300.6  407.62   -1117  405.36  -847.7  404.95  -796.7  399.21  -757.9  399.21
  -475.3  399.21  -305.9  405.45    96.6  404.52   486.9  402.33   756.5  402.53
    1349  401.85  1711.3   403.8  2101.5  401.83  2194.2  399.21 10815.5  399.21
   10854   404.3 10859.7  402.16 10911.5  406.99 11484.9  425.47 11730.8  431.44
#Mann= 19 ,-1 , 0
 -5049.9     .12       0 -4958.9     .12       0 -4498.9     .12       0
 -4137.1     .16       0 -3193.2     .12       0 -2849.9     .12       0
 -1862.5     .12       0   -1117     .16       0  -796.7    .033       0
  -757.9     .05       0  -305.9     .16       0    96.6     .12       0
   486.9     .16       0   756.5     .12       0    1349     .12       0
  1711.3     .12       0  2101.5     .03       0 10859.7     .16       0
 11484.9     .05       0
Bank Sta=2101.5,10859.7
XS Rating Curve= 0 ,0
Exp/Cntr=0.3,0.1

Type RM Length L Ch R = 1 ,172280  ,206,206,206
BEGIN DESCRIPTION:
LFC120
END DESCRIPTION:
XS GIS Cut Line= 6
      2882044.41      6997187.54      2882196.32      6993802.11
      2882239.73      6993085.96       2881892.5       6992152.8
       2875577.4      6986380.23      2874818.93      6985253.36
#Sta/Elev= 30
 -1076.9  436.25  -904.2   434.4  -794.1   429.3    -754  431.84  -513.8  426.24
  -183.5  426.51   -27.5  423.27    70.6  423.55     287  416.09   477.2  420.65
   755.3  420.76  1007.7  419.21  1157.9  405.21    1288  412.63  1388.1  406.75
  1538.3  406.81  1628.4  413.97  1838.6  419.27  2900.1  399.63  2900.2  399.21
 12737.7  399.21 12756.1  401.74 12799.5  410.25 12903.3  414.16 12919.4  414.51
   13203  416.34 13250.2  414.86 13616.5  423.24 13826.4  431.29 13939.3   430.7
#Mann= 11 ,-1 , 0
 -1076.9     .16       0   -27.5     .05       0    70.6     .16       0
   755.3     .05       0  2900.1     .03       0 12737.7     .05       0
 12756.1     .12       0 12799.5     .05       0 12903.3     .12       0
 12919.4     .16       0   13203     .05       0
Bank Sta=2900.1,12737.7
XS Rating Curve= 0 ,0
Exp/Cntr=0.3,0.1

Type RM Length L Ch R = 1 ,172074  ,287,287,287
BEGIN DESCRIPTION:
LFC122
END DESCRIPTION:
XS GIS Cut Line= 6
      2882234.52      6997167.51      2882378.61      6992999.16
      2882079.13      6992191.87      2881532.26      6991566.87
      2875356.04      6985750.89      2875147.85      6985169.69
#Sta/Elev= 30
 -1116.7  434.42  -144.5  422.93    33.7  422.88   612.3  421.37  1127.8  419.76
  1585.6  419.26  3141.7  418.26    3934  419.31  4259.6  413.92    4288   418.4
  4777.1  418.67  4840.6  401.79  4847.9  405.61  4883.1  392.24 4885.87386.4554
  4889.9  384.93 5110.11 386.481  5173.5  411.28  5208.6  417.36  5371.4  413.85
  5385.5  417.84  6220.4  419.06  6425.6  415.12 12247.9  419.52 13246.4     414
 13302.8  415.18 13674.9  430.36 13777.5  437.05 13787.3  442.48 13857.5  438.52
#Mann= 11 ,-1 , 0
 -1116.7     .16       0  -144.5     .08       0    33.7     .05       0
   612.3     .08       0  1127.8     .05       0  1585.6     .08       0
  3141.7     .05       0 4885.87    .033       0 5110.11     .05       0
 13246.4     .16       0 13302.8     .05       0
Bank Sta=4885.87,5110.11
XS Rating Curve= 0 ,0
Exp/Cntr=0.3,0.1

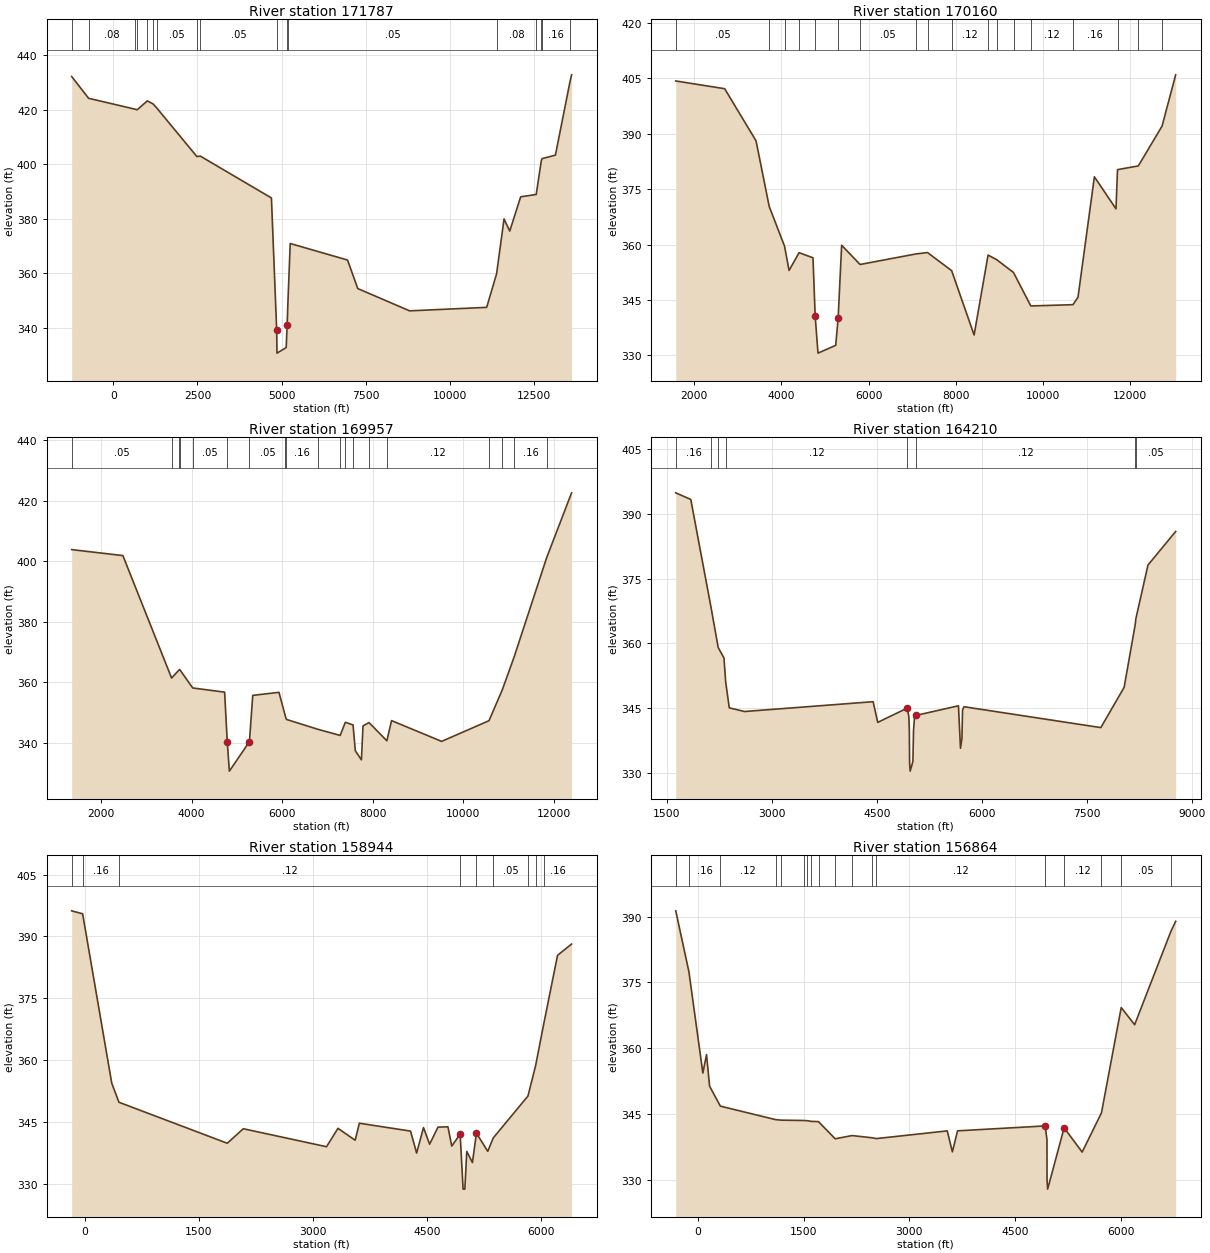
Type RM Length L Ch R = 1 ,171787  ,1627,1627,1627
BEGIN DESCRIPTION:
LFC121
END DESCRIPTION:
XS GIS Cut Line= 6
      2882326.53      6997122.45      2882621.67      6993546.03
      2882465.42        6992487.       2881892.5      6991566.87
      2881302.23       6990924.5       2875364.7      6985195.32
#Sta/Elev= 30
 -1241.5  432.16  -737.4  424.16   632.1  420.19   706.8  419.94  1008.6   423.2
  1180.9  422.09  1305.6  420.36  2483.2  402.76  2582.5  402.95  4699.1  387.57
  4855.1   339.2  4864.6  330.61  5138.1  332.65  5166.5  340.97  5196.3  351.45
  5258.3  370.85  6962.8  364.78  7266.9  354.31  8808.6  346.13   11100  347.41
 11395.4  359.75 11616.3  379.87 11786.1  375.41 12111.3  387.99   12573  388.85
 12724.4  401.19 12743.8  401.99 13143.9  403.28 13570.7   429.8 13624.8  432.77
#Mann= 17 ,-1 , 0
 -1241.5     .16       0  -737.4     .08       0   632.1     .05       0
   706.8     .08       0  1008.6     .05       0  1180.9     .08       0
  1305.6     .05       0  2483.2     .08       0  2582.5     .05       0
  4855.1    .033       0  5166.5      .1       0  5196.3     .05       0
 11395.4     .08       0   12573     .16       0 12724.4     .05       0
 12743.8     .16       0 13570.7     .05       0
Bank Sta=4855.1,5166.5
XS Rating Curve= 0 ,0
Exp/Cntr=0.3,0.1

Type RM Length L Ch R = 1 ,170160  ,203,203,203
BEGIN DESCRIPTION:
Mapping XS e314d136
END DESCRIPTION:
XS GIS Cut Line= 5
      2883379.42      6992839.61      2882563.46      6989888.25
       2880445.4        6989107.      2878726.65      6987700.75
      2875775.28      6985113.96
#Sta/Elev= 30
  1578.3   404.3  2700.2   402.2  3419.8  388.09  3721.2  370.34  4073.9  359.54
  4176.9  352.99  4406.3  357.81  4725.7  356.42  4775.9  340.66  4840.5  330.61
  5246.9  332.72  5302.4  340.07  5383.1  359.82  5805.4  354.61  7085.9  357.46
  7352.2  357.84    7906  352.93  8420.8  335.52  8740.9  357.16    8942  355.89
  9324.7  352.43  9721.4  343.38 10687.8  343.73 10803.4  345.75 11179.2  378.35
 11674.6  369.67 11709.6  380.29 12187.1   381.3   12731  392.07 13043.2  405.96
#Mann= 18 ,-1 , 0
  1578.3     .05       0  3721.2     .05       0  4073.9     .08       0
  4406.3     .05       0  4775.9    .033       0  5302.4     .08       0
  5805.4     .05       0  7085.9     .08       0  7352.2     .16       0
    7906     .12       0  8740.9     .12       0    8942     .16       0
  9324.7     .12       0  9721.4     .12       0 10687.8     .16       0
 11709.6     .05       0 12187.1     .16       0   12731     .08       0
Bank Sta=4775.9,5302.4
XS Rating Curve= 0 ,0
Exp/Cntr=0.3,0.1

Type RM Length L Ch R = 1 ,169957  ,5747,5747,5747
BEGIN DESCRIPTION:
LFC123
END DESCRIPTION:
XS GIS Cut Line= 4
      2883553.96      6992831.61      2882703.27      6989793.43
      2881731.04      6989289.96      2876696.35      6984741.37
#Sta/Elev= 30
  1354.5  403.89    2485  401.91  3560.3   361.4  3734.4  364.22    3749  364.04
  4026.5  358.12  4730.8  356.73  4789.1  340.38  4835.7  330.61  5278.5  340.35
  5352.2  355.67  5930.9  356.67  6073.9  348.65  6094.4  347.72  6790.8  344.44
  7281.5  342.42  7395.5  346.76  7565.7   345.9    7616  337.32  7750.5  334.35
  7785.6  345.57  7918.4  346.67  8312.2  340.65  8415.7  347.32  9520.8  340.45
 10566.8  347.29 10862.3  357.59 11122.9  368.44 11837.5  401.13 12389.5  422.67
#Mann= 19 ,-1 , 0
  1354.5     .05       0  3560.3     .08       0  3734.4      .1       0
    3749     .08       0  4026.5     .05       0  4789.1    .033       0
  5278.5     .05       0  6073.9     .12       0  6094.4     .16       0
  6790.8     .12       0  7281.5     .16       0  7395.5     .12       0
  7565.7     .16       0  7918.4     .05       0  8312.2     .12       0
 10566.8     .16       0 10862.3     .05       0 11122.9     .16       0
 11837.5     .05       0
Bank Sta=4789.1,5278.5
XS Rating Curve= 0 ,0
Exp/Cntr=0.3,0.1

Type RM Length L Ch R = 1 ,164210  ,5266,5266,5266
BEGIN DESCRIPTION:
LFC124
END DESCRIPTION:
XS GIS Cut Line= 4
      2884144.24      6989498.28      2882816.26      6986396.18
      2882321.32      6985730.93      2879404.69      6985348.99
#Sta/Elev= 30
  1625.6  394.89  1840.5  393.35  2131.4  368.18  2232.1  359.01  2314.5  356.58
  2339.6  350.97  2390.6  345.01  2608.2  344.15  4446.5  346.43  4512.5  341.63
  4935.1  344.95  4957.8  342.86  4964.1   339.8  4967.8  332.32  4976.3  330.32
  5015.3  332.59  5023.7  339.68  5038.3  342.88  5065.4  343.27  5666.1  345.48
  5695.3  335.62  5716.1   337.9  5724.4  344.46  5745.3  345.26  7701.3  340.42
  8034.2  349.76  8192.7  364.34  8201.7  365.67  8374.9  378.13  8770.7  385.93
#Mann= 8 ,-1 , 0
  1625.6     .16       0  2131.4     .12       0  2232.1     .16       0
  2339.6     .12       0  4935.1     .07       0  5065.4     .12       0
  8192.7     .16       0  8201.7     .05       0
Bank Sta=4935.1,5065.4
XS Rating Curve= 0 ,0
Exp/Cntr=0.3,0.1

Type RM Length L Ch R = 1 ,158944  ,2080,2080,2080
BEGIN DESCRIPTION:
LFC125
END DESCRIPTION:
XS GIS Cut Line= 4
      2885481.06      6988994.84      2884404.66      6987501.76
      2884061.57       6984184.8      2883415.07      6982935.79
#Sta/Elev= 30
  -175.3  396.21   -30.9  395.49   352.5   354.4     447  349.77  1873.2  339.82
  2084.3  343.34  3180.1  338.98  3330.9  343.44  3557.2  340.55  3612.4  344.68
    4286  342.77  4366.4  337.44  4456.9  343.63  4537.3  339.59  4647.9  343.73
  4778.6  343.81  4828.9  339.13  4939.5  342.04  4978.2  328.69  5001.2  328.69
  5026.5  337.83  5101.1  335.14  5153.7  342.26  5303.1  337.86  5374.7   341.1
  5832.2  351.28  5932.4   358.6  6043.9  369.14  6221.6  385.41  6406.4  388.15
#Mann= 9 ,-1 , 0
  -175.3     .05       0   -30.9     .16       0     447     .12       0
  4939.5     .07       0  5153.7     .12       0  5374.7     .05       0
  5832.2     .16       0  5932.4     .12       0  6043.9     .16       0
Bank Sta=4939.5,5153.7
XS Rating Curve= 0 ,0
Exp/Cntr=0.3,0.1

Type RM Length L Ch R = 1 ,156864  ,4747,4747,4747
BEGIN DESCRIPTION:
LFC126
END DESCRIPTION:
XS GIS Cut Line= 3
      2887182.44      6988178.87      2885466.59      6983149.72
      2883727.56      6982779.54
#Sta/Elev= 30
  -313.8  391.29  -126.7  377.41    70.7  354.41   122.8  358.61   165.8  351.45
   318.8  346.89  1102.3343.8208  1185.3   343.7  1502.9  343.62  1549.1  343.58
  1607.2  343.43  1711.4  343.36  1947.8  339.46  2186.4   340.2  2469.2   339.7
  2532.7  339.51  3537.8  341.26  3610.3  336.49  3683.9  341.27  4926.6  342.39
  4952.2  339.31  4953.3  330.02  4961.8  328.02  5195.9  341.96  5451.5  336.44
  5725.2345.3484  6005.6   369.3  6196.1   365.4  6710.8  386.64    6778  388.89
#Mann= 18 ,-1 , 0
  -313.8     .05       0  -126.7     .16       0   318.8     .12       0
  1102.3     .07       0  1185.3     .12       0  1502.9     .05       0
  1549.1     .07       0  1607.2     .05       0  1711.4     .12       0
  1947.8     .07       0  2186.4     .12       0  2469.2     .08       0
  2532.7     .12       0  4926.6     .07       0  5195.9     .12       0
  5725.2     .16       0  6005.6     .05       0  6710.8     .16       0
Bank Sta=4926.6,5195.9
XS Rating Curve= 0 ,0
Exp/Cntr=0.3,0.1

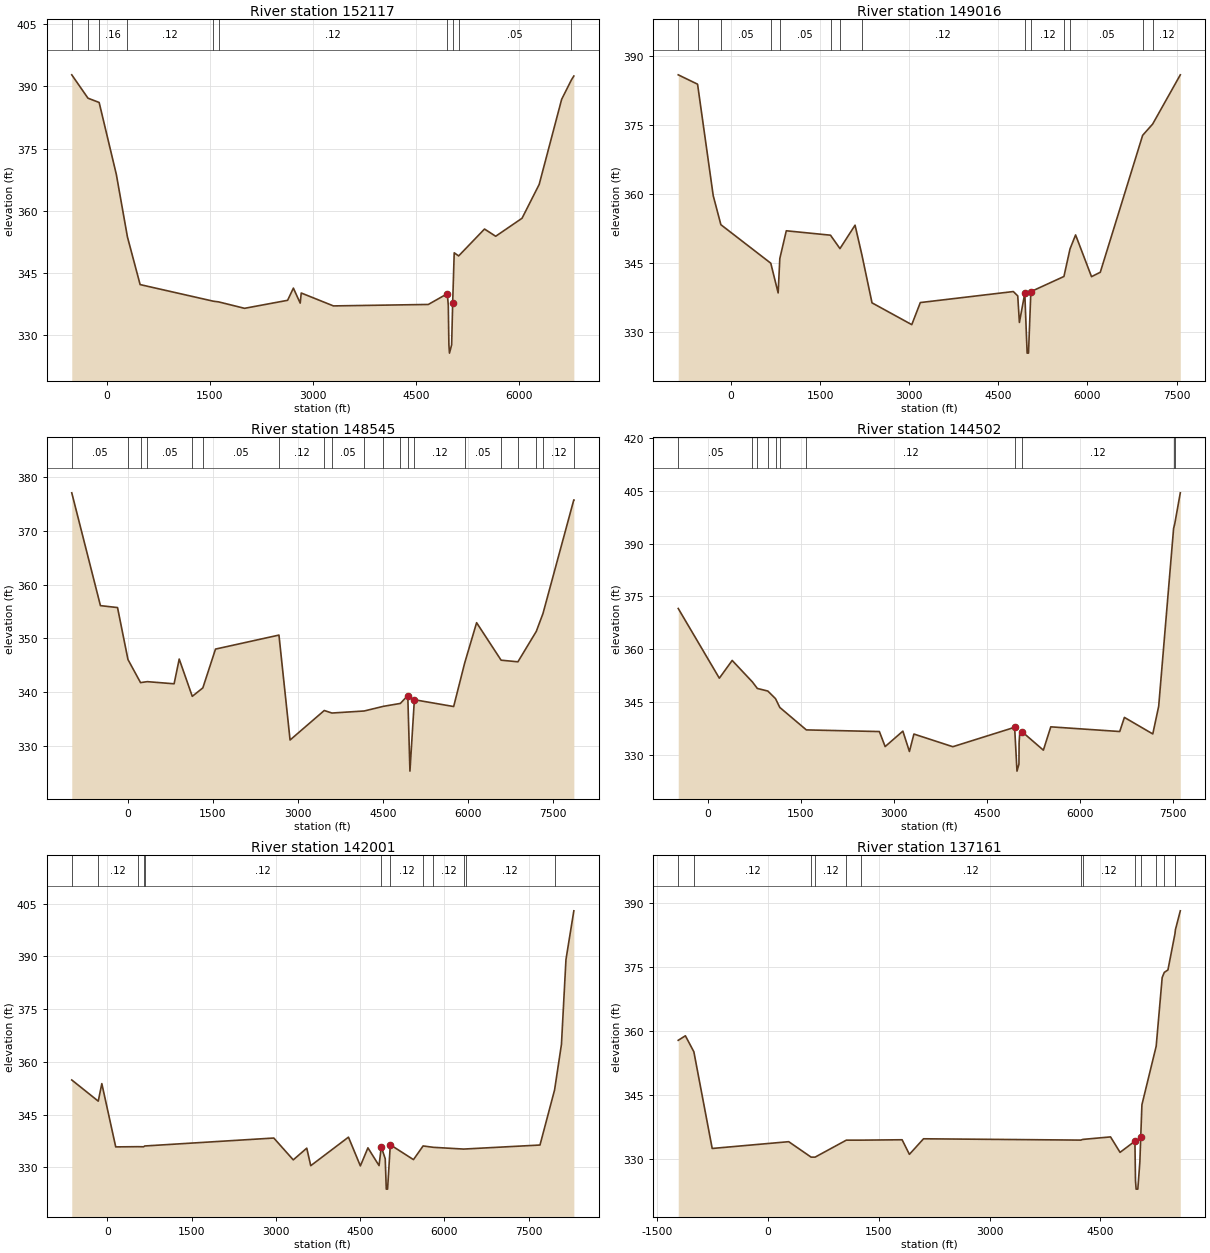
Type RM Length L Ch R = 1 ,152117  ,3101,3101,3101
BEGIN DESCRIPTION:
LFC127
END DESCRIPTION:
XS GIS Cut Line= 3
      2889526.18      6987102.43      2888102.57      6982362.87
      2886279.94      6980870.05
#Sta/Elev= 30
  -509.7  392.78  -273.8  387.15  -111.4  386.12   138.8  368.77   300.2  353.71
   484.9  342.22  1548.8  338.22  1627.2  338.05    2004   336.5  2630.5  338.43
  2714.6  341.37  2813.7  337.75  2828.9  340.19  3297.2  337.08  4677.7  337.43
    4954  340.02  4968.4  337.23  4977.1   327.7  4985.6   325.7  5017.1   327.7
  5032.2  337.86  5054.5  349.88  5119.1  349.13  5495.2  355.61  5658.1  353.87
  6041.4  358.21  6290.4  366.35  6617.7  386.88  6760.4  391.58    6795  392.49
#Mann= 10 ,-1 , 0
  -509.7     .16       0  -273.8     .12       0  -111.4     .16       0
   300.2     .12       0  1548.8     .07       0  1627.2     .12       0
    4954     .07       0  5032.2     .12       0  5119.1     .05       0
  6760.4     .16       0
Bank Sta=4954,5032.2
XS Rating Curve= 0 ,0
Exp/Cntr=0.3,0.1

Type RM Length L Ch R = 1 ,149016  ,471,471,471
BEGIN DESCRIPTION:
LFC128
END DESCRIPTION:
XS GIS Cut Line= 5
      2894890.76       6982571.2      2891748.41      6981668.43
      2891001.88      6981164.96      2889543.54      6981130.23
      2887060.92      6979793.44
#Sta/Elev= 30
    -886  385.94  -560.6   383.9  -297.2  359.62  -168.5  353.31   671.3  344.92
   795.1  338.45   823.4  345.94   932.4  351.98  1676.2  351.02  1835.5   348.1
  2089.3   353.2  2204.1  346.76  2374.6  336.29  3043.7  331.54  3187.6  336.35
  4752.4  338.75  4826.8   337.8  4854.6  332.02  4945.4  338.34  4984.9  325.34
  5007.9  325.34  5047.6  338.73    5604  342.03  5706.4  348.03  5800.3  351.08
  6068.1  341.99  6215.7  342.95  6928.3  372.76  7097.5  375.23  7562.3  385.94
#Mann= 14 ,-1 , 0
    -886     .05       0  -560.6     .16       0  -168.5     .05       0
   671.3     .12       0   823.4     .05       0  1676.2     .16       0
  1835.5     .05       0  2204.1     .12       0  4945.4     .07       0
  5047.6     .12       0    5604     .16       0  5706.4     .05       0
  6928.3     .16       0  7097.5     .12       0
Bank Sta=4945.4,5047.6
XS Rating Curve= 0 ,0
Exp/Cntr=0.3,0.1

Type RM Length L Ch R = 1 ,148545  ,4043,4043,4043
BEGIN DESCRIPTION:
LFC129
END DESCRIPTION:
XS GIS Cut Line= 6
      2895220.67      6982102.48      2893744.93      6981078.15
      2892078.27       6981147.6      2889856.04      6980783.01
      2888727.57      6980175.37      2887182.42       6979133.7
#Sta/Elev= 30
  -992.1  377.12  -486.1  356.09  -184.5  355.73       0  346.04   221.7  341.74
   340.4  341.92   814.2  341.52   904.3  346.13  1134.9  339.18  1321.6  340.76
  1544.9  347.99  2664.7   350.6  2860.8  331.04  3464.1  336.54  3599.7  336.07
  4168.9  336.45  4508.6  337.32  4807.7  337.86  4938.6  339.33  4976.6  325.24
  5054.9  338.55  5748.3  337.28  5942.9   345.4  6153.3  352.91  6585.8  345.92
  6882.4  345.62  7206.8  351.29  7324.4  354.61  7868.7   375.8  7869.5   375.8
#Mann= 20 ,-1 , 0
  -992.1     .05       0       0     .16       0   221.7     .05       0
   340.4     .05       0  1134.9     .12       0  1321.6     .05       0
  2664.7     .12       0  3464.1     .12       0  3599.7     .05       0
  4168.9     .12       0  4508.6     .07       0  4807.7     .12       0
  4938.6     .07       0  5054.9     .12       0  5942.9     .05       0
  6585.8     .16       0  6882.4     .12       0  7206.8     .07       0
  7324.4     .12       0  7868.7     .16       0
Bank Sta=4938.6,5054.9
XS Rating Curve= 0 ,0
Exp/Cntr=0.3,0.1

Type RM Length L Ch R = 1 ,144502  ,2501,2501,2501
BEGIN DESCRIPTION:
LFC130
END DESCRIPTION:
XS GIS Cut Line= 3
      2895359.55       6982050.4      2891088.68      6978664.96
      2888779.82      6977397.69
#Sta/Elev= 30
    -472  371.58   189.8  351.76   396.6  356.81   721.9   350.7   802.1  348.84
   970.1  348.11  1094.2  345.95    1163  343.45  1590.5  337.06  2766.5  336.59
  2859.5  332.32  3144.7  336.71  3250.4  330.92  3322.6  335.88    3949  332.28
  4944.3   337.8  4982.2  325.34  5013.7  327.34  5016.3  333.51  5025.9  335.99
    5062  336.57  5406.9   331.3  5526.3  337.93  6636.2   336.6  6711.8  340.61
  7168.5  335.91  7263.6  343.78  7503.7  394.35  7521.5  395.59  7611.7  404.46
#Mann= 11 ,-1 , 0
    -472     .05       0   721.9     .16       0   802.1     .05       0
   970.1     .16       0  1094.2     .05       0    1163     .16       0
  1590.5     .12       0  4944.3     .07       0    5062     .12       0
  7503.7     .16       0  7521.5     .12       0
Bank Sta=4944.3,5062
XS Rating Curve= 0 ,0
Exp/Cntr=0.3,0.1

Type RM Length L Ch R = 1 ,142001  ,4840,4840,4840
BEGIN DESCRIPTION:
LFC131
END DESCRIPTION:
XS GIS Cut Line= 3
      2895932.43       6981234.4      2892095.63      6977293.43
      2888675.52      6976928.85
#Sta/Elev= 30
    -636  354.87  -164.4  348.85  -100.8  353.83   146.7  335.84   545.4   335.9
   641.8  335.87   664.9   336.1  2961.3  338.36  3307.8  332.15  3548.3  335.48
    3619  330.49  4290.7  338.61  4502.8  330.43  4637.3  335.57  4835.2  330.52
  4874.9  335.84  4945.3  332.48    4964  323.83    4987  323.83  5035.8  336.44
  5448.1  332.22  5619.7  336.11  5801.4  335.72  6340.3  335.22    6377  335.25
  7700.8  336.37  7960.6  352.03    8083  364.98  8163.4  389.12  8303.7  402.97
#Mann= 12 ,-1 , 0
    -636     .05       0  -164.4     .12       0   545.4     .05       0
   641.8     .07       0   664.9     .12       0  4874.9     .07       0
  5035.8     .12       0  5619.7     .16       0  5801.4     .12       0
  6340.3     .16       0    6377     .12       0  7960.6     .16       0
Bank Sta=4874.9,5035.8
XS Rating Curve= 0 ,0
Exp/Cntr=0.3,0.1

Type RM Length L Ch R = 1 ,137161  ,6077,6077,6077
BEGIN DESCRIPTION:
LFC132
END DESCRIPTION:
XS GIS Cut Line= 4
      2897685.89      6980435.74      2896887.29      6978300.37
      2894751.88      6975765.65      2893675.48      6975227.45
#Sta/Elev= 30
 -1215.9  357.88   -1119  358.94 -1004.2  355.19    -756  332.53   279.6  334.12
     583   330.5   637.3   330.5    1060  334.48  1254.9  334.48    1815  334.57
  1913.8  331.15    2105   334.8  4235.5  334.49  4260.1  334.65  4637.2  335.24
  4765.8  331.62    4967  334.24  4974.9     325  4983.4     323  5006.4     323
  5034.1  329.36  5045.6  335.12    5062  342.78  5255.1   356.5  5336.3   372.6
  5364.6  373.79  5414.2  374.38  5509.6  382.88  5515.3   383.8  5581.7  388.23
#Mann= 14 ,-1 , 0
 -1215.9     .05       0 -1004.2     .12       0     583     .05       0
   637.3     .12       0    1060     .05       0  1254.9     .12       0
  4235.5     .07       0  4260.1     .12       0    4967     .07       0
  5045.6     .12       0  5255.1     .16       0  5364.6     .12       0
  5509.6     .16       0  5515.3     .12       0
Bank Sta=4967,5045.6
XS Rating Curve= 0 ,0
Exp/Cntr=0.3,0.1

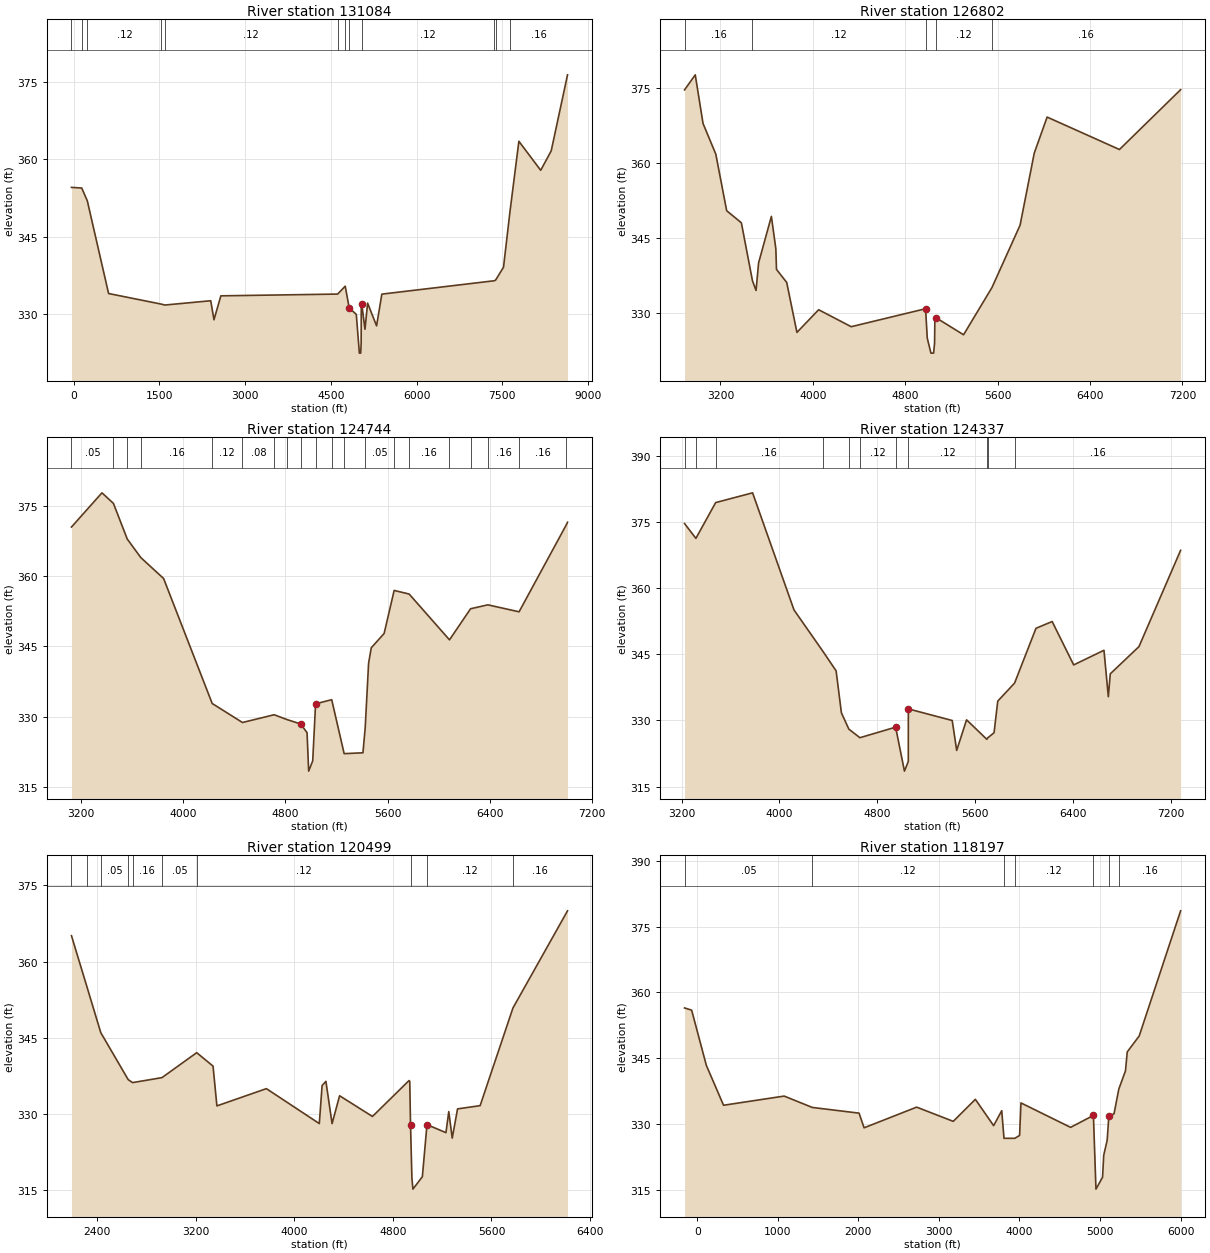
Type RM Length L Ch R = 1 ,131084  ,4282,4282,4282
BEGIN DESCRIPTION:
LFC133
END DESCRIPTION:
XS GIS Cut Line= 4
      2898293.54      6980453.15      2897998.41      6975783.01
      2897737.99      6975314.26       2895307.4      6972848.95
#Sta/Elev= 30
   -36.8  354.52   142.6   354.4   240.8  351.91   612.6  333.98  1536.7  331.92
  1598.3  331.75  2399.4  332.58  2456.3   328.9  2576.6  333.53  4619.6  333.87
  4752.4   335.4  4821.2  331.21  4945.9  329.93  4999.6  322.44  5022.6  322.44
  5031.1  324.44  5032.8  331.54  5040.8  331.96    5098  327.06  5143.7  332.12
  5300.7  327.72  5392.6  333.86  7360.4  336.45  7383.3  336.59  7521.1  339.07
  7632.7   349.7  7789.8  363.45  8171.6  357.83  8355.4  361.59  8640.9  376.31
#Mann= 12 ,-1 , 0
   -36.8     .05       0   142.6     .16       0   240.8     .12       0
  1536.7     .07       0  1598.3     .12       0  4619.6     .07       0
  4752.4     .12       0  4821.2     .07       0  5040.8     .12       0
  7360.4     .16       0  7383.3     .12       0  7632.7     .16       0
Bank Sta=4821.2,5040.8
XS Rating Curve= 0 ,0
Exp/Cntr=0.3,0.1

Type RM Length L Ch R = 1 ,126802  ,2058,2058,2058
BEGIN DESCRIPTION:
LFC134
END DESCRIPTION:
XS GIS Cut Line= 4
      2901106.03      6976807.28      2900133.82      6974932.32
      2899578.27      6973994.82      2899387.43      6972919.19
#Sta/Elev= 30
    2890   374.6  2982.7  377.61  3049.9   367.9  3160.5  361.77  3254.7  350.46
  3381.8  348.05  3477.9  336.47  3508.9  334.53  3531.1  340.05  3641.7  349.33
  3680.3  342.86  3685.9  338.74  3774.4  336.13  3862.9  326.15  4050.8  330.68
  4332.8  327.29  4976.5  330.88    4991  325.02  5022.9  322.01  5045.9  322.01
  5054.4  324.01    5057  329.06  5065.6   329.1  5305.4  325.68  5551.3  335.12
  5794.7  347.58  5917.4  361.98  6028.6  369.17  6654.8  362.69  7184.2  374.64
#Mann= 5 ,-1 , 0
    2890     .16       0  3477.9     .12       0  4976.5     .07       0
  5065.6     .12       0  5551.3     .16       0
Bank Sta=4976.5,5065.6
XS Rating Curve= 0 ,0
Exp/Cntr=0.3,0.1

Type RM Length L Ch R = 1 ,124744  ,407,407,407
BEGIN DESCRIPTION:
LFC135
END DESCRIPTION:
XS GIS Cut Line= 3
      2902460.22      6975583.38      2901587.82      6973929.71
      2900416.26      6972289.54
#Sta/Elev= 30
    3124  370.55  3362.7  377.87  3452.7  375.61  3560.9  367.99  3667.1  364.02
  3845.8  359.54  4226.2  332.81  4463.5  328.74  4711.6   330.4    4812  329.37
  4919.5  328.42  4969.2  326.56  4981.9  318.34  5013.5  320.54  5035.9  332.73
  5162.3  333.62  5259.8  322.08    5407  322.26  5424.8   327.7  5451.2  341.42
  5472.1  344.72  5572.9  347.79  5651.4  356.99  5768.9  356.22  6084.8  346.42
  6249.9  353.07  6385.2  353.91  6629.8  352.42  6996.7  370.87  7009.3  371.58
#Mann= 20 ,-1 , 0
    3124     .05       0  3452.7     .16       0  3560.9     .12       0
  3667.1     .16       0  4226.2     .12       0  4463.5     .08       0
  4711.6     .12       0    4812     .08       0  4919.5     .07       0
  5035.9     .08       0  5162.3     .08       0  5259.8     .05       0
  5424.8     .05       0  5651.4     .16       0  5768.9     .16       0
  6084.8     .05       0  6249.9      .1       0  6385.2     .16       0
  6629.8     .16       0  6996.7     .08       0
Bank Sta=4919.5,5035.9
XS Rating Curve= 0 ,0
Exp/Cntr=0.3,0.1

Type RM Length L Ch R = 1 ,124337  ,3838,3838,3838
BEGIN DESCRIPTION:
LFC136
END DESCRIPTION:
XS GIS Cut Line= 4
      2902824.81      6975544.32       2902017.5      6974125.03
      2901939.38      6973851.59      2900859.33       6972003.8
#Sta/Elev= 30
  3223.8  374.61  3316.6  371.25  3478.3  379.36  3780.3  381.57    4119  355.04
  4352.3  345.79  4463.5  341.24  4506.8  331.73  4567.6  328.04  4658.2  326.09
  4950.3  328.48  5022.5  318.52  5054.1  320.72  5054.3  332.62  5413.2  329.99
  5449.8  323.22  5530.6  330.14  5696.5  325.72  5703.1  326.04  5755.4  327.22
  5785.7  334.38  5923.3  338.47  6098.4  350.88  6230.7  352.41  6406.7  342.58
  6654.4   345.9  6690.2  335.38  6705.9  340.56  6940.7  346.73  7281.3  368.54
#Mann= 11 ,-1 , 0
  3223.8     .16       0  3316.6     .08       0  3478.3     .16       0
  4352.3     .12       0  4567.6     .16       0  4658.2     .12       0
  4950.3     .07       0  5054.3     .12       0  5696.5     .07       0
  5703.1     .12       0  5923.3     .16       0
Bank Sta=4950.3,5054.3
XS Rating Curve= 0 ,0
Exp/Cntr=0.3,0.1

Type RM Length L Ch R = 1 ,120499  ,2302,2302,2302
BEGIN DESCRIPTION:
LFC137
END DESCRIPTION:
XS GIS Cut Line= 3
      2903931.55      6974645.83      2902759.69      6972354.19
      2901496.67      6971638.05
#Sta/Elev= 30
  2191.6   365.1  2314.7  355.23  2429.4     346  2651.9  336.74  2687.5  336.15
  2926.1  337.13    3208  342.05  3340.5   339.4  3371.9  331.56  3773.5  334.96
    4203  328.08  4225.5  335.57  4256.6   336.4  4306.6  328.07  4367.6  333.56
  4634.2  329.48  4931.1  336.55  4936.9  336.41  4943.3  327.87  4954.4  317.36
  4962.7  315.16  5039.3  317.61  5076.8  327.87  5230.7  326.29  5253.7  330.44
  5281.6  325.21  5324.9  330.97  5508.1  331.61  5774.6  350.86  6217.4     370
#Mann= 10 ,-1 , 0
  2191.6     .12       0  2314.7     .16       0  2429.4     .05       0
  2651.9     .12       0  2687.5     .16       0  2926.1     .05       0
    3208     .12       0  4943.3     .07       0  5076.8     .12       0
  5774.6     .16       0
Bank Sta=4943.3,5076.8
XS Rating Curve= 0 ,0
Exp/Cntr=0.3,0.1

Type RM Length L Ch R = 1 ,118197  ,1962,1962,1962
BEGIN DESCRIPTION:
LFC138
END DESCRIPTION:
XS GIS Cut Line= 3
      2905038.35      6975023.51      2903462.82      6970401.07
      2902473.21      6969593.76
#Sta/Elev= 30
  -159.3  356.46   -71.2  355.96   111.5  343.37   325.1  334.28    1078  336.37
    1427  333.78  2007.8  332.48  2070.5  329.14  2723.4  333.85  3177.6  330.61
  3452.3  335.63  3679.3  329.63  3779.8  333.04    3808  326.74  3941.5  326.74
  4001.7   327.4  4018.8  334.81  4635.2  329.24  4918.6  331.96  4950.1  315.16
  5032.1  317.87  5046.4  322.87  5089.5  326.33  5110.3  331.88  5174.3  332.31
  5233.8  337.96  5316.4   342.1  5338.7  346.44  5487.3  350.08  6001.4   378.6
#Mann= 7 ,-1 , 0
  -159.3     .05       0    1427     .12       0    3808     .05       0
  3941.5     .12       0  4918.6     .07       0  5110.3     .12       0
  5233.8     .16       0
Bank Sta=4918.6,5110.3
XS Rating Curve= 0 ,0
Exp/Cntr=0.3,0.1

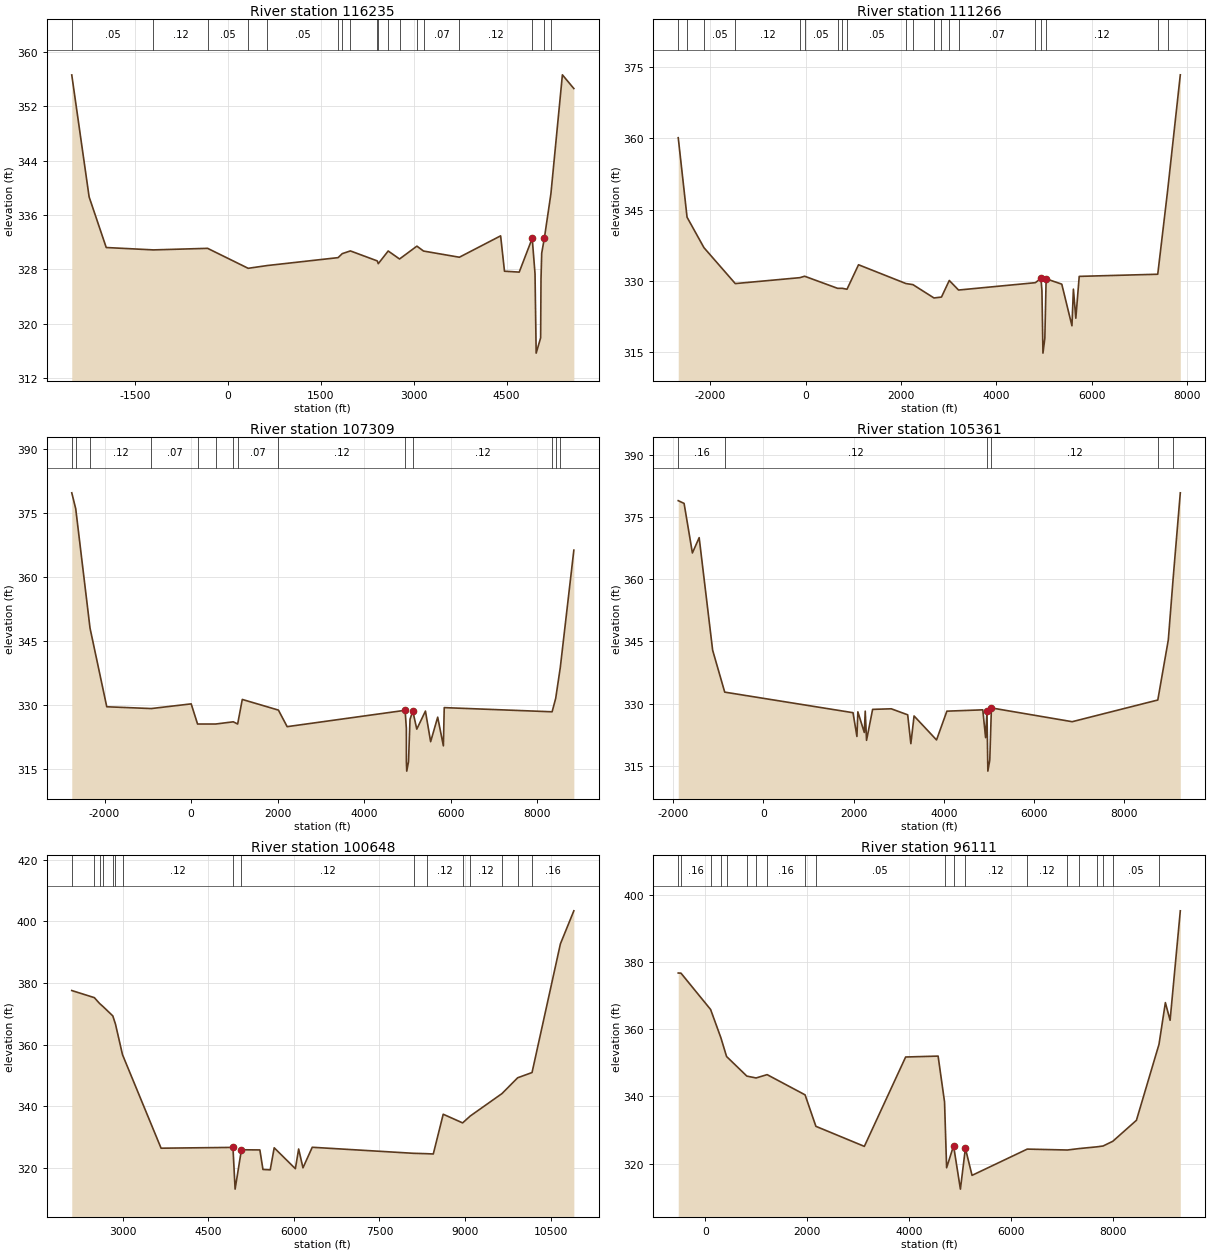
Type RM Length L Ch R = 1 ,116235  ,4969,4969,4969
BEGIN DESCRIPTION:
LFC139
END DESCRIPTION:
XS GIS Cut Line= 3
        2906080.      6975205.72      2905207.61      6969125.03
      2903436.73      6968278.65
#Sta/Elev= 30
 -2519.6  356.64 -2239.5  338.69 -1963.2  331.23   -1202  330.88  -326.7  331.11
   328.5  328.17   639.5  328.58  1780.1 329.742  1847.4  330.33  1978.5  330.73
  2412.5  329.26  2428.7  328.85  2588.9  330.72    2772  329.54  3052.2 331.433
  3159.8  330.71  3738.1   329.8    4404  332.95  4466.5  327.74  4704.3  327.61
    4914  332.59  4959.3  327.37  4977.9  315.68    5050  317.93    5056  326.63
  5067.1  330.39  5111.4  332.68  5216.1  339.17  5401.3  356.66  5586.1  354.64
#Mann= 18 ,-1 , 0
 -2519.6     .05       0   -1202     .12       0  -326.7     .05       0
   328.5     .12       0   639.5     .05       0  1780.1     .07       0
  1847.4     .05       0  1978.5     .12       0  2412.5     .07       0
  2428.7     .12       0  2588.9     .05       0    2772     .07       0
  3052.2     .05       0  3159.8     .07       0  3738.1     .12       0
    4914     .07       0  5111.4     .12       0  5216.1     .16       0
Bank Sta=4914,5111.4
XS Rating Curve= 0 ,0
Exp/Cntr=0.3,0.1

Type RM Length L Ch R = 1 ,111266  ,3957,3957,3957
BEGIN DESCRIPTION:
LFC140
END DESCRIPTION:
XS GIS Cut Line= 4
      2906757.08      6975661.46      2905962.82      6968213.57
      2906132.09      6967223.98      2904725.83      6965765.64
#Sta/Elev= 30
 -2666.8  360.16 -2481.8   343.4 -2127.5  336.98 -1471.6  329.41  -117.2  330.66
   -18.5  330.96   672.1  328.41   770.7  328.41   869.4  328.22    1111  333.38
  2103.7  329.42  2250.6  329.19  2691.6  326.38  2849.1  326.57  3012.5  330.07
  3206.7  328.05  4815.8   329.6  4933.5  330.52  4953.8  327.92  4975.3  314.75
  5014.6  317.85  5041.9  330.42  5369.7  329.29  5582.8  320.51  5613.2  328.24
  5663.9  322.11  5734.9  330.93  7380.4  331.38  7585.7  348.86  7853.2  373.42
#Mann= 20 ,-1 , 0
 -2666.8     .05       0 -2481.8     .16       0 -2127.5     .05       0
 -1471.6     .12       0  -117.2     .16       0   -18.5     .05       0
   672.1     .12       0   770.7     .07       0   869.4     .05       0
  2103.7     .12       0  2250.6     .07       0  2691.6     .07       0
  2849.1     .12       0  3012.5     .07       0  3206.7     .07       0
  4815.8     .05       0  4933.5     .07       0  5041.9     .12       0
  7380.4     .16       0  7585.7     .05       0
Bank Sta=4933.5,5041.9
XS Rating Curve= 0 ,0
Exp/Cntr=0.3,0.1

Type RM Length L Ch R = 1 ,107309  ,1948,1948,1948
BEGIN DESCRIPTION:
LFC141
END DESCRIPTION:
XS GIS Cut Line= 4
       2909938.5      6974962.65       2908224.1      6967605.93
      2907573.06      6966802.98       2904795.3      6965631.11
#Sta/Elev= 30
 -2757.9  379.74 -2666.7  376.02 -2336.3     348 -1949.1  329.51  -920.8  329.09
     1.8  330.19     149  325.46   567.7  325.46   974.5  325.98  1075.5  325.46
  1182.6  331.23  2017.4  328.73  2219.6  324.84  4945.3  328.68    4974  324.44
  4974.8   316.6  4983.2   314.4  5023.6   316.6  5058.8  326.56  5122.7   328.5
  5215.4  324.26  5415.1   328.5  5535.1  321.31  5698.3  327.07  5829.7  320.33
  5849.3  329.31  8342.4  328.33  8425.1  331.49  8531.6  338.75  8844.5  366.28
#Mann= 14 ,-1 , 0
 -2757.9     .05       0 -2666.7     .16       0 -2336.3     .12       0
  -920.8     .07       0     149     .12       0   567.7     .07       0
   974.5     .12       0  1075.5     .07       0  2017.4     .12       0
  4945.3     .07       0  5122.7     .12       0  8342.4     .16       0
  8425.1      .1       0  8531.6     .05       0
Bank Sta=4945.3,5122.7
XS Rating Curve= 0 ,0
Exp/Cntr=0.3,0.1

Type RM Length L Ch R = 1 ,105361  ,4713,4713,4713
BEGIN DESCRIPTION:
LFC142
END DESCRIPTION:
XS GIS Cut Line= 3
      2912803.08      6971208.34      2908636.43      6965956.62
      2904469.86      6964480.97
#Sta/Elev= 30
 -1886.3  378.96 -1756.7   378.3 -1572.5  366.35 -1422.5  370.04 -1123.8  342.89
  -856.3  332.79  1986.1  327.83  2072.7   322.1  2093.5  328.04  2236.1  323.06
  2256.9   328.2  2285.8  321.17  2420.3  328.63  2833.7  328.77  3197.5  327.32
  3267.9  320.36  3338.9  327.04  3836.7  321.26  4065.9   328.2  4861.5  328.52
  4923.5  321.81  4954.4  328.18  4973.7  313.74  5016.2  316.39  5052.4  328.98
  6842.1  325.66  8739.1  330.89  8971.7  345.39  9081.8   360.6  9237.7  380.85
#Mann= 6 ,-1 , 0
 -1886.3     .16       0  -856.3     .12       0  4954.4     .07       0
  5052.4     .12       0  8739.1     .05       0  9081.8     .16       0
Bank Sta=4954.4,5052.4
XS Rating Curve= 0 ,0
Exp/Cntr=0.3,0.1

Type RM Length L Ch R = 1 ,100648  ,4537,4537,4537
BEGIN DESCRIPTION:
LFC143
END DESCRIPTION:
XS GIS Cut Line= 3
      2912607.78      6966564.26      2910502.75      6964394.12
      2905229.65      6962050.52
#Sta/Elev= 30
  2110.2  377.53  2505.8  375.22  2596.6  373.34  2663.8  372.23  2828.8   369.3
  2875.6  366.64  2999.1   356.7  3674.5  326.37  4933.4  326.63  4971.1  313.09
  5081.8  325.86  5404.7  325.81  5458.9  319.47  5586.1  319.34  5655.8   326.5
  6026.5  319.72    6084  326.11  6159.8     320    6322  326.67  8097.6  324.71
  8323.8  324.59  8442.2  324.49    8616  337.39  8955.8  334.58  9090.8  336.83
  9645.7   344.1  9919.9  349.22 10171.8  350.92 10668.3  392.65   10904  403.39
#Mann= 16 ,-1 , 0
  2110.2     .05       0  2505.8     .16       0  2596.6     .12       0
  2663.8     .16       0  2828.8     .12       0  2875.6     .16       0
  2999.1     .12       0  4933.4     .07       0  5081.8     .12       0
  8097.6     .07       0  8323.8     .12       0  8955.8     .16       0
  9090.8     .12       0  9645.7     .16       0  9919.9     .12       0
 10171.8     .16       0
Bank Sta=4933.4,5081.8
XS Rating Curve= 0 ,0
Exp/Cntr=0.3,0.1

Type RM Length L Ch R = 1 ,96111   ,676,676,676
BEGIN DESCRIPTION:
LFC144
END DESCRIPTION:
XS GIS Cut Line= 6
      2913627.75      6966477.46      2913389.03      6964502.63
      2912347.36      6963721.38       2911327.4       6962462.7
      2909113.86       6960835.1      2907724.98       6959142.4
#Sta/Elev= 30
    -533  376.71  -479.1  376.67   102.6  365.86   305.9  357.38   415.6  351.89
     814  346.06   995.2  345.51  1211.5   346.5  1956.4  340.49  2168.9  331.13
  3119.9  325.17  3930.4  351.74  4567.5  352.01  4693.8  338.38  4734.5  318.81
    4871  325.36  5005.1  312.46    5103   324.6  5233.2  316.55    6317  324.36
  7104.5  324.09  7336.4  324.52  7681.7  325.03  7805.5  325.28  7996.4  326.69
  8459.7  332.92  8902.9  355.52  9028.1  367.91  9120.6  362.66  9321.1   395.2
#Mann= 20 ,-1 , 0
    -533     .05       0  -479.1     .16       0   102.6     .16       0
   305.9     .16       0   415.6     .12       0     814     .16       0
   995.2     .12       0  1211.5     .16       0  1956.4     .12       0
  2168.9     .05       0  4693.8     .12       0    4871     .07       0
    5103     .12       0    6317     .12       0  7104.5     .07       0
  7336.4     .12       0  7681.7     .05       0  7805.5     .08       0
  7996.4     .05       0  8902.9     .16       0
Bank Sta=4871,5103
XS Rating Curve= 0 ,0
Exp/Cntr=0.3,0.1