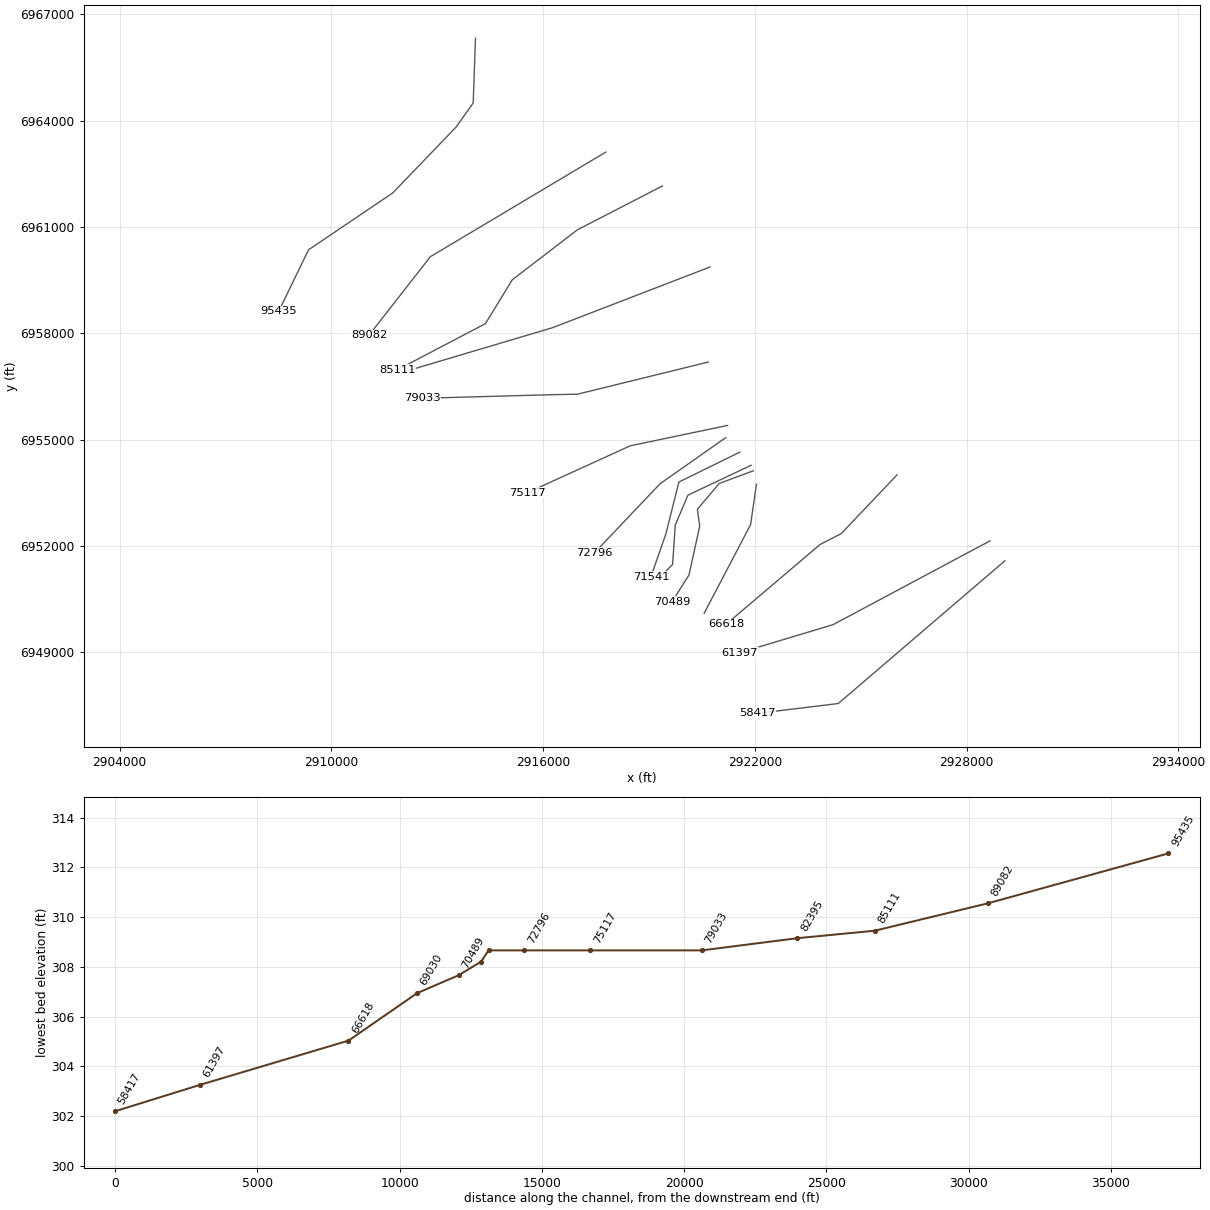
HEC-RAS study Lake Fork Creek.prj: Lake Fork Creek Base Level Engineering

--- Lake Fork Creek.g01 (geometry) --- (continued)

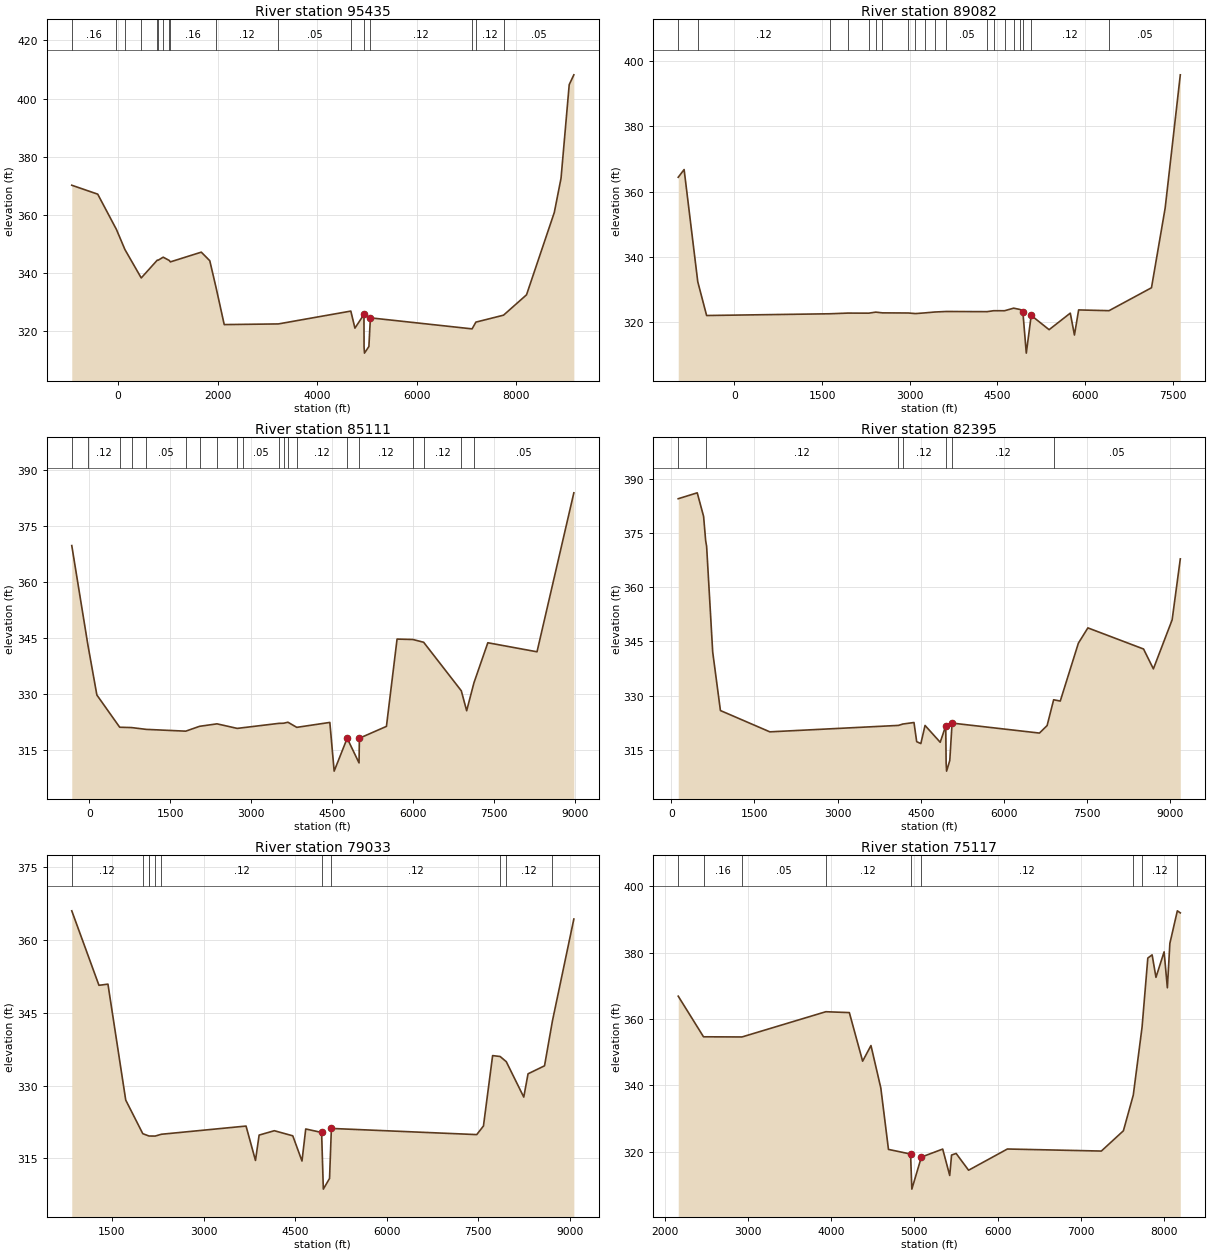
Type RM Length L Ch R = 1 ,95435   ,6353,6353,6353
BEGIN DESCRIPTION:
LFC145
END DESCRIPTION:
XS GIS Cut Line= 6
      2914083.48      6966325.58      2914018.37      6964502.63
      2913540.94      6963829.89      2911739.73      6961963.57
      2909352.57      6960357.66       2908506.2      6958621.52
#Sta/Elev= 30
  -924.9  370.23    -404  367.16   -28.7  355.04   142.3  348.13   469.5  338.38
   791.9  344.51   809.5  344.48   909.5  345.51  1031.5  344.39  1054.3   343.9
  1674.5  347.24  1844.9   344.3  1972.4  334.96  2134.8  322.36    3221  322.59
  4675.5     327    4758  321.14  4939.1  325.86  4941.1  314.76  4949.4  312.56
  5038.1  314.83  5068.1  324.68    7109  320.89  7185.5  323.21  7739.9  325.59
  8201.6  332.59  8759.1  360.87  8894.4  372.64  9058.4  404.77  9151.3  408.15
#Mann= 17 ,-1 , 0
  -924.9     .16       0   -28.7      .1       0   142.3     .16       0
   469.5     .07       0   791.9     .16       0   809.5     .05       0
   909.5     .07       0  1031.5     .05       0  1054.3     .16       0
  1972.4     .12       0    3221     .05       0  4675.5     .12       0
  4939.1     .07       0  5068.1     .12       0    7109     .05       0
  7185.5     .12       0  7739.9     .05       0
Bank Sta=4939.1,5068.1
XS Rating Curve= 0 ,0
Exp/Cntr=0.3,0.1

Type RM Length L Ch R = 1 ,89082   ,3971,3971,3971
BEGIN DESCRIPTION:
LFC146
END DESCRIPTION:
XS GIS Cut Line= 3
      2917772.67      6963113.72      2912803.09      6960162.35
      2911067.45      6957949.41
#Sta/Elev= 30
    -961  364.41  -860.3  366.77  -626.7  332.41  -475.2  322.07  1631.8   322.6
  1938.8  322.81  2300.5  322.79  2419.9  323.11  2533.8  322.88  2976.1  322.84
  3098.6  322.66  3264.3  322.88  3427.1  323.14  3626.6   323.3  4324.6  323.25
  4438.2  323.54    4624  323.53    4779  324.32  4889.6  323.91  4936.8  323.22
  4995.6  310.55  5079.6   322.1  5386.1  317.73  5748.6   322.8  5819.5   316.1
  5891.4  323.78  6411.6  323.55    7138  330.57  7372.1  354.98  7631.3  395.78
#Mann= 20 ,-1 , 0
    -961     .16       0  -626.7     .12       0  1631.8     .07       0
  1938.8     .07       0  2300.5     .05       0  2419.9     .07       0
  2533.8     .05       0  2976.1     .07       0  3098.6     .07       0
  3264.3     .07       0  3427.1     .05       0  3626.6     .05       0
  4324.6     .12       0  4438.2     .07       0    4624     .07       0
    4779     .05       0  4889.6     .12       0  4936.8     .07       0
  5079.6     .12       0  6411.6     .05       0
Bank Sta=4936.8,5079.6
XS Rating Curve= 0 ,0
Exp/Cntr=0.3,0.1

Type RM Length L Ch R = 1 ,85111   ,2716,2716,2716
BEGIN DESCRIPTION:
LFC147
END DESCRIPTION:
XS GIS Cut Line= 5
       2919378.6      6962158.87      2916969.76       6960921.9
      2915125.14      6959511.31      2914365.59      6958274.33
      2911869.94      6956972.25
#Sta/Elev= 30
  -323.7  369.84   -26.4  343.34   141.2  329.83   563.7   321.2   783.4  321.11
  1053.6  320.63  1786.5  320.15  2043.7  321.45  2365.7  322.11    2740  320.89
  2848.2  321.08  3512.8  322.24  3597.4  322.27    3679  322.54  3842.4  321.17
  4454.7  322.49  4534.8  309.45  4775.9  318.25  4995.4  311.65    5002  318.26
  5502.8  321.43  5699.5   344.8  5993.6  344.69  6191.9  343.95    6889  330.96
  6988.2  325.62  7123.1   333.1  7380.1  343.82  8290.9   341.4  8972.8  383.96
#Mann= 20 ,-1 , 0
  -323.7     .16       0   -26.4     .12       0   563.7     .07       0
   783.4     .12       0  1053.6     .05       0  1786.5     .05       0
  2043.7     .07       0  2365.7     .05       0    2740     .12       0
  2848.2     .05       0  3512.8     .07       0  3597.4     .08       0
    3679     .07       0  3842.4     .12       0  4775.9     .07       0
    5002     .12       0  5993.6     .16       0  6191.9     .12       0
    6889     .16       0  7123.1     .05       0
Bank Sta=4775.9,5002
XS Rating Curve= 0 ,0
Exp/Cntr=0.3,0.1

Type RM Length L Ch R = 1 ,82395   ,3362,3362,3362
BEGIN DESCRIPTION:
LFC148
END DESCRIPTION:
XS GIS Cut Line= 3
      2920728.54      6959873.27      2916269.99      6958161.39
      2912169.59      6956947.88
#Sta/Elev= 30
   126.7  384.46   469.3  386.09     584  379.58   621.3  372.84   638.7  371.27
     748  342.09   887.4   325.9  1778.3  320.01  4097.2  321.79  4175.9  322.17
  4377.1  322.59  4425.9  317.29  4500.9  316.77  4576.5  321.78  4849.9  317.13
  4949.5  321.67  4956.8  311.35  4965.1  309.15  5022.5  312.09  5064.2  322.43
  6639.2  319.67  6777.4  321.75  6895.2  328.88  7014.4  328.52  7340.9  344.52
  7512.5  348.75  8516.1  342.91  8693.4  337.42  9031.4  350.97  9178.8  367.83
#Mann= 7 ,-1 , 0
   126.7     .16       0   621.3     .12       0  4097.2     .08       0
  4175.9     .12       0  4949.5     .07       0  5064.2     .12       0
  6895.2     .05       0
Bank Sta=4949.5,5064.2
XS Rating Curve= 0 ,0
Exp/Cntr=0.3,0.1

Type RM Length L Ch R = 1 ,79033   ,3916,3916,3916
BEGIN DESCRIPTION:
LFC149
END DESCRIPTION:
XS GIS Cut Line= 4
      2920677.49      6957190.47      2916972.63      6956283.42
      2916282.76      6956270.65      2912565.13      6956168.44
#Sta/Elev= 30
   840.9  365.98  1286.2  350.64  1433.5  350.88  1724.8     327  2004.3  320.08
  2105.7   319.6  2105.8   319.6    2207  319.59  2308.4  319.96  3695.3  321.65
  3849.7  314.57  3909.5  319.79  4158.6  320.69  4460.8  319.64  4611.6  314.45
  4672.8  321.05  4932.9  320.33  4961.2  308.66  5062.9  310.86  5092.9  321.16
  7473.7  319.89  7583.8  321.67  7733.8  336.16  7856.3  335.98  7957.6  334.91
    8244  327.62    8314  332.41  8584.1  334.06  8713.6  343.31  9064.2  364.29
#Mann= 11 ,-1 , 0
   840.9     .12       0  2004.3     .05       0  2105.7     .07       0
  2105.8     .05       0    2207     .07       0  2308.4     .12       0
  4932.9     .07       0  5092.9     .12       0  7856.3     .16       0
  7957.6     .12       0  8713.6     .05       0
Bank Sta=4932.9,5092.9
XS Rating Curve= 0 ,0
Exp/Cntr=0.3,0.1

Type RM Length L Ch R = 1 ,75117   ,2321,2321,2321
BEGIN DESCRIPTION:
LFC150
END DESCRIPTION:
XS GIS Cut Line= 3
      2921226.79      6955401.92      2918467.34      6954827.04
      2915543.53      6953499.19
#Sta/Elev= 30
  2164.4  366.85    2468   354.6  2930.1  354.55  3936.7  362.16  4219.4   361.9
    4379  347.25  4479.1  351.96  4597.3  339.18  4689.3  320.64  4954.8  319.24
    4970  308.66  5084.5  318.32  5340.6  320.74    5425  312.78    5447  318.94
  5501.9  319.42  5651.6  314.36  6117.5  320.76  7245.9  320.14  7510.7  326.25
  7629.6  337.03  7734.8  357.47  7804.1  378.34  7855.7  379.32  7901.9  372.53
  7999.7  380.22  8038.9  369.38  8068.9  382.77  8158.7  392.59  8194.3  391.97
#Mann= 9 ,-1 , 0
  2164.4     .05       0    2468     .16       0  2930.1     .05       0
  3936.7     .12       0  4954.8     .07       0  5084.5     .12       0
  7629.6     .16       0  7734.8     .12       0  8158.7     .16       0
Bank Sta=4954.8,5084.5
XS Rating Curve= 0 ,0
Exp/Cntr=0.3,0.1

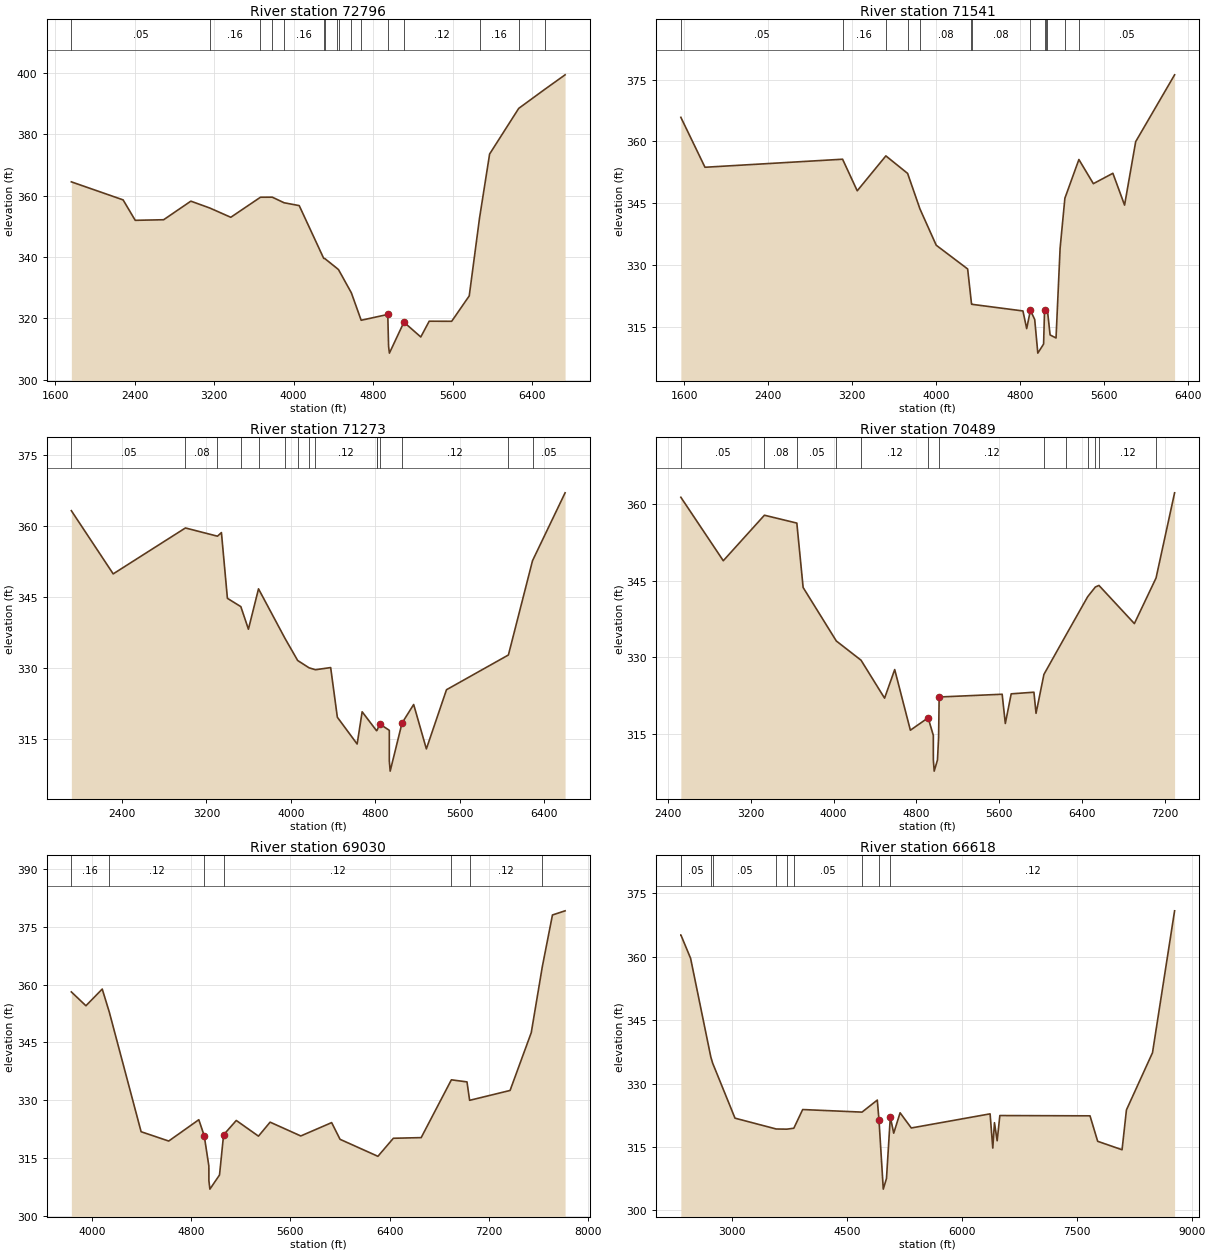
Type RM Length L Ch R = 1 ,72796   ,1255,1255,1255
BEGIN DESCRIPTION:
Mapping XS df733bc2
END DESCRIPTION:
XS GIS Cut Line= 3
      2921175.85      6955059.36      2919313.83      6953757.25
      2917451.85      6951804.12
#Sta/Elev= 30
  1761.8  364.54  2282.8  358.66  2404.9  351.99  2690.9  352.18  2964.7  358.24
  3153.8  356.03  3366.8  352.98  3665.7  359.52  3784.6  359.54  3903.5  357.72
  4055.9  356.79  4302.4  339.57  4313.9   339.5  4440.7  336.21  4452.2  335.86
  4580.8  328.33  4679.5  319.38  4947.3  321.28  4955.6  310.86  4963.8  308.66
  5109.9  318.76  5279.7  313.93  5364.3  319.07  5590.8  319.05  5767.5  327.34
    5871  352.71  5972.6  373.62  6265.6  388.51  6526.4  394.69  6732.4  399.46
#Mann= 16 ,-1 , 0
  1761.8     .05       0  3153.8     .16       0  3665.7     .12       0
  3784.6     .08       0  3903.5     .16       0  4302.4     .05       0
  4313.9     .12       0  4440.7     .05       0  4452.2     .16       0
  4580.8     .05       0  4679.5     .12       0  4947.3     .07       0
  5109.9     .12       0    5871     .16       0  6265.6     .12       0
  6526.4     .05       0
Bank Sta=4947.3,5109.9
XS Rating Curve= 0 ,0
Exp/Cntr=0.3,0.1

Type RM Length L Ch R = 1 ,71541   ,268,268,268
BEGIN DESCRIPTION:
LFC151
END DESCRIPTION:
XS GIS Cut Line= 4
      2921571.76      6954648.19      2919847.08      6953805.01
      2919476.59      6952335.85      2919055.02      6951135.01
#Sta/Elev= 30
  1569.3  365.85  1799.4  353.74  3111.4  355.69    3251  348.03    3524   356.5
  3731.3  352.25  3849.5   343.6  4004.2  334.83  4303.8  329.07  4340.4320.6604
    4342320.5071  4830.8  318.89  4866.7  314.61    4902  319.05  4943.2  316.81
  4972.7  308.66  5027.9  310.86  5036.9  319.12  5052.5 319.429  5064.4319.0625
  5089.9  313.07  5146.5  312.33  5185.3  334.09  5230.8346.2204  5364.4  355.62
  5502.5  349.76  5688.5  352.28    5800  344.56    5906  359.96  6276.9  376.16
#Mann= 13 ,-1 , 0
  1569.3     .05       0  3111.4     .16       0    3524     .08       0
  3731.3     .05       0  3849.5     .08       0  4340.4      .1       0
    4342     .08       0    4902     .07       0  5036.9      .1       0
  5052.5     .08       0  5064.4     .12       0  5230.8     .16       0
  5364.4     .05       0
Bank Sta=4902,5036.9
XS Rating Curve= 0 ,0
Exp/Cntr=0.3,0.1

Type RM Length L Ch R = 1 ,71273   ,784,784,784
BEGIN DESCRIPTION:
LFC152
END DESCRIPTION:
XS GIS Cut Line= 5
       2921891.1      6954277.68      2920102.58      6953434.53
      2919744.87      6952591.36      2919668.22       6951479.9
      2919196.93      6951008.61
#Sta/Elev= 30
  1921.6  363.27  2317.8  349.91  3001.4  359.62  3304.9  357.88  3342.3  358.64
  3398.9  344.74  3526.2  342.98  3597.7  338.21  3693.3  346.75  3943.7  336.28
  4064.2  331.59  4171.6  330.05  4232.4  329.64  4376.3   330.1  4439.6   319.6
    4627  313.93  4674.4  320.75  4810.9  316.74  4815.7316.8596  4841.2  318.16
  4931.4  316.83  4931.5   310.4  4939.7   308.2  5051.7  318.36    5162  322.29
  5282.3   312.9  5472.7  325.41  6058.9  332.76  6287.3  352.71  6595.4  367.05
#Mann= 15 ,-1 , 0
  1921.6     .05       0  3001.4     .08       0  3304.9     .05       0
  3526.2     .16       0  3693.3     .12       0  3943.7     .16       0
  4064.2     .12       0  4171.6     .16       0  4232.4     .12       0
  4810.9      .1       0  4815.7     .12       0  4841.2     .07       0
  5051.7     .12       0  6058.9     .08       0  6287.3     .05       0
Bank Sta=4841.2,5051.7
XS Rating Curve= 0 ,0
Exp/Cntr=0.3,0.1

Type RM Length L Ch R = 1 ,70489   ,1459,1459,1459
BEGIN DESCRIPTION:
Mapping XS b495ea7e
END DESCRIPTION:
XS GIS Cut Line= 6
      2921955.77      6954122.19      2920990.08      6953764.13
      2920371.59      6953037.13       2920436.7       6952559.7
      2920132.88      6951181.66      2919655.42      6950429.81
#Sta/Elev= 30
  2524.1  361.34  2934.3   348.9  3331.8  357.82  3645.3  356.28  3706.2  343.65
  4026.9  333.17    4266   329.4  4493.6  321.96  4591.4  327.57  4742.8  315.68
  4914.4  318.11  4964.8  314.67    4965  309.86  4973.3  307.66    5005  309.86
  5015.7  314.27  5021.1  322.19  5630.2  322.73  5660.8     317  5717.6  322.81
  5937.3  323.13  5957.8  318.99    6034  326.62  6251.7  334.49  6457.3  341.86
  6531.3  343.75    6566  344.06  6908.4  336.58    7118  345.52  7297.2  362.21
#Mann= 13 ,-1 , 0
  2524.1     .05       0  3331.8     .08       0  3645.3     .05       0
  4026.9     .16       0    4266     .12       0  4914.4     .07       0
  5021.1     .12       0    6034     .16       0  6251.7      .1       0
  6457.3     .16       0  6531.3      .1       0    6566     .12       0
    7118     .16       0
Bank Sta=4914.4,5021.1
XS Rating Curve= 0 ,0
Exp/Cntr=0.3,0.1

Type RM Length L Ch R = 1 ,69030   ,2412,2412,2412
BEGIN DESCRIPTION:
LFC153
END DESCRIPTION:
XS GIS Cut Line= 3
      2922044.43      6953741.14      2921878.35      6952604.13
      2920562.51       6950100.2
#Sta/Elev= 30
  3835.8  358.09  3953.2   354.5  4084.6  358.83  4141.5  352.86  4397.8  321.83
  4620.2  319.41  4862.7  324.94  4906.2   320.8  4943.6  312.93  4943.8  309.14
    4952  306.94  5029.5  310.61  5062.3  321.02  5164.6  324.75  5343.3  320.68
  5437.1  324.31  5684.3  320.73  5932.8  324.19  6000.6  319.86  6305.6  315.45
  6429.9  320.13  6654.1   320.3  6897.4  335.29  7023.2  334.75  7044.4  329.97
  7370.3  332.53    7541  347.53  7629.9  364.61  7711.7  378.04  7813.5  379.12
#Mann= 7 ,-1 , 0
  3835.8     .16       0  4141.5     .12       0  4906.2     .07       0
  5062.3     .12       0  6897.4     .16       0  7044.4     .12       0
  7629.9     .16       0
Bank Sta=4906.2,5062.3
XS Rating Curve= 0 ,0
Exp/Cntr=0.3,0.1

Type RM Length L Ch R = 1 ,66618   ,5221,5221,5221
BEGIN DESCRIPTION:
LFC154
END DESCRIPTION:
XS GIS Cut Line= 4
      2926030.34      6954009.43      2924446.19      6952348.62
      2923845.75      6952042.02      2921189.21      6949794.18
#Sta/Elev= 30
  2327.1  365.13  2327.7  365.13  2454.3  359.61  2718.2   336.3  2742.7  334.81
  3034.3  321.81  3572.6  319.25  3710.9  319.21  3802.5  319.43  3918.4  323.85
  4693.5  323.24  4893.1  326.09  4915.5  321.26  4971.2  305.03    5013  307.55
  5063.1  322.09  5107.5  318.26  5190.8  323.08  5336.9  319.49  6366.4  322.83
  6401.6  314.74  6423.6  320.74  6458.7  316.46  6493.8  322.43  7671.6  322.36
  7771.6  316.34  8090.2  314.34  8147.4  323.76  8487.9  337.29  8776.4  370.84
#Mann= 10 ,-1 , 0
  2327.1     .16       0  2327.7     .05       0  2718.2     .08       0
  2742.7     .05       0  3572.6     .07       0  3710.9     .12       0
  3802.5     .05       0  4693.5     .12       0  4915.5     .07       0
  5063.1     .12       0
Bank Sta=4915.5,5063.1
XS Rating Curve= 0 ,0
Exp/Cntr=0.3,0.1

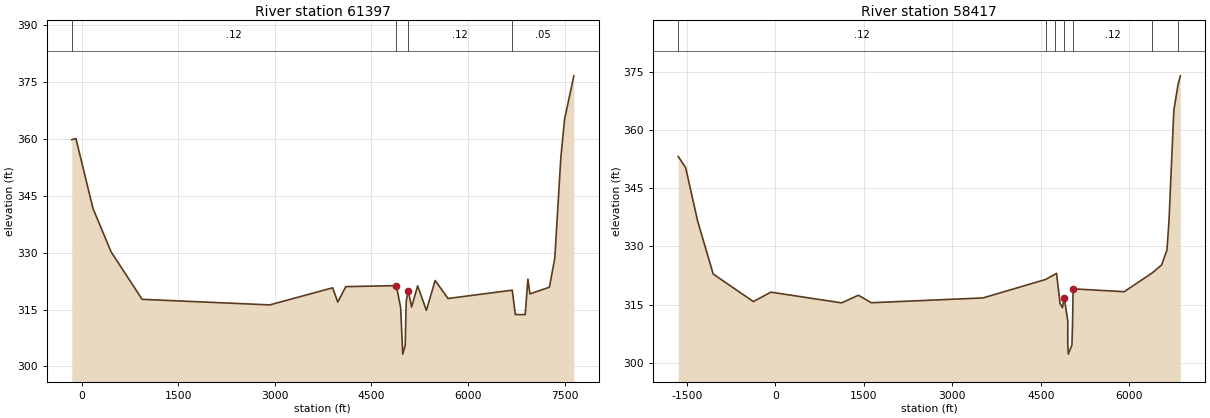
Type RM Length L Ch R = 1 ,61397   ,2980,2980,2980
BEGIN DESCRIPTION:
LFC155
END DESCRIPTION:
XS GIS Cut Line= 3
      2928662.05      6952144.22      2924216.23      6949780.79
      2921571.79      6948988.73
#Sta/Elev= 30
  -153.4  359.83   -88.8  360.14   176.3  341.69   456.3  330.26   939.1  317.71
  2920.7  316.24  3897.7  320.75    3977  316.99  4101.5  321.06  4886.2  321.32
  4952.4  315.57    4986  303.25  5023.8  305.61  5039.5  317.21  5070.8  319.98
    5123  315.69  5216.9  321.26  5352.6   314.8  5488.3  322.68  5688.9  317.93
  6685.6  320.13  6733.6  313.69  6887.1  313.68  6928.9  323.05  6960.2  319.14
  7262.9  320.91  7346.5  328.59  7440.4  355.15    7498  365.21  7642.1  376.68
#Mann= 4 ,-1 , 0
  -153.4     .12       0  4886.2     .07       0  5070.8     .12       0
  6685.6     .05       0
Bank Sta=4886.2,5070.8
XS Rating Curve= 0 ,0
Exp/Cntr=0.3,0.1

Type RM Length L Ch R = 1 ,58417   ,4102,4102,4102
BEGIN DESCRIPTION:
LFC156
END DESCRIPTION:
XS GIS Cut Line= 3
      2929084.22      6951582.44      2924361.98      6947554.64
      2922070.32      6947276.87
#Sta/Elev= 30
 -1647.4  353.24   -1522   350.4 -1316.7  336.47 -1054.2  322.88  -373.5  315.78
   -74.8   318.2  1124.2  315.43  1407.4  317.41    1627  315.47  3521.1  316.71
  4583.2  321.48  4736.2  322.77  4768.4  323.07  4828.2  315.28  4868.5   314.2
  4898.7  316.81  4959.2  310.77  4959.3  304.49  4967.5  302.19  5029.7  304.52
  5039.7  309.88  5049.8  319.06  5916.1  318.32    6393  323.19  6550.7  325.24
  6641.4   329.1    6676  336.69  6757.9  365.15  6828.6  371.77  6867.7  374.09
#Mann= 7 ,-1 , 0
 -1647.4     .12       0  4583.2     .05       0  4736.2     .12       0
  4898.7     .07       0  5049.8     .12       0    6393     .16       0
  6828.6     .05       0
Bank Sta=4898.7,5049.8
XS Rating Curve= 0 ,0
Exp/Cntr=0.3,0.1