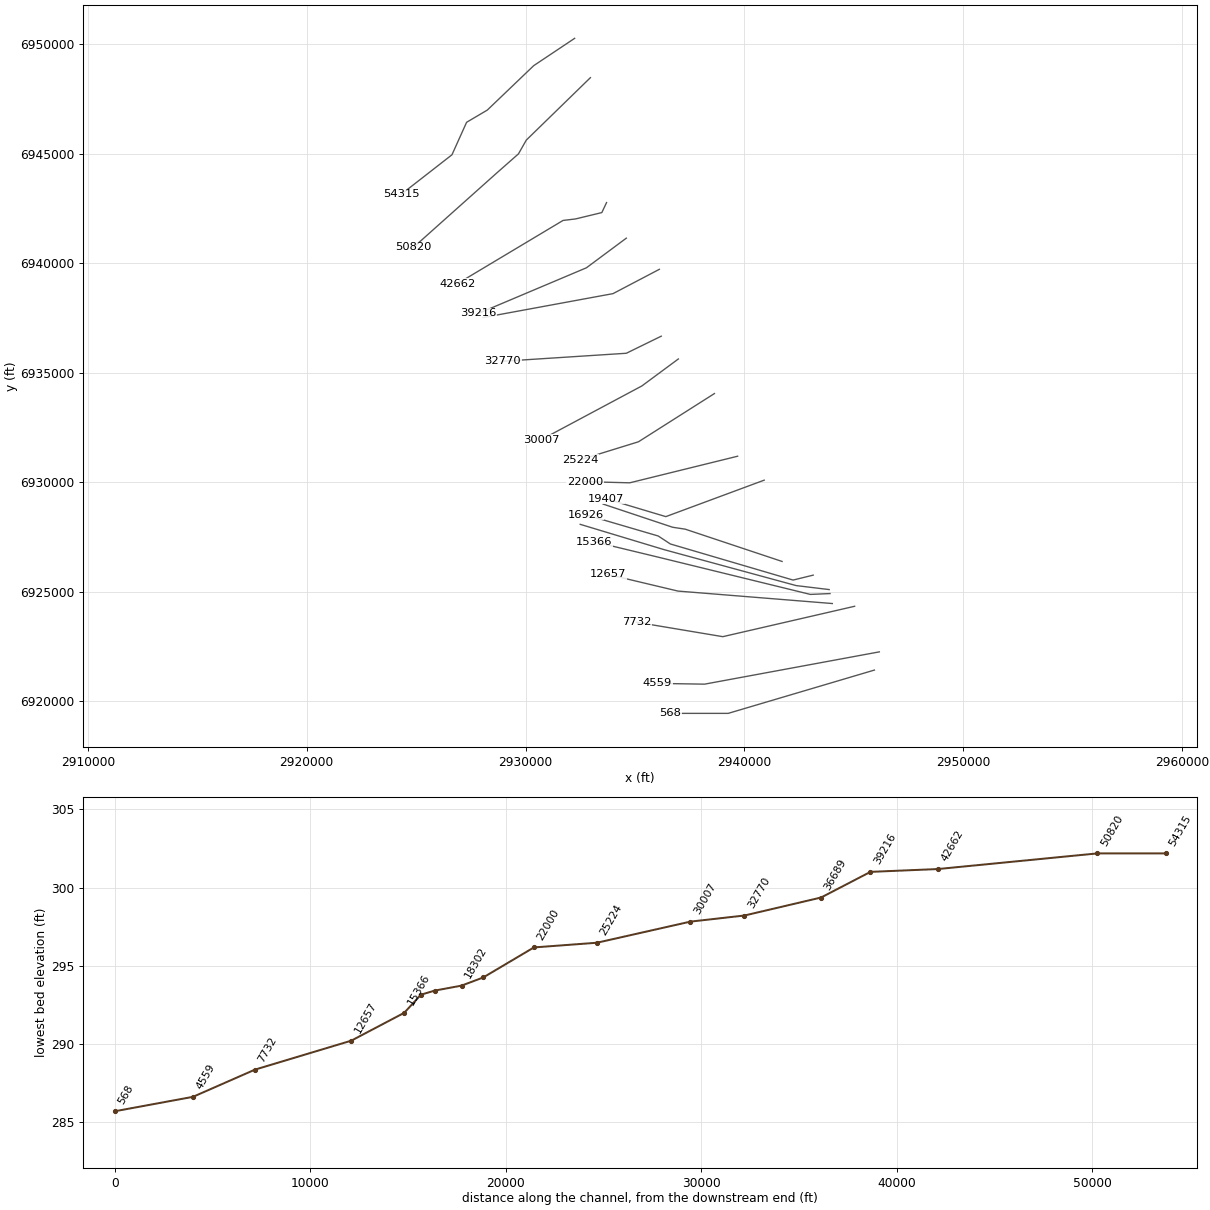
HEC-RAS study Lake Fork Creek.prj: Lake Fork Creek Base Level Engineering

--- Lake Fork Creek.g01 (geometry) --- (continued)

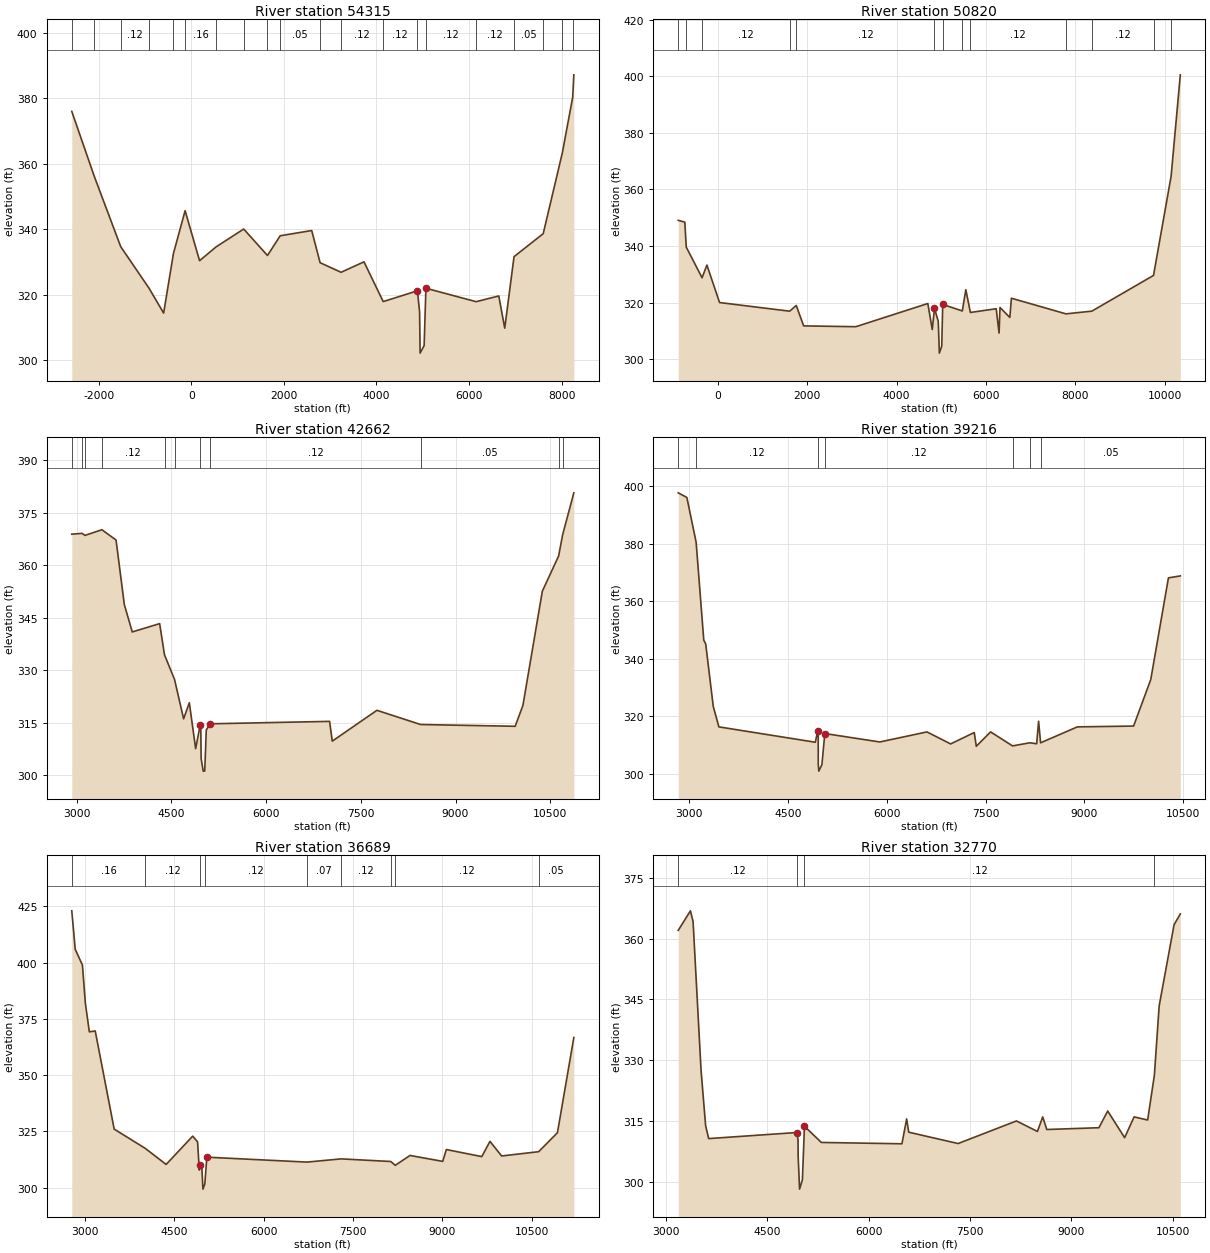
Type RM Length L Ch R = 1 ,54315   ,3495,3495,3495
BEGIN DESCRIPTION:
LFC157
END DESCRIPTION:
XS GIS Cut Line= 6
      2932243.89      6950280.31      2930374.81      6949032.95
      2928252.41       6947001.7      2927306.23      6946443.54
      2926637.83      6944959.17      2924320.13      6943153.62
#Sta/Elev= 30
 -2583.4  376.03 -2093.2  356.04 -1525.6   334.7  -914.4  322.03  -598.1  314.42
  -385.9  332.65  -134.2  345.69   178.3  330.42   536.2  334.65  1132.2  340.09
  1645.5  332.01  1920.8  338.04  2601.5  339.63  2782.7  329.81  3236.4  326.88
  3731.3  330.07  4146.4  317.93  4886.3  321.23  4932.6  314.76    4944  302.19
  5030.6  304.49  5069.3  322.01  6154.7   317.9  6644.1  319.65  6772.5  309.81
  6973.9  331.66  7603.9  338.67  8017.7  363.38  8241.1  380.35  8265.9  387.19
#Mann= 20 ,-1 , 0
 -2583.4     .05       0 -2093.2     .16       0 -1525.6     .12       0
  -914.4     .12       0  -385.9     .16       0  -134.2     .16       0
   536.2     .05       0  1132.2     .08       0  1645.5     .05       0
  1920.8     .05       0  2782.7     .12       0  3236.4     .12       0
  4146.4     .12       0  4886.3     .07       0  5069.3     .12       0
  6154.7     .12       0  6973.9     .05       0  7603.9     .16       0
  8017.7     .16       0  8241.1     .05       0
Bank Sta=4886.3,5069.3
XS Rating Curve= 0 ,0
Exp/Cntr=0.3,0.1

Type RM Length L Ch R = 1 ,50820   ,8158,8158,8158
BEGIN DESCRIPTION:
LFC158
END DESCRIPTION:
XS GIS Cut Line= 5
      2932964.36      6948483.49      2930034.66      6945629.74
      2929676.59       6945000.4      2928678.32       6944121.5
      2924882.84      6940731.75
#Sta/Elev= 30
  -885.7  349.09  -738.7  348.45  -706.3  339.63  -352.7  328.81  -243.8  333.29
    39.1  320.05  1607.1     317  1754.7  319.03  1920.2  311.81  3087.1  311.52
  4698.5  319.71  4797.2  310.51  4847.5  318.01    4932  313.39  4956.2  302.19
  5009.8  304.64  5031.5  319.38  5469.7  317.09  5548.4   324.6  5650.3  316.55
  6228.1  317.87  6292.4  309.28  6313.3  318.31  6533.2  314.79  6568.3  321.58
    7788  316.06  8367.3  317.01  9747.8  329.63 10140.8   364.6 10347.1  400.47
#Mann= 13 ,-1 , 0
  -885.7     .05       0  -706.3     .16       0  -352.7     .12       0
  1607.1     .05       0  1754.7     .12       0  4847.5     .07       0
  5031.5     .12       0  5469.7     .07       0  5650.3     .12       0
    7788     .07       0  8367.3     .12       0  9747.8     .16       0
 10140.8     .12       0
Bank Sta=4847.5,5031.5
XS Rating Curve= 0 ,0
Exp/Cntr=0.3,0.1

Type RM Length L Ch R = 1 ,42662   ,3446,3446,3446
BEGIN DESCRIPTION:
LFC159
END DESCRIPTION:
XS GIS Cut Line= 6
      2933701.77      6942773.86      2933485.99       6942317.3
      2932957.97      6942189.61      2932286.83      6942027.31
      2931713.91      6941957.87      2926879.66      6939065.25
#Sta/Elev= 30
  2923.9  368.83  3086.3  369.06  3133.5  368.48  3400.8   370.1  3625.2  367.15
  3755.9  348.76  3881.4  340.92  4315.3  343.29  4392.3  334.38  4550.8  327.38
  4694.7  316.12  4785.3   320.7  4885.3   307.6  4956.6  314.29  4966.6  313.58
  4972.2  304.77  5005.2  301.19  5028.8  301.19    5054  312.96  5117.7   314.7
  7005.9  315.39  7048.7  309.75  7755.6  318.55  8447.6  314.49  9944.7  313.99
 10067.2  319.95 10374.5  352.55 10632.3   362.6 10696.1  368.67 10873.3  380.63
#Mann= 11 ,-1 , 0
  2923.9     .16       0  3086.3     .12       0  3133.5     .16       0
  3400.8     .12       0  4392.3     .07       0  4550.8     .12       0
  4956.6     .07       0  5117.7     .12       0  8447.6     .05       0
 10632.3     .16       0 10696.1     .05       0
Bank Sta=4956.6,5117.7
XS Rating Curve= 0 ,0
Exp/Cntr=0.3,0.1

Type RM Length L Ch R = 1 ,39216   ,2527,2527,2527
BEGIN DESCRIPTION:
LFC160
END DESCRIPTION:
XS GIS Cut Line= 3
      2934605.07      6941148.42      2932782.12      6939794.23
       2927851.6      6937710.91
#Sta/Elev= 30
  2833.4  397.62  2964.6     396  3105.3  380.46  3221.2  346.47  3250.4  345.18
  3365.2  323.48  3450.7  316.37  4915.1  311.04  4951.2  314.96    4959  313.49
  4959.8  303.31    4968  301.01  5015.3  303.31  5059.1  314.06  5893.7  311.13
  6610.5  314.62  6969.4  310.45  7328.4  314.41  7359.2  309.63  7576.3  314.63
  7909.8  309.77    8172  310.84    8276  310.52  8305.1  318.34  8335.7  310.84
  8893.7  316.37  9747.6  316.65 10008.1  332.78 10276.7   368.1 10456.9  368.78
#Mann= 7 ,-1 , 0
  2833.4     .16       0  3105.3     .12       0  4951.2     .07       0
  5059.1     .12       0  7909.8     .07       0    8172     .12       0
  8335.7     .05       0
Bank Sta=4951.2,5059.1
XS Rating Curve= 0 ,0
Exp/Cntr=0.3,0.1

Type RM Length L Ch R = 1 ,36689   ,3919,3919,3919
BEGIN DESCRIPTION:
LFC161
END DESCRIPTION:
XS GIS Cut Line= 3
      2936115.47      6939724.79       2933997.4      6938613.67
      2928060.12      6937519.96
#Sta/Elev= 30
  2777.7  423.03  2835.7  405.94  2956.7  398.94  3006.5  381.86  3072.7  369.27
  3171.7  369.63  3489.7  326.04  4010.5   317.5  4362.1  310.34  4808.4  322.92
  4889.9  320.37  4918.6  307.83    4935  309.98  4962.7  308.41  4979.8  299.37
  5011.6  301.67  5045.3  313.57  6725.6  311.38  7298.3  312.81  8133.9  311.65
  8208.8  309.95  8456.3  314.33  9005.4   311.7  9066.4  316.96  9661.1  313.82
  9798.5   320.6  9994.5   314.1 10615.7     316 10931.4  324.44 11206.7  366.75
#Mann= 9 ,-1 , 0
  2777.7     .16       0  4010.5     .12       0    4935     .07       0
  5011.6     .12       0  6725.6     .07       0  7298.3     .12       0
  8133.9     .16       0  8208.8     .12       0 10615.7     .05       0
Bank Sta=4935,5045.3
XS Rating Curve= 0 ,0
Exp/Cntr=0.3,0.1

Type RM Length L Ch R = 1 ,32770   ,2763,2763,2763
BEGIN DESCRIPTION:
LFC162
END DESCRIPTION:
XS GIS Cut Line= 3
      2936202.26      6936669.23      2934605.04      6935887.98
      2928962.65      6935523.39
#Sta/Elev= 30
  3182.3  362.02  3362.8  366.84  3401.9  364.19  3520.3  327.48  3587.9  313.84
  3632.9  310.68  4938.3  312.18  4955.3  310.43    4958  306.16  4978.6  298.22
  5020.5  300.54  5050.6  313.72  5301.1  309.73  6493.6   309.4  6563.7  315.53
  6593.8  312.26  7325.3  309.46  8188.9  315.03  8499.3  312.44  8577.9  316.03
    8638  312.92  9409.6  313.36  9539.9  317.47  9790.4  310.91  9930.7  316.03
 10131.1  315.26 10230.8  326.33 10301.5  343.39   10522   363.4 10614.5  366.08
#Mann= 4 ,-1 , 0
  3182.3     .12       0  4938.3     .07       0  5050.6     .12       0
 10230.8     .05       0
Bank Sta=4938.3,5050.6
XS Rating Curve= 0 ,0
Exp/Cntr=0.3,0.1

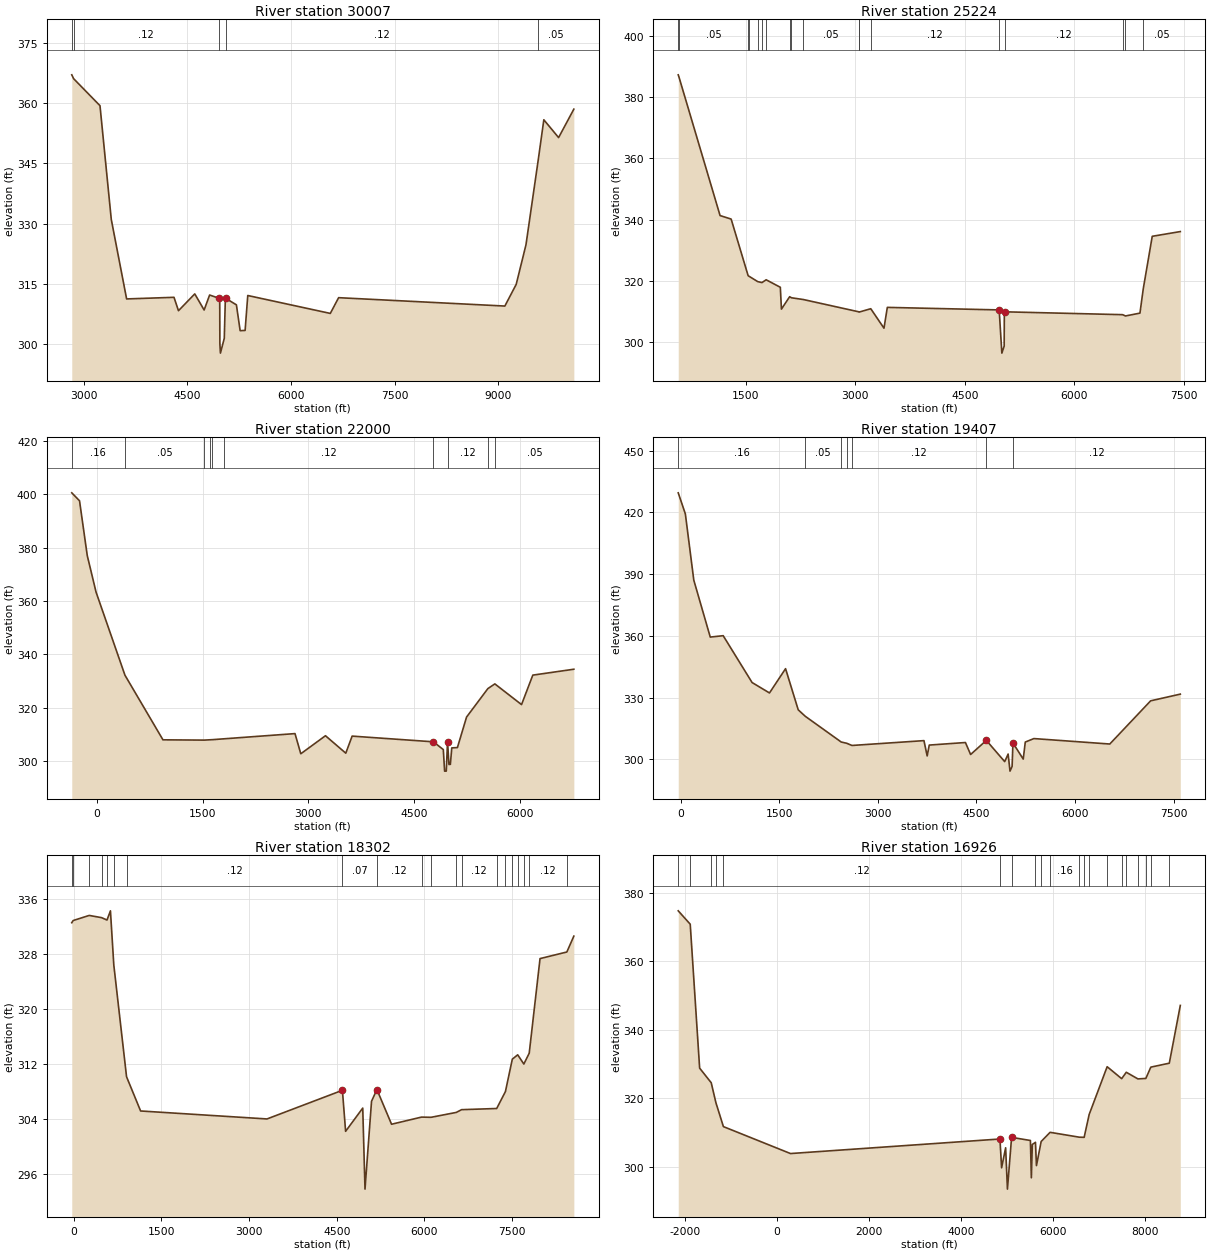
Type RM Length L Ch R = 1 ,30007   ,4783,4783,4783
BEGIN DESCRIPTION:
LFC163
END DESCRIPTION:
XS GIS Cut Line= 3
       2936983.5      6935627.55      2935316.84      6934394.92
      2930733.54      6931947.02
#Sta/Elev= 30
    2825     367  2851.6  366.05  3233.6  359.33  3397.1  331.06  3619.2   311.3
  4305.1   311.7  4369.9  308.37  4605.7  312.55  4741.4  308.55  4820.8  312.27
  4956.7  311.47  4967.2  310.92  4969.2  300.13  4977.3  297.83  5033.1  301.51
  5047.4  310.63    5055  311.44  5208.7  309.83  5262.8  303.41  5334.7  303.47
    5373  312.15  6568.1   307.7  6688.5  311.61  9095.2  309.53  9259.5  314.92
  9400.8  324.74  9578.8  345.89  9659.5  355.83  9873.3   351.4   10094  358.47
#Mann= 5 ,-1 , 0
    2825     .16       0  2851.6     .12       0  4956.7     .07       0
    5055     .12       0  9578.8     .05       0
Bank Sta=4956.7,5055
XS Rating Curve= 0 ,0
Exp/Cntr=0.3,0.1

Type RM Length L Ch R = 1 ,25224   ,3224,3224,3224
BEGIN DESCRIPTION:
LFC164
END DESCRIPTION:
XS GIS Cut Line= 3
      2938632.81      6934047.69      2935160.59      6931842.84
      2932521.68      6931026.86
#Sta/Elev= 30
   575.4  387.24   584.8  386.58  1148.4  341.34    1300   340.2  1532.4  321.75
  1548.2   321.5  1663.8   319.8  1721.9  319.49  1779.4   320.4  1973.4  317.95
  1988.6  310.83    2101  314.88  2126.2  314.53  2290.5  313.95  3048.5  309.95
  3051.8  309.86  3211.9  310.96    3393  304.61  3438.7   311.4  4970.3  310.57
    5007  296.48  5038.8  298.78  5040.8  309.09  5050.2  309.95  6660.3  309.02
    6700   308.6  6898.1  309.53  6943.1  317.42  7066.4  334.58  7450.7  336.12
#Mann= 18 ,-1 , 0
   575.4     .16       0   584.8     .05       0  1532.4     .16       0
  1548.2     .05       0  1663.8     .16       0  1721.9     .05       0
  1779.4     .12       0    2101     .05       0  2126.2     .08       0
  2290.5     .05       0  3048.5     .12       0  3051.8     .05       0
  3211.9     .12       0  4970.3     .07       0  5050.2     .12       0
  6660.3     .05       0    6700     .12       0  6943.1     .05       0
Bank Sta=4970.3,5050.2
XS Rating Curve= 0 ,0
Exp/Cntr=0.3,0.1

Type RM Length L Ch R = 1 ,22000   ,2593,2593,2593
BEGIN DESCRIPTION:
LFC165
END DESCRIPTION:
XS GIS Cut Line= 3
      2939691.87      6931183.12      2934761.29      6929967.84
      2932712.69      6930019.92
#Sta/Elev= 30
    -359  400.54  -248.9  397.55  -138.9  376.99   -14.4  363.33   395.9  332.16
   935.5  307.92  1519.4  307.81  1608.9  307.94  1635.8  307.97  1797.6  308.29
    2810  310.25  2892.3  302.69  3242.5  309.45  3530.9  302.91  3621.1  309.31
  4775.5  307.17  4915.5  304.25  4933.7  296.18  4957.4  296.18  4975.5  307.29
  4995.5  298.67  5015.5  298.72  5035.5  304.89  5115.6  305.01  5245.6  316.46
  5547.9  327.12    5647  328.89  6025.9  321.13  6185.9  332.18  6768.4  334.39
#Mann= 10 ,-1 , 0
    -359     .16       0   395.9     .05       0  1519.4     .07       0
  1608.9     .05       0  1635.8     .07       0  1797.6     .12       0
  4775.5     .07       0  4975.5     .12       0  5547.9     .16       0
    5647     .05       0
Bank Sta=4775.5,4975.5
XS Rating Curve= 0 ,0
Exp/Cntr=0.3,0.1

Type RM Length L Ch R = 1 ,19407   ,1105,1105,1105
BEGIN DESCRIPTION:
LFC166
END DESCRIPTION:
XS GIS Cut Line= 3
      2940907.13      6930089.37      2936410.59       6928422.7
      2933684.89      6929238.67
#Sta/Elev= 30
   -38.7   429.5    69.7  419.25   198.2  387.06   448.7   359.4   645.4  360.08
  1085.2  337.31    1350  332.25  1594.7  344.05  1787.3  324.06  1894.5  320.91
  2441.8   308.4  2525.8  307.79  2605.6  306.73  3700.8  309.08  3749.6  301.64
  3781.3  306.92  4331.9  308.16  4410.8  302.34  4650.1   309.2  4929.6  298.87
  4981.8  302.56  5010.5  294.26  5042.3  296.56  5054.9  307.95  5211.5  300.12
  5242.8  308.38  5374.1  310.08  6528.8  307.43  7150.6  328.42    7602  331.68
#Mann= 7 ,-1 , 0
   -38.7     .16       0  1894.5     .05       0  2441.8     .07       0
  2525.8     .05       0  2605.6     .12       0  4650.1     .07       0
  5054.9     .12       0
Bank Sta=4650.1,5054.9
XS Rating Curve= 0 ,0
Exp/Cntr=0.3,0.1

Type RM Length L Ch R = 1 ,18302   ,1376,1376,1376
BEGIN DESCRIPTION:
LFC167
END DESCRIPTION:
XS GIS Cut Line= 4
      2941723.14      6926374.07      2937296.01      6927849.78
      2936723.09      6927936.59      2933546.01      6928995.62
#Sta/Elev= 30
   -35.4   332.5   -10.9  332.82   263.4  333.56   473.7  333.24   567.9  332.89
   626.7  334.23   684.1  326.36   902.4  310.09  1143.2  305.11  3306.6  303.95
  4597.8  308.12  4652.4  302.15  4945.8  305.53  4984.5  293.74  5096.2  306.52
  5188.5  308.23    5439  303.18  5951.9  304.22  6115.1  304.19  6546.8   304.9
  6638.4   305.3  7238.9  305.47  7388.2  307.93  7506.4  312.65  7598.5  313.28
  7703.7  311.94  7795.8  313.52  7980.9  327.28  8439.9  328.24  8559.6  330.55
#Mann= 20 ,-1 , 0
   -35.4     .08       0   -10.9      .1       0   263.4     .08       0
   473.7     .05       0   567.9     .08       0   684.1     .12       0
   902.4     .12       0  4597.8     .07       0  5188.5     .12       0
  5951.9     .07       0  6115.1     .12       0  6546.8     .07       0
  6638.4     .12       0  7238.9     .12       0  7388.2     .07       0
  7506.4     .12       0  7598.5      .1       0  7703.7     .07       0
  7795.8     .12       0  8439.9     .05       0
Bank Sta=4597.8,5188.5
XS Rating Curve= 0 ,0
Exp/Cntr=0.3,0.1

Type RM Length L Ch R = 1 ,16926   ,703,703,703
BEGIN DESCRIPTION:
LFC168
END DESCRIPTION:
XS GIS Cut Line= 5
      2943146.73      6925749.09      2942226.56      6925523.39
      2936618.93       6927172.7      2936063.37      6927537.28
       2932748.7      6928509.12
#Sta/Elev= 30
 -2140.9   374.7 -1880.4   370.8 -1675.8  328.76 -1423.8  324.49 -1322.4  318.67
 -1159.3  311.68   298.7  303.81  4850.5  308.06  4886.7  299.65  4974.1  305.49
  5013.5  293.42  5103.7  308.53  5512.5  307.63  5533.3  296.73  5554.2  306.47
  5622.4  307.09  5644.2  300.29  5746.4  307.33  5940.4  310.01  6575.1  308.59
  6680.6  308.55  6789.8  315.23  7180.6  329.17  7496.1  325.68  7596.1  327.55
    7849  325.61  8021.5  325.75  8129.6  329.05  8531.1   330.2  8770.4  347.07
#Mann= 20 ,-1 , 0
 -2140.9     .16       0 -1880.4     .08       0 -1423.8     .05       0
 -1322.4     .16       0 -1159.3     .12       0  4850.5     .07       0
  5103.7     .12       0  5622.4     .08       0  5746.4     .12       0
  5940.4     .16       0  6575.1     .16       0  6680.6     .12       0
  6789.8     .16       0  7180.6     .05       0  7496.1     .16       0
  7596.1     .05       0    7849     .05       0  8021.5     .16       0
  8129.6     .05       0  8531.1     .16       0
Bank Sta=4850.5,5103.7
XS Rating Curve= 0 ,0
Exp/Cntr=0.3,0.1

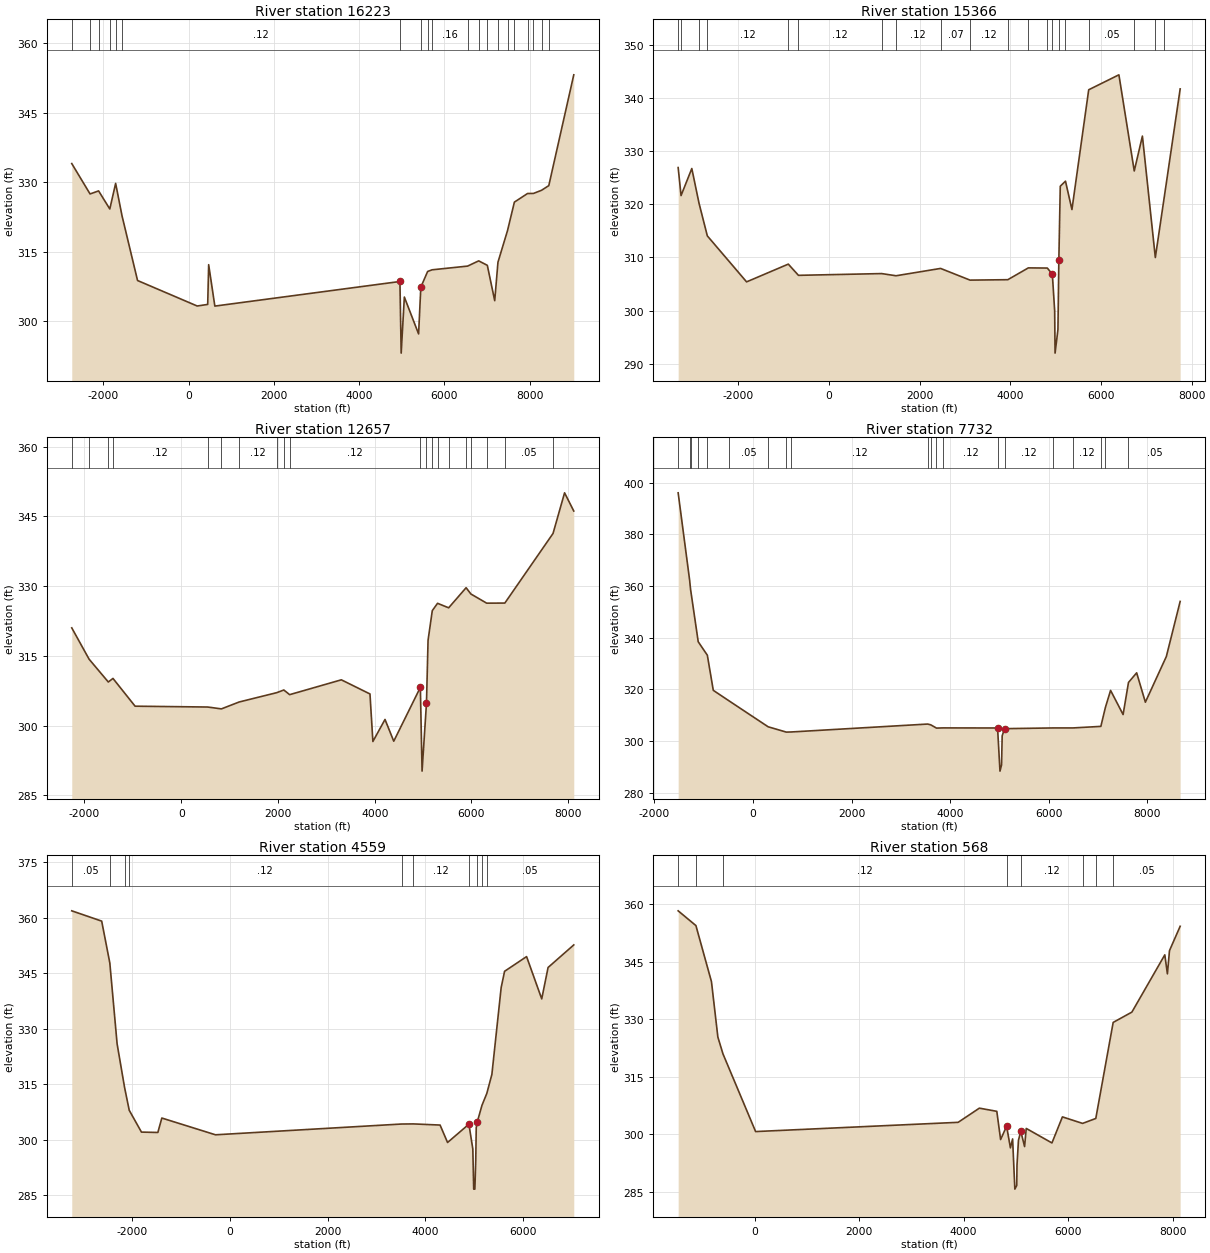
Type RM Length L Ch R = 1 ,16223   ,857,857,857
BEGIN DESCRIPTION:
Mapping XS dc915856
END DESCRIPTION:
XS GIS Cut Line= 4
      2943876.83      6925088.78      2942366.41      6925271.07
      2936337.76       6926911.7      2932499.23      6928069.76
#Sta/Elev= 30
 -2742.7  334.07 -2313.2  327.51 -2113.2  328.17 -1850.2  324.27 -1713.2  329.79
 -1564.1  322.82 -1199.1  308.83     200  303.33   446.9  303.67   469.4  312.25
   614.5  303.31  4956.9  308.62  4986.5  293.16  5060.8  305.26  5395.1   297.3
  5447.3  307.39    5607  310.78  5711.1  311.14  6544.3  311.94  6804.8  313.07
  7007.5  312.11  7181.2  304.48  7257.2  312.78  7481.6  319.61  7642.5  325.75
  7952.1  327.61  8088.5  327.62  8279.5   328.3    8450  329.31    9036  353.22
#Mann= 20 ,-1 , 0
 -2742.7     .16       0 -2313.2     .08       0 -2113.2     .08       0
 -1850.2     .08       0 -1713.2     .16       0 -1564.1     .12       0
  4956.9     .07       0  5447.3     .12       0    5607     .05       0
  5711.1     .16       0  6544.3     .12       0  6804.8     .16       0
  7007.5     .12       0  7257.2     .16       0  7481.6     .12       0
  7642.5     .05       0  7952.1     .12       0  8088.5     .05       0
  8279.5     .16       0    8450     .05       0
Bank Sta=4956.9,5447.3
XS Rating Curve= 0 ,0
Exp/Cntr=0.3,0.1

Type RM Length L Ch R = 1 ,15366   ,2709,2709,2709
BEGIN DESCRIPTION:
Mapping XS c8906611
END DESCRIPTION:
XS GIS Cut Line= 4
       2943915.9      6924906.49      2943017.45      6924867.42
      2936103.38      6926560.13      2933134.59      6927276.29
#Sta/Elev= 30
 -3324.3   326.9 -3260.3  321.63 -3023.1  326.72 -2864.3   320.2 -2680.9  314.05
 -1815.1   305.4  -895.1  308.74  -671.5  306.63  1163.8  306.96  1480.6  306.55
  2463.5  307.93    3113  305.73  3946.2  305.81  4398.4  308.03  4817.2     308
  4928.2  306.84  4979.6  299.96  4988.3     292  5051.6  296.43  5071.8  309.57
  5103.1  323.39  5218.1  324.34  5360.2     319  5730.2  341.53  6396.2  344.34
  6734.7  326.26  6914.4  332.82  7199.5  309.98  7399.4  321.51  7747.2  341.69
#Mann= 20 ,-1 , 0
 -3324.3     .16       0 -3260.3     .08       0 -2864.3     .16       0
 -2680.9     .12       0  -895.1     .07       0  -671.5     .12       0
  1163.8     .07       0  1480.6     .12       0  2463.5     .07       0
    3113     .12       0  3946.2     .07       0  4398.4     .07       0
  4817.2     .12       0  4928.2     .07       0  5071.8     .12       0
  5218.1     .16       0  5730.2     .05       0  6734.7     .05       0
  7199.5     .16       0  7399.4     .05       0
Bank Sta=4928.2,5071.8
XS Rating Curve= 0 ,0
Exp/Cntr=0.3,0.1

Type RM Length L Ch R = 1 ,12657   ,4925,4925,4925
BEGIN DESCRIPTION:
LFC169
END DESCRIPTION:
XS GIS Cut Line= 3
        2944020.      6924450.76      2936966.15      6925019.92
      2933754.32      6925783.82
#Sta/Elev= 30
 -2262.8  321.02   -1904  314.28 -1507.3  309.38 -1410.9  310.15  -953.6  304.18
   548.7     304     831   303.6    1197  305.08  1975.7  307.09  2121.3  307.66
  2241.7  306.66  3310.3  309.85  3902.2  306.81  3962.4  296.59  4213.2  301.33
  4393.8  296.65  4943.8  308.23  4979.3  290.22  5070.3  304.82    5103  318.35
  5190.5  324.72  5299.3   326.3  5528.9  325.33  5889.6  329.65  5988.7   328.3
  6314.8  326.33  6690.4  326.35  7686.9  341.32  7925.3  350.05  8115.4  346.14
#Mann= 20 ,-1 , 0
 -2262.8     .05       0   -1904     .05       0 -1507.3     .07       0
 -1410.9     .12       0   548.7     .12       0     831     .07       0
    1197     .12       0  1975.7     .12       0  2121.3     .07       0
  2241.7     .12       0  4943.8     .07       0  5070.3     .12       0
  5190.5     .16       0  5299.3     .12       0  5528.9     .16       0
  5889.6     .12       0  5988.7     .05       0  6314.8     .16       0
  6690.4     .05       0  7686.9     .05       0
Bank Sta=4943.8,5070.3
XS Rating Curve= 0 ,0
Exp/Cntr=0.3,0.1

Type RM Length L Ch R = 1 ,7732    ,3173,3173,3173
BEGIN DESCRIPTION:
LFC170
END DESCRIPTION:
XS GIS Cut Line= 3
       2945039.1      6924325.49      2939014.76      6922936.59
      2935073.77      6923596.31
#Sta/Elev= 30
 -1515.3  396.04 -1282.7  362.25 -1263.9  358.74 -1108.4  338.42  -923.5  333.21
    -803  319.63  -489.5  315.63   309.5  305.52   677.1  303.47   779.4  303.52
  3543.3  306.58  3606.8  306.28  3722.1  305.02  3858.3  305.09  4960.9  305.06
  5009.8  288.37  5041.7  290.77  5054.2  302.03  5102.8   304.8  6093.3  305.08
    6489  305.08  7054.9  305.68  7146.8     313  7252.3   319.6  7505.8  310.26
  7615.3  322.68  7780.7   326.4  7957.7  315.04  8382.6  332.71  8662.9  354.03
#Mann= 20 ,-1 , 0
 -1515.3     .16       0 -1282.7     .08       0 -1263.9     .16       0
 -1108.4     .08       0  -923.5     .16       0  -489.5     .05       0
   309.5     .12       0   677.1     .07       0   779.4     .12       0
  3543.3     .07       0  3606.8     .12       0  3722.1     .07       0
  3858.3     .12       0  4960.9     .07       0  5102.8     .12       0
  6093.3     .05       0    6489     .12       0  7054.9     .16       0
  7146.8     .05       0  7615.3     .05       0
Bank Sta=4960.9,5102.8
XS Rating Curve= 0 ,0
Exp/Cntr=0.3,0.1

Type RM Length L Ch R = 1 ,4559    ,3991,3991,3991
BEGIN DESCRIPTION:
LFC171
END DESCRIPTION:
XS GIS Cut Line= 3
      2946167.51      6922242.14      2938181.43      6920766.45
      2936029.29      6920801.16
#Sta/Elev= 30
 -3237.1  361.83 -2624.7  359.05 -2458.3  347.75 -2309.1  325.89 -2155.9  314.07
 -2061.2  307.94 -1810.8  302.04 -1475.3  301.94 -1393.9  305.84  -295.6  301.31
  3511.1  304.22  3756.5  304.25  4300.9  303.94  4453.4  299.23  4890.6  304.18
  4970.6  297.48  4988.8  286.63  5012.5  286.63  5030.6  294.45  5040.6  303.22
  5060.6  304.72  5157.8  309.27  5256.9  312.49  5360.7  317.63  5550.7   341.1
  5620.7  345.49  6070.8  349.46  6380.8  338.04  6510.8  346.52  7036.6  352.62
#Mann= 10 ,-1 , 0
 -3237.1     .05       0 -2458.3     .12       0 -2155.9     .05       0
 -2061.2     .12       0  3511.1     .07       0  3756.5     .12       0
  4890.6     .07       0  5060.6     .12       0  5157.8     .16       0
  5256.9     .05       0
Bank Sta=4890.6,5060.6
XS Rating Curve= 0 ,0
Exp/Cntr=0.3,0.1

Type RM Length L Ch R = 1 ,568     ,0,0,0
BEGIN DESCRIPTION:
Mapping XS 338178f2
END DESCRIPTION:
XS GIS Cut Line= 3
      2945943.77      6921410.32      2939259.71      6919431.15
      2936620.83      6919431.15
#Sta/Elev= 30
 -1464.4  358.33 -1124.4  354.48  -826.8  339.85  -704.4  325.41  -607.6  321.04
    18.3  300.73  3895.3  303.14  4301.6  306.84  4635.4  306.01  4708.4  298.64
  4823.1  302.14  4896.1  296.48  4937.8  298.81    4981  285.71  5016.8  286.65
    5022  292.01    5050  298.46  5094.3  300.82  5167.3  296.81  5198.7  301.55
  5691.2  297.76  5891.2  304.56  6277.7  302.86  6530.5  304.15    6863  329.21
  7221.2   331.9  7851.2  346.84  7901.2  341.89  7941.2  347.95  8145.4   354.3
#Mann= 8 ,-1 , 0
 -1464.4     .05       0 -1124.4     .16       0  -607.6     .12       0
  4823.1     .07       0  5094.3     .12       0  6277.7     .07       0
  6530.5     .16       0    6863     .05       0
Bank Sta=4823.1,5094.3
XS Rating Curve= 0 ,0
Exp/Cntr=0.3,0.1
Stream Node=Lake Fork Creek ,Reach-1         , 0 , 0 ,Upstream end
Stream Node=Lake Fork Creek ,Reach-1         , 0 , 1 ,Downstream end
LCMann Table=0

Chan Stop Cuts=-1
Use User Specified Reach Order=0
Composite Channel Slope=5