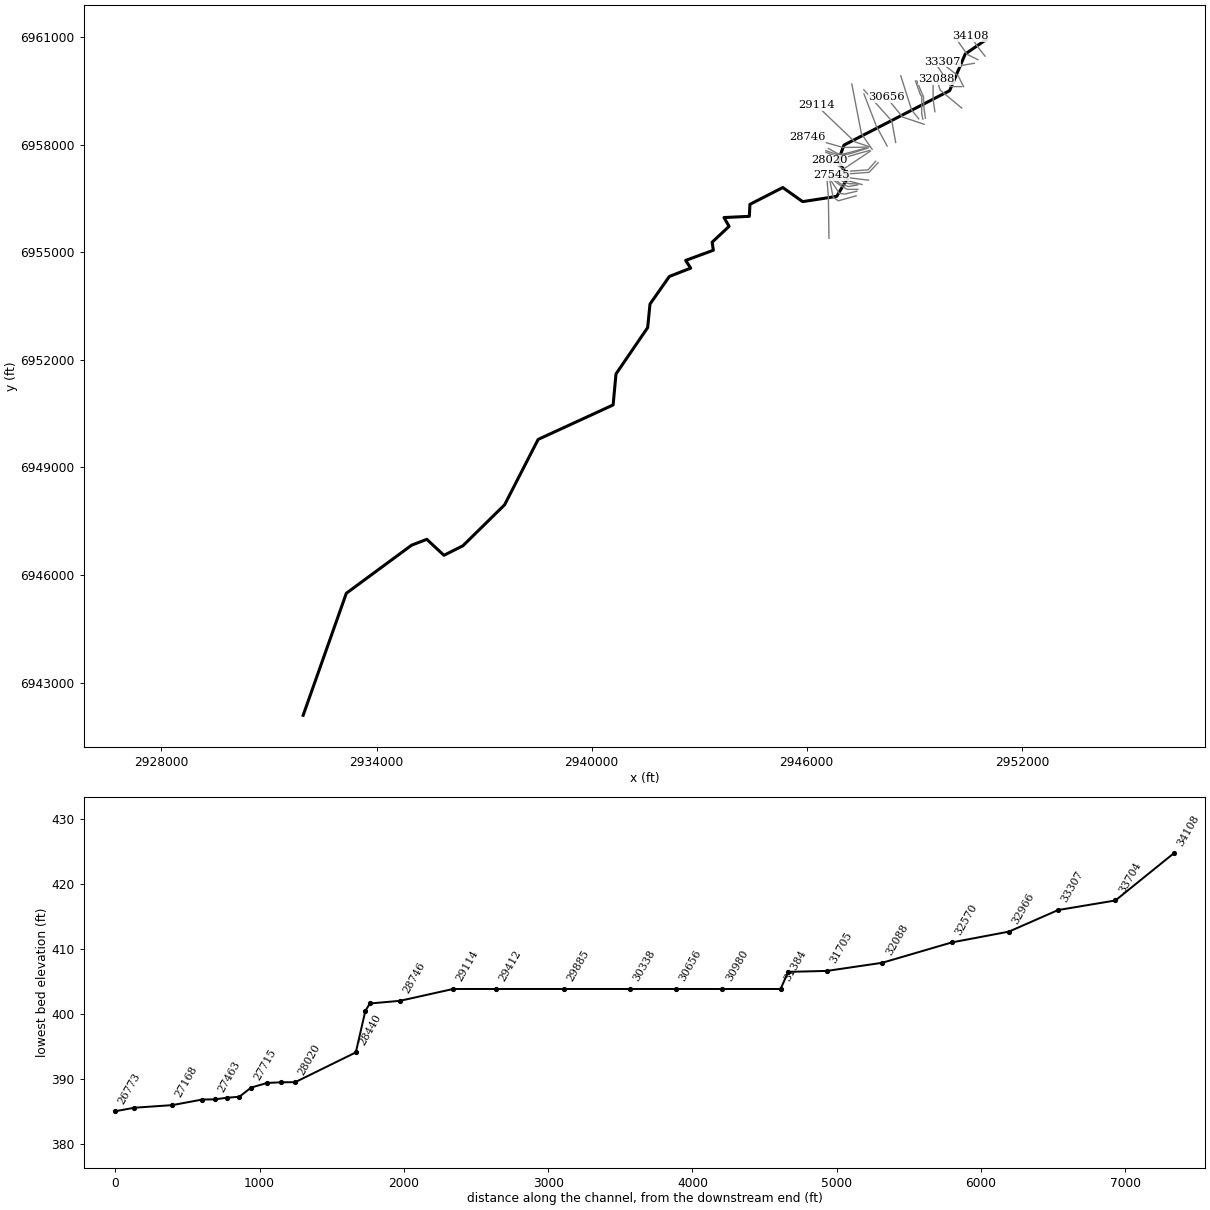
--- MILL RACE.prj (project) ---

Proj Title=MILL RACE Base Level Engineering
Current Plan=p01
Default Exp/Contr=0.3,0.1
English Units
Geom File=g01
Flow File=f01
Plan File=p01
BEGIN DESCRIPTION:
MILL RACE
END DESCRIPTION:

--- MILL RACE.p01 (plan) ---

Plan Title=Multiple Run
Short Identifier=Multiple
Geom File=g01
Flow File=f01
Subcritical Flow
K Sum by GR= 0
Std Step Tol= 0.01
Critical Tol= 0.01
Num of Std Step Trials= 20
Max Error Tol= 0.3
Flow Tol Ratio= 0.001
Split Flow NTrial= 30
Split Flow Tol= 0.02
Split Flow Ratio= 0.02
Log Output Level= 0
Friction Slope Method= 1
Unsteady Friction Slope Method= 2
Unsteady Bridges Friction Slope Method= 1
Parabolic Critical Depth
Global Vel Dist=  1 , 1 , 1
Global Log Level= 0
CheckData=True
Encroach Param= -1, 0, 0, 0
BEGIN DESCRIPTION:
Multiple Run
END DESCRIPTION:

--- MILL RACE.f01 (steady flow) ---

Flow Title=Multiple
Program Version=5.07
Number of Profiles= 7
Profile Names=10-year,25-year,50-year,1pct_min,100-year,1pct_plu,500-year
River Rch & RM=MILL RACE,Reach-1         ,34108
     426     565     678     405     808    1613    1150
River Rch & RM=MILL RACE,Reach-1         ,30338
    1286    1828    2297    1433    2860    5707    4444
River Rch & RM=MILL RACE,Reach-1         ,28440
    1319    1876    2357    1471    2936    5857    4563
River Rch & RM=MILL RACE,Reach-1         ,26905
    1558    2229    2811    1760    3511    7006    5491
River Rch & RM=MILL RACE,Reach-1         ,23651
    1582    2255    2836    1770    3531    7046    5487
River Rch & RM=MILL RACE,Reach-1         ,18789
    2247    3233    4089    2562    5113   10201    8011
River Rch & RM=MILL RACE,Reach-1         ,15012
    2750    3984    5066    3188    6360   12690   10053
River Rch & RM=MILL RACE,Reach-1         ,12921
    3105    4517    5758    3632    7247   14459   11509
River Rch & RM=MILL RACE,Reach-1         ,9183
    3262    4740    6037    3803    7588   15140   12019
River Rch & RM=MILL RACE,Reach-1         ,896
    3273    4752    6048    3807    7595   15154   12011
Boundary for River Rch & Prof#=MILL RACE,Reach-1         , 1
Up Type= 0
Dn Type= 3
Dn Slope=0.005
Boundary for River Rch & Prof#=MILL RACE,Reach-1         , 2
Up Type= 0
Dn Type= 3
Dn Slope=0.005
Boundary for River Rch & Prof#=MILL RACE,Reach-1         , 3
Up Type= 0
Dn Type= 3
Dn Slope=0.005
Boundary for River Rch & Prof#=MILL RACE,Reach-1         , 4
Up Type= 0
Dn Type= 3
Dn Slope=0.005
Boundary for River Rch & Prof#=MILL RACE,Reach-1         , 5
Up Type= 0
Dn Type= 3
Dn Slope=0.005
Boundary for River Rch & Prof#=MILL RACE,Reach-1         , 6
Up Type= 0
Dn Type= 3
Dn Slope=0.005
Boundary for River Rch & Prof#=MILL RACE,Reach-1         , 7
Up Type= 0
Dn Type= 3
Dn Slope=0.005
DSS Import GetInterval= 0
DSS Import GetPeak= 0
DSS Import FillOption= 0

--- MILL RACE.g01 (geometry) ---

Geom Title=Existing Conditions

River Reach=MILL RACE,Reach-1
Reach XY= 30
      2950995.59      6960930.71      2950420.93      6960533.21
      2949986.16      6959511.71      2947037.32      6957992.86
      2946875.87      6957544.94      2947160.59      6957106.58
      2946836.66      6956563.35      2945886.30      6956415.87
      2945331.90      6956809.69      2944415.59      6956340.71
      2944398.42      6956005.81      2943691.84      6955972.42
      2943833.95      6955726.34      2943360.71      6955284.30
      2943395.19      6955060.25      2942622.25      6954776.03
      2942763.31      6954561.18      2942168.31      6954329.47
      2941628.14      6953559.65      2941562.25      6952902.14
      2940679.32      6951609.22      2940599.06      6950744.31
      2938507.82      6949783.14      2937570.83      6947957.79
      2936408.52      6946815.69      2935879.19      6946550.19
      2935401.16      6946995.93      2934976.68      6946831.87
      2933156.39      6945490.99      2931951.89      6942086.96

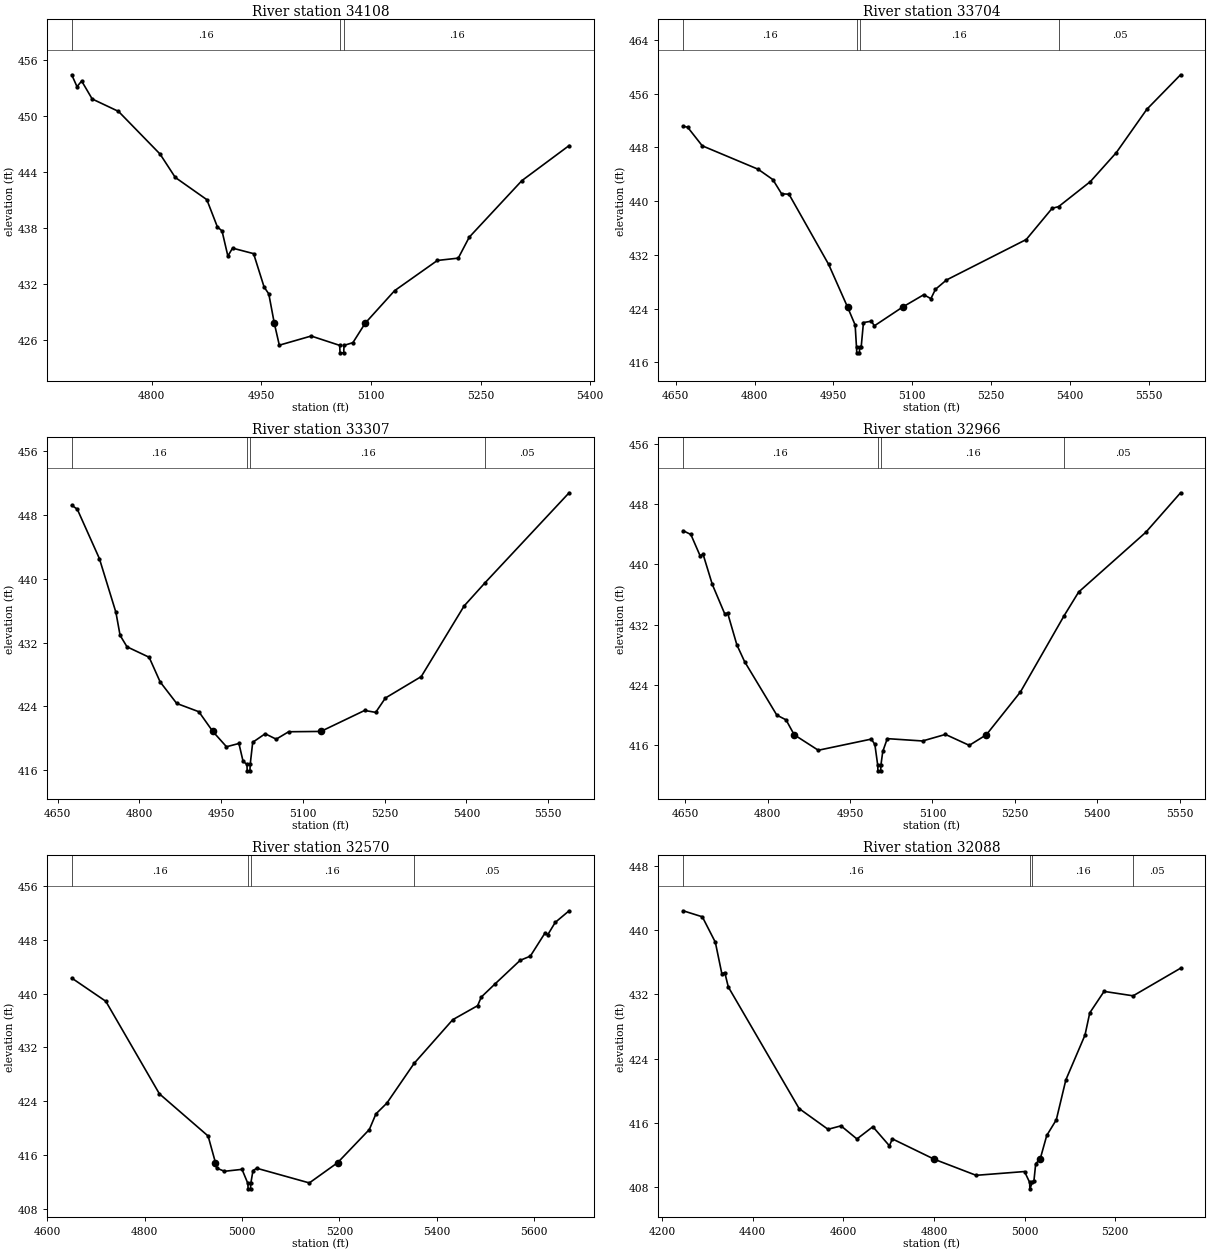
Type RM Length L Ch R = 1,34108,404,404,404
BEGIN DESCRIPTION:
MILL RACE 51.0
END DESCRIPTION:
XS GIS Cut Line= 3
      2950975.00      6960475.00      2950775.00      6960725.00
      2950575.01      6961024.99
#Sta/Elev= 30
  4690.4  454.41  4697.6  453.14  4704.0  453.74  4718.4  451.82  4754.4  450.49
  4811.3  445.92  4832.1  443.42  4875.3  441.04  4889.7  438.13  4896.1  437.69
  4904.1  435.00  4910.5  435.85  4939.3  435.26  4953.7  431.68  4960.1  430.95
  4967.6  427.82  4974.5  425.46  5018.1  426.44  5057.1  425.44  5057.6  424.64
  5062.6  424.64  5063.1  425.44  5075.2  425.73  5092.1  427.82  5132.2  431.29
  5190.8  434.53  5219.4  434.78  5234.4  437.02  5306.5  443.08  5371.1  446.83
#Mann=3,-1,0
  4690.4    0.16       0  5057.1    0.07       0  5063.1    0.16       0
Bank Sta=4967.6,5092.1
Exp/Cntr=0.3,0.1

Type RM Length L Ch R = 1,33704,397,397,397
BEGIN DESCRIPTION:
MILL RACE 50.0
END DESCRIPTION:
XS GIS Cut Line= 3
      2950774.98      6960375.01      2950475.00      6960525.00
      2950125.01      6961024.99
#Sta/Elev= 30
  4664.3  451.14  4672.7  451.02  4700.6  448.24  4806.8  444.75  4834.8  443.21
  4851.5  441.09  4865.5  441.03  4941.0  430.56  4976.9  424.21  4991.3  421.55
  4993.9  418.20  4994.4  417.40  4999.4  417.40  4999.9  418.20  5002.7  418.20
  5007.1  421.91  5021.9  422.11  5028.0  421.43  5081.4  424.21  5121.8  426.06
  5135.3  425.47  5144.0  426.86  5164.9  428.25  5316.6  434.28  5365.9  438.93
  5378.1  439.18  5438.7  442.92  5487.9  447.23  5545.9  453.68  5610.0  458.82
#Mann=4,-1,0
  4664.3    0.16       0  4993.9    0.07       0  4999.9    0.16       0
  5378.1    0.05       0
Bank Sta=4976.9,5081.4
Exp/Cntr=0.3,0.1

Type RM Length L Ch R = 1,33307,341,341,341
BEGIN DESCRIPTION:
MILL RACE 49.0
END DESCRIPTION:
XS GIS Cut Line= 3
      2950675.02      6960275.00      2950375.00      6960225.00
      2949775.04      6960324.99
#Sta/Elev= 30
  4675.9  449.23  4686.1  448.73  4726.6  442.55  4757.0  435.79  4764.6  432.92
  4777.3  431.48  4817.9  430.17  4838.1  427.08  4868.5  424.38  4909.1  423.34
  4934.7  420.87  4959.8  418.95  4982.6  419.36  4990.2  417.13  4997.3  416.73
  4997.8  415.93  5002.8  415.93  5003.3  416.73  5007.9  419.51  5030.8  420.58
  5051.0  419.90  5073.8  420.83  5132.9  420.87  5213.2  423.50  5233.5  423.26
  5251.3  425.06  5317.1  427.75  5395.7  436.60  5434.5  439.54  5588.3  450.79
#Mann=4,-1,0
  4675.9    0.16       0  4997.3    0.07       0  5003.3    0.16       0
  5434.5    0.05       0
Bank Sta=4934.7,5132.9
Exp/Cntr=0.3,0.1

Type RM Length L Ch R = 1,32966,396,396,396
BEGIN DESCRIPTION:
MILL RACE 48.0
END DESCRIPTION:
XS GIS Cut Line= 3
      2950374.99      6959625.01      2950225.00      6959925.00
      2949774.99      6960275.01
#Sta/Elev= 30
  4646.1  444.45  4660.1  443.95  4676.8  441.15  4682.4  441.32  4699.2  437.32
  4721.6  433.46  4727.1  433.52  4743.9  429.31  4757.9  427.10  4816.6  420.00
  4833.4  419.37  4848.3  417.39  4892.1  415.34  4988.7  416.82  4995.1  416.11
  5000.2  413.41  5000.7  412.61  5005.7  412.61  5006.2  413.41  5009.5  415.18
  5017.7  416.88  5081.9  416.57  5123.6  417.44  5167.0  415.99  5198.0  417.39
  5260.2  423.08  5339.8  433.20  5366.1  436.32  5488.2  444.23  5551.6  449.48
#Mann=4,-1,0
  4646.1    0.16       0  5000.2    0.07       0  5006.2    0.16       0
  5339.8    0.05       0
Bank Sta=4848.3,5198
Exp/Cntr=0.3,0.1

Type RM Length L Ch R = 1,32570,482,482,482
BEGIN DESCRIPTION:
MILL RACE 47.0
END DESCRIPTION:
XS GIS Cut Line= 3
      2950325.00      6959625.00      2950025.00      6959625.00
      2949625.01      6960224.99
#Sta/Elev= 30
  4650.5  442.32  4720.5  438.86  4830.5  425.09  4930.5  418.81  4945.6  414.84
  4948.0  414.04  4964.0  413.56  5000.1  413.85  5012.1  411.75  5012.6  410.95
  5017.6  410.95  5018.1  411.75  5022.6  413.65  5030.1  414.02  5138.3  411.83
  5196.3  414.84  5261.5  419.78  5275.0  422.10  5297.5  423.71  5353.3  429.61
  5432.7  436.12  5483.8  438.21  5491.3  439.49  5519.9  441.47  5571.0  444.95
  5592.0  445.58  5622.0  449.01  5628.0  448.79  5643.1  450.60  5671.6  452.33
#Mann=4,-1,0
  4650.5    0.16       0  5012.1    0.07       0  5018.1    0.16       0
  5353.3    0.05       0
Bank Sta=4945.6,5196.3
Exp/Cntr=0.3,0.1

Type RM Length L Ch R = 1,32088,383,383,383
BEGIN DESCRIPTION:
MILL RACE 46.0
END DESCRIPTION:
XS GIS Cut Line= 3
      2950325.02      6959024.98      2949725.00      6959525.00
      2949624.99      6959825.02
#Sta/Elev= 30
  4246.8  442.38  4289.1  441.63  4317.8  438.47  4332.1  434.57  4338.6  434.70
  4346.4  432.91  4502.6  417.80  4566.4  415.22  4595.0  415.65  4630.2  414.02
  4665.3  415.54  4701.8  413.17  4708.3  414.03  4800.7  411.50  4893.1  409.50
  4999.9  409.97  5011.2  408.62  5011.7  407.82  5017.2  408.62  5020.7  408.84
  5024.6  410.96  5034.3  411.50  5048.9  414.45  5070.0  416.40  5091.1  421.37
  5133.3  426.93  5143.8  429.69  5175.4  432.36  5239.5  431.81  5344.1  435.24
#Mann=4,-1,0
  4246.8    0.16       0  5011.2    0.07       0  5017.2    0.16       0
  5239.5    0.05       0
Bank Sta=4800.7,5034.3
Exp/Cntr=0.3,0.1

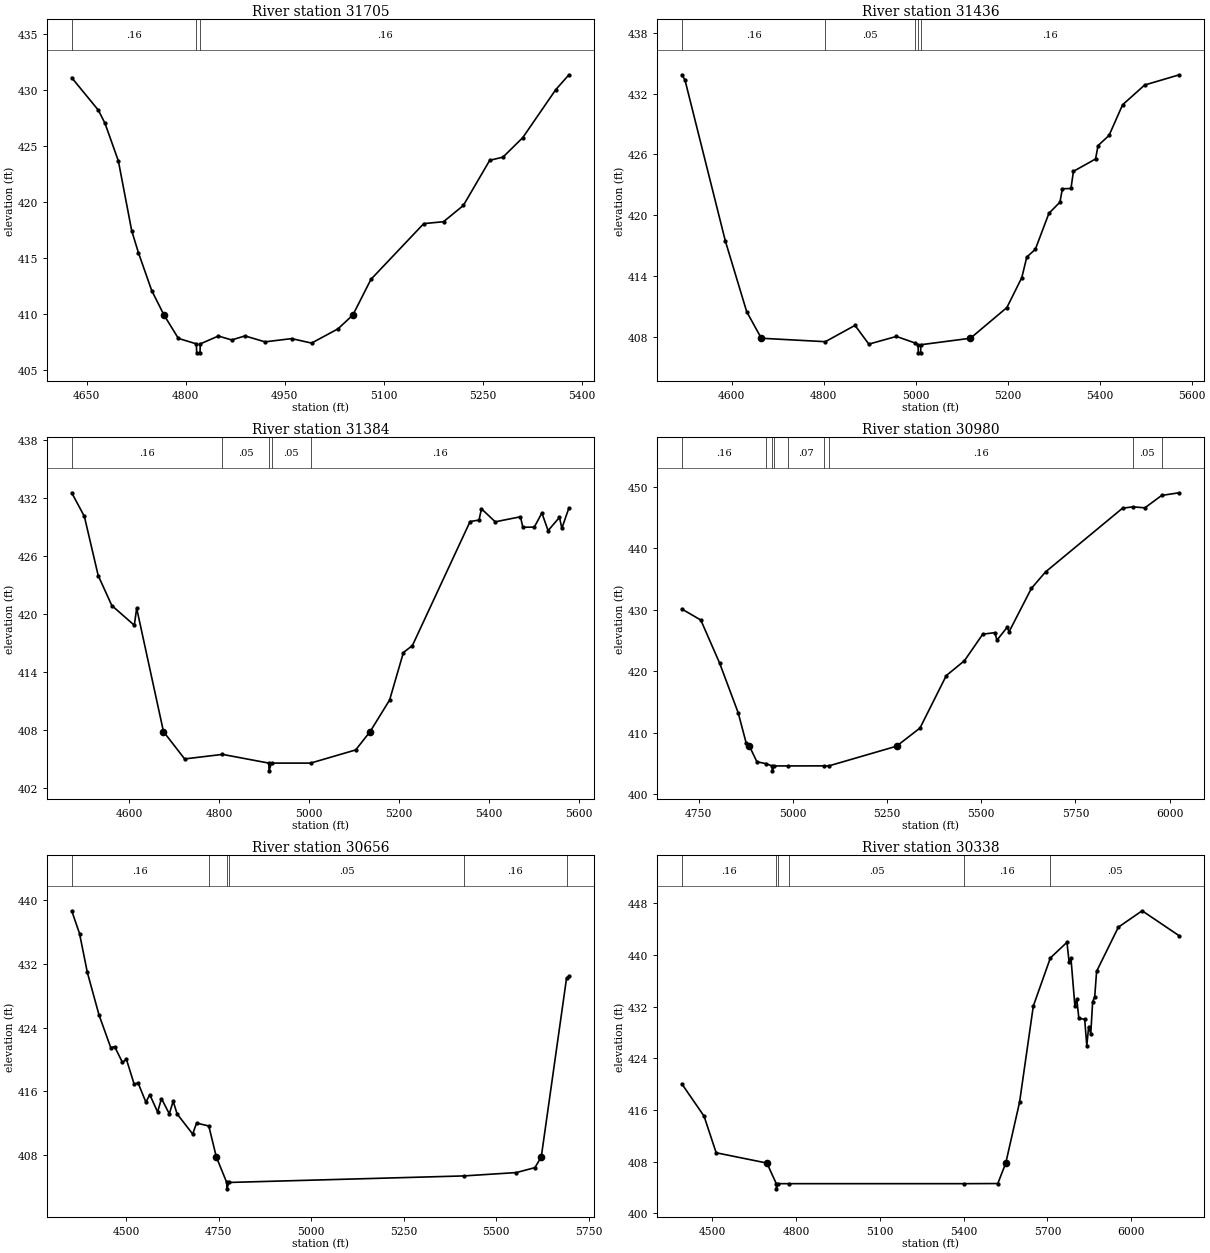
Type RM Length L Ch R = 1,31705,269,269,269
BEGIN DESCRIPTION:
MILL RACE 45.0
END DESCRIPTION:
XS GIS Cut Line= 3
      2949575.00      6958925.02      2949525.00      6959275.00
      2949525.00      6959674.97
#Sta/Elev= 30
  4627.1  431.12  4667.5  428.22  4677.6  427.04  4697.8  423.69  4718.0  417.47
  4728.1  415.52  4748.3  412.13  4766.9  409.95  4788.7  407.86  4816.0  407.37
  4816.5  406.57  4821.5  406.57  4822.0  407.37  4849.3  408.07  4869.5  407.72
  4889.7  408.08  4920.0  407.55  4960.4  407.84  4990.6  407.44  5030.6  408.71
  5053.2  409.95  5080.6  413.13  5160.6  418.10  5190.6  418.27  5220.6  419.72
  5260.6  423.75  5280.6  424.03  5310.6  425.77  5360.6  430.05  5380.6  431.38
#Mann=3,-1,0
  4627.1    0.16       0  4816.0    0.07       0  4822.0    0.16       0
Bank Sta=4766.9,5053.2
Exp/Cntr=0.3,0.1

Type RM Length L Ch R = 1,31436,52,52,52
BEGIN DESCRIPTION:
Mapping XS bb2ee626
END DESCRIPTION:
XS GIS Cut Line= 5
      2949310.75      6958741.38      2949271.70      6959006.09
      2949254.33      6959357.65      2949228.29      6959401.05
      2949072.67      6959781.47
#Sta/Elev= 30
  4491.4  433.86  4498.3  433.34  4586.0  417.47  4632.5  410.48  4664.3  407.86
  4803.5  407.52  4868.0  409.13  4898.1  407.28  4958.1  408.04  4999.3  407.38
  5005.2  407.22  5005.7  406.42  5010.7  406.42  5011.2  407.22  5119.0  407.86
  5198.3  410.89  5230.7  413.84  5241.6  415.88  5260.2  416.64  5289.6  420.18
  5313.6  421.29  5319.0  422.61  5337.6  422.64  5343.0  424.33  5391.1  425.55
  5396.5  426.87  5420.5  427.88  5449.9  430.90  5497.9  432.85  5572.6  433.85
#Mann=5,-1,0
  4491.4    0.16       0  4803.5    0.05       0  4999.3    0.16       0
  5005.2    0.07       0  5011.2    0.16       0
Bank Sta=4664.3,5119
Exp/Cntr=0.3,0.1

Type RM Length L Ch R = 1,31384,404,404,404
BEGIN DESCRIPTION:
Mapping XS 4a0fa439
END DESCRIPTION:
XS GIS Cut Line= 5
      2949239.15      6958717.45      2949206.59      6958873.71
      2949208.76      6959351.14      2949174.04      6959392.37
      2949033.51      6959781.52
#Sta/Elev= 30
  4472.7  432.52  4500.8  430.08  4531.5  423.97  4561.8  420.87  4611.8  418.83
  4617.0  420.59  4676.6  407.84  4723.6  405.02  4807.7  405.49  4910.6  404.59
  4911.1  403.79  4916.6  404.59  5003.5  404.59  5103.6  405.95  5135.8  407.85
  5179.0  411.11  5209.6  416.01  5229.7  416.74  5357.8  429.55  5377.7  429.70
  5383.0  430.87  5413.7  429.52  5469.7  430.04  5475.0  428.96  5500.4  428.97
  5517.3  430.43  5531.1  428.61  5556.4  429.98  5561.7  428.85  5577.4  430.96
#Mann=5,-1,0
  4472.7    0.16       0  4807.7    0.05       0  4910.6   0.035       0
  4916.6    0.05       0  5003.5    0.16       0
Bank Sta=4676.6,5135.8
Exp/Cntr=0.3,0.1

Type RM Length L Ch R = 1,30980,324,324,324
BEGIN DESCRIPTION:
MILL RACE 43.0
END DESCRIPTION:
XS GIS Cut Line= 3
      2949125.00      6958725.00      2948925.00      6958975.00
      2948623.10      6959927.86
#Sta/Elev= 30
  4705.2  430.14  4755.6  428.34  4805.3  421.37  4854.9  413.23  4875.7  408.40
  4884.7  407.80  4904.5  405.27  4927.9  404.97  4944.7  404.59  4945.2  403.79
  4950.7  404.59  4987.3  404.59  5082.9  404.60  5095.7  404.60  5275.1  407.80
  5337.4  410.76  5407.2  419.30  5455.4  421.72  5504.0  426.04  5536.3  426.29
  5541.6  425.06  5568.6  427.15  5573.9  426.44  5633.2  433.51  5670.7  436.18
  5875.0  446.55  5902.6  446.77  5934.3  446.61  5978.9  448.63  6024.9  449.06
#Mann=9,-1,0
  4705.2    0.16       0  4927.9    0.05       0  4944.7    0.07       0
  4950.7    0.05       0  4987.3    0.07       0  5082.9    0.05       0
  5095.7    0.16       0  5902.6    0.05       0  5978.9    0.16       0
Bank Sta=4884.7,5275.1
Exp/Cntr=0.3,0.1

Type RM Length L Ch R = 1,30656,318,318,318
BEGIN DESCRIPTION:
MILL RACE 42.0
END DESCRIPTION:
XS GIS Cut Line= 3
      2949275.03      6958574.99      2948675.00      6958775.00
      2948225.01      6959324.98
#Sta/Elev= 30
  4353.2  438.66  4374.3  435.81  4395.4  430.93  4427.0  425.59  4458.6  421.50
  4469.2  421.62  4490.3  419.64  4500.8  420.06  4521.9  416.91  4532.4  417.08
  4553.5  414.67  4564.1  415.60  4585.1  413.43  4595.7  415.10  4616.8  413.20
  4627.3  414.78  4637.8  413.19  4680.0  410.66  4690.5  412.04  4723.5  411.67
  4743.8  407.79  4771.9  404.59  4772.4  403.79  4777.9  404.59  5412.4  405.41
  5554.2  405.83  5604.4  406.45  5621.6  407.79  5689.9  430.22  5696.3  430.48
#Mann=6,-1,0
  4353.2    0.16       0  4723.5    0.05       0  4771.9   0.033       0
  4777.9    0.05       0  5412.4    0.16       0  5689.9    0.05       0
Bank Sta=4743.8,5621.6
Exp/Cntr=0.3,0.1

Type RM Length L Ch R = 1,30338,453,453,453
BEGIN DESCRIPTION:
MILL RACE 41.0
END DESCRIPTION:
XS GIS Cut Line= 3
      2948481.61      6958066.73      2948372.61      6958665.59
      2947591.82      6959538.15
#Sta/Elev= 30
  4391.3  420.04  4470.9  415.04  4514.3  409.37  4695.8  407.78  4729.5  404.59
  4730.0  403.79  4735.9  404.59  4774.3  404.59  5403.0  404.59  5522.3  404.61
  5550.8  407.78  5600.1  417.18  5649.4  432.08  5710.4  439.52  5769.8  441.94
  5777.3  438.96  5784.0  439.51  5798.2  432.10  5804.9  433.14  5812.4  430.20
  5833.3  430.01  5840.8  425.94  5847.5  428.88  5855.0  427.78  5861.7  432.73
  5869.2  433.52  5875.9  437.45  5953.7  444.28  6038.9  446.82  6170.9  442.97
#Mann=6,-1,0
  4391.3    0.16       0  4729.5   0.033       0  4735.9    0.16       0
  4774.3    0.05       0  5403.0    0.16       0  5710.4    0.05       0
Bank Sta=4695.8,5550.8
Exp/Cntr=0.3,0.1

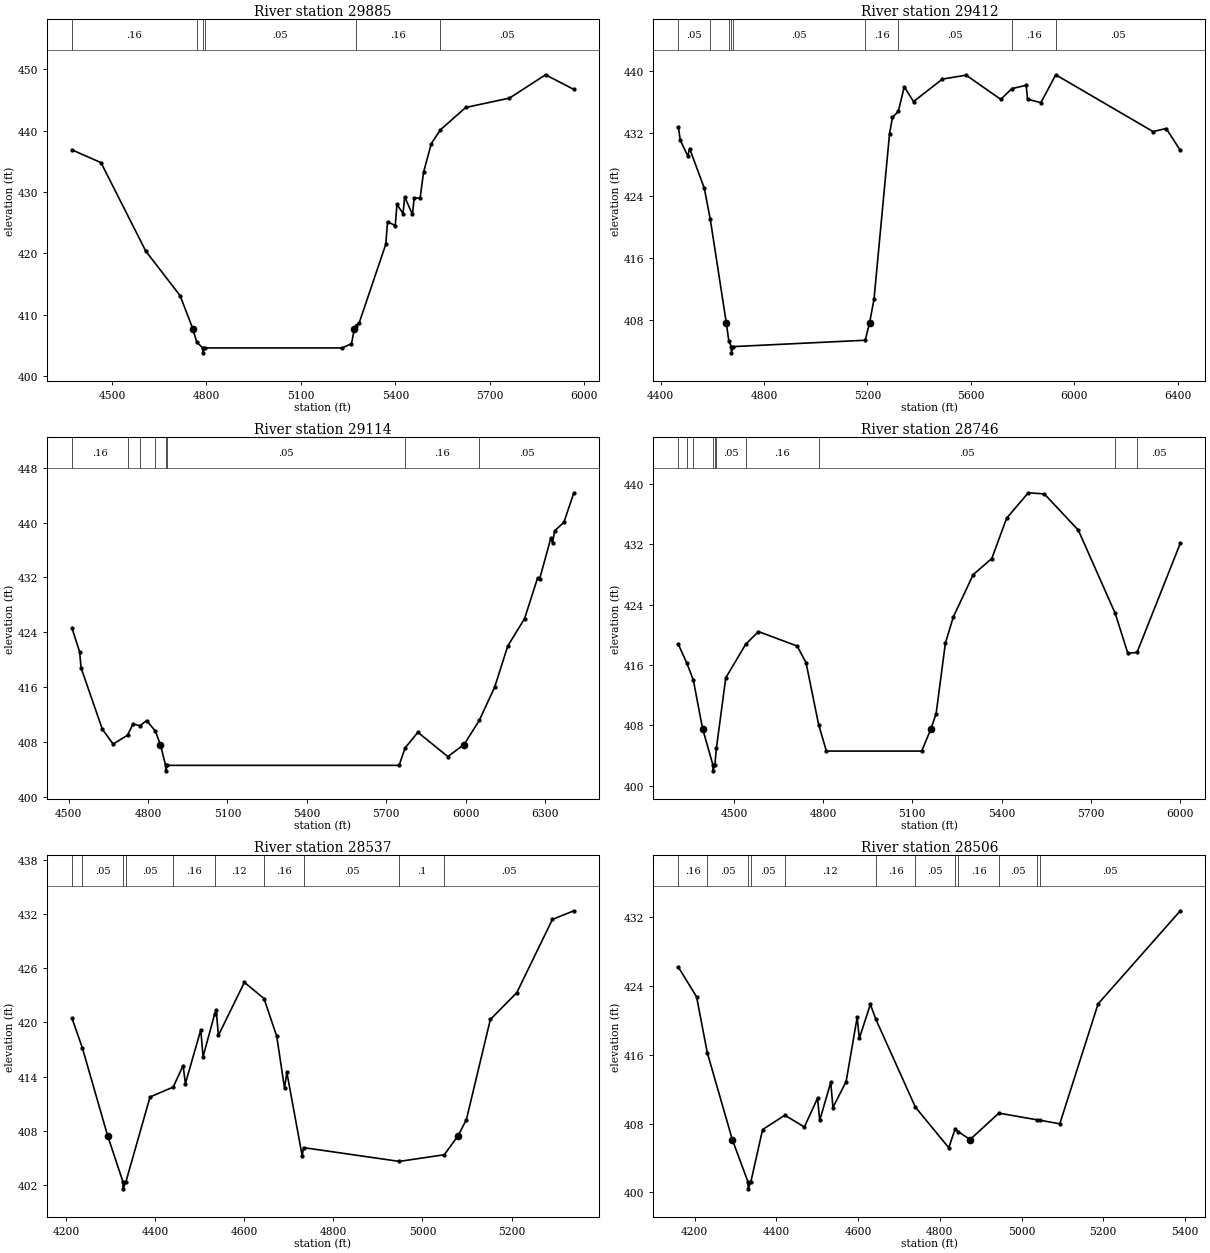
Type RM Length L Ch R = 1,29885,473,473,473
BEGIN DESCRIPTION:
MILL RACE 40.0
END DESCRIPTION:
XS GIS Cut Line= 3
      2948242.91      6957966.90      2947944.43      6958518.30
      2947596.36      6959420.49
#Sta/Elev= 30
  4373.0  436.87  4465.3  434.79  4607.1  420.40  4716.4  413.12  4756.8  407.72
  4769.2  405.56  4788.2  404.59  4788.7  403.79  4794.9  404.59  5230.7  404.59
  5260.7  405.27  5270.0  407.71  5273.6  408.23  5285.3  408.69  5369.9  421.51
  5375.2  425.17  5399.8  424.53  5405.2  427.98  5424.4  426.50  5429.8  429.22
  5454.4  426.34  5459.8  429.01  5478.8  429.04  5489.7  433.24  5514.3  437.89
  5543.0  440.13  5623.5  443.78  5762.6  445.31  5877.1  449.11  5967.0  446.72
#Mann=6,-1,0
  4373.0    0.16       0  4769.2    0.05       0  4788.2   0.033       0
  4794.9    0.05       0  5273.6    0.16       0  5543.0    0.05       0
Bank Sta=4756.8,5270
Exp/Cntr=0.3,0.1

Type RM Length L Ch R = 1,29412,298,298,298
BEGIN DESCRIPTION:
MILL RACE 39.0
END DESCRIPTION:
XS GIS Cut Line= 3
      2947824.98      6957875.03      2947524.93      6958313.36
      2947257.65      6959698.72
#Sta/Elev= 30
  4468.8  432.77  4476.2  431.10  4505.1  429.10  4512.1  430.06  4569.0  424.95
  4591.9  421.00  4654.1  407.64  4663.7  405.36  4673.3  404.59  4673.8  403.79
  4680.0  404.59  5191.6  405.41  5208.4  407.64  5225.7  410.69  5285.8  431.98
  5297.0  434.06  5319.6  434.83  5342.8  438.00  5378.5  436.09  5490.5  438.99
  5582.2  439.49  5716.0  436.38  5758.9  437.76  5814.6  438.19  5819.7  436.39
  5871.5  435.96  5928.8  439.54  6305.3  432.24  6356.2  432.63  6410.9  429.82
#Mann=9,-1,0
  4468.8    0.05       0  4591.9    0.16       0  4663.7    0.05       0
  4673.3   0.033       0  4680.0    0.05       0  5191.6    0.16       0
  5319.6    0.05       0  5758.9    0.16       0  5928.8    0.05       0
Bank Sta=4654.1,5208.4
Exp/Cntr=0.3,0.1

Type RM Length L Ch R = 1,29114,368,368,368
BEGIN DESCRIPTION:
Mapping XS 43888954
END DESCRIPTION:
XS GIS Cut Line= 3
      2947743.78      6957949.57      2947340.11      6958084.12
      2946276.72      6959099.77
#Sta/Elev= 30
  4512.4  424.61  4541.4  421.15  4546.7  418.83  4627.1  409.87  4667.9  407.69
  4722.3  408.98  4743.0  410.62  4769.5  410.37  4794.4  411.12  4827.5  409.59
  4846.5  407.62  4866.2  404.59  4866.7  403.79  4872.9  404.59  5748.3  404.59
  5770.9  407.13  5819.1  409.41  5932.3  405.87  5993.5  407.62  6051.0  411.14
  6109.1  415.98  6158.8  422.00  6222.3  426.00  6272.0  431.98  6278.9  431.75
  6321.4  437.72  6328.3  437.03  6335.5  438.78  6370.7  440.02  6408.4  444.34
#Mann=8,-1,0
  4512.4    0.16       0  4722.3    0.05       0  4769.5    0.16       0
  4827.5    0.05       0  4866.2   0.033       0  4872.9    0.05       0
  5770.9    0.16       0  6051.0    0.05       0
Bank Sta=4846.5,5993.5
Exp/Cntr=0.3,0.1

Type RM Length L Ch R = 1,28746,209,209,209
BEGIN DESCRIPTION:
Mapping XS 7fdf793a
END DESCRIPTION:
XS GIS Cut Line= 3
      2947674.32      6957936.55      2947010.25      6957927.87
      2946024.97      6958210.00
#Sta/Elev= 30
  4312.7  418.72  4341.5  416.20  4363.0  413.99  4394.1  407.55  4428.7  402.77
  4429.2  401.97  4435.4  402.77  4440.5  404.95  4472.0  414.30  4539.5  418.77
  4582.0  420.43  4712.1  418.52  4742.1  416.32  4784.6  408.09  4810.6  404.59
  5131.5  404.59  5162.5  407.55  5179.9  409.54  5211.1  418.90  5238.0  422.39
  5304.7  427.98  5367.2  430.11  5417.2  435.46  5490.0  438.83  5544.0  438.68
  5658.4  433.88  5782.7  422.83  5825.1  417.55  5856.0  417.67  6001.7  432.14
#Mann=10,-1,0
  4312.7    0.16       0  4341.5    0.05       0  4363.0    0.16       0
  4428.7   0.033       0  4435.4    0.16       0  4440.5    0.05       0
  4539.5    0.16       0  4784.6    0.05       0  5782.7    0.16       0
  5856.0    0.05       0
Bank Sta=4394.1,5162.5
Exp/Cntr=0.3,0.1

Type RM Length L Ch R = 1,28537,31,31,31
BEGIN DESCRIPTION:
Mapping XS a22d6017
END DESCRIPTION:
XS GIS Cut Line= 5
      2947668.71      6957916.40      2947147.93      6957774.05
      2947002.09      6957739.33      2946866.68      6957753.22
      2946602.81      6957899.04
#Sta/Elev= 30
  4212.6  420.49  4236.0  417.18  4292.6  407.47  4327.0  402.36  4327.5  401.56
  4333.9  402.36  4388.0  411.74  4440.0  412.84  4462.3  415.22  4467.4  413.23
  4502.0  419.17  4507.1  416.20  4533.1  420.93  4536.5  421.42  4541.6  418.57
  4600.0  424.45  4644.0  422.65  4672.6  418.47  4690.1  412.72  4695.3  414.47
  4729.8  405.21  4732.8  406.13  4947.9  404.60  5049.0  405.34  5080.2  407.47
  5098.6  409.23  5152.4  420.33  5211.8  423.30  5291.8  431.42  5340.0  432.38
#Mann=10,-1,0
  4212.6    0.16       0  4236.0    0.05       0  4327.0    0.07       0
  4333.9    0.05       0  4440.0    0.16       0  4533.1    0.12       0
  4644.0    0.16       0  4732.8    0.05       0  4947.9     0.1       0
  5049.0    0.05       0
Bank Sta=4292.6,5080.2
Exp/Cntr=0.3,0.1

Type RM Length L Ch R = 1,28506,66,66,66
BEGIN DESCRIPTION:
Mapping XS fd9054e9
END DESCRIPTION:
XS GIS Cut Line= 5
      2947713.90      6957912.94      2947231.26      6957760.16
      2947019.45      6957718.50      2946877.09      6957718.50
      2946533.37      6957836.54
#Sta/Elev= 30
  4160.5  426.17  4205.0  422.73  4231.1  416.24  4292.3  406.15  4330.7  401.22
  4331.2  400.42  4337.6  401.22  4366.5  407.31  4420.9  408.97  4468.6  407.61
  4500.9  410.95  4506.2  408.37  4533.2  412.80  4538.5  409.87  4570.8  412.88
  4597.8  420.35  4603.1  417.90  4630.1  421.86  4643.6  420.11  4740.3  409.91
  4822.0  405.19  4837.7  407.42  4845.1  407.06  4873.9  406.15  4944.7  409.22
  5037.5  408.44  5044.9  408.39  5093.5  407.98  5187.3  421.92  5388.4  432.73
#Mann=12,-1,0
  4160.5    0.16       0  4231.1    0.05       0  4330.7    0.03       0
  4337.6    0.05       0  4420.9    0.12       0  4643.6    0.16       0
  4740.3    0.05       0  4837.7    0.12       0  4845.1    0.16       0
  4944.7    0.05       0  5037.5     0.1       0  5044.9    0.05       0
Bank Sta=4292.3,4873.9
Exp/Cntr=0.3,0.1

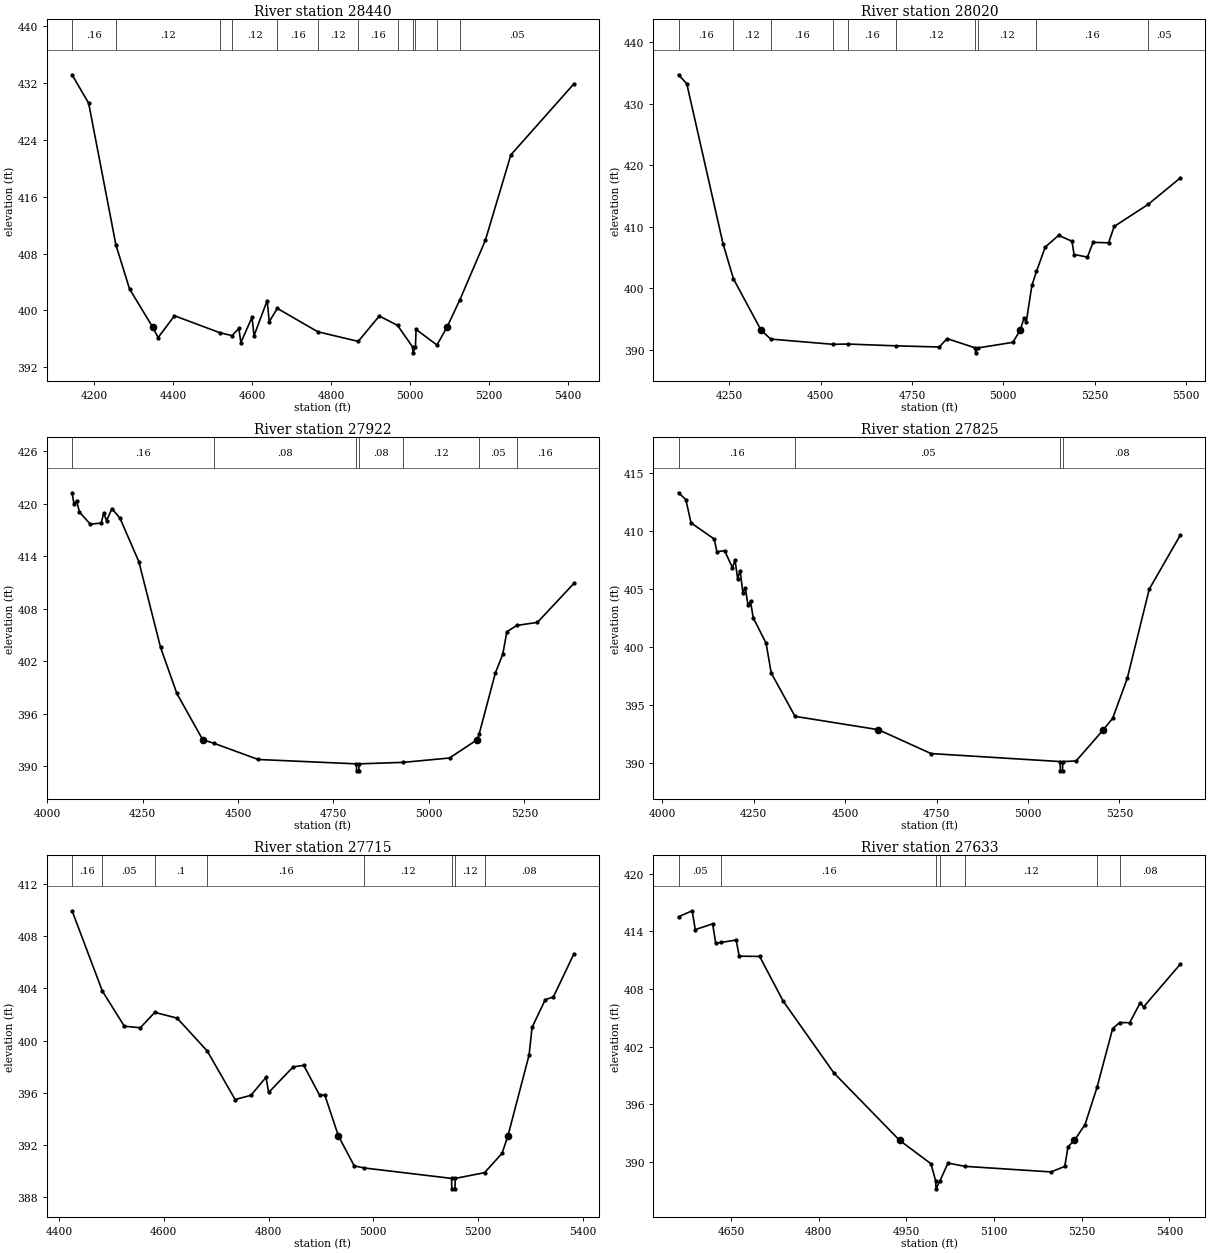
Type RM Length L Ch R = 1,28440,420,420,420
BEGIN DESCRIPTION:
Mapping XS cc8b65f6
END DESCRIPTION:
XS GIS Cut Line= 5
      2947755.54      6957843.49      2947460.43      6957763.64
      2947061.12      6957645.58      2946849.31      6957666.41
      2946536.83      6957791.41
#Sta/Elev= 30
  4144.2  433.13  4186.2  429.14  4255.3  409.21  4289.8  403.03  4348.2  397.68
  4362.3  396.19  4403.7  399.25  4518.6  396.87  4549.6  396.46  4566.8  397.47
  4572.0  395.48  4600.1  399.03  4605.3  396.45  4638.6  401.39  4643.8  398.42
  4664.3  400.29  4766.9  397.00  4869.3  395.65  4922.7  399.22  4969.1  397.89
  5007.4  394.84  5007.9  394.04  5014.3  394.84  5015.9  397.33  5068.8  395.14
  5094.5  397.68  5126.9  401.50  5191.3  409.84  5256.1  421.87  5415.7  431.85
#Mann=12,-1,0
  4144.2    0.16       0  4255.3    0.12       0  4518.6    0.16       0
  4549.6    0.12       0  4664.3    0.16       0  4766.9    0.12       0
  4869.3    0.16       0  4969.1    0.05       0  5007.4    0.03       0
  5014.3    0.05       0  5068.8    0.16       0  5126.9    0.05       0
Bank Sta=4348.2,5094.5
Exp/Cntr=0.3,0.1

Type RM Length L Ch R = 1,28020,98,98,98
BEGIN DESCRIPTION:
MILL RACE 37.0
END DESCRIPTION:
XS GIS Cut Line= 3
      2947775.03      6957825.02      2947025.00      6957325.00
      2946625.02      6957574.99
#Sta/Elev= 30
  4111.3  434.73  4133.9  433.26  4233.0  407.24  4261.6  401.51  4337.3  393.13
  4363.6  391.70  4533.4  390.85  4575.1  390.89  4705.7  390.60  4824.9  390.41
  4846.0  391.78  4923.6  390.26  4924.1  389.46  4930.5  390.26  5026.3  391.17
  5046.1  393.13  5056.9  395.17  5062.8  394.47  5078.2  400.44  5090.8  402.71
  5114.7  406.68  5151.3  408.59  5187.8  407.63  5193.7  405.47  5230.3  405.05
  5245.6  407.45  5288.1  407.37  5303.4  410.03  5396.8  413.65  5484.4  417.94
#Mann=10,-1,0
  4111.3    0.16       0  4261.6    0.12       0  4363.6    0.16       0
  4533.4    0.12       0  4575.1    0.16       0  4705.7    0.12       0
  4923.6    0.07       0  4930.5    0.12       0  5090.8    0.16       0
  5396.8    0.05       0
Bank Sta=4337.3,5046.1
Exp/Cntr=0.3,0.1

Type RM Length L Ch R = 1,27922,97,97,97
BEGIN DESCRIPTION:
Mapping XS 4536a792
END DESCRIPTION:
XS GIS Cut Line= 4
      2947923.94      6957543.13      2947712.16      6957303.57
      2947156.61      6957261.90      2946719.59      6957275.77
#Sta/Elev= 30
  4065.4  421.27  4070.5  419.94  4077.1  420.37  4084.7  419.07  4113.1  417.68
  4141.6  417.80  4148.3  418.93  4155.8  418.08  4169.7  419.46  4190.9  418.36
  4240.3  413.38  4297.2  403.56  4339.8  398.30  4407.7  392.99  4437.3  392.59
  4552.8  390.74  4810.1  390.24  4810.6  389.44  4816.5  389.44  4817.0  390.24
  4932.9  390.41  5053.9  390.91  5125.8  392.99  5131.2  393.61  5174.0  400.65
  5193.3  402.78  5204.0  405.36  5230.3  406.09  5284.0  406.43  5379.5  410.89
#Mann=7,-1,0
  4065.4    0.16       0  4437.3    0.08       0  4810.1    0.07       0
  4817.0    0.08       0  4932.9    0.12       0  5131.2    0.05       0
  5230.3    0.16       0
Bank Sta=4407.7,5125.8
Exp/Cntr=0.3,0.1

Type RM Length L Ch R = 1,27825,110,110,110
BEGIN DESCRIPTION:
Mapping XS ca047c95
END DESCRIPTION:
XS GIS Cut Line= 4
      2947993.40      6957504.94      2947739.94      6957234.12
      2947191.33      6957192.46      2946739.94      6957192.46
#Sta/Elev= 30
  4044.3  413.33  4064.3  412.74  4078.5  410.73  4142.0  409.34  4149.3  408.24
  4170.3  408.34  4191.8  406.86  4198.7  407.54  4206.0  405.92  4212.8  406.62
  4220.2  404.71  4227.0  405.13  4234.3  403.63  4241.2  403.96  4248.5  402.55
  4283.7  400.36  4297.8  397.78  4363.0  394.04  4590.9  392.89  4734.9  390.83
  5088.2  390.14  5088.7  389.34  5094.7  389.34  5095.2  390.14  5131.7  390.19
  5206.4  392.89  5231.7  393.87  5271.7  397.32  5331.7  405.01  5416.8  409.68
#Mann=4,-1,0
  4044.3    0.16       0  4363.0    0.05       0  5088.2    0.04       0
  5095.2    0.08       0
Bank Sta=4590.9,5206.4
Exp/Cntr=0.3,0.1

Type RM Length L Ch R = 1,27715,82,82,82
BEGIN DESCRIPTION:
Mapping XS 82dc17ff
END DESCRIPTION:
XS GIS Cut Line= 3
      2947724.03      6957014.84      2947153.32      6957084.28
      2946782.23      6957179.76
#Sta/Elev= 30
  4424.8  409.95  4482.7  403.79  4524.6  401.10  4555.1  400.98  4582.7  402.16
  4625.3  401.72  4682.7  399.21  4736.1  395.48  4766.3  395.80  4795.1  397.18
  4800.2  396.02  4846.9  397.98  4867.1  398.10  4897.3  395.82  4907.4  395.82
  4933.3  392.69  4963.5  390.39  4982.8  390.23  5149.4  389.43  5149.9  388.63
  5155.9  388.63  5156.4  389.43  5212.4  389.87  5245.8  391.35  5257.0  392.69
  5297.4  398.89  5303.1  401.01  5328.4  403.14  5343.8  403.34  5382.9  406.64
#Mann=8,-1,0
  4424.8    0.16       0  4482.7    0.05       0  4582.7     0.1       0
  4682.7    0.16       0  4982.8    0.12       0  5149.4    0.07       0
  5156.4    0.12       0  5212.4    0.08       0
Bank Sta=4933.3,5257
Exp/Cntr=0.3,0.1

Type RM Length L Ch R = 1,27633,88,88,88
BEGIN DESCRIPTION:
Mapping XS 4db33c5a
END DESCRIPTION:
XS GIS Cut Line= 3
      2947542.04      6956893.84      2947149.66      6956998.01
      2946733.00      6957175.09
#Sta/Elev= 30
  4559.9  415.52  4583.3  416.14  4588.5  414.18  4618.3  414.78  4623.5  412.76
  4633.3  412.85  4658.5  413.10  4663.7  411.42  4698.7  411.39  4738.8  406.76
  4825.8  399.27  4938.3  392.26  4991.9  389.83  5000.0  388.02  5000.5  387.22
  5007.0  388.02  5021.0  389.90  5050.0  389.56  5197.4  388.98  5220.8  389.55
  5226.5  391.61  5237.3  392.26  5255.5  393.90  5276.2  397.81  5302.8  403.89
  5314.9  404.52  5331.9  404.50  5350.1  406.59  5355.6  406.13  5418.6  410.59
#Mann=7,-1,0
  4559.9    0.05       0  4633.3    0.16       0  5000.0    0.07       0
  5007.0    0.16       0  5050.0    0.12       0  5276.2    0.16       0
  5314.9    0.08       0
Bank Sta=4938.3,5237.3
Exp/Cntr=0.3,0.1

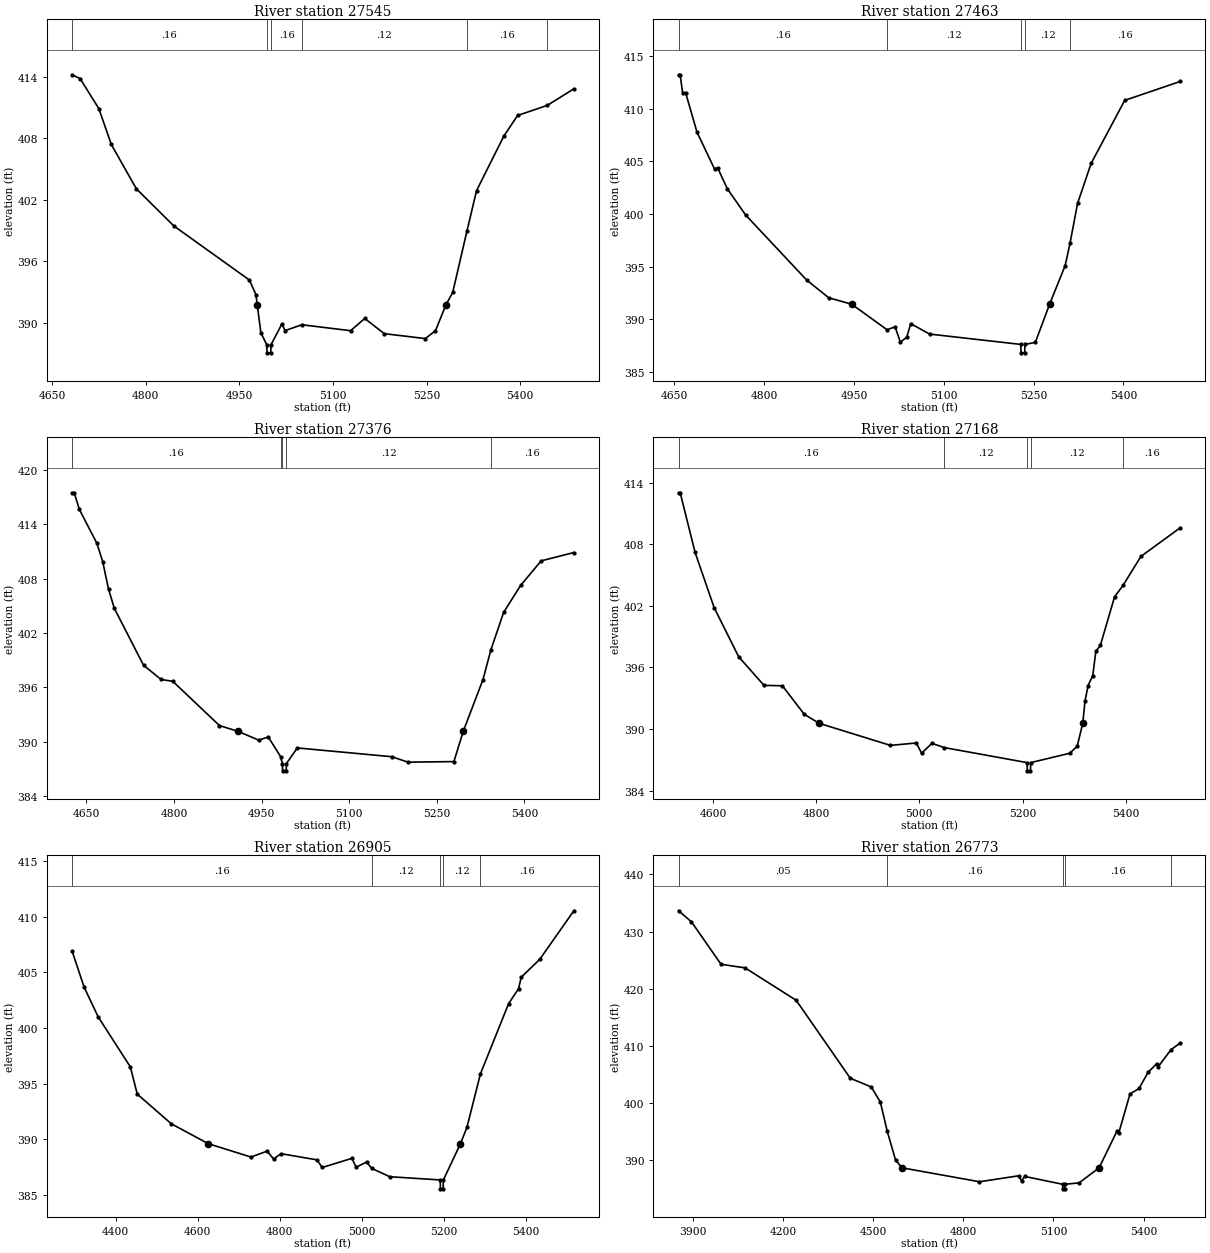
Type RM Length L Ch R = 1,27545,82,82,82
BEGIN DESCRIPTION:
Mapping XS 540871a3
END DESCRIPTION:
XS GIS Cut Line= 4
      2947437.89      6956909.23      2947182.69      6956916.18
      2947068.11      6956949.16      2946689.78      6957152.21
#Sta/Elev= 30
  4681.9  414.18  4694.8  413.81  4724.8  410.88  4744.8  407.38  4784.8  403.07
  4844.9  399.44  4966.0  394.16  4976.4  392.75  4978.5  391.77  4984.4  389.01
  4993.7  387.86  4994.2  387.06  5000.2  387.06  5000.7  387.86  5018.0  389.87
  5023.3  389.23  5050.1  389.80  5128.1  389.22  5150.8  390.41  5182.1  388.93
  5247.9  388.45  5264.1  389.22  5281.1  391.77  5291.7  392.95  5314.5  398.93
  5329.9  402.88  5373.7  408.21  5395.7  410.21  5443.4  411.20  5485.8  412.81
#Mann=6,-1,0
  4681.9    0.16       0  4993.7    0.07       0  5000.7    0.16       0
  5050.1    0.12       0  5314.5    0.16       0  5443.4    0.08       0
Bank Sta=4978.5,5281.1
Exp/Cntr=0.3,0.1

Type RM Length L Ch R = 1,27463,87,87,87
BEGIN DESCRIPTION:
Mapping XS 0e5a4508
END DESCRIPTION:
XS GIS Cut Line= 4
      2947415.32      6956881.45      2947167.07      6956836.32
      2946950.06      6956909.23      2946668.56      6957128.55
#Sta/Elev= 30
  4657.1  413.21  4659.8  413.21  4663.9  411.50  4668.9  411.51  4687.9  407.77
  4717.2  404.27  4722.3  404.39  4738.7  402.38  4769.2  399.90  4870.9  393.74
  4907.9  392.05  4946.5  391.43  5005.4  389.01  5018.8  389.29  5027.6  387.83
  5038.2  388.30  5045.0  389.59  5076.5  388.60  5228.7  387.62  5229.2  386.82
  5235.2  386.82  5235.7  387.62  5253.0  387.81  5276.8  391.43  5302.8  395.09
  5311.1  397.26  5323.6  401.01  5346.2  404.80  5402.3  410.78  5495.2  412.58
#Mann=5,-1,0
  4657.1    0.16       0  5005.4    0.12       0  5228.7    0.07       0
  5235.7    0.12       0  5311.1    0.16       0
Bank Sta=4946.5,5276.8
Exp/Cntr=0.3,0.1

Type RM Length L Ch R = 1,27376,208,208,208
BEGIN DESCRIPTION:
Mapping XS eb26c1a9
END DESCRIPTION:
XS GIS Cut Line= 4
      2947427.44      6956758.19      2947134.08      6956758.19
      2946960.47      6956850.21      2946668.55      6957076.49
#Sta/Elev= 30
  4625.6  417.50  4629.3  417.50  4638.0  415.67  4668.0  411.93  4678.0  409.91
  4688.0  406.86  4698.0  404.73  4748.0  398.45  4778.0  396.88  4798.0  396.68
  4878.0  391.79  4910.3  391.14  4945.2  390.18  4961.5  390.53  4982.6  388.37
  4985.7  387.59  4986.2  386.79  4992.2  386.79  4992.7  387.59  5011.2  389.32
  5173.0  388.35  5200.7  387.75  5279.4  387.81  5295.3  391.14  5329.2  396.87
  5342.8  400.16  5364.5  404.28  5393.5  407.26  5428.8  409.98  5484.8  410.90
#Mann=5,-1,0
  4625.6    0.16       0  4982.6    0.12       0  4985.7    0.07       0
  4992.7    0.12       0  5342.8    0.16       0
Bank Sta=4910.3,5295.3
Exp/Cntr=0.3,0.1

Type RM Length L Ch R = 1,27168,263,263,263
BEGIN DESCRIPTION:
Mapping XS 71658a1b
END DESCRIPTION:
XS GIS Cut Line= 4
      2947396.25      6956706.11      2947064.64      6956627.98
      2946908.39      6956647.08      2946648.97      6957044.86
#Sta/Elev= 30
  4533.0  413.00  4536.2  413.00  4565.1  407.19  4602.2  401.80  4649.6  397.04
  4698.7  394.25  4734.4  394.21  4776.7  391.44  4805.4  390.56  4943.8  388.41
  4994.2  388.64  5004.3  387.64  5024.4  388.61  5047.7  388.20  5208.9  386.73
  5209.4  385.93  5215.4  385.93  5215.9  386.73  5291.3  387.64  5306.0  388.32
  5316.8  390.56  5321.1  392.69  5327.1  394.23  5336.2  395.21  5342.2  397.56
  5351.0  398.15  5378.4  402.86  5395.0  403.99  5429.7  406.81  5506.0  409.60
#Mann=5,-1,0
  4533.0    0.16       0  5047.7    0.12       0  5208.9    0.07       0
  5215.9    0.12       0  5395.0    0.16       0
Bank Sta=4805.4,5316.8
Exp/Cntr=0.3,0.1

Type RM Length L Ch R = 1,26905,132,132,132
BEGIN DESCRIPTION:
Mapping XS 75789ff5
END DESCRIPTION:
XS GIS Cut Line= 4
      2947378.06      6956577.99      2946881.07      6956439.09
      2946735.67      6956541.09      2946633.86      6957060.98
#Sta/Elev= 30
  4294.0  406.92  4323.4  403.67  4357.6  401.00  4436.2  396.49  4452.9  394.05
  4536.0  391.38  4626.2  389.59  4730.2  388.39  4769.6  388.92  4785.2  388.22
  4803.7  388.69  4890.7  388.14  4903.9  387.45  4976.2  388.27  4986.7  387.48
  5012.0  387.94  5024.5  387.37  5068.6  386.62  5191.5  386.33  5192.2  385.53
  5198.7  385.53  5199.3  386.33  5240.9  389.59  5256.6  391.05  5289.6  395.87
  5358.5  402.20  5382.7  403.54  5389.0  404.56  5434.2  406.17  5517.4  410.54
#Mann=5,-1,0
  4294.0    0.16       0  5024.5    0.12       0  5191.5    0.07       0
  5199.3    0.12       0  5289.6    0.16       0
Bank Sta=4626.2,5240.9
Exp/Cntr=0.3,0.1

Type RM Length L Ch R = 1,26773,513,513,513
BEGIN DESCRIPTION:
MILL RACE 35.0
END DESCRIPTION:
XS GIS Cut Line= 3
      2946620.58      6955393.49      2946603.66      6956540.87
      2946564.35      6957061.89
#Sta/Elev= 30
  3852.5  433.64  3895.5  431.71  3994.0  424.28  4074.0  423.65  4244.0  417.98
  4424.1  404.34  4494.1  402.81  4524.1  400.18  4547.0  395.08  4574.6  390.05
  4596.3  388.67  4854.1  386.23  4984.1  387.27  4994.1  386.41  5004.6  387.16
  5130.6  385.79  5131.3  384.99  5137.8  384.99  5138.4  385.79  5185.6  386.03
  5252.2  388.67  5312.3  395.17  5317.3  394.71  5355.1  401.60  5385.2  402.55
  5415.3  405.39  5443.9  406.88  5448.9  406.35  5491.1  409.32  5522.5  410.53
#Mann=5,-1,0
  3852.5    0.05       0  4547.0    0.16       0  5130.6    0.07       0
  5138.4    0.16       0  5491.1    0.05       0
Bank Sta=4596.3,5252.2
Exp/Cntr=0.3,0.1