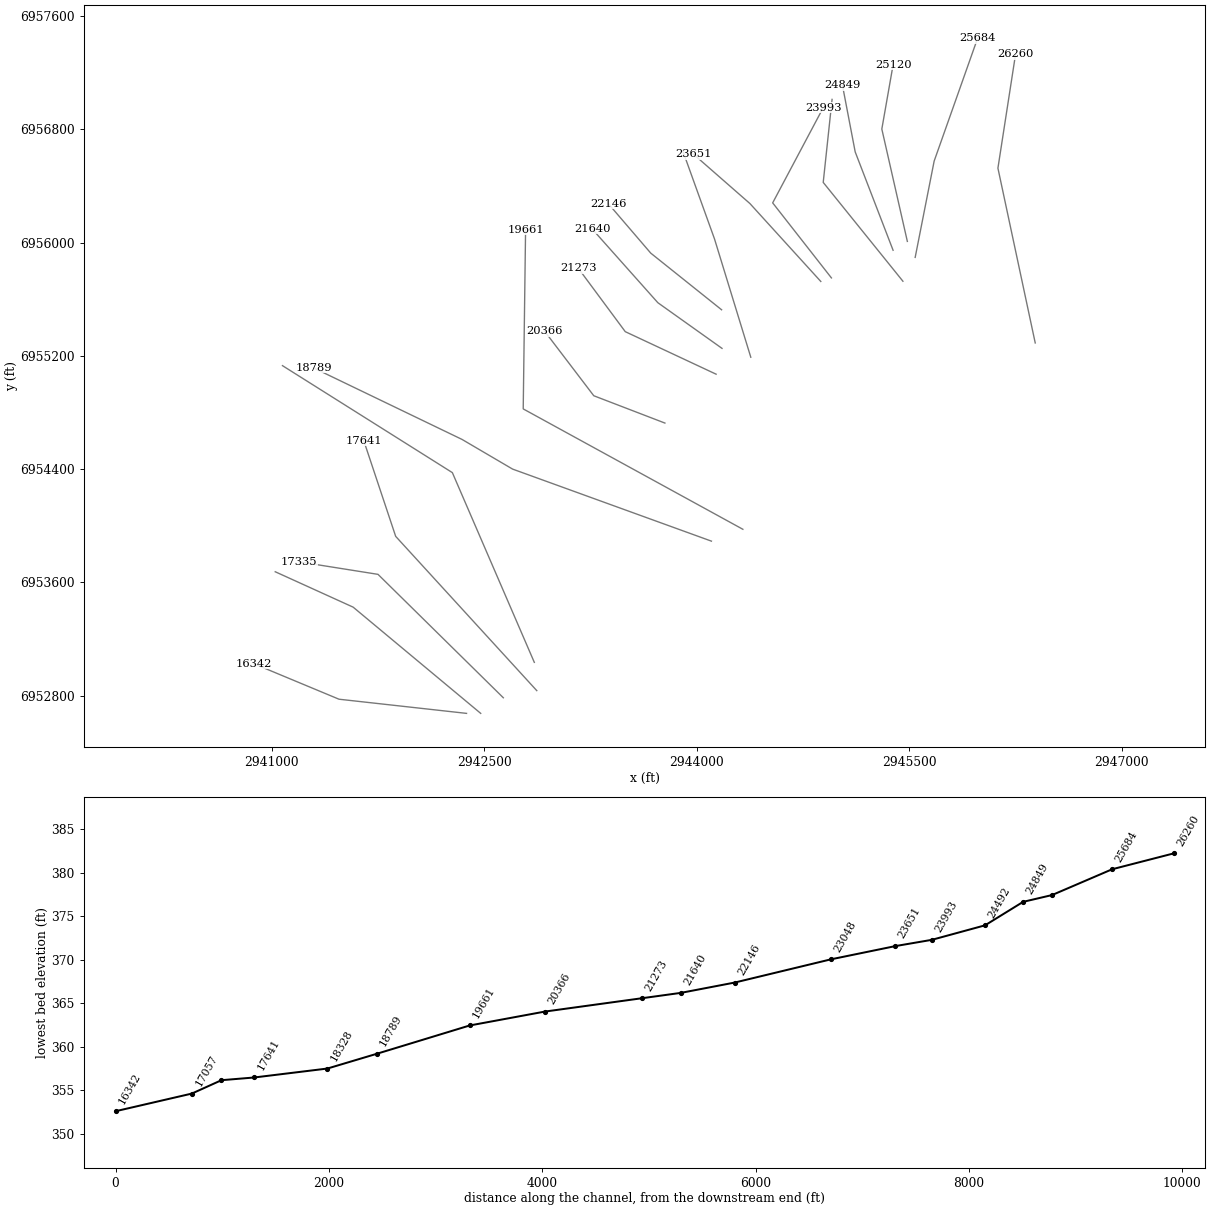
HEC-RAS study MILL RACE.prj: MILL RACE Base Level Engineering

--- MILL RACE.g01 (geometry) --- (continued)

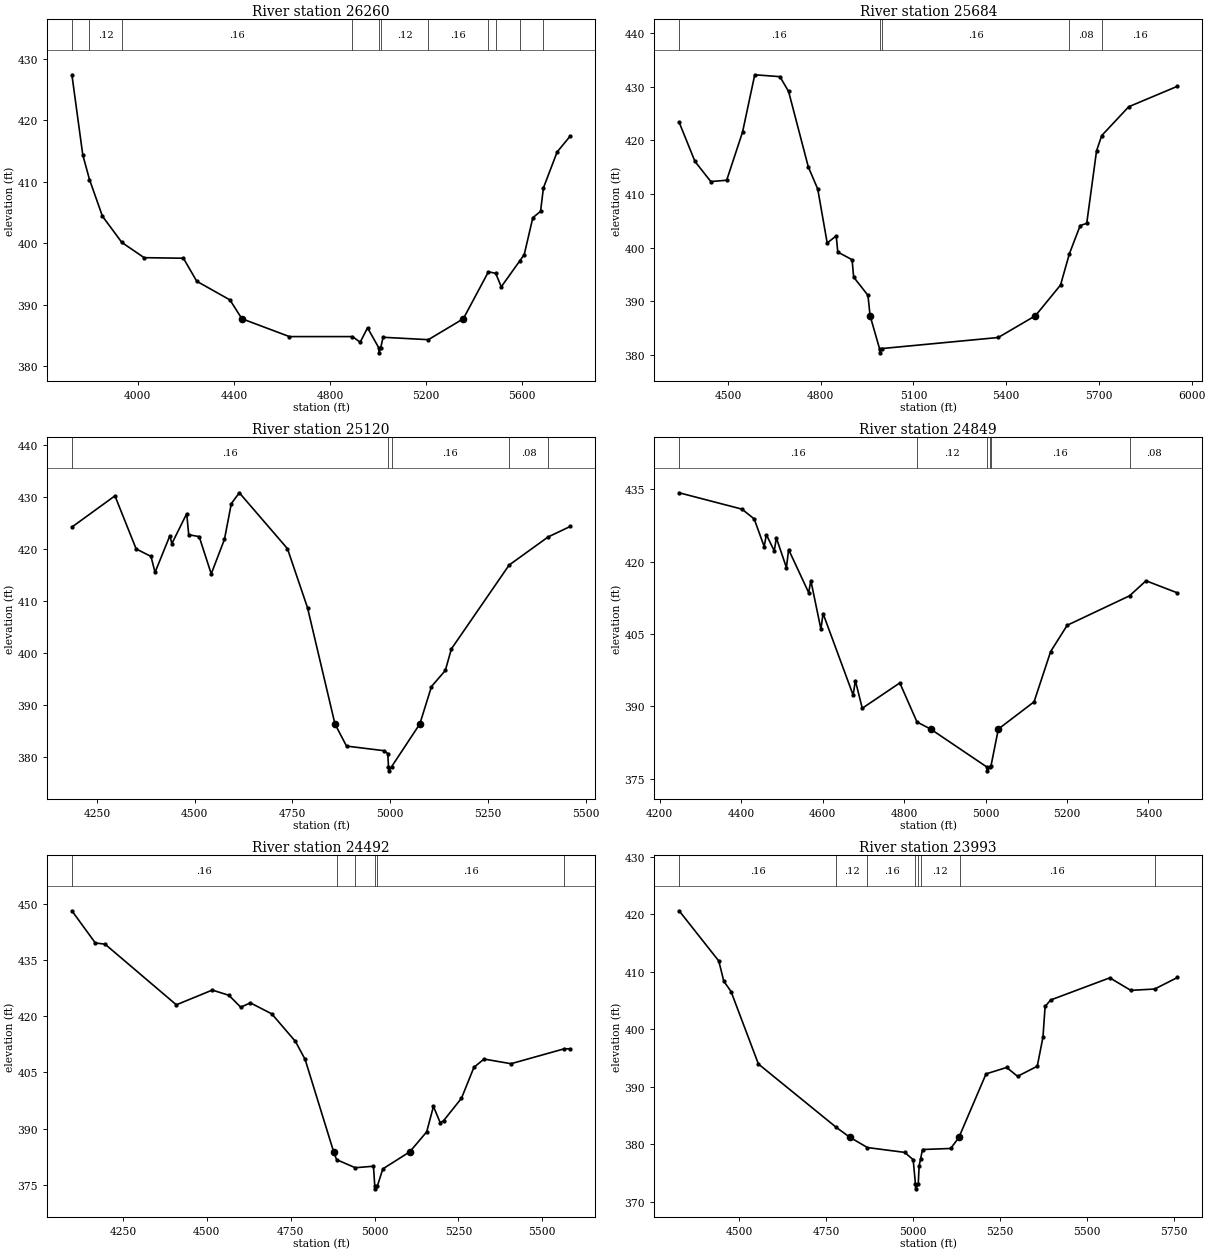
Type RM Length L Ch R = 1,26260,576,576,576
BEGIN DESCRIPTION:
MILL RACE 34.0
END DESCRIPTION:
XS GIS Cut Line= 3
      2946388.30      6955290.69      2946125.00      6956525.00
      2946249.41      6957328.95
#Sta/Elev= 30
  3725.3  427.42  3770.6  414.40  3798.6  410.39  3852.4  404.44  3933.2  400.17
  4026.2  397.69  4189.8  397.60  4245.2  393.86  4383.6  390.82  4433.4  387.76
  4631.3  384.86  4893.9  384.86  4926.0  383.95  4956.7  386.29  5003.7  383.02
  5004.4  382.22  5011.5  383.02  5021.4  384.75  5210.0  384.36  5355.6  387.76
  5460.1  395.39  5490.4  395.15  5513.6  392.95  5589.8  397.12  5609.2  398.18
  5645.1  404.19  5677.3  405.22  5689.2  409.03  5746.3  414.87  5800.9  417.46
#Mann=11,-1,0
  3725.3    0.16       0  3798.6    0.12       0  3933.2    0.16       0
  4893.9    0.12       0  5003.7    0.07       0  5011.5    0.12       0
  5210.0    0.16       0  5460.1    0.05       0  5490.4    0.16       0
  5589.8    0.08       0  5689.2    0.16       0
Bank Sta=4433.4,5355.6
Exp/Cntr=0.3,0.1

Type RM Length L Ch R = 1,25684,564,564,564
BEGIN DESCRIPTION:
MILL RACE 33.0
END DESCRIPTION:
XS GIS Cut Line= 3
      2945541.07      6955894.92      2945675.00      6956575.00
      2945981.43      6957441.78
#Sta/Elev= 30
  4341.7  423.39  4392.9  416.09  4444.2  412.33  4495.6  412.58  4546.9  421.56
  4586.4  432.24  4667.9  431.89  4695.9  429.13  4759.7  415.06  4790.2  410.94
  4820.8  400.87  4850.0  402.21  4855.1  399.19  4901.4  397.76  4906.4  394.52
  4952.7  391.12  4959.6  387.32  4990.1  381.20  4990.8  380.40  4998.0  381.20
  5374.3  383.26  5494.6  387.32  5575.8  393.04  5604.6  398.89  5639.4  404.12
  5660.6  404.55  5692.4  418.07  5709.2  420.91  5796.5  426.28  5954.2  430.10
#Mann=5,-1,0
  4341.7    0.16       0  4990.1    0.07       0  4998.0    0.16       0
  5604.6    0.08       0  5709.2    0.16       0
Bank Sta=4959.6,5494.6
Exp/Cntr=0.3,0.1

Type RM Length L Ch R = 1,25120,271,271,271
BEGIN DESCRIPTION:
MILL RACE 32.0
END DESCRIPTION:
XS GIS Cut Line= 3
      2945485.86      6956007.75      2945305.70      6956801.25
      2945385.16      6957254.24
#Sta/Elev= 30
  4186.3  424.20  4296.3  430.19  4350.5  420.01  4388.4  418.57  4398.8  415.51
  4436.7  422.54  4441.8  421.02  4479.7  426.77  4484.9  422.73  4511.6  422.37
  4542.4  415.22  4576.2  421.85  4593.7  428.69  4614.2  430.78  4737.2  420.06
  4788.5  408.72  4858.6  386.43  4888.1  382.18  4984.5  381.29  4993.6  380.74
  4995.4  378.23  4996.1  377.43  5003.4  378.23  5075.5  386.43  5105.3  393.61
  5140.7  396.69  5156.1  400.82  5303.7  416.91  5403.5  422.31  5459.9  424.32
#Mann=5,-1,0
  4186.3    0.16       0  4995.4    0.07       0  5003.4    0.16       0
  5303.7    0.08       0  5403.5    0.16       0
Bank Sta=4858.6,5075.5
Exp/Cntr=0.3,0.1

Type RM Length L Ch R = 1,24849,357,357,357
BEGIN DESCRIPTION:
Mapping XS 7f84bbf3
END DESCRIPTION:
XS GIS Cut Line= 3
      2945385.15      6955945.26      2945117.80      6956639.68
      2945027.71      6957110.94
#Sta/Elev= 30
  4247.5  434.28  4401.8  430.89  4431.8  428.87  4456.4  423.13  4461.8  425.59
  4481.1  422.24  4486.4  424.90  4511.0  418.78  4516.4  422.51  4565.7  413.58
  4571.0  416.09  4595.7  406.02  4601.0  409.25  4674.9  392.34  4680.3  395.35
  4697.3  389.62  4789.5  394.87  4831.7  386.77  4865.1  385.31  5003.2  377.45
  5003.9  376.65  5011.2  377.45  5013.2  377.58  5031.5  385.31  5119.2  390.95
  5159.9  401.37  5200.6  406.82  5353.8  412.93  5394.1  416.04  5471.4  413.53
#Mann=6,-1,0
  4247.5    0.16       0  4831.7    0.12       0  5003.2    0.07       0
  5011.2    0.12       0  5013.2    0.16       0  5353.8    0.08       0
Bank Sta=4865.1,5031.5
Exp/Cntr=0.3,0.1

Type RM Length L Ch R = 1,24492,499,499,499
BEGIN DESCRIPTION:
Mapping XS 25fed4a8
END DESCRIPTION:
XS GIS Cut Line= 3
      2945454.61      6955726.49      2944892.11      6956424.40
      2944954.55      6957010.61
#Sta/Elev= 30
  4097.6  448.08  4167.5  439.49  4196.3  439.19  4409.0  423.01  4516.2  426.94
  4565.8  425.55  4601.0  422.37  4629.8  423.53  4693.7  420.59  4764.1  413.25
  4792.9  408.47  4878.1  383.82  4886.8  381.73  4942.5  379.58  4996.8  379.98
  5000.6  374.75  5001.3  373.95  5008.6  374.75  5024.7  379.27  5105.1  383.82
  5155.5  389.15  5175.6  395.92  5195.7  391.60  5205.8  392.11  5259.2  398.10
  5296.3  406.34  5326.4  408.55  5406.9  407.31  5565.9  411.29  5583.5  411.28
#Mann=6,-1,0
  4097.6    0.16       0  4886.8    0.12       0  4942.5    0.16       0
  5000.6    0.07       0  5008.6    0.16       0  5565.9    0.08       0
Bank Sta=4878.1,5105.1
Exp/Cntr=0.3,0.1

Type RM Length L Ch R = 1,23993,342,342,342
BEGIN DESCRIPTION:
MILL RACE 31.0
END DESCRIPTION:
XS GIS Cut Line= 3
      2944950.01      6955749.99      2944535.45      6956279.89
      2944891.53      6956951.09
#Sta/Elev= 30
  4327.2  420.64  4441.2  411.91  4455.6  408.40  4476.4  406.60  4555.1  393.99
  4779.0  382.97  4817.5  381.27  4868.5  379.46  4975.6  378.62  5000.0  377.35
  5006.6  373.08  5007.2  372.28  5014.6  373.08  5017.1  376.27  5021.2  377.46
  5026.9  379.12  5107.7  379.30  5132.4  381.28  5133.4  381.50  5209.5  392.27
  5268.8  393.39  5300.1  391.85  5356.7  393.60  5373.1  398.64  5379.3  404.00
  5395.1  405.12  5565.3  408.98  5625.6  406.80  5694.2  407.03  5759.8  409.04
#Mann=8,-1,0
  4327.2    0.16       0  4779.0    0.12       0  4868.5    0.16       0
  5006.6    0.07       0  5014.6    0.16       0  5021.2    0.12       0
  5133.4    0.16       0  5694.2    0.08       0
Bank Sta=4817.5,5132.4
Exp/Cntr=0.3,0.1

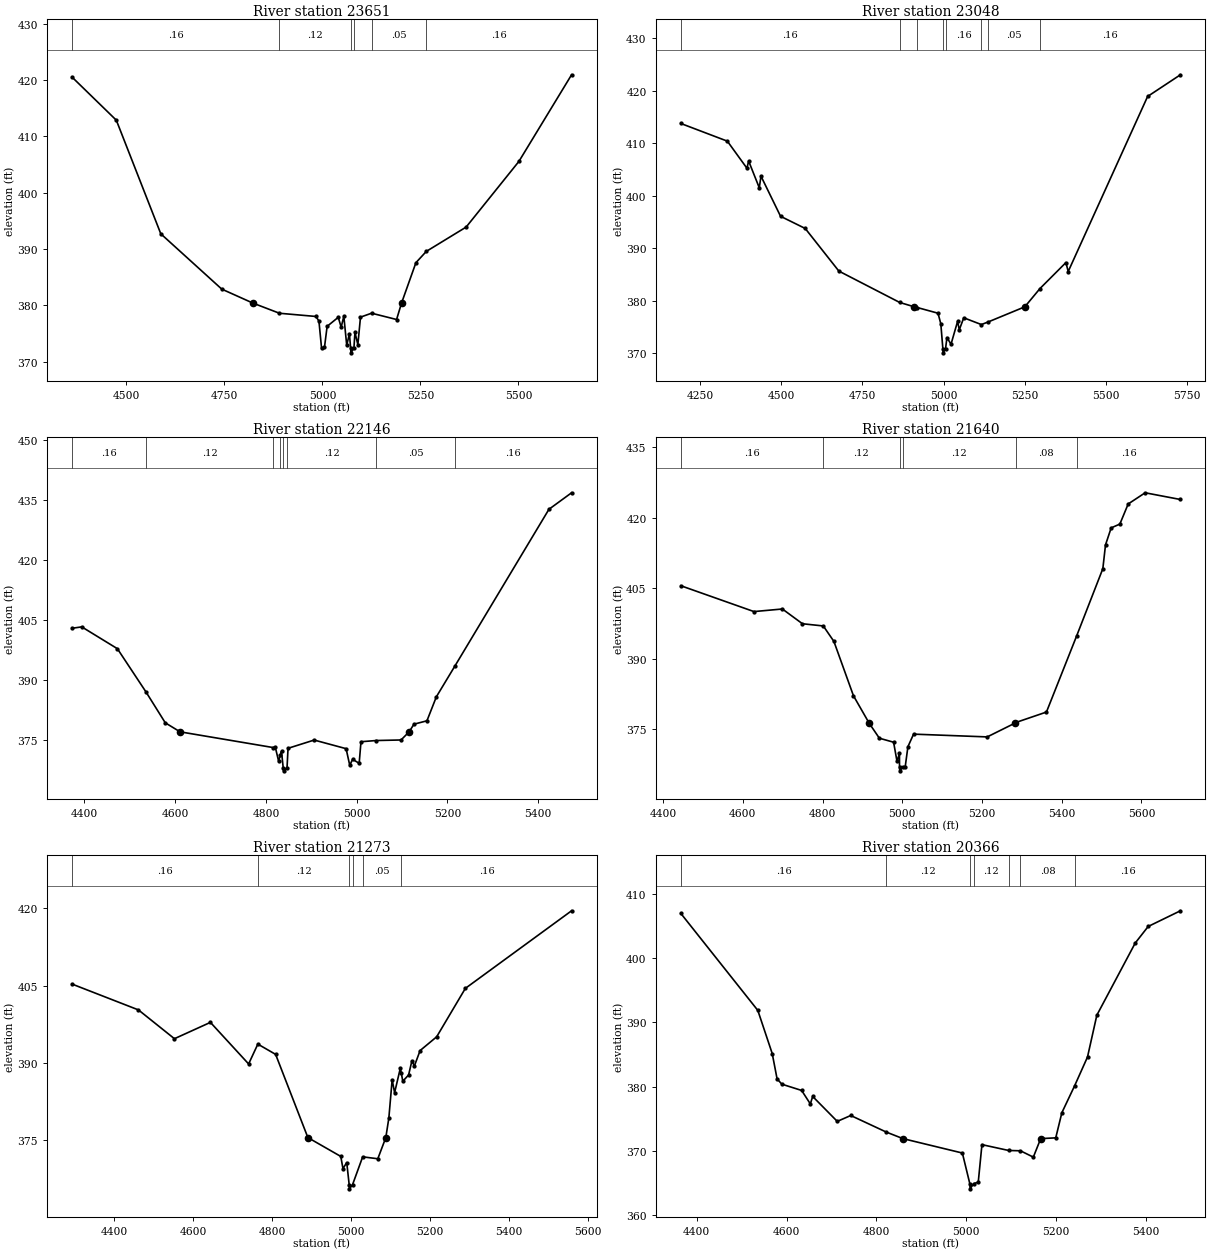
Type RM Length L Ch R = 1,23651,603,603,603
BEGIN DESCRIPTION:
MILL RACE 30.0
END DESCRIPTION:
XS GIS Cut Line= 3
      2944875.03      6955724.97      2944375.00      6956275.00
      2943975.04      6956624.97
#Sta/Elev= 30
  4360.9  420.55  4474.1  412.88  4587.6  392.70  4743.1  382.88  4822.8  380.39
  4890.4  378.59  4983.6  378.02  4991.1  377.19  4997.8  372.36  5005.2  372.53
  5012.0  376.27  5040.4  377.87  5047.8  376.12  5054.6  378.06  5062.0  372.89
  5068.8  374.96  5072.0  372.36  5072.7  371.56  5080.3  372.36  5083.0  375.19
  5090.4  373.02  5097.1  377.90  5125.4  378.60  5189.2  377.48  5201.8  380.39
  5238.5  387.57  5265.1  389.58  5366.7  393.90  5501.4  405.57  5635.7  420.95
#Mann=6,-1,0
  4360.9    0.16       0  4890.4    0.12       0  5072.0    0.07       0
  5080.3    0.12       0  5125.4    0.05       0  5265.1    0.16       0
Bank Sta=4822.8,5201.8
Exp/Cntr=0.3,0.1

Type RM Length L Ch R = 1,23048,902,902,902
BEGIN DESCRIPTION:
MILL RACE 29.0
END DESCRIPTION:
XS GIS Cut Line= 3
      2944381.01      6955189.92      2944125.00      6956025.00
      2943900.00      6956649.99
#Sta/Elev= 30
  4191.3  413.75  4334.5  410.38  4394.8  405.22  4400.0  406.60  4432.8  401.49
  4438.0  403.71  4498.3  396.06  4574.2  393.74  4677.7  385.62  4865.0  379.64
  4910.0  378.81  4918.7  378.68  4982.9  377.59  4991.5  375.57  4997.8  370.84
  4998.5  370.04  5006.1  370.84  5010.4  372.95  5022.9  371.68  5043.1  376.03
  5048.4  374.44  5062.1  376.72  5116.3  375.43  5136.6  375.91  5250.0  378.81
  5296.8  382.30  5376.5  387.24  5383.6  385.54  5628.0  418.90  5729.0  423.03
#Mann=8,-1,0
  4191.3    0.16       0  4865.0    0.12       0  4918.7    0.16       0
  4997.8    0.07       0  5006.1    0.16       0  5116.3    0.12       0
  5136.6    0.05       0  5296.8    0.16       0
Bank Sta=4910,5250
Exp/Cntr=0.3,0.1

Type RM Length L Ch R = 1,22146,506,506,506
BEGIN DESCRIPTION:
MILL RACE 28.0
END DESCRIPTION:
XS GIS Cut Line= 3
      2944175.02      6955524.98      2943675.00      6955925.00
      2943375.01      6956274.99
#Sta/Elev= 30
  4372.4  402.93  4394.0  403.28  4472.5  397.84  4535.8  387.01  4578.1  379.35
  4610.7  377.10  4816.4  373.17  4820.6  373.27  4827.9  369.81  4831.9  371.32
  4834.3  372.22  4838.0  368.17  4838.8  367.37  4846.5  368.17  4848.7  372.99
  4906.3  375.05  4976.7  372.90  4984.7  368.76  4991.1  370.24  5005.5  369.25
  5009.5  374.63  5042.9  374.93  5097.8  375.07  5115.6  377.10  5126.3  379.01
  5154.9  379.85  5175.7  385.85  5216.4  393.49  5423.8  432.61  5473.7  436.73
#Mann=8,-1,0
  4372.4    0.16       0  4535.8    0.12       0  4816.4    0.16       0
  4831.9    0.12       0  4838.0    0.07       0  4846.5    0.12       0
  5042.9    0.05       0  5216.4    0.16       0
Bank Sta=4610.7,5115.6
Exp/Cntr=0.3,0.1

Type RM Length L Ch R = 1,21640,367,367,367
BEGIN DESCRIPTION:
MILL RACE 27.0
END DESCRIPTION:
XS GIS Cut Line= 3
      2944177.86      6955252.45      2943725.00      6955575.00
      2943261.25      6956096.15
#Sta/Elev= 30
  4444.4  405.57  4627.9  400.07  4699.2  400.62  4749.6  397.48  4801.9  397.01
  4828.5  393.72  4877.6  382.15  4917.2  376.29  4942.6  373.12  4978.3  372.27
  4986.9  368.17  4993.0  369.95  4993.1  366.98  4993.8  366.18  5001.6  366.98
  5007.5  367.09  5014.2  371.31  5028.4  373.99  5213.2  373.40  5281.8  376.29
  5284.4  376.45  5361.8  378.69  5437.3  394.83  5503.3  409.20  5510.0  414.26
  5524.2  417.88  5546.0  418.69  5566.9  422.97  5609.5  425.35  5698.0  423.92
#Mann=6,-1,0
  4444.4    0.16       0  4801.9    0.12       0  4993.1    0.07       0
  5001.6    0.12       0  5284.4    0.08       0  5437.3    0.16       0
Bank Sta=4917.2,5281.8
Exp/Cntr=0.3,0.1

Type RM Length L Ch R = 1,21273,907,907,907
BEGIN DESCRIPTION:
MILL RACE 26.0
END DESCRIPTION:
XS GIS Cut Line= 3
      2944136.23      6955070.14      2943495.17      6955370.42
      2943162.34      6955820.03
#Sta/Elev= 30
  4292.1  405.31  4460.7  400.29  4552.0  394.70  4643.3  397.87  4740.2  389.80
  4763.6  393.65  4808.7  391.66  4890.5  375.51  4974.0  371.85  4979.5  369.49
  4989.1  370.66  4995.3  366.36  4996.0  365.56  5003.8  366.36  5029.5  371.77
  5067.9  371.40  5088.2  375.51  5095.9  379.30  5104.3  386.74  5110.5  384.22
  5125.1  389.00  5127.6  387.97  5131.3  386.45  5146.0  387.66  5154.4  390.42
  5160.6  389.39  5175.2  392.40  5217.2  395.07  5290.0  404.47  5559.4  419.53
#Mann=6,-1,0
  4292.1    0.16       0  4763.6    0.12       0  4995.3    0.07       0
  5003.8    0.12       0  5029.5    0.05       0  5127.6    0.16       0
Bank Sta=4890.5,5088.2
Exp/Cntr=0.3,0.1

Type RM Length L Ch R = 1,20366,705,705,705
BEGIN DESCRIPTION:
MILL RACE 25.0
END DESCRIPTION:
XS GIS Cut Line= 3
      2943774.97      6954725.01      2943272.90      6954917.95
      2942924.97      6955375.04
#Sta/Elev= 30
  4364.7  407.03  4536.1  391.89  4568.2  385.15  4579.0  381.20  4589.6  380.37
  4633.7  379.39  4653.0  377.29  4658.3  378.45  4713.0  374.56  4743.0  375.48
  4822.2  372.89  4859.2  371.87  4991.5  369.62  5008.1  364.83  5008.8  364.03
  5016.6  364.83  5026.9  365.09  5035.1  370.93  5094.5  370.02  5120.8  369.97
  5149.5  368.98  5165.9  371.87  5199.4  371.99  5213.0  375.91  5241.7  380.16
  5270.1  384.61  5290.9  391.14  5376.4  402.41  5405.2  404.99  5477.0  407.44
#Mann=7,-1,0
  4364.7    0.16       0  4822.2    0.12       0  5008.1    0.07       0
  5016.6    0.12       0  5094.5    0.05       0  5120.8    0.08       0
  5241.7    0.16       0
Bank Sta=4859.2,5165.9
Exp/Cntr=0.3,0.1

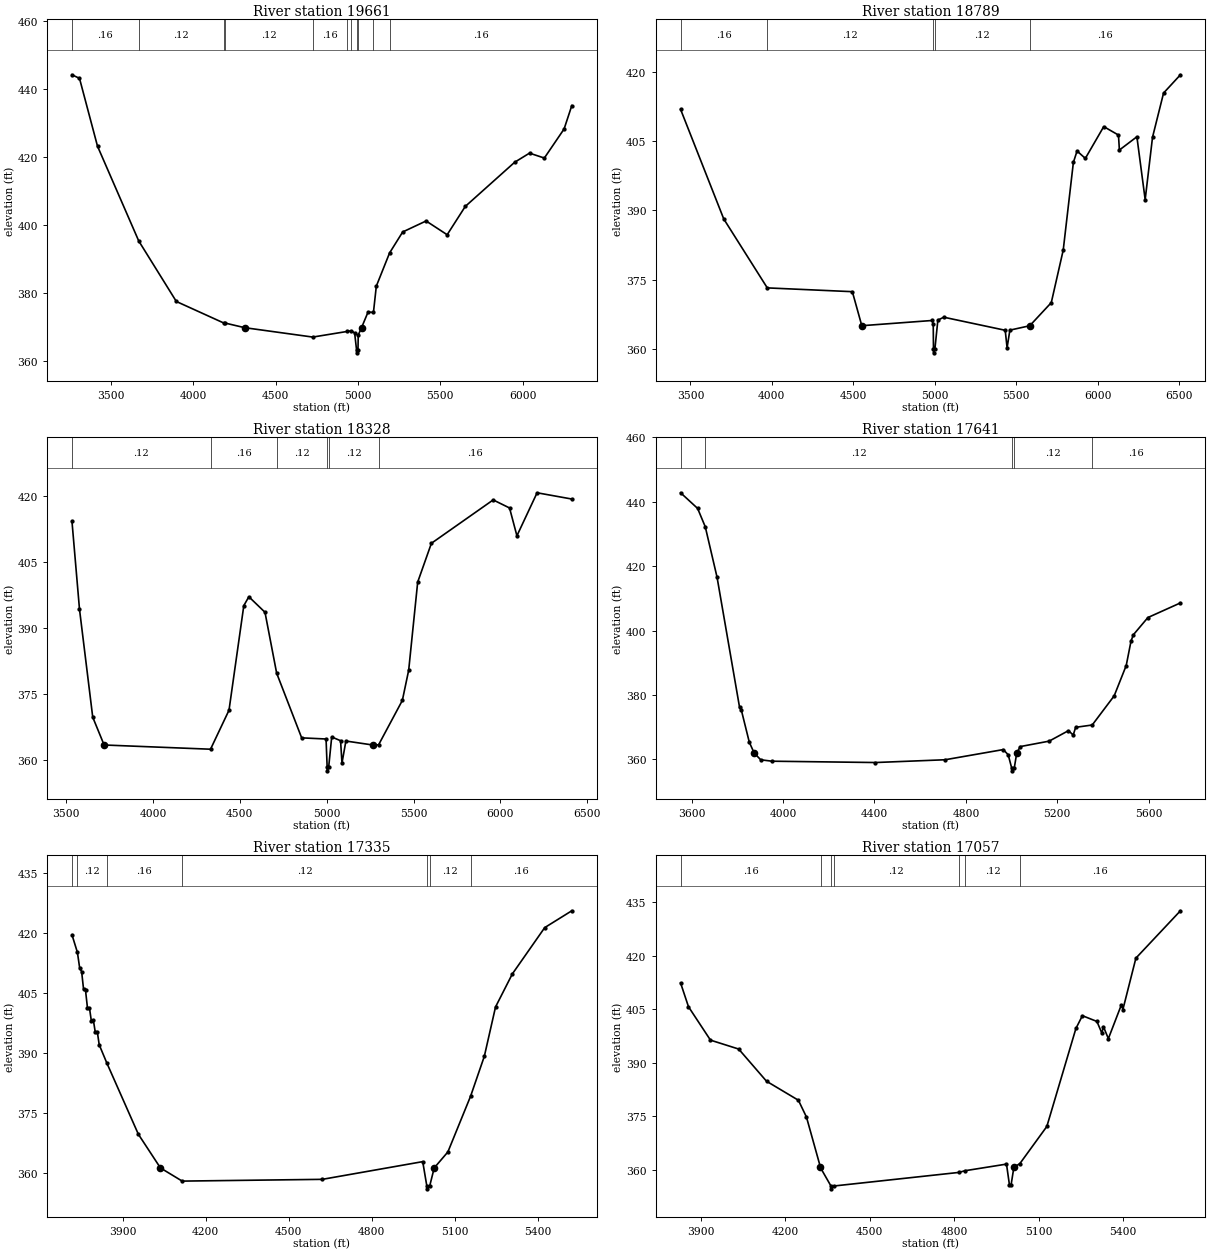
Type RM Length L Ch R = 1,19661,872,872,872
BEGIN DESCRIPTION:
MILL RACE 24.0
END DESCRIPTION:
XS GIS Cut Line= 3
      2944325.04      6953974.98      2942775.00      6954825.00
      2942791.70      6956091.68
#Sta/Elev= 30
  3263.7  444.08  3309.4  443.03  3418.7  423.11  3669.1  395.28  3897.4  377.51
  4186.2  371.17  4194.6  371.16  4312.1  369.82  4725.6  367.06  4933.2  368.70
  4960.8  368.91  4979.9  368.24  4991.7  363.23  4992.5  362.43  5000.2  363.23
  5001.7  367.66  5021.8  369.82  5061.5  374.43  5094.0  374.28  5111.5  382.01
  5191.9  391.75  5271.5  397.92  5413.7  401.15  5541.6  397.11  5651.6  405.42
  5951.6  418.40  6041.6  421.07  6131.6  419.63  6251.6  428.17  6298.3  435.02
#Mann=11,-1,0
  3263.7    0.16       0  3669.1    0.12       0  4186.2    0.16       0
  4194.6    0.12       0  4725.6    0.16       0  4933.2    0.12       0
  4960.8    0.05       0  4991.7    0.04       0  5000.2    0.05       0
  5094.0    0.08       0  5191.9    0.16       0
Bank Sta=4312.1,5021.8
Exp/Cntr=0.3,0.1

Type RM Length L Ch R = 1,18789,461,461,461
BEGIN DESCRIPTION:
MILL RACE 23.0
END DESCRIPTION:
XS GIS Cut Line= 4
      2944103.29      6953891.19      2942700.00      6954400.00
      2942343.09      6954609.57      2941295.81      6955114.45
#Sta/Elev= 30
  3439.8  411.83  3704.8  388.13  3972.1  373.22  4494.4  372.40  4552.5  365.04
  4984.7  366.17  4991.1  365.33  4992.6  359.97  4993.4  359.17  5001.2  359.97
  5019.5  366.24  5055.5  366.88  5433.1  364.05  5444.6  360.26  5461.7  364.08
  5583.8  365.03  5584.3  365.05  5716.0  370.03  5789.4  381.41  5851.7  400.37
  5874.3  402.83  5925.1  401.23  6038.1  408.11  6128.6  406.28  6134.2  403.04
  6241.7  405.91  6292.5  392.31  6337.7  405.81  6405.5  415.37  6509.0  419.32
#Mann=5,-1,0
  3439.8    0.16       0  3972.1    0.12       0  4992.6    0.07       0
  5001.2    0.12       0  5584.3    0.16       0
Bank Sta=4552.5,5583.8
Exp/Cntr=0.3,0.1

Type RM Length L Ch R = 1,18328,687,687,687
BEGIN DESCRIPTION:
double MILL RACE 22.0
END DESCRIPTION:
XS GIS Cut Line= 3
      2942853.32      6953035.27      2942275.00      6954375.00
      2941076.08      6955130.46
#Sta/Elev= 30
  3534.2  414.14  3577.5  394.17  3653.7  369.66  3719.2  363.35  4331.6  362.39
  4437.9  371.25  4523.1  395.00  4552.1  397.01  4644.9  393.49  4712.1  379.66
  4856.0  364.97  4996.4  364.71  5002.7  358.28  5003.5  357.48  5011.3  358.28
  5028.9  365.17  5079.9  364.32  5088.0  359.24  5110.5  364.25  5265.0  363.35
  5298.7  363.39  5435.4  373.47  5471.9  380.34  5523.7  400.34  5602.6  409.15
  5958.1  419.00  6052.3  417.17  6094.7  410.85  6210.8  420.62  6410.5  419.20
#Mann=6,-1,0
  3534.2    0.12       0  4331.6    0.16       0  4712.1    0.12       0
  5002.7    0.07       0  5011.3    0.12       0  5298.7    0.16       0
Bank Sta=3719.2,5265
Exp/Cntr=0.3,0.1

Type RM Length L Ch R = 1,17641,306,306,306
BEGIN DESCRIPTION:
double MILL RACE 21.0
END DESCRIPTION:
XS GIS Cut Line= 3
      2942870.65      6952835.65      2941875.00      6953925.00
      2941650.01      6954599.98
#Sta/Elev= 30
  3551.5  442.77  3625.9  437.92  3659.5  432.20  3711.0  416.56  3809.6  376.13
  3817.0  375.40  3852.2  365.32  3873.5  361.98  3902.1  359.88  3951.5  359.44
  4404.1  359.03  4708.8  359.89  4963.5  363.05  4985.1  361.44  5000.6  357.25
  5001.4  356.45  5011.5  357.25  5022.5  361.98  5037.8  363.98  5164.3  365.67
  5248.7  368.92  5269.7  367.57  5280.3  369.96  5352.8  370.68  5448.9  379.73
  5501.6  389.15  5522.7  396.77  5533.3  398.73  5596.5  404.04  5738.8  408.58
#Mann=5,-1,0
  3551.5    0.16       0  3659.5    0.12       0  5000.6    0.07       0
  5011.5    0.12       0  5352.8    0.16       0
Bank Sta=3873.5,5022.5
Exp/Cntr=0.3,0.1

Type RM Length L Ch R = 1,17335,278,278,278
BEGIN DESCRIPTION:
double Mapping XS 1b578394
END DESCRIPTION:
XS GIS Cut Line= 3
      2942634.57      6952785.27      2941750.21      6953656.72
      2941192.88      6953745.27
#Sta/Elev= 30
  3716.7  419.55  3736.4  415.14  3744.4  411.32  3751.6  410.37  3758.6  405.93
  3765.7  405.65  3772.7  401.29  3779.8  401.34  3786.9  397.95  3794.0  398.24
  3801.0  395.18  3808.1  395.39  3815.2  392.08  3842.0  387.65  3956.6  369.76
  4036.3  361.36  4114.9  358.07  4621.3  358.51  4984.0  362.93  4998.6  356.94
  4999.4  356.14  5009.5  356.94  5025.5  361.36  5074.9  365.35  5157.0  379.27
  5206.6  389.22  5247.1  401.54  5307.8  409.78  5424.8  421.34  5522.6  425.54
#Mann=7,-1,0
  3716.7    0.16       0  3736.4    0.12       0  3842.0    0.16       0
  4114.9    0.12       0  4998.6    0.07       0  5009.5    0.12       0
  5157.0    0.16       0
Bank Sta=4036.3,5025.5
Exp/Cntr=0.3,0.1

Type RM Length L Ch R = 1,17057,715,715,715
BEGIN DESCRIPTION:
double MILL RACE 20.0
END DESCRIPTION:
XS GIS Cut Line= 3
      2942474.97      6952675.02      2941575.00      6953425.00
      2941024.96      6953675.02
#Sta/Elev= 30
  3828.2  412.36  3856.2  405.70  3934.3  396.33  4034.5  393.83  4133.4  384.80
  4246.7  379.46  4275.3  374.75  4324.9  360.70  4325.9  360.43  4362.3  355.40
  4363.1  354.60  4373.2  355.40  4816.1  359.20  4839.2  359.69  4986.0  361.54
  4996.4  355.75  5002.4  355.75  5012.3  360.70  5033.2  361.65  5129.3  372.10
  5232.6  399.60  5255.6  403.19  5307.3  401.57  5324.8  398.29  5330.3  400.12
  5347.9  396.75  5394.1  406.23  5399.5  404.92  5445.7  419.34  5603.9  432.63
#Mann=7,-1,0
  3828.2    0.16       0  4325.9    0.12       0  4362.3    0.07       0
  4373.2    0.12       0  4816.1    0.16       0  4839.2    0.12       0
  5033.2    0.16       0
Bank Sta=4324.9,5012.3
Exp/Cntr=0.3,0.1

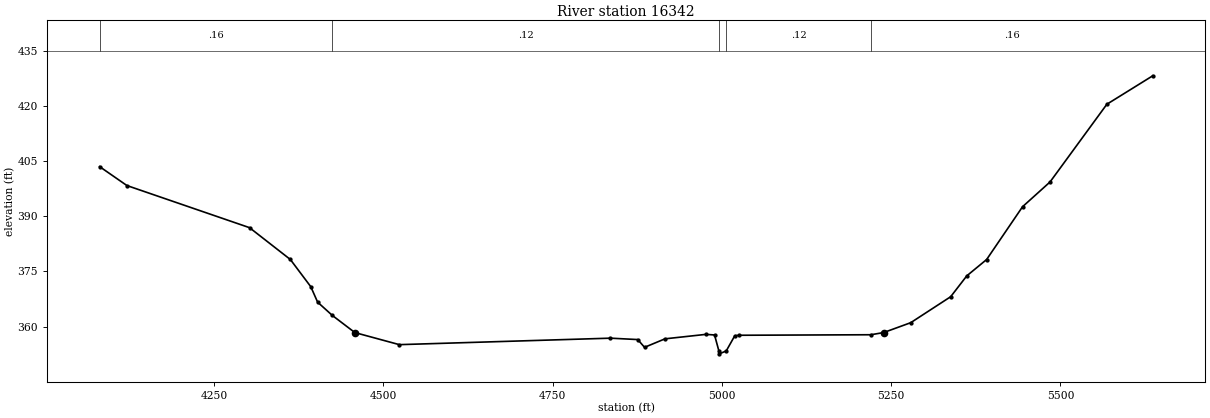
Type RM Length L Ch R = 1,16342,702,702,702
BEGIN DESCRIPTION:
doubleMILL RACE 19.0
END DESCRIPTION:
XS GIS Cut Line= 3
      2942375.01      6952675.00      2941475.00      6952775.00
      2940874.96      6953025.02
#Sta/Elev= 30
  4080.8  403.46  4121.1  398.32  4302.2  386.87  4362.5  378.22  4392.7  370.82
  4402.8  366.62  4424.6  363.00  4457.8  358.35  4523.5  355.07  4835.4  356.83
  4875.7  356.45  4885.7  354.34  4915.9  356.65  4976.3  357.86  4989.1  357.70
  4995.5  353.37  4996.3  352.57  5006.4  353.37  5018.9  357.46  5024.8  357.62
  5219.9  357.76  5238.8  358.35  5278.9  361.04  5337.9  368.10  5361.7  373.77
  5391.0  378.21  5444.1  392.57  5484.7  399.30  5568.6  420.42  5636.4  428.16
#Mann=5,-1,0
  4080.8    0.16       0  4424.6    0.12       0  4995.5    0.07       0
  5006.4    0.12       0  5219.9    0.16       0
Bank Sta=4457.8,5238.8
Exp/Cntr=0.3,0.1