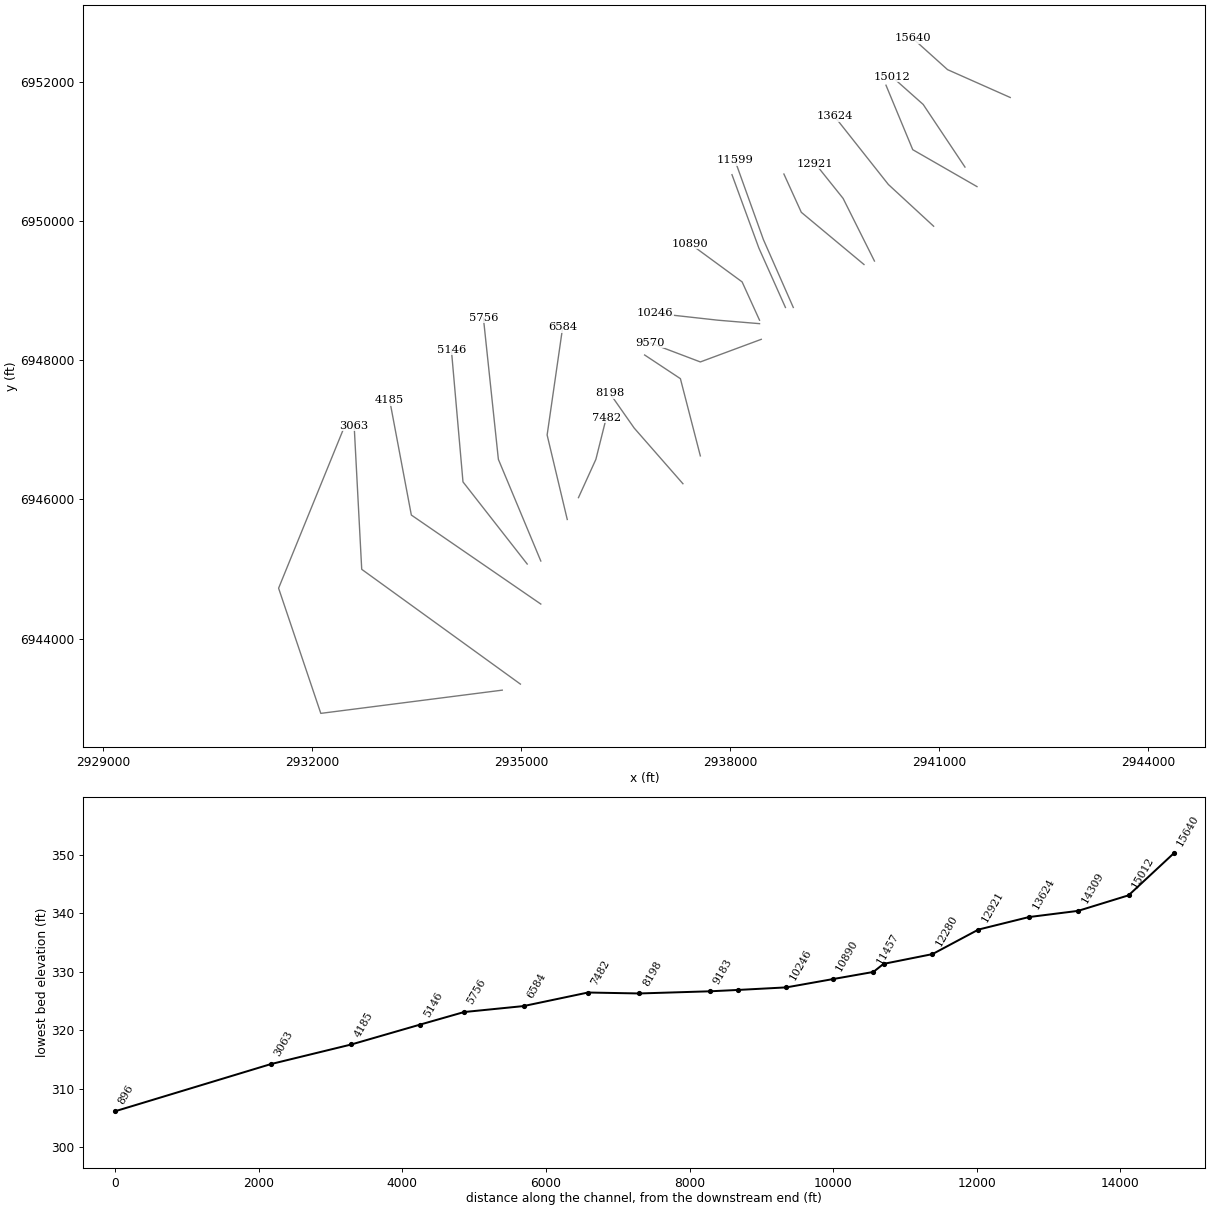
HEC-RAS study MILL RACE.prj: MILL RACE Base Level Engineering

--- MILL RACE.g01 (geometry) --- (continued)

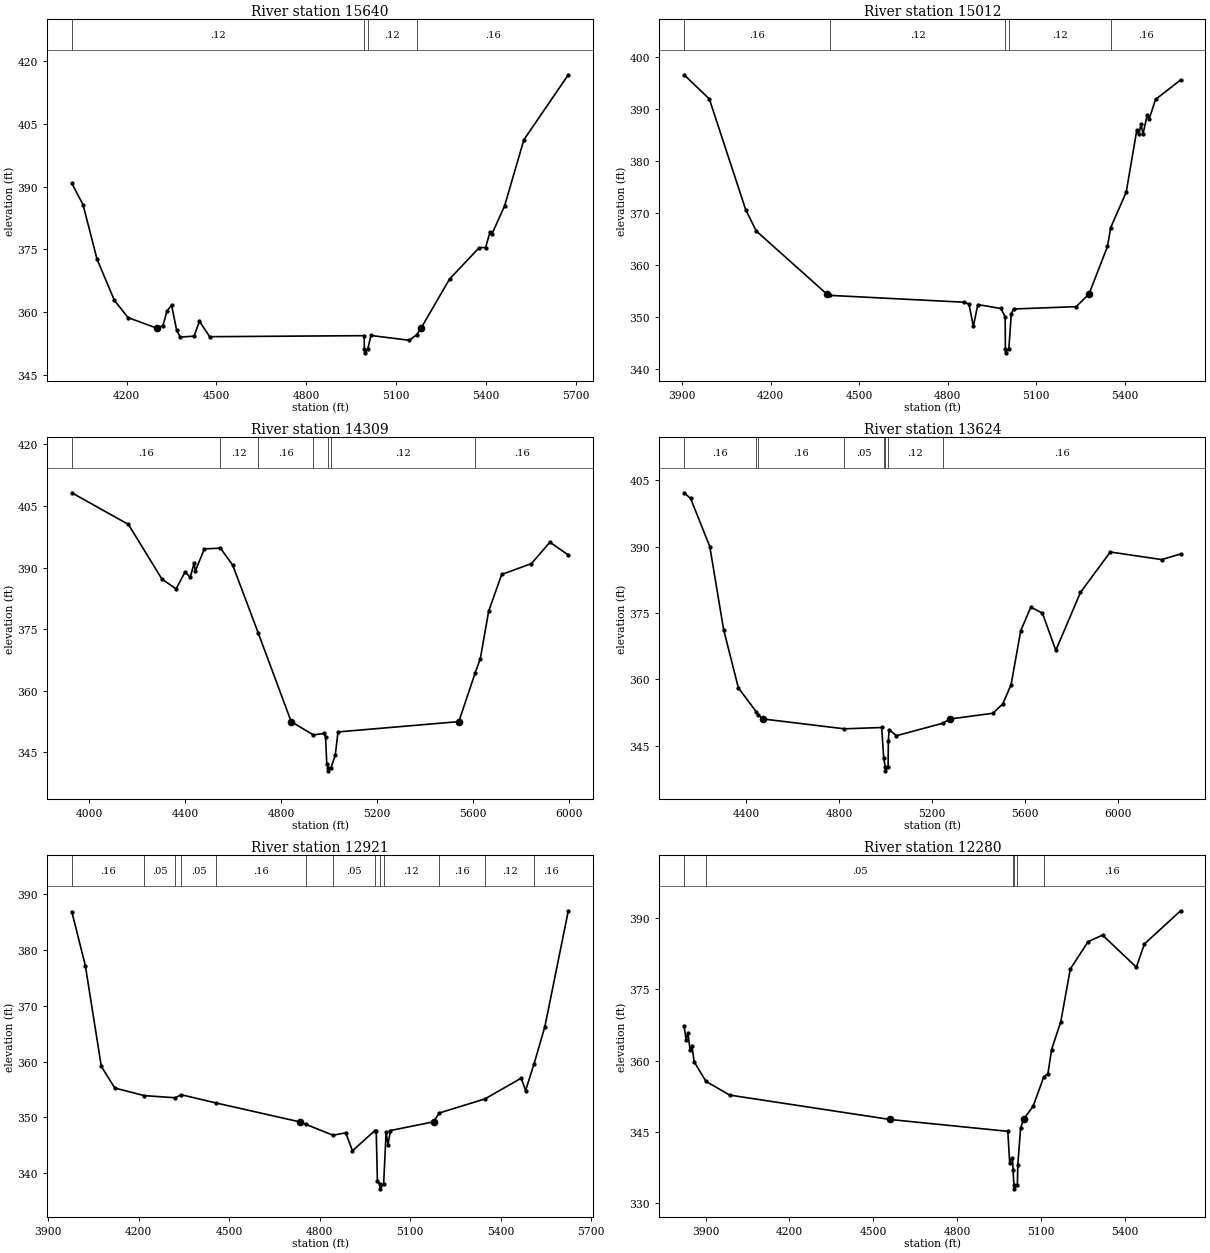
Type RM Length L Ch R = 1,15640,628,628,628
BEGIN DESCRIPTION:
double MILL RACE 18.0
END DESCRIPTION:
XS GIS Cut Line= 3
      2942024.97      6951775.02      2941125.00      6952175.00
      2940625.02      6952624.98
#Sta/Elev= 30
  4017.2  390.80  4054.8  385.66  4101.3  372.68  4159.4  362.79  4205.2  358.67
  4300.1  356.18  4321.5  356.73  4334.5  360.20  4350.2  361.67  4367.3  355.64
  4379.0  354.02  4425.5  354.24  4443.3  357.80  4477.5  354.11  4993.2  354.36
  4993.9  351.05  4994.7  350.25  5004.8  351.05  5015.9  354.40  5143.7  353.25
  5168.7  354.59  5183.4  356.18  5278.2  367.90  5377.6  375.42  5398.6  375.42
  5412.8  379.03  5419.5  378.62  5462.1  385.42  5526.4  401.20  5674.7  416.75
#Mann=4,-1,0
  4017.2    0.12       0  4993.9    0.07       0  5004.8    0.12       0
  5168.7    0.16       0
Bank Sta=4300.1,5183.4
Exp/Cntr=0.3,0.1

Type RM Length L Ch R = 1,15012,703,703,703
BEGIN DESCRIPTION:
double MILL RACE 17.0
END DESCRIPTION:
XS GIS Cut Line= 3
      2941374.98      6950775.03      2940775.00      6951675.00
      2940325.01      6952074.99
#Sta/Elev= 30
  3906.3  396.66  3991.9  392.00  4115.1  370.69  4151.1  366.55  4390.3  354.41
  4402.6  354.15  4857.2  352.83  4872.3  352.47  4887.3  348.19  4902.3  352.38
  4980.4  351.63  4995.0  350.04  4995.9  343.88  4996.4  343.08  5007.6  343.88
  5015.9  350.56  5023.5  351.53  5235.9  351.98  5279.5  354.41  5342.1  363.59
  5353.1  367.23  5405.6  374.04  5441.6  386.02  5448.3  385.18  5455.8  387.14
  5462.5  385.23  5476.7  388.87  5483.4  388.13  5505.1  391.91  5590.0  395.66
#Mann=5,-1,0
  3906.3    0.16       0  4402.6    0.12       0  4995.9    0.07       0
  5007.6    0.12       0  5353.1    0.16       0
Bank Sta=4390.3,5279.5
Exp/Cntr=0.3,0.1

Type RM Length L Ch R = 1,14309,685,685,685
BEGIN DESCRIPTION:
MILL RACE 16.0
END DESCRIPTION:
XS GIS Cut Line= 3
      2941547.67      6950494.25      2940625.00      6951025.00
      2940240.91      6951951.29
#Sta/Elev= 30
  3928.4  408.22  4164.3  400.49  4303.7  387.17  4362.6  384.78  4400.0  388.92
  4421.5  387.61  4437.3  391.00  4443.1  389.20  4480.4  394.55  4547.3  394.71
  4598.3  390.58  4705.2  373.94  4841.8  352.42  4933.9  349.18  4979.2  349.54
  4984.9  348.72  4990.0  342.03  4996.1  341.22  4996.7  340.42  5008.0  341.22
  5025.3  344.23  5036.8  349.91  5539.7  352.42  5607.9  364.31  5629.3  367.78
  5664.0  379.35  5718.2  388.30  5842.0  390.95  5919.0  396.17  5995.6  393.05
#Mann=7,-1,0
  3928.4    0.16       0  4547.3    0.12       0  4705.2    0.16       0
  4933.9    0.12       0  4996.1    0.07       0  5008.0    0.12       0
  5607.9    0.16       0
Bank Sta=4841.8,5539.7
Exp/Cntr=0.3,0.1

Type RM Length L Ch R = 1,13624,703,703,703
BEGIN DESCRIPTION:
MILL RACE 15.0
END DESCRIPTION:
XS GIS Cut Line= 3
      2940924.98      6949925.02      2940275.00      6950525.00
      2939500.81      6951504.65
#Sta/Elev= 30
  4134.5  402.17  4162.5  400.89  4245.0  390.01  4304.3  371.27  4367.8  358.10
  4445.5  352.64  4453.6  352.01  4474.6  351.07  4823.3  348.85  4983.6  349.15
  4992.1  342.22  4999.2  340.16  4999.8  339.36  5011.1  340.16  5012.0  346.11
  5015.7  348.64  5047.1  347.30  5245.1  350.10  5276.8  351.07  5460.7  352.36
  5503.4  354.44  5539.3  358.80  5580.9  371.02  5624.2  376.34  5673.9  374.98
  5731.6  366.58  5837.4  379.65  5965.6  388.79  6186.8  387.08  6267.7  388.35
#Mann=8,-1,0
  4134.5    0.16       0  4445.5    0.05       0  4453.6    0.16       0
  4823.3    0.05       0  4992.1    0.12       0  4999.2    0.07       0
  5011.1    0.12       0  5245.1    0.16       0
Bank Sta=4474.6,5276.8
Exp/Cntr=0.3,0.1

Type RM Length L Ch R = 1,12921,641,641,641
BEGIN DESCRIPTION:
MILL RACE 14.0
END DESCRIPTION:
XS GIS Cut Line= 3
      2940075.02      6949424.96      2939625.00      6950325.00
      2939224.99      6950825.01
#Sta/Elev= 30
  3978.1  386.85  4022.9  377.21  4076.0  359.14  4120.7  355.27  4218.8  353.91
  4321.5  353.53  4341.0  354.07  4457.0  352.59  4733.3  349.22  4754.2  348.77
  4844.3  346.82  4886.5  347.25  4908.9  344.03  4982.5  347.63  4987.6  347.63
  4991.6  338.65  4999.7  338.02  5000.2  337.22  5012.2  338.02  5020.4  347.33
  5026.8  345.15  5034.8  347.66  5177.7  349.22  5196.7  350.80  5348.1  353.32
  5468.6  357.04  5483.0  354.81  5511.3  359.64  5547.0  366.27  5624.7  387.01
#Mann=13,-1,0
  3978.1    0.16       0  4218.8    0.05       0  4321.5    0.16       0
  4341.0    0.05       0  4457.0    0.16       0  4754.2    0.12       0
  4844.3    0.05       0  4982.5    0.12       0  4999.7    0.07       0
  5012.2    0.12       0  5196.7    0.16       0  5348.1    0.12       0
  5511.3    0.16       0
Bank Sta=4733.3,5177.7
Exp/Cntr=0.3,0.1

Type RM Length L Ch R = 1,12280,681,681,681
BEGIN DESCRIPTION:
MILL RACE 13.0
END DESCRIPTION:
XS GIS Cut Line= 3
      2939924.98      6949375.01      2939025.00      6950125.00
      2938774.99      6950675.03
#Sta/Elev= 30
  3823.1  367.31  3830.2  364.42  3836.7  365.79  3844.6  362.24  3851.1  363.16
  3858.9  359.78  3901.3  355.63  3986.4  352.74  4559.7  347.61  4980.9  345.12
  4987.5  338.55  4997.4  339.57  4999.7  337.03  5002.6  333.82  5003.1  333.02
  5015.1  333.82  5016.6  338.04  5026.5  345.72  5037.0  347.61  5071.5  350.41
  5110.1  356.65  5124.2  357.22  5137.4  362.31  5170.4  368.21  5204.4  379.27
  5268.1  385.03  5319.8  386.40  5440.6  379.65  5469.2  384.53  5598.8  391.52
#Mann=6,-1,0
  3823.1    0.16       0  3901.3    0.05       0  4999.7    0.12       0
  5002.6    0.07       0  5015.1    0.12       0  5110.1    0.16       0
Bank Sta=4559.7,5037
Exp/Cntr=0.3,0.1

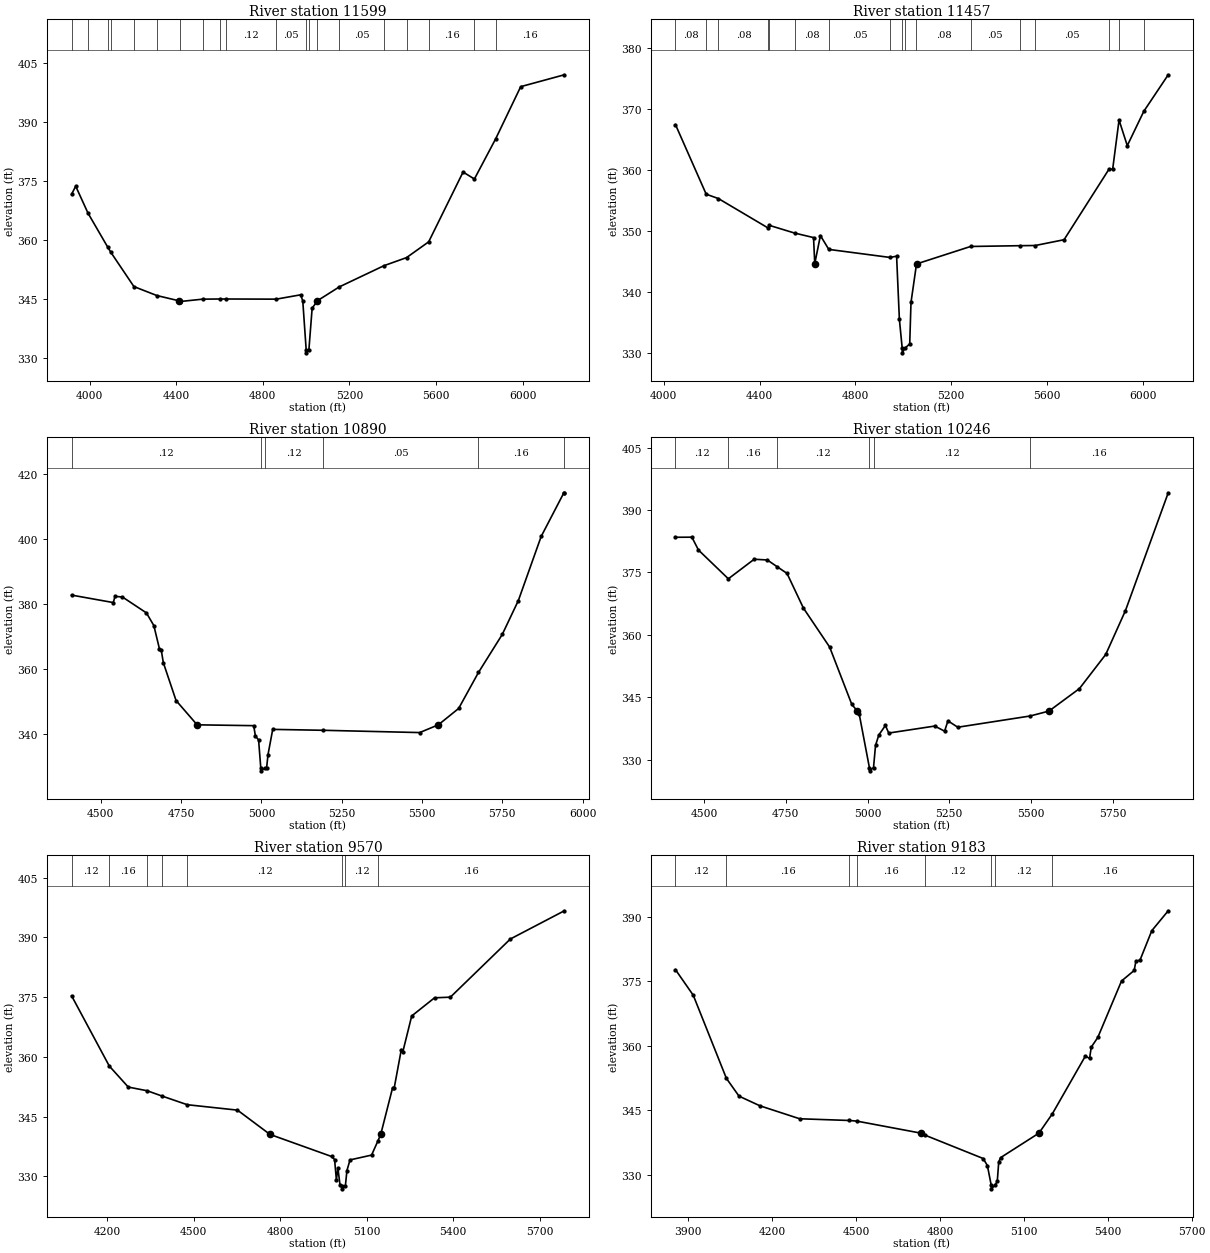
Type RM Length L Ch R = 1,11599,142,142,142
BEGIN DESCRIPTION:
Mapping XS b4379949
END DESCRIPTION:
XS GIS Cut Line= 3
      2938909.79      6948757.72      2938480.12      6949734.24
      2938072.37      6950870.74
#Sta/Elev= 30
  3917.4  371.69  3936.3  373.72  3993.2  366.85  4083.5  358.28  4099.0  356.87
  4204.9  348.20  4310.7  345.92  4413.1  344.58  4416.6  344.39  4522.4  345.00
  4602.4  345.04  4628.2  345.04  4861.9  345.00  4974.2  346.10  4984.3  344.58
  5000.0  332.15  5000.5  331.35  5012.6  332.15  5027.6  342.72  5049.9  344.38
  5051.4  344.58  5153.0  348.12  5359.2  353.51  5463.2  355.56  5565.4  359.57
  5724.2  377.32  5776.5  375.55  5874.8  385.78  5990.2  399.03  6191.7  402.05
#Mann=20,-1,0
  3917.4    0.05       0  3993.2    0.16       0  4083.5    0.08       0
  4099.0    0.12       0  4204.9    0.16       0  4310.7    0.05       0
  4416.6    0.16       0  4522.4    0.05       0  4602.4    0.08       0
  4628.2    0.12       0  4861.9    0.05       0  5000.0    0.04       0
  5012.6    0.05       0  5049.9    0.12       0  5153.0    0.05       0
  5359.2    0.12       0  5463.2    0.08       0  5565.4    0.16       0
  5776.5    0.08       0  5874.8    0.16       0
Bank Sta=4413.1,5051.4
Exp/Cntr=0.3,0.1

Type RM Length L Ch R = 1,11457,567,567,567
BEGIN DESCRIPTION:
Mapping XS 0d5722f1
END DESCRIPTION:
XS GIS Cut Line= 3
      2938796.97      6948757.66      2938415.02      6949612.72
      2938029.38      6950665.63
#Sta/Elev= 30
  4049.0  367.41  4177.2  356.00  4228.3  355.28  4437.2  350.42  4440.5  350.89
  4546.5  349.62  4625.5  348.88  4630.6  344.60  4654.2  349.21  4689.2  346.94
  4945.2  345.62  4972.4  345.83  4984.0  335.47  4995.7  330.77  4996.2  329.97
  5008.3  330.77  5027.2  331.44  5032.5  338.23  5054.8  344.34  5059.1  344.60
  5281.3  347.42  5488.0  347.55  5551.6  347.58  5671.8  348.53  5858.9  360.07
  5874.8  360.11  5901.4  368.16  5935.8  363.96  6004.7  369.59  6106.8  375.59
#Mann=17,-1,0
  4049.0    0.08       0  4177.2    0.05       0  4228.3    0.08       0
  4437.2    0.12       0  4440.5    0.05       0  4546.5    0.08       0
  4689.2    0.05       0  4945.2    0.12       0  4995.7    0.07       0
  5008.3    0.12       0  5054.8    0.08       0  5281.3    0.05       0
  5488.0    0.08       0  5551.6    0.05       0  5858.9    0.16       0
  5901.4    0.05       0  6004.7    0.08       0
Bank Sta=4630.6,5059.1
Exp/Cntr=0.3,0.1

Type RM Length L Ch R = 1,10890,644,644,644
BEGIN DESCRIPTION:
MILL RACE 11.0
END DESCRIPTION:
XS GIS Cut Line= 3
      2938425.02      6948574.96      2938175.00      6949125.00
      2937424.96      6949675.03
#Sta/Elev= 30
  4408.9  382.70  4538.6  380.41  4544.1  382.31  4567.1  382.12  4641.8  377.24
  4664.9  373.35  4682.5  366.15  4688.0  365.81  4694.5  361.95  4734.1  350.33
  4799.7  342.87  4975.8  342.61  4981.2  339.46  4991.1  338.21  4998.0  329.54
  4998.5  328.74  5010.6  329.54  5016.2  329.75  5020.4  333.71  5035.1  341.47
  5192.7  341.19  5492.8  340.49  5550.8  342.87  5614.0  347.89  5675.7  358.94
  5749.8  370.61  5800.0  381.04  5871.0  400.71  5941.7  414.12  5943.2  414.12
#Mann=6,-1,0
  4408.9    0.12       0  4998.0    0.07       0  5010.6    0.12       0
  5192.7    0.05       0  5675.7    0.16       0  5941.7     0.1       0
Bank Sta=4799.7,5550.8
Exp/Cntr=0.3,0.1

Type RM Length L Ch R = 1,10246,676,676,676
BEGIN DESCRIPTION:
MILL RACE 10.0
END DESCRIPTION:
XS GIS Cut Line= 3
      2938425.00      6948525.00      2937825.00      6948575.00
      2936925.02      6948675.00
#Sta/Elev= 30
  4412.5  383.46  4462.7  383.48  4482.7  380.40  4574.2  373.48  4653.3  378.18
  4693.5  378.00  4724.1  376.35  4753.7  374.78  4803.9  366.44  4884.1  357.08
  4951.9  343.30  4969.0  341.69  4974.4  341.07  5005.7  328.13  5006.2  327.33
  5018.4  328.13  5024.6  333.46  5034.7  335.96  5054.8  338.23  5064.9  336.41
  5205.7  338.09  5235.9  336.86  5246.0  339.34  5276.2  337.81  5497.6  340.51
  5555.2  341.69  5648.5  347.10  5728.9  355.30  5789.3  365.85  5920.1  394.15
#Mann=6,-1,0
  4412.5    0.12       0  4574.2    0.16       0  4724.1    0.12       0
  5005.7    0.07       0  5018.4    0.12       0  5497.6    0.16       0
Bank Sta=4969,5555.2
Exp/Cntr=0.3,0.1

Type RM Length L Ch R = 1,9570,387,387,387
BEGIN DESCRIPTION:
MILL RACE 9.0
END DESCRIPTION:
XS GIS Cut Line= 3
      2938449.97      6948299.99      2937575.00      6947975.00
      2936849.98      6948250.01
#Sta/Elev= 30
  4077.0  375.32  4207.6  357.71  4273.5  352.43  4339.2  351.50  4389.2  350.21
  4478.1  348.00  4652.2  346.64  4764.9  340.55  4978.4  335.01  4989.0  334.25
  4995.2  329.13  5000.5  332.11  5007.7  327.87  5013.8  327.69  5014.3  326.89
  5026.5  327.69  5031.8  331.49  5042.5  334.15  5117.3  335.36  5139.5  338.96
  5149.0  340.55  5190.3  352.30  5195.6  352.16  5220.4  361.84  5225.7  361.31
  5256.4  370.27  5335.6  374.83  5390.5  374.99  5598.6  389.59  5785.8  396.67
#Mann=8,-1,0
  4077.0    0.12       0  4207.6    0.16       0  4339.2    0.12       0
  4389.2    0.16       0  4478.1    0.12       0  5013.8    0.07       0
  5026.5    0.12       0  5139.5    0.16       0
Bank Sta=4764.9,5149
Exp/Cntr=0.3,0.1

Type RM Length L Ch R = 1,9183,985,985,985
BEGIN DESCRIPTION:
MILL RACE 8.0
END DESCRIPTION:
XS GIS Cut Line= 3
      2937575.00      6946625.00      2937288.67      6947734.65
      2936775.00      6948075.00
#Sta/Elev= 30
  3854.0  377.73  3917.6  371.77  4036.1  352.40  4081.2  348.26  4156.4  346.00
  4298.1  342.99  4476.0  342.59  4502.9  342.44  4731.7  339.64  4747.2  339.15
  4954.3  333.73  4969.4  332.09  4983.3  327.46  4983.8  326.66  4996.2  327.46
  5004.8  328.40  5010.0  332.92  5016.4  333.92  5153.8  339.64  5201.7  344.14
  5319.9  357.61  5334.9  357.05  5340.9  359.68  5364.3  361.94  5449.2  375.10
  5494.4  377.55  5500.4  379.65  5515.4  379.98  5557.5  386.83  5616.2  391.46
#Mann=8,-1,0
  3854.0    0.12       0  4036.1    0.16       0  4476.0    0.12       0
  4502.9    0.16       0  4747.2    0.12       0  4983.3    0.07       0
  4996.2    0.12       0  5201.7    0.16       0
Bank Sta=4731.7,5153.8
Exp/Cntr=0.3,0.1

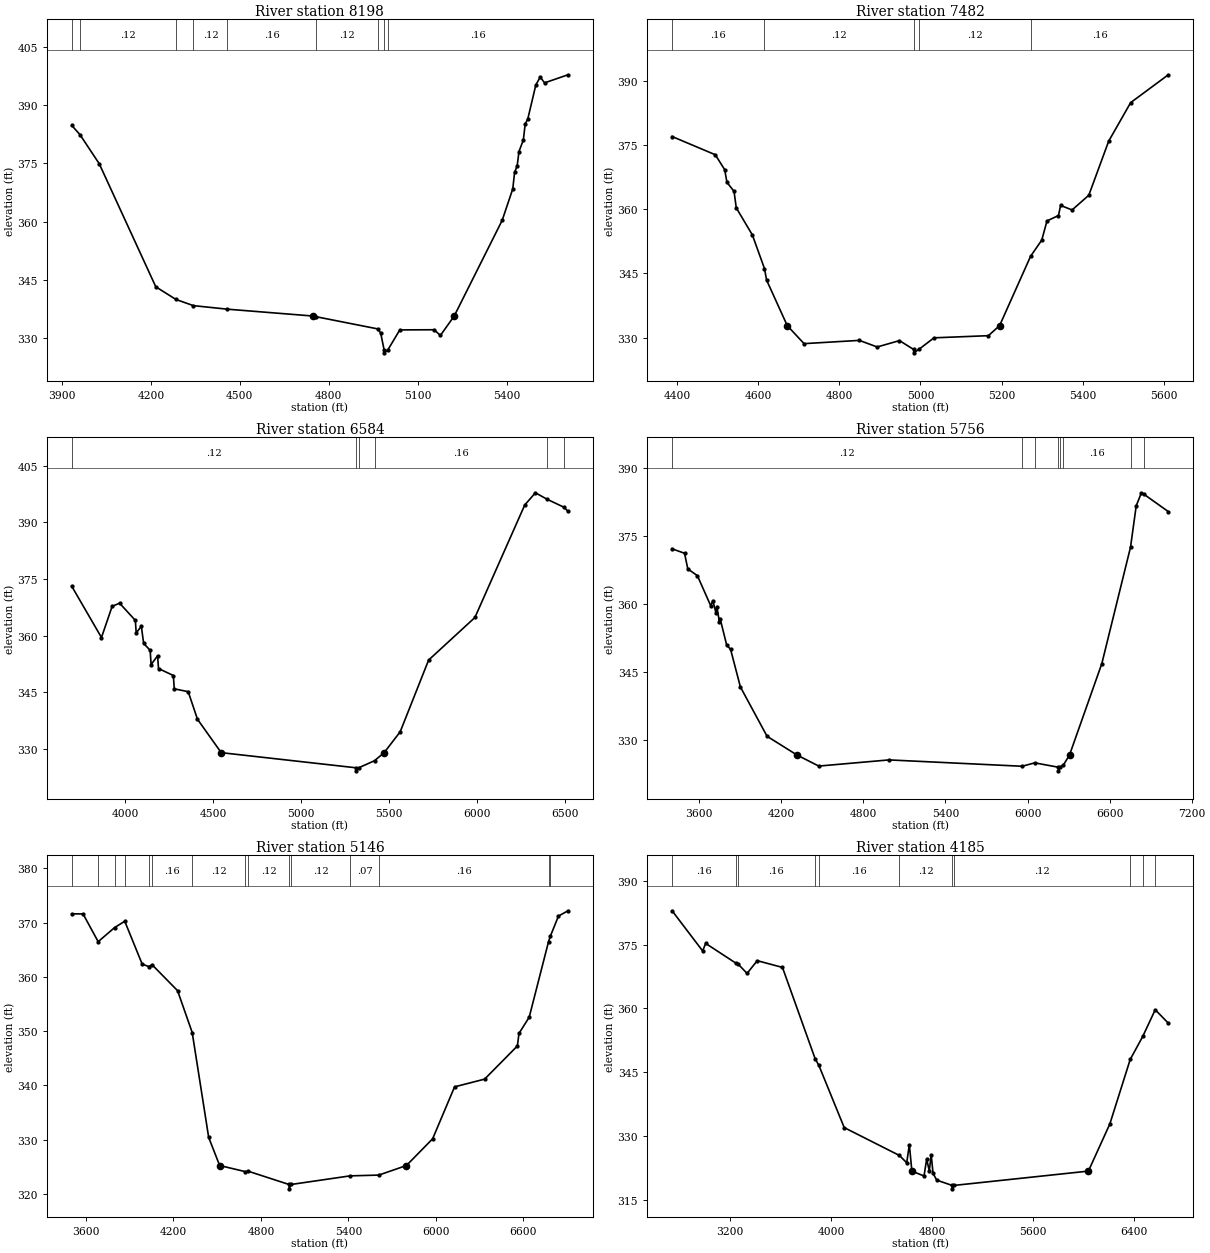
Type RM Length L Ch R = 1,8198,716,716,716
BEGIN DESCRIPTION:
MILL RACE 7.0
END DESCRIPTION:
XS GIS Cut Line= 3
      2937325.01      6946224.99      2936625.00      6947025.00
      2936274.97      6947525.04
#Sta/Elev= 30
  3933.3  384.79  3961.2  382.38  4025.8  374.95  4216.6  343.28  4284.6  340.02
  4343.5  338.43  4458.3  337.52  4746.4  335.76  4755.3  335.61  4964.3  332.46
  4975.0  331.40  4986.5  327.09  4987.0  326.29  4999.5  327.09  5039.5  332.19
  5155.0  332.23  5176.4  330.77  5223.0  335.76  5384.8  360.38  5420.5  368.48
  5426.6  372.72  5435.3  374.38  5441.4  378.07  5456.2  381.07  5462.4  385.17
  5471.1  386.44  5498.1  395.17  5512.9  397.24  5527.7  395.74  5606.7  397.82
#Mann=9,-1,0
  3933.3    0.16       0  3961.2    0.12       0  4284.6    0.16       0
  4343.5    0.12       0  4458.3    0.16       0  4755.3    0.12       0
  4964.3    0.16       0  4986.5    0.07       0  4999.5    0.16       0
Bank Sta=4746.4,5223
Exp/Cntr=0.3,0.1

Type RM Length L Ch R = 1,7482,898,898,898
BEGIN DESCRIPTION:
MILL RACE 6.0
END DESCRIPTION:
XS GIS Cut Line= 3
      2935825.02      6946025.04      2936075.00      6946575.00
      2936225.01      6947175.02
#Sta/Elev= 30
  4388.2  377.00  4494.7  372.74  4517.8  369.24  4523.3  366.30  4540.8  364.18
  4546.3  360.33  4585.9  354.01  4615.8  346.14  4621.0  343.45  4671.9  332.81
  4713.3  328.60  4849.5  329.36  4893.5  327.82  4948.4  329.31  4983.1  327.25
  4983.6  326.45  4996.1  327.25  5033.5  329.96  5167.5  330.46  5195.1  332.81
  5271.5  349.02  5299.0  352.80  5311.9  357.28  5340.2  358.54  5345.4  360.90
  5373.7  359.84  5414.9  363.28  5463.9  375.92  5518.0  384.92  5610.8  391.43
#Mann=5,-1,0
  4388.2    0.16       0  4615.8    0.12       0  4983.1    0.07       0
  4996.1    0.12       0  5271.5    0.16       0
Bank Sta=4671.9,5195.1
Exp/Cntr=0.3,0.1

Type RM Length L Ch R = 1,6584,828,828,828
BEGIN DESCRIPTION:
MILL RACE 5.0
END DESCRIPTION:
XS GIS Cut Line= 3
      2935664.00      6945711.07      2935375.00      6946925.00
      2935598.88      6948477.99
#Sta/Elev= 30
  3698.3  373.04  3866.8  359.47  3927.4  367.74  3969.6  368.57  4059.0  364.02
  4064.1  360.66  4093.0  362.48  4106.3  357.91  4143.3  356.07  4148.4  352.29
  4185.4  354.63  4190.6  351.25  4274.9  349.40  4280.0  345.87  4359.2  345.11
  4411.6  337.82  4546.6  328.95  5313.4  324.93  5314.0  324.13  5326.5  324.93
  5416.8  326.81  5471.5  328.95  5562.5  334.47  5724.1  353.50  5986.8  364.78
  6269.7  394.60  6330.3  397.84  6395.0  396.16  6494.2  393.96  6515.2  392.90
#Mann=6,-1,0
  3698.3    0.12       0  5313.4    0.07       0  5326.5    0.12       0
  5416.8    0.16       0  6395.0    0.08       0  6494.2    0.05       0
Bank Sta=4546.6,5471.5
Exp/Cntr=0.3,0.1

Type RM Length L Ch R = 1,5756,610,610,610
BEGIN DESCRIPTION:
MILL RACE 4.0
END DESCRIPTION:
XS GIS Cut Line= 3
      2935284.24      6945114.27      2934675.00      6946575.00
      2934459.57      6948608.23
#Sta/Elev= 30
  3401.5  372.07  3492.4  371.09  3516.2  367.64  3586.5  366.14  3684.0  359.50
  3699.3  360.65  3723.1  357.82  3728.5  359.33  3746.9  356.02  3752.3  356.69
  3800.0  350.90  3829.2  349.87  3900.7  341.61  4095.7  330.73  4313.8  326.61
  4473.6  324.16  4986.7  325.52  5960.4  324.12  6052.7  324.87  6224.6  323.91
  6225.1  323.11  6237.7  323.91  6261.8  324.39  6306.7  326.61  6542.9  346.77
  6752.6  372.44  6794.3  381.57  6832.2  384.43  6850.8  384.10  7028.8  380.28
#Mann=8,-1,0
  3401.5    0.12       0  5960.4    0.07       0  6052.7    0.12       0
  6224.6    0.07       0  6237.7    0.12       0  6261.8    0.16       0
  6752.6    0.08       0  6850.8    0.16       0
Bank Sta=4313.8,6306.7
Exp/Cntr=0.3,0.1

Type RM Length L Ch R = 1,5146,961,961,961
BEGIN DESCRIPTION:
MILL RACE 3.0
END DESCRIPTION:
XS GIS Cut Line= 3
      2935088.88      6945070.95      2934166.78      6946251.14
      2934000.00      6948150.03
#Sta/Elev= 30
  3502.3  371.61  3579.5  371.59  3683.3  366.48  3795.7  369.07  3865.6  370.24
  3985.5  362.33  4031.3  361.90  4052.8  362.24  4227.9  357.46  4328.4  349.75
  4441.4  330.43  4516.8  325.26  4692.6  324.14  4713.2  324.21  4992.7  321.77
  4993.3  320.97  5005.9  321.77  5412.0  323.36  5608.1  323.50  5797.7  325.26
  5977.6  330.18  6128.2  339.75  6334.3  341.17  6559.1  347.28  6569.9  349.58
  6640.2  352.58  6772.7  366.48  6784.6  367.45  6840.9  371.20  6906.2  372.17
#Mann=15,-1,0
  3502.3    0.12       0  3683.3    0.16       0  3795.7    0.12       0
  3865.6    0.16       0  4031.3    0.12       0  4052.8    0.16       0
  4328.4    0.12       0  4692.6    0.07       0  4713.2    0.12       0
  4992.7    0.07       0  5005.9    0.12       0  5412.0    0.07       0
  5608.1    0.16       0  6772.7    0.05       0  6784.6    0.08       0
Bank Sta=4516.8,5797.7
Exp/Cntr=0.3,0.1

Type RM Length L Ch R = 1,4185,1122,1122,1122
BEGIN DESCRIPTION:
MILL RACE 2.0
END DESCRIPTION:
XS GIS Cut Line= 3
      2935284.25      6944495.80      2933425.00      6945775.00
      2933114.09      6947425.46
#Sta/Elev= 30
  2739.2  382.94  2981.5  373.49  3005.3  375.27  3247.4  370.58  3258.8  370.53
  3334.0  368.21  3414.5  371.21  3614.7  369.62  3873.7  348.16  3903.2  346.60
  4104.5  331.96  4542.2  325.41  4600.3  323.69  4621.2  327.94  4641.3  321.73
  4737.6  320.58  4758.6  324.55  4779.5  321.77  4794.4  325.58  4809.3  321.20
  4838.2  319.61  4960.9  318.36  4961.6  317.56  4974.3  318.36  6041.6  321.73
  6211.7  332.82  6373.4  347.99  6472.5  353.38  6571.7  359.67  6675.5  356.52
#Mann=11,-1,0
  2739.2    0.16       0  3247.4    0.12       0  3258.8    0.16       0
  3873.7    0.12       0  3903.2    0.16       0  4542.2    0.12       0
  4960.9    0.07       0  4974.3    0.12       0  6373.4    0.16       0
  6472.5    0.05       0  6571.7    0.16       0
Bank Sta=4641.3,6041.6
Exp/Cntr=0.3,0.1

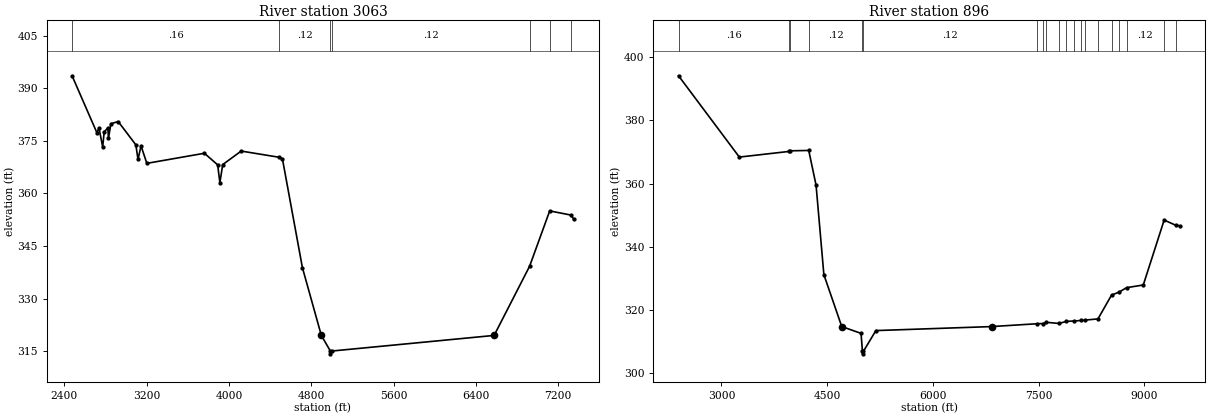
Type RM Length L Ch R = 1,3063,2167,2167,2167
BEGIN DESCRIPTION:
Mapping XS e79153e9
END DESCRIPTION:
XS GIS Cut Line= 3
      2934991.24      6943345.65      2932712.61      6944994.95
      2932604.10      6947056.60
#Sta/Elev= 30
  2475.0  393.61  2716.1  377.36  2737.0  378.66  2772.6  373.27  2787.3  377.60
  2822.8  378.71  2829.0  375.80  2852.2  379.91  2923.4  380.54  3095.1  373.88
  3116.0  369.72  3145.4  373.60  3201.8  368.60  3761.0  371.48  3890.0  368.18
  3911.8  363.10  3939.4  368.25  4119.0  372.11  4485.6  370.35  4519.6  369.90
  4713.8  338.83  4897.8  319.46  4985.4  315.00  4986.1  314.20  4999.0  315.00
  6577.4  319.46  6921.8  339.19  7117.6  355.02  7326.2  353.82  7352.4  352.57
#Mann=7,-1,0
  2475.0    0.16       0  4485.6    0.12       0  4985.4    0.07       0
  4999.0    0.12       0  6921.8    0.05       0  7117.6    0.08       0
  7326.2    0.05       0
Bank Sta=4897.8,6577.4
Exp/Cntr=0.3,0.1

Type RM Length L Ch R = 1,896,0,0,0
BEGIN DESCRIPTION:
MILL RACE 1.0
END DESCRIPTION:
XS GIS Cut Line= 4
      2934730.80      6943258.84      2932125.00      6942925.00
      2931519.03      6944723.69      2932497.77      6947127.78
#Sta/Elev= 30
  2391.0  394.14  3253.8  368.41  3964.3  370.21  3978.1  370.39  4238.6  370.51
  4342.6  359.53  4453.5  331.20  4707.2  314.77  4980.8  312.62  5001.0  306.94
  5001.9  306.14  5015.0  306.94  5191.3  313.50  6835.3  314.77  7480.4  315.67
  7565.6  315.72  7608.7  316.12  7788.8  315.76  7895.7  316.41  8002.1  316.53
  8108.8  316.71  8159.6  316.82  8343.3  317.20  8535.5  324.73  8642.2  325.67
  8748.9  327.08  8986.2  327.93  9282.3  348.48  9444.3  346.86  9511.8  346.62
#Mann=20,-1,0
  2391.0    0.16       0  3964.3    0.12       0  3978.1    0.16       0
  4238.6    0.12       0  5001.0    0.07       0  5015.0    0.12       0
  7480.4    0.07       0  7565.6    0.12       0  7608.7    0.07       0
  7788.8    0.12       0  7895.7    0.12       0  8002.1    0.07       0
  8108.8    0.12       0  8159.6    0.08       0  8343.3    0.12       0
  8535.5    0.08       0  8642.2    0.05       0  8748.9    0.12       0
  9282.3    0.05       0  9444.3    0.05       0
Bank Sta=4707.2,6835.3
Exp/Cntr=0.3,0.1

Chan Stop Cuts=-1