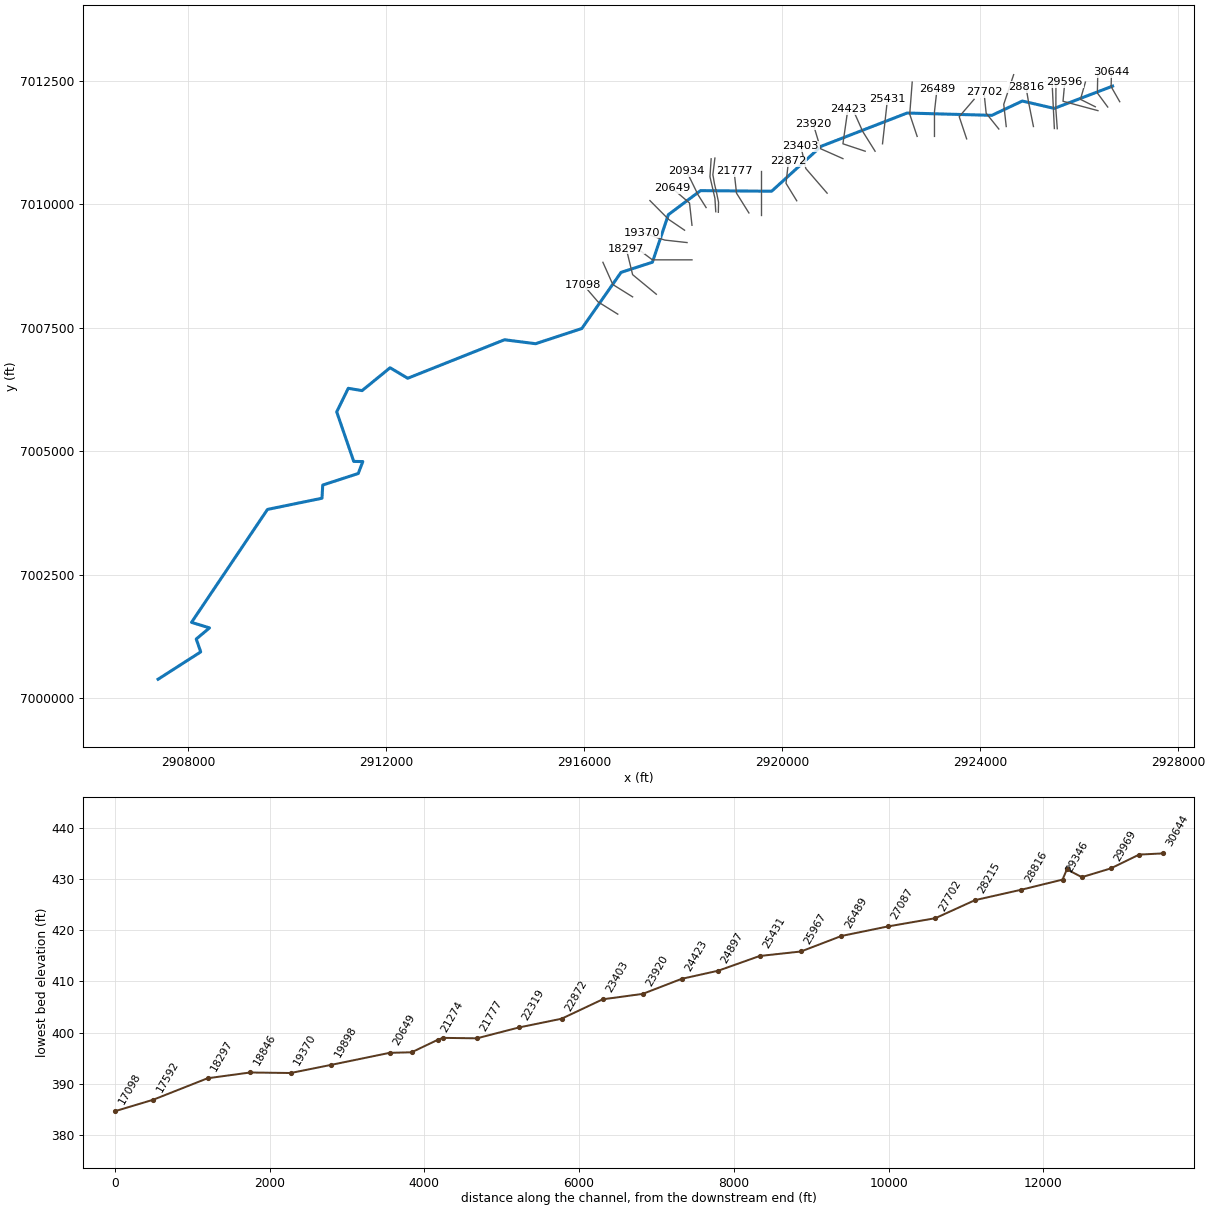
--- MUDDY CREEK.prj (project) ---

Proj Title=MUDDY CREEK Base Level Engineering
Current Plan=p01
Default Exp/Contr=0.3,0.1
English Units
Geom File=g01
Flow File=f01
Plan File=p01
BEGIN DESCRIPTION:
MUDDY CREEK
END DESCRIPTION:

--- MUDDY CREEK.p01 (plan) ---

Plan Title=Multiple Run
Short Identifier=Multiple
Geom File=g01
Flow File=f01
Subcritical Flow
K Sum by GR= 0
Std Step Tol= 0.01
Critical Tol= 0.01
Num of Std Step Trials= 20
Max Error Tol= 0.3
Flow Tol Ratio= 0.001
Split Flow NTrial= 30
Split Flow Tol= 0.02
Split Flow Ratio= 0.02
Log Output Level= 0
Friction Slope Method= 1
Unsteady Friction Slope Method= 2
Unsteady Bridges Friction Slope Method= 1
Parabolic Critical Depth
Global Vel Dist=  1 , 1 , 1
Global Log Level= 0
CheckData=True
Encroach Param= -1, 0, 0, 0
BEGIN DESCRIPTION:
Multiple Run
END DESCRIPTION:

--- MUDDY CREEK.f01 (steady flow) ---

Flow Title=Multiple
Program Version=5.07
Number of Profiles= 7
Profile Names=10-year,25-year,50-year,1pct_min,100-year,1pct_plu,500-year
River Rch & RM=MUDDY CREEK,Reach-1         ,30644
     488     649     779     466     929    1854    1322
River Rch & RM=MUDDY CREEK,Reach-1         ,29403
     729     990    1204     728    1452    2897    2115
River Rch & RM=MUDDY CREEK,Reach-1         ,23403
     952    1305    1597     970    1935    3862    2848
River Rch & RM=MUDDY CREEK,Reach-1         ,13713
    1701    2398    2992    1848    3687    7356    5617
River Rch & RM=MUDDY CREEK,Reach-1         ,11344
    2634    3760    4730    2941    5868   11709    9060
River Rch & RM=MUDDY CREEK,Reach-1         ,10909
    2711    3869    4866    3025    6036   12043    9314
River Rch & RM=MUDDY CREEK,Reach-1         ,5744
    2827    4030    5063    3144    6273   12516    9656
Boundary for River Rch & Prof#=MUDDY CREEK,Reach-1         , 1
Up Type= 0
Dn Type= 3
Dn Slope=0.00352
Boundary for River Rch & Prof#=MUDDY CREEK,Reach-1         , 2
Up Type= 0
Dn Type= 3
Dn Slope=0.00352
Boundary for River Rch & Prof#=MUDDY CREEK,Reach-1         , 3
Up Type= 0
Dn Type= 3
Dn Slope=0.00352
Boundary for River Rch & Prof#=MUDDY CREEK,Reach-1         , 4
Up Type= 0
Dn Type= 3
Dn Slope=0.00352
Boundary for River Rch & Prof#=MUDDY CREEK,Reach-1         , 5
Up Type= 0
Dn Type= 3
Dn Slope=0.00352
Boundary for River Rch & Prof#=MUDDY CREEK,Reach-1         , 6
Up Type= 0
Dn Type= 3
Dn Slope=0.00352
Boundary for River Rch & Prof#=MUDDY CREEK,Reach-1         , 7
Up Type= 0
Dn Type= 3
Dn Slope=0.00352
DSS Import GetInterval= 0
DSS Import GetPeak= 0
DSS Import FillOption= 0

--- MUDDY CREEK.g01 (geometry) ---

Geom Title=Existing Conditions

River Reach=MUDDY CREEK,Reach-1
Reach XY= 30
      2926674.62      7012393.24      2925495.28      7011941.95
      2924850.49      7012091.35      2924235.05      7011801.53
      2922521.57      7011848.40      2920784.18      7011174.27
      2919784.07      7010264.37      2918347.29      7010276.81
      2917697.34      7009789.51      2917374.88      7008826.57
      2916741.41      7008621.43      2915948.89      7007484.43
      2915013.99      7007176.19      2914387.00      7007256.61
      2912430.66      7006476.71      2912074.25      7006689.42
      2911508.26      7006226.33      2911229.15      7006273.29
      2910995.64      7005795.92      2911339.49      7004792.55
      2911522.57      7004789.51      2911430.98      7004547.72
      2910713.37      7004314.07      2910698.11      7004046.88
      2909596.39      7003820.05      2908061.64      7001532.55
      2908425.59      7001420.71      2908157.20      7001195.36
      2908247.45      7000934.52      2907385.59      7000380.71

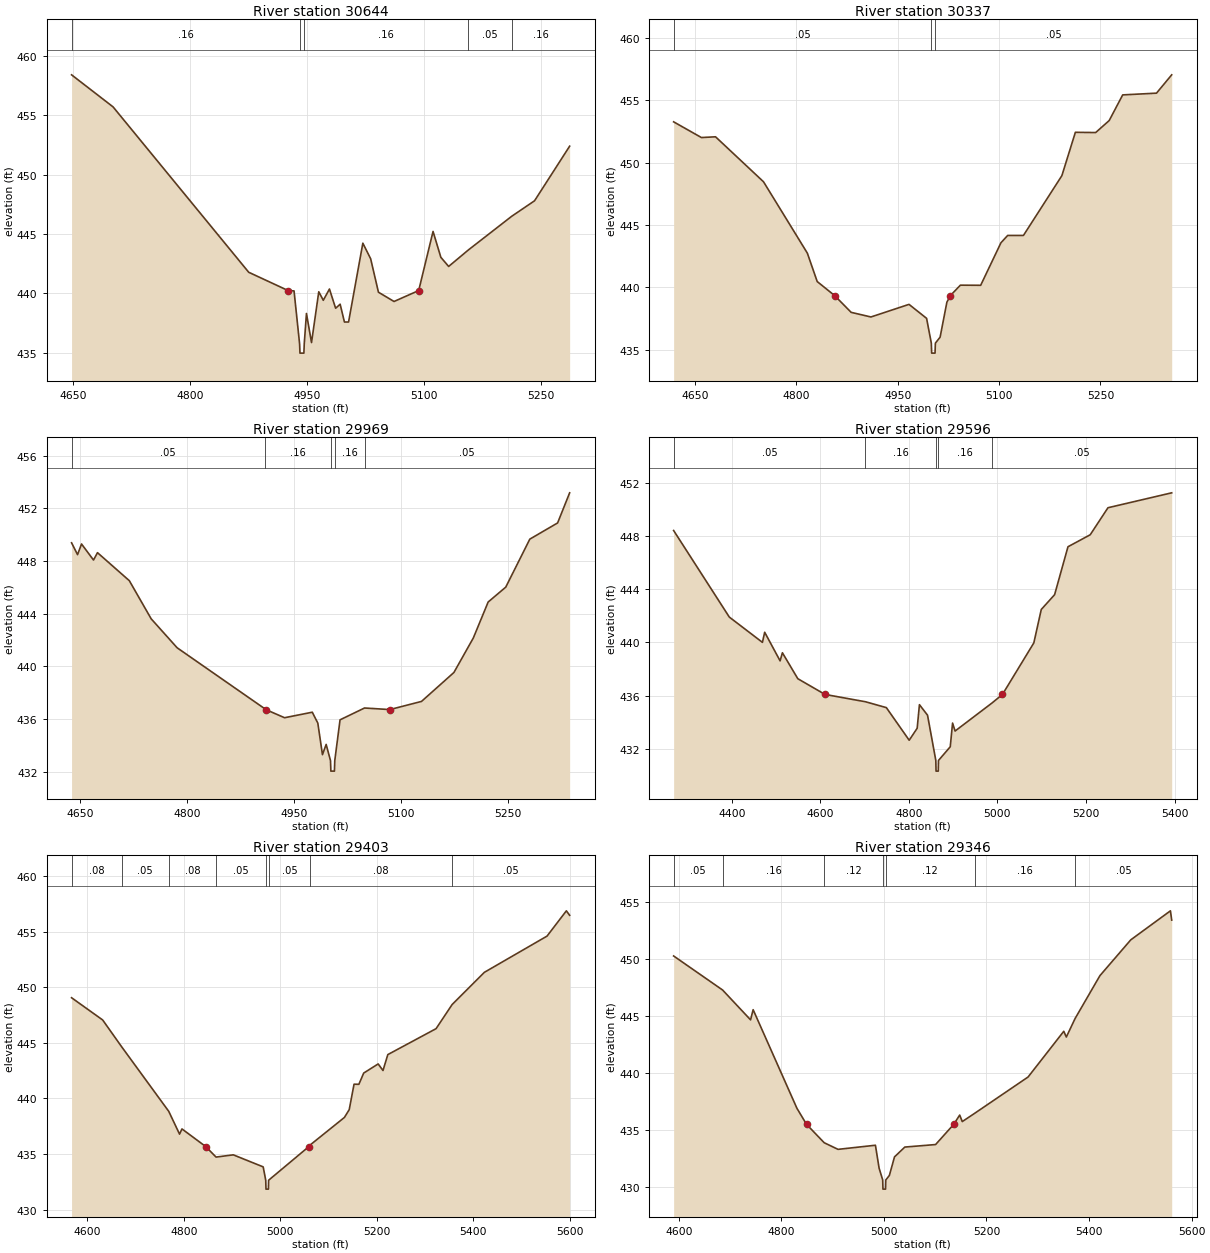
Type RM Length L Ch R = 1,30644,307,307,307
BEGIN DESCRIPTION:
MUDDY CREEK 43.0
END DESCRIPTION:
XS GIS Cut Line= 3
      2926818.52      7012077.64      2926644.54      7012383.29
      2926651.85      7012670.00
#Sta/Elev= 30
  4648.3  458.40  4701.5  455.70  4875.4  441.77  4925.9  440.23  4933.5  440.20
  4940.6  435.76  4941.1  434.96  4946.1  434.96  4946.6  435.76  4949.4  438.30
  4955.9  435.85  4965.2  440.13  4971.0  439.41  4978.9  440.36  4986.8  438.74
  4992.6  439.08  4998.1  437.58  5003.4  437.58  5021.7  444.22  5031.7  442.91
  5041.7  440.09  5061.7  439.31  5093.3  440.23  5111.7  445.21  5121.7  443.03
  5131.7  442.26  5156.8  443.64  5212.4  446.48  5241.8  447.79  5286.8  452.39
#Mann=5,-1,0
  4648.3    0.16       0  4940.6    0.07       0  4946.6    0.16       0
  5156.8    0.05       0  5212.4    0.16       0
Bank Sta=4925.9,5093.3
Exp/Cntr=0.3,0.1

Type RM Length L Ch R = 1,30337,368,368,368
BEGIN DESCRIPTION:
Mapping XS d6b5b69d
END DESCRIPTION:
XS GIS Cut Line= 3
      2926576.34      7011969.56      2926366.70      7012254.72
      2926374.51      7012637.51
#Sta/Elev= 30
  4618.6  453.28  4659.7  452.02  4680.6  452.08  4751.6  448.47  4816.4  442.75
  4831.0  440.47  4856.9  439.34  4881.2  438.00  4910.5  437.63  4966.8  438.64
  4992.8  437.52  4999.8  435.53  5000.3  434.73  5005.3  434.73  5005.8  435.53
  5012.8  436.01  5022.8  438.81  5027.9  439.34  5042.8  440.18  5072.8  440.17
  5102.8  443.58  5112.8  444.17  5136.1  444.17  5192.9  448.96  5212.9  452.44
  5242.9  452.42  5262.9  453.38  5282.9  455.44  5332.9  455.58  5355.4  457.05
#Mann=3,-1,0
  4618.6    0.05       0  4999.8    0.03       0  5005.8    0.05       0
Bank Sta=4856.9,5027.9
Exp/Cntr=0.3,0.1

Type RM Length L Ch R = 1,29969,373,373,373
BEGIN DESCRIPTION:
MUDDY CREEK 42.0
END DESCRIPTION:
XS GIS Cut Line= 3
      2926325.02      7011974.99      2926025.00      7012125.00
      2926124.99      7012474.97
#Sta/Elev= 30
  4637.5  449.39  4645.9  448.49  4651.5  449.30  4668.3  448.08  4673.9  448.64
  4718.6  446.51  4749.3  443.61  4785.7  441.41  4908.9  436.77  4910.3  436.71
  4936.6  436.09  4975.5  436.51  4983.3  435.68  4989.8  433.28  4995.0  434.06
  5001.1  432.83  5001.6  432.03  5006.6  432.03  5007.1  432.83  5014.5  435.93
  5048.9  436.83  5084.4  436.71  5128.9  437.33  5174.4  439.53  5201.7  442.16
  5222.5  444.89  5247.2  446.02  5281.0  449.67  5320.0  450.90  5336.9  453.19
#Mann=5,-1,0
  4637.5    0.05       0  4908.9    0.16       0  5001.1    0.07       0
  5007.1    0.16       0  5048.9    0.05       0
Bank Sta=4910.3,5084.4
Exp/Cntr=0.3,0.1

Type RM Length L Ch R = 1,29596,193,193,193
BEGIN DESCRIPTION:
MUDDY CREEK 41.0
END DESCRIPTION:
XS GIS Cut Line= 3
      2926378.70      7011896.66      2925672.65      7012086.41
      2925708.61      7012478.27
#Sta/Elev= 30
  4268.9  448.40  4394.6  441.90  4469.4  440.00  4474.5  440.76  4509.3  438.61
  4514.5  439.22  4549.3  437.27  4610.7  436.09  4702.0  435.54  4749.2  435.10
  4800.8  432.65  4818.8  433.55  4823.9  435.32  4842.2  434.53  4860.9  431.13
  4861.4  430.33  4866.4  430.33  4866.9  431.13  4893.5  432.16  4898.7  433.94
  4904.4  433.34  4987.9  435.45  5011.4  436.09  5082.2  439.96  5099.0  442.47
  5129.1  443.58  5159.3  447.18  5209.5  448.08  5249.6  450.11  5393.5  451.23
#Mann=5,-1,0
  4268.9    0.05       0  4702.0    0.16       0  4860.9    0.03       0
  4866.9    0.16       0  4987.9    0.05       0
Bank Sta=4610.7,5011.4
Exp/Cntr=0.3,0.1

Type RM Length L Ch R = 1,29403,57,57,57
BEGIN DESCRIPTION:
Mapping XS 3d2a18f9
END DESCRIPTION:
XS GIS Cut Line= 3
      2925556.31      7011530.64      2925528.10      7011923.38
      2925530.27      7012561.82
#Sta/Elev= 30
  4567.6  449.05  4632.1  447.05  4671.1  444.66  4769.0  438.84  4791.4  436.79
  4796.4  437.26  4845.8  435.67  4867.0  434.73  4902.8  434.93  4964.7  433.85
  4970.0  432.65  4970.5  431.85  4975.5  431.85  4976.0  432.65  5059.3  435.67
  5062.7  435.84  5133.0  438.29  5143.0  438.99  5153.0  441.28  5163.0  441.27
  5173.0  442.28  5203.0  443.10  5213.0  442.51  5223.0  443.94  5323.0  446.27
  5356.3  448.44  5423.0  451.33  5553.0  454.59  5593.0  456.86  5599.8  456.46
#Mann=8,-1,0
  4567.6    0.08       0  4671.1    0.05       0  4769.0    0.08       0
  4867.0    0.05       0  4970.0    0.04       0  4976.0    0.05       0
  5062.7    0.08       0  5356.3    0.05       0
Bank Sta=4845.8,5059.3
Exp/Cntr=0.3,0.1

Type RM Length L Ch R = 1,29346,530,530,530
BEGIN DESCRIPTION:
Mapping XS 291769f7
END DESCRIPTION:
XS GIS Cut Line= 3
      2925497.72      7011534.89      2925478.19      7011925.55
      2925449.99      7012504.72
#Sta/Elev= 30
  4590.1  450.25  4685.6  447.27  4740.1  444.66  4745.1  445.55  4830.5  436.92
  4849.2  435.52  4883.6  433.91  4910.6  433.33  4983.5  433.69  4990.7  431.68
  4997.7  430.65  4998.2  429.85  5003.2  429.85  5003.7  430.65  5010.7  431.05
  5020.7  432.67  5040.8  433.53  5100.8  433.75  5136.2  435.52  5147.8  436.33
  5152.8  435.76  5177.2  436.49  5281.1  439.66  5350.7  443.66  5355.7  443.16
  5372.8  444.78  5421.2  448.53  5481.3  451.66  5558.6  454.20  5561.1  453.39
#Mann=7,-1,0
  4590.1    0.05       0  4685.6    0.16       0  4883.6    0.12       0
  4997.7    0.07       0  5003.7    0.12       0  5177.2    0.16       0
  5372.8    0.05       0
Bank Sta=4849.2,5136.2
Exp/Cntr=0.3,0.1

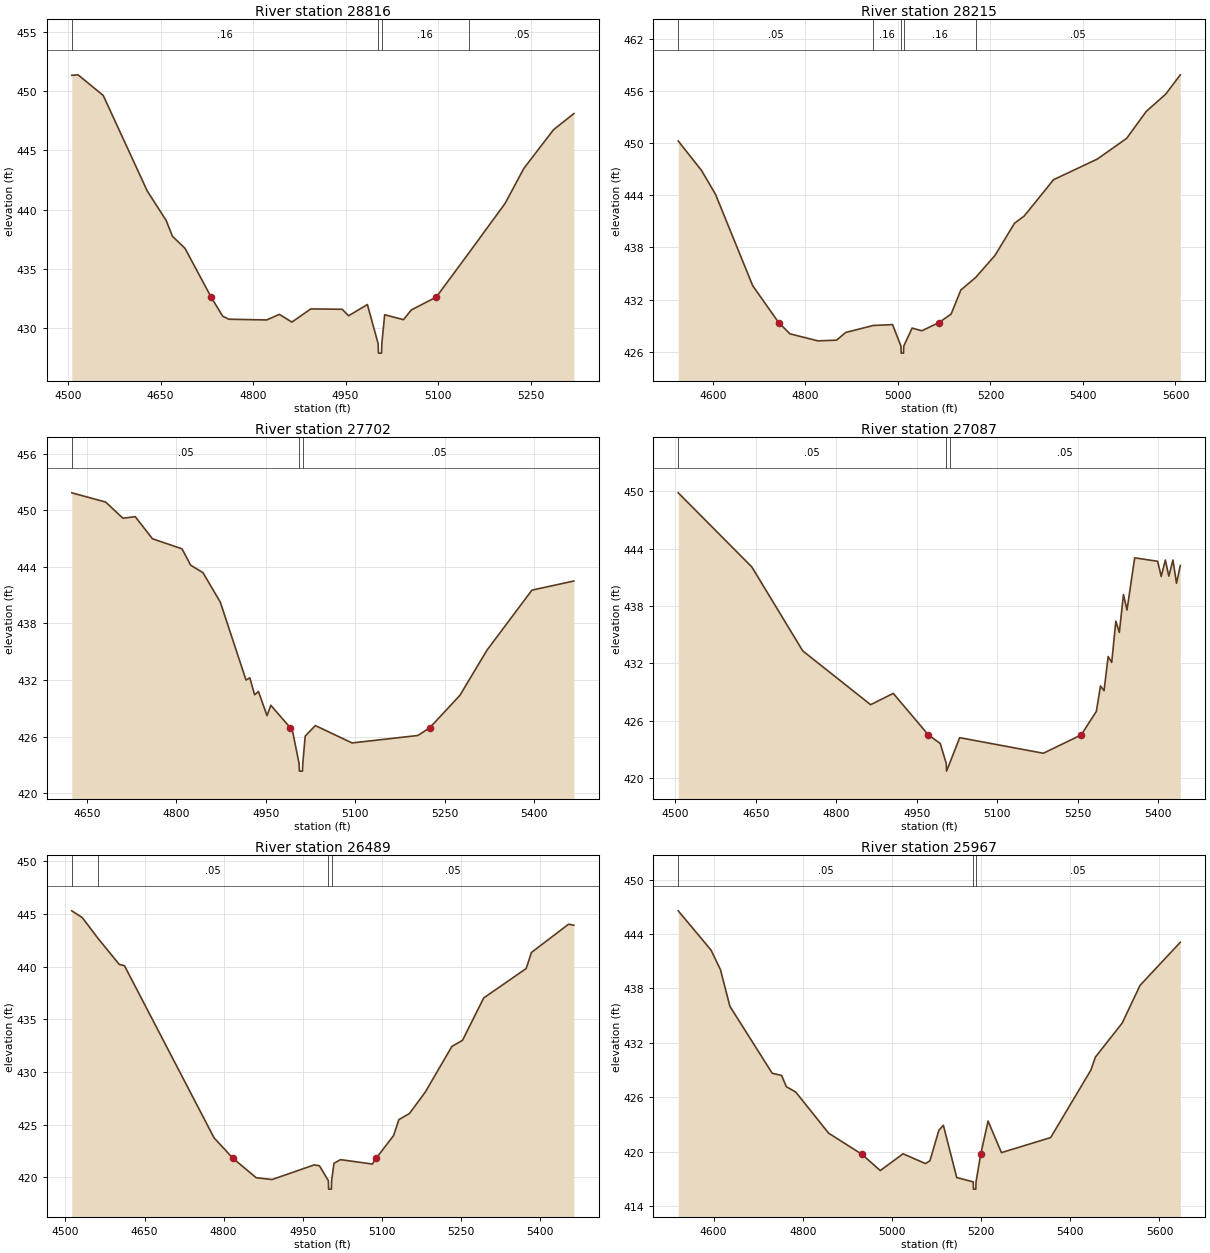
Type RM Length L Ch R = 1,28816,601,601,601
BEGIN DESCRIPTION:
MUDDY CREEK 39.0
END DESCRIPTION:
XS GIS Cut Line= 3
      2925075.00      7011575.01      2924975.00      7012075.00
      2924925.01      7012374.97
#Sta/Elev= 30
  4506.1  451.33  4516.3  451.37  4557.1  449.63  4628.5  441.57  4659.1  439.09
  4669.3  437.75  4689.7  436.73  4732.0  432.62  4750.8  431.00  4761.0  430.75
  4822.2  430.69  4842.6  431.16  4863.0  430.51  4893.6  431.62  4944.6  431.59
  4954.8  431.04  4985.4  431.99  5002.8  428.69  5003.3  427.89  5008.3  427.89
  5008.8  428.69  5013.4  431.13  5043.9  430.71  5056.5  431.53  5097.1  432.62
  5149.9  436.34  5208.6  440.52  5239.0  443.47  5287.2  446.74  5320.1  448.10
#Mann=4,-1,0
  4506.1    0.16       0  5002.8    0.07       0  5008.8    0.16       0
  5149.9    0.05       0
Bank Sta=4732,5097.1
Exp/Cntr=0.3,0.1

Type RM Length L Ch R = 1,28215,513,513,513
BEGIN DESCRIPTION:
MUDDY CREEK 38.0
END DESCRIPTION:
XS GIS Cut Line= 3
      2924525.00      7011574.99      2924475.00      7012025.00
      2924674.99      7012624.97
#Sta/Elev= 30
  4525.3  450.24  4575.6  446.86  4605.8  444.12  4686.3  433.60  4742.3  429.37
  4766.8  428.07  4827.2  427.26  4867.4  427.34  4887.5  428.23  4947.0  429.03
  4988.6  429.13  5006.7  426.65  5007.2  425.85  5012.2  425.85  5012.7  426.65
  5030.8  428.73  5051.9  428.42  5089.0  429.37  5115.1  430.34  5136.2  433.11
  5168.2  434.55  5210.0  437.09  5252.1  440.78  5273.2  441.62  5336.5  445.79
  5431.3  448.17  5494.6  450.55  5536.7  453.63  5578.9  455.63  5610.5  457.85
#Mann=5,-1,0
  4525.3    0.05       0  4947.0    0.16       0  5006.7    0.07       0
  5012.7    0.16       0  5168.2    0.05       0
Bank Sta=4742.3,5089
Exp/Cntr=0.3,0.1

Type RM Length L Ch R = 1,27702,615,615,615
BEGIN DESCRIPTION:
MUDDY CREEK 37.0
END DESCRIPTION:
XS GIS Cut Line= 3
      2924375.02      7011524.97      2924119.68      7011844.04
      2924075.00      7012274.97
#Sta/Elev= 30
  4624.9  451.84  4681.8  450.86  4710.6  449.15  4731.4  449.31  4760.2  446.97
  4809.8  445.90  4824.2  444.17  4845.0  443.37  4873.9  440.26  4917.1  431.99
  4923.5  432.22  4931.5  430.42  4937.9  430.78  4952.3  428.21  4958.7  429.31
  4991.1  426.95  4995.5  426.46  5006.1  423.13  5006.6  422.33  5011.8  422.33
  5012.3  423.13  5016.3  426.04  5033.3  427.16  5094.9  425.32  5205.4  426.11
  5225.5  426.95  5275.8  430.37  5321.2  435.16  5396.5  441.52  5466.8  442.49
#Mann=3,-1,0
  4624.9    0.05       0  5006.1    0.03       0  5012.3    0.05       0
Bank Sta=4991.1,5225.5
Exp/Cntr=0.3,0.1

Type RM Length L Ch R = 1,27087,598,598,598
BEGIN DESCRIPTION:
MUDDY CREEK 36.0
END DESCRIPTION:
XS GIS Cut Line= 3
      2923725.01      7011324.98      2923575.00      7011775.00
      2923874.97      7012124.97
#Sta/Elev= 30
  4505.6  449.83  4642.7  442.08  4737.5  433.30  4864.0  427.67  4906.2  428.85
  4971.6  424.51  4993.7  423.61  5004.9  421.52  5005.4  420.72  5011.1  421.52
  5029.9  424.22  5185.8  422.59  5256.3  424.51  5284.5  426.97  5292.2  429.62
  5298.8  429.13  5306.5  432.71  5313.1  432.09  5320.8  436.41  5327.3  435.23
  5335.0  439.19  5341.6  437.57  5355.9  443.03  5398.7  442.67  5405.3  441.08
  5413.0  442.80  5419.5  441.11  5427.2  442.80  5433.8  440.37  5440.9  442.22
#Mann=3,-1,0
  4505.6    0.05       0  5004.9    0.03       0  5011.1    0.05       0
Bank Sta=4971.6,5256.3
Exp/Cntr=0.3,0.1

Type RM Length L Ch R = 1,26489,522,522,522
BEGIN DESCRIPTION:
MUDDY CREEK 35.0
END DESCRIPTION:
XS GIS Cut Line= 3
      2923075.00      7011375.02      2923075.00      7011875.00
      2923124.99      7012324.95
#Sta/Elev= 30
  4511.9  445.29  4531.9  444.65  4561.5  442.69  4601.9  440.21  4611.9  440.08
  4781.9  423.74  4817.7  421.80  4861.9  419.95  4891.9  419.78  4971.9  421.17
  4981.9  421.09  4998.8  419.67  4999.3  418.87  5004.5  418.87  5005.0  419.67
  5009.4  421.32  5021.9  421.67  5082.3  421.25  5089.5  421.80  5122.6  423.96
  5132.6  425.47  5152.7  426.05  5182.9  428.10  5233.2  432.42  5253.4  433.00
  5293.6  437.02  5374.1  439.81  5384.2  441.34  5454.6  444.02  5464.6  443.92
#Mann=4,-1,0
  4511.9     0.1       0  4561.5    0.05       0  4998.8    0.03       0
  5005.0    0.05       0
Bank Sta=4817.7,5089.5
Exp/Cntr=0.3,0.1

Type RM Length L Ch R = 1,25967,536,536,536
BEGIN DESCRIPTION:
MUDDY CREEK 34.0
END DESCRIPTION:
XS GIS Cut Line= 3
      2922724.99      7011375.04      2922575.00      7011825.00
      2922625.00      7012474.98
#Sta/Elev= 30
  4520.5  446.57  4594.2  442.23  4615.3  440.06  4636.4  436.03  4731.3  428.64
  4752.4  428.40  4762.9  427.16  4784.0  426.57  4857.8  422.03  4932.4  419.70
  4973.7  417.90  5024.9  419.75  5075.0  418.67  5085.1  418.98  5105.1  422.34
  5115.2  422.90  5145.2  417.13  5182.2  416.65  5182.7  415.85  5188.0  415.85
  5188.5  416.65  5199.0  419.70  5215.5  423.36  5245.5  419.88  5355.9  421.54
  5446.1  428.99  5456.2  430.42  5516.3  434.18  5556.5  438.35  5646.7  443.10
#Mann=3,-1,0
  4520.5    0.05       0  5182.2    0.03       0  5188.5    0.05       0
Bank Sta=4932.4,5199
Exp/Cntr=0.3,0.1

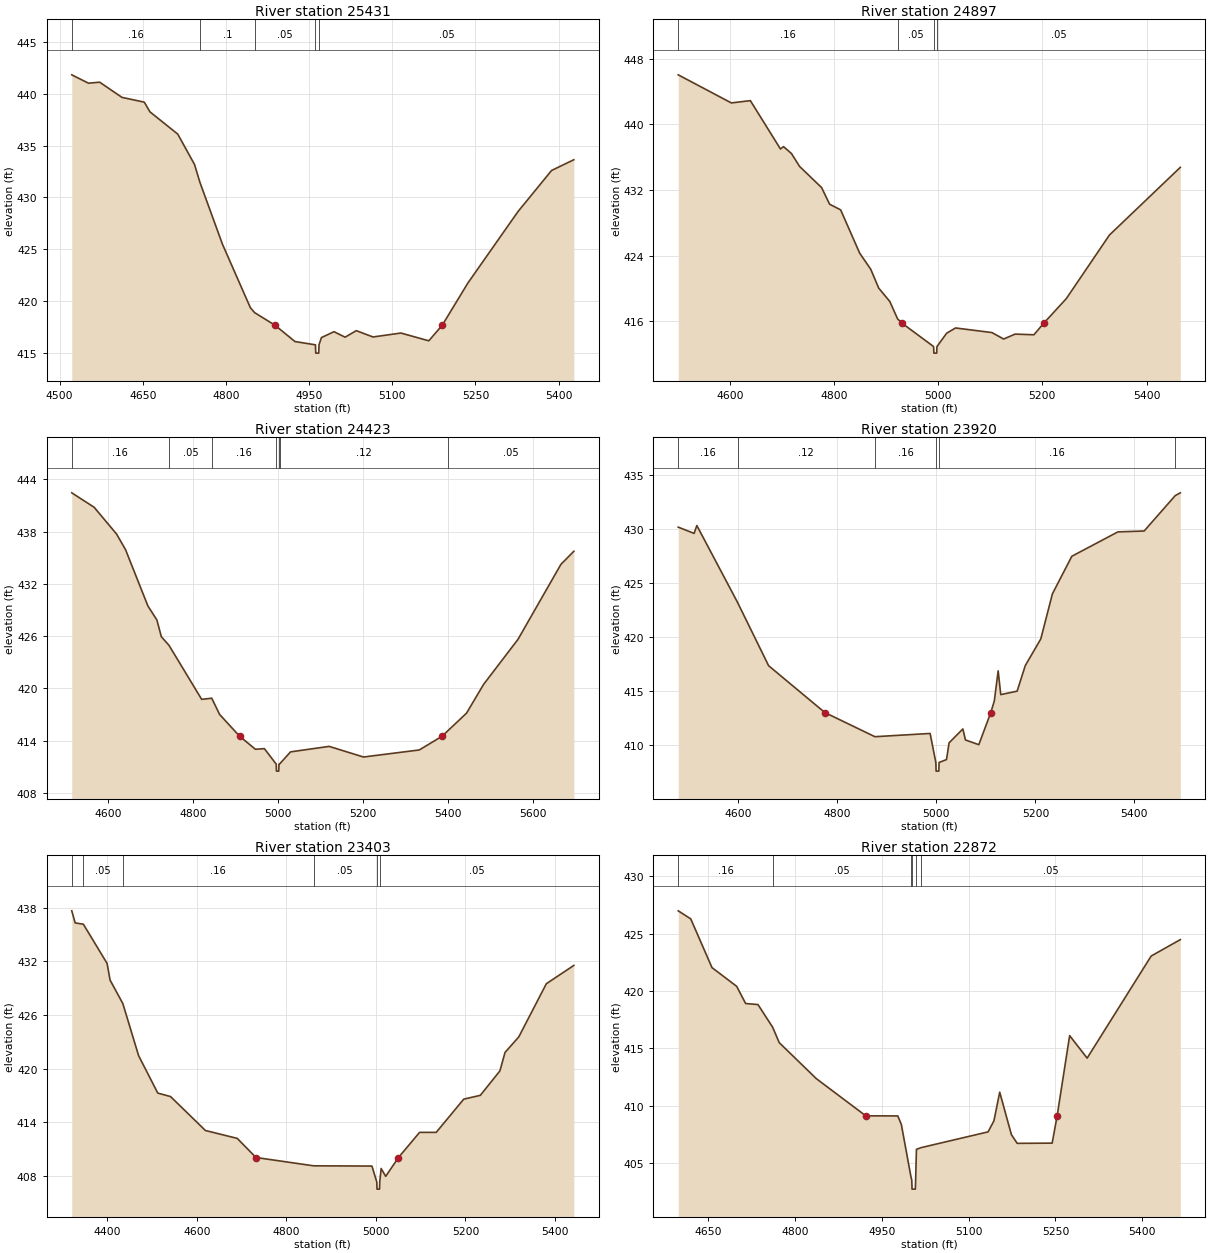
Type RM Length L Ch R = 1,25431,534,534,534
BEGIN DESCRIPTION:
MUDDY CREEK 33.0
END DESCRIPTION:
XS GIS Cut Line= 3
      2922025.00      7011225.00      2922075.00      7011675.00
      2922125.00      7012124.96
#Sta/Elev= 30
  4521.9  441.84  4552.1  441.03  4572.2  441.13  4612.5  439.66  4652.7  439.20
  4662.8  438.27  4713.1  436.11  4743.3  433.18  4753.0  431.46  4793.6  425.49
  4843.9  419.36  4851.7  418.87  4888.6  417.65  4924.4  416.08  4961.4  415.76
  4961.9  414.96  4967.3  414.96  4967.8  415.76  4972.2  416.46  4994.8  417.03
  5014.9  416.50  5035.0  417.13  5065.2  416.52  5115.5  416.90  5165.8  416.15
  5190.0  417.65  5236.3  421.73  5326.8  428.64  5387.2  432.60  5427.4  433.64
#Mann=5,-1,0
  4521.9    0.16       0  4753.0     0.1       0  4851.7    0.05       0
  4961.4    0.03       0  4967.8    0.05       0
Bank Sta=4888.6,5190
Exp/Cntr=0.3,0.1

Type RM Length L Ch R = 1,24897,474,474,474
BEGIN DESCRIPTION:
MUDDY CREEK 32.0
END DESCRIPTION:
XS GIS Cut Line= 3
      2921874.99      7011075.02      2921625.00      7011475.00
      2921425.01      7011924.98
#Sta/Elev= 30
  4500.8  446.06  4602.8  442.63  4639.3  442.91  4697.1  437.01  4703.0  437.30
  4718.3  436.45  4733.7  434.89  4776.1  432.30  4791.5  430.27  4812.7  429.58
  4849.2  424.30  4870.5  422.33  4885.8  420.03  4907.0  418.41  4922.1  416.27
  4931.0  415.73  4991.2  412.90  4991.7  412.10  4997.1  412.10  4997.6  412.90
  5016.2  414.53  5033.3  415.17  5103.1  414.61  5125.7  413.82  5147.6  414.42
  5183.8  414.34  5202.4  415.73  5246.1  418.76  5328.8  426.51  5464.9  434.77
#Mann=4,-1,0
  4500.8    0.16       0  4922.1    0.05       0  4991.2    0.03       0
  4997.6    0.05       0
Bank Sta=4931,5202.4
Exp/Cntr=0.3,0.1

Type RM Length L Ch R = 1,24423,503,503,503
BEGIN DESCRIPTION:
MUDDY CREEK 31.0
END DESCRIPTION:
XS GIS Cut Line= 3
      2921675.01      7011075.00      2921225.00      7011225.00
      2921325.01      7011925.05
#Sta/Elev= 30
  4514.0  442.46  4566.7  440.80  4619.4  437.73  4640.5  435.94  4693.2  429.47
  4714.3  427.86  4724.8  425.94  4742.7  424.96  4819.7  418.75  4843.4  418.88
  4861.9  417.02  4908.9  414.52  4946.2  413.02  4967.3  413.09  4995.2  411.31
  4995.7  410.51  5001.1  410.51  5001.6  411.31  5003.3  411.34  5028.8  412.72
  5119.7  413.35  5200.5  412.13  5331.8  412.94  5385.6  414.52  5400.0  415.19
  5442.9  417.16  5483.3  420.48  5564.1  425.64  5665.1  434.25  5695.5  435.75
#Mann=7,-1,0
  4514.0    0.16       0  4742.7    0.05       0  4843.4    0.16       0
  4995.2    0.07       0  5001.6    0.16       0  5003.3    0.12       0
  5400.0    0.05       0
Bank Sta=4908.9,5385.6
Exp/Cntr=0.3,0.1

Type RM Length L Ch R = 1,23920,517,517,517
BEGIN DESCRIPTION:
MUDDY CREEK 30.0
END DESCRIPTION:
XS GIS Cut Line= 3
      2921224.97      7010925.01      2920775.00      7011125.00
      2920625.01      7011624.97
#Sta/Elev= 30
  4478.4  430.19  4510.5  429.61  4516.0  430.34  4598.2  423.22  4661.0  417.35
  4774.6  413.01  4875.8  410.77  4987.3  411.07  4998.9  408.38  4999.4  407.58
  5004.9  407.58  5005.4  408.38  5020.4  408.65  5025.6  410.20  5053.5  411.49
  5058.7  410.47  5085.7  410.03  5109.9  413.01  5117.0  414.08  5124.8  416.87
  5130.0  414.67  5163.1  414.99  5179.6  417.36  5210.9  419.83  5234.4  424.01
  5273.6  427.49  5366.7  429.75  5419.7  429.83  5482.5  433.11  5492.8  433.37
#Mann=6,-1,0
  4478.4    0.16       0  4598.2    0.12       0  4875.8    0.16       0
  4998.9    0.07       0  5005.4    0.16       0  5482.5    0.05       0
Bank Sta=4774.6,5109.9
Exp/Cntr=0.3,0.1

Type RM Length L Ch R = 1,23403,531,531,531
BEGIN DESCRIPTION:
MUDDY CREEK 29.0
END DESCRIPTION:
XS GIS Cut Line= 3
      2920905.80      7010225.16      2920475.00      7010725.00
      2920375.01      7011174.95
#Sta/Elev= 30
  4321.1  437.67  4328.7  436.32  4347.0  436.17  4400.0  431.78  4406.6  429.92
  4435.1  427.29  4470.3  421.46  4513.1  417.27  4541.6  416.88  4619.5  413.08
  4690.5  412.20  4732.3  410.06  4860.8  409.13  4991.2  409.10  5002.0  407.32
  5002.5  406.52  5008.1  406.52  5008.6  407.32  5011.7  408.83  5021.9  407.95
  5050.4  410.06  5097.5  412.87  5134.6  412.87  5196.1  416.59  5233.2  417.02
  5276.8  419.75  5288.3  421.82  5319.0  423.56  5380.5  429.51  5441.9  431.56
#Mann=6,-1,0
  4321.1    0.16       0  4347.0    0.05       0  4435.1    0.16       0
  4860.8    0.05       0  5002.0    0.03       0  5008.6    0.05       0
Bank Sta=4732.3,5050.4
Exp/Cntr=0.3,0.1

Type RM Length L Ch R = 1,22872,553,553,553
BEGIN DESCRIPTION:
MUDDY CREEK 28.0
END DESCRIPTION:
XS GIS Cut Line= 3
      2920291.21      7010071.51      2920075.00      7010425.00
      2920125.00      7010874.96
#Sta/Elev= 30
  4598.5  427.00  4620.1  426.30  4656.8  422.05  4699.4  420.42  4714.9  418.92
  4736.2  418.83  4761.7  416.84  4772.9  415.51  4837.0  412.37  4922.4  409.13
  4977.7  409.12  4983.8  408.38  5000.4  403.82  5001.8  403.54  5002.3  402.74
  5008.0  402.74  5008.5  403.54  5009.9  406.21  5018.2  406.36  5133.6  407.73
  5143.7  408.69  5153.7  411.19  5173.9  407.49  5183.9  406.73  5244.3  406.75
  5252.9  409.13  5274.5  416.12  5304.7  414.16  5415.3  423.06  5465.6  424.49
#Mann=6,-1,0
  4598.5    0.16       0  4761.7    0.05       0  5000.4    0.16       0
  5001.8    0.03       0  5008.5    0.16       0  5018.2    0.05       0
Bank Sta=4922.4,5252.9
Exp/Cntr=0.3,0.1

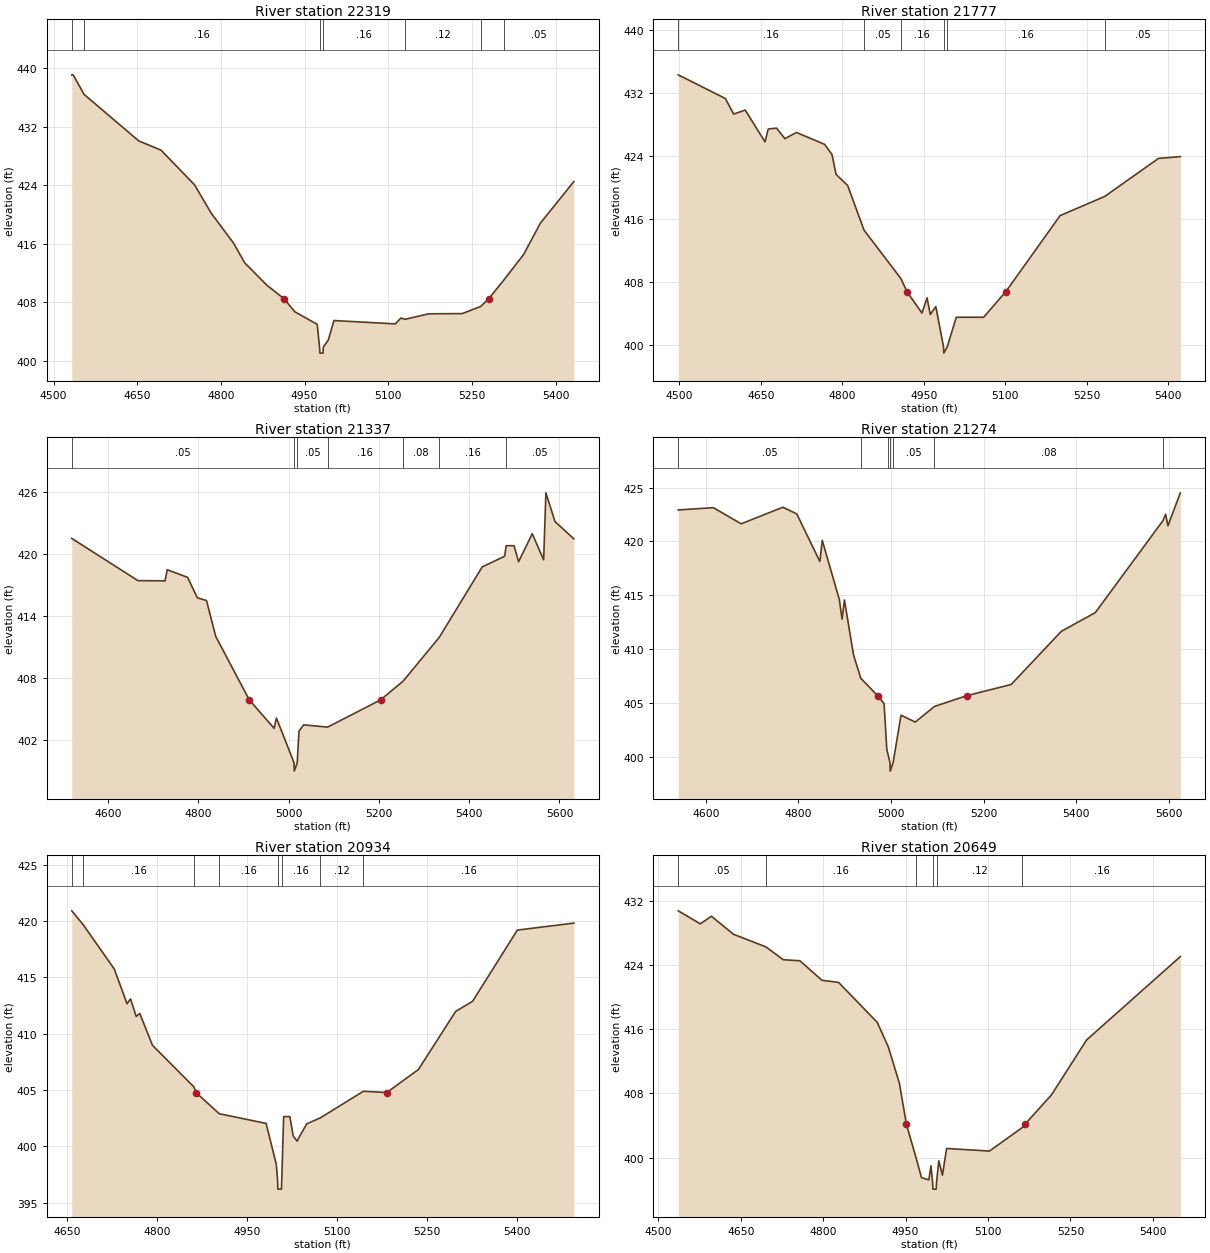
Type RM Length L Ch R = 1,22319,542,542,542
BEGIN DESCRIPTION:
MUDDY CREEK 27.0
END DESCRIPTION:
XS GIS Cut Line= 3
      2919575.00      7009775.00      2919575.00      7010225.00
      2919575.00      7010675.00
#Sta/Elev= 30
  4532.7  439.12  4535.2  439.12  4554.8  436.44  4652.7  430.08  4692.7  428.81
  4752.7  424.07  4782.7  420.18  4822.7  416.09  4842.7  413.39  4882.7  410.31
  4912.9  408.49  4932.7  406.68  4972.7  404.97  4976.9  401.83  4977.4  401.03
  4983.1  401.03  4983.6  401.83  4992.7  402.85  5002.7  405.49  5112.7  405.03
  5122.7  405.84  5130.0  405.66  5172.7  406.41  5232.7  406.44  5265.7  407.42
  5280.3  408.49  5307.0  411.01  5342.7  414.53  5372.7  418.82  5432.7  424.51
#Mann=7,-1,0
  4532.7    0.05       0  4554.8    0.16       0  4976.9    0.07       0
  4983.6    0.16       0  5130.0    0.12       0  5265.7    0.16       0
  5307.0    0.05       0
Bank Sta=4912.9,5280.3
Exp/Cntr=0.3,0.1

Type RM Length L Ch R = 1,21777,440,440,440
BEGIN DESCRIPTION:
MUDDY CREEK 26.0
END DESCRIPTION:
XS GIS Cut Line= 3
      2919325.03      7009824.96      2919075.00      7010225.00
      2919025.00      7010674.98
#Sta/Elev= 30
  4498.0  434.31  4584.7  431.30  4600.1  429.32  4621.3  429.83  4657.8  425.78
  4663.7  427.42  4679.1  427.53  4694.4  426.19  4715.6  426.98  4767.5  425.47
  4781.1  424.18  4788.7  421.64  4810.0  420.24  4840.1  414.56  4907.7  408.43
  4919.3  406.72  4946.8  404.01  4956.2  405.95  4962.1  403.83  4972.3  404.84
  4986.5  399.72  4987.0  398.92  4993.3  399.72  5010.0  403.48  5060.3  403.48
  5101.0  406.72  5201.2  416.41  5283.2  418.84  5382.3  423.68  5422.5  423.91
#Mann=6,-1,0
  4498.0    0.16       0  4840.1    0.05       0  4907.7    0.16       0
  4986.5    0.07       0  4993.3    0.16       0  5283.2    0.05       0
Bank Sta=4919.3,5101
Exp/Cntr=0.3,0.1

Type RM Length L Ch R = 1,21337,63,63,63
BEGIN DESCRIPTION:
Mapping XS 79cd95e1
END DESCRIPTION:
XS GIS Cut Line= 6
      2918707.57      7009838.44      2918711.91      7010040.29
      2918675.02      7010218.25      2918629.45      7010413.56
      2918596.90      7010600.19      2918638.12      7010936.53
#Sta/Elev= 30
  4519.4  421.54  4666.0  417.45  4726.0  417.43  4731.0  418.50  4776.0  417.77
  4797.6  415.79  4818.0  415.52  4838.4  412.05  4912.8  405.90  4967.8  403.15
  4972.9  404.15  5012.0  399.81  5012.5  399.01  5018.9  399.81  5022.9  402.89
  5033.2  403.49  5086.3  403.27  5203.5  405.90  5253.6  407.72  5333.7  411.96
  5428.9  418.78  5478.6  419.81  5482.0  420.83  5499.4  420.83  5509.5  419.28
  5539.7  421.99  5565.0  419.46  5570.0  425.95  5590.1  423.17  5631.9  421.50
#Mann=7,-1,0
  4519.4    0.05       0  5012.0    0.04       0  5018.9    0.05       0
  5086.3    0.16       0  5253.6    0.08       0  5333.7    0.16       0
  5482.0    0.05       0
Bank Sta=4912.8,5203.5
Exp/Cntr=0.3,0.1

Type RM Length L Ch R = 1,21274,340,340,340
BEGIN DESCRIPTION:
MUDDY CREEK 25.0
END DESCRIPTION:
XS GIS Cut Line= 4
      2918655.49      7009849.29      2918638.13      7010122.76
      2918538.25      7010556.93      2918562.06      7010921.73
#Sta/Elev= 30
  4540.2  422.93  4616.1  423.14  4676.2  421.64  4766.4  423.18  4796.4  422.56
  4846.3  418.14  4851.5  420.10  4888.3  414.61  4894.3  412.78  4899.4  414.56
  4919.1  409.44  4934.8  407.28  4971.0  405.67  4985.1  404.91  4991.0  400.67
  4994.0  400.13  4997.8  399.45  4998.3  398.65  5004.7  399.45  5021.7  403.85
  5052.5  403.21  5093.9  404.66  5164.2  405.67  5259.7  406.70  5368.0  411.64
  5441.7  413.39  5587.7  421.93  5593.6  422.52  5598.6  421.46  5625.3  424.52
#Mann=7,-1,0
  4540.2    0.05       0  4934.8    0.16       0  4994.0    0.05       0
  4997.8    0.04       0  5004.7    0.05       0  5093.9    0.08       0
  5587.7    0.16       0
Bank Sta=4971,5164.2
Exp/Cntr=0.3,0.1

Type RM Length L Ch R = 1,20934,285,285,285
BEGIN DESCRIPTION:
Mapping XS 2d0ab1ba
END DESCRIPTION:
XS GIS Cut Line= 3
      2918460.20      7009933.92      2918297.42      7010192.20
      2918065.21      7010669.63
#Sta/Elev= 30
  4658.4  420.89  4677.3  419.67  4729.2  415.73  4750.4  412.65  4756.3  413.08
  4765.7  411.52  4771.6  411.79  4792.8  408.96  4862.0  405.26  4865.3  404.77
  4904.0  402.89  4982.1  402.03  4999.1  398.38  5001.2  397.00  5001.7  396.20
  5007.6  396.20  5008.1  397.00  5011.3  402.63  5021.6  402.64  5027.2  400.92
  5033.5  400.46  5049.7  401.99  5072.3  402.52  5144.0  404.88  5183.1  404.77
  5235.7  406.81  5297.8  411.97  5325.9  412.86  5400.5  419.18  5494.6  419.80
#Mann=8,-1,0
  4658.4    0.05       0  4677.3    0.16       0  4862.0    0.12       0
  4904.0    0.16       0  5001.2    0.07       0  5008.1    0.16       0
  5072.3    0.12       0  5144.0    0.16       0
Bank Sta=4865.3,5183.1
Exp/Cntr=0.3,0.1

Type RM Length L Ch R = 1,20649,751,751,751
BEGIN DESCRIPTION:
MUDDY CREEK 24.0
END DESCRIPTION:
XS GIS Cut Line= 3
      2918175.00      7009575.00      2918125.00      7010025.00
      2917775.04      7010324.97
#Sta/Elev= 30
  4536.3  430.74  4576.5  429.12  4596.7  430.07  4636.9  427.82  4695.9  426.25
  4727.5  424.65  4757.7  424.52  4797.9  422.09  4828.1  421.83  4898.5  416.85
  4918.6  413.80  4938.8  409.26  4951.6  404.15  4969.0  400.02  4979.0  397.52
  4992.4  397.24  4996.2  399.00  4999.3  396.89  4999.8  396.09  5005.8  396.09
  5006.3  396.89  5010.5  399.62  5017.1  397.83  5024.7  401.15  5102.7  400.83
  5162.7  403.77  5167.1  404.15  5215.7  407.84  5279.4  414.66  5450.0  425.04
#Mann=6,-1,0
  4536.3    0.05       0  4695.9    0.16       0  4969.0    0.12       0
  4999.3    0.07       0  5006.3    0.12       0  5162.7    0.16       0
Bank Sta=4951.6,5167.1
Exp/Cntr=0.3,0.1

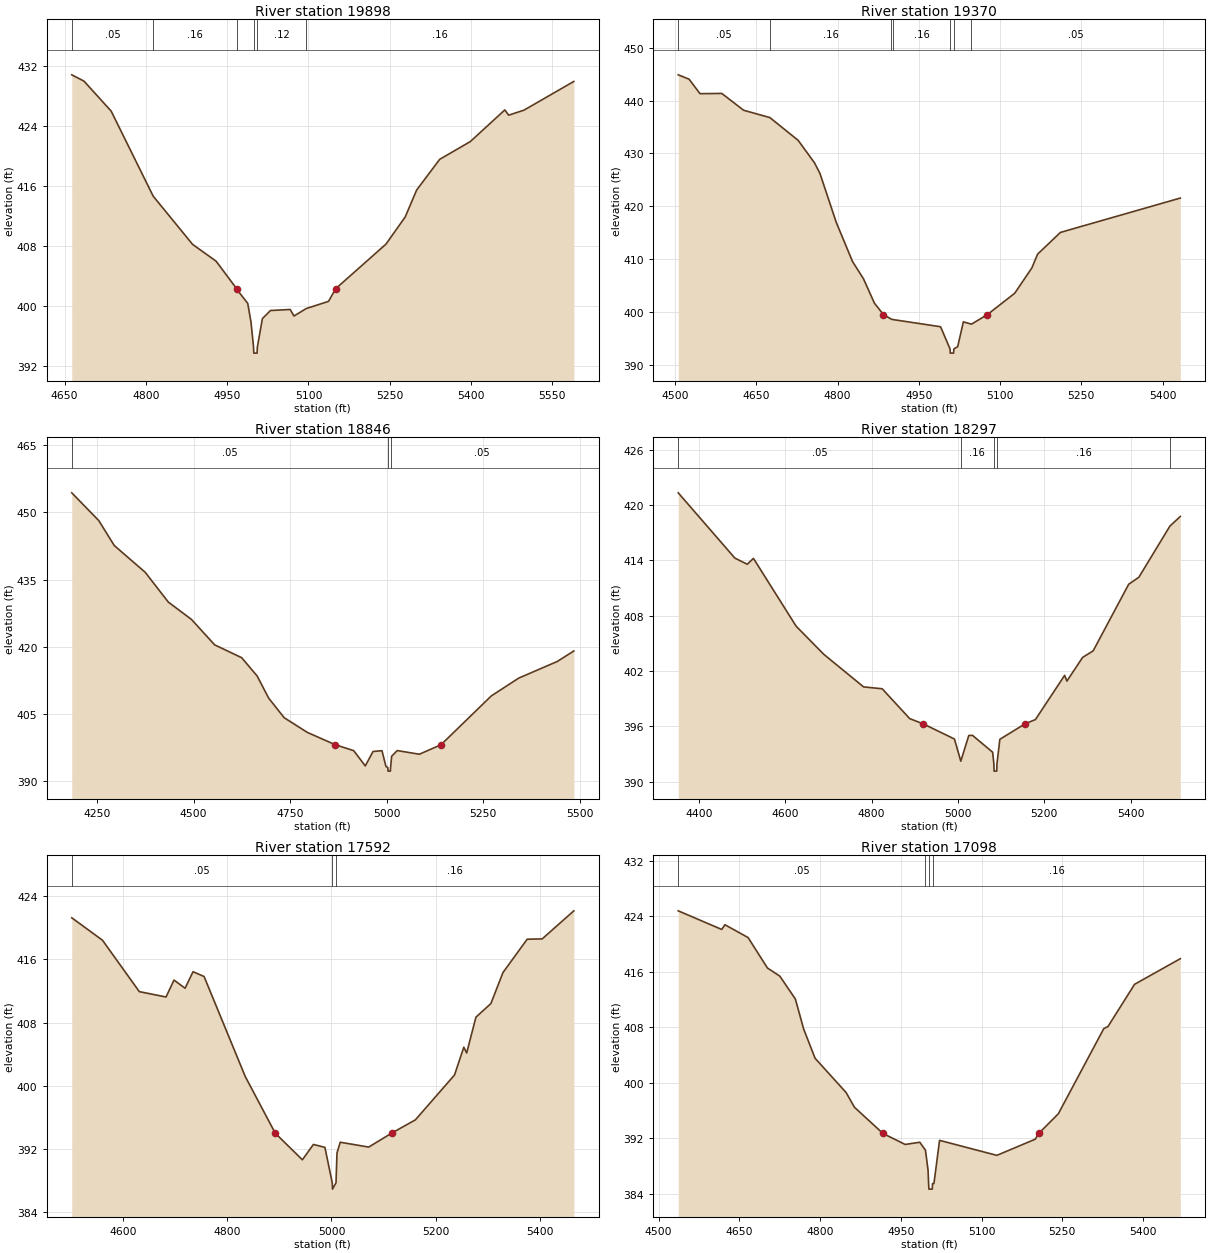
Type RM Length L Ch R = 1,19898,528,528,528
BEGIN DESCRIPTION:
MUDDY CREEK 23.0
END DESCRIPTION:
XS GIS Cut Line= 3
      2918024.98      7009475.02      2917700.67      7009695.97
      2917324.99      7010075.01
#Sta/Elev= 30
  4663.4  430.80  4685.8  429.97  4736.0  425.98  4813.6  414.65  4886.3  408.23
  4929.6  406.00  4967.5  402.34  4968.7  402.16  4988.0  400.38  4994.0  397.89
  4998.7  394.56  4999.2  393.76  5005.2  393.76  5005.7  394.56  5015.0  398.35
  5029.9  399.43  5066.2  399.57  5073.3  398.70  5095.8  399.69  5137.0  400.65
  5150.3  402.34  5243.0  408.27  5278.4  411.88  5299.6  415.47  5342.0  419.55
  5398.6  421.92  5462.2  426.13  5469.3  425.43  5497.6  426.10  5589.5  429.92
#Mann=6,-1,0
  4663.4    0.05       0  4813.6    0.16       0  4968.7    0.12       0
  4998.7    0.07       0  5005.7    0.12       0  5095.8    0.16       0
Bank Sta=4967.5,5150.3
Exp/Cntr=0.3,0.1

Type RM Length L Ch R = 1,19370,524,524,524
BEGIN DESCRIPTION:
MUDDY CREEK 22.0
END DESCRIPTION:
XS GIS Cut Line= 3
      2918074.97      7009225.00      2917625.00      7009275.00
      2917174.98      7009425.01
#Sta/Elev= 30
  4505.6  444.89  4525.7  444.06  4545.8  441.32  4586.1  441.36  4626.3  438.18
  4674.8  436.79  4726.9  432.49  4757.1  428.24  4767.2  426.23  4797.4  416.93
  4827.5  409.50  4847.7  406.24  4867.8  401.64  4884.6  399.45  4899.3  398.59
  4901.9  398.52  4990.0  397.16  5007.5  392.96  5008.0  392.16  5014.0  392.16
  5014.6  392.96  5021.6  393.38  5032.1  398.08  5047.1  397.65  5076.3  399.45
  5127.0  403.51  5158.6  408.31  5169.2  410.91  5211.3  415.03  5432.7  421.54
#Mann=7,-1,0
  4505.6    0.05       0  4674.8    0.16       0  4899.3    0.12       0
  4901.9    0.16       0  5007.5    0.07       0  5014.6    0.16       0
  5047.1    0.05       0
Bank Sta=4884.6,5076.3
Exp/Cntr=0.3,0.1

Type RM Length L Ch R = 1,18846,549,549,549
BEGIN DESCRIPTION:
MUDDY CREEK 21.0
END DESCRIPTION:
XS GIS Cut Line= 3
      2918175.03      7008875.00      2917375.00      7008875.00
      2916975.02      7009174.98
#Sta/Elev= 30
  4184.7  454.37  4254.7  448.17  4294.7  442.61  4374.7  436.65  4434.7  429.99
  4494.7  426.11  4554.7  420.44  4624.7  417.57  4664.7  413.49  4694.7  408.53
  4734.7  404.18  4794.7  400.90  4866.7  398.16  4914.7  396.83  4944.7  393.42
  4964.7  396.64  4987.9  396.82  4998.3  393.28  5003.1  393.06  5003.6  392.26
  5009.7  392.26  5010.2  393.06  5012.9  395.57  5027.4  396.85  5084.7  396.03
  5140.9  398.16  5271.2  409.06  5342.0  413.02  5442.0  416.74  5484.7  419.08
#Mann=3,-1,0
  4184.7    0.05       0  5003.1    0.03       0  5010.2    0.05       0
Bank Sta=4866.7,5140.9
Exp/Cntr=0.3,0.1

Type RM Length L Ch R = 1,18297,705,705,705
BEGIN DESCRIPTION:
MUDDY CREEK 20.0
END DESCRIPTION:
XS GIS Cut Line= 3
      2917454.07      7008178.77      2916975.00      7008575.00
      2916846.74      7009101.20
#Sta/Elev= 30
  4351.8  421.31  4483.1  414.23  4511.7  413.57  4526.1  414.20  4625.0  406.85
  4688.9  403.81  4781.3  400.27  4824.3  400.07  4888.2  396.83  4919.2  396.27
  4991.8  394.62  5006.5  392.22  5025.0  395.00  5033.5  395.02  5080.3  393.19
  5083.1  391.94  5083.7  391.14  5089.8  391.14  5090.3  391.94  5097.0  394.59
  5155.5  396.27  5179.4  396.73  5247.1  401.52  5252.3  400.90  5288.8  403.47
  5313.2  404.18  5395.5  411.40  5419.1  412.16  5491.1  417.71  5515.1  418.75
#Mann=5,-1,0
  4351.8    0.05       0  5006.5    0.16       0  5083.1    0.03       0
  5090.3    0.16       0  5491.1    0.05       0
Bank Sta=4919.2,5155.5
Exp/Cntr=0.3,0.1

Type RM Length L Ch R = 1,17592,494,494,494
BEGIN DESCRIPTION:
MUDDY CREEK 19.0
END DESCRIPTION:
XS GIS Cut Line= 3
      2916975.00      7008125.00      2916575.00      7008375.00
      2916375.02      7008824.97
#Sta/Elev= 30
  4501.3  421.26  4560.3  418.42  4631.0  411.92  4682.3  411.24  4697.6  413.38
  4718.9  412.35  4734.2  414.44  4755.4  413.83  4834.4  401.19  4892.1  394.01
  4944.1  390.65  4965.3  392.59  4987.4  392.22  5001.5  387.74  5002.0  386.94
  5008.7  387.74  5010.6  391.52  5016.8  392.87  5071.5  392.26  5115.3  394.01
  5161.1  395.70  5236.3  401.38  5254.1  404.89  5259.6  404.16  5277.4  408.69
  5306.1  410.41  5329.3  414.33  5375.8  418.55  5404.6  418.59  5465.4  422.14
#Mann=3,-1,0
  4501.3    0.05       0  5001.5    0.03       0  5008.7    0.16       0
Bank Sta=4892.1,5115.3
Exp/Cntr=0.3,0.1

Type RM Length L Ch R = 1,17098,548,548,548
BEGIN DESCRIPTION:
MUDDY CREEK 18.0
END DESCRIPTION:
XS GIS Cut Line= 3
      2916675.04      7007774.98      2916275.00      7008025.00
      2915975.01      7008374.98
#Sta/Elev= 30
  4536.4  424.77  4617.2  422.09  4623.1  422.77  4666.2  420.92  4702.1  416.54
  4725.1  415.37  4754.0  412.08  4769.3  407.78  4790.6  403.55  4848.4  398.60
  4863.7  396.50  4916.8  392.72  4958.0  391.14  4985.1  391.46  4995.7  390.31
  5000.5  387.43  5001.5  385.51  5002.1  384.71  5008.3  384.71  5008.8  385.51
  5011.4  385.51  5021.9  391.73  5128.3  389.57  5199.7  391.90  5206.0  392.72
  5242.5  395.56  5327.0  407.82  5334.7  408.11  5384.1  414.19  5469.1  417.88
#Mann=4,-1,0
  4536.4    0.05       0  4995.7    0.16       0  5001.5    0.07       0
  5008.8    0.16       0
Bank Sta=4916.8,5206
Exp/Cntr=0.3,0.1