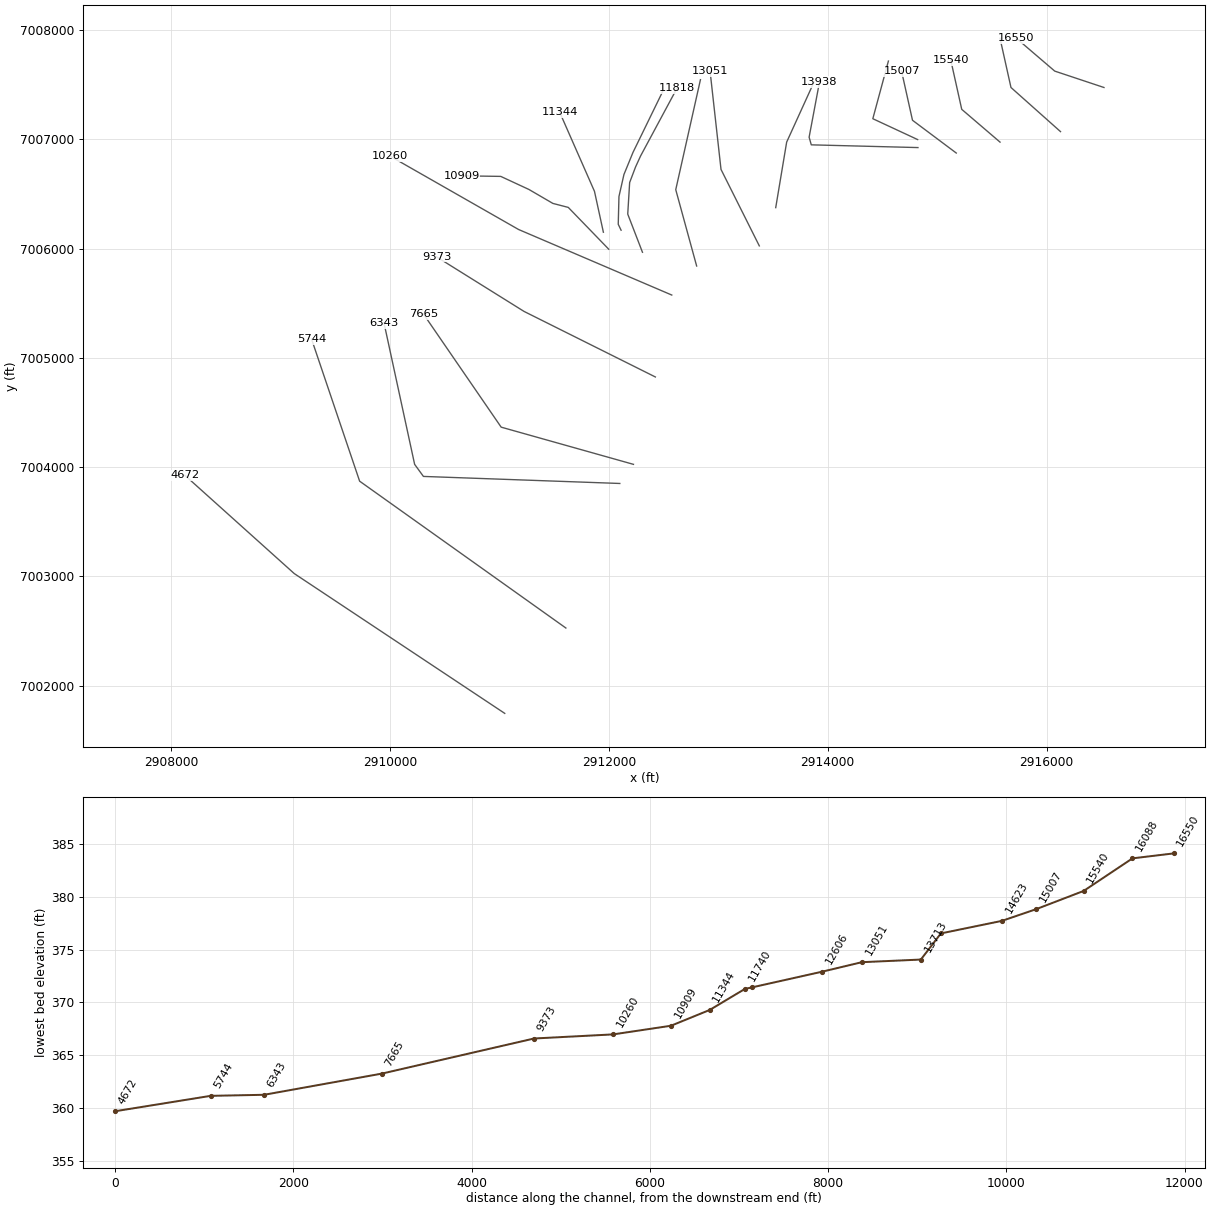
HEC-RAS study MUDDY CREEK.prj: MUDDY CREEK Base Level Engineering

--- MUDDY CREEK.g01 (geometry) --- (continued)

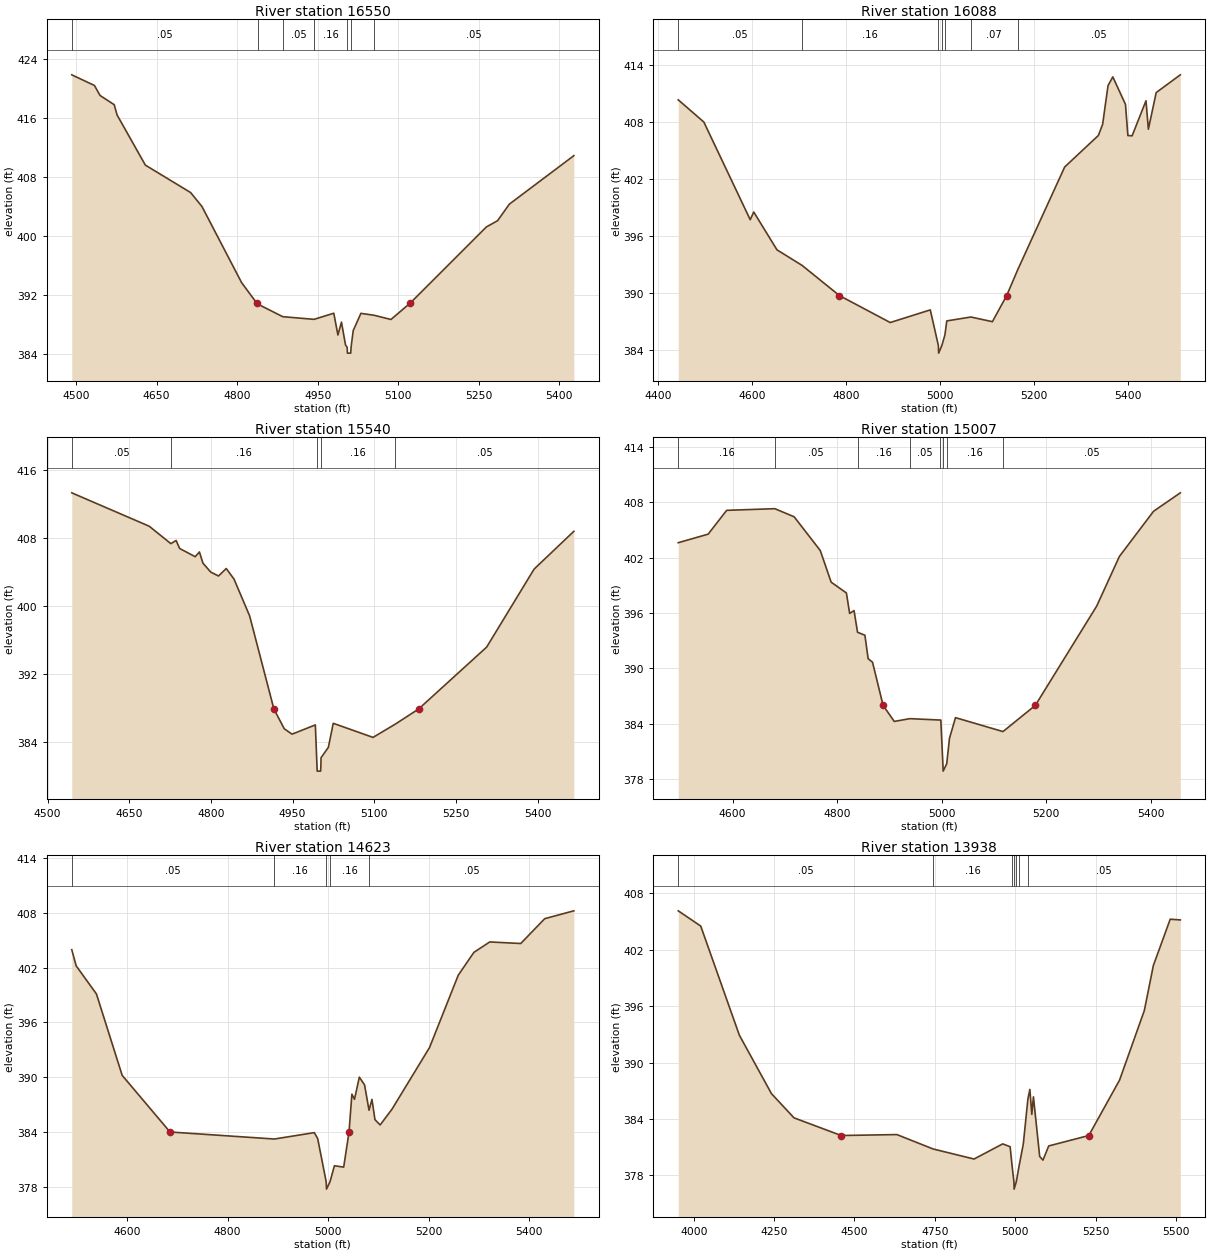
Type RM Length L Ch R = 1,16550,462,462,462
BEGIN DESCRIPTION:
MUDDY CREEK 17.0
END DESCRIPTION:
XS GIS Cut Line= 3
      2916525.03      7007474.99      2916075.00      7007625.00
      2915725.04      7007924.97
#Sta/Elev= 30
  4491.9  421.87  4534.1  420.43  4544.6  419.07  4571.0  417.82  4576.3  416.43
  4629.0  409.63  4713.3  405.91  4734.4  404.02  4808.2  393.71  4836.2  390.95
  4838.1  390.80  4885.0  389.08  4943.3  388.72  4980.0  389.55  4987.7  386.60
  4994.3  388.34  5001.9  385.24  5004.9  384.94  5005.4  384.14  5011.6  384.14
  5012.2  384.94  5016.2  387.20  5030.5  389.53  5055.4  389.27  5086.5  388.70
  5122.6  390.94  5264.3  401.25  5285.1  402.09  5307.1  404.34  5427.2  410.91
#Mann=7,-1,0
  4491.9    0.05       0  4838.1    0.16       0  4885.0    0.05       0
  4943.3    0.16       0  5004.9    0.07       0  5012.2    0.16       0
  5055.4    0.05       0
Bank Sta=4836.2,5122.6
Exp/Cntr=0.3,0.1

Type RM Length L Ch R = 1,16088,548,548,548
BEGIN DESCRIPTION:
MUDDY CREEK 16.0
END DESCRIPTION:
XS GIS Cut Line= 3
      2916127.70      7007071.12      2915675.00      7007475.00
      2915574.99      7007925.05
#Sta/Elev= 30
  4442.9  410.33  4497.4  407.99  4596.0  397.71  4603.5  398.52  4652.9  394.54
  4706.1  392.91  4785.6  389.73  4893.7  386.89  4978.9  388.22  4996.1  384.47
  4996.7  383.67  5003.5  384.47  5010.0  385.59  5014.0  387.06  5065.2  387.47
  5111.0  386.98  5141.4  389.73  5164.9  392.45  5264.7  403.26  5336.4  406.58
  5345.4  407.75  5356.9  411.83  5367.1  412.74  5394.0  409.85  5399.1  406.57
  5408.1  406.54  5437.6  410.23  5442.7  407.24  5459.3  411.09  5510.6  412.96
#Mann=7,-1,0
  4442.9    0.05       0  4706.1    0.16       0  4996.1    0.07       0
  5003.5    0.16       0  5010.0    0.12       0  5065.2    0.07       0
  5164.9    0.05       0
Bank Sta=4785.6,5141.4
Exp/Cntr=0.3,0.1

Type RM Length L Ch R = 1,15540,533,533,533
BEGIN DESCRIPTION:
MUDDY CREEK 15.0
END DESCRIPTION:
XS GIS Cut Line= 3
      2915575.02      7006974.98      2915225.00      7007275.00
      2915125.00      7007725.02
#Sta/Elev= 30
  4544.5  413.34  4686.7  409.41  4726.5  407.36  4736.1  407.73  4742.6  406.79
  4771.2  405.82  4778.9  406.38  4785.4  405.06  4799.7  404.01  4814.0  403.55
  4828.2  404.43  4842.5  403.18  4871.1  398.86  4915.7  387.89  4934.7  385.57
  4949.0  384.93  4991.8  386.02  4994.7  381.38  4995.2  380.58  5001.5  380.58
  5002.1  381.38  5002.2  382.15  5015.7  383.38  5024.7  386.21  5097.7  384.55
  5138.3  386.10  5181.4  387.89  5306.4  395.18  5393.5  404.36  5466.5  408.81
#Mann=5,-1,0
  4544.5    0.05       0  4726.5    0.16       0  4994.7    0.07       0
  5002.1    0.16       0  5138.3    0.05       0
Bank Sta=4915.7,5181.4
Exp/Cntr=0.3,0.1

Type RM Length L Ch R = 1,15007,384,384,384
BEGIN DESCRIPTION:
MUDDY CREEK 14.0
END DESCRIPTION:
XS GIS Cut Line= 3
      2915175.00      7006875.00      2914775.00      7007175.00
      2914674.99      7007625.03
#Sta/Elev= 30
  4496.0  403.62  4553.3  404.55  4588.7  407.13  4680.9  407.31  4717.9  406.43
  4767.9  402.77  4788.7  399.34  4817.9  398.17  4824.1  395.95  4832.5  396.26
  4839.2  393.91  4853.3  393.59  4859.5  391.04  4867.9  390.66  4888.1  385.98
  4909.5  384.24  4939.4  384.54  4996.9  384.39  4998.6  384.39  5002.5  379.65
  5003.1  378.85  5009.9  379.65  5015.2  382.41  5026.7  384.65  5117.6  383.14
  5179.5  385.98  5296.9  396.74  5340.4  402.13  5405.8  407.03  5457.0  409.03
#Mann=8,-1,0
  4496.0    0.16       0  4680.9    0.05       0  4839.2    0.16       0
  4939.4    0.05       0  4996.9    0.16       0  5002.5    0.07       0
  5009.9    0.16       0  5117.6    0.05       0
Bank Sta=4888.1,5179.5
Exp/Cntr=0.3,0.1

Type RM Length L Ch R = 1,14623,685,685,685
BEGIN DESCRIPTION:
Mapping XS 0205cc4b
END DESCRIPTION:
XS GIS Cut Line= 3
      2914822.16      7006998.19      2914412.43      7007189.17
      2914554.80      7007716.96
#Sta/Elev= 30
  4490.1  403.97  4498.9  402.20  4539.2  399.12  4590.4  390.20  4685.6  384.00
  4893.1  383.23  4972.6  383.93  4979.3  383.27  4996.2  378.54  4996.8  377.74
  5003.7  378.54  5012.6  380.30  5031.0  380.15  5041.6  384.00  5047.3  388.14
  5052.5  387.58  5062.1  390.01  5072.5  389.16  5081.4  386.38  5087.2  387.57
  5093.2  385.35  5103.5  384.77  5127.1  386.50  5201.8  393.26  5258.9  401.18
  5290.0  403.68  5321.5  404.82  5383.2  404.65  5430.9  407.37  5488.8  408.23
#Mann=5,-1,0
  4490.1    0.05       0  4893.1    0.16       0  4996.2    0.07       0
  5003.7    0.16       0  5081.4    0.05       0
Bank Sta=4685.6,5041.6
Exp/Cntr=0.3,0.1

Type RM Length L Ch R = 1,13938,225,225,225
BEGIN DESCRIPTION:
MUDDY CREEK 13.0
END DESCRIPTION:
XS GIS Cut Line= 4
      2914825.02      7006925.00      2913850.00      7006950.00
      2913830.27      7007020.03      2913925.00      7007525.02
#Sta/Elev= 30
  3951.9  406.14  4021.9  404.52  4142.0  392.92  4242.0  386.70  4312.0  384.13
  4459.0  382.25  4632.1  382.35  4744.7  380.82  4872.2  379.75  4961.3  381.36
  4984.4  381.06  4990.3  379.08  4996.2  377.35  4996.8  376.55  5003.7  377.35
  5011.7  378.91  5025.4  381.35  5039.7  386.14  5045.8  387.15  5051.8  384.50
  5056.9  386.36  5076.3  380.03  5086.5  379.63  5104.4  381.14  5229.1  382.25
  5324.8  388.14  5401.9  395.54  5429.9  400.32  5482.4  405.25  5513.8  405.17
#Mann=7,-1,0
  3951.9    0.05       0  4744.7    0.16       0  4990.3    0.05       0
  4996.2    0.03       0  5003.7    0.05       0  5011.7    0.16       0
  5039.7    0.05       0
Bank Sta=4459,5229.1
Exp/Cntr=0.3,0.1

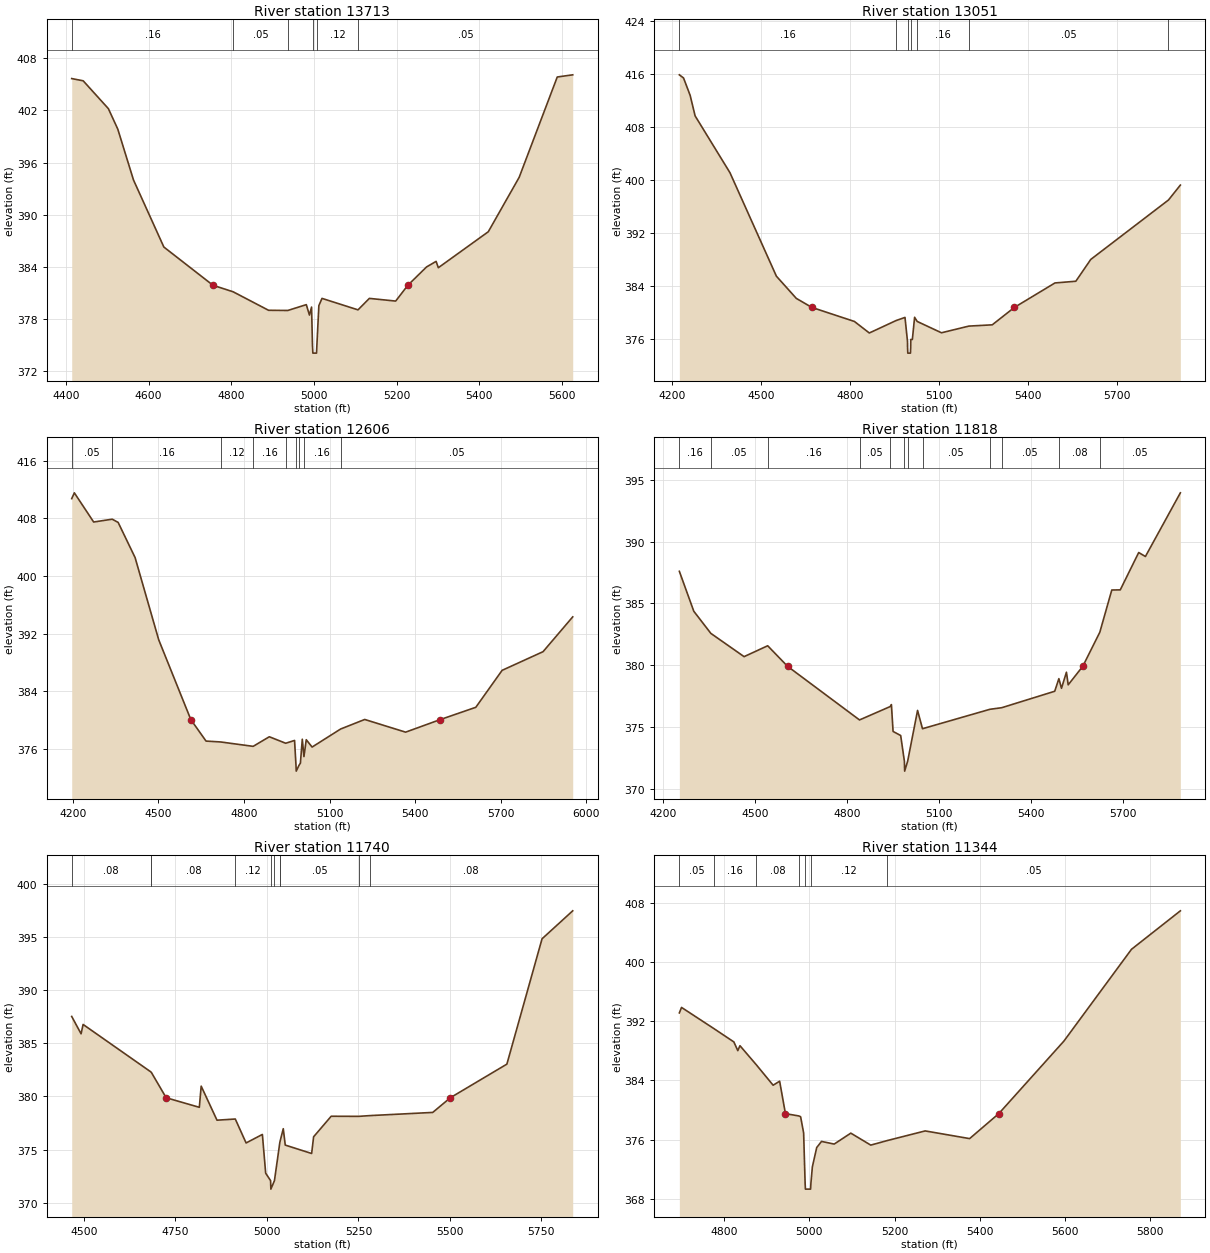
Type RM Length L Ch R = 1,13713,662,662,662
BEGIN DESCRIPTION:
MUDDY CREEK 12.0
END DESCRIPTION:
XS GIS Cut Line= 3
      2913525.01      7006375.04      2913625.00      7006975.00
      2913875.01      7007525.01
#Sta/Elev= 30
  4414.0  405.67  4441.8  405.41  4502.7  402.21  4525.5  399.85  4563.5  394.00
  4637.0  386.28  4755.9  381.88  4804.6  381.13  4890.4  379.00  4937.0  378.98
  4981.7  379.65  4989.3  378.45  4994.4  379.37  4996.7  374.87  4997.6  374.07
  5006.4  374.07  5007.2  374.87  5012.1  379.54  5019.7  380.37  5106.8  379.05
  5134.3  380.37  5198.0  380.06  5227.4  381.88  5272.7  383.99  5295.8  384.63
  5301.2  383.90  5422.1  388.04  5496.8  394.30  5589.0  405.85  5626.4  406.10
#Mann=6,-1,0
  4414.0    0.16       0  4804.6    0.05       0  4937.0    0.12       0
  4996.7    0.07       0  5007.2    0.12       0  5106.8    0.05       0
Bank Sta=4755.9,5227.4
Exp/Cntr=0.3,0.1

Type RM Length L Ch R = 1,13051,445,445,445
BEGIN DESCRIPTION:
MUDDY CREEK 11.0
END DESCRIPTION:
XS GIS Cut Line= 3
      2913375.00      7006025.00      2913025.00      7006725.00
      2912925.00      7007625.03
#Sta/Elev= 30
  4224.7  415.82  4238.7  415.35  4261.0  412.73  4277.8  409.62  4395.2  401.05
  4551.7  385.43  4618.8  382.08  4671.1  380.72  4814.5  378.60  4864.8  376.86
  4955.2  378.74  4985.0  379.21  4993.4  375.61  4993.7  374.62  4994.5  373.82
  5003.3  373.82  5004.2  374.62  5004.5  375.88  5009.8  375.88  5017.4  379.23
  5026.1  378.60  5107.9  376.89  5200.3  377.90  5279.0  378.09  5353.7  380.72
  5490.3  384.41  5560.7  384.67  5611.0  387.96  5872.9  396.93  5912.9  399.18
#Mann=7,-1,0
  4224.7    0.16       0  4955.2    0.12       0  4993.7    0.07       0
  5004.2    0.12       0  5026.1    0.16       0  5200.3    0.05       0
  5872.9    0.16       0
Bank Sta=4671.1,5353.7
Exp/Cntr=0.3,0.1

Type RM Length L Ch R = 1,12606,788,788,788
BEGIN DESCRIPTION:
Mapping XS c08a6137
END DESCRIPTION:
XS GIS Cut Line= 3
      2912802.32      7005840.79      2912611.34      7006539.58
      2912837.03      7007546.48
#Sta/Elev= 30
  4195.9  410.74  4205.1  411.55  4272.8  407.50  4338.0  407.89  4358.7  407.44
  4418.0  402.57  4500.9  391.15  4613.5  380.07  4666.8  377.09  4717.5  376.97
  4832.0  376.36  4888.6  377.69  4946.0  376.79  4977.1  377.18  4982.1  373.72
  4983.0  372.92  4992.6  373.72  4997.6  374.03  5004.2  377.35  5010.0  374.94
  5018.1  377.28  5038.6  376.26  5138.8  378.77  5223.1  380.09  5366.4  378.33
  5487.5  380.07  5612.5  381.78  5704.7  386.91  5848.2  389.50  5952.2  394.33
#Mann=9,-1,0
  4195.9    0.05       0  4338.0    0.16       0  4717.5    0.12       0
  4832.0    0.16       0  4946.0    0.12       0  4982.1    0.07       0
  4992.6    0.12       0  5010.0    0.16       0  5138.8    0.05       0
Bank Sta=4613.5,5487.5
Exp/Cntr=0.3,0.1

Type RM Length L Ch R = 1,11818,78,78,78
BEGIN DESCRIPTION:
Mapping XS 24f19b06
END DESCRIPTION:
XS GIS Cut Line= 6
      2912307.16      7005966.66      2912172.61      7006316.06
      2912189.97      7006604.68      2912244.23      7006747.91
      2912289.80      7006847.74      2912623.87      7007470.32
#Sta/Elev= 30
  4254.3  387.59  4301.4  384.36  4357.0  382.57  4465.3  380.69  4542.2  381.57
  4606.9  379.91  4841.5  375.57  4941.3  376.65  4945.5  376.81  4950.9  374.64
  4975.7  374.31  4987.8  372.23  4988.6  371.43  4998.4  372.23  5030.7  376.34
  5046.8  374.86  5266.4  376.43  5305.1  376.56  5477.8  377.89  5491.3  378.91
  5499.8  378.13  5516.0  379.43  5521.7  378.41  5569.3  379.91  5624.7  382.66
  5663.8  386.08  5691.4  386.09  5751.5  389.11  5773.4  388.79  5887.3  393.94
#Mann=12,-1,0
  4254.3    0.16       0  4357.0    0.05       0  4542.2    0.16       0
  4841.5    0.05       0  4941.3    0.08       0  4987.8    0.07       0
  4998.4    0.08       0  5046.8    0.05       0  5266.4    0.08       0
  5305.1    0.05       0  5491.3    0.08       0  5624.7    0.05       0
Bank Sta=4606.9,5569.3
Exp/Cntr=0.3,0.1

Type RM Length L Ch R = 1,11740,396,396,396
BEGIN DESCRIPTION:
Mapping XS 8187fc98
END DESCRIPTION:
XS GIS Cut Line= 6
      2912111.83      7006168.52      2912085.81      7006222.74
      2912092.32      7006476.65      2912137.89      7006678.47
      2912220.36      7006880.29      2912495.98      7007446.74
#Sta/Elev= 30
  4466.5  387.52  4492.1  385.89  4497.6  386.77  4682.3  382.32  4684.5  382.24
  4724.6  379.88  4815.2  378.98  4820.3  380.97  4863.5  377.77  4913.5  377.88
  4943.0  375.63  4987.5  376.43  4996.5  372.79  5009.9  372.09  5010.7  371.29
  5020.5  372.09  5035.2  375.68  5036.1  375.82  5044.6  376.97  5050.0  375.43
  5122.1  374.64  5127.5  376.21  5175.5  378.14  5250.9  378.13  5280.8  378.20
  5453.0  378.50  5501.1  379.88  5655.6  383.04  5751.7  394.82  5835.5  397.45
#Mann=10,-1,0
  4466.5    0.08       0  4682.3    0.05       0  4684.5    0.08       0
  4913.5    0.12       0  5009.9    0.07       0  5020.5    0.12       0
  5035.2    0.08       0  5036.1    0.05       0  5250.9    0.12       0
  5280.8    0.08       0
Bank Sta=4724.6,5501.1
Exp/Cntr=0.3,0.1

Type RM Length L Ch R = 1,11344,435,435,435
BEGIN DESCRIPTION:
MUDDY CREEK 9.0
END DESCRIPTION:
XS GIS Cut Line= 3
      2911950.00      7006150.02      2911868.60      7006524.40
      2911550.00      7007250.01
#Sta/Elev= 30
  4695.0  393.15  4700.1  393.89  4775.9  391.03  4822.9  389.22  4832.1  388.04
  4837.2  388.71  4875.5  386.13  4915.0  383.36  4930.3  383.90  4943.9  379.51
  4975.1  379.20  4979.5  379.10  4986.6  376.90  4990.1  370.09  4990.8  369.29
  5002.9  369.29  5003.7  370.09  5007.1  372.31  5017.3  374.92  5028.6  375.75
  5058.3  375.39  5097.3  376.87  5144.1  375.25  5183.2  375.87  5271.8  377.17
  5376.1  376.13  5444.5  379.51  5597.3  389.33  5755.9  401.76  5870.6  406.97
#Mann=7,-1,0
  4695.0    0.05       0  4775.9    0.16       0  4875.5    0.08       0
  4975.1    0.12       0  4990.1    0.07       0  5003.7    0.12       0
  5183.2    0.05       0
Bank Sta=4943.9,5444.5
Exp/Cntr=0.3,0.1

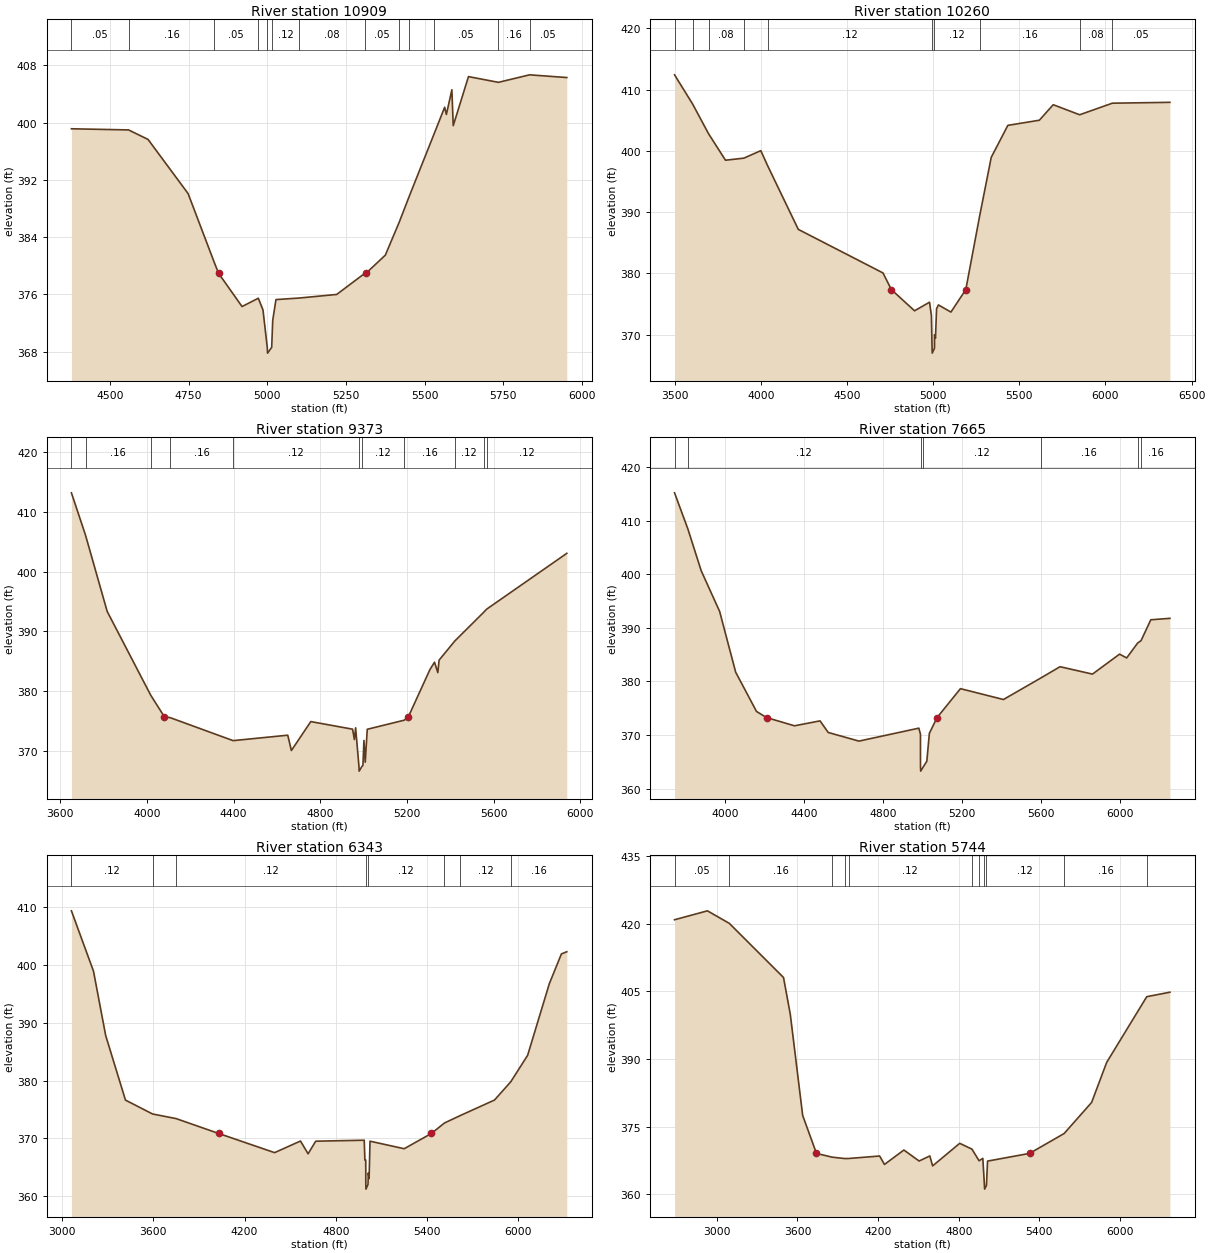
Type RM Length L Ch R = 1,10909,649,649,649
BEGIN DESCRIPTION:
Mapping XS 70f4417b
END DESCRIPTION:
XS GIS Cut Line= 6
      2911998.91      7005994.52      2911629.13      7006377.33
      2911488.50      7006413.79      2911269.75      7006541.39
      2911011.94      7006661.18      2910652.53      7006666.39
#Sta/Elev= 30
  4377.7  399.14  4559.4  398.98  4621.3  397.65  4748.6  390.08  4831.7  380.47
  4845.3  378.95  4920.0  374.30  4971.7  375.46  4986.5  373.84  5000.2  368.59
  5001.1  367.79  5014.2  368.59  5017.5  372.37  5027.8  375.27  5102.1  375.49
  5220.9  375.99  5309.6  378.92  5314.0  378.95  5375.4  381.48  5419.9  386.12
  5452.1  389.78  5530.3  398.41  5564.0  402.15  5569.5  401.14  5586.9  404.59
  5591.3  399.58  5639.7  406.43  5734.9  405.63  5834.0  406.68  5952.2  406.30
#Mann=13,-1,0
  4377.7    0.05       0  4559.4    0.16       0  4831.7    0.05       0
  4971.7    0.12       0  5000.2    0.07       0  5014.2    0.12       0
  5102.1    0.08       0  5309.6    0.05       0  5419.9    0.12       0
  5452.1    0.08       0  5530.3    0.05       0  5734.9    0.16       0
  5834.0    0.05       0
Bank Sta=4845.3,5314
Exp/Cntr=0.3,0.1

Type RM Length L Ch R = 1,10260,887,887,887
BEGIN DESCRIPTION:
MUDDY CREEK 8.0
END DESCRIPTION:
XS GIS Cut Line= 3
      2912575.00      7005575.00      2911175.00      7006175.00
      2910001.96      7006845.90
#Sta/Elev= 30
  3499.3  412.40  3604.1  407.64  3696.5  402.79  3794.9  398.46  3902.0  398.80
  3999.8  400.02  4039.4  397.57  4217.4  387.17  4708.8  380.06  4757.5  377.34
  4891.9  373.88  4978.9  375.28  4989.8  373.13  4993.7  367.77  4994.6  366.97
  5007.7  367.77  5008.0  369.97  5013.4  369.41  5019.7  374.20  5030.4  374.84
  5103.1  373.67  5189.4  377.34  5269.6  389.34  5337.0  398.93  5433.4  404.15
  5616.2  404.99  5696.8  407.52  5850.3  405.88  6039.7  407.77  6373.8  407.91
#Mann=10,-1,0
  3499.3    0.08       0  3604.1    0.05       0  3696.5    0.08       0
  3902.0    0.16       0  4039.4    0.12       0  4993.7    0.07       0
  5007.7    0.12       0  5269.6    0.16       0  5850.3    0.08       0
  6039.7    0.05       0
Bank Sta=4757.5,5189.4
Exp/Cntr=0.3,0.1

Type RM Length L Ch R = 1,9373,1708,1708,1708
BEGIN DESCRIPTION:
MUDDY CREEK 7.0
END DESCRIPTION:
XS GIS Cut Line= 3
      2912425.00      7004825.00      2911225.00      7005425.00
      2910425.04      7005924.98
#Sta/Elev= 30
  3652.4  413.21  3717.8  406.07  3817.3  393.34  4018.2  379.30  4080.7  375.72
  4108.6  375.53  4398.1  371.69  4650.3  372.60  4667.0  370.03  4756.5  374.88
  4949.3  373.61  4957.7  371.87  4963.3  373.84  4978.7  367.38  4979.6  366.58
  4992.7  367.38  4997.0  367.54  5001.7  371.72  5007.6  368.08  5017.0  373.59
  5188.0  375.12  5207.1  375.72  5306.0  383.59  5327.2  384.83  5342.5  383.09
  5348.4  385.18  5420.5  388.37  5554.0  393.19  5567.5  393.71  5937.4  403.07
#Mann=11,-1,0
  3652.4    0.12       0  3717.8    0.16       0  4018.2    0.12       0
  4108.6    0.16       0  4398.1    0.12       0  4978.7    0.07       0
  4992.7    0.12       0  5188.0    0.16       0  5420.5    0.12       0
  5554.0    0.16       0  5567.5    0.12       0
Bank Sta=4080.7,5207.1
Exp/Cntr=0.3,0.1

Type RM Length L Ch R = 1,7665,1322,1322,1322
BEGIN DESCRIPTION:
MUDDY CREEK 6.0
END DESCRIPTION:
XS GIS Cut Line= 3
      2912224.98      7004025.01      2911015.82      7004365.53
      2910305.96      7005400.85
#Sta/Elev= 30
  3743.8  415.25  3811.6  408.48  3878.8  400.70  3972.3  393.10  4053.8  381.73
  4159.3  374.40  4210.8  373.25  4352.0  371.72  4481.4  372.64  4523.0  370.47
  4678.8  368.86  4982.4  371.28  4990.5  370.16  4990.8  364.05  4991.7  363.25
  5004.9  364.05  5022.8  365.09  5035.7  370.31  5074.7  373.25  5193.3  378.66
  5411.3  376.63  5599.8  380.63  5698.2  382.76  5862.7  381.38  6000.1  385.11
  6036.0  384.40  6092.4  387.21  6108.8  387.62  6158.5  391.53  6255.3  391.80
#Mann=7,-1,0
  3743.8    0.16       0  3811.6    0.12       0  4990.8    0.07       0
  5004.9    0.12       0  5599.8    0.16       0  6092.4    0.12       0
  6108.8    0.16       0
Bank Sta=4210.8,5074.7
Exp/Cntr=0.3,0.1

Type RM Length L Ch R = 1,6343,599,599,599
BEGIN DESCRIPTION:
MUDDY CREEK 5.0
END DESCRIPTION:
XS GIS Cut Line= 4
      2912100.04      7003850.00      2910305.37      7003914.49
      2910225.00      7004025.00      2909945.12      7005319.52
#Sta/Elev= 30
  3061.6  409.38  3206.7  398.94  3286.8  387.81  3416.9  376.64  3594.8  374.24
  3749.8  373.44  4029.6  370.87  4397.5  367.55  4567.6  369.56  4617.6  367.35
  4667.7  369.53  4986.7  369.70  4991.0  366.27  4996.6  366.27  4997.1  362.04
  4998.1  361.24  5011.4  362.04  5013.6  364.03  5018.7  363.05  5024.8  369.53
  5249.5  368.23  5428.4  370.87  5514.2  372.68  5616.9  373.95  5843.2  376.65
  5949.6  379.79  6061.0  384.38  6203.6  396.77  6283.2  401.93  6318.5  402.30
#Mann=8,-1,0
  3061.6    0.12       0  3594.8    0.16       0  3749.8    0.12       0
  4997.1    0.07       0  5011.4    0.12       0  5514.2    0.16       0
  5616.9    0.12       0  5949.6    0.16       0
Bank Sta=4029.6,5428.4
Exp/Cntr=0.3,0.1

Type RM Length L Ch R = 1,5744,1072,1072,1072
BEGIN DESCRIPTION:
MUDDY CREEK 4.0
END DESCRIPTION:
XS GIS Cut Line= 3
      2911607.25      7002526.68      2909722.31      7003870.99
      2909283.25      7005171.15
#Sta/Elev= 30
  2684.8  420.85  2929.4  422.83  3092.5  420.05  3496.0  408.05  3546.4  399.90
  3638.6  377.47  3741.2  369.06  3857.2  368.23  3951.3  367.92  3980.9  367.93
  4211.4  368.48  4247.5  366.61  4392.1  369.81  4505.4  367.37  4585.1  368.50
  4606.0  366.29  4807.6  371.29  4898.6  370.01  4951.7  367.43  4979.7  367.96
  4991.7  361.94  4993.0  361.14  5006.6  361.94  5014.8  367.35  5327.6  369.06
  5585.1  373.47  5789.6  380.36  5901.4  389.22  6200.1  403.80  6372.3  404.79
#Mann=11,-1,0
  2684.8    0.05       0  3092.5    0.16       0  3857.2    0.05       0
  3951.3    0.16       0  3980.9    0.12       0  4898.6    0.05       0
  4951.7    0.12       0  4991.7    0.07       0  5006.6    0.12       0
  5585.1    0.16       0  6200.1    0.05       0
Bank Sta=3741.2,5327.6
Exp/Cntr=0.3,0.1

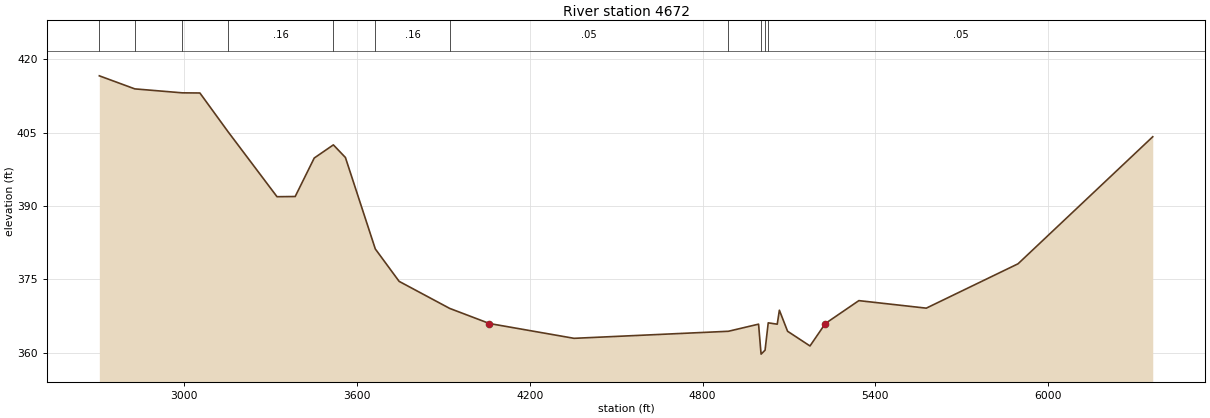
Type RM Length L Ch R = 1,4672,813,813,813
BEGIN DESCRIPTION:
MUDDY CREEK 3.0
END DESCRIPTION:
XS GIS Cut Line= 3
      2911048.50      7001745.26      2909125.00      7003025.00
      2908124.99      7003925.01
#Sta/Elev= 30
  2706.7  416.59  2829.8  413.92  2994.5  413.11  3055.7  413.08  3152.9  405.20
  3323.3  391.87  3386.4  391.91  3452.5  399.78  3518.9  402.47  3560.7  399.89
  3664.4  381.19  3747.1  374.56  3922.5  369.03  4060.5  365.94  4354.2  362.91
  4889.5  364.35  4994.5  365.81  5002.0  360.48  5003.3  359.68  5017.0  360.48
  5028.0  366.08  5059.3  365.80  5066.7  368.66  5095.1  364.36  5172.9  361.35
  5226.3  365.94  5342.5  370.62  5576.5  369.08  5894.9  378.15  6362.4  404.13
#Mann=11,-1,0
  2706.7    0.05       0  2829.8    0.16       0  2994.5    0.05       0
  3152.9    0.16       0  3518.9    0.05       0  3664.4    0.16       0
  3922.5    0.05       0  4889.5    0.07       0  5002.0    0.07       0
  5017.0    0.07       0  5028.0    0.05       0
Bank Sta=4060.5,5226.3
Exp/Cntr=0.3,0.1