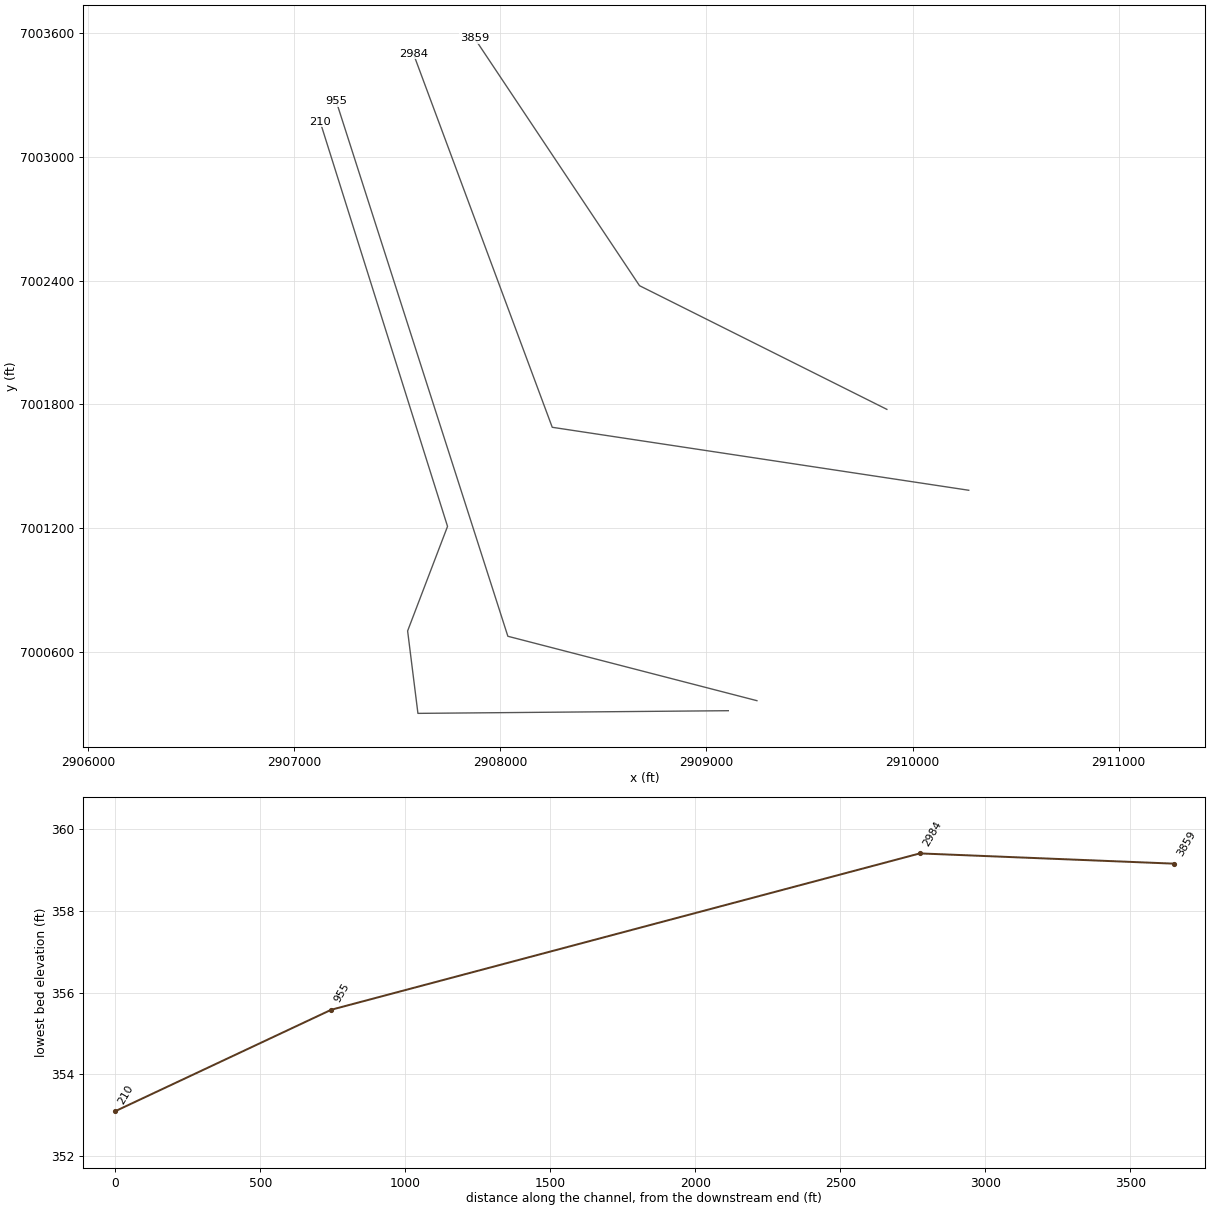
HEC-RAS study MUDDY CREEK.prj: MUDDY CREEK Base Level Engineering

--- MUDDY CREEK.g01 (geometry) --- (continued)

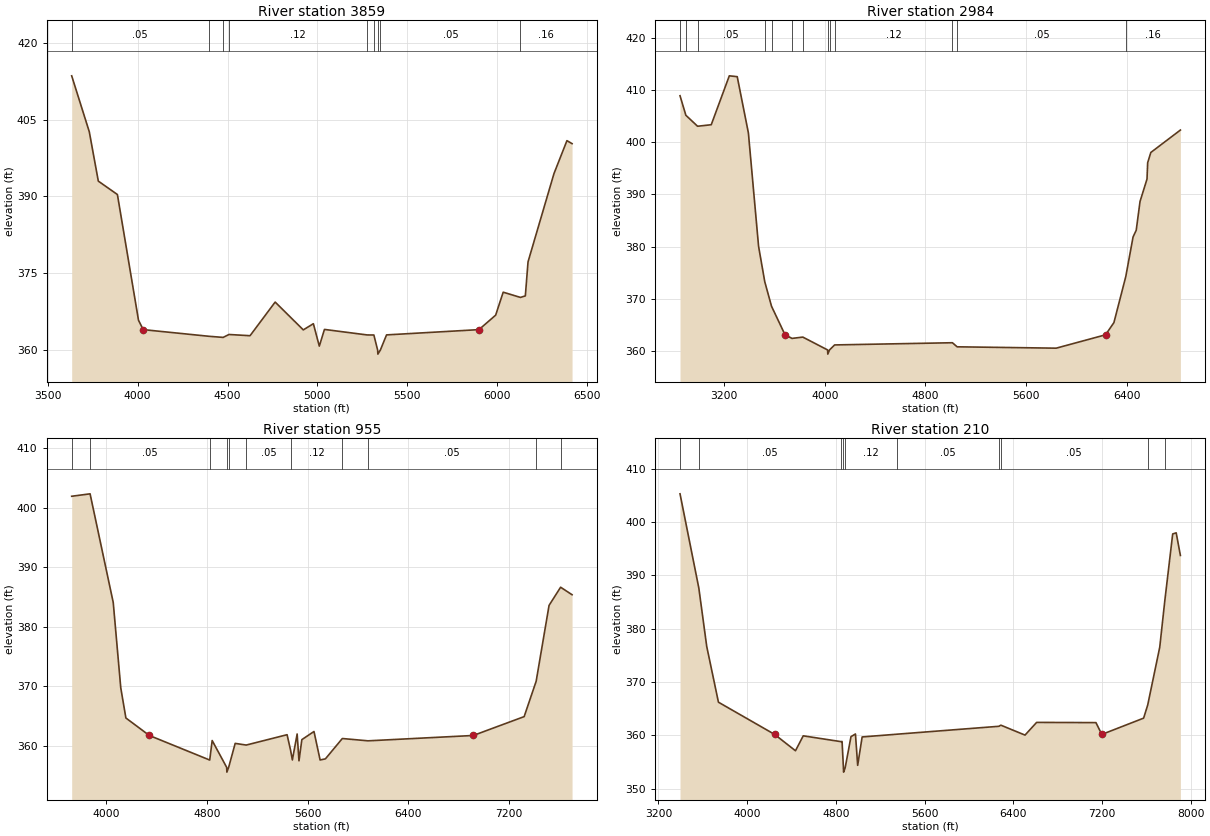
Type RM Length L Ch R = 1,3859,875,875,875
BEGIN DESCRIPTION:
MUDDY CREEK 2.0
END DESCRIPTION:
XS GIS Cut Line= 3
      2909875.04      7001774.98      2908675.00      7002375.00
      2907875.00      7003575.00
#Sta/Elev= 30
  3632.8  413.57  3730.7  402.64  3781.0  392.98  3887.2  390.36  4004.6  365.77
  4030.9  363.94  4396.0  362.64  4475.5  362.42  4508.0  362.99  4625.1  362.75
  4764.9  369.33  4921.4  363.89  4977.5  365.10  5010.5  360.71  5039.1  363.98
  5277.1  362.90  5314.1  362.89  5335.0  359.95  5336.4  359.15  5350.2  359.95
  5384.6  362.91  5898.7  363.94  5991.6  366.77  6033.6  371.26  6129.7  370.24
  6156.8  370.54  6171.8  377.20  6316.1  394.45  6388.2  400.89  6416.7  400.31
#Mann=9,-1,0
  3632.8    0.05       0  4396.0    0.12       0  4475.5    0.07       0
  4508.0    0.12       0  5277.1    0.07       0  5314.1    0.05       0
  5335.0    0.07       0  5350.2    0.05       0  6129.7    0.16       0
Bank Sta=4030.9,5898.7
Exp/Cntr=0.3,0.1

Type RM Length L Ch R = 1,2984,2029,2029,2029
BEGIN DESCRIPTION:
Mapping XS 83cc54de
END DESCRIPTION:
XS GIS Cut Line= 3
      2910272.39      7001382.44      2908251.59      7001687.99
      2907578.08      7003500.22
#Sta/Elev= 30
  2849.3  408.86  2895.7  405.12  2988.8  403.02  3097.5  403.31  3241.1  412.67
  3304.0  412.51  3392.8  401.73  3473.7  380.03  3522.9  373.25  3576.5  368.57
  3684.0  363.10  3739.3  362.41  3825.4  362.66  4022.4  360.20  4023.8  359.40
  4037.6  360.20  4078.0  361.16  5014.3  361.58  5051.8  360.80  5839.3  360.54
  6231.6  363.10  6298.1  365.44  6392.3  374.24  6450.2  381.83  6475.3  383.11
  6505.6  388.62  6561.0  392.91  6566.3  396.04  6591.4  398.00  6826.4  402.29
#Mann=13,-1,0
  2849.3    0.05       0  2895.7    0.16       0  2988.8    0.05       0
  3522.9    0.16       0  3576.5    0.05       0  3739.3    0.16       0
  3825.4    0.05       0  4022.4    0.07       0  4037.6    0.05       0
  4078.0    0.12       0  5014.3    0.16       0  5051.8    0.05       0
  6392.3    0.16       0
Bank Sta=3684,6231.6
Exp/Cntr=0.3,0.1

Type RM Length L Ch R = 1,955,745,745,745
BEGIN DESCRIPTION:
Mapping XS 69a10afb
END DESCRIPTION:
XS GIS Cut Line= 3
      2909244.61      7000361.61      2908036.31      7000674.10
      2907203.19      7003270.67
#Sta/Elev= 30
  3726.1  401.95  3872.3  402.36  4056.2  384.09  4116.0  369.75  4156.7  364.68
  4343.1  361.74  4822.7  357.61  4842.2  360.89  4957.4  356.38  4958.9  355.58
  4973.0  356.38  5025.0  360.41  5112.9  360.13  5437.2  361.87  5465.0  359.27
  5479.2  357.63  5517.2  361.99  5531.7  357.48  5554.6  361.04  5651.0  362.41
  5699.7  357.62  5741.7  357.81  5876.2  361.23  6080.2  360.84  6916.3  361.74
  7320.5  364.91  7416.0  370.86  7518.5  383.61  7610.2  386.66  7701.1  385.40
#Mann=11,-1,0
  3726.1    0.16       0  3872.3    0.05       0  4822.7    0.16       0
  4957.4    0.07       0  4973.0    0.16       0  5112.9    0.05       0
  5465.0    0.12       0  5876.2    0.16       0  6080.2    0.05       0
  7416.0    0.12       0  7610.2    0.05       0
Bank Sta=4343.1,6916.3
Exp/Cntr=0.3,0.1

Type RM Length L Ch R = 1,210,0,0,0
BEGIN DESCRIPTION:
MUDDY CREEK 1.0
END DESCRIPTION:
XS GIS Cut Line= 5
      2909105.80      7000312.99      2907600.00      7000300.00
      2907550.00      7000700.00      2907743.61      7001207.09
      2907125.23      7003171.18
#Sta/Elev= 30
  3394.4  405.32  3564.1  387.62  3635.2  376.68  3740.8  366.22  4247.9  360.17
  4435.2  357.11  4505.2  359.91  4845.5  358.82  4855.3  358.85  4867.5  353.90
  4869.0  353.10  4883.1  353.90  4935.5  359.75  4975.8  360.26  4996.0  354.37
  5036.3  359.70  5352.4  360.22  6268.8  361.70  6286.8  361.91  6504.5  360.05
  6609.3  362.43  7144.0  362.39  7196.7  360.17  7573.8  363.23  7610.7  365.70
  7719.1  376.54  7765.2  385.33  7835.9  397.79  7867.4  398.00  7905.3  393.76
#Mann=10,-1,0
  3394.4    0.16       0  3564.1    0.05       0  4845.5    0.12       0
  4867.5    0.07       0  4883.1    0.12       0  5352.4    0.05       0
  6268.8    0.12       0  6286.8    0.05       0  7610.7    0.16       0
  7765.2    0.12       0
Bank Sta=4247.9,7196.7
Exp/Cntr=0.3,0.1

Chan Stop Cuts=-1