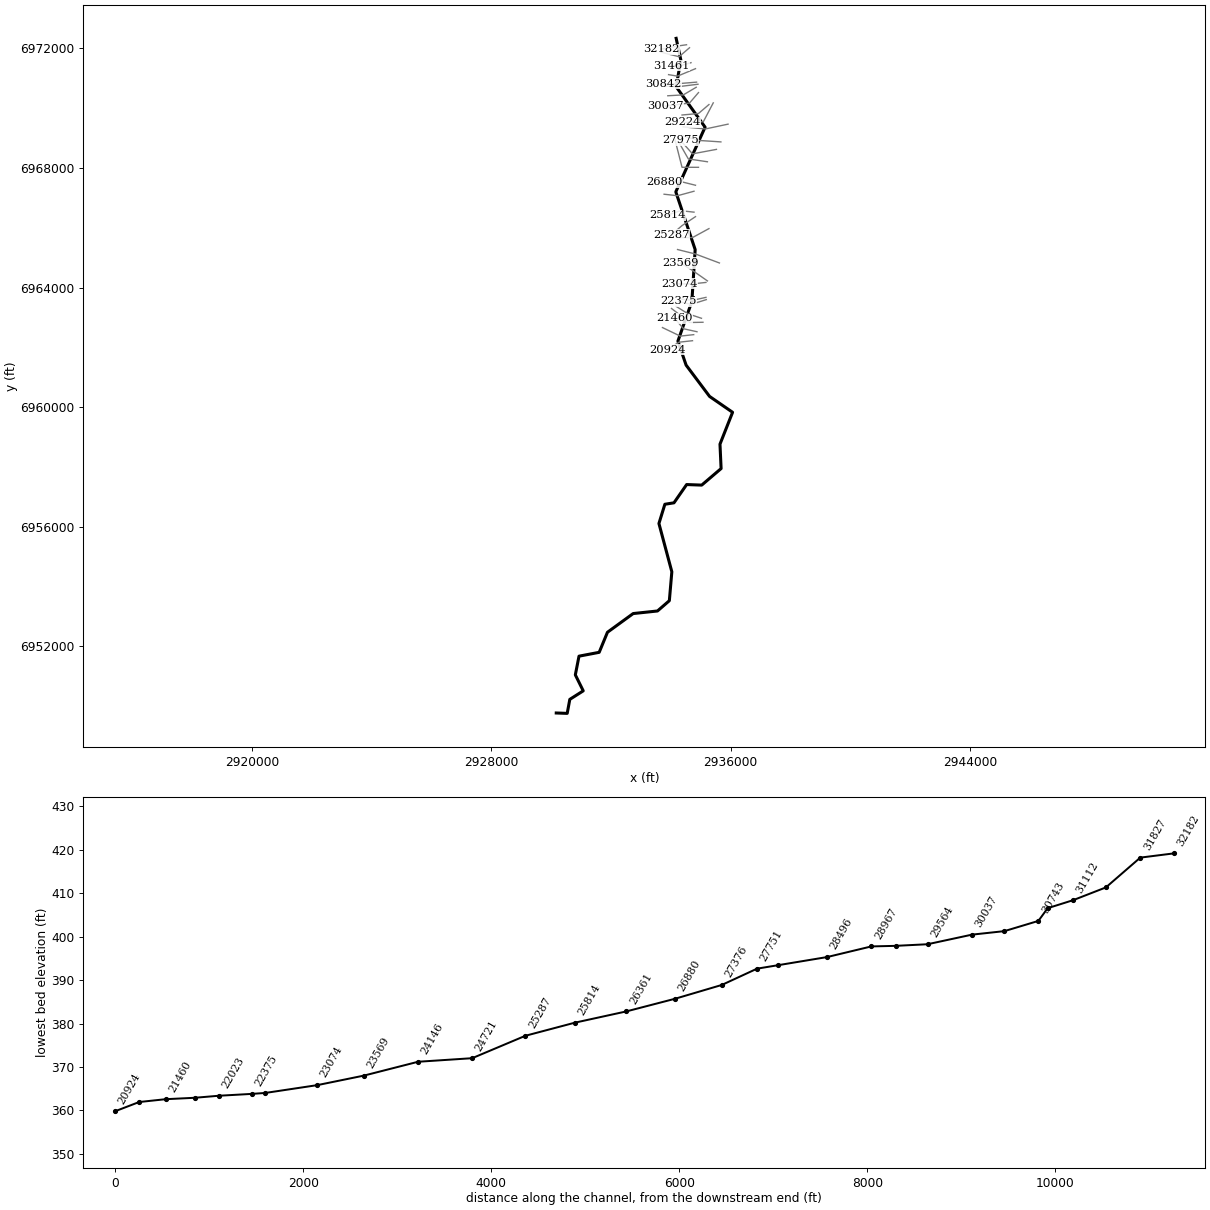
--- PATTON CREEK.prj (project) ---

Proj Title=PATTON CREEK Base Level Engineering
Current Plan=p01
Default Exp/Contr=0.3,0.1
English Units
Geom File=g01
Flow File=f01
Plan File=p01
BEGIN DESCRIPTION:
PATTON CREEK
END DESCRIPTION:

--- PATTON CREEK.p01 (plan) ---

Plan Title=Multiple Run
Short Identifier=Multiple
Geom File=g01
Flow File=f01
Subcritical Flow
K Sum by GR= 0
Std Step Tol= 0.01
Critical Tol= 0.01
Num of Std Step Trials= 20
Max Error Tol= 0.3
Flow Tol Ratio= 0.001
Split Flow NTrial= 30
Split Flow Tol= 0.02
Split Flow Ratio= 0.02
Log Output Level= 0
Friction Slope Method= 1
Unsteady Friction Slope Method= 2
Unsteady Bridges Friction Slope Method= 1
Parabolic Critical Depth
Global Vel Dist=  1 , 1 , 1
Global Log Level= 0
CheckData=True
Encroach Param= -1, 0, 0, 0
BEGIN DESCRIPTION:
Multiple Run
END DESCRIPTION:

--- PATTON CREEK.f01 (steady flow) ---

Flow Title=Multiple
Program Version=5.07
Number of Profiles= 7
Profile Names=10-year,25-year,50-year,1pct_min,100-year,1pct_plu,500-year
River Rch & RM=PATTON CREEK,Reach-1         ,32182
     808    1120    1384     851    1698    3388    2559
River Rch & RM=PATTON CREEK,Reach-1         ,30743
     867    1206    1492     919    1833    3657    2769
River Rch & RM=PATTON CREEK,Reach-1         ,28967
    1363    1941    2440    1524    3041    6067    4732
River Rch & RM=PATTON CREEK,Reach-1         ,26880
    1505    2146    2700    1686    3365    6713    5237
River Rch & RM=PATTON CREEK,Reach-1         ,24721
    1654    2358    2967    1851    3693    7369    5737
River Rch & RM=PATTON CREEK,Reach-1         ,17787
    2039    2933    3713    2329    4647    9272    7298
River Rch & RM=PATTON CREEK,Reach-1         ,15869
    2318    3350    4252    2674    5335   10645    8420
River Rch & RM=PATTON CREEK,Reach-1         ,13510
    2328    3364    4270    2685    5356   10687    8451
River Rch & RM=PATTON CREEK,Reach-1         ,13029
    2506    3620    4593    2885    5757   11487    9068
River Rch & RM=PATTON CREEK,Reach-1         ,5586
    2565    3701    4692    2944    5874   11720    9232
Boundary for River Rch & Prof#=PATTON CREEK,Reach-1         , 1
Up Type= 0
Dn Type= 3
Dn Slope=0.005
Boundary for River Rch & Prof#=PATTON CREEK,Reach-1         , 2
Up Type= 0
Dn Type= 3
Dn Slope=0.005
Boundary for River Rch & Prof#=PATTON CREEK,Reach-1         , 3
Up Type= 0
Dn Type= 3
Dn Slope=0.005
Boundary for River Rch & Prof#=PATTON CREEK,Reach-1         , 4
Up Type= 0
Dn Type= 3
Dn Slope=0.005
Boundary for River Rch & Prof#=PATTON CREEK,Reach-1         , 5
Up Type= 0
Dn Type= 3
Dn Slope=0.005
Boundary for River Rch & Prof#=PATTON CREEK,Reach-1         , 6
Up Type= 0
Dn Type= 3
Dn Slope=0.005
Boundary for River Rch & Prof#=PATTON CREEK,Reach-1         , 7
Up Type= 0
Dn Type= 3
Dn Slope=0.005
DSS Import GetInterval= 0
DSS Import GetPeak= 0
DSS Import FillOption= 0

--- PATTON CREEK.g01 (geometry) ---

Geom Title=Existing Conditions

River Reach=PATTON CREEK,Reach-1
Reach XY= 30
      2934178.28      6972339.60      2934335.92      6971610.88
      2934178.02      6970721.88      2935145.84      6969367.96
      2934166.77      6967204.74      2934813.99      6965273.73
      2934703.77      6963536.47      2934236.88      6962211.39
      2934511.04      6961408.22      2935295.87      6960360.89
      2936064.86      6959830.36      2935643.58      6958764.14
      2935680.98      6957947.91      2935033.03      6957394.53
      2934529.23      6957413.20      2934105.37      6956802.17
      2933801.17      6956753.80      2933602.48      6956110.54
      2934034.04      6954494.94      2933950.77      6953528.07
      2933554.36      6953183.86      2932741.85      6953097.93
      2931881.75      6952471.94      2931605.50      6951800.85
      2930930.58      6951672.23      2930807.94      6951046.41
      2931072.32      6950512.38      2930623.33      6950227.11
      2930536.25      6949758.71      2930169.98      6949771.60

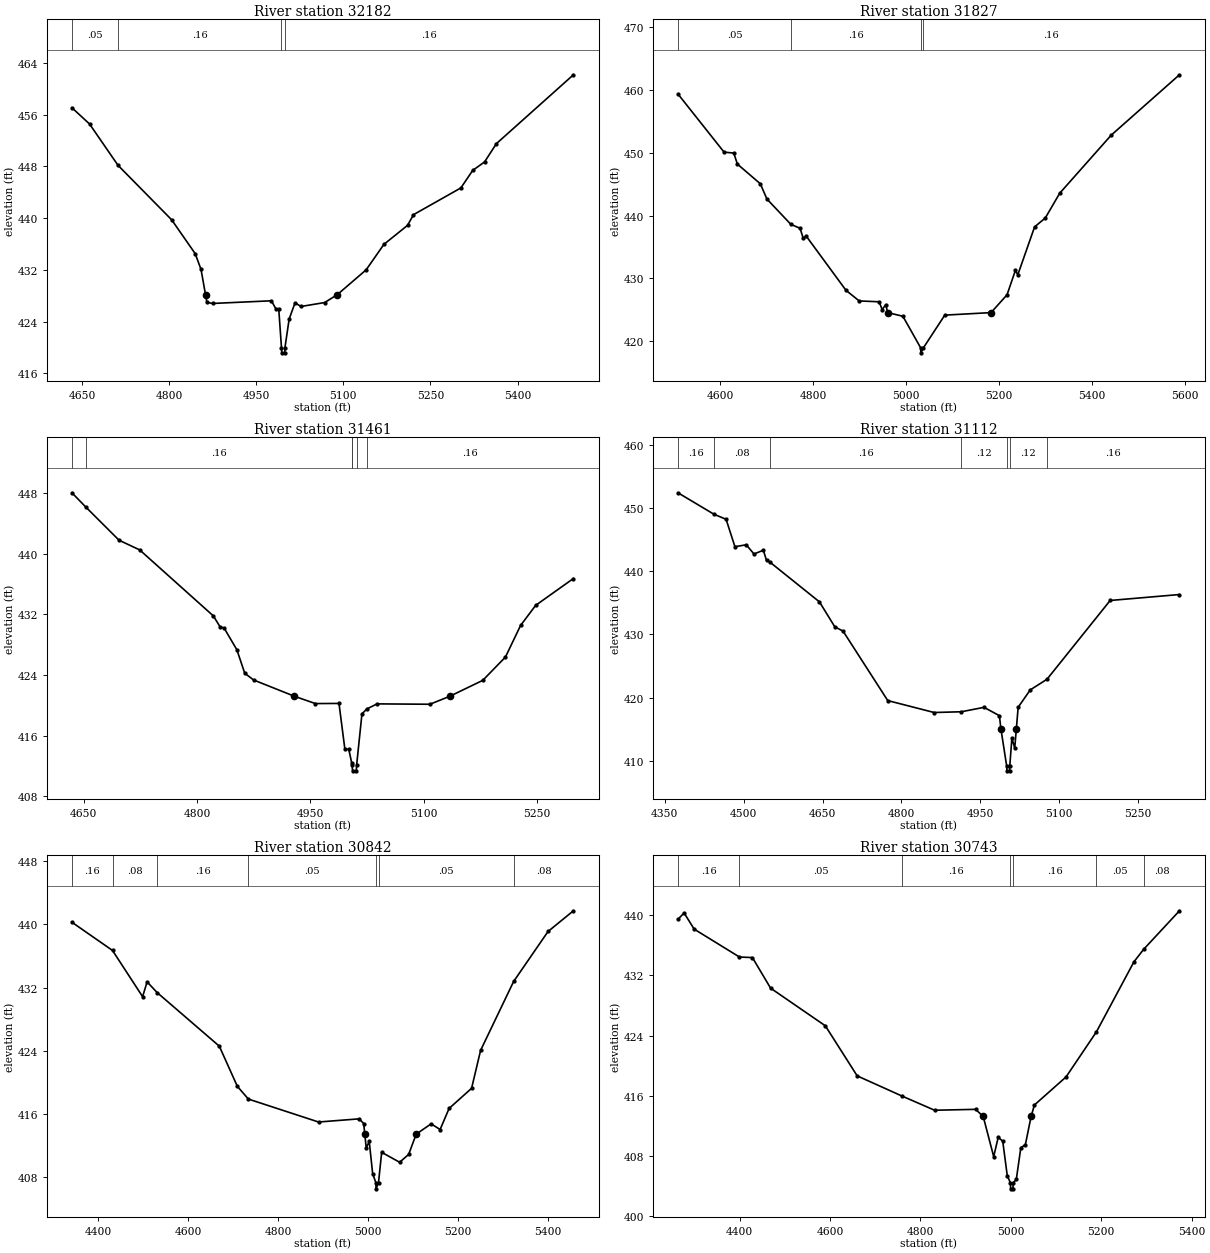
Type RM Length L Ch R = 1,32182,355,355,355
BEGIN DESCRIPTION:
PATTON CREEK 50.0
END DESCRIPTION:
XS GIS Cut Line= 3
      2934525.03      6972125.00      2934175.00      6972075.00
      2933674.99      6971975.00
#Sta/Elev= 30
  4632.7  457.07  4663.0  454.56  4712.1  448.16  4804.5  439.73  4844.9  434.51
  4855.0  432.06  4862.7  428.16  4865.1  426.96  4875.2  426.80  4976.2  427.21
  4983.8  425.97  4988.8  425.97  4993.5  419.96  4994.0  419.16  4999.0  419.16
  4999.5  419.96  5006.7  424.38  5016.9  426.90  5027.1  426.33  5067.9  426.94
  5089.6  428.16  5139.3  432.00  5169.9  435.94  5210.6  438.88  5220.8  440.53
  5302.4  444.67  5322.8  447.38  5343.2  448.69  5363.6  451.52  5496.2  462.17
#Mann=4,-1,0
  4632.7    0.05       0  4712.1    0.16       0  4993.5    0.07       0
  4999.5    0.16       0
Bank Sta=4862.7,5089.6
Exp/Cntr=0.3,0.1

Type RM Length L Ch R = 1,31827,366,366,366
BEGIN DESCRIPTION:
PATTON CREEK 49.0
END DESCRIPTION:
XS GIS Cut Line= 3
      2934625.01      6972025.01      2934275.00      6971725.00
      2933674.96      6971875.01
#Sta/Elev= 30
  4508.6  459.30  4607.9  450.06  4628.8  449.92  4636.5  448.17  4685.9  445.04
  4700.1  442.62  4751.7  438.59  4771.5  437.97  4778.1  436.42  4785.2  436.68
  4870.3  428.12  4898.8  426.43  4941.6  426.30  4948.2  425.07  4955.9  425.83
  4960.1  424.58  4992.8  424.00  5031.0  418.99  5031.5  418.19  5037.0  418.99
  5083.0  424.18  5182.6  424.58  5217.0  427.41  5235.0  431.29  5240.2  430.59
  5276.3  438.19  5299.4  439.61  5330.4  443.54  5441.2  452.76  5588.1  462.35
#Mann=4,-1,0
  4508.6    0.05       0  4751.7    0.16       0  5031.0    0.07       0
  5037.0    0.16       0
Bank Sta=4960.1,5182.6
Exp/Cntr=0.3,0.1

Type RM Length L Ch R = 1,31461,349,349,349
BEGIN DESCRIPTION:
PATTON CREEK 48.0
END DESCRIPTION:
XS GIS Cut Line= 3
      2934675.01      6971525.00      2934325.00      6971425.00
      2934025.02      6971425.00
#Sta/Elev= 30
  4634.3  448.08  4652.5  446.21  4696.7  441.81  4724.0  440.53  4821.5  431.81
  4830.6  430.34  4835.8  430.20  4852.7  427.33  4863.1  424.23  4874.8  423.34
  4928.8  421.19  4956.7  420.22  4987.9  420.24  4995.7  414.19  5000.8  414.19
  5004.7  412.40  5005.3  412.13  5005.8  411.33  5010.8  411.33  5011.3  412.13
  5018.3  418.86  5024.8  419.51  5038.3  420.18  5108.3  420.13  5134.7  421.19
  5178.3  423.29  5208.3  426.37  5228.3  430.54  5248.3  433.20  5298.3  436.75
#Mann=6,-1,0
  4634.3    0.05       0  4652.5    0.16       0  5004.7    0.12       0
  5005.3    0.07       0  5011.3    0.12       0  5024.8    0.16       0
Bank Sta=4928.8,5134.7
Exp/Cntr=0.3,0.1

Type RM Length L Ch R = 1,31112,270,270,270
BEGIN DESCRIPTION:
PATTON CREEK 47.0
END DESCRIPTION:
XS GIS Cut Line= 3
      2934825.03      6971325.01      2934225.00      6971075.00
      2933924.97      6971125.00
#Sta/Elev= 30
  4374.9  452.44  4443.6  449.03  4466.5  448.24  4483.3  443.90  4504.9  444.20
  4519.6  442.74  4537.4  443.34  4543.4  441.72  4549.8  441.46  4644.1  435.16
  4673.4  431.20  4689.1  430.52  4774.1  419.52  4862.4  417.63  4914.2  417.75
  4957.2  418.45  4986.5  417.13  4989.4  415.05  5000.3  409.19  5000.8  408.39
  5005.8  408.39  5006.3  409.19  5010.3  413.55  5015.7  412.01  5018.8  415.05
  5022.2  418.46  5045.2  421.21  5077.1  422.90  5197.3  435.38  5329.1  436.32
#Mann=7,-1,0
  4374.9    0.16       0  4443.6    0.08       0  4549.8    0.16       0
  4914.2    0.12       0  5000.3    0.07       0  5006.3    0.12       0
  5077.1    0.16       0
Bank Sta=4989.4,5018.8
Exp/Cntr=0.3,0.1

Type RM Length L Ch R = 1,30842,99,99,99
BEGIN DESCRIPTION:
Mapping XS 23aa800a
END DESCRIPTION:
XS GIS Cut Line= 3
      2934861.62      6970874.43      2934205.38      6970819.74
      2933748.53      6970814.55
#Sta/Elev= 30
  4341.0  440.26  4431.3  436.69  4498.2  430.85  4508.2  432.72  4530.5  431.37
  4668.8  424.59  4708.9  419.51  4733.5  417.90  4889.5  415.00  4979.8  415.40
  4989.9  414.81  4992.4  413.46  4995.6  411.68  5002.2  412.57  5009.9  408.45
  5016.9  407.35  5017.4  406.55  5022.9  407.35  5029.9  411.17  5069.9  409.91
  5089.9  410.90  5106.7  413.46  5139.9  414.77  5159.9  414.05  5179.9  416.72
  5229.9  419.26  5249.9  424.05  5323.4  432.77  5399.9  439.09  5456.4  441.71
#Mann=7,-1,0
  4341.0    0.16       0  4431.3    0.08       0  4530.5    0.16       0
  4733.5    0.05       0  5016.9    0.04       0  5022.9    0.05       0
  5323.4    0.08       0
Bank Sta=4992.4,5106.7
Exp/Cntr=0.3,0.1

Type RM Length L Ch R = 1,30743,361,361,361
BEGIN DESCRIPTION:
Mapping XS 14b138f5
END DESCRIPTION:
XS GIS Cut Line= 3
      2934908.46      6970804.11      2934262.68      6970723.38
      2933804.35      6970739.01
#Sta/Elev= 30
  4263.5  439.45  4277.1  440.30  4299.4  438.15  4399.6  434.44  4428.2  434.37
  4468.5  430.30  4589.5  425.30  4660.0  418.64  4758.3  415.98  4831.3  414.07
  4922.0  414.19  4938.8  413.24  4962.0  407.90  4972.0  410.48  4982.0  409.95
  4992.0  405.37  4999.0  404.42  4999.5  403.62  5004.6  403.62  5005.1  404.42
  5012.0  404.87  5022.0  409.08  5032.1  409.50  5044.7  413.24  5052.1  414.77
  5122.1  418.50  5189.3  424.50  5272.2  433.80  5293.8  435.47  5372.9  440.59
#Mann=7,-1,0
  4263.5    0.16       0  4399.6    0.05       0  4758.3    0.16       0
  4999.0    0.07       0  5005.1    0.16       0  5189.3    0.05       0
  5293.8    0.08       0
Bank Sta=4938.8,5044.7
Exp/Cntr=0.3,0.1

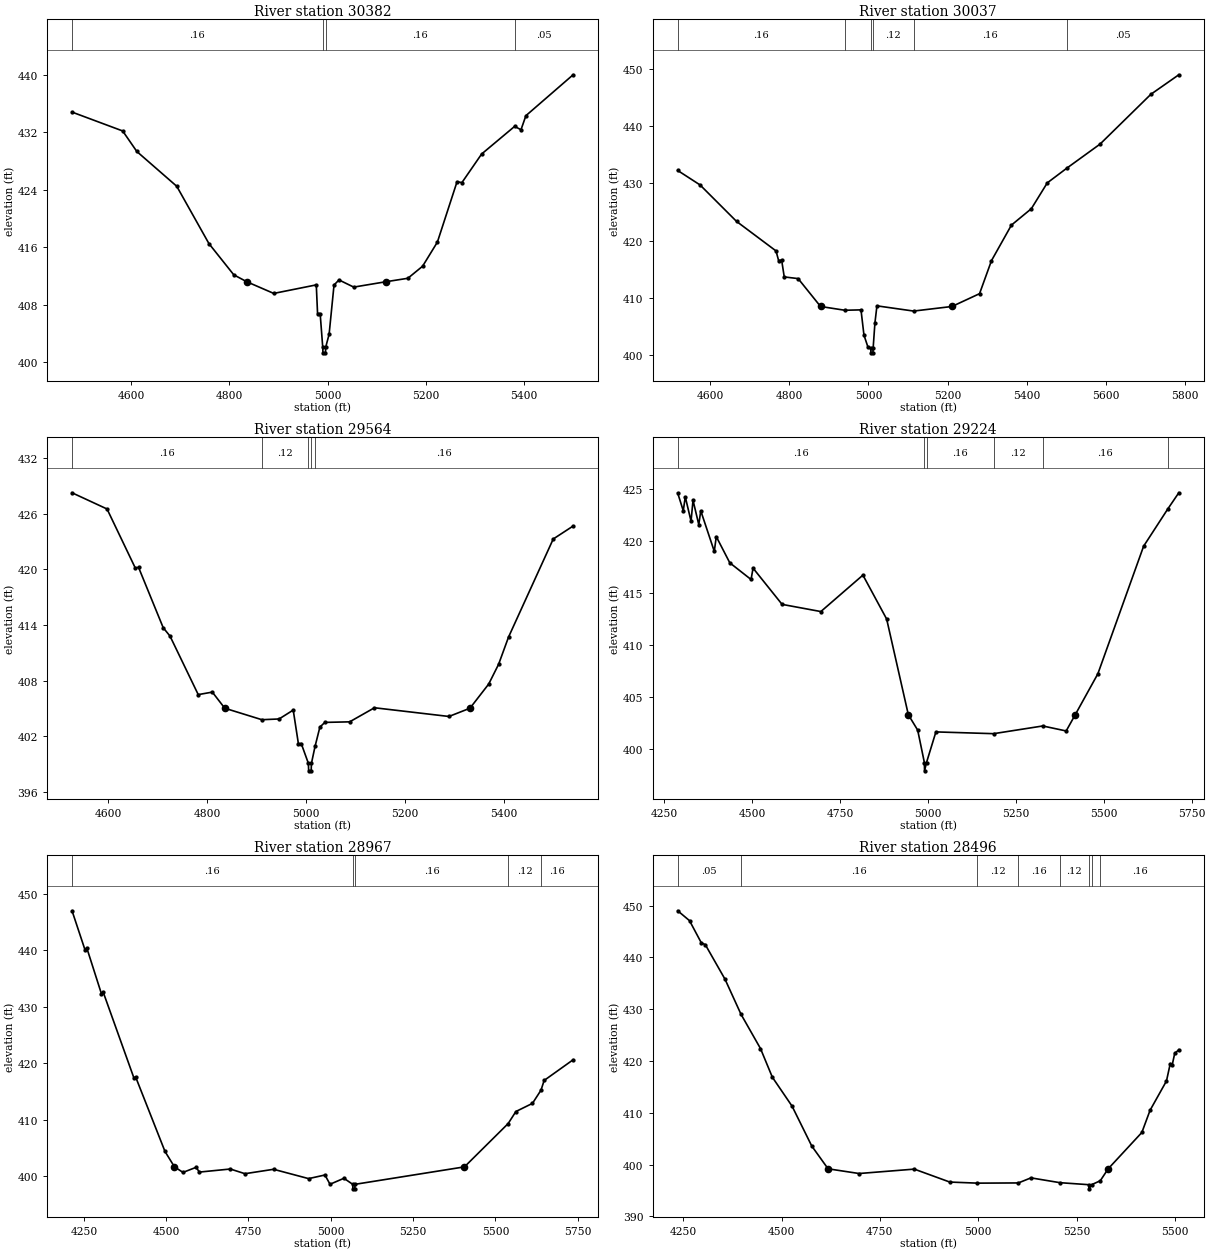
Type RM Length L Ch R = 1,30382,345,345,345
BEGIN DESCRIPTION:
Mapping XS 61cf500b
END DESCRIPTION:
XS GIS Cut Line= 3
      2934848.59      6970702.54      2934416.32      6970447.34
      2933899.09      6970418.75
#Sta/Elev= 30
  4479.9  434.82  4583.0  432.19  4611.8  429.33  4693.1  424.48  4758.6  416.49
  4809.2  412.14  4835.9  411.17  4890.5  409.55  4977.1  410.74  4979.7  406.73
  4985.0  406.73  4990.2  402.07  4990.7  401.27  4995.8  401.27  4996.3  402.07
  5003.2  403.85  5013.2  410.72  5023.3  411.43  5053.3  410.43  5118.1  411.17
  5163.5  411.66  5193.5  413.34  5223.6  416.70  5263.6  425.11  5273.6  425.00
  5313.7  428.98  5380.9  432.83  5393.8  432.36  5403.8  434.32  5499.9  440.02
#Mann=4,-1,0
  4479.9    0.16       0  4990.2    0.07       0  4996.3    0.16       0
  5380.9    0.05       0
Bank Sta=4835.9,5118.1
Exp/Cntr=0.3,0.1

Type RM Length L Ch R = 1,30037,473,473,473
BEGIN DESCRIPTION:
PATTON CREEK 45.0
END DESCRIPTION:
XS GIS Cut Line= 3
      2934924.98      6970524.98      2934625.00      6970175.00
      2933824.97      6970075.00
#Sta/Elev= 30
  4517.7  432.24  4574.2  429.72  4666.4  423.37  4766.3  418.22  4772.9  416.53
  4780.5  416.63  4787.1  413.69  4822.2  413.40  4878.9  408.54  4940.5  407.88
  4981.2  407.95  4988.7  403.55  4998.8  401.46  5005.8  401.26  5006.3  400.46
  5011.4  400.46  5011.9  401.26  5016.4  405.65  5021.5  408.65  5114.3  407.74
  5211.3  408.54  5281.0  410.77  5311.2  416.53  5361.6  422.72  5412.0  425.58
  5452.3  430.08  5502.8  432.70  5585.8  436.84  5714.3  445.52  5784.9  448.92
#Mann=6,-1,0
  4517.7    0.16       0  4940.5    0.12       0  5005.8    0.07       0
  5011.9    0.12       0  5114.3    0.16       0  5502.8    0.05       0
Bank Sta=4878.9,5211.3
Exp/Cntr=0.3,0.1

Type RM Length L Ch R = 1,29564,340,340,340
BEGIN DESCRIPTION:
PATTON CREEK 44.0
END DESCRIPTION:
XS GIS Cut Line= 3
      2935275.01      6970125.01      2934925.00      6969825.00
      2934374.96      6969775.00
#Sta/Elev= 30
  4526.4  428.27  4597.2  426.52  4654.3  420.15  4660.9  420.22  4710.8  413.70
  4724.5  412.80  4781.6  406.48  4810.1  406.75  4835.3  405.01  4910.3  403.77
  4945.1  403.85  4973.7  404.81  4984.1  401.20  4989.9  401.20  5004.4  399.05
  5004.9  398.25  5010.0  398.25  5010.5  399.05  5017.8  400.88  5027.6  402.97
  5037.6  403.48  5087.8  403.54  5138.0  405.06  5288.6  404.12  5331.1  405.01
  5369.0  407.62  5389.0  409.75  5409.1  412.69  5499.5  423.28  5539.7  424.68
#Mann=5,-1,0
  4526.4    0.16       0  4910.3    0.12       0  5004.4    0.07       0
  5010.5    0.12       0  5017.8    0.16       0
Bank Sta=4835.3,5331.1
Exp/Cntr=0.3,0.1

Type RM Length L Ch R = 1,29224,257,257,257
BEGIN DESCRIPTION:
PATTON CREEK 43.0
END DESCRIPTION:
XS GIS Cut Line= 3
      2935418.91      6970181.04      2935088.03      6969551.72
      2934375.03      6969525.00
#Sta/Elev= 30
  4289.0  424.56  4304.8  422.86  4310.5  424.20  4326.9  421.86  4332.5  423.87
  4348.9  421.53  4354.5  422.86  4393.0  418.96  4398.6  420.38  4437.1  417.86
  4497.5  416.26  4503.2  417.35  4585.7  413.87  4695.9  413.18  4815.5  416.68
  4883.0  412.46  4944.6  403.27  4971.2  401.79  4990.2  398.68  4990.7  397.88
  4996.3  398.68  5023.0  401.62  5187.0  401.45  5326.8  402.19  5393.3  401.71
  5419.1  403.27  5483.4  407.20  5613.5  419.46  5682.1  423.03  5713.5  424.59
#Mann=6,-1,0
  4289.0    0.16       0  4990.2    0.07       0  4996.3    0.16       0
  5187.0    0.12       0  5326.8    0.16       0  5682.1    0.05       0
Bank Sta=4944.6,5419.1
Exp/Cntr=0.3,0.1

Type RM Length L Ch R = 1,28967,471,471,471
BEGIN DESCRIPTION:
Mapping XS 242afa05
END DESCRIPTION:
XS GIS Cut Line= 3
      2935913.68      6969469.25      2935158.51      6969308.67
      2934411.99      6969378.11
#Sta/Elev= 30
  4214.2  446.98  4253.7  440.04  4258.8  440.44  4303.3  432.32  4308.4  432.65
  4402.5  417.32  4407.6  417.52  4496.5  404.37  4525.3  401.64  4551.2  400.66
  4590.6  401.55  4601.3  400.72  4694.9  401.26  4739.4  400.43  4826.3  401.21
  4932.7  399.56  4982.3  400.20  4997.7  398.56  5040.0  399.62  5066.6  398.55
  5067.1  397.75  5073.1  397.75  5073.6  398.55  5406.0  401.64  5538.8  409.31
  5562.2  411.44  5612.5  412.88  5638.5  415.22  5648.0  416.94  5736.0  420.60
#Mann=5,-1,0
  4214.2    0.16       0  5066.6    0.07       0  5073.6    0.16       0
  5538.8    0.12       0  5638.5    0.16       0
Bank Sta=4525.3,5406
Exp/Cntr=0.3,0.1

Type RM Length L Ch R = 1,28496,521,521,521
BEGIN DESCRIPTION:
PATTON CREEK 42.0
END DESCRIPTION:
XS GIS Cut Line= 3
      2935674.97      6968875.00      2934925.00      6968925.00
      2934425.04      6969074.99
#Sta/Elev= 30
  4236.2  449.02  4266.2  447.11  4296.3  442.81  4306.3  442.48  4356.4  435.80
  4397.1  429.02  4446.6  422.40  4476.7  416.87  4526.8  411.28  4576.9  403.57
  4618.4  399.17  4697.2  398.26  4837.5  399.11  4927.7  396.61  4997.9  396.40
  5102.0  396.44  5134.0  397.42  5207.7  396.49  5281.0  396.10  5281.5  395.30
  5288.1  396.10  5310.2  396.86  5330.3  399.17  5415.9  406.19  5436.8  410.48
  5478.5  416.14  5488.1  419.50  5493.3  419.32  5499.4  421.46  5509.8  422.17
#Mann=8,-1,0
  4236.2    0.05       0  4397.1    0.16       0  4997.9    0.12       0
  5102.0    0.16       0  5207.7    0.12       0  5281.0    0.07       0
  5288.1    0.12       0  5310.2    0.16       0
Bank Sta=4618.4,5330.3
Exp/Cntr=0.3,0.1

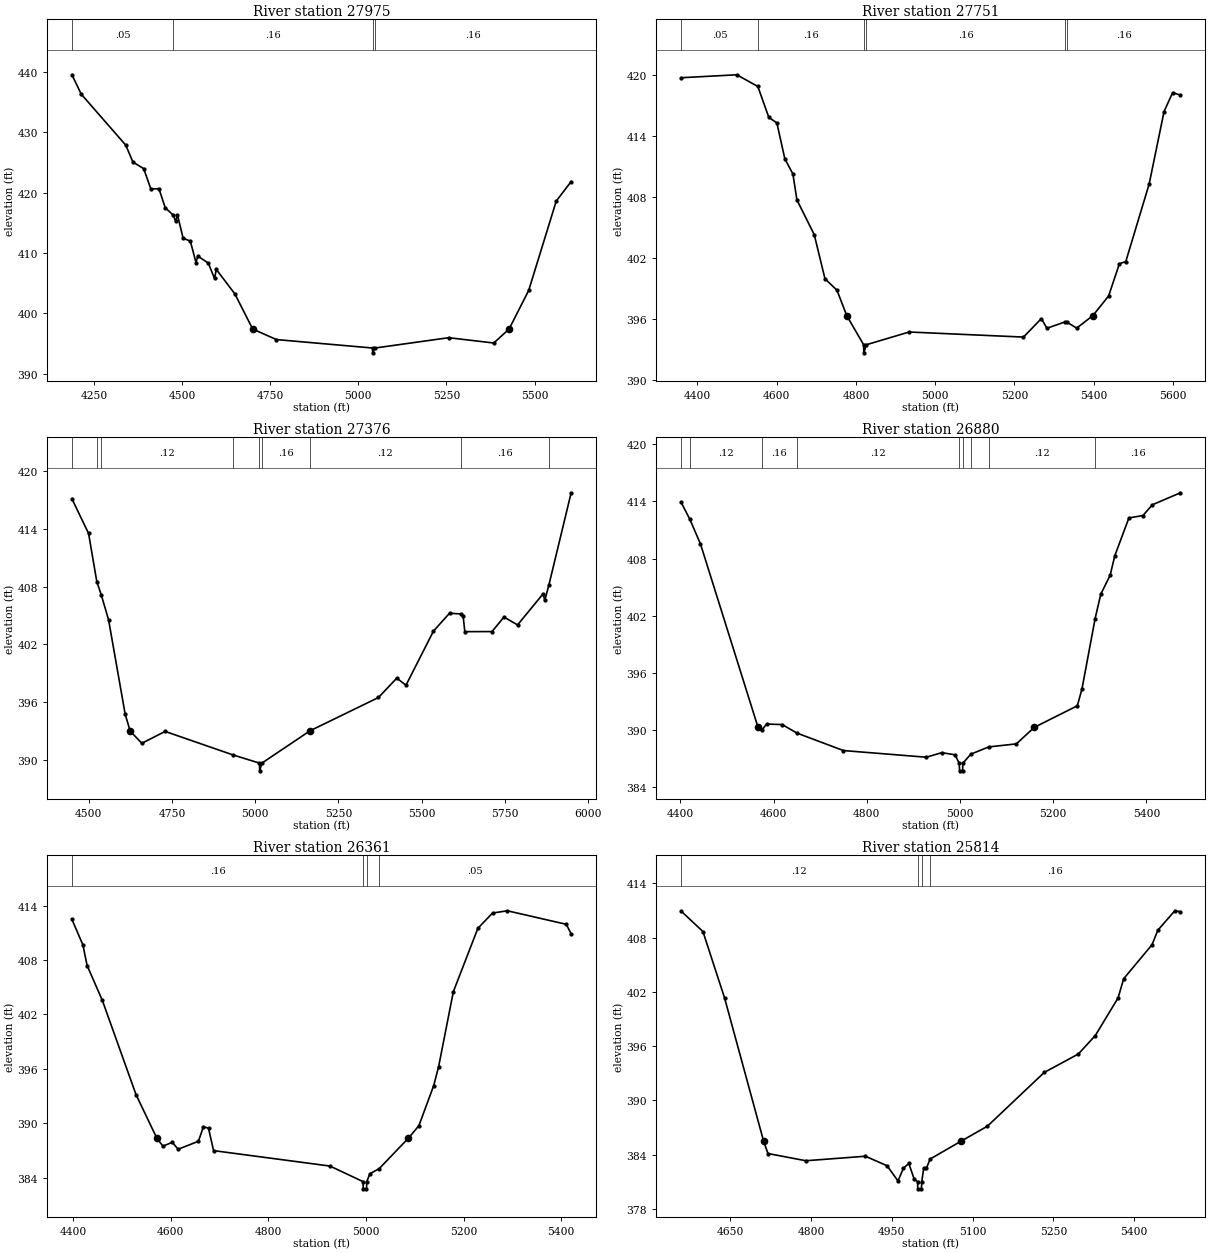
Type RM Length L Ch R = 1,27975,224,224,224
BEGIN DESCRIPTION:
PATTON CREEK 41.0
END DESCRIPTION:
XS GIS Cut Line= 3
      2935525.04      6968625.01      2934725.00      6968475.00
      2934324.97      6968925.03
#Sta/Elev= 30
  4187.5  439.54  4213.8  436.33  4340.2  427.87  4360.5  425.06  4391.0  423.98
  4411.4  420.60  4434.3  420.65  4452.1  417.50  4475.1  416.24  4481.7  415.22
  4486.8  416.33  4502.9  412.43  4523.3  411.96  4539.4  408.41  4544.5  409.47
  4574.2  408.32  4592.0  405.76  4597.1  407.25  4649.6  403.21  4700.2  397.38
  4767.5  395.63  5040.2  394.23  5040.7  393.43  5047.3  394.23  5256.1  395.94
  5384.1  395.06  5427.6  397.38  5483.1  403.77  5561.3  418.59  5603.6  421.84
#Mann=4,-1,0
  4187.5    0.05       0  4475.1    0.16       0  5040.2    0.07       0
  5047.3    0.16       0
Bank Sta=4700.2,5427.6
Exp/Cntr=0.3,0.1

Type RM Length L Ch R = 1,27751,375,375,375
BEGIN DESCRIPTION:
Mapping XS 83996bfd
END DESCRIPTION:
XS GIS Cut Line= 3
      2935223.59      6968210.58      2934585.59      6968306.07
      2934281.75      6968839.96
#Sta/Elev= 30
  4359.4  419.70  4499.5  419.99  4552.6  418.84  4580.4  415.79  4600.6  415.26
  4620.8  411.71  4641.1  410.23  4651.2  407.68  4695.0  404.25  4722.0  399.92
  4752.3  398.79  4776.9  396.29  4819.5  393.43  4820.0  392.63  4826.7  393.43
  4934.3  394.68  5222.8  394.18  5267.9  396.00  5281.9  395.05  5326.8  395.66
  5332.2  395.66  5356.9  395.06  5397.8  396.29  5437.6  398.23  5464.9  401.41
  5480.8  401.60  5539.9  409.25  5577.4  416.37  5599.0  418.23  5618.8  417.99
#Mann=6,-1,0
  4359.4    0.05       0  4552.6    0.16       0  4819.5    0.07       0
  4826.7    0.16       0  5326.8    0.12       0  5332.2    0.16       0
Bank Sta=4776.9,5397.8
Exp/Cntr=0.3,0.1

Type RM Length L Ch R = 1,27376,496,496,496
BEGIN DESCRIPTION:
double PATTON CREEK 40.0
END DESCRIPTION:
XS GIS Cut Line= 3
      2934924.98      6968025.00      2934374.68      6968025.98
      2934140.20      6968945.87
#Sta/Elev= 30
  4449.7  417.10  4499.7  413.51  4524.4  408.51  4537.5  407.17  4559.7  404.56
  4609.7  394.74  4624.7  393.00  4659.7  391.74  4729.7  392.97  4933.6  390.53
  5013.1  389.68  5013.7  388.88  5020.3  389.68  5163.4  393.00  5163.5  393.01
  5370.5  396.49  5425.5  398.50  5453.1  397.76  5535.6  403.37  5583.9  405.23
  5618.0  405.16  5624.8  404.94  5629.9  403.32  5711.7  403.33  5747.4  404.84
  5788.3  404.02  5864.9  407.24  5870.1  406.57  5882.3  408.14  5949.3  417.73
#Mann=9,-1,0
  4449.7    0.05       0  4524.4    0.16       0  4537.5    0.12       0
  4933.6    0.16       0  5013.1    0.07       0  5020.3    0.16       0
  5163.5    0.12       0  5618.0    0.16       0  5882.3    0.12       0
Bank Sta=4624.7,5163.4
Exp/Cntr=0.3,0.1

Type RM Length L Ch R = 1,26880,519,519,519
BEGIN DESCRIPTION:
PATTON CREEK 39.0
END DESCRIPTION:
XS GIS Cut Line= 3
      2934825.00      6967425.00      2934225.00      6967575.00
      2933775.03      6967525.00
#Sta/Elev= 30
  4401.9  413.88  4420.3  412.12  4443.1  409.54  4566.7  390.27  4574.4  389.95
  4584.9  390.62  4618.4  390.57  4650.4  389.67  4749.8  387.84  4927.6  387.14
  4961.1  387.62  4989.4  387.39  4998.4  386.51  4999.1  385.71  5005.6  385.71
  5006.2  386.51  5023.3  387.46  5061.6  388.22  5121.0  388.54  5159.3  390.27
  5251.8  392.54  5261.8  394.31  5290.0  401.70  5302.1  404.25  5322.2  406.24
  5332.3  408.30  5362.5  412.26  5392.6  412.51  5412.8  413.64  5473.1  414.90
#Mann=9,-1,0
  4401.9    0.16       0  4420.3    0.12       0  4574.4    0.16       0
  4650.4    0.12       0  4998.4    0.07       0  5006.2    0.12       0
  5023.3    0.16       0  5061.6    0.12       0  5290.0    0.16       0
Bank Sta=4566.7,5159.3
Exp/Cntr=0.3,0.1

Type RM Length L Ch R = 1,26361,547,547,547
BEGIN DESCRIPTION:
PATTON CREEK 38.0
END DESCRIPTION:
XS GIS Cut Line= 3
      2934774.97      6967224.99      2934225.00      6967075.00
      2933775.03      6967125.00
#Sta/Elev= 30
  4397.7  412.47  4420.1  409.67  4428.8  407.39  4459.9  403.56  4529.0  393.17
  4571.8  388.35  4584.2  387.49  4603.3  387.92  4615.3  387.15  4656.8  388.03
  4667.2  389.64  4677.5  389.46  4687.9  387.00  4926.3  385.30  4994.0  383.59
  4994.7  382.79  5001.2  382.79  5001.8  383.59  5008.0  384.45  5027.3  385.02
  5086.7  388.35  5108.6  389.75  5138.8  394.15  5148.9  396.23  5179.1  404.50
  5229.4  411.49  5259.5  413.17  5289.7  413.42  5410.5  411.93  5420.5  410.88
#Mann=4,-1,0
  4397.7    0.16       0  4994.0    0.07       0  5001.8    0.16       0
  5027.3    0.05       0
Bank Sta=4571.8,5086.7
Exp/Cntr=0.3,0.1

Type RM Length L Ch R = 1,25814,527,527,527
BEGIN DESCRIPTION:
PATTON CREEK 37.0
END DESCRIPTION:
XS GIS Cut Line= 3
      2934775.02      6966525.00      2934325.00      6966575.00
      2933875.03      6966425.01
#Sta/Elev= 30
  4558.9  410.93  4599.2  408.68  4639.4  401.32  4711.9  385.47  4719.9  384.11
  4790.3  383.31  4901.0  383.81  4941.3  382.75  4961.4  381.07  4971.4  382.47
  4981.5  383.01  4991.6  381.26  4997.7  381.00  4998.3  380.20  5004.9  380.20
  5005.6  381.00  5009.2  382.50  5014.3  382.50  5021.1  383.50  5078.4  385.47
  5127.6  387.14  5233.1  393.09  5296.3  395.12  5327.9  397.17  5370.1  401.33
  5380.6  403.46  5433.3  407.23  5443.9  408.82  5475.5  410.98  5486.0  410.88
#Mann=4,-1,0
  4558.9    0.12       0  4997.7    0.07       0  5005.6    0.12       0
  5021.1    0.16       0
Bank Sta=4711.9,5078.4
Exp/Cntr=0.3,0.1

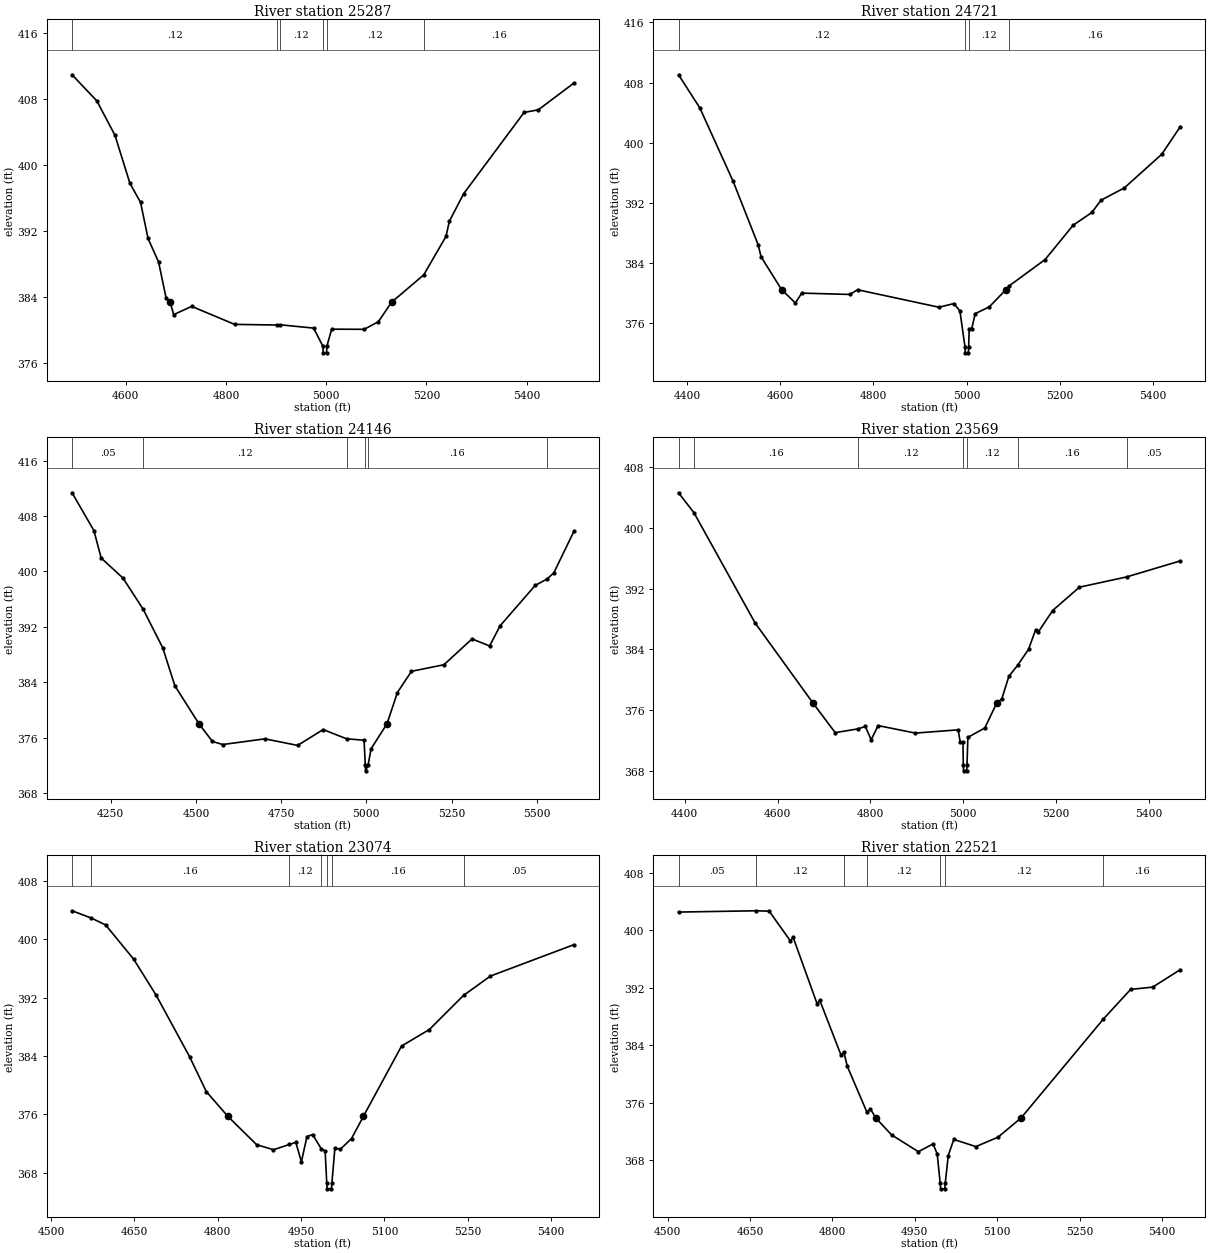
Type RM Length L Ch R = 1,25287,566,566,566
BEGIN DESCRIPTION:
PATTON CREEK 36.0
END DESCRIPTION:
XS GIS Cut Line= 3
      2934824.97      6966374.98      2934375.00      6966075.00
      2934024.98      6965774.98
#Sta/Elev= 30
  4492.6  410.88  4542.1  407.71  4578.2  403.55  4608.2  397.71  4629.3  395.42
  4644.3  391.04  4665.3  388.19  4680.3  383.85  4688.5  383.31  4695.4  381.81
  4731.4  382.81  4817.1  380.63  4901.9  380.55  4907.6  380.58  4974.8  380.18
  4993.4  377.98  4994.0  377.18  5000.6  377.18  5001.3  377.98  5010.9  380.05
  5075.6  380.03  5104.2  380.95  5130.4  383.31  5194.7  386.63  5239.2  391.30
  5245.8  393.12  5274.3  396.46  5395.0  406.31  5423.6  406.64  5494.4  409.87
#Mann=6,-1,0
  4492.6    0.12       0  4901.9    0.16       0  4907.6    0.12       0
  4993.4    0.07       0  5001.3    0.12       0  5194.7    0.16       0
Bank Sta=4688.5,5130.4
Exp/Cntr=0.3,0.1

Type RM Length L Ch R = 1,24721,575,575,575
BEGIN DESCRIPTION:
double PATTON CREEK 35.0
END DESCRIPTION:
XS GIS Cut Line= 3
      2935275.00      6965975.00      2934725.00      6965675.00
      2934275.00      6965675.00
#Sta/Elev= 30
  4381.9  409.03  4427.5  404.63  4499.1  394.84  4552.8  386.39  4558.9  384.82
  4602.9  380.44  4632.5  378.66  4646.3  379.97  4749.7  379.79  4765.9  380.42
  4940.5  378.09  4972.8  378.58  4985.6  377.58  4996.4  372.82  4997.0  372.02
  5003.6  372.02  5004.3  372.82  5005.5  375.25  5010.9  375.25  5018.4  377.24
  5048.4  378.13  5084.5  380.44  5090.8  380.91  5168.4  384.44  5228.4  389.00
  5268.4  390.70  5288.4  392.34  5338.4  393.98  5418.4  398.44  5458.4  402.13
#Mann=4,-1,0
  4381.9    0.12       0  4996.4    0.07       0  5004.3    0.12       0
  5090.8    0.16       0
Bank Sta=4602.9,5084.5
Exp/Cntr=0.3,0.1

Type RM Length L Ch R = 1,24146,577,577,577
BEGIN DESCRIPTION:
double PATTON CREEK 34.0
END DESCRIPTION:
XS GIS Cut Line= 3
      2935624.98      6964825.01      2934825.00      6965125.00
      2934225.05      6965274.99
#Sta/Elev= 30
  4136.3  411.35  4200.4  405.89  4221.7  401.93  4285.8  399.03  4345.2  394.51
  4402.4  388.97  4438.0  383.48  4508.6  378.00  4548.4  375.44  4578.6  375.00
  4702.3  375.82  4798.4  374.87  4873.2  377.16  4941.8  375.83  4993.3  375.62
  4997.0  372.00  4997.7  371.20  5005.0  372.00  5013.9  374.39  5060.7  378.00
  5091.2  382.51  5132.4  385.57  5227.8  386.52  5310.2  390.25  5361.8  389.23
  5392.7  392.15  5495.8  397.98  5529.7  398.88  5549.9  399.76  5609.1  405.76
#Mann=6,-1,0
  4136.3    0.05       0  4345.2    0.12       0  4941.8    0.16       0
  4997.0    0.07       0  5005.0    0.16       0  5529.7    0.05       0
Bank Sta=4508.6,5060.7
Exp/Cntr=0.3,0.1

Type RM Length L Ch R = 1,23569,495,495,495
BEGIN DESCRIPTION:
double PATTON CREEK 33.0
END DESCRIPTION:
XS GIS Cut Line= 3
      2935224.98      6964225.01      2934725.00      6964575.00
      2934325.00      6964825.00
#Sta/Elev= 30
  4386.6  404.62  4419.9  401.99  4551.8  387.47  4676.6  376.93  4724.4  373.04
  4773.2  373.53  4789.4  373.86  4802.0  372.10  4816.9  373.97  4897.1  372.98
  4989.5  373.41  4993.9  371.83  4999.9  371.83  5000.6  368.81  5001.2  368.01
  5007.9  368.01  5008.6  368.81  5010.5  372.42  5047.0  373.65  5072.6  376.93
  5083.6  377.48  5098.9  380.45  5118.3  381.95  5141.4  384.02  5156.7  386.61
  5162.6  386.31  5193.3  389.12  5251.0  392.19  5352.7  393.54  5468.6  395.65
#Mann=7,-1,0
  4386.6    0.05       0  4419.9    0.16       0  4773.2    0.12       0
  5000.6    0.07       0  5008.6    0.12       0  5118.3    0.16       0
  5352.7    0.05       0
Bank Sta=4676.6,5072.6
Exp/Cntr=0.3,0.1

Type RM Length L Ch R = 1,23074,553,553,553
BEGIN DESCRIPTION:
PATTON CREEK 32.0
END DESCRIPTION:
XS GIS Cut Line= 3
      2935175.04      6964175.00      2934725.00      6964125.00
      2934275.01      6964125.00
#Sta/Elev= 30
  4537.9  403.87  4571.7  402.90  4598.3  401.93  4648.6  397.26  4688.9  392.35
  4749.2  383.92  4779.4  379.13  4818.4  375.72  4870.0  371.86  4900.2  371.17
  4928.8  371.89  4940.4  372.18  4950.5  369.52  4960.5  372.97  4970.6  373.25
  4986.6  371.26  4993.2  371.01  4996.1  366.62  4997.0  365.82  5004.5  365.82
  5005.4  366.62  5010.7  371.36  5020.7  371.25  5040.7  372.70  5061.9  375.72
  5130.7  385.36  5180.7  387.62  5242.2  392.29  5290.7  394.94  5440.7  399.23
#Mann=7,-1,0
  4537.9    0.05       0  4571.7    0.16       0  4928.8    0.12       0
  4986.6    0.16       0  4996.1    0.07       0  5005.4    0.16       0
  5242.2    0.05       0
Bank Sta=4818.4,5061.9
Exp/Cntr=0.3,0.1

Type RM Length L Ch R = 1,22521,146,146,146
BEGIN DESCRIPTION:
PATTON CREEK 31.0
END DESCRIPTION:
XS GIS Cut Line= 3
      2935174.96      6963674.99      2934725.00      6963575.00
      2934275.00      6963625.00
#Sta/Elev= 30
  4519.7  402.53  4660.7  402.71  4684.8  402.66  4723.3  398.52  4728.4  399.01
  4771.9  389.79  4777.0  390.23  4815.5  382.64  4820.7  383.05  4827.0  381.07
  4862.6  374.71  4869.2  375.12  4878.7  373.90  4907.6  371.53  4956.3  369.19
  4983.2  370.27  4990.7  368.87  4996.1  364.82  4997.0  364.02  5004.5  364.02
  5005.4  364.82  5010.8  368.65  5020.9  370.89  5061.1  369.90  5101.4  371.20
  5143.6  373.90  5293.2  387.64  5342.9  391.77  5383.1  392.09  5433.4  394.52
#Mann=7,-1,0
  4519.7    0.05       0  4660.7    0.12       0  4820.7    0.16       0
  4862.6    0.12       0  4996.1    0.07       0  5005.4    0.12       0
  5293.2    0.16       0
Bank Sta=4878.7,5143.6
Exp/Cntr=0.3,0.1

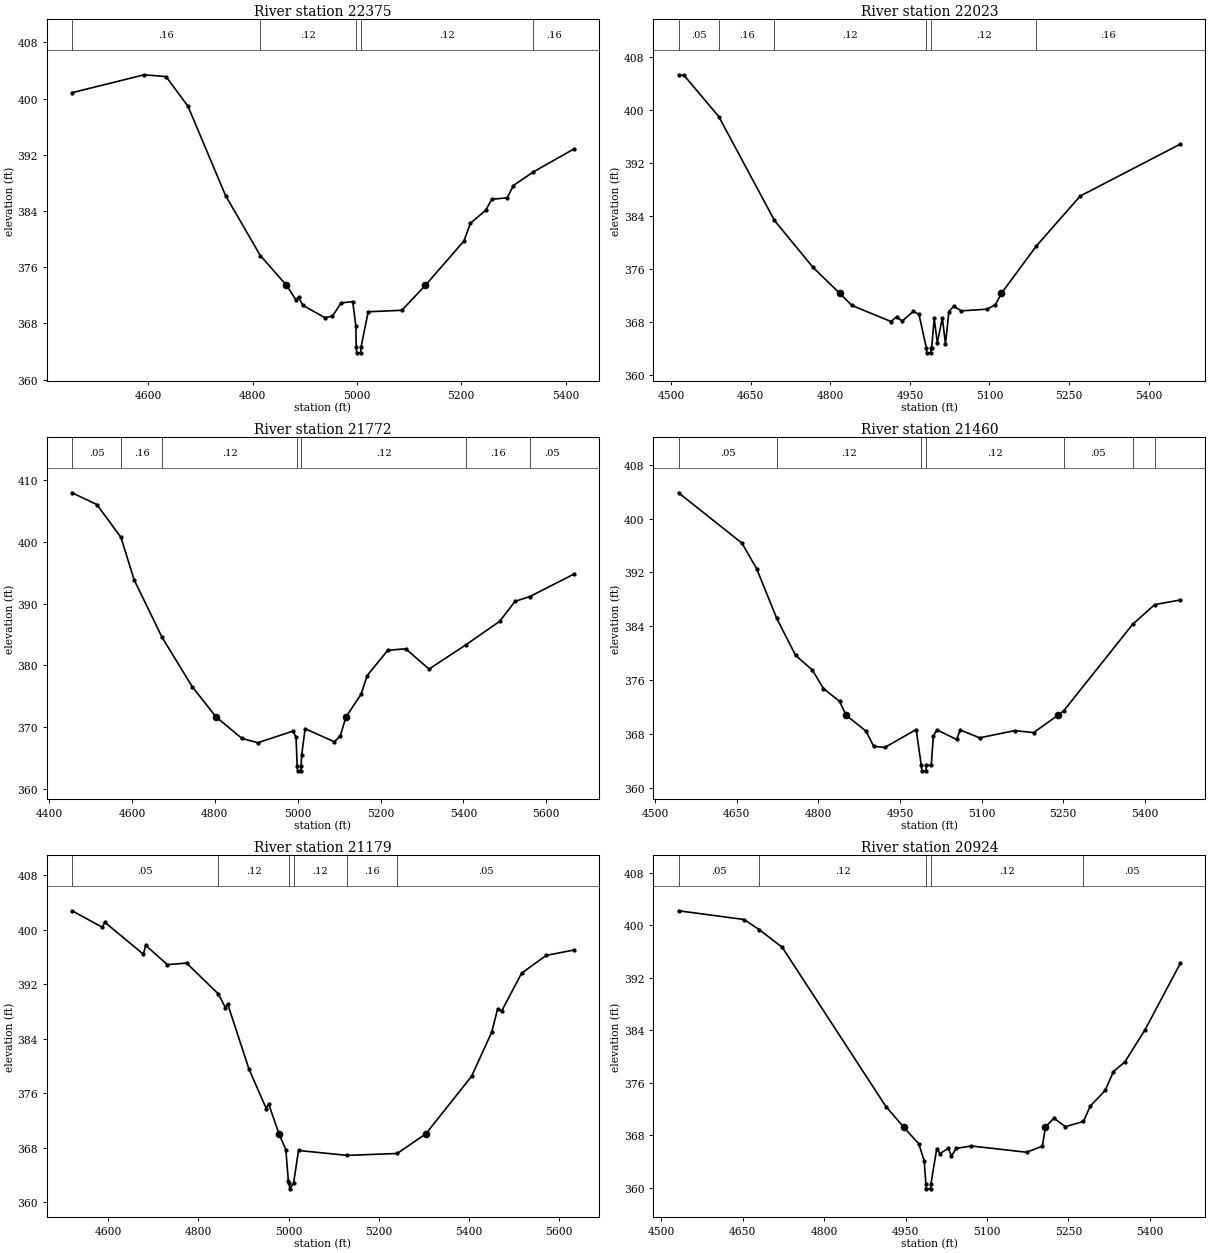
Type RM Length L Ch R = 1,22375,352,352,352
BEGIN DESCRIPTION:
Mapping XS 788670c0
END DESCRIPTION:
XS GIS Cut Line= 3
      2935186.81      6963599.49      2934673.79      6963438.03
      2934262.36      6963539.58
#Sta/Elev= 30
  4454.1  400.85  4592.3  403.40  4634.2  403.14  4676.2  398.92  4748.2  386.20
  4814.8  377.66  4865.0  373.42  4883.0  371.37  4888.2  371.72  4896.3  370.57
  4938.2  368.82  4953.0  369.02  4969.7  370.90  4991.9  371.11  4998.0  367.57
  4998.5  364.60  4999.4  363.80  5006.9  363.80  5007.8  364.60  5021.6  369.65
  5086.1  369.86  5131.2  373.42  5205.3  379.75  5217.3  382.24  5246.8  384.11
  5258.5  385.67  5288.2  385.88  5299.7  387.63  5338.2  389.57  5415.7  392.83
#Mann=5,-1,0
  4454.1    0.16       0  4814.8    0.12       0  4998.5    0.07       0
  5007.8    0.12       0  5338.2    0.16       0
Bank Sta=4865,5131.2
Exp/Cntr=0.3,0.1

Type RM Length L Ch R = 1,22023,251,251,251
BEGIN DESCRIPTION:
PATTON CREEK 30.0
END DESCRIPTION:
XS GIS Cut Line= 3
      2935025.04      6962974.99      2934575.00      6963125.00
      2934174.99      6963375.01
#Sta/Elev= 30
  4513.7  405.38  4524.3  405.28  4589.5  399.07  4694.6  383.37  4766.7  376.33
  4817.5  372.37  4840.5  370.53  4914.3  368.10  4924.8  368.80  4935.4  368.18
  4956.5  369.64  4967.0  369.17  4980.8  364.17  4981.7  363.37  4989.3  363.37
  4990.2  364.17  4991.0  364.17  4995.8  368.57  5001.6  364.88  5011.1  368.65
  5017.0  364.73  5023.5  369.60  5032.3  370.40  5047.0  369.71  5096.0  369.97
  5111.3  370.67  5122.6  372.37  5188.1  379.49  5271.1  387.06  5459.8  394.91
#Mann=6,-1,0
  4513.7    0.05       0  4589.5    0.16       0  4694.6    0.12       0
  4980.8    0.07       0  4990.2    0.12       0  5188.1    0.16       0
Bank Sta=4817.5,5122.6
Exp/Cntr=0.3,0.1

Type RM Length L Ch R = 1,21772,312,312,312
BEGIN DESCRIPTION:
Mapping XS 6af0bd96
END DESCRIPTION:
XS GIS Cut Line= 3
      2935074.80      6962841.67      2934634.73      6962833.86
      2934022.76      6963302.60
#Sta/Elev= 30
  4455.6  407.93  4515.4  406.02  4573.6  400.71  4605.4  393.83  4672.6  384.55
  4745.4  376.55  4803.1  371.64  4865.5  368.16  4903.8  367.46  4989.0  369.35
  4996.2  368.31  4998.8  363.71  4999.7  362.91  5007.3  362.91  5008.2  363.71
  5009.8  365.52  5018.0  369.73  5088.7  367.61  5103.2  368.62  5116.6  371.64
  5153.1  375.30  5167.6  378.32  5217.5  382.43  5260.7  382.67  5317.2  379.39
  5407.0  383.36  5487.6  387.12  5524.8  390.36  5559.9  391.11  5666.6  394.76
#Mann=7,-1,0
  4455.6    0.05       0  4573.6    0.16       0  4672.6    0.12       0
  4998.8    0.07       0  5008.2    0.12       0  5407.0    0.16       0
  5559.9    0.05       0
Bank Sta=4803.1,5116.6
Exp/Cntr=0.3,0.1

Type RM Length L Ch R = 1,21460,281,281,281
BEGIN DESCRIPTION:
PATTON CREEK 29.0
END DESCRIPTION:
XS GIS Cut Line= 3
      2934874.99      6962525.00      2934425.00      6962625.00
      2934125.03      6962974.97
#Sta/Elev= 30
  4543.1  403.82  4659.6  396.35  4686.5  392.58  4723.5  385.20  4758.2  379.70
  4788.9  377.53  4809.4  374.78  4838.9  372.89  4851.4  370.79  4887.5  368.48
  4901.6  366.22  4922.1  366.05  4979.7  368.71  4989.1  363.38  4990.0  362.58
  4997.6  362.58  4998.5  363.38  5007.4  363.41  5011.2  367.73  5017.8  368.66
  5054.0  367.23  5060.6  368.64  5096.3  367.48  5160.5  368.54  5195.6  368.26
  5239.5  370.79  5251.0  371.51  5377.3  384.30  5417.8  387.23  5465.0  387.92
#Mann=7,-1,0
  4543.1    0.05       0  4723.5    0.12       0  4989.1    0.07       0
  4998.5    0.12       0  5251.0    0.05       0  5377.3    0.16       0
  5417.8    0.05       0
Bank Sta=4851.4,5239.5
Exp/Cntr=0.3,0.1

Type RM Length L Ch R = 1,21179,255,255,255
BEGIN DESCRIPTION:
Mapping XS 8913a265
END DESCRIPTION:
XS GIS Cut Line= 3
      2934764.90      6962427.61      2934317.02      6962378.13
      2933720.66      6962664.59
#Sta/Elev= 30
  4520.1  402.81  4587.4  400.38  4592.4  401.14  4678.2  396.42  4683.2  397.74
  4731.3  394.89  4774.0  395.12  4844.5  390.57  4859.8  388.58  4864.9  389.13
  4912.4  379.50  4950.6  373.72  4955.7  374.43  4978.7  370.02  4993.9  367.69
  4999.4  363.15  5001.5  362.73  5002.4  361.93  5011.0  362.73  5022.0  367.57
  5129.7  366.85  5240.8  367.13  5304.3  370.02  5405.6  378.48  5450.0  384.93
  5463.3  388.36  5472.2  388.06  5516.5  393.63  5571.0  396.25  5632.3  397.04
#Mann=6,-1,0
  4520.1    0.05       0  4844.5    0.12       0  5001.5    0.07       0
  5011.0    0.12       0  5129.7    0.16       0  5240.8    0.05       0
Bank Sta=4978.7,5304.3
Exp/Cntr=0.3,0.1

Type RM Length L Ch R = 1,20924,313,313,313
BEGIN DESCRIPTION:
PATTON CREEK 28.0
END DESCRIPTION:
XS GIS Cut Line= 3
      2934724.95      6962224.99      2934275.00      6962175.00
      2933875.02      6961925.01
#Sta/Elev= 30
  4531.7  402.21  4652.4  400.88  4680.3  399.34  4722.8  396.63  4914.0  372.33
  4946.2  369.25  4974.4  366.66  4984.4  364.03  4987.3  360.61  4988.2  359.81
  4995.9  359.81  4996.8  360.61  5007.4  365.93  5013.3  365.19  5028.6  365.97
  5034.5  364.82  5043.4  365.98  5071.1  366.34  5173.1  365.39  5202.0  366.32
  5207.7  369.25  5223.2  370.58  5244.4  369.29  5277.5  370.08  5290.4  372.45
  5317.6  374.81  5332.9  377.69  5354.1  379.18  5390.7  384.01  5456.1  394.20
#Mann=5,-1,0
  4531.7    0.05       0  4680.3    0.12       0  4987.3    0.07       0
  4996.8    0.12       0  5277.5    0.05       0
Bank Sta=4946.2,5207.7
Exp/Cntr=0.3,0.1