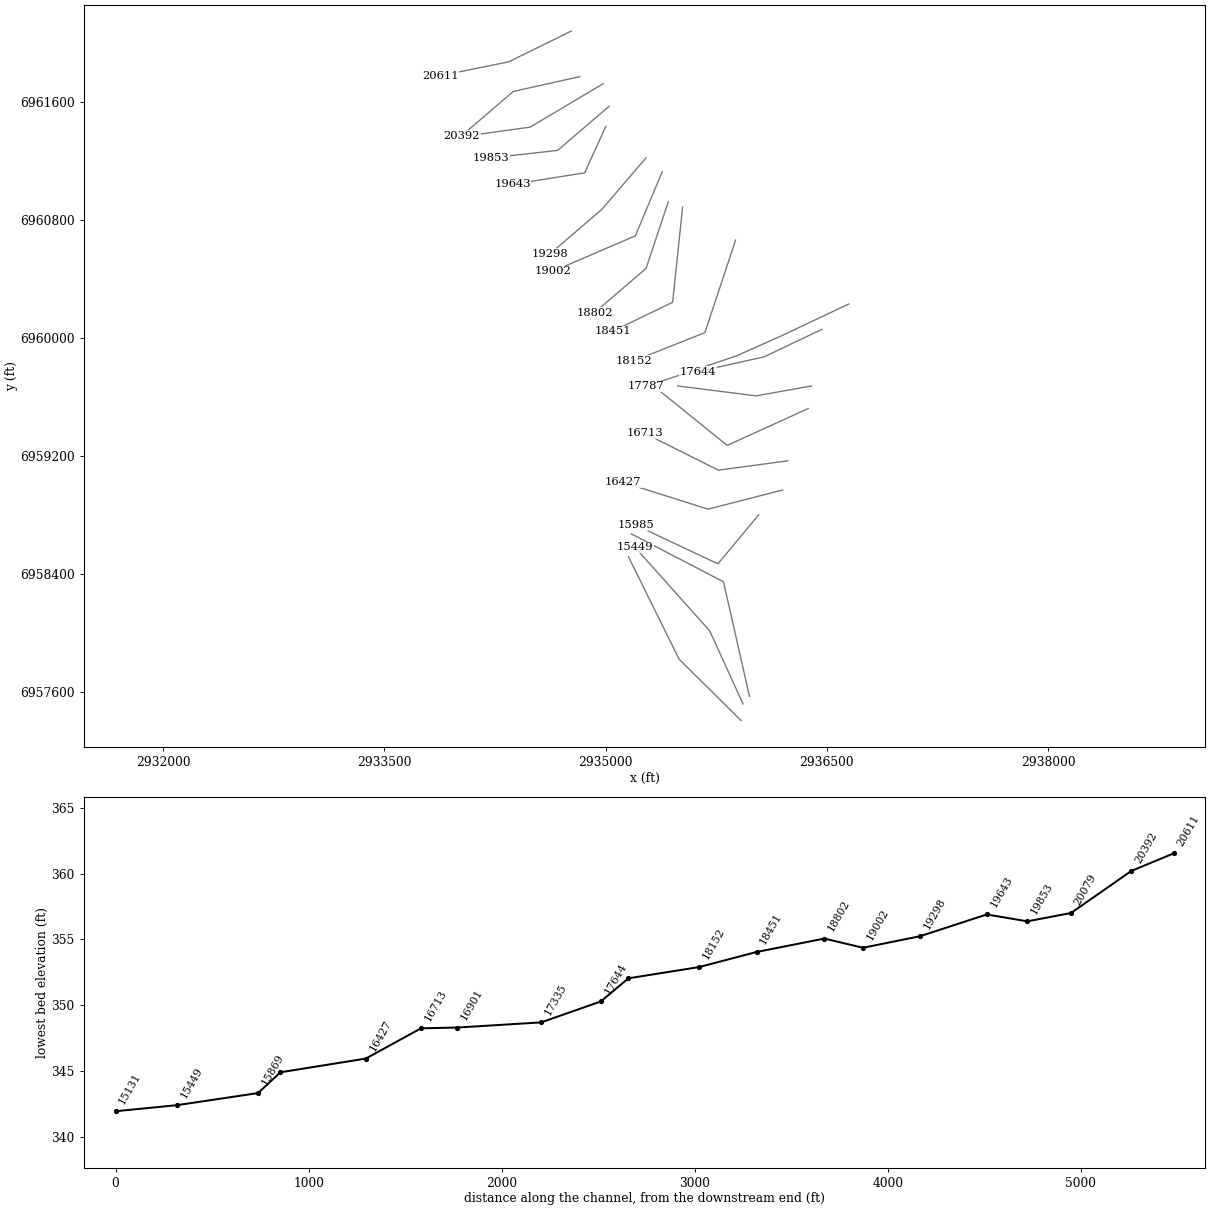
HEC-RAS study PATTON CREEK.prj: PATTON CREEK Base Level Engineering

--- PATTON CREEK.g01 (geometry) --- (continued)

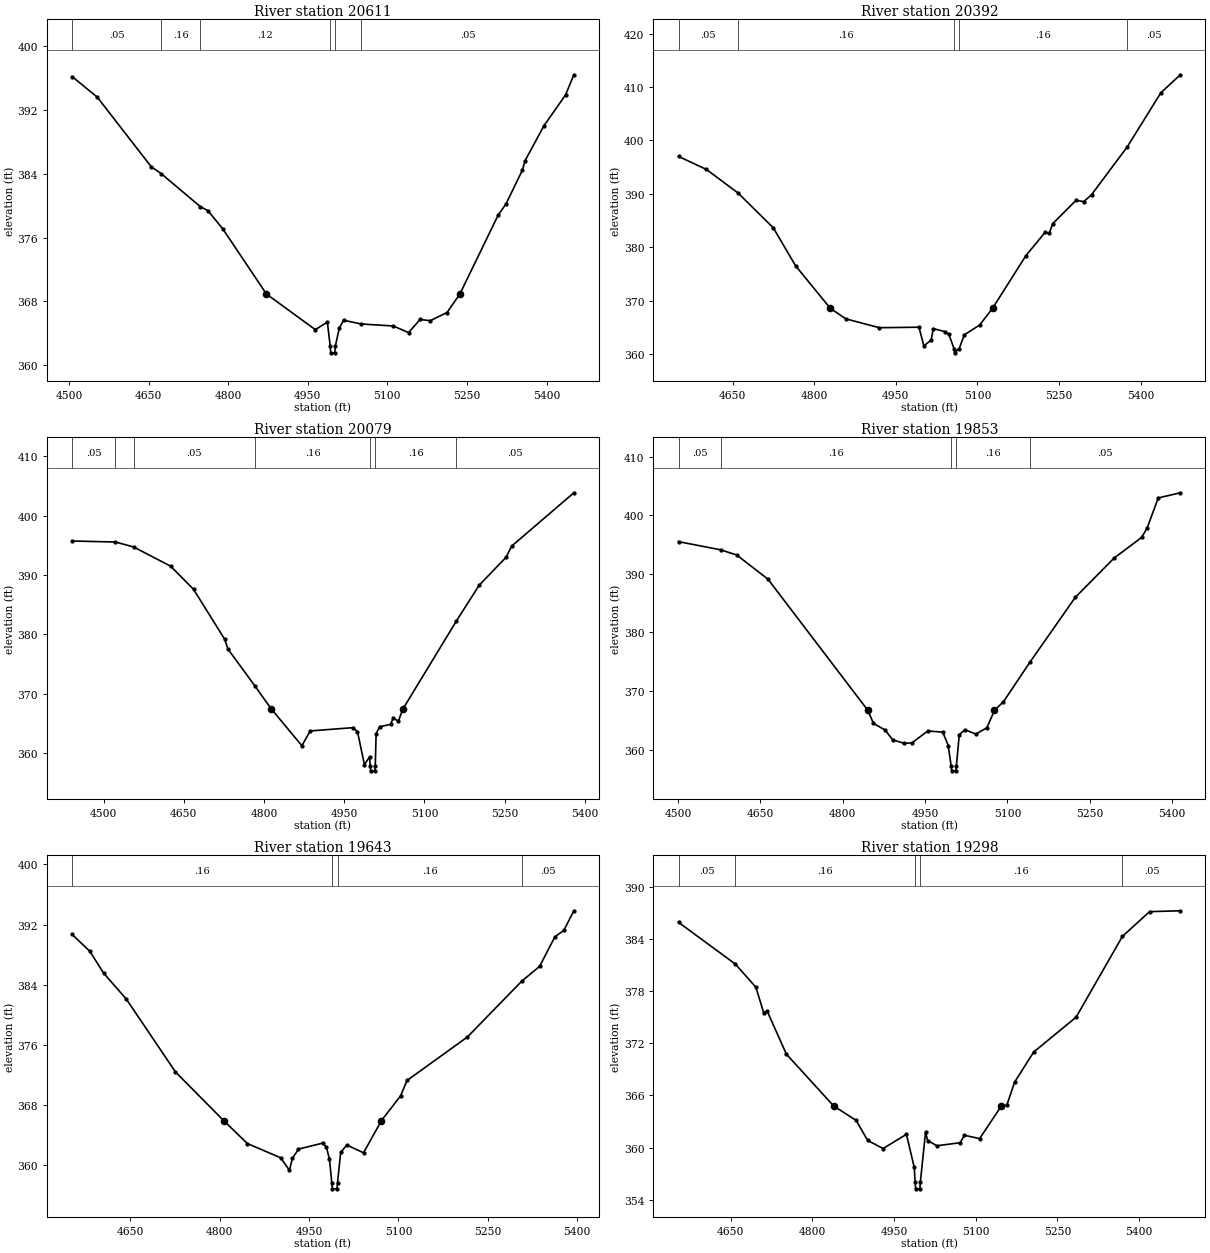
Type RM Length L Ch R = 1,20611,219,219,219
BEGIN DESCRIPTION:
Mapping XS f681f051
END DESCRIPTION:
XS GIS Cut Line= 3
      2934767.56      6962083.87      2934343.06      6961875.53
      2933879.72      6961781.82
#Sta/Elev= 30
  4505.9  396.21  4553.3  393.63  4655.0  384.90  4674.1  384.01  4747.7  379.88
  4761.9  379.38  4789.9  377.10  4872.2  368.92  4964.3  364.45  4987.0  365.40
  4992.4  362.34  4993.3  361.54  5001.0  361.54  5001.9  362.34  5009.6  364.68
  5017.6  365.63  5050.9  365.16  5111.0  364.91  5140.0  364.08  5161.8  365.73
  5180.8  365.57  5212.5  366.60  5236.7  368.92  5308.9  378.83  5323.7  380.24
  5354.3  384.43  5359.6  385.66  5395.1  390.03  5435.9  393.91  5451.5  396.43
#Mann=6,-1,0
  4505.9    0.05       0  4674.1    0.16       0  4747.7    0.12       0
  4992.4    0.07       0  5001.9    0.12       0  5050.9    0.05       0
Bank Sta=4872.2,5236.7
Exp/Cntr=0.3,0.1

Type RM Length L Ch R = 1,20392,313,313,313
BEGIN DESCRIPTION:
PATTON CREEK 27.0
END DESCRIPTION:
XS GIS Cut Line= 3
      2934825.02      6961775.00      2934375.00      6961675.00
      2934024.98      6961374.98
#Sta/Elev= 30
  4550.8  397.00  4602.0  394.57  4660.2  390.15  4725.0  383.62  4765.9  376.51
  4829.6  368.56  4858.1  366.58  4919.6  364.92  4992.6  365.01  5001.6  361.50
  5015.1  362.62  5018.9  364.75  5039.8  364.20  5047.5  363.65  5057.0  361.01
  5057.9  360.21  5066.5  361.01  5076.0  363.60  5104.0  365.41  5127.8  368.56
  5189.1  378.42  5224.2  382.77  5231.9  382.61  5238.4  384.42  5281.2  388.78
  5295.5  388.54  5309.8  389.85  5375.3  398.80  5437.1  408.94  5472.8  412.30
#Mann=5,-1,0
  4550.8    0.05       0  4660.2    0.16       0  5057.0    0.07       0
  5066.5    0.16       0  5375.3    0.05       0
Bank Sta=4829.6,5127.8
Exp/Cntr=0.3,0.1

Type RM Length L Ch R = 1,20079,226,226,226
BEGIN DESCRIPTION:
Mapping XS 2cb7cc36
END DESCRIPTION:
XS GIS Cut Line= 3
      2934983.65      6961727.07      2934488.90      6961432.82
      2934129.72      6961383.37
#Sta/Elev= 30
  4441.2  395.71  4522.3  395.54  4556.1  394.71  4625.5  391.47  4668.4  387.56
  4726.8  379.13  4732.6  377.52  4783.0  371.31  4813.7  367.43  4870.9  361.24
  4886.5  363.73  4966.3  364.28  4974.8  363.62  4987.8  358.07  4997.5  359.35
  4998.6  357.81  4999.5  357.01  5007.2  357.01  5008.1  357.81  5009.7  363.27
  5016.2  364.44  5036.7  364.83  5041.8  365.93  5051.1  365.35  5059.8  367.43
  5159.8  382.24  5202.5  388.28  5252.7  392.97  5263.0  394.84  5379.4  403.83
#Mann=7,-1,0
  4441.2    0.05       0  4522.3    0.16       0  4556.1    0.05       0
  4783.0    0.16       0  4998.6    0.07       0  5008.1    0.16       0
  5159.8    0.05       0
Bank Sta=4813.7,5059.8
Exp/Cntr=0.3,0.1

Type RM Length L Ch R = 1,19853,210,210,210
BEGIN DESCRIPTION:
PATTON CREEK 26.0
END DESCRIPTION:
XS GIS Cut Line= 3
      2935024.96      6961574.97      2934675.00      6961275.00
      2934225.00      6961225.00
#Sta/Elev= 30
  4501.1  395.49  4577.6  394.10  4607.0  393.22  4664.0  389.08  4845.8  366.70
  4856.1  364.46  4877.0  363.37  4891.2  361.66  4912.1  361.07  4926.4  361.17
  4954.9  363.18  4982.2  362.99  4992.2  360.70  4997.5  357.18  4998.4  356.38
  5006.1  356.38  5007.0  357.18  5012.3  362.55  5022.4  363.40  5042.5  362.65
  5062.6  363.74  5076.4  366.70  5092.8  368.18  5141.4  374.98  5223.6  385.99
  5294.1  392.68  5344.4  396.21  5354.4  397.83  5374.6  402.95  5414.8  403.83
#Mann=5,-1,0
  4501.1    0.05       0  4577.6    0.16       0  4997.5    0.07       0
  5007.0    0.16       0  5141.4    0.05       0
Bank Sta=4845.8,5076.4
Exp/Cntr=0.3,0.1

Type RM Length L Ch R = 1,19643,345,345,345
BEGIN DESCRIPTION:
Mapping XS 2fea7a8c
END DESCRIPTION:
XS GIS Cut Line= 3
      2935001.92      6961438.04      2934858.69      6961122.92
      2934368.27      6961045.08
#Sta/Elev= 30
  4551.9  390.70  4581.7  388.45  4604.8  385.56  4643.1  382.09  4725.6  372.42
  4806.4  365.97  4846.4  362.91  4902.4  361.02  4916.8  359.36  4922.0  360.95
  4932.1  362.18  4972.7  362.97  4979.1  362.43  4984.2  360.81  4988.1  357.70
  4989.1  356.90  4996.8  356.90  4997.7  357.70  5003.0  361.73  5013.2  362.72
  5041.4  361.69  5071.5  365.97  5103.6  369.25  5114.4  371.29  5215.7  377.06
  5306.7  384.45  5337.2  386.46  5362.8  390.39  5377.7  391.22  5394.6  393.83
#Mann=4,-1,0
  4551.9    0.16       0  4988.1    0.07       0  4997.7    0.16       0
  5306.7    0.05       0
Bank Sta=4806.4,5071.5
Exp/Cntr=0.3,0.1

Type RM Length L Ch R = 1,19298,296,296,296
BEGIN DESCRIPTION:
PATTON CREEK 25.0
END DESCRIPTION:
XS GIS Cut Line= 3
      2935274.98      6961224.98      2934975.00      6960875.00
      2934625.02      6960575.02
#Sta/Elev= 30
  4553.9  385.93  4658.4  381.12  4696.0  378.46  4710.3  375.53  4716.9  375.69
  4752.0  370.76  4838.8  364.80  4880.4  363.12  4901.3  360.82  4929.8  359.89
  4972.6  361.53  4986.9  357.72  4988.6  356.05  4989.6  355.25  4997.3  355.25
  4998.2  356.05  5007.7  361.76  5011.6  360.81  5028.6  360.21  5071.4  360.56
  5079.1  361.42  5107.0  361.03  5147.2  364.80  5157.0  364.87  5171.3  367.53
  5206.4  371.00  5284.3  375.01  5369.5  384.32  5419.3  387.16  5475.8  387.26
#Mann=5,-1,0
  4553.9    0.05       0  4658.4    0.16       0  4988.6    0.07       0
  4998.2    0.16       0  5369.5    0.05       0
Bank Sta=4838.8,5147.2
Exp/Cntr=0.3,0.1

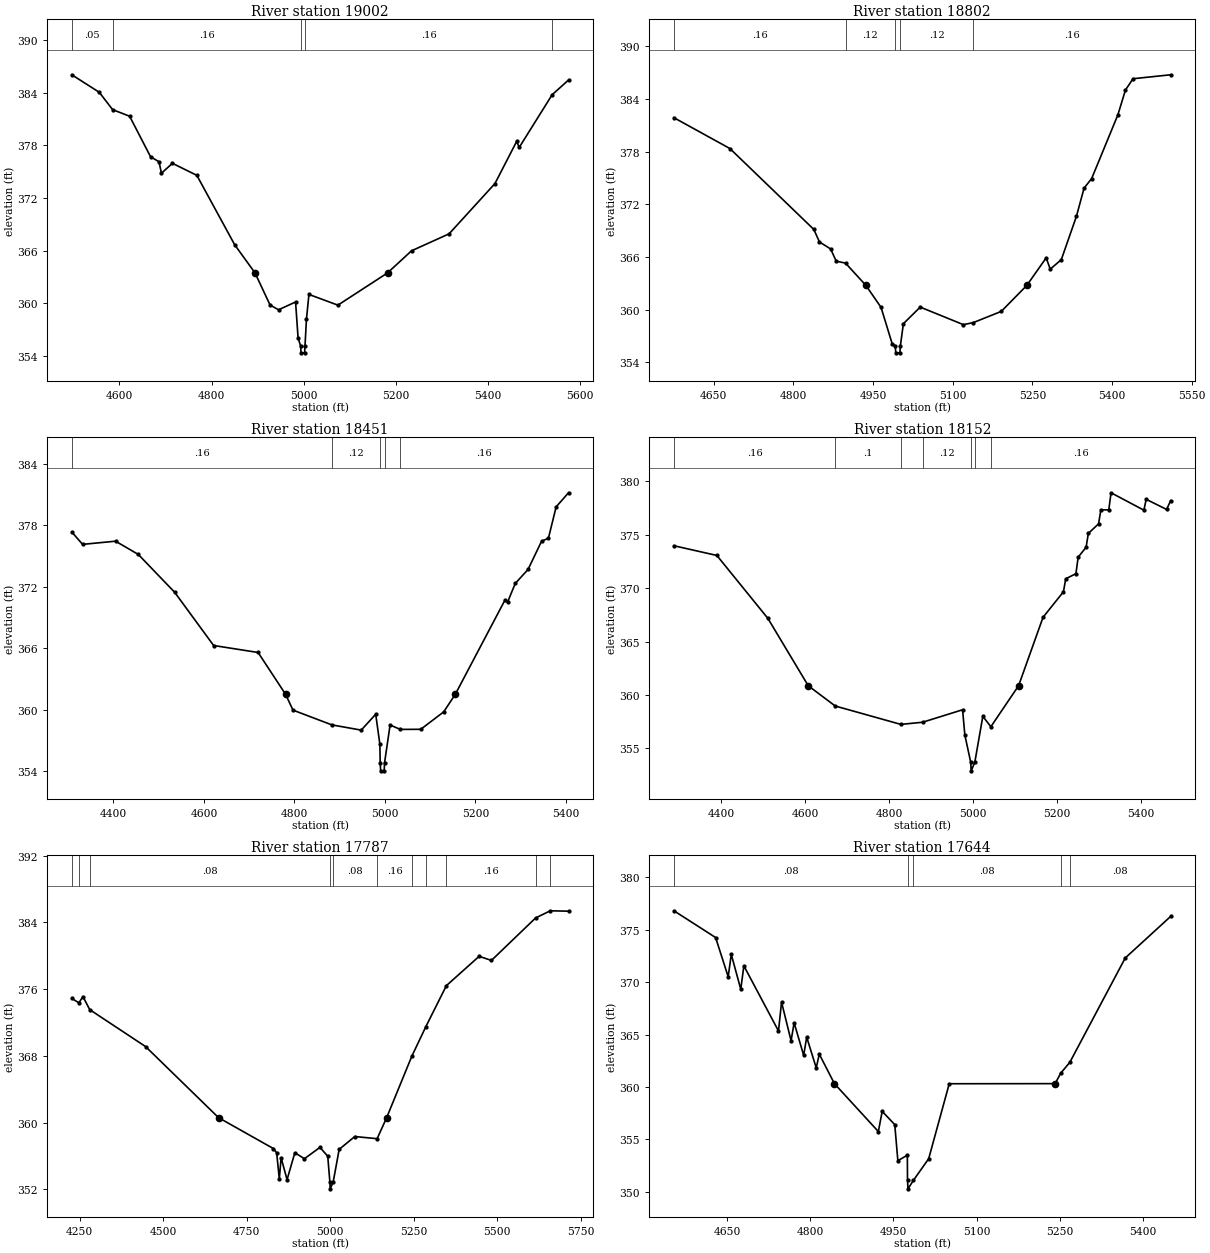
Type RM Length L Ch R = 1,19002,200,200,200
BEGIN DESCRIPTION:
Mapping XS d3d93c50
END DESCRIPTION:
XS GIS Cut Line= 3
      2935384.73      6961130.74      2935202.44      6960695.84
      2934645.12      6960456.24
#Sta/Elev= 30
  4496.6  386.03  4556.1  384.04  4585.2  382.06  4622.1  381.31  4667.5  376.70
  4685.8  376.13  4691.2  374.82  4715.0  375.95  4768.0  374.58  4850.2  366.67
  4894.3  363.47  4926.9  359.82  4945.3  359.27  4982.3  360.16  4987.8  356.05
  4993.2  355.17  4994.2  354.37  5001.9  354.37  5002.8  355.17  5005.9  358.17
  5011.3  361.02  5074.2  359.80  5181.9  363.47  5234.1  365.99  5315.6  367.92
  5415.2  373.65  5462.3  378.45  5467.8  377.76  5539.3  383.76  5574.8  385.43
#Mann=5,-1,0
  4496.6    0.05       0  4585.2    0.16       0  4993.2    0.07       0
  5002.8    0.16       0  5539.3    0.05       0
Bank Sta=4894.3,5181.9
Exp/Cntr=0.3,0.1

Type RM Length L Ch R = 1,18802,351,351,351
BEGIN DESCRIPTION:
PATTON CREEK 24.0
END DESCRIPTION:
XS GIS Cut Line= 3
      2935424.99      6960924.96      2935275.00      6960475.00
      2934924.99      6960174.99
#Sta/Elev= 30
  4575.1  381.85  4680.5  378.34  4838.6  369.12  4849.1  367.70  4870.2  366.90
  4880.7  365.51  4898.2  365.29  4936.6  362.75  4965.1  360.25  4986.2  356.08
  4991.9  355.87  4992.8  355.07  5000.6  355.07  5001.5  355.87  5007.2  358.39
  5038.9  360.28  5120.2  358.28  5139.1  358.52  5191.5  359.79  5239.6  362.75
  5276.1  365.89  5283.7  364.60  5304.6  365.69  5333.1  370.63  5347.4  373.83
  5361.7  374.92  5411.1  382.18  5425.3  385.00  5439.6  386.29  5510.4  386.74
#Mann=5,-1,0
  4575.1    0.16       0  4898.2    0.12       0  4991.9    0.07       0
  5001.5    0.12       0  5139.1    0.16       0
Bank Sta=4936.6,5239.6
Exp/Cntr=0.3,0.1

Type RM Length L Ch R = 1,18451,299,299,299
BEGIN DESCRIPTION:
Mapping XS 876c6073
END DESCRIPTION:
XS GIS Cut Line= 3
      2935522.75      6960891.11      2935455.04      6960245.32
      2935051.43      6960050.03
#Sta/Elev= 30
  4308.1  377.33  4331.9  376.13  4404.7  376.44  4455.0  375.15  4535.4  371.46
  4621.5  366.27  4719.8  365.59  4780.4  361.52  4796.9  359.97  4882.8  358.53
  4947.7  358.02  4979.7  359.57  4988.9  356.65  4989.6  354.85  4990.6  354.05
  4998.4  354.05  4999.3  354.85  5011.5  358.52  5033.9  358.09  5079.3  358.10
  5130.0  359.80  5155.7  361.52  5265.5  370.71  5271.1  370.49  5288.1  372.32
  5316.3  373.68  5346.3  376.44  5361.4  376.73  5378.5  379.79  5405.8  381.16
#Mann=5,-1,0
  4308.1    0.16       0  4882.8    0.12       0  4989.6    0.07       0
  4999.3    0.12       0  5033.9    0.16       0
Bank Sta=4780.4,5155.7
Exp/Cntr=0.3,0.1

Type RM Length L Ch R = 1,18152,365,365,365
BEGIN DESCRIPTION:
Mapping XS cbe3ea3d
END DESCRIPTION:
XS GIS Cut Line= 3
      2935882.13      6960667.21      2935673.79      6960039.59
      2935189.70      6959846.99
#Sta/Elev= 30
  4287.5  373.98  4389.7  373.07  4511.1  367.18  4607.2  360.87  4671.5  358.97
  4827.7  357.25  4879.3  357.45  4974.6  358.62  4980.0  356.25  4994.0  353.70
  4995.0  352.90  5003.7  353.70  5022.8  358.01  5041.9  357.03  5107.9  360.87
  5166.1  367.28  5214.7  369.67  5220.1  370.89  5244.4  371.36  5249.7  372.91
  5268.6  373.84  5274.0  375.14  5298.3  376.03  5303.7  377.34  5322.6  377.34
  5328.0  378.94  5406.2  377.31  5411.6  378.33  5460.2  377.38  5469.8  378.20
#Mann=7,-1,0
  4287.5    0.16       0  4671.5     0.1       0  4827.7    0.16       0
  4879.3    0.12       0  4994.0    0.07       0  5003.7    0.12       0
  5041.9    0.16       0
Bank Sta=4607.2,5107.9
Exp/Cntr=0.3,0.1

Type RM Length L Ch R = 1,17787,143,143,143
BEGIN DESCRIPTION:
double PATTON CREEK 23.0
END DESCRIPTION:
XS GIS Cut Line= 4
      2936650.31      6960234.22      2936191.96      6960017.20
      2935884.73      6959880.74      2935275.01      6959675.00
#Sta/Elev= 30
  4226.4  374.87  4247.6  374.35  4259.8  375.09  4280.0  373.53  4447.3  369.10
  4665.7  360.58  4829.7  356.88  4839.6  356.37  4847.5  353.23  4852.9  355.78
  4870.7  353.15  4894.0  356.38  4922.7  355.66  4969.2  357.02  4992.5  355.96
  4998.9  352.85  4999.8  352.05  5008.7  352.85  5026.7  356.78  5073.4  358.32
  5140.3  358.06  5168.8  360.58  5244.0  367.93  5285.9  371.47  5347.7  376.41
  5445.7  379.92  5482.5  379.43  5614.7  384.52  5658.8  385.38  5713.2  385.33
#Mann=11,-1,0
  4226.4    0.08       0  4247.6    0.05       0  4280.0    0.08       0
  4998.9    0.07       0  5008.7    0.08       0  5140.3    0.16       0
  5244.0    0.12       0  5285.9    0.08       0  5347.7    0.16       0
  5614.7    0.08       0  5658.8    0.16       0
Bank Sta=4665.7,5168.8
Exp/Cntr=0.3,0.1

Type RM Length L Ch R = 1,17644,309,309,309
BEGIN DESCRIPTION:
PATTON CREEK 22.0
END DESCRIPTION:
XS GIS Cut Line= 3
      2936467.98      6960062.33      2936075.00      6959875.00
      2935625.02      6959775.00
#Sta/Elev= 30
  4554.0  376.80  4629.2  374.25  4651.9  370.51  4657.5  372.64  4674.6  369.32
  4680.2  371.55  4742.7  365.34  4748.2  368.09  4765.4  364.41  4770.9  366.12
  4788.1  363.02  4793.6  364.75  4810.8  361.82  4816.3  363.13  4843.6  360.32
  4922.9  355.75  4929.8  357.68  4952.5  356.41  4958.1  352.97  4975.2  353.50
  4975.5  351.09  4976.4  350.29  4986.0  351.09  5013.7  353.16  5050.8  360.31
  5241.9  360.32  5251.9  361.31  5268.4  362.35  5368.4  372.30  5450.3  376.26
#Mann=5,-1,0
  4554.0    0.08       0  4975.5    0.07       0  4986.0    0.08       0
  5251.9    0.16       0  5268.4    0.08       0
Bank Sta=4843.6,5241.9
Exp/Cntr=0.3,0.1

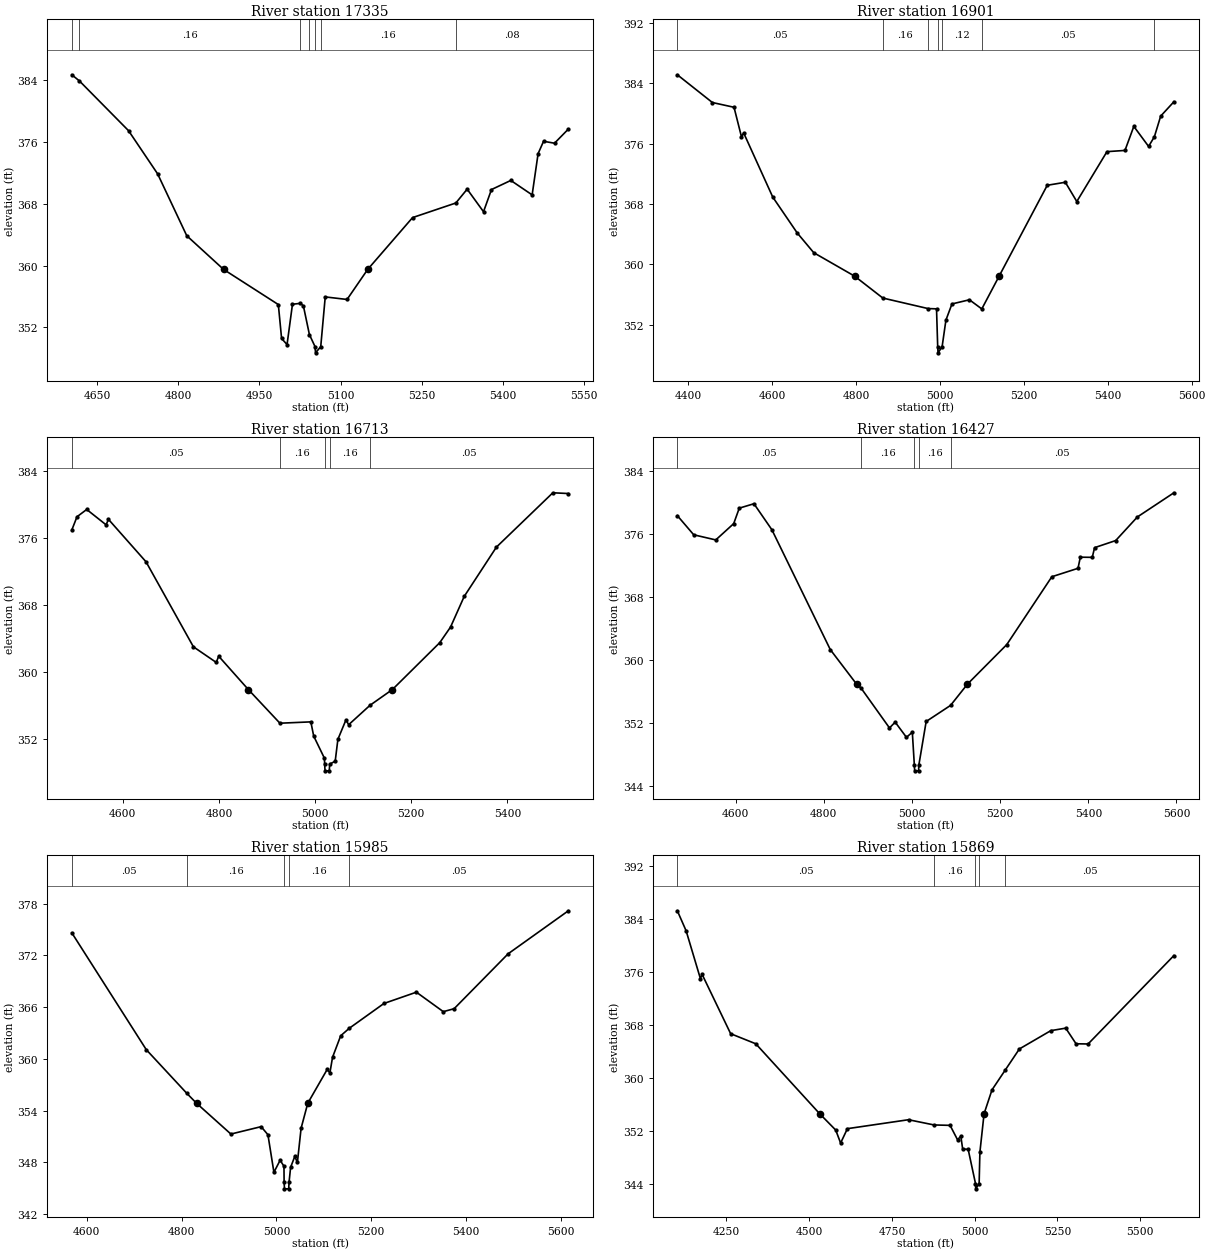
Type RM Length L Ch R = 1,17335,434,434,434
BEGIN DESCRIPTION:
Mapping XS 28333881
END DESCRIPTION:
XS GIS Cut Line= 3
      2936396.36      6959677.91      2936020.94      6959610.64
      2935489.58      6959677.87
#Sta/Elev= 30
  4603.7  384.70  4617.8  383.90  4708.5  377.46  4762.2  371.87  4816.0  363.86
  4884.0  359.50  4985.1  354.95  4991.1  350.56  5001.2  349.77  5011.2  354.99
  5026.0  355.11  5031.4  354.77  5042.5  351.06  5052.9  349.50  5053.8  348.70
  5063.4  349.50  5071.7  355.94  5112.0  355.61  5150.1  359.50  5233.0  366.21
  5312.9  368.10  5333.8  369.89  5364.0  366.97  5378.7  369.84  5414.4  371.02
  5453.8  369.15  5464.8  374.49  5474.9  376.09  5495.1  375.84  5520.7  377.67
#Mann=7,-1,0
  4603.7    0.05       0  4617.8    0.16       0  5026.0    0.12       0
  5042.5    0.16       0  5052.9    0.07       0  5063.4    0.16       0
  5312.9    0.08       0
Bank Sta=4884,5150.1
Exp/Cntr=0.3,0.1

Type RM Length L Ch R = 1,16901,188,188,188
BEGIN DESCRIPTION:
PATTON CREEK 21.0
END DESCRIPTION:
XS GIS Cut Line= 3
      2936374.98      6959524.99      2935825.00      6959275.00
      2935374.25      6959638.84
#Sta/Elev= 30
  4374.3  385.10  4457.8  381.43  4509.4  380.80  4527.0  376.93  4532.5  377.39
  4601.7  368.92  4659.9  364.18  4699.4  361.56  4797.0  358.45  4864.0  355.56
  4971.6  354.17  4992.0  354.13  4994.8  349.11  4995.6  348.31  5005.3  349.11
  5014.4  352.64  5028.8  354.78  5070.4  355.33  5099.9  354.12  5141.1  358.45
  5255.9  370.48  5299.0  370.88  5326.3  368.33  5398.2  374.93  5441.1  375.09
  5462.2  378.27  5497.4  375.62  5511.2  376.90  5526.2  379.63  5557.7  381.53
#Mann=7,-1,0
  4374.3    0.05       0  4864.0    0.16       0  4971.6    0.12       0
  4994.8    0.07       0  5005.3    0.12       0  5099.9    0.05       0
  5511.2    0.08       0
Bank Sta=4797,5141.1
Exp/Cntr=0.3,0.1

Type RM Length L Ch R = 1,16713,286,286,286
BEGIN DESCRIPTION:
Mapping XS de6be1b5
END DESCRIPTION:
XS GIS Cut Line= 3
      2936235.74      6959170.10      2935764.87      6959107.17
      2935265.74      6959356.73
#Sta/Elev= 30
  4493.8  376.97  4504.6  378.55  4524.8  379.42  4565.1  377.59  4570.1  378.24
  4648.2  373.18  4746.8  363.04  4794.3  361.18  4799.4  361.92  4861.0  357.95
  4926.8  353.93  4991.1  354.09  4997.1  352.39  5019.5  349.74  5019.8  349.05
  5020.7  348.25  5029.5  348.25  5030.3  349.05  5041.8  349.40  5047.4  352.01
  5064.2  354.33  5069.8  353.75  5114.3  356.07  5160.9  357.95  5259.4  363.54
  5281.8  365.40  5310.2  369.05  5377.2  374.93  5494.6  381.41  5526.9  381.32
#Mann=5,-1,0
  4493.8    0.05       0  4926.8    0.16       0  5019.8    0.07       0
  5030.3    0.16       0  5114.3    0.05       0
Bank Sta=4861,5160.9
Exp/Cntr=0.3,0.1

Type RM Length L Ch R = 1,16427,442,442,442
BEGIN DESCRIPTION:
Mapping XS 4968c59e
END DESCRIPTION:
XS GIS Cut Line= 3
      2936201.05      6958972.61      2935695.42      6958842.41
      2935119.10      6959024.41
#Sta/Elev= 30
  4467.6  378.32  4504.8  375.89  4554.8  375.24  4595.5  377.31  4608.1  379.27
  4641.4  379.83  4682.1  376.53  4814.6  361.33  4874.2  356.95  4884.6  356.43
  4948.9  351.39  4961.8  352.13  4987.4  350.20  5000.7  350.85  5005.2  346.75
  5006.0  345.95  5014.8  345.95  5015.7  346.75  5032.1  352.21  5087.4  354.25
  5125.8  356.95  5214.9  361.96  5317.2  370.57  5376.6  371.64  5381.8  373.05
  5408.9  373.03  5414.2  374.26  5462.1  375.16  5511.2  378.15  5594.1  381.22
#Mann=5,-1,0
  4467.6    0.05       0  4884.6    0.16       0  5005.2    0.07       0
  5015.7    0.16       0  5087.4    0.05       0
Bank Sta=4874.2,5125.8
Exp/Cntr=0.3,0.1

Type RM Length L Ch R = 1,15985,116,116,116
BEGIN DESCRIPTION:
PATTON CREEK 20.0
END DESCRIPTION:
XS GIS Cut Line= 3
      2936038.32      6958803.37      2935762.14      6958472.09
      2935204.99      6958733.89
#Sta/Elev= 30
  4568.7  374.63  4725.8  361.06  4811.3  355.99  4831.6  354.85  4904.1  351.27
  4967.9  352.13  4982.2  351.19  4994.8  346.83  5007.9  348.23  5016.0  347.53
  5016.3  345.71  5017.1  344.91  5025.9  344.91  5026.8  345.71  5030.0  347.41
  5038.8  348.67  5044.3  347.97  5052.1  351.94  5066.2  354.85  5107.2  358.78
  5112.8  358.36  5118.4  360.18  5135.6  362.68  5153.7  363.55  5226.8  366.43
  5295.2  367.74  5351.9  365.48  5374.7  365.82  5488.7  372.20  5615.6  377.19
#Mann=5,-1,0
  4568.7    0.05       0  4811.3    0.16       0  5016.3    0.07       0
  5026.8    0.16       0  5153.7    0.05       0
Bank Sta=4831.6,5066.2
Exp/Cntr=0.3,0.1

Type RM Length L Ch R = 1,15869,420,420,420
BEGIN DESCRIPTION:
PATTON CREEK 19.0
END DESCRIPTION:
XS GIS Cut Line= 3
      2935975.84      6957573.88      2935800.00      6958350.00
      2935175.04      6958674.98
#Sta/Elev= 30
  4101.8  385.29  4128.4  382.26  4171.5  375.05  4176.7  375.69  4262.9  366.74
  4338.8  365.22  4531.9  354.66  4580.3  352.20  4595.1  350.24  4615.6  352.41
  4800.2  353.76  4877.4  352.97  4925.8  352.91  4948.3  350.74  4958.3  351.27
  4963.9  349.32  4980.4  349.30  5002.6  344.13  5003.4  343.33  5013.6  344.13
  5015.9  348.86  5028.5  354.66  5052.4  358.26  5093.2  361.31  5135.2  364.44
  5230.1  367.20  5275.2  367.58  5306.4  365.22  5342.8  365.19  5602.0  378.53
#Mann=5,-1,0
  4101.8    0.05       0  4877.4    0.16       0  5002.6    0.07       0
  5013.6    0.16       0  5093.2    0.05       0
Bank Sta=4531.9,5028.5
Exp/Cntr=0.3,0.1

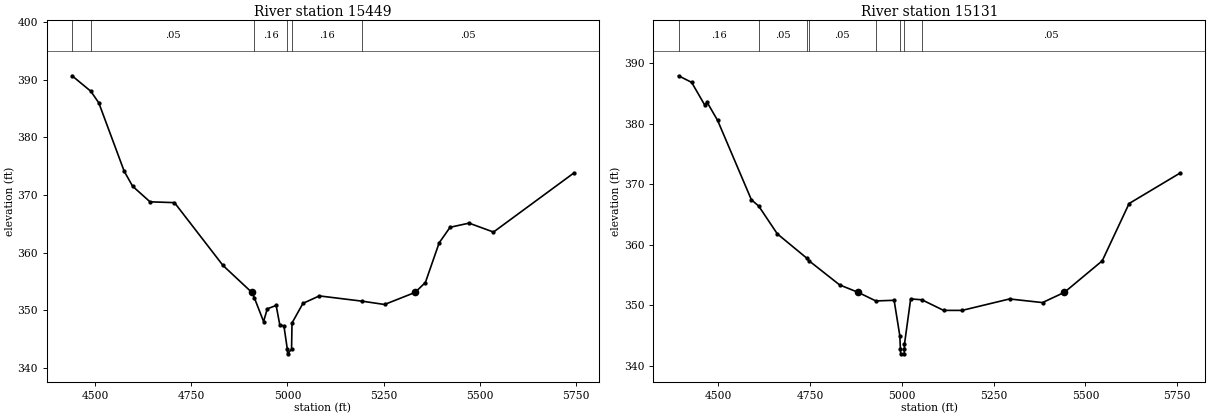
Type RM Length L Ch R = 1,15449,318,318,318
BEGIN DESCRIPTION:
Mapping XS 27e04031
END DESCRIPTION:
XS GIS Cut Line= 3
      2935932.46      6957521.74      2935706.75      6958016.57
      2935199.48      6958584.54
#Sta/Elev= 30
  4439.6  390.70  4488.4  388.01  4509.1  386.00  4575.1  374.14  4597.1  371.52
  4642.4  368.81  4706.0  368.67  4832.2  357.76  4907.4  353.07  4914.1  352.09
  4937.8  348.02  4947.4  350.22  4970.5  350.82  4979.9  347.47  4990.8  347.23
  4999.6  343.21  5000.3  342.41  5010.6  343.21  5011.8  347.77  5040.2  351.17
  5082.8  352.47  5193.8  351.56  5252.5  350.98  5331.7  353.07  5358.7  354.79
  5394.6  361.69  5423.0  364.39  5472.4  365.11  5535.9  363.56  5745.0  373.82
#Mann=6,-1,0
  4439.6    0.16       0  4488.4    0.05       0  4914.1    0.16       0
  4999.6    0.07       0  5010.6    0.16       0  5193.8    0.05       0
Bank Sta=4907.4,5331.7
Exp/Cntr=0.3,0.1

Type RM Length L Ch R = 1,15131,382,382,382
BEGIN DESCRIPTION:
Mapping XS 994984cd
END DESCRIPTION:
XS GIS Cut Line= 3
      2935919.41      6957408.94      2935498.41      6957825.60
      2935155.53      6958520.05
#Sta/Elev= 30
  4391.5  387.90  4427.2  386.81  4462.5  383.10  4469.6  383.49  4497.9  380.53
  4589.8  367.43  4610.1  366.35  4660.5  361.78  4741.6  357.72  4746.0  357.37
  4830.3  353.34  4880.8  352.11  4929.0  350.69  4978.7  350.80  4994.3  344.92
  4995.8  342.75  4996.6  341.95  5006.1  341.95  5006.8  342.75  5006.9  343.52
  5023.8  351.03  5054.4  350.88  5113.6  349.13  5164.0  349.13  5293.1  351.02
  5382.9  350.42  5442.5  352.11  5545.6  357.32  5618.8  366.79  5758.3  371.85
#Mann=8,-1,0
  4391.5    0.16       0  4610.1    0.05       0  4741.6    0.12       0
  4746.0    0.05       0  4929.0    0.16       0  4995.8    0.07       0
  5006.8    0.16       0  5054.4    0.05       0
Bank Sta=4880.8,5442.5
Exp/Cntr=0.3,0.1