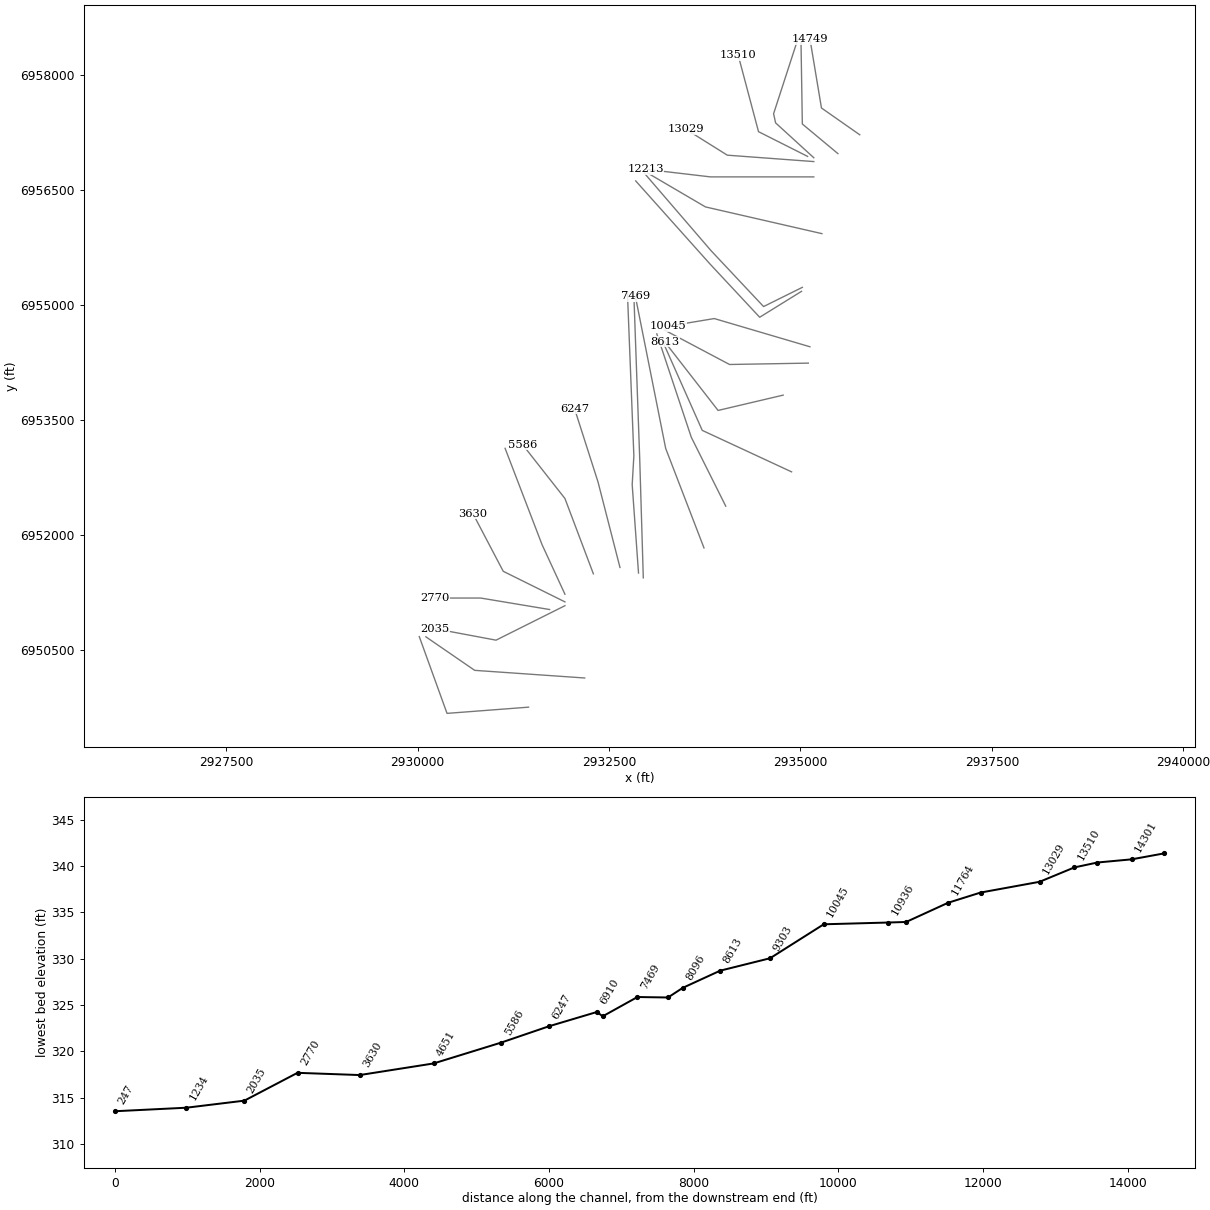
HEC-RAS study PATTON CREEK.prj: PATTON CREEK Base Level Engineering

--- PATTON CREEK.g01 (geometry) --- (continued)

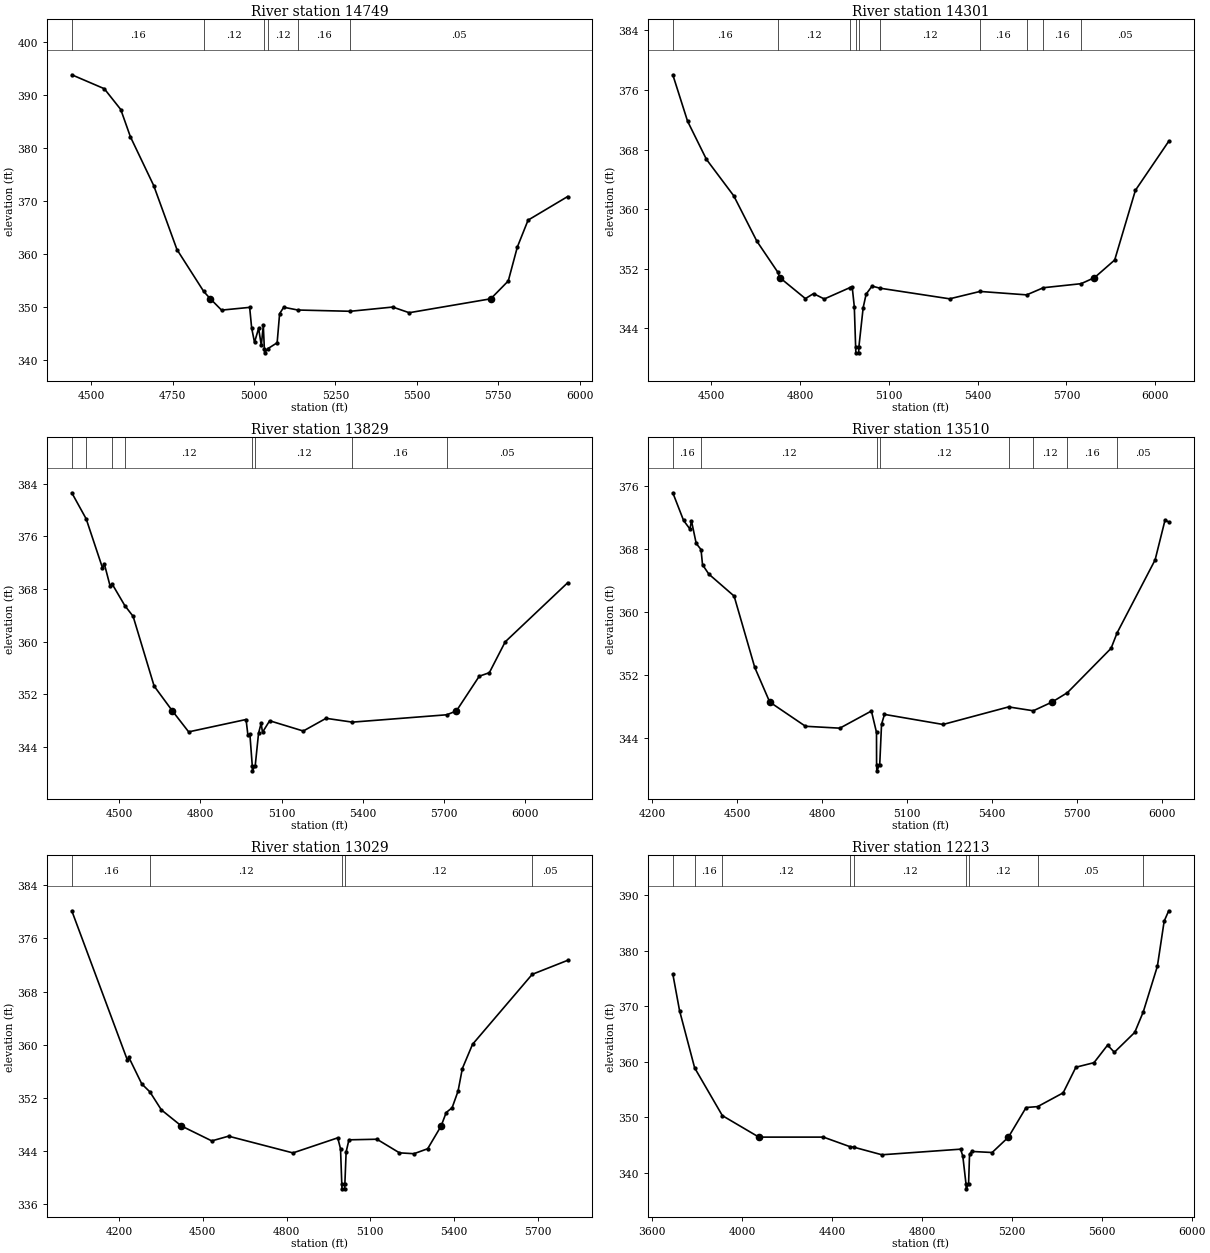
Type RM Length L Ch R = 1,14749,448,448,448
BEGIN DESCRIPTION:
PATTON CREEK 18.0
END DESCRIPTION:
XS GIS Cut Line= 3
      2935774.99      6957225.00      2935275.00      6957575.00
      2935125.01      6958474.97
#Sta/Elev= 30
  4440.3  393.88  4540.1  391.25  4590.7  387.32  4620.3  382.17  4691.8  372.96
  4763.3  360.86  4845.5  352.94  4865.8  351.56  4900.2  349.42  4986.5  349.94
  4992.6  346.07  5001.4  343.33  5014.0  345.98  5022.3  342.76  5028.4  346.55
  5031.6  342.15  5032.4  341.35  5042.6  342.15  5070.9  343.25  5078.5  348.76
  5091.2  349.96  5134.3  349.44  5295.5  349.20  5425.7  350.00  5476.4  348.93
  5726.8  351.56  5780.6  354.93  5808.4  361.33  5841.4  366.42  5963.0  370.88
#Mann=6,-1,0
  4440.3    0.16       0  4845.5    0.12       0  5031.6    0.07       0
  5042.6    0.12       0  5134.3    0.16       0  5295.5    0.05       0
Bank Sta=4865.8,5726.8
Exp/Cntr=0.3,0.1

Type RM Length L Ch R = 1,14301,472,472,472
BEGIN DESCRIPTION:
Mapping XS 7121511f
END DESCRIPTION:
XS GIS Cut Line= 3
      2935489.70      6956979.27      2935025.32      6957365.53
      2935007.96      6958437.56
#Sta/Elev= 30
  4369.3  378.03  4419.1  371.81  4482.9  366.68  4575.4  361.78  4653.5  355.69
  4724.1  351.54  4731.1  350.80  4817.5  347.99  4844.9  348.66  4881.3  347.94
  4968.4  349.47  4975.6  349.58  4982.8  346.89  4987.3  341.51  4988.0  340.71
  4997.5  340.71  4998.3  341.51  5012.8  346.79  5022.8  348.59  5042.8  349.67
  5069.0  349.39  5305.0  347.96  5407.7  348.95  5565.4  348.49  5621.9  349.45
  5749.3  349.99  5794.6  350.80  5862.9  353.17  5932.9  362.52  6045.5  369.10
#Mann=10,-1,0
  4369.3    0.16       0  4724.1    0.12       0  4968.4    0.16       0
  4987.3    0.07       0  4998.3    0.16       0  5069.0    0.12       0
  5407.7    0.16       0  5565.4    0.12       0  5621.9    0.16       0
  5749.3    0.05       0
Bank Sta=4731.1,5794.6
Exp/Cntr=0.3,0.1

Type RM Length L Ch R = 1,13829,319,319,319
BEGIN DESCRIPTION:
PATTON CREEK 17.0
END DESCRIPTION:
XS GIS Cut Line= 4
      2935175.01      6956924.99      2934676.11      6957380.40
      2934650.00      6957500.00      2934969.77      6958484.45
#Sta/Elev= 30
  4324.5  382.62  4377.8  378.65  4437.7  371.25  4445.1  371.78  4466.1  368.46
  4473.7  368.76  4520.5  365.48  4551.2  363.85  4628.9  353.25  4696.3  349.48
  4756.6  346.29  4968.7  348.17  4975.5  345.82  4982.9  345.91  4991.6  341.17
  4992.3  340.37  5002.6  341.17  5014.9  346.09  5024.4  347.58  5029.5  346.23
  5055.9  347.98  5180.2  346.42  5264.4  348.35  5361.5  347.77  5711.0  348.89
  5746.3  349.48  5830.7  354.75  5867.9  355.28  5926.6  359.97  6157.5  368.95
#Mann=8,-1,0
  4324.5    0.16       0  4377.8    0.12       0  4473.7    0.16       0
  4520.5    0.12       0  4991.6    0.07       0  5002.6    0.12       0
  5361.5    0.16       0  5711.0    0.05       0
Bank Sta=4696.3,5746.3
Exp/Cntr=0.3,0.1

Type RM Length L Ch R = 1,13510,481,481,481
BEGIN DESCRIPTION:
Mapping XS 5bbde344
END DESCRIPTION:
XS GIS Cut Line= 3
      2935093.64      6956942.66      2934453.02      6957265.57
      2934187.39      6958265.59
#Sta/Elev= 30
  4272.6  375.16  4310.7  371.64  4333.0  370.56  4338.6  371.59  4355.3  368.72
  4372.3  367.95  4377.6  366.02  4399.9  364.83  4489.2  362.04  4562.2  352.97
  4615.0  348.58  4741.4  345.50  4862.8  345.26  4974.3  347.44  4992.3  344.72
  4992.6  340.64  4993.4  339.84  5003.7  340.64  5010.1  345.75  5020.4  347.01
  5227.4  345.73  5459.0  347.96  5546.2  347.47  5612.8  348.58  5666.8  349.77
  5821.0  355.40  5842.6  357.38  5976.6  366.63  6011.5  371.66  6024.7  371.47
#Mann=8,-1,0
  4272.6    0.16       0  4372.3    0.12       0  4992.6    0.07       0
  5003.7    0.12       0  5459.0    0.16       0  5546.2    0.12       0
  5666.8    0.16       0  5842.6    0.05       0
Bank Sta=4615,5612.8
Exp/Cntr=0.3,0.1

Type RM Length L Ch R = 1,13029,816,816,816
BEGIN DESCRIPTION:
double PATTON CREEK 16.0
END DESCRIPTION:
XS GIS Cut Line= 3
      2935175.02      6956875.00      2934045.65      6956958.51
      2933499.96      6957300.03
#Sta/Elev= 30
  4030.7  380.16  4230.2  357.64  4235.2  358.08  4281.4  354.09  4310.5  352.89
  4351.6  350.18  4423.2  347.76  4532.1  345.51  4592.2  346.22  4822.9  343.70
  4983.3  345.97  4993.3  344.32  4997.8  339.09  4998.6  338.29  5008.2  338.29
  5008.9  339.09  5013.4  343.85  5023.4  345.67  5123.7  345.76  5204.4  343.71
  5256.3  343.58  5305.5  344.33  5353.7  347.76  5371.8  349.78  5393.1  350.51
  5414.3  353.01  5429.6  356.40  5466.1  360.05  5679.9  370.59  5806.9  372.70
#Mann=5,-1,0
  4030.7    0.16       0  4310.5    0.12       0  4997.8    0.07       0
  5008.9    0.12       0  5679.9    0.05       0
Bank Sta=4423.2,5353.7
Exp/Cntr=0.3,0.1

Type RM Length L Ch R = 1,12213,449,449,449
BEGIN DESCRIPTION:
PATTON CREEK 15.0
END DESCRIPTION:
XS GIS Cut Line= 3
      2935175.01      6956675.00      2933825.00      6956675.00
      2932974.98      6956775.00
#Sta/Elev= 30
  3692.0  375.81  3722.0  369.21  3789.1  358.91  3912.4  350.31  4074.9  346.44
  4362.0  346.44  4478.0  344.75  4499.7  344.60  4622.0  343.26  4972.0  344.27
  4982.0  343.03  4996.4  337.93  4997.1  337.13  5007.6  337.93  5012.0  343.35
  5022.0  343.86  5112.5  343.67  5185.0  346.44  5263.5  351.77  5314.9  351.93
  5428.4  354.41  5485.0  359.02  5565.6  359.84  5626.0  363.00  5656.2  361.71
  5746.8  365.29  5784.7  368.98  5847.5  377.19  5877.7  385.31  5897.9  387.18
#Mann=9,-1,0
  3692.0    0.12       0  3789.1    0.16       0  3912.4    0.12       0
  4478.0    0.05       0  4499.7    0.12       0  4996.4    0.07       0
  5007.6    0.12       0  5314.9    0.05       0  5784.7    0.12       0
Bank Sta=4074.9,5185
Exp/Cntr=0.3,0.1

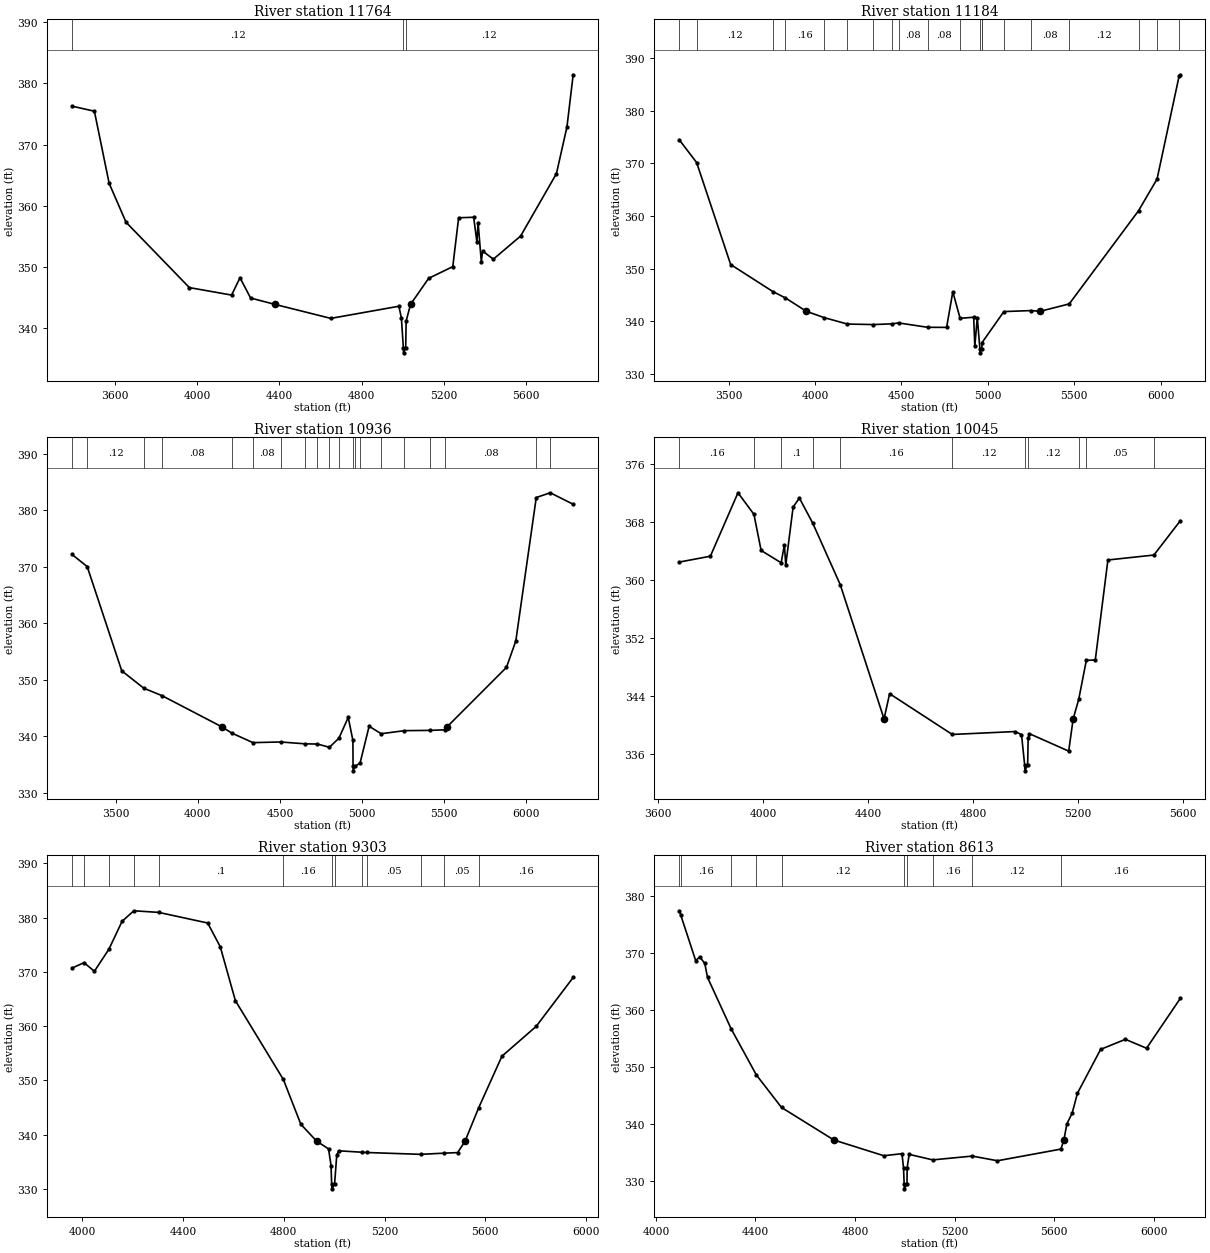
Type RM Length L Ch R = 1,11764,580,580,580
BEGIN DESCRIPTION:
Mapping XS e9644874
END DESCRIPTION:
XS GIS Cut Line= 3
      2935280.82      6955933.97      2933759.96      6956282.93
      2933004.74      6956725.65
#Sta/Elev= 30
  3392.0  376.26  3500.6  375.44  3572.4  363.67  3654.5  357.33  3962.3  346.67
  4167.5  345.45  4208.5  348.28  4259.8  344.97  4377.3  343.94  4649.7  341.65
  4980.8  343.63  4992.9  341.70  5002.5  336.83  5003.2  336.03  5013.7  336.83
  5016.1  341.23  5037.4  343.94  5125.4  348.18  5242.7  350.09  5271.1  358.06
  5344.2  358.14  5359.9  354.12  5365.7  357.28  5381.4  350.85  5387.2  352.64
  5440.0  351.31  5572.5  355.08  5746.4  365.25  5797.7  372.89  5827.8  381.38
#Mann=3,-1,0
  3392.0    0.12       0  5002.5    0.07       0  5013.7    0.12       0
Bank Sta=4377.3,5037.4
Exp/Cntr=0.3,0.1

Type RM Length L Ch R = 1,11184,248,248,248
BEGIN DESCRIPTION:
Mapping XS fe88dada
END DESCRIPTION:
XS GIS Cut Line= 4
      2935025.61      6955232.60      2934518.97      6954981.58
      2933832.88      6955711.75      2932964.05      6956721.05
#Sta/Elev= 30
  3214.9  374.50  3315.6  370.17  3512.5  350.76  3757.2  345.61  3829.6  344.40
  3950.0  341.87  4053.5  340.66  4187.5  339.44  4335.7  339.34  4447.8  339.48
  4484.0  339.65  4652.3  338.82  4761.7  338.80  4797.6  345.58  4839.8  340.53
  4918.3  340.73  4924.9  335.17  4939.1  340.68  4954.3  334.76  4955.0  333.96
  4965.6  334.76  4966.4  335.89  5093.0  341.81  5248.3  342.00  5304.0  341.87
  5471.1  343.27  5872.1  361.00  5979.2  367.03  6106.4  386.57  6114.0  386.87
#Mann=20,-1,0
  3214.9    0.16       0  3315.6    0.12       0  3757.2    0.08       0
  3829.6    0.16       0  4053.5    0.16       0  4187.5    0.16       0
  4335.7    0.08       0  4447.8    0.16       0  4484.0    0.08       0
  4652.3    0.08       0  4839.8    0.16       0  4954.3    0.07       0
  4965.6    0.08       0  4966.4    0.16       0  5093.0    0.16       0
  5248.3    0.08       0  5471.1    0.12       0  5872.1    0.05       0
  5979.2    0.12       0  6106.4    0.08       0
Bank Sta=3950,5304
Exp/Cntr=0.3,0.1

Type RM Length L Ch R = 1,10936,891,891,891
BEGIN DESCRIPTION:
Mapping XS fa4599b2
END DESCRIPTION:
XS GIS Cut Line= 4
      2935015.18      6955180.51      2934468.30      6954841.96
      2933817.26      6955539.88      2932849.26      6956622.37
#Sta/Elev= 30
  3234.2  372.19  3326.5  370.05  3536.7  351.60  3671.0  348.52  3782.1  347.20
  4145.3  341.70  4205.2  340.60  4335.0  338.89  4502.9  339.01  4651.7  338.68
  4728.0  338.64  4800.6  338.07  4858.5  339.68  4915.1  343.36  4943.5  339.28
  4944.6  334.70  4945.3  333.90  4955.9  334.70  4987.1  335.27  5042.2  341.79
  5115.7  340.47  5257.3  341.01  5409.7  341.06  5501.5  341.16  5517.0  341.70
  5878.1  352.21  5934.9  356.88  6059.4  382.27  6144.6  383.11  6284.0  381.08
#Mann=20,-1,0
  3234.2    0.16       0  3326.5    0.12       0  3671.0    0.16       0
  3782.1    0.08       0  4205.2    0.05       0  4335.0    0.08       0
  4502.9    0.12       0  4651.7    0.12       0  4728.0    0.08       0
  4800.6    0.12       0  4858.5    0.05       0  4944.6    0.04       0
  4955.9    0.05       0  4987.1    0.05       0  5115.7    0.05       0
  5257.3    0.05       0  5409.7    0.16       0  5501.5    0.08       0
  6059.4    0.05       0  6144.6    0.08       0
Bank Sta=4145.3,5517
Exp/Cntr=0.3,0.1

Type RM Length L Ch R = 1,10045,742,742,742
BEGIN DESCRIPTION:
PATTON CREEK 12.0
END DESCRIPTION:
XS GIS Cut Line= 3
      2935124.52      6954456.55      2933875.00      6954825.00
      2933274.99      6954725.00
#Sta/Elev= 30
  3680.2  362.51  3799.0  363.32  3904.2  372.07  3965.0  369.10  3992.5  364.11
  4068.9  362.41  4081.2  364.90  4086.4  362.10  4114.5  370.10  4138.4  371.34
  4189.3  367.88  4294.0  359.41  4461.2  340.88  4482.5  344.35  4721.3  338.73
  4961.0  339.13  4985.4  338.71  4997.5  334.51  4998.2  333.71  5008.8  334.51
  5010.8  338.27  5015.9  338.83  5165.4  336.43  5182.4  340.88  5203.6  343.56
  5232.6  348.95  5266.8  349.01  5314.9  362.80  5490.3  363.48  5591.2  368.22
#Mann=11,-1,0
  3680.2    0.16       0  3965.0    0.08       0  4068.9     0.1       0
  4189.3    0.08       0  4294.0    0.16       0  4721.3    0.12       0
  4997.5    0.07       0  5008.8    0.12       0  5203.6    0.16       0
  5232.6    0.05       0  5490.3    0.16       0
Bank Sta=4461.2,5182.4
Exp/Cntr=0.3,0.1

Type RM Length L Ch R = 1,9303,690,690,690
BEGIN DESCRIPTION:
PATTON CREEK 11.0
END DESCRIPTION:
XS GIS Cut Line= 3
      2935103.76      6954243.00      2934075.00      6954225.00
      2933224.99      6954675.01
#Sta/Elev= 30
  3958.7  370.69  4006.2  371.69  4047.5  370.10  4105.2  374.17  4157.5  379.30
  4204.2  381.24  4303.2  380.94  4497.5  378.99  4547.6  374.61  4607.6  364.69
  4798.2  350.18  4867.6  341.94  4930.4  338.83  4977.6  337.41  4987.6  334.33
  4990.1  330.85  4990.7  330.05  5001.5  330.85  5010.2  336.21  5017.8  337.05
  5110.9  336.79  5128.7  336.74  5343.6  336.40  5437.5  336.62  5490.5  336.72
  5520.0  338.83  5574.0  344.97  5666.5  354.47  5802.3  359.95  5949.4  368.96
#Mann=13,-1,0
  3958.7    0.08       0  4006.2    0.05       0  4105.2    0.08       0
  4204.2    0.15       0  4303.2     0.1       0  4798.2    0.16       0
  4990.1    0.07       0  5001.5    0.16       0  5110.9    0.16       0
  5128.7    0.05       0  5343.6    0.16       0  5437.5    0.05       0
  5574.0    0.16       0
Bank Sta=4930.4,5520
Exp/Cntr=0.3,0.1

Type RM Length L Ch R = 1,8613,517,517,517
BEGIN DESCRIPTION:
PATTON CREEK 10.0
END DESCRIPTION:
XS GIS Cut Line= 3
      2934774.97      6953824.99      2933925.00      6953625.00
      2933224.97      6954525.03
#Sta/Elev= 30
  4093.8  377.42  4100.1  376.65  4159.9  368.68  4176.0  369.34  4196.5  368.20
  4207.4  365.75  4302.5  356.73  4403.6  348.67  4504.8  342.96  4714.9  337.27
  4915.6  334.51  4988.7  334.87  4995.0  332.34  4997.5  329.51  4998.1  328.71
  5008.9  329.51  5009.5  332.42  5017.7  334.75  5112.1  333.78  5271.0  334.45
  5372.4  333.63  5627.2  335.67  5639.3  337.27  5651.1  340.07  5672.8  342.01
  5693.6  345.45  5786.8  353.14  5886.4  354.90  5971.4  353.34  6107.2  362.08
#Mann=10,-1,0
  4093.8     0.1       0  4100.1    0.16       0  4302.5    0.12       0
  4403.6    0.16       0  4504.8    0.12       0  4997.5    0.07       0
  5008.9    0.12       0  5112.1    0.16       0  5271.0    0.12       0
  5627.2    0.16       0
Bank Sta=4714.9,5639.3
Exp/Cntr=0.3,0.1

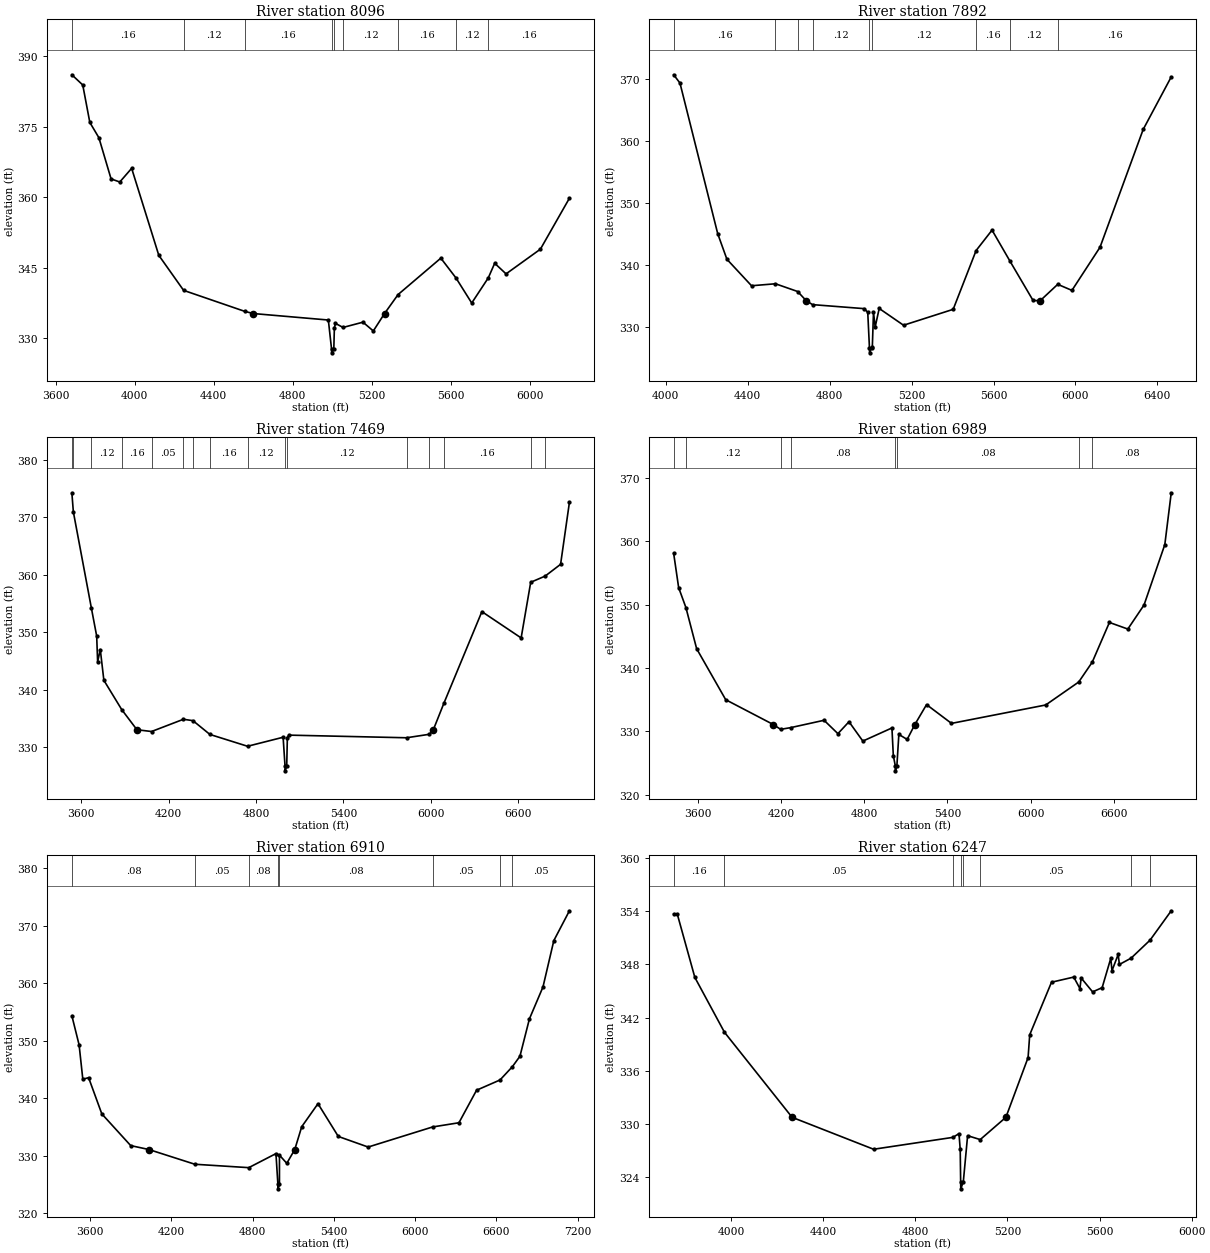
Type RM Length L Ch R = 1,8096,204,204,204
BEGIN DESCRIPTION:
Mapping XS 3478c13b
END DESCRIPTION:
XS GIS Cut Line= 3
      2934884.94      6952822.88      2933718.30      6953364.53
      2933218.28      6954489.57
#Sta/Elev= 30
  3682.4  386.09  3737.5  383.92  3773.3  375.94  3819.1  372.69  3880.8  363.91
  3924.9  363.25  3984.9  366.16  4122.3  347.63  4247.7  340.17  4556.8  335.70
  4600.2  335.23  4980.1  333.85  4996.3  327.66  4996.9  326.86  5007.7  327.66
  5010.6  332.18  5016.1  333.13  5054.4  332.27  5155.2  333.39  5207.6  331.52
  5264.3  335.23  5333.0  339.28  5549.2  347.03  5625.7  342.82  5705.5  337.47
  5789.3  342.83  5821.7  345.94  5879.2  343.68  6052.9  348.94  6199.8  359.80
#Mann=9,-1,0
  3682.4    0.16       0  4247.7    0.12       0  4556.8    0.16       0
  4996.3    0.07       0  5007.7    0.16       0  5054.4    0.12       0
  5333.0    0.16       0  5625.7    0.12       0  5789.3    0.16       0
Bank Sta=4600.2,5264.3
Exp/Cntr=0.3,0.1

Type RM Length L Ch R = 1,7892,423,423,423
BEGIN DESCRIPTION:
PATTON CREEK 9.0
END DESCRIPTION:
XS GIS Cut Line= 3
      2934024.99      6952375.02      2933575.00      6953275.00
      2933125.01      6954624.97
#Sta/Elev= 30
  4038.4  370.75  4069.1  369.41  4253.6  345.05  4298.3  340.94  4418.5  336.66
  4535.4  336.98  4643.6  335.73  4685.7  334.24  4716.4  333.61  4969.1  332.96
  4985.9  332.35  4994.2  326.62  4994.8  325.82  5005.6  326.62  5008.3  326.82
  5013.9  332.36  5022.2  330.01  5041.8  332.99  5160.6  330.28  5403.0  332.85
  5514.9  342.35  5592.7  345.65  5680.5  340.62  5793.0  334.28  5827.6  334.24
  5913.4  336.89  5982.7  335.91  6119.8  342.88  6330.6  361.92  6467.6  370.41
#Mann=9,-1,0
  4038.4    0.16       0  4535.4    0.12       0  4643.6    0.16       0
  4716.4    0.12       0  4994.2    0.07       0  5005.6    0.12       0
  5514.9    0.16       0  5680.5    0.12       0  5913.4    0.16       0
Bank Sta=4685.7,5827.6
Exp/Cntr=0.3,0.1

Type RM Length L Ch R = 1,7469,480,480,480
BEGIN DESCRIPTION:
Mapping XS 3b65aaea
END DESCRIPTION:
XS GIS Cut Line= 3
      2933740.87      6951829.80      2933240.87      6953128.42
      2932845.04      6955114.51
#Sta/Elev= 30
  3534.8  374.30  3545.1  370.97  3669.3  354.16  3705.3  349.34  3711.8  344.85
  3730.0  347.00  3754.6  341.64  3877.4  336.53  3981.6  333.03  4082.2  332.72
  4300.9  334.85  4366.3  334.61  4482.7  332.21  4741.3  330.15  4985.5  331.72
  4998.7  326.67  4999.3  325.87  5010.2  326.67  5014.6  331.67  5024.8  332.09
  5832.9  331.63  5990.3  332.24  6017.0  333.03  6089.6  337.65  6350.4  353.60
  6619.9  349.02  6685.6  358.71  6784.9  359.79  6890.8  361.84  6951.5  372.64
#Mann=16,-1,0
  3534.8     0.1       0  3545.1    0.16       0  3669.3    0.12       0
  3877.4    0.16       0  4082.2    0.05       0  4300.9    0.08       0
  4366.3    0.05       0  4482.7    0.16       0  4741.3    0.12       0
  4998.7    0.07       0  5010.2    0.12       0  5832.9    0.05       0
  5990.3     0.1       0  6089.6    0.16       0  6685.6    0.05       0
  6784.9    0.08       0
Bank Sta=3981.6,6017
Exp/Cntr=0.3,0.1

Type RM Length L Ch R = 1,6989,79,79,79
BEGIN DESCRIPTION:
Mapping XS dcd21527
END DESCRIPTION:
XS GIS Cut Line= 3
      2932948.44      6951439.14      2932901.57      6952996.42
      2932828.70      6955031.43
#Sta/Elev= 30
  3422.3  358.05  3458.2  352.67  3510.6  349.53  3588.2  343.04  3798.3  335.00
  4141.9  331.09  4195.1  330.33  4267.4  330.60  4508.6  331.76  4608.7  329.65
  4688.7  331.53  4788.8  328.48  4998.9  330.55  5008.9  326.20  5023.2  324.59
  5023.9  323.79  5034.7  324.59  5048.9  329.53  5108.9  328.74  5164.5  331.09
  5249.0  334.23  5429.2  331.27  6109.6  334.17  6348.1  337.79  6445.9  340.92
  6569.9  347.18  6702.9  346.14  6820.0  349.93  6970.1  359.45  7016.6  367.62
#Mann=8,-1,0
  3422.3    0.16       0  3510.6    0.12       0  4195.1    0.16       0
  4267.4    0.08       0  5023.2    0.07       0  5034.7    0.08       0
  6348.1     0.1       0  6445.9    0.08       0
Bank Sta=4141.9,5164.5
Exp/Cntr=0.3,0.1

Type RM Length L Ch R = 1,6910,663,663,663
BEGIN DESCRIPTION:
PATTON CREEK 8.0
END DESCRIPTION:
XS GIS Cut Line= 4
      2932885.94      6951501.64      2932803.37      6952656.20
      2932825.18      6953031.95      2932740.87      6955170.09
#Sta/Elev= 30
  3466.1  354.33  3519.6  349.27  3547.0  343.30  3589.8  343.57  3687.3  337.28
  3900.6  331.77  4034.7  331.09  4374.5  328.53  4772.2  327.94  4973.0  330.38
  4987.3  325.06  4987.9  324.26  4998.8  325.06  4999.0  330.11  5053.1  328.69
  5111.9  331.09  5163.2  335.05  5283.3  339.05  5433.4  333.36  5653.6  331.52
  6129.8  335.01  6324.1  335.74  6454.2  341.39  6627.3  343.17  6718.3  345.47
  6774.4  347.29  6844.5  353.79  6944.6  359.33  7024.6  367.38  7139.8  372.56
#Mann=8,-1,0
  3466.1    0.08       0  4374.5    0.05       0  4772.2    0.08       0
  4987.3    0.07       0  4998.8    0.08       0  6129.8    0.05       0
  6627.3    0.16       0  6718.3    0.05       0
Bank Sta=4034.7,5111.9
Exp/Cntr=0.3,0.1

Type RM Length L Ch R = 1,6247,661,661,661
BEGIN DESCRIPTION:
PATTON CREEK 7.0
END DESCRIPTION:
XS GIS Cut Line= 3
      2932643.76      6951574.51      2932357.29      6952689.99
      2932049.99      6953650.03
#Sta/Elev= 30
  3751.7  353.70  3767.3  353.68  3843.6  346.54  3972.2  340.36  4265.7  330.78
  4619.5  327.18  4963.8  328.52  4990.1  328.94  4995.4  327.16  4997.3  323.52
  4997.9  322.72  5008.9  323.52  5027.5  328.71  5082.2  328.27  5193.7  330.78
  5290.0  337.51  5297.1  340.08  5391.7  346.00  5488.2  346.58  5515.1  345.28
  5520.3  346.48  5570.1  344.91  5611.5  345.39  5648.9  348.69  5654.2  347.30
  5681.1  349.13  5686.3  348.00  5737.0  348.71  5819.4  350.74  5911.4  354.05
#Mann=8,-1,0
  3751.7    0.16       0  3972.2    0.05       0  4963.8    0.16       0
  4997.3    0.07       0  5008.9    0.16       0  5082.2    0.05       0
  5737.0    0.08       0  5819.4    0.05       0
Bank Sta=4265.7,5193.7
Exp/Cntr=0.3,0.1

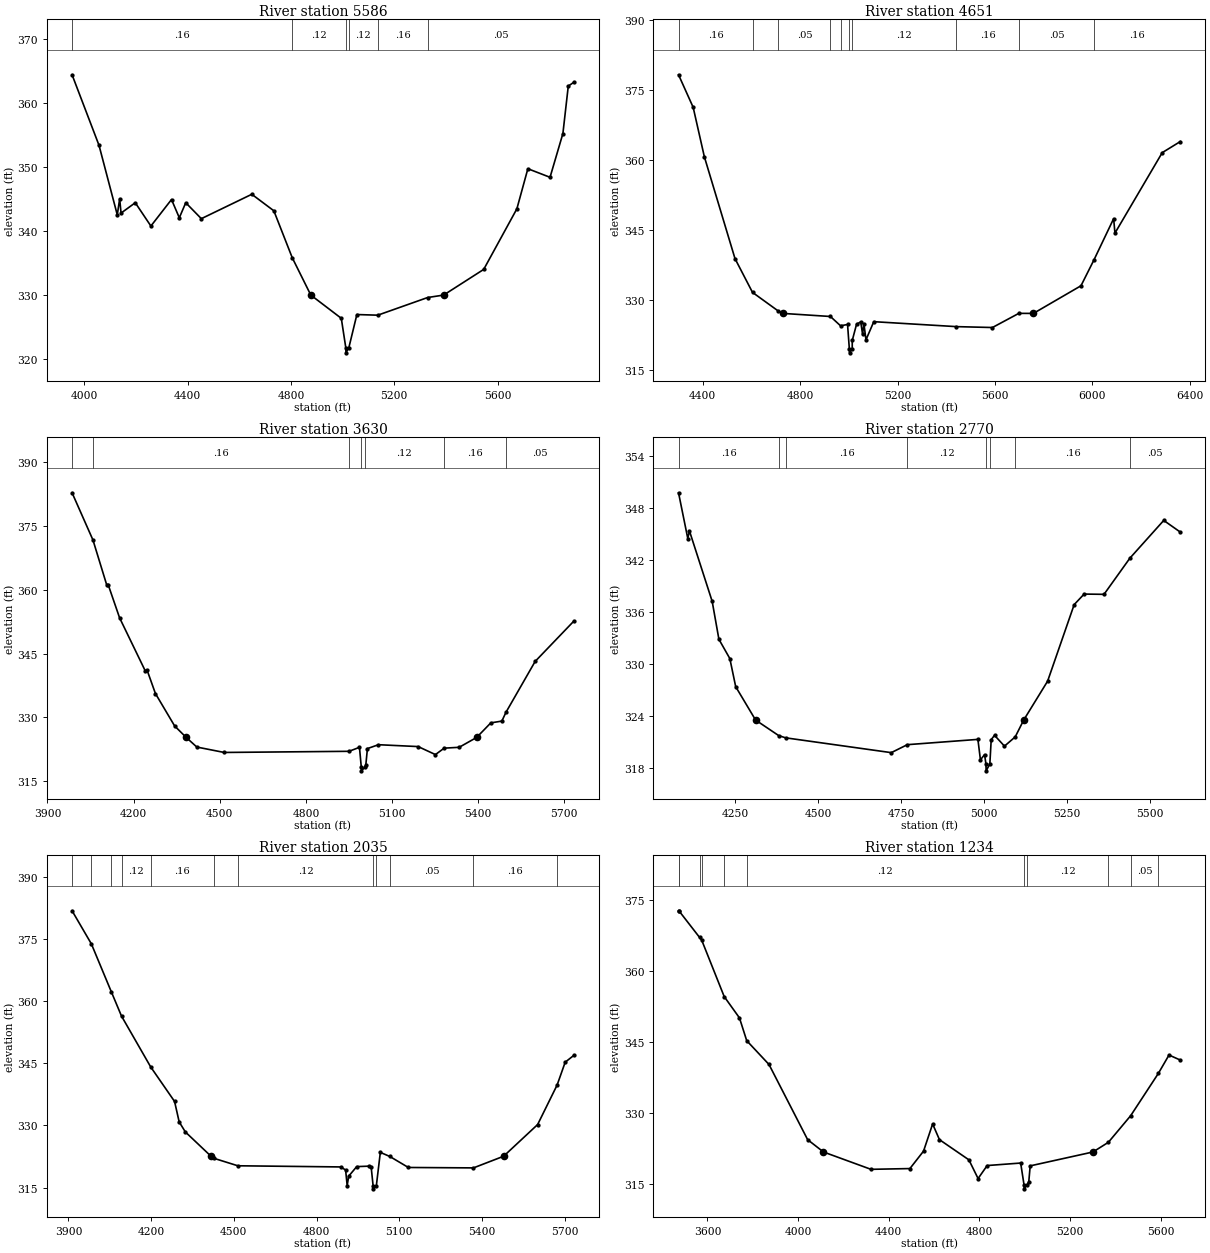
Type RM Length L Ch R = 1,5586,935,935,935
BEGIN DESCRIPTION:
PATTON CREEK 6.0
END DESCRIPTION:
XS GIS Cut Line= 3
      2932296.42      6951491.27      2931925.00      6952475.00
      2931375.03      6953174.97
#Sta/Elev= 30
  3953.3  364.38  4057.6  353.36  4128.3  342.50  4137.5  345.03  4142.8  342.78
  4197.9  344.40  4258.3  340.76  4338.1  344.90  4368.3  342.05  4393.2  344.40
  4453.5  341.91  4648.8  345.72  4734.1  343.14  4805.2  335.82  4877.1  329.98
  4995.1  326.35  5012.5  321.76  5013.1  320.96  5024.3  321.76  5055.4  326.94
  5136.2  326.84  5329.4  329.60  5391.1  329.98  5546.2  333.99  5674.5  343.45
  5717.0  349.71  5802.8  348.37  5852.6  355.21  5873.4  362.62  5895.0  363.21
#Mann=6,-1,0
  3953.3    0.16       0  4805.2    0.12       0  5012.5    0.07       0
  5024.3    0.12       0  5136.2    0.16       0  5329.4    0.05       0
Bank Sta=4877.1,5391.1
Exp/Cntr=0.3,0.1

Type RM Length L Ch R = 1,4651,1021,1021,1021
BEGIN DESCRIPTION:
PATTON CREEK 5.0
END DESCRIPTION:
XS GIS Cut Line= 3
      2931925.01      6951224.98      2931625.00      6951875.00
      2931143.68      6953130.06
#Sta/Elev= 30
  4300.9  378.23  4361.0  371.26  4406.9  360.68  4532.7  338.88  4604.6  331.65
  4711.2  327.63  4729.5  327.15  4924.5  326.49  4966.0  324.50  4994.8  324.78
  5002.2  319.51  5002.8  318.71  5014.0  319.51  5014.1  321.36  5031.8  324.84
  5048.9  325.32  5056.5  322.70  5061.9  324.98  5070.4  321.49  5102.5  325.38
  5441.9  324.32  5589.6  324.13  5698.0  327.16  5757.8  327.15  5953.2  333.07
  6006.6  338.62  6087.2  347.43  6092.6  344.34  6286.7  361.56  6361.0  363.94
#Mann=10,-1,0
  4300.9    0.16       0  4604.6    0.12       0  4711.2    0.05       0
  4924.5    0.16       0  4966.0    0.12       0  5002.2    0.07       0
  5014.0    0.12       0  5441.9    0.16       0  5698.0    0.05       0
  6006.6    0.16       0
Bank Sta=4729.5,5757.8
Exp/Cntr=0.3,0.1

Type RM Length L Ch R = 1,3630,860,860,860
BEGIN DESCRIPTION:
PATTON CREEK 4.0
END DESCRIPTION:
XS GIS Cut Line= 3
      2931925.02      6951124.99      2931119.34      6951524.25
      2930725.00      6952275.01
#Sta/Elev= 30
  3985.9  382.80  4058.7  371.69  4106.4  361.18  4112.0  361.13  4151.3  353.42
  4241.0  340.91  4246.6  341.22  4276.1  335.63  4343.1  328.00  4383.3  325.31
  4420.3  323.05  4515.6  321.78  4950.4  322.05  4986.6  322.99  4993.0  318.26
  4993.5  317.46  5004.8  318.26  5008.6  318.76  5014.3  322.69  5052.7  323.60
  5190.9  323.16  5251.1  321.28  5281.5  322.79  5333.7  322.99  5394.7  325.31
  5443.9  328.73  5482.4  329.15  5496.5  331.19  5598.3  343.17  5733.1  352.65
#Mann=7,-1,0
  3985.9    0.05       0  4058.7    0.16       0  4950.4    0.12       0
  4993.0    0.07       0  5004.8    0.12       0  5281.5    0.16       0
  5496.5    0.05       0
Bank Sta=4383.3,5394.7
Exp/Cntr=0.3,0.1

Type RM Length L Ch R = 1,2770,735,735,735
BEGIN DESCRIPTION:
PATTON CREEK 3.0
END DESCRIPTION:
XS GIS Cut Line= 3
      2931725.00      6951025.00      2930825.00      6951175.00
      2930225.01      6951175.00
#Sta/Elev= 30
  4078.5  349.79  4106.4  344.51  4111.4  345.39  4179.9  337.26  4200.2  332.88
  4233.1  330.66  4250.8  327.41  4310.8  323.56  4380.3  321.77  4401.2  321.51
  4719.7  319.80  4768.1  320.72  4980.8  321.33  4988.4  318.97  5000.9  319.57
  5005.0  318.50  5005.6  317.70  5016.8  318.50  5020.9  321.30  5030.9  321.80
  5060.9  320.55  5093.3  321.62  5118.8  323.56  5190.9  328.05  5270.9  336.88
  5300.9  338.10  5360.9  338.07  5438.8  342.24  5540.9  346.60  5590.9  345.25
#Mann=8,-1,0
  4078.5    0.16       0  4380.3     0.1       0  4401.2    0.16       0
  4768.1    0.12       0  5005.0    0.07       0  5016.8    0.12       0
  5093.3    0.16       0  5438.8    0.05       0
Bank Sta=4310.8,5118.8
Exp/Cntr=0.3,0.1

Type RM Length L Ch R = 1,2035,801,801,801
BEGIN DESCRIPTION:
PATTON CREEK 2.0
END DESCRIPTION:
XS GIS Cut Line= 3
      2931925.02      6951075.01      2931025.00      6950625.00
      2930225.00      6950775.00
#Sta/Elev= 30
  3913.2  381.74  3983.2  373.76  4055.5  362.22  4092.6  356.34  4198.4  344.09
  4285.0  335.77  4301.7  330.84  4324.1  328.42  4417.2  322.56  4426.8  322.08
  4514.5  320.26  4888.7  319.98  4905.5  319.22  4911.1  315.50  4916.7  317.76
  4945.7  320.06  4990.7  320.17  4998.3  319.86  5005.1  315.50  5005.6  314.70
  5017.0  315.50  5031.4  323.49  5065.6  322.51  5133.1  319.85  5369.2  319.75
  5478.6  322.56  5602.0  330.20  5672.7  339.73  5702.0  345.24  5733.4  346.88
#Mann=12,-1,0
  3913.2    0.16       0  3983.2    0.12       0  4055.5    0.16       0
  4092.6    0.12       0  4198.4    0.16       0  4426.8     0.1       0
  4514.5    0.12       0  5005.1    0.07       0  5017.0    0.12       0
  5065.6    0.05       0  5369.2    0.16       0  5672.7    0.12       0
Bank Sta=4417.2,5478.6
Exp/Cntr=0.3,0.1

Type RM Length L Ch R = 1,1234,987,987,987
BEGIN DESCRIPTION:
Mapping XS 0eb04767
END DESCRIPTION:
XS GIS Cut Line= 3
      2932183.05      6950130.92      2930746.39      6950230.75
      2930109.21      6950668.54
#Sta/Elev= 30
  3472.6  372.79  3475.1  372.74  3565.6  367.14  3574.5  366.61  3673.9  354.64
  3741.3  350.12  3773.3  345.30  3871.6  340.26  4042.0  324.35  4111.8  321.74
  4321.3  318.07  4493.1  318.23  4553.2  321.92  4593.3  327.67  4623.4  324.35
  4753.2  320.08  4793.8  316.12  4833.9  318.87  4981.6  319.40  4996.6  314.74
  4997.1  313.94  5008.5  314.74  5017.4  315.43  5023.6  318.80  5300.5  321.74
  5368.5  323.79  5466.8  329.42  5588.9  338.37  5635.9  342.26  5685.8  341.19
#Mann=11,-1,0
  3472.6    0.16       0  3475.1    0.05       0  3565.6    0.08       0
  3574.5    0.12       0  3673.9    0.16       0  3773.3    0.12       0
  4996.6    0.07       0  5008.5    0.12       0  5368.5    0.16       0
  5466.8    0.05       0  5588.9    0.12       0
Bank Sta=4111.8,5300.5
Exp/Cntr=0.3,0.1

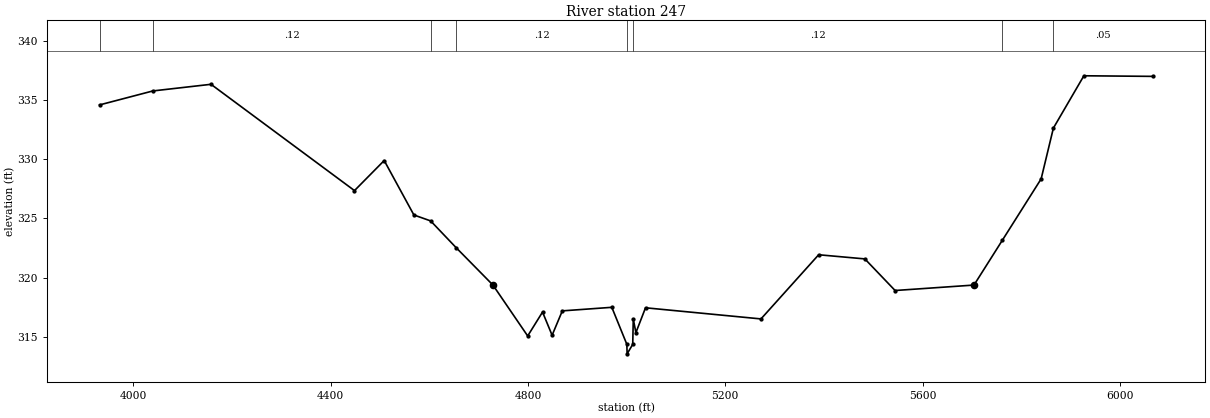
Type RM Length L Ch R = 1,247,0,0,0
BEGIN DESCRIPTION:
Mapping XS e1798b42
END DESCRIPTION:
XS GIS Cut Line= 3
      2931450.03      6949750.00      2930385.21      6949668.86
      2930022.76      6950671.78
#Sta/Elev= 30
  3932.1  334.59  4040.1  335.77  4157.8  336.33  4448.6  327.35  4508.8  329.89
  4569.0  325.29  4602.9  324.79  4654.8  322.52  4729.2  319.37  4799.6  315.07
  4829.7  317.09  4849.1  315.13  4869.8  317.19  4970.1  317.49  5000.6  314.36
  5001.1  313.56  5012.5  314.36  5013.6  316.50  5018.9  315.35  5038.4  317.45
  5272.4  316.51  5389.3  321.93  5482.9  321.58  5544.2  318.91  5704.1  319.37
  5761.8  323.17  5840.2  328.34  5865.0  332.63  5926.8  337.05  6066.4  337.00
#Mann=8,-1,0
  3932.1    0.16       0  4040.1    0.12       0  4602.9    0.08       0
  4654.8    0.12       0  5000.6    0.07       0  5012.5    0.12       0
  5761.8    0.16       0  5865.0    0.05       0
Bank Sta=4729.2,5704.1
Exp/Cntr=0.3,0.1

Chan Stop Cuts=-1