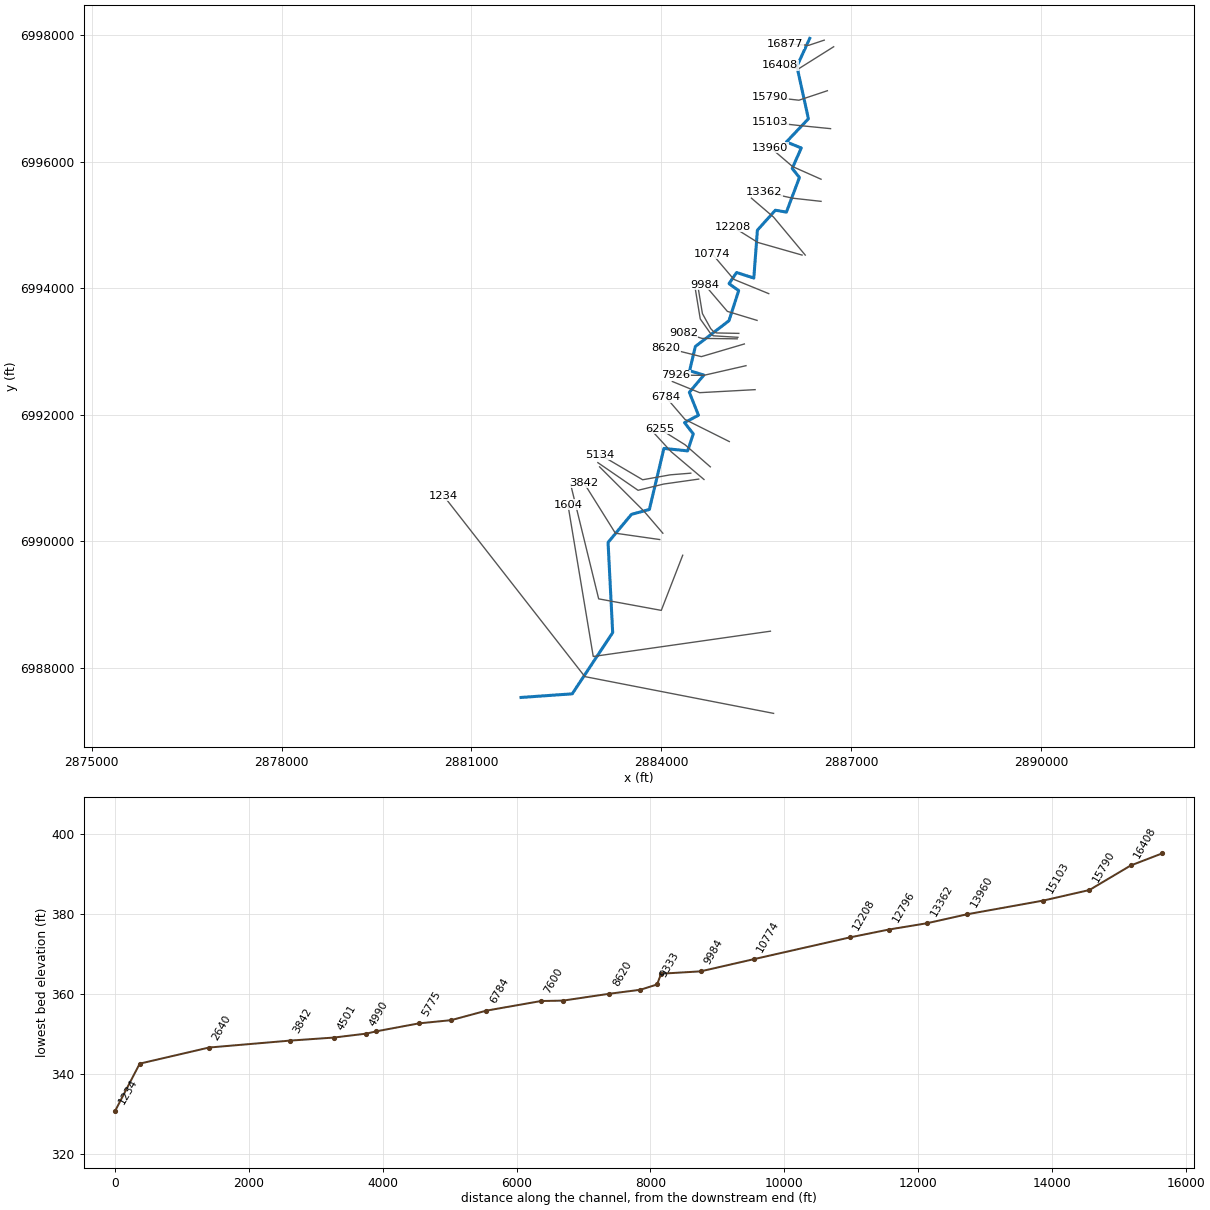
--- RAINWATER CREEK.prj (project) ---

Proj Title=RAINWATER CREEK Base Level Engineering
Current Plan=p01
Default Exp/Contr=0.3,0.1
English Units
Geom File=g01
Flow File=f01
Plan File=p01
BEGIN DESCRIPTION:
RAINWATER CREEK
END DESCRIPTION:

--- RAINWATER CREEK.p01 (plan) ---

Plan Title=Multiple Run
Short Identifier=Multiple
Geom File=g01
Flow File=f01
Subcritical Flow
K Sum by GR= 0
Std Step Tol= 0.01
Critical Tol= 0.01
Num of Std Step Trials= 20
Max Error Tol= 0.3
Flow Tol Ratio= 0.001
Split Flow NTrial= 30
Split Flow Tol= 0.02
Split Flow Ratio= 0.02
Log Output Level= 0
Friction Slope Method= 1
Unsteady Friction Slope Method= 2
Unsteady Bridges Friction Slope Method= 1
Parabolic Critical Depth
Global Vel Dist=  1 , 1 , 1
Global Log Level= 0
CheckData=True
Encroach Param= -1, 0, 0, 0
BEGIN DESCRIPTION:
Multiple Run
END DESCRIPTION:

--- RAINWATER CREEK.f01 (steady flow) ---

Flow Title=Multiple
Number of Profiles=7
Profile Names=10-year,25-year,50-year,1pct_min,100-year,1pct_plu,500-year
River Rch & RM= RAINWATER CREEK,Reach-1,16877
     463     613     734     438     873    1742    1236
River Rch & RM= RAINWATER CREEK,Reach-1,15790
     855    1175    1443     880    1755    3503    2604
River Rch & RM= RAINWATER CREEK,Reach-1,12796
     915    1259    1546     942    1880    3751    2787
River Rch & RM= RAINWATER CREEK,Reach-1,9082
    1164    1617    1998    1225    2443    4875    3662
Boundary for River Rch & Prof#=RAINWATER CREEK,Reach-1,1
Up Type=0
Dn Type=3
Dn Slope=0.005
Boundary for River Rch & Prof#=RAINWATER CREEK,Reach-1,2
Up Type=0
Dn Type=3
Dn Slope=0.005
Boundary for River Rch & Prof#=RAINWATER CREEK,Reach-1,3
Up Type=0
Dn Type=3
Dn Slope=0.005
Boundary for River Rch & Prof#=RAINWATER CREEK,Reach-1,4
Up Type=0
Dn Type=3
Dn Slope=0.005
Boundary for River Rch & Prof#=RAINWATER CREEK,Reach-1,5
Up Type=0
Dn Type=3
Dn Slope=0.005
Boundary for River Rch & Prof#=RAINWATER CREEK,Reach-1,6
Up Type=0
Dn Type=3
Dn Slope=0.005
Boundary for River Rch & Prof#=RAINWATER CREEK,Reach-1,7
Up Type=0
Dn Type=3
Dn Slope=0.005

--- RAINWATER CREEK.g01 (geometry) ---

Geom Title=Existing Conditions

River Reach=RAINWATER CREEK,Reach-1
Reach XY= 30
      2886346.49      6997953.71      2886143.20      6997510.72
      2886325.21      6996680.97      2885977.60      6996314.75
      2886212.32      6996219.41      2886069.12      6995895.71
      2886183.18      6995752.33      2885977.55      6995204.86
      2885802.83      6995234.73      2885518.92      6994919.21
      2885462.49      6994161.57      2885190.51      6994248.92
      2885070.87      6994072.95      2885223.39      6993962.76
      2885069.84      6993486.53      2884538.88      6993079.04
      2884447.40      6992695.99      2884672.95      6992626.85
      2884443.37      6992353.69      2884588.08      6991991.11
      2884367.31      6991874.83      2884505.33      6991696.22
      2884416.71      6991427.50      2884041.71      6991466.57
      2883811.42      6990500.32      2883529.33      6990423.37
      2883159.05      6989979.19      2883232.07      6988552.21
      2882592.49      6987584.17      2881783.68      6987526.63

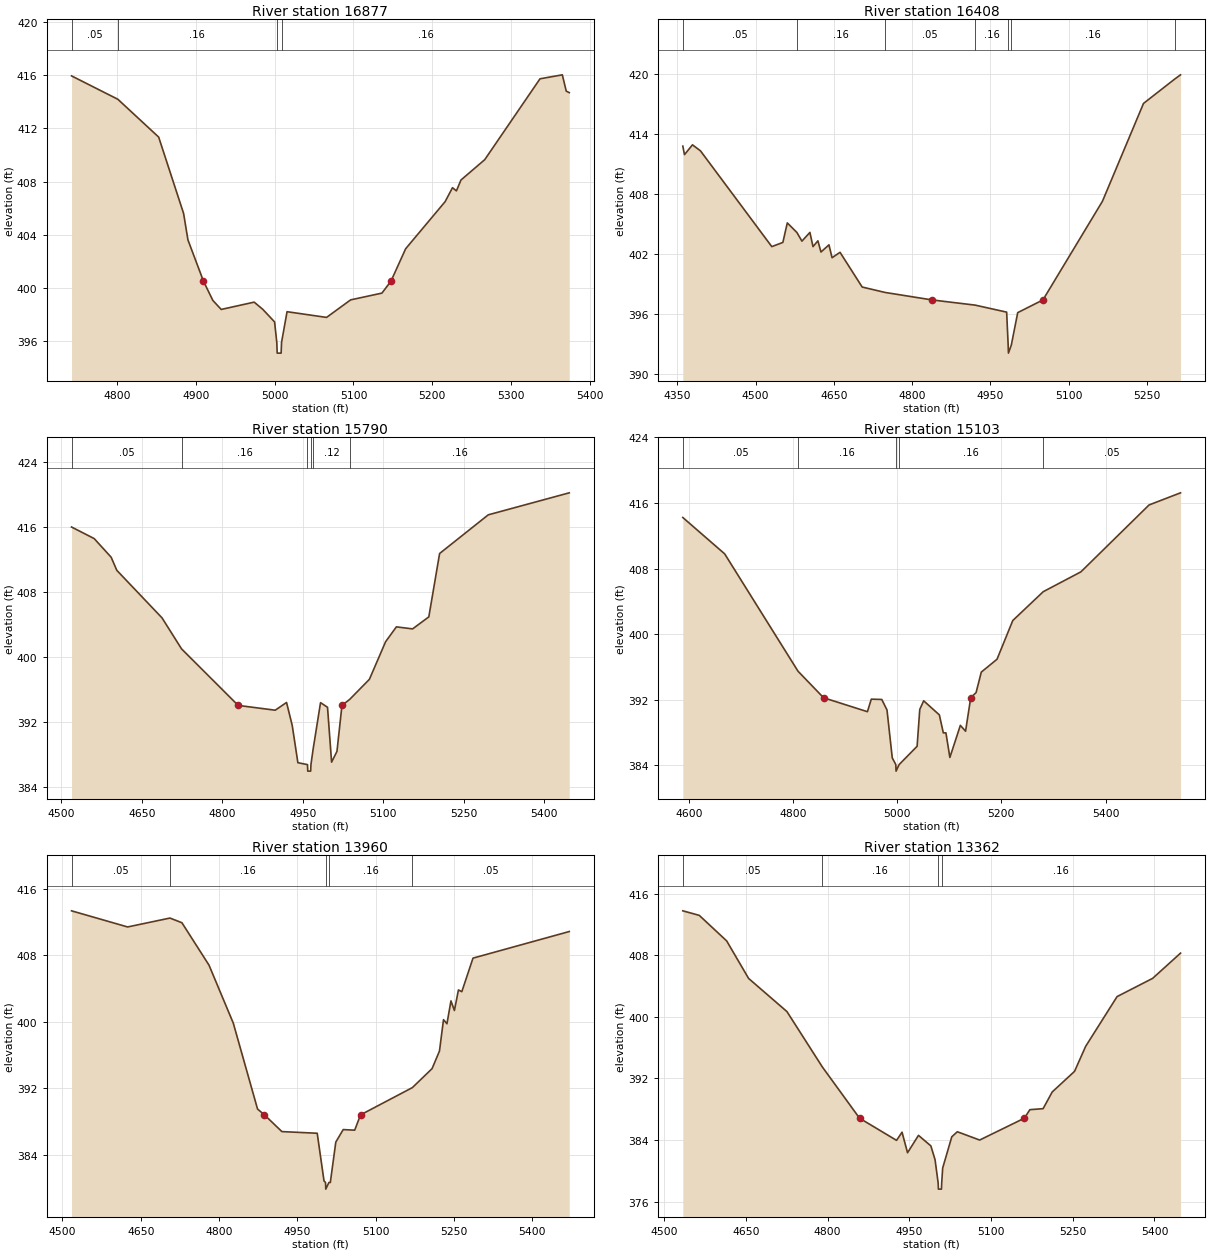
Type RM Length L Ch R = 1,16877,469,469,469
BEGIN DESCRIPTION:
RAINWATER CREEK 21.0
END DESCRIPTION:
XS GIS Cut Line= 3
      2886574.98      6997924.99      2886330.76      6997843.37
      2885958.03      6997870.40
#Sta/Elev= 30
  4742.5  415.96  4801.2  414.20  4853.0  411.35  4884.6  405.60  4890.1  403.61
  4909.8  400.50  4921.7  399.05  4932.3  398.37  4974.1  398.92  4985.0  398.38
  5000.0  397.43  5002.8  395.88  5003.3  395.08  5008.3  395.08  5008.8  395.88
  5015.8  398.20  5065.9  397.77  5096.4  399.09  5136.1  399.60  5147.6  400.50
  5166.2  402.94  5216.3  406.49  5225.6  407.54  5230.6  407.30  5236.4  408.12
  5266.5  409.65  5336.6  415.74  5364.9  416.04  5369.9  414.81  5373.7  414.70
#Mann=4,-1,0
  4742.5    0.05       0  4801.2    0.16       0  5002.8    0.07       0
  5008.8    0.16       0
Bank Sta=4909.8,5147.6
Exp/Cntr=0.3,0.1

Type RM Length L Ch R = 1,16408,618,618,618
BEGIN DESCRIPTION:
RAINWATER CREEK 20.0
END DESCRIPTION:
XS GIS Cut Line= 3
      2886724.41      6997820.65      2886175.00      6997475.00
      2885875.03      6997524.99
#Sta/Elev= 30
  4360.8  412.76  4364.0  411.91  4379.3  412.89  4394.6  412.29  4531.2  402.71
  4552.4  403.13  4560.9  405.08  4579.2  404.13  4588.9  403.26  4604.2  404.13
  4610.1  402.71  4619.5  403.29  4625.4  402.17  4640.7  402.89  4646.6  401.60
  4661.9  402.14  4704.3  398.67  4748.0  398.13  4838.1  397.38  4920.7  396.86
  4981.0  396.16  4983.9  392.86  4984.4  392.06  4989.9  392.86  5002.2  396.11
  5050.5  397.38  5164.5  407.25  5243.1  417.03  5303.2  419.48  5314.0  419.89
#Mann=7,-1,0
  4360.8    0.05       0  4579.2    0.16       0  4748.0    0.05       0
  4920.7    0.16       0  4983.9    0.07       0  4989.9    0.16       0
  5303.2    0.05       0
Bank Sta=4838.1,5050.5
Exp/Cntr=0.3,0.1

Type RM Length L Ch R = 1,15790,687,687,687
BEGIN DESCRIPTION:
RAINWATER CREEK 19.0
END DESCRIPTION:
XS GIS Cut Line= 3
      2886624.97      6997124.99      2886175.00      6996975.00
      2885724.98      6997025.00
#Sta/Elev= 30
  4519.2  415.97  4561.3  414.55  4593.0  412.25  4603.5  410.64  4687.8  404.78
  4724.1  400.97  4829.6  394.01  4898.6  393.42  4919.7  394.37  4930.3  391.53
  4940.8  386.96  4958.7  386.72  4959.2  385.92  4964.6  385.92  4965.1  386.72
  4969.3  388.67  4983.0  394.35  4996.0  393.78  5003.6  387.03  5013.6  388.35
  5022.9  394.01  5037.3  394.75  5074.0  397.22  5104.2  401.85  5124.3  403.68
  5154.5  403.43  5184.7  404.91  5204.8  412.71  5295.4  417.47  5446.3  420.18
#Mann=6,-1,0
  4519.2    0.05       0  4724.1    0.16       0  4958.7    0.07       0
  4965.1    0.16       0  4969.3    0.12       0  5037.3    0.16       0
Bank Sta=4829.6,5022.9
Exp/Cntr=0.3,0.1

Type RM Length L Ch R = 1,15103,1143,1143,1143
BEGIN DESCRIPTION:
RAINWATER CREEK 18.0
END DESCRIPTION:
XS GIS Cut Line= 3
      2886675.00      6996525.00      2886175.00      6996575.00
      2885724.97      6996625.00
#Sta/Elev= 30
  4588.7  414.23  4669.1  409.79  4809.8  395.48  4858.9  392.24  4943.0  390.54
  4950.5  392.07  4970.6  392.03  4980.6  390.75  4990.7  384.91  4997.5  384.09
  4998.0  383.29  5003.9  384.09  5038.4  386.32  5043.5  390.81  5051.0  391.87
  5081.1  390.15  5088.7  387.96  5093.7  387.96  5101.3  384.96  5121.4  388.87
  5131.4  388.16  5141.3  392.24  5151.6  392.87  5161.6  395.37  5191.8  396.94
  5222.0  401.66  5280.5  405.18  5352.8  407.60  5483.6  415.76  5544.0  417.24
#Mann=5,-1,0
  4588.7    0.05       0  4809.8    0.16       0  4997.5    0.07       0
  5003.9    0.16       0  5280.5    0.05       0
Bank Sta=4858.9,5141.3
Exp/Cntr=0.3,0.1

Type RM Length L Ch R = 1,13960,598,598,598
BEGIN DESCRIPTION:
RAINWATER CREEK 17.0
END DESCRIPTION:
XS GIS Cut Line= 3
      2886525.01      6995724.99      2886075.00      6995925.00
      2885725.02      6996224.98
#Sta/Elev= 30
  4517.4  413.32  4624.8  411.38  4705.9  412.45  4728.8  411.89  4780.7  406.79
  4827.2  399.82  4873.7  389.48  4886.9  388.78  4920.3  386.77  4988.0  386.57
  5001.0  380.84  5003.9  380.65  5004.4  379.85  5010.4  380.65  5013.1  380.65
  5023.6  385.51  5037.8  387.01  5059.8  386.94  5071.0  388.78  5170.3  392.06
  5208.0  394.34  5222.2  396.46  5229.9  400.23  5236.5  399.74  5244.2  402.49
  5250.8  401.33  5258.5  403.80  5265.0  403.60  5286.4  407.63  5470.8  410.83
#Mann=5,-1,0
  4517.4    0.05       0  4705.9    0.16       0  5003.9    0.07       0
  5010.4    0.16       0  5170.3    0.05       0
Bank Sta=4886.9,5071
Exp/Cntr=0.3,0.1

Type RM Length L Ch R = 1,13362,566,566,566
BEGIN DESCRIPTION:
RAINWATER CREEK 16.0
END DESCRIPTION:
XS GIS Cut Line= 3
      2886525.05      6995374.99      2886075.00      6995425.00
      2885624.99      6995525.00
#Sta/Elev= 30
  4534.1  413.79  4564.3  413.20  4614.6  409.88  4654.9  405.00  4725.3  400.69
  4790.2  393.50  4858.6  386.83  4926.5  383.95  4936.6  385.01  4946.7  382.34
  4966.8  384.60  4989.5  383.23  4997.2  381.44  5002.9  378.41  5003.4  377.61
  5008.9  377.61  5009.4  378.41  5011.2  380.35  5027.9  384.41  5038.1  385.07
  5079.1  383.99  5161.2  386.83  5171.3  387.94  5195.6  388.07  5212.3  390.24
  5253.3  392.92  5273.7  396.17  5331.4  402.64  5396.7  405.01  5447.9  408.29
#Mann=4,-1,0
  4534.1    0.05       0  4790.2    0.16       0  5002.9    0.07       0
  5009.4    0.16       0
Bank Sta=4858.6,5161.2
Exp/Cntr=0.3,0.1

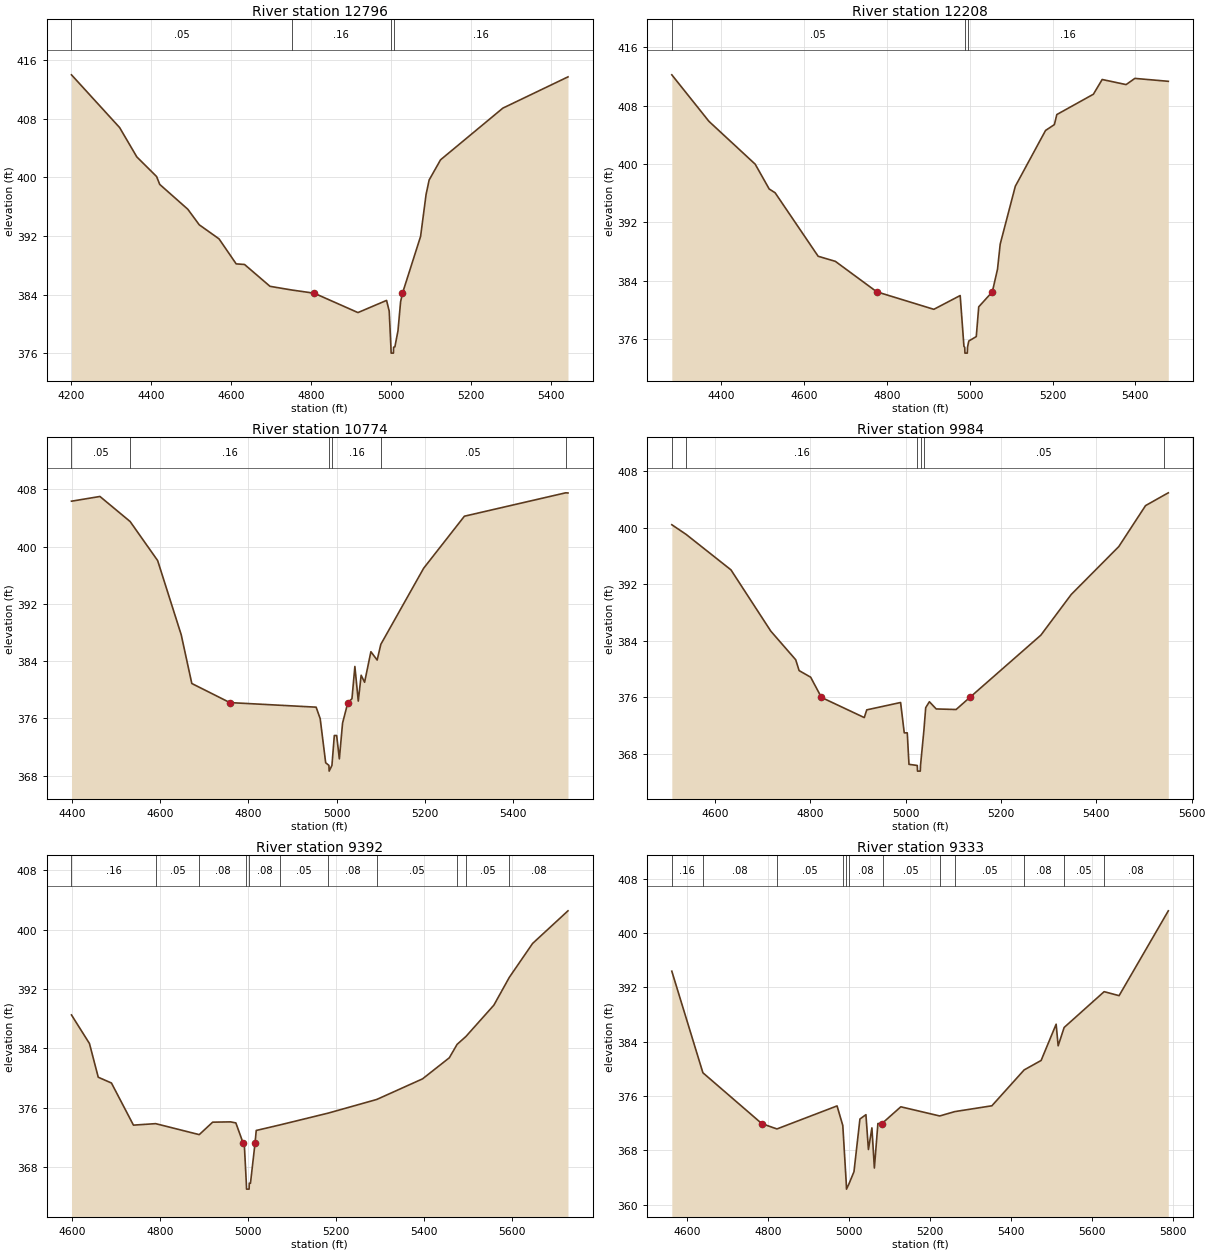
Type RM Length L Ch R = 1,12796,588,588,588
BEGIN DESCRIPTION:
RAINWATER CREEK 15.0
END DESCRIPTION:
XS GIS Cut Line= 3
      2886275.02      6994524.97      2885775.00      6995125.00
      2885425.03      6995424.97
#Sta/Elev= 30
  4200.9  414.00  4321.3  406.81  4364.3  402.81  4413.8  400.13  4421.6  399.06
  4491.9  395.67  4520.5  393.55  4570.0  391.63  4612.9  388.22  4633.8  388.14
  4697.5  385.16  4751.6  384.66  4808.1  384.22  4917.5  381.58  4989.1  383.24
  4995.7  381.78  5000.0  376.85  5000.5  376.05  5006.2  376.05  5006.7  376.85
  5009.9  376.91  5017.6  379.09  5024.2  383.06  5028.9  384.22  5074.2  391.97
  5087.9  397.68  5095.6  399.66  5124.1  402.41  5280.0  409.46  5442.9  413.72
#Mann=4,-1,0
  4200.9    0.05       0  4751.6    0.16       0  5000.0    0.07       0
  5006.7    0.16       0
Bank Sta=4808.1,5028.9
Exp/Cntr=0.3,0.1

Type RM Length L Ch R = 1,12208,1434,1434,1434
BEGIN DESCRIPTION:
RAINWATER CREEK 14.0
END DESCRIPTION:
XS GIS Cut Line= 3
      2886225.01      6994525.00      2885525.00      6994725.00
      2885125.02      6994974.99
#Sta/Elev= 30
  4280.0  412.24  4369.7  405.86  4481.5  399.98  4515.3  396.58  4529.6  396.06
  4633.6  387.35  4675.2  386.65  4775.3  382.47  4913.1  380.07  4976.8  381.96
  4985.9  374.98  4987.8  374.86  4988.3  374.06  4994.0  374.06  4994.5  374.86
  4997.6  375.72  5015.7  376.33  5021.6  380.41  5054.5  382.47  5067.0  385.58
  5073.5  389.02  5110.0  396.95  5183.1  404.61  5204.4  405.41  5210.3  406.79
  5298.7  409.58  5319.9  411.60  5377.7  410.90  5398.9  411.75  5479.7  411.35
#Mann=3,-1,0
  4280.0    0.05       0  4987.8    0.07       0  4994.5    0.16       0
Bank Sta=4775.3,5054.5
Exp/Cntr=0.3,0.1

Type RM Length L Ch R = 1,10774,790,790,790
BEGIN DESCRIPTION:
Mapping XS 34f3adb7
END DESCRIPTION:
XS GIS Cut Line= 3
      2885698.18      6993914.97      2885146.95      6994140.68
      2884804.05      6994544.34
#Sta/Elev= 30
  4399.0  406.35  4463.5  407.01  4531.9  403.51  4594.3  398.05  4647.7  387.68
  4671.7  380.87  4757.9  378.20  4953.5  377.56  4962.7  375.95  4975.1  369.79
  4982.5  369.42  4983.0  368.62  4989.3  369.42  4994.7  373.60  5000.0  373.60
  5006.1  370.33  5013.4  375.34  5025.4  378.20  5034.7  378.74  5041.3  383.25
  5049.0  378.41  5055.5  382.02  5063.3  381.04  5077.6  385.31  5091.8  384.15
  5100.1  386.34  5197.2  396.98  5289.5  404.25  5519.0  407.52  5524.3  407.50
#Mann=6,-1,0
  4399.0    0.05       0  4531.9    0.16       0  4982.5    0.07       0
  4989.3    0.16       0  5100.1    0.05       0  5519.0    0.08       0
Bank Sta=4757.9,5025.4
Exp/Cntr=0.3,0.1

Type RM Length L Ch R = 1,9984,592,592,592
BEGIN DESCRIPTION:
Mapping XS 0a4c3c73
END DESCRIPTION:
XS GIS Cut Line= 3
      2885513.73      6993491.80      2885044.23      6993634.48
      2884686.87      6994053.88
#Sta/Elev= 30
  4509.3  400.42  4539.4  399.05  4633.4  394.04  4717.0  385.38  4769.3  381.33
  4776.4  379.80  4800.6  378.87  4823.2  376.01  4913.1  373.16  4918.3  374.25
  4989.3  375.29  4997.0  371.00  5003.3  371.00  5006.9  366.55  5024.3  366.39
  5024.8  365.59  5030.6  365.59  5031.1  366.39  5038.2  371.35  5042.0  374.56
  5049.7  375.40  5064.0  374.38  5105.8  374.30  5134.6  376.01  5283.6  384.81
  5347.3  390.56  5447.2  397.34  5503.2  403.12  5542.4  404.61  5551.0  404.93
#Mann=6,-1,0
  4509.3    0.05       0  4539.4    0.16       0  5024.3    0.07       0
  5031.1    0.16       0  5038.2    0.05       0  5542.4     0.1       0
Bank Sta=4823.2,5134.6
Exp/Cntr=0.3,0.1

Type RM Length L Ch R = 1,9392,59,59,59
BEGIN DESCRIPTION:
RAINWATER CREEK 13.0
END DESCRIPTION:
XS GIS Cut Line= 6
      2885225.78      6993286.37      2884876.40      6993292.88
      2884828.52      6993311.18      2884780.92      6993362.32
      2884650.00      6993600.00      2884587.23      6993981.15
#Sta/Elev= 30
  4599.3  388.49  4640.1  384.64  4660.1  380.09  4690.1  379.31  4740.1  373.63
  4790.5  373.83  4889.6  372.35  4920.1  374.03  4960.9  374.07  4972.8  373.93
  4989.4  371.20  4992.2  370.78  4996.6  365.80  4997.1  365.00  5002.9  365.00
  5003.4  365.80  5006.0  365.80  5016.4  371.20  5019.1  372.91  5072.3  373.65
  5182.6  375.25  5292.9  377.09  5397.0  379.87  5457.8  382.71  5475.5  384.52
  5495.5  385.58  5559.1  389.81  5594.3  393.57  5647.1  398.13  5727.5  402.53
#Mann=11,-1,0
  4599.3    0.16       0  4790.5    0.05       0  4889.6    0.08       0
  4996.6    0.07       0  5003.4    0.08       0  5072.3    0.05       0
  5182.6    0.08       0  5292.9    0.05       0  5475.5    0.08       0
  5495.5    0.05       0  5594.3    0.08       0
Bank Sta=4989.4,5016.4
Exp/Cntr=0.3,0.1

Type RM Length L Ch R = 1,9333,251,251,251
BEGIN DESCRIPTION:
RAINWATER CREEK 12.0
END DESCRIPTION:
XS GIS Cut Line= 5
      2885211.69      6993223.97      2884821.06      6993247.85
      2884784.29      6993276.54      2884615.98      6993514.77
      2884535.18      6994004.97
#Sta/Elev= 30
  4562.0  394.39  4638.8  379.44  4784.4  371.95  4821.7  371.17  4970.2  374.56
  4984.4  371.67  4993.0  363.11  4993.5  362.31  4999.8  363.11  5012.0  364.88
  5026.7  372.63  5041.5  373.27  5047.7  368.14  5056.3  371.33  5062.4  365.42
  5071.1  371.97  5081.3  371.94  5083.3  372.08  5127.7  374.43  5223.8  373.08
  5260.8  373.72  5352.7  374.58  5432.4  379.86  5474.3  381.25  5511.4  386.59
  5516.4  383.41  5531.2  386.11  5630.0  391.38  5666.9  390.79  5788.5  403.28
#Mann=12,-1,0
  4562.0    0.16       0  4638.8    0.08       0  4821.7    0.05       0
  4984.4    0.08       0  4993.0    0.07       0  4999.8    0.08       0
  5083.3    0.05       0  5223.8    0.08       0  5260.8    0.05       0
  5432.4    0.08       0  5531.2    0.05       0  5630.0    0.08       0
Bank Sta=4784.4,5081.3
Exp/Cntr=0.3,0.1

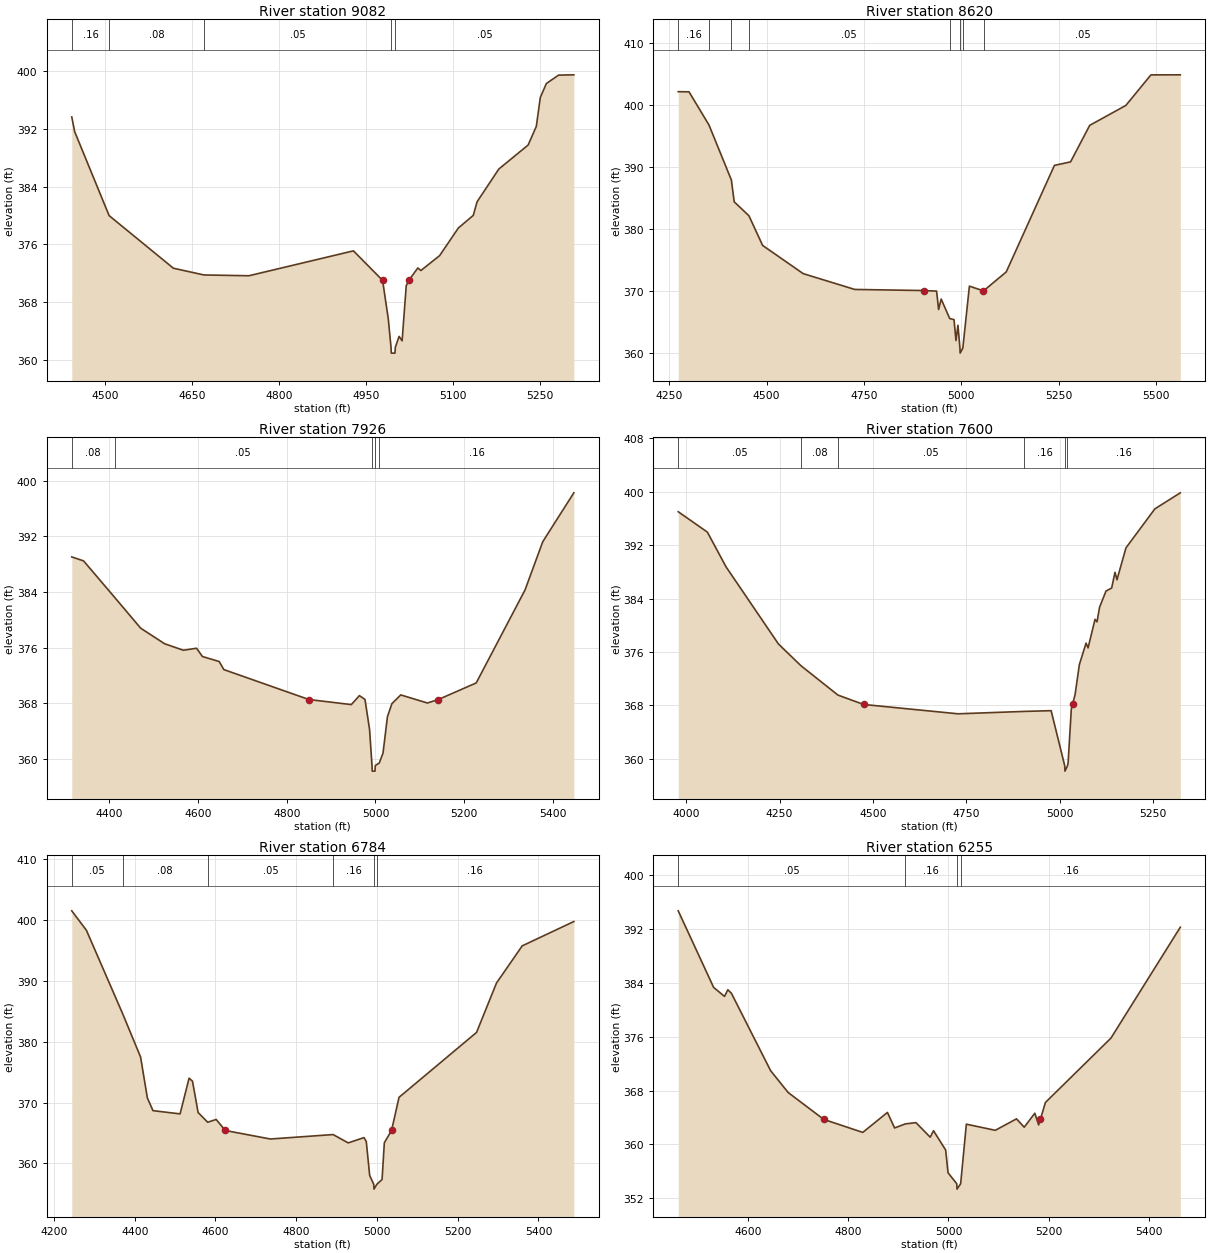
Type RM Length L Ch R = 1,9082,462,462,462
BEGIN DESCRIPTION:
RAINWATER CREEK 11.0
END DESCRIPTION:
XS GIS Cut Line= 3
      2885199.99      6993200.00      2884643.34      6993206.88
      2884349.96      6993300.01
#Sta/Elev= 30
  4443.3  393.61  4448.3  391.58  4507.6  379.98  4618.3  372.71  4670.8  371.78
  4748.3  371.67  4928.3  375.11  4978.5  371.03  4988.3  365.72  4993.0  361.78
  4993.5  360.98  4999.8  360.98  5000.4  361.78  5006.9  363.29  5012.1  362.68
  5019.2  370.29  5023.6  371.03  5039.2  372.75  5044.4  372.39  5076.7  374.45
  5108.9  378.26  5134.6  380.01  5141.2  381.89  5178.7  386.42  5229.1  389.73
  5243.2  392.31  5250.1  396.31  5260.5  398.23  5281.5  399.39  5307.8  399.43
#Mann=5,-1,0
  4443.3    0.16       0  4507.6    0.08       0  4670.8    0.05       0
  4993.0    0.03       0  5000.4    0.05       0
Bank Sta=4978.5,5023.6
Exp/Cntr=0.3,0.1

Type RM Length L Ch R = 1,8620,694,694,694
BEGIN DESCRIPTION:
Mapping XS 64046c12
END DESCRIPTION:
XS GIS Cut Line= 3
      2885312.95      6993118.93      2884633.28      6992918.42
      2884069.11      6993058.81
#Sta/Elev= 30
  4272.8  402.15  4300.5  402.13  4351.8  396.78  4409.4  387.90  4416.6  384.39
  4454.4  382.15  4489.6  377.36  4593.9  372.81  4726.3  370.26  4904.6  370.08
  4936.6  369.99  4941.8  367.03  4948.4  368.71  4970.3  365.57  4981.4  365.39
  4986.4  362.02  4991.5  364.48  4996.6  360.79  4997.1  359.99  5004.0  360.79
  5020.9  370.79  5054.7  370.08  5059.5  370.15  5115.5  373.08  5239.4  390.27
  5280.8  390.83  5330.0  396.72  5422.8  399.93  5487.3  404.86  5562.8  404.87
#Mann=8,-1,0
  4272.8    0.16       0  4351.8    0.05       0  4409.4    0.08       0
  4454.4    0.05       0  4970.3    0.16       0  4996.6    0.07       0
  5004.0    0.16       0  5059.5    0.05       0
Bank Sta=4904.6,5054.7
Exp/Cntr=0.3,0.1

Type RM Length L Ch R = 1,7926,326,326,326
BEGIN DESCRIPTION:
RAINWATER CREEK 10.0
END DESCRIPTION:
XS GIS Cut Line= 3
      2885339.05      6992775.20      2884671.99      6992622.55
      2884225.00      6992625.00
#Sta/Elev= 30
  4315.7  389.05  4342.3  388.48  4412.0  383.26  4471.0  378.81  4525.0  376.57
  4567.2  375.64  4596.8  375.93  4610.1  374.74  4647.9  374.02  4658.4  372.86
  4850.0  368.56  4945.6  367.83  4963.8  369.12  4976.4  368.57  4986.7  364.27
  4992.2  359.07  4992.7  358.27  4999.0  358.27  4999.6  359.07  5008.5  359.43
  5017.0  360.86  5027.0  366.09  5037.0  367.96  5057.0  369.22  5117.0  368.06
  5141.7  368.56  5227.0  370.94  5337.0  384.30  5377.0  391.24  5447.0  398.26
#Mann=5,-1,0
  4315.7    0.08       0  4412.0    0.05       0  4992.2    0.03       0
  4999.6    0.05       0  5008.5    0.16       0
Bank Sta=4850,5141.7
Exp/Cntr=0.3,0.1

Type RM Length L Ch R = 1,7600,816,816,816
BEGIN DESCRIPTION:
RAINWATER CREEK 9.0
END DESCRIPTION:
XS GIS Cut Line= 3
      2885482.89      6992396.07      2884606.16      6992348.32
      2884174.98      6992525.01
#Sta/Elev= 30
  3978.7  397.00  4056.7  393.95  4106.8  388.74  4247.0  377.20  4307.2  373.95
  4406.3  369.55  4474.8  368.15  4727.7  366.75  4905.6  367.11  4976.9  367.22
  5013.3  358.97  5013.9  358.17  5020.7  358.97  5022.4  359.44  5030.9  367.45
  5034.1  368.15  5041.0  369.63  5052.5  374.12  5070.4  377.33  5075.8  376.62
  5094.4  380.89  5099.8  380.52  5106.5  382.69  5123.8  385.13  5139.0  385.58
  5147.8  387.93  5153.2  386.82  5177.2  391.59  5254.6  397.43  5322.7  399.83
#Mann=6,-1,0
  3978.7    0.05       0  4307.2    0.08       0  4406.3    0.05       0
  4905.6    0.16       0  5013.3    0.07       0  5020.7    0.16       0
Bank Sta=4474.8,5034.1
Exp/Cntr=0.3,0.1

Type RM Length L Ch R = 1,6784,529,529,529
BEGIN DESCRIPTION:
RAINWATER CREEK 8.0
END DESCRIPTION:
XS GIS Cut Line= 3
      2885074.96      6991575.02      2884375.00      6991925.00
      2884074.97      6992275.04
#Sta/Elev= 30
  4244.0  401.52  4280.3  398.32  4370.4  384.55  4414.5  377.48  4431.2  370.77
  4445.2  368.67  4512.3  368.14  4534.6  374.01  4543.0  373.52  4557.0  368.36
  4580.6  366.77  4601.7  367.22  4624.3  365.41  4735.9  364.01  4891.4  364.74
  4928.7  363.37  4967.9  364.24  4973.5  363.59  4981.9  358.02  4991.9  356.57
  4992.6  355.77  4999.7  356.57  5012.6  357.36  5018.2  363.40  5036.1  365.41
  5054.6  370.86  5246.6  381.53  5296.0  389.65  5359.7  395.76  5487.6  399.76
#Mann=6,-1,0
  4244.0    0.05       0  4370.4    0.08       0  4580.6    0.05       0
  4891.4    0.16       0  4991.9    0.07       0  4999.7    0.16       0
Bank Sta=4624.3,5036.1
Exp/Cntr=0.3,0.1

Type RM Length L Ch R = 1,6255,480,480,480
BEGIN DESCRIPTION:
RAINWATER CREEK 7.0
END DESCRIPTION:
XS GIS Cut Line= 3
      2884774.97      6991175.03      2884375.00      6991525.00
      2883974.97      6991775.02
#Sta/Elev= 30
  4460.0  394.64  4530.7  383.29  4552.5  381.95  4559.1  382.94  4566.3  382.41
  4644.6  370.94  4679.7  367.70  4750.7  363.72  4828.7  361.79  4878.0  364.75
  4892.3  362.45  4913.8  363.05  4935.0  363.24  4963.5  361.08  4970.1  362.04
  4994.4  359.17  4999.1  355.81  5016.5  354.18  5017.1  353.38  5024.3  354.18
  5035.7  363.01  5093.5  362.10  5135.9  363.80  5151.3  362.56  5172.5  364.63
  5180.1  362.90  5183.6  363.72  5193.7  366.23  5324.6  375.77  5463.2  392.21
#Mann=4,-1,0
  4460.0    0.05       0  4913.8    0.16       0  5016.5    0.07       0
  5024.3    0.16       0
Bank Sta=4750.7,5183.6
Exp/Cntr=0.3,0.1

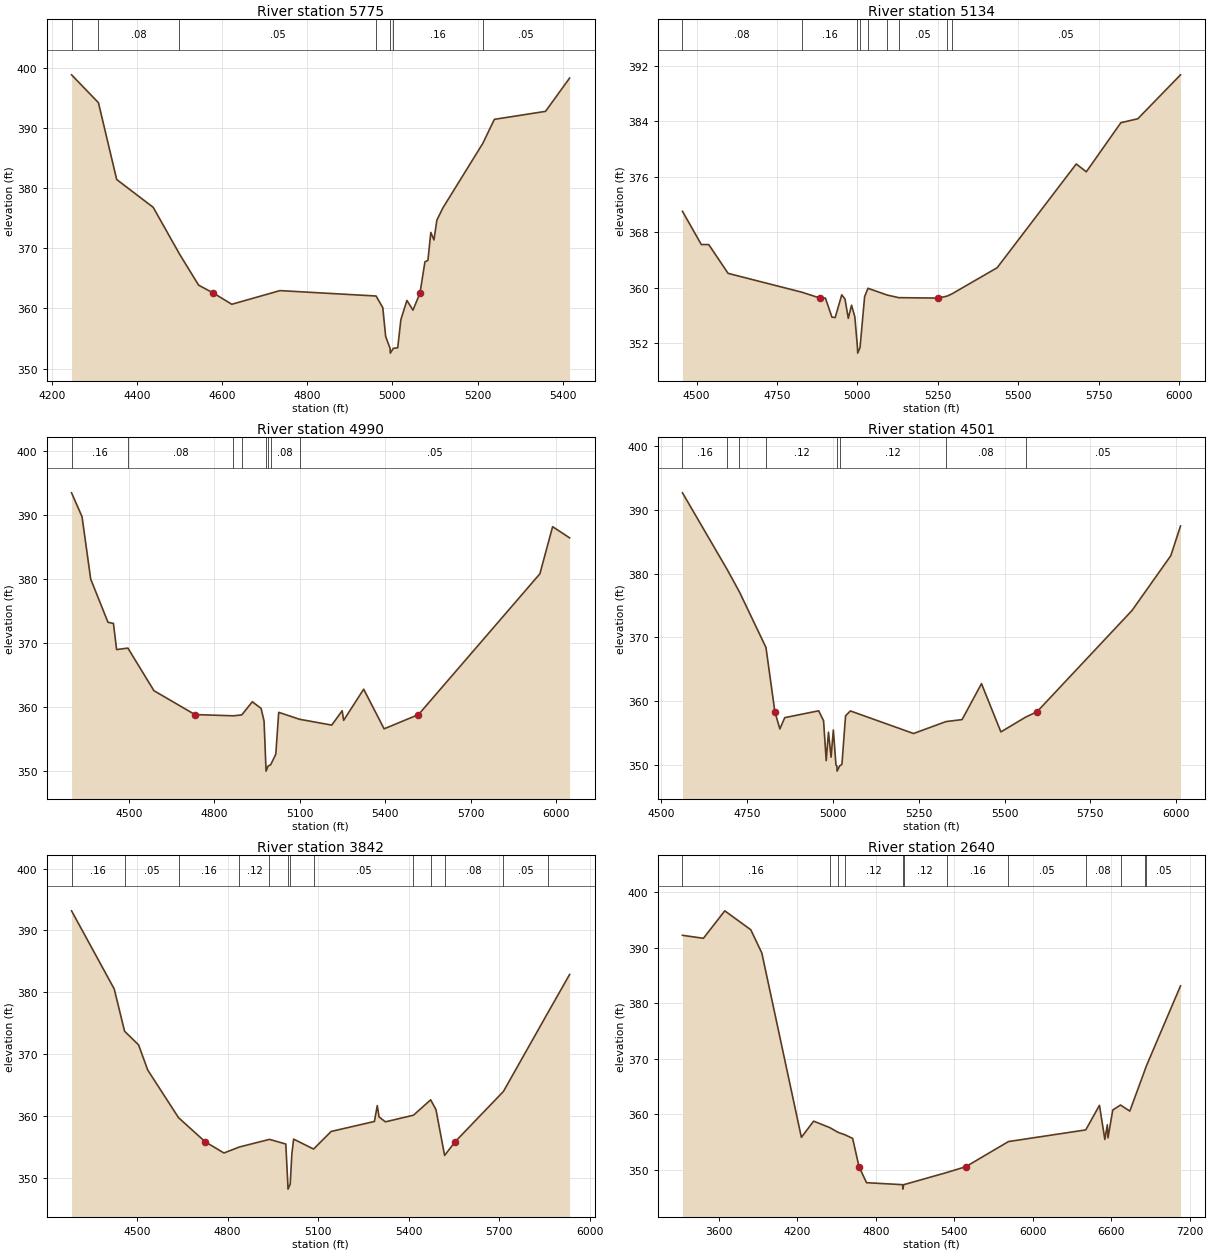
Type RM Length L Ch R = 1,5775,641,641,641
BEGIN DESCRIPTION:
RAINWATER CREEK 6.0
END DESCRIPTION:
XS GIS Cut Line= 3
      2884674.98      6990975.01      2884158.24      6991412.56
      2883824.97      6991775.03
#Sta/Elev= 30
  4246.6  398.83  4309.7  394.20  4352.6  381.43  4438.3  376.81  4500.0  369.06
  4544.9  363.88  4579.6  362.56  4622.9  360.70  4736.0  362.97  4961.7  362.07
  4977.4  360.14  4984.2  355.34  4994.5  353.38  4995.1  352.58  5002.3  353.38
  5012.5  353.47  5019.9  358.15  5034.1  361.33  5048.3  359.73  5064.8  362.56
  5076.4  367.76  5083.4  368.00  5090.2  372.64  5097.6  371.39  5104.4  374.68
  5118.6  376.72  5212.3  387.44  5239.4  391.43  5359.6  392.76  5416.1  398.29
#Mann=7,-1,0
  4246.6    0.05       0  4309.7    0.08       0  4500.0    0.05       0
  4961.7    0.16       0  4994.5    0.07       0  5002.3    0.16       0
  5212.3    0.05       0
Bank Sta=4579.6,5064.8
Exp/Cntr=0.3,0.1

Type RM Length L Ch R = 1,5134,144,144,144
BEGIN DESCRIPTION:
Mapping XS 8678658f
END DESCRIPTION:
XS GIS Cut Line= 4
      2884466.35      6991074.88      2884143.48      6991048.84
      2883705.98      6990970.72      2883034.15      6991366.53
#Sta/Elev= 30
  4456.3  371.01  4514.9  366.22  4537.9  366.22  4598.1  362.07  4827.9  359.35
  4883.8  358.51  4900.6  358.51  4920.9  355.76  4931.0  355.71  4951.4  358.98
  4961.5  358.37  4971.7  355.59  4981.8  357.48  4992.0  355.82  5000.3  351.38
  5000.9  350.58  5008.2  351.38  5022.5  358.72  5032.9  359.92  5092.4  358.95
  5128.4  358.57  5250.8  358.51  5278.6  358.79  5292.9  359.09  5434.4  362.88
  5680.3  377.83  5711.6  376.70  5818.9  383.77  5871.6  384.34  6004.4  390.67
#Mann=9,-1,0
  4456.3    0.08       0  4827.9    0.16       0  5000.3    0.07       0
  5008.2    0.16       0  5032.9    0.05       0  5092.4    0.08       0
  5128.4    0.05       0  5278.6    0.08       0  5292.9    0.05       0
Bank Sta=4883.8,5250.8
Exp/Cntr=0.3,0.1

Type RM Length L Ch R = 1,4990,489,489,489
BEGIN DESCRIPTION:
Mapping XS b57066e2
END DESCRIPTION:
XS GIS Cut Line= 4
      2884591.44      6990981.14      2884039.31      6990903.01
      2883633.06      6990804.05      2882997.67      6991241.54
#Sta/Elev= 30
  4299.6  393.43  4336.4  389.70  4366.7  379.98  4427.3  373.24  4446.5  373.06
  4457.6  368.98  4497.3  369.21  4588.5  362.57  4732.5  358.84  4867.3  358.65
  4896.7  358.79  4933.7  360.84  4964.6  359.80  4974.9  357.83  4981.2  350.82
  4981.9  350.02  4989.1  350.82  4998.1  351.01  5016.1  352.66  5026.3  359.19
  5099.4  358.11  5212.4  357.20  5248.9  359.44  5254.1  357.94  5324.4  362.80
  5396.1  356.62  5516.7  358.84  5942.6  380.80  5987.2  388.15  6046.8  386.41
#Mann=8,-1,0
  4299.6    0.16       0  4497.3    0.08       0  4867.3    0.12       0
  4896.7    0.05       0  4981.2    0.07       0  4989.1    0.05       0
  4998.1    0.08       0  5099.4    0.05       0
Bank Sta=4732.5,5516.7
Exp/Cntr=0.3,0.1

Type RM Length L Ch R = 1,4501,659,659,659
BEGIN DESCRIPTION:
RAINWATER CREEK 4.0
END DESCRIPTION:
XS GIS Cut Line= 3
      2884024.97      6990125.03      2883725.00      6990475.00
      2883024.99      6991175.01
#Sta/Elev= 30
  4561.7  392.68  4692.8  380.57  4727.8  377.12  4804.9  368.43  4830.9  358.34
  4845.4  355.65  4859.6  357.42  4958.4  358.49  4972.7  356.95  4980.4  350.67
  4987.0  355.14  4994.6  351.22  5001.2  355.48  5008.9  349.98  5011.5  349.83
  5012.2  349.03  5019.4  349.83  5026.2  350.10  5036.8  357.71  5050.9  358.47
  5234.8  354.93  5329.3  356.80  5376.2  357.11  5432.8  362.75  5489.3  355.18
  5561.4  357.50  5594.5  358.34  5871.2  374.22  5984.3  382.82  6012.6  387.48
#Mann=8,-1,0
  4561.7    0.16       0  4692.8    0.12       0  4727.8    0.16       0
  4804.9    0.12       0  5011.5    0.07       0  5019.4    0.12       0
  5329.3    0.08       0  5561.4    0.05       0
Bank Sta=4830.9,5594.5
Exp/Cntr=0.3,0.1

Type RM Length L Ch R = 1,3842,1202,1202,1202
BEGIN DESCRIPTION:
RAINWATER CREEK 3.0
END DESCRIPTION:
XS GIS Cut Line= 3
      2883974.97      6990025.00      2883275.00      6990125.00
      2882774.99      6990925.02
#Sta/Elev= 30
  4283.1  393.17  4424.5  380.56  4458.8  373.74  4505.3  371.53  4535.6  367.47
  4637.8  359.78  4726.0  355.90  4788.1  354.09  4839.4  355.06  4938.9  356.29
  4993.1  355.54  4999.8  349.06  5000.4  348.26  5007.7  349.06  5013.2  353.99
  5019.1  356.33  5085.1  354.73  5143.5  357.57  5286.8  359.18  5296.2  361.74
  5302.1  359.91  5323.3  359.12  5416.2  360.19  5473.2  362.67  5490.8  361.08
  5519.4  353.70  5554.1  355.90  5714.4  364.03  5861.4  376.71  5933.6  382.90
#Mann=13,-1,0
  4283.1    0.16       0  4458.8    0.05       0  4637.8    0.16       0
  4839.4    0.12       0  4938.9    0.16       0  4999.8    0.07       0
  5007.7    0.16       0  5085.1    0.05       0  5416.2    0.08       0
  5473.2     0.1       0  5519.4    0.08       0  5714.4    0.05       0
  5861.4    0.08       0
Bank Sta=4726,5554.1
Exp/Cntr=0.3,0.1

Type RM Length L Ch R = 1,2640,1036,1036,1036
BEGIN DESCRIPTION:
Mapping XS 6f72ee3b
END DESCRIPTION:
XS GIS Cut Line= 4
      2884338.80      6989776.71      2884000.25      6988904.31
      2883010.67      6989086.60      2882567.95      6990896.53
#Sta/Elev= 30
  3322.2  392.27  3482.1  391.73  3645.5  396.68  3844.2  393.27  3928.5  389.08
  4230.7  355.87  4324.3  358.79  4447.1  357.63  4513.4  356.74  4560.8  356.36
  4622.4  355.68  4671.1  350.58  4728.5  347.70  5004.8  347.34  5005.5  346.54
  5012.8  347.34  5339.6  349.52  5486.8  350.58  5812.9  355.11  6403.6  357.21
  6508.2  361.64  6549.4  355.49  6568.3  358.13  6573.5  355.78  6609.9  360.80
  6669.2  361.69  6740.0  360.60  6852.9  367.83  6865.5  368.67  7127.5  383.16
#Mann=12,-1,0
  3322.2    0.16       0  4447.1    0.12       0  4513.4    0.16       0
  4560.8    0.12       0  5004.8    0.07       0  5012.8    0.12       0
  5339.6    0.16       0  5812.9    0.05       0  6403.6    0.08       0
  6669.2    0.05       0  6852.9    0.08       0  6865.5    0.05       0
Bank Sta=4671.1,5486.8
Exp/Cntr=0.3,0.1

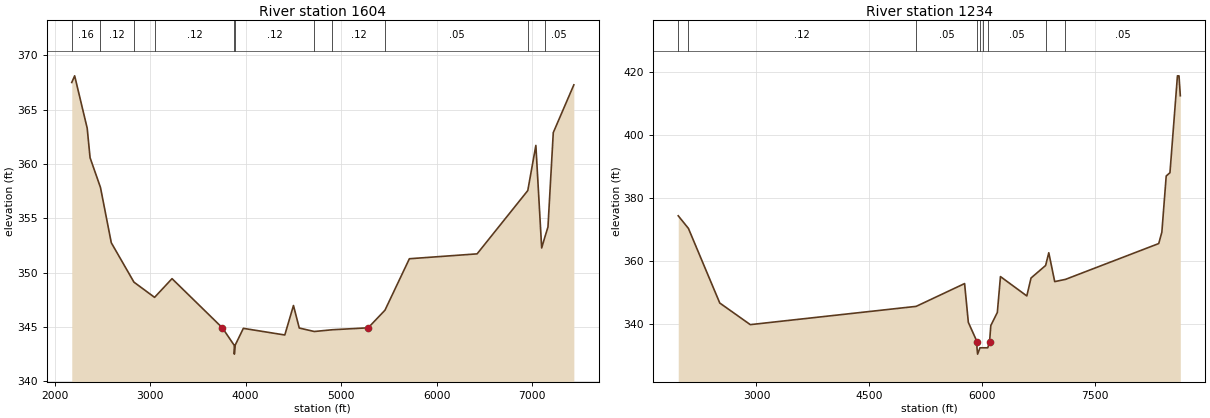
Type RM Length L Ch R = 1,1604,370,370,370
BEGIN DESCRIPTION:
RAINWATER CREEK 2.0
END DESCRIPTION:
XS GIS Cut Line= 3
      2885725.02      6988575.00      2882925.00      6988175.00
      2882524.99      6990575.05
#Sta/Elev= 30
  2177.7  367.49  2208.0  368.10  2339.3  363.29  2369.6  360.57  2478.7  357.83
  2591.9  352.75  2829.3  349.13  3045.5  347.73  3228.3  349.45  3755.9  344.93
  3880.9  343.31  3881.5  342.51  3888.9  343.31  3975.8  344.88  4410.2  344.27
  4501.1  346.98  4561.7  344.91  4719.3  344.59  4906.5  344.75  5283.9  344.93
  5460.0  346.55  5715.8  351.28  6425.5  351.73  6956.6  357.55  7041.3  361.70
  7102.2  352.27  7132.8  353.19  7168.1  354.20  7223.8  362.88  7439.3  367.27
#Mann=11,-1,0
  2177.7    0.16       0  2478.7    0.12       0  2829.3    0.16       0
  3045.5    0.12       0  3880.9    0.07       0  3888.9    0.12       0
  4719.3    0.07       0  4906.5    0.12       0  5460.0    0.05       0
  6956.6    0.08       0  7132.8    0.05       0
Bank Sta=3755.9,5283.9
Exp/Cntr=0.3,0.1

Type RM Length L Ch R = 1,1234,0,0,0
BEGIN DESCRIPTION:
RAINWATER CREEK 1.0
END DESCRIPTION:
XS GIS Cut Line= 3
      2885774.96      6987275.01      2882791.76      6987856.79
      2880557.23      6990720.95
#Sta/Elev= 30
  1960.6  374.37  2095.8  370.39  2512.5  346.78  2918.3  339.94  5122.7  345.72
  5766.0  352.93  5815.8  340.66  5930.1  334.60  5930.6  332.61  5939.1  330.61
  5970.5  332.61  6008.4  332.61  6073.9  332.61  6098.2  334.60  6114.3  339.64
  6201.1  343.79  6242.7  355.14  6592.8  349.02  6648.9  354.69  6842.7  358.65
  6884.9  362.68  6963.6  353.55  7106.9  354.26  8345.8  365.59  8387.4  369.18
  8445.3  386.96  8495.1  388.00  8594.6  418.65  8615.4  418.64  8632.7  412.36
#Mann=9,-1,0
  1960.6    0.16       0  2095.8    0.12       0  5122.7    0.05       0
  5930.6    0.07       0  5970.5    0.05       0  6008.4    0.07       0
  6073.9    0.05       0  6842.7    0.08       0  7106.9    0.05       0
Bank Sta=5930.1,6098.2
Exp/Cntr=0.3,0.1

Chan Stop Cuts=-1