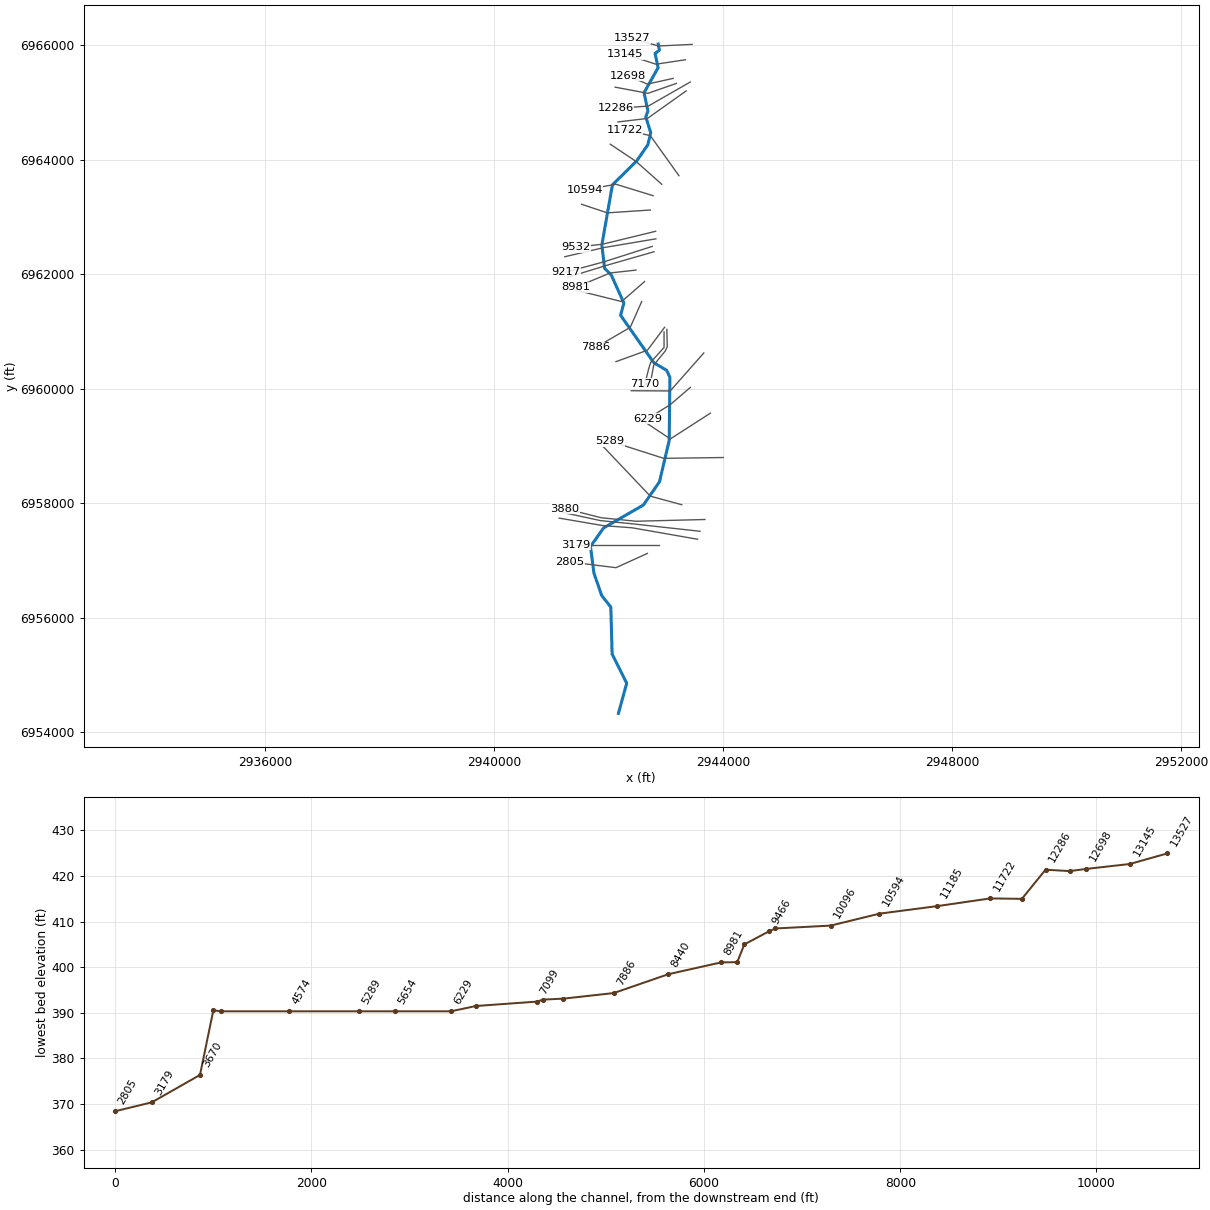
--- RED BRANCH.prj (project) ---

Proj Title=RED BRANCH Base Level Engineering
Current Plan=p01
Default Exp/Contr=0.3,0.1
English Units
Geom File=g01
Flow File=f01
Plan File=p01
BEGIN DESCRIPTION:
RED BRANCH
END DESCRIPTION:

--- RED BRANCH.p01 (plan) ---

Plan Title=Multiple Run
Short Identifier=Multiple
Geom File=g01
Flow File=f01
Subcritical Flow
K Sum by GR= 0
Std Step Tol= 0.01
Critical Tol= 0.01
Num of Std Step Trials= 20
Max Error Tol= 0.3
Flow Tol Ratio= 0.001
Split Flow NTrial= 30
Split Flow Tol= 0.02
Split Flow Ratio= 0.02
Log Output Level= 0
Friction Slope Method= 1
Unsteady Friction Slope Method= 2
Unsteady Bridges Friction Slope Method= 1
Parabolic Critical Depth
Global Vel Dist=  1 , 1 , 1
Global Log Level= 0
CheckData=True
Encroach Param= -1, 0, 0, 0
BEGIN DESCRIPTION:
Multiple Run
END DESCRIPTION:

--- RED BRANCH.f01 (steady flow) ---

Flow Title=Multiple
Number of Profiles=7
Profile Names=10-year,25-year,50-year,1pct_min,100-year,1pct_plu,500-year
River Rch & RM= RED BRANCH,Reach-1,13527
     601     811     984     594    1186    2366    1723
River Rch & RM= RED BRANCH,Reach-1,11722
     917    1264    1554     949    1894    3780    2820
River Rch & RM= RED BRANCH,Reach-1,5289
    1178    1642    2035    1251    2496    4980    3765
River Rch & RM= RED BRANCH,Reach-1,3880
    1272    1783    2216    1367    2727    5441    4139
Boundary for River Rch & Prof#=RED BRANCH,Reach-1,1
Up Type=0
Dn Type=3
Dn Slope=0.005
Boundary for River Rch & Prof#=RED BRANCH,Reach-1,2
Up Type=0
Dn Type=3
Dn Slope=0.005
Boundary for River Rch & Prof#=RED BRANCH,Reach-1,3
Up Type=0
Dn Type=3
Dn Slope=0.005
Boundary for River Rch & Prof#=RED BRANCH,Reach-1,4
Up Type=0
Dn Type=3
Dn Slope=0.005
Boundary for River Rch & Prof#=RED BRANCH,Reach-1,5
Up Type=0
Dn Type=3
Dn Slope=0.005
Boundary for River Rch & Prof#=RED BRANCH,Reach-1,6
Up Type=0
Dn Type=3
Dn Slope=0.005
Boundary for River Rch & Prof#=RED BRANCH,Reach-1,7
Up Type=0
Dn Type=3
Dn Slope=0.005

--- RED BRANCH.g01 (geometry) ---

Geom Title=Existing Conditions

River Reach=RED BRANCH,Reach-1
Reach XY= 30
      2942864.93      6966025.87      2942883.39      6965916.36
      2942807.93      6965861.06      2942861.95      6965612.34
      2942616.20      6965175.45      2942683.31      6964855.31
      2942646.38      6964750.12      2942732.55      6964474.96
      2942683.23      6964266.17      2942488.11      6963983.12
      2942062.85      6963563.70      2941878.80      6962515.84
      2941926.77      6962106.23      2942044.47      6961986.90
      2942263.12      6961499.27      2942205.79      6961285.74
      2942787.39      6960455.77      2943011.68      6960323.06
      2943067.90      6960200.78      2943055.59      6959098.44
      2942885.48      6958375.52      2942604.23      6957969.70
      2941909.79      6957570.39      2941679.75      6957244.87
      2941740.52      6956780.46      2941875.07      6956389.84
      2942035.66      6956185.85      2942057.86      6955366.55
      2942312.70      6954855.25      2942168.31      6954329.47

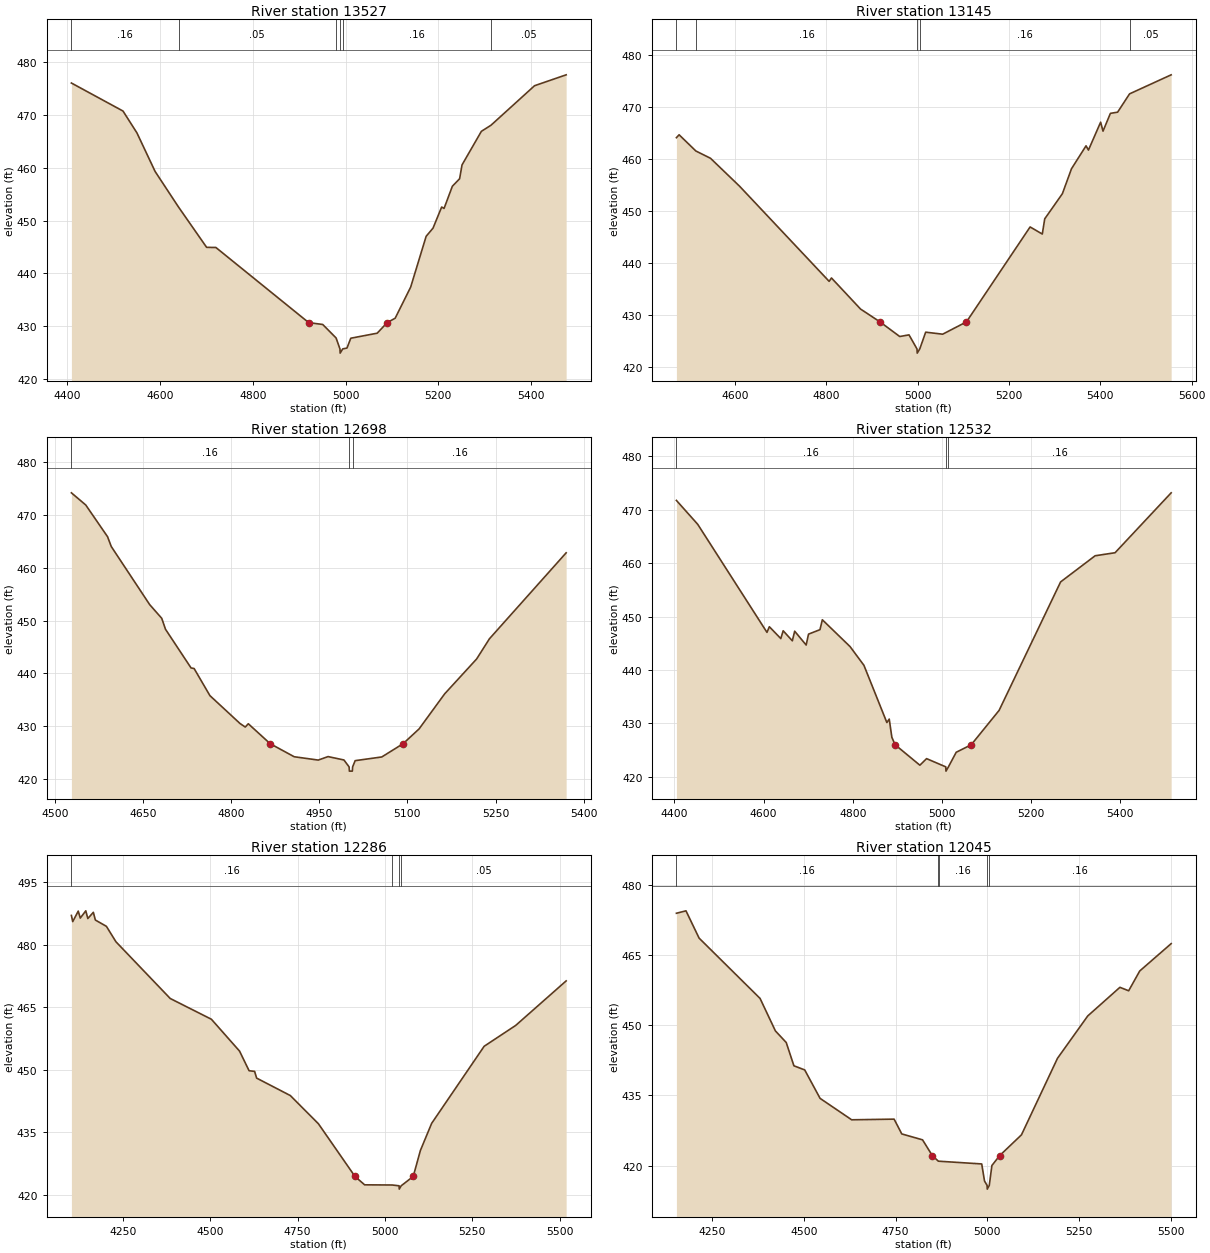
Type RM Length L Ch R = 1,13527,382,382,382
BEGIN DESCRIPTION:
RED BRANCH 24.0
END DESCRIPTION:
XS GIS Cut Line= 3
      2943456.04      6966018.67      2942865.89      6965990.93
      2942409.66      6966124.57
#Sta/Elev= 30
  4409.2  476.02  4520.4  470.72  4550.4  466.59  4589.6  459.29  4640.0  452.57
  4700.6  444.94  4720.6  444.91  4920.6  430.70  4950.8  430.35  4979.6  427.80
  4987.9  425.73  4988.4  424.93  4993.9  425.73  5003.1  425.89  5011.3  427.75
  5068.2  428.70  5089.7  430.70  5106.9  431.53  5140.3  437.41  5173.7  447.03
  5188.5  448.57  5207.1  452.56  5212.3  452.30  5230.2  456.50  5245.8  457.91
  5251.0  460.53  5292.7  466.88  5313.5  468.04  5407.3  475.51  5475.4  477.57
#Mann=6,-1,0
  4409.2    0.16       0  4640.0    0.05       0  4979.6    0.16       0
  4987.9    0.07       0  4993.9    0.16       0  5313.5    0.05       0
Bank Sta=4920.6,5089.7
Exp/Cntr=0.3,0.1

Type RM Length L Ch R = 1,13145,447,447,447
BEGIN DESCRIPTION:
Mapping XS 12aa95bb
END DESCRIPTION:
XS GIS Cut Line= 3
      2943338.83      6965750.43      2942823.25      6965672.32
      2942288.39      6965846.28
#Sta/Elev= 30
  4471.2  464.15  4477.1  464.71  4513.9  461.58  4545.9  460.18  4609.6  454.79
  4805.8  436.45  4810.9  437.10  4874.6  431.11  4917.3  428.63  4960.5  425.81
  4980.8  426.13  4998.3  423.41  4998.8  422.61  5004.3  423.41  5017.3  426.65
  5054.5  426.26  5106.6  428.63  5246.1  446.94  5272.8  445.57  5278.1  448.50
  5316.8  453.35  5336.7  458.15  5368.6  462.58  5373.9  461.76  5400.6  467.14
  5405.8  465.41  5422.0  468.84  5437.8  469.07  5464.0  472.60  5555.1  476.27
#Mann=5,-1,0
  4471.2    0.05       0  4513.9    0.16       0  4998.3    0.07       0
  5004.3    0.16       0  5464.0    0.05       0
Bank Sta=4917.3,5106.6
Exp/Cntr=0.3,0.1

Type RM Length L Ch R = 1,12698,166,166,166
BEGIN DESCRIPTION:
RED BRANCH 23.0
END DESCRIPTION:
XS GIS Cut Line= 3
      2943125.04      6965425.01      2942675.00      6965325.00
      2942325.01      6965475.00
#Sta/Elev= 30
  4528.3  474.17  4552.7  471.87  4589.8  465.87  4596.2  464.00  4661.5  453.02
  4682.0  450.43  4688.4  448.36  4731.9  441.04  4737.1  440.93  4764.0  435.80
  4815.2  430.53  4824.1  429.86  4829.3  430.48  4866.5  426.71  4907.4  424.24
  4948.3  423.61  4965.0  424.27  4992.0  423.63  5000.8  422.32  5001.3  421.52
  5006.3  421.52  5006.8  422.32  5011.1  423.50  5056.4  424.20  5092.7  426.71
  5119.9  429.51  5163.4  436.14  5217.8  442.74  5239.6  446.56  5370.1  462.82
#Mann=3,-1,0
  4528.3    0.16       0  5000.8    0.07       0  5006.8    0.16       0
Bank Sta=4866.5,5092.7
Exp/Cntr=0.3,0.1

Type RM Length L Ch R = 1,12532,246,246,246
BEGIN DESCRIPTION:
Mapping XS 294915af
END DESCRIPTION:
XS GIS Cut Line= 3
      2943180.88      6965337.24      2942684.36      6965163.64
      2942111.48      6965271.27
#Sta/Elev= 30
  4404.8  471.76  4452.6  467.28  4607.8  447.04  4613.1  448.10  4638.8  445.88
  4644.1  447.34  4664.6  445.46  4669.9  447.26  4695.6  444.67  4700.9  446.71
  4726.6  447.55  4731.9  449.40  4794.0  444.38  4825.1  440.87  4876.5  430.15
  4881.8  430.80  4887.7  427.38  4895.0  425.99  4950.5  422.16  4965.5  423.39
  5008.5  421.85  5009.0  421.05  5014.5  421.85  5031.9  424.58  5065.6  425.99
  5128.1  432.43  5265.9  456.49  5343.3  461.39  5388.0  461.96  5513.7  473.18
#Mann=3,-1,0
  4404.8    0.16       0  5008.5    0.07       0  5014.5    0.16       0
Bank Sta=4895,5065.6
Exp/Cntr=0.3,0.1

Type RM Length L Ch R = 1,12286,241,241,241
BEGIN DESCRIPTION:
Mapping XS fedf7e74
END DESCRIPTION:
XS GIS Cut Line= 3
      2943423.94      6965361.55      2942691.30      6964941.41
      2942120.96      6964899.93
#Sta/Elev= 30
  4102.6  487.01  4106.4  485.53  4122.2  488.05  4128.0  486.38  4143.8  488.12
  4149.6  486.27  4165.4  487.76  4171.2  485.91  4202.8  484.40  4230.1  480.70
  4385.5  467.09  4503.4  462.11  4584.0  454.47  4611.3  449.76  4627.1  449.60
  4632.9  447.99  4729.3  443.81  4809.8  437.04  4914.5  424.40  4942.1  422.39
  5020.6  422.35  5040.7  422.16  5041.2  421.36  5046.7  422.16  5081.2  424.40
  5101.7  430.62  5133.9  437.13  5284.3  455.63  5374.6  460.63  5519.0  471.31
#Mann=4,-1,0
  4102.6    0.16       0  5020.6    0.05       0  5040.7    0.07       0
  5046.7    0.05       0
Bank Sta=4914.5,5081.2
Exp/Cntr=0.3,0.1

Type RM Length L Ch R = 1,12045,323,323,323
BEGIN DESCRIPTION:
RED BRANCH 22.0
END DESCRIPTION:
XS GIS Cut Line= 3
      2943351.04      6965205.31      2942675.00      6964725.00
      2942160.04      6964663.63
#Sta/Elev= 30
  4152.7  473.90  4178.8  474.42  4214.5  468.59  4380.6  455.71  4422.4  448.77
  4451.9  446.29  4472.8  441.32  4502.3  440.43  4544.1  434.36  4630.2  429.78
  4745.8  429.92  4766.7  426.76  4823.3  425.50  4849.9  422.13  4866.2  420.95
  4868.0  420.93  4984.5  420.35  4992.1  416.70  4999.1  415.77  4999.6  414.97
  5005.1  415.77  5012.2  420.01  5033.4  422.13  5092.8  426.57  5190.9  442.91
  5273.4  451.97  5361.0  458.08  5384.8  457.34  5415.0  461.57  5500.6  467.41
#Mann=5,-1,0
  4152.7    0.16       0  4866.2    0.12       0  4868.0    0.16       0
  4999.1    0.07       0  5005.1    0.16       0
Bank Sta=4849.9,5033.4
Exp/Cntr=0.3,0.1

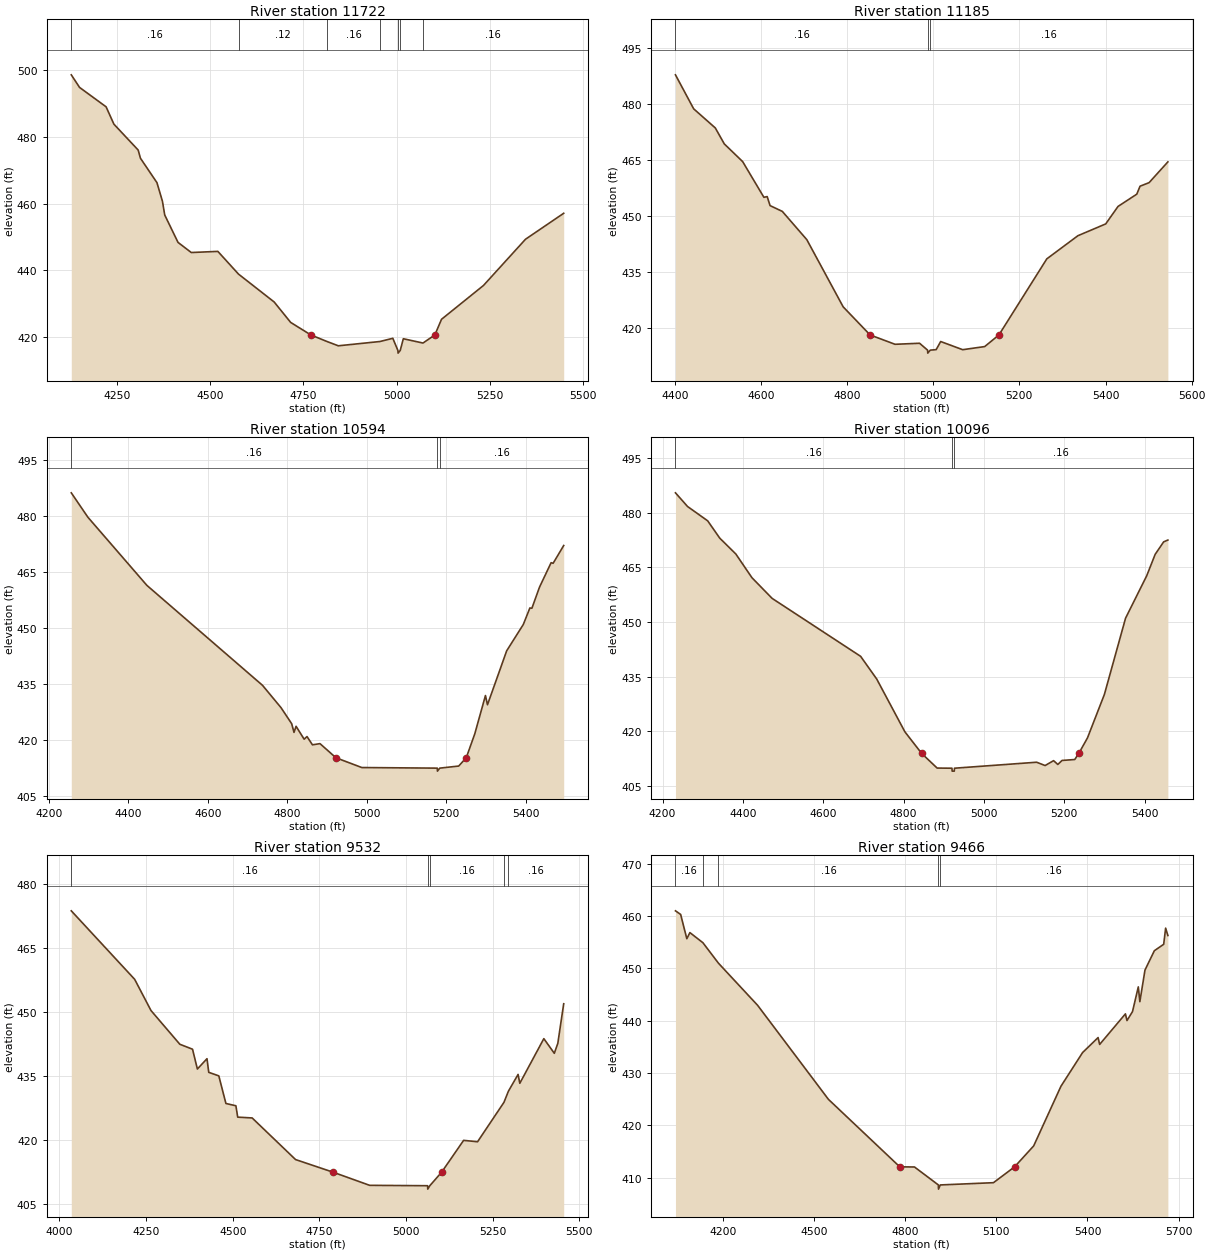
Type RM Length L Ch R = 1,11722,537,537,537
BEGIN DESCRIPTION:
RED BRANCH 21.0
END DESCRIPTION:
XS GIS Cut Line= 3
      2943225.02      6963724.97      2942725.00      6964425.00
      2942274.95      6964525.01
#Sta/Elev= 30
  4127.2  498.66  4149.4  494.88  4220.6  489.05  4241.5  483.85  4306.7  476.06
  4312.8  473.60  4357.0  466.28  4371.8  460.69  4377.9  456.57  4413.6  448.32
  4449.2  445.28  4520.5  445.62  4575.9  438.80  4671.6  430.42  4715.9  424.28
  4770.1  420.52  4813.6  418.54  4843.7  417.26  4955.4  418.55  4990.0  419.51
  5003.6  415.86  5004.1  415.06  5009.8  415.86  5018.2  419.38  5070.9  418.09
  5102.8  420.52  5120.6  425.22  5233.3  435.39  5346.0  449.27  5448.5  457.07
#Mann=7,-1,0
  4127.2    0.16       0  4575.9    0.12       0  4813.6    0.16       0
  4955.4    0.12       0  5003.6    0.07       0  5009.8    0.12       0
  5070.9    0.16       0
Bank Sta=4770.1,5102.8
Exp/Cntr=0.3,0.1

Type RM Length L Ch R = 1,11185,591,591,591
BEGIN DESCRIPTION:
RED BRANCH 20.0
END DESCRIPTION:
XS GIS Cut Line= 3
      2942925.04      6963574.97      2942475.00      6963975.00
      2942024.97      6964275.02
#Sta/Elev= 30
  4401.8  487.77  4444.1  478.68  4494.3  473.57  4515.2  469.30  4557.8  464.57
  4607.1  455.03  4614.7  455.22  4621.4  452.81  4649.8  451.27  4706.7  443.71
  4791.1  425.75  4853.6  418.24  4911.5  415.74  4968.4  416.02  4987.0  414.18
  4987.5  413.38  4993.3  414.18  5006.9  414.31  5017.4  416.48  5068.5  414.30
  5119.6  415.13  5152.6  418.24  5263.8  438.58  5335.9  444.76  5400.5  447.92
  5429.1  452.59  5472.6  455.87  5480.2  458.00  5501.2  458.95  5544.8  464.50
#Mann=3,-1,0
  4401.8    0.16       0  4987.0    0.07       0  4993.3    0.16       0
Bank Sta=4853.6,5152.6
Exp/Cntr=0.3,0.1

Type RM Length L Ch R = 1,10594,498,498,498
BEGIN DESCRIPTION:
RED BRANCH 19.0
END DESCRIPTION:
XS GIS Cut Line= 3
      2942774.96      6963375.01      2942125.00      6963575.00
      2941575.05      6963475.01
#Sta/Elev= 30
  4256.8  486.21  4298.6  479.68  4447.0  461.44  4738.0  434.68  4784.5  428.71
  4811.3  424.42  4817.2  422.09  4822.4  423.72  4842.7  420.27  4849.9  420.97
  4863.6  418.76  4882.6  419.08  4922.7  415.30  4987.7  412.68  5177.6  412.52
  5178.1  411.72  5183.9  412.52  5231.6  413.08  5250.6  415.30  5272.2  421.75
  5298.9  431.95  5304.0  429.48  5352.3  443.92  5394.2  450.98  5410.7  455.39
  5415.8  455.32  5434.9  460.96  5464.1  467.51  5469.2  467.35  5495.8  472.11
#Mann=3,-1,0
  4256.8    0.16       0  5177.6    0.07       0  5183.9    0.16       0
Bank Sta=4922.7,5250.6
Exp/Cntr=0.3,0.1

Type RM Length L Ch R = 1,10096,564,564,564
BEGIN DESCRIPTION:
RED BRANCH 18.0
END DESCRIPTION:
XS GIS Cut Line= 3
      2942725.03      6963125.00      2941975.00      6963075.00
      2941525.03      6963224.99
#Sta/Elev= 30
  4232.0  485.44  4262.1  481.69  4312.2  477.76  4342.3  473.01  4382.4  468.65
  4422.4  462.16  4472.6  456.49  4693.0  440.59  4733.1  434.36  4803.3  419.87
  4845.1  413.94  4883.5  409.94  4920.4  409.90  4920.9  409.10  4926.2  409.10
  4926.7  409.90  5131.3  411.54  5152.3  410.63  5173.4  411.97  5184.0  410.93
  5194.5  412.03  5226.1  412.28  5236.1  413.94  5257.8  418.21  5299.9  430.13
  5352.6  451.04  5405.3  462.69  5426.4  468.58  5447.5  471.99  5458.0  472.49
#Mann=3,-1,0
  4232.0    0.16       0  4920.4    0.07       0  4926.7    0.16       0
Bank Sta=4845.1,5236.1
Exp/Cntr=0.3,0.1

Type RM Length L Ch R = 1,9532,66,66,66
BEGIN DESCRIPTION:
Mapping XS 0c4b0923
END DESCRIPTION:
XS GIS Cut Line= 3
      2942818.39      6962753.03      2941891.33      6962527.34
      2941428.06      6962475.49
#Sta/Elev= 30
  4034.4  473.81  4217.2  457.73  4264.3  450.40  4347.5  442.48  4384.1  441.32
  4398.1  436.67  4425.8  439.09  4430.9  435.89  4459.9  435.06  4480.4  428.58
  4509.2  428.04  4514.4  425.37  4556.1  425.18  4681.3  415.41  4790.4  412.42
  4895.0  409.36  5062.1  409.27  5062.6  408.47  5068.5  409.27  5102.4  412.42
  5166.0  419.92  5206.2  419.59  5282.4  428.85  5295.2  431.46  5323.1  435.40
  5328.1  433.32  5397.4  443.80  5427.6  440.36  5437.7  442.69  5454.7  451.99
#Mann=5,-1,0
  4034.4    0.16       0  5062.1    0.07       0  5068.5    0.16       0
  5282.4     0.1       0  5295.2    0.16       0
Bank Sta=4790.4,5102.4
Exp/Cntr=0.3,0.1

Type RM Length L Ch R = 1,9466,249,249,249
BEGIN DESCRIPTION:
Mapping XS 707fe614
END DESCRIPTION:
XS GIS Cut Line= 3
      2942821.85      6962621.09      2941912.16      6962468.32
      2941231.58      6962308.59
#Sta/Elev= 30
  4043.3  461.00  4060.4  460.31  4080.7  455.67  4090.8  456.84  4133.6  454.91
  4184.8  451.00  4313.9  442.94  4547.1  424.97  4782.0  412.08  4830.4  412.05
  4909.0  408.62  4909.5  407.82  4915.4  408.62  5090.4  409.05  5160.1  412.08
  5222.9  416.08  5312.8  427.49  5384.0  433.92  5435.0  436.78  5440.1  435.47
  5525.0  441.31  5530.1  440.03  5548.3  441.74  5567.4  446.47  5572.5  443.64
  5589.4  449.68  5620.2  453.37  5651.0  454.61  5657.4  457.69  5664.8  456.28
#Mann=5,-1,0
  4043.3    0.16       0  4133.6    0.08       0  4184.8    0.16       0
  4909.0    0.07       0  4915.4    0.16       0
Bank Sta=4782,5160.1
Exp/Cntr=0.3,0.1

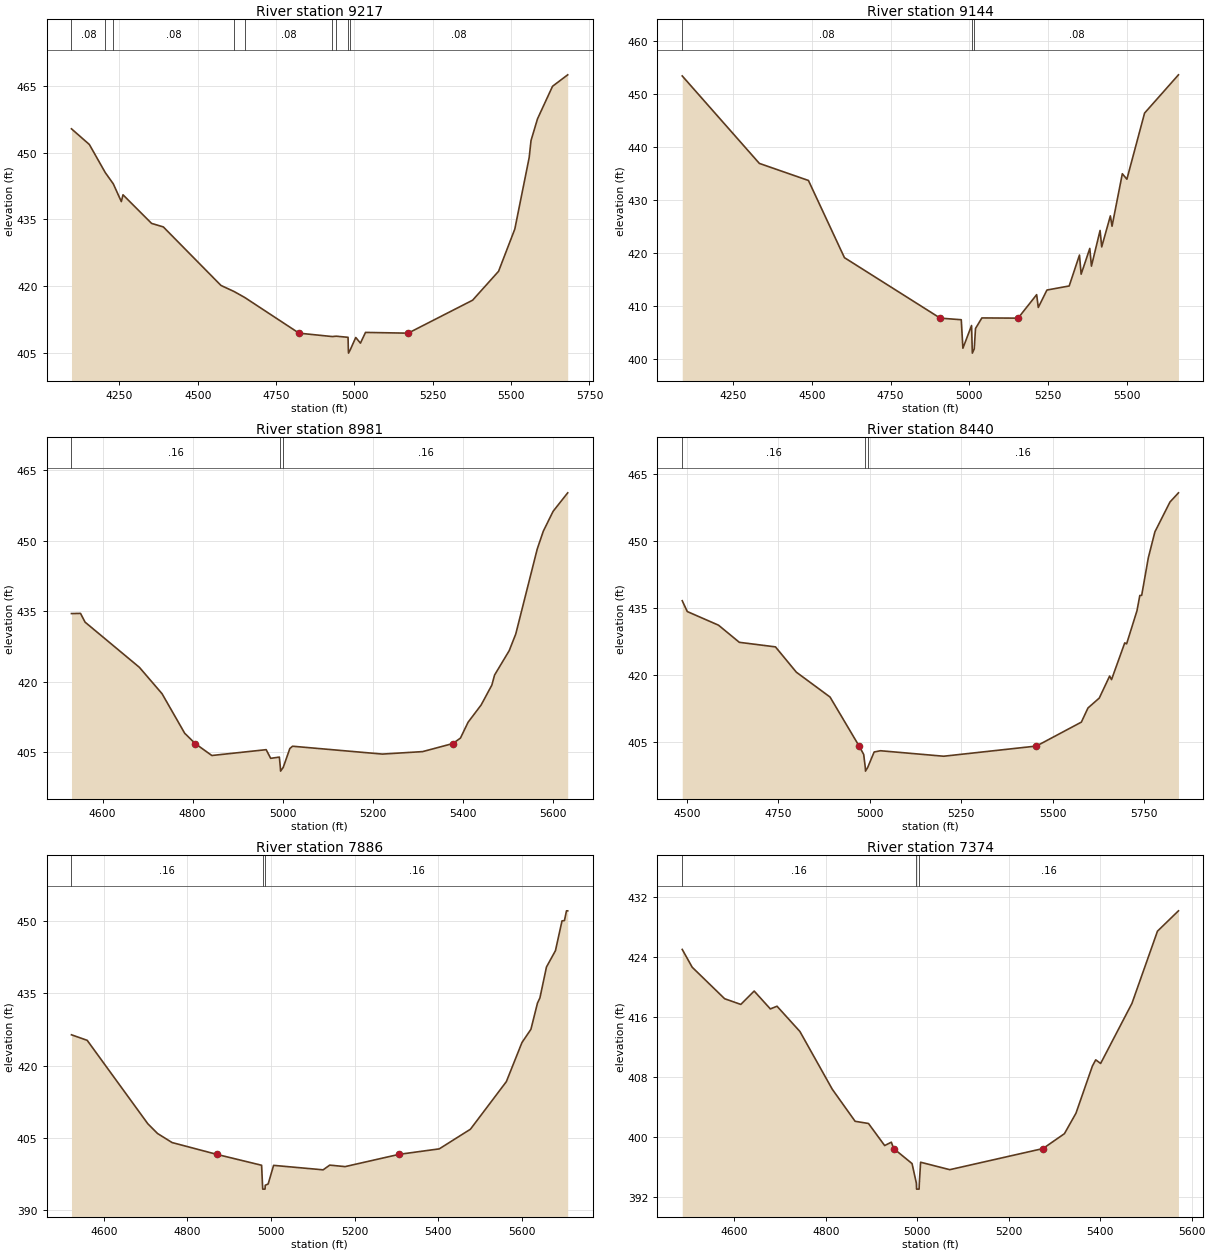
Type RM Length L Ch R = 1,9217,73,73,73
BEGIN DESCRIPTION:
Mapping XS 23e9a709
END DESCRIPTION:
XS GIS Cut Line= 3
      2942759.40      6962489.15      2941912.16      6962218.32
      2941242.03      6962037.76
#Sta/Elev= 30
  4097.0  455.33  4154.1  451.81  4204.7  445.52  4230.6  442.96  4256.1  438.99
  4261.4  440.52  4352.6  434.10  4390.1  433.31  4574.1  420.17  4616.5  418.79
  4649.9  417.47  4823.2  409.46  4929.0  408.70  4942.1  408.78  4979.6  408.53
  4980.5  405.78  4981.0  404.98  4986.9  405.78  5004.2  408.49  5019.1  407.22
  5035.3  409.63  5171.2  409.46  5377.1  416.86  5459.9  423.35  5511.7  432.82
  5557.5  448.85  5563.5  452.71  5584.2  457.58  5632.1  464.88  5680.5  467.45
#Mann=9,-1,0
  4097.0    0.08       0  4204.7    0.16       0  4230.6    0.08       0
  4616.5    0.16       0  4649.9    0.08       0  4929.0    0.16       0
  4942.1    0.08       0  4980.5    0.07       0  4986.9    0.08       0
Bank Sta=4823.2,5171.2
Exp/Cntr=0.3,0.1

Type RM Length L Ch R = 1,9144,163,163,163
BEGIN DESCRIPTION:
Mapping XS 87643f32
END DESCRIPTION:
XS GIS Cut Line= 3
      2942790.59      6962395.39      2941978.13      6962162.76
      2941278.36      6961947.98
#Sta/Elev= 30
  4087.8  453.37  4332.9  436.87  4488.9  433.65  4603.3  419.09  4907.7  407.68
  4974.6  407.38  4979.8  402.00  5007.3  406.29  5009.4  401.88  5009.9  401.08
  5015.8  401.88  5019.9  405.73  5040.1  407.72  5155.1  407.68  5214.2  412.11
  5219.4  409.70  5246.9  412.98  5317.6  413.75  5350.3  419.58  5355.6  415.97
  5383.1  420.83  5388.3  417.49  5415.8  424.22  5421.0  421.12  5448.5  426.97
  5453.8  425.02  5486.5  434.92  5501.0  433.89  5557.2  446.36  5664.9  453.58
#Mann=3,-1,0
  4087.8    0.08       0  5009.4    0.07       0  5015.8    0.08       0
Bank Sta=4907.7,5155.1
Exp/Cntr=0.3,0.1

Type RM Length L Ch R = 1,8981,541,541,541
BEGIN DESCRIPTION:
RED BRANCH 16.0
END DESCRIPTION:
XS GIS Cut Line= 3
      2942475.03      6962075.00      2942025.00      6962025.00
      2941425.00      6961775.00
#Sta/Elev= 30
  4530.7  434.52  4550.8  434.56  4560.9  432.70  4681.6  423.10  4732.0  417.49
  4782.3  409.09  4805.5  406.91  4842.6  404.36  4963.4  405.60  4973.4  403.76
  4992.7  404.02  4994.9  401.84  4995.4  401.04  5001.3  401.84  5016.0  405.84
  5022.0  406.33  5221.8  404.66  5311.2  405.19  5378.5  406.91  5395.2  408.07
  5412.0  411.41  5441.2  415.11  5465.0  419.34  5471.0  421.46  5503.5  426.64
  5518.1  430.19  5565.8  448.24  5579.3  452.03  5601.0  456.24  5633.5  460.18
#Mann=3,-1,0
  4530.7    0.16       0  4994.9    0.07       0  5001.3    0.16       0
Bank Sta=4805.5,5378.5
Exp/Cntr=0.3,0.1

Type RM Length L Ch R = 1,8440,554,554,554
BEGIN DESCRIPTION:
RED BRANCH 15.0
END DESCRIPTION:
XS GIS Cut Line= 3
      2942625.01      6961875.01      2942225.00      6961525.00
      2941425.04      6961724.99
#Sta/Elev= 30
  4487.2  436.62  4501.0  434.20  4586.4  431.14  4643.3  427.30  4742.0  426.28
  4799.0  420.61  4891.1  415.04  4970.6  404.05  4983.1  402.17  4987.5  399.23
  4988.0  398.43  4993.9  399.23  5011.6  402.72  5029.0  403.00  5201.7  401.77
  5455.1  404.05  5577.9  409.41  5596.0  412.58  5626.9  414.81  5655.2  419.74
  5660.4  418.94  5696.5  427.18  5701.6  426.96  5730.0  434.40  5737.7  437.80
  5742.8  437.83  5760.9  446.24  5778.9  452.06  5820.1  458.75  5843.3  460.81
#Mann=3,-1,0
  4487.2    0.16       0  4987.5    0.07       0  4993.9    0.16       0
Bank Sta=4970.6,5455.1
Exp/Cntr=0.3,0.1

Type RM Length L Ch R = 1,7886,512,512,512
BEGIN DESCRIPTION:
RED BRANCH 14.0
END DESCRIPTION:
XS GIS Cut Line= 3
      2942574.99      6961524.97      2942375.00      6961075.00
      2941775.03      6960725.02
#Sta/Elev= 30
  4522.9  426.39  4560.5  425.24  4705.5  407.90  4728.7  405.88  4763.6  403.99
  4870.3  401.54  4977.7  399.27  4979.9  395.11  4980.4  394.31  4985.9  394.31
  4986.4  395.11  4993.4  395.38  5006.4  399.25  5124.9  398.32  5140.6  399.30
  5177.4  398.99  5306.5  401.54  5402.7  402.68  5477.2  406.76  5563.2  416.66
  5600.4  424.77  5621.9  427.53  5637.6  432.98  5643.4  434.05  5659.1  440.48
  5680.6  443.88  5696.3  450.07  5702.1  450.13  5707.0  452.16  5709.9  452.16
#Mann=3,-1,0
  4522.9    0.16       0  4979.9    0.07       0  4986.4    0.16       0
Bank Sta=4870.3,5306.5
Exp/Cntr=0.3,0.1

Type RM Length L Ch R = 1,7374,204,204,204
BEGIN DESCRIPTION:
RED BRANCH 13.0
END DESCRIPTION:
XS GIS Cut Line= 3
      2942974.98      6961074.98      2942675.00      6960675.00
      2942125.01      6960475.00
#Sta/Elev= 30
  4486.0  425.00  4507.8  422.63  4578.7  418.44  4614.1  417.68  4643.3  419.46
  4678.7  417.08  4693.3  417.44  4743.3  414.08  4814.1  406.39  4864.1  402.12
  4893.3  401.83  4928.7  398.89  4943.3  399.34  4948.4  398.49  4988.6  396.49
  4998.0  393.89  4998.5  393.09  5004.0  393.09  5004.5  393.89  5007.3  396.67
  5071.1  395.68  5274.9  398.49  5321.8  400.47  5347.1  403.20  5383.0  409.48
  5390.3  410.30  5401.0  409.82  5469.5  417.82  5525.3  427.43  5571.2  430.14
#Mann=3,-1,0
  4486.0    0.16       0  4998.0    0.07       0  5004.5    0.16       0
Bank Sta=4948.4,5274.9
Exp/Cntr=0.3,0.1

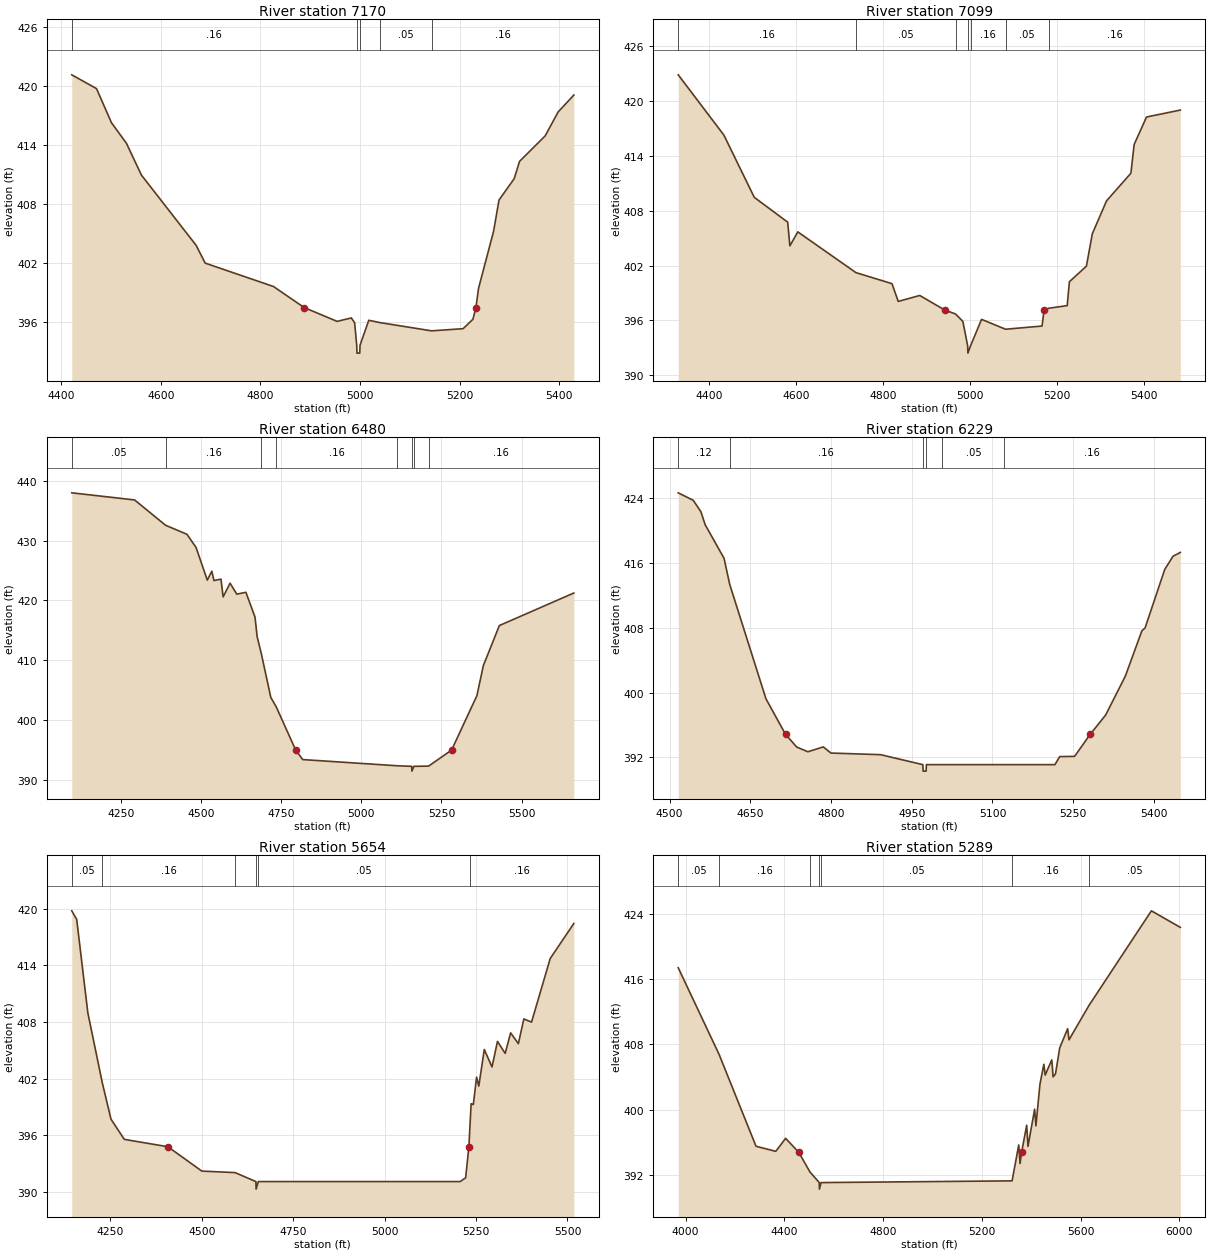
Type RM Length L Ch R = 1,7170,71,71,71
BEGIN DESCRIPTION:
Mapping XS dbda5b98
END DESCRIPTION:
XS GIS Cut Line= 5
      2942965.63      6960994.74      2942965.63      6960723.87
      2942732.99      6960463.45      2942698.27      6960355.82
      2942632.48      6960089.18
#Sta/Elev= 30
  4421.5  421.11  4471.2  419.71  4501.2  416.25  4531.2  414.17  4561.2  410.95
  4671.2  403.81  4689.3  402.01  4826.3  399.64  4888.1  397.50  4954.2  396.10
  4982.6  396.45  4989.3  395.96  4993.5  393.68  4994.0  392.88  4999.6  392.88
  5000.1  393.68  5017.7  396.21  5039.8  395.98  5143.8  395.14  5207.0  395.36
  5226.7  396.31  5232.8  397.50  5237.9  399.43  5268.2  405.24  5279.1  408.41
  5309.6  410.58  5320.3  412.33  5371.8  414.92  5397.7  417.34  5429.3  419.06
#Mann=5,-1,0
  4421.5    0.16       0  4993.5    0.07       0  5000.1    0.16       0
  5039.8    0.05       0  5143.8    0.16       0
Bank Sta=4888.1,5232.8
Exp/Cntr=0.3,0.1

Type RM Length L Ch R = 1,7099,619,619,619
BEGIN DESCRIPTION:
Mapping XS 672dcade
END DESCRIPTION:
XS GIS Cut Line= 6
      2943014.24      6961039.84      2943021.19      6960734.29
      2942986.46      6960661.37      2942785.08      6960414.84
      2942736.46      6960154.43      2942599.13      6960030.82
#Sta/Elev= 30
  4329.6  422.84  4434.5  416.26  4504.5  409.45  4581.3  406.74  4586.3  404.15
  4604.5  405.68  4738.1  401.23  4821.1  400.02  4835.4  398.08  4884.9  398.73
  4942.4  397.14  4967.1  396.71  4984.0  395.90  4995.1  393.23  4995.6  392.43
  5001.7  393.23  5027.1  396.12  5082.1  395.04  5166.1  395.39  5170.8  397.14
  5182.1  397.34  5223.9  397.62  5229.0  400.23  5268.1  401.93  5281.7  405.47
  5314.4  409.07  5370.4  412.09  5377.9  415.23  5406.3  418.23  5484.0  418.99
#Mann=7,-1,0
  4329.6    0.16       0  4738.1    0.05       0  4967.1    0.16       0
  4995.1    0.07       0  5001.7    0.16       0  5082.1    0.05       0
  5182.1    0.16       0
Bank Sta=4942.4,5170.8
Exp/Cntr=0.3,0.1

Type RM Length L Ch R = 1,6480,251,251,251
BEGIN DESCRIPTION:
Mapping XS 1750c73e
END DESCRIPTION:
XS GIS Cut Line= 3
      2943660.06      6960626.64      2943073.27      6959963.45
      2942392.70      6959966.93
#Sta/Elev= 30
  4096.9  438.00  4292.9  436.81  4389.4  432.58  4456.1  431.07  4484.5  428.88
  4519.6  423.41  4533.8  424.90  4540.5  423.33  4562.3  423.57  4569.0  420.60
  4590.7  422.89  4611.6  421.06  4640.1  421.37  4668.5  417.22  4675.2  413.93
  4688.5  411.04  4717.8  403.78  4734.3  402.26  4795.4  394.99  4817.4  393.40
  5110.8  392.37  5157.4  392.27  5157.9  391.47  5164.0  392.27  5209.9  392.31
  5281.7  394.99  5360.7  404.10  5380.7  409.12  5430.7  415.81  5663.0  421.25
#Mann=8,-1,0
  4096.9    0.05       0  4389.4    0.16       0  4688.5    0.12       0
  4734.3    0.16       0  5110.8    0.12       0  5157.4    0.07       0
  5164.0    0.12       0  5209.9    0.16       0
Bank Sta=4795.4,5281.7
Exp/Cntr=0.3,0.1

Type RM Length L Ch R = 1,6229,575,575,575
BEGIN DESCRIPTION:
RED BRANCH 11.0
END DESCRIPTION:
XS GIS Cut Line= 3
      2943425.01      6960025.01      2943075.00      6959725.00
      2942674.99      6959474.99
#Sta/Elev= 30
  4516.2  424.65  4544.2  423.72  4558.5  422.29  4566.2  420.72  4601.3  416.57
  4611.8  413.36  4679.2  399.23  4715.6  394.84  4736.3  393.28  4757.1  392.70
  4785.7  393.30  4799.9  392.54  4892.1  392.34  4970.6  391.11  4971.1  390.31
  4976.7  390.31  4977.2  391.11  5007.0  391.11  5122.1  391.11  5216.0  391.11
  5224.8  392.10  5252.5  392.13  5281.4  394.84  5310.3  397.24  5346.9  402.05
  5377.5  407.62  5383.4  407.97  5420.0  415.20  5435.3  416.82  5448.9  417.30
#Mann=6,-1,0
  4516.2    0.12       0  4611.8    0.16       0  4970.6    0.07       0
  4977.2    0.16       0  5007.0    0.05       0  5122.1    0.16       0
Bank Sta=4715.6,5281.4
Exp/Cntr=0.3,0.1

Type RM Length L Ch R = 1,5654,365,365,365
BEGIN DESCRIPTION:
RED BRANCH 10.0
END DESCRIPTION:
XS GIS Cut Line= 3
      2943775.01      6959575.01      2943075.00      6959125.00
      2942625.01      6959425.00
#Sta/Elev= 30
  4144.5  419.79  4158.0  418.88  4188.4  409.00  4228.1  401.55  4251.8  397.72
  4288.2  395.58  4407.4  394.80  4500.2  392.22  4591.2  392.06  4648.1  391.11
  4648.6  390.31  4654.7  391.11  5206.5  391.11  5221.6  391.51  5230.5  394.80
  5232.8  396.52  5236.6  399.36  5242.6  399.27  5251.6  402.17  5257.6  401.22
  5272.6  405.10  5293.7  403.25  5308.7  405.96  5329.7  404.69  5344.7  406.86
  5365.8  405.72  5380.8  408.34  5401.8  408.00  5452.9  414.74  5517.5  418.45
#Mann=6,-1,0
  4144.5    0.05       0  4228.1    0.16       0  4591.2    0.05       0
  4648.1   0.033       0  4654.7    0.05       0  5232.8    0.16       0
Bank Sta=4407.4,5230.5
Exp/Cntr=0.3,0.1

Type RM Length L Ch R = 1,5289,715,715,715
BEGIN DESCRIPTION:
RED BRANCH 9.0
END DESCRIPTION:
XS GIS Cut Line= 3
      2944000.04      6958800.00      2942959.72      6958785.59
      2942013.42      6959088.44
#Sta/Elev= 30
  3970.1  417.37  4135.9  406.76  4285.2  395.55  4365.2  394.93  4405.2  396.52
  4459.0  394.79  4503.2  392.43  4541.5  391.11  4542.0  390.31  4548.9  391.11
  5322.6  391.32  5349.6  395.71  5354.9  393.44  5361.0  394.79  5381.8  398.12
  5387.0  395.53  5413.9  400.08  5419.2  398.05  5435.5  403.14  5451.3  405.57
  5456.6  404.25  5483.5  406.11  5488.7  404.03  5498.5  404.40  5515.7  407.59
  5547.8  409.92  5553.1  408.56  5634.0  412.76  5886.9  424.33  6004.1  422.31
#Mann=7,-1,0
  3970.1    0.05       0  4135.9    0.16       0  4503.2    0.05       0
  4541.5   0.033       0  4548.9    0.05       0  5322.6    0.16       0
  5634.0    0.05       0
Bank Sta=4459,5361
Exp/Cntr=0.3,0.1

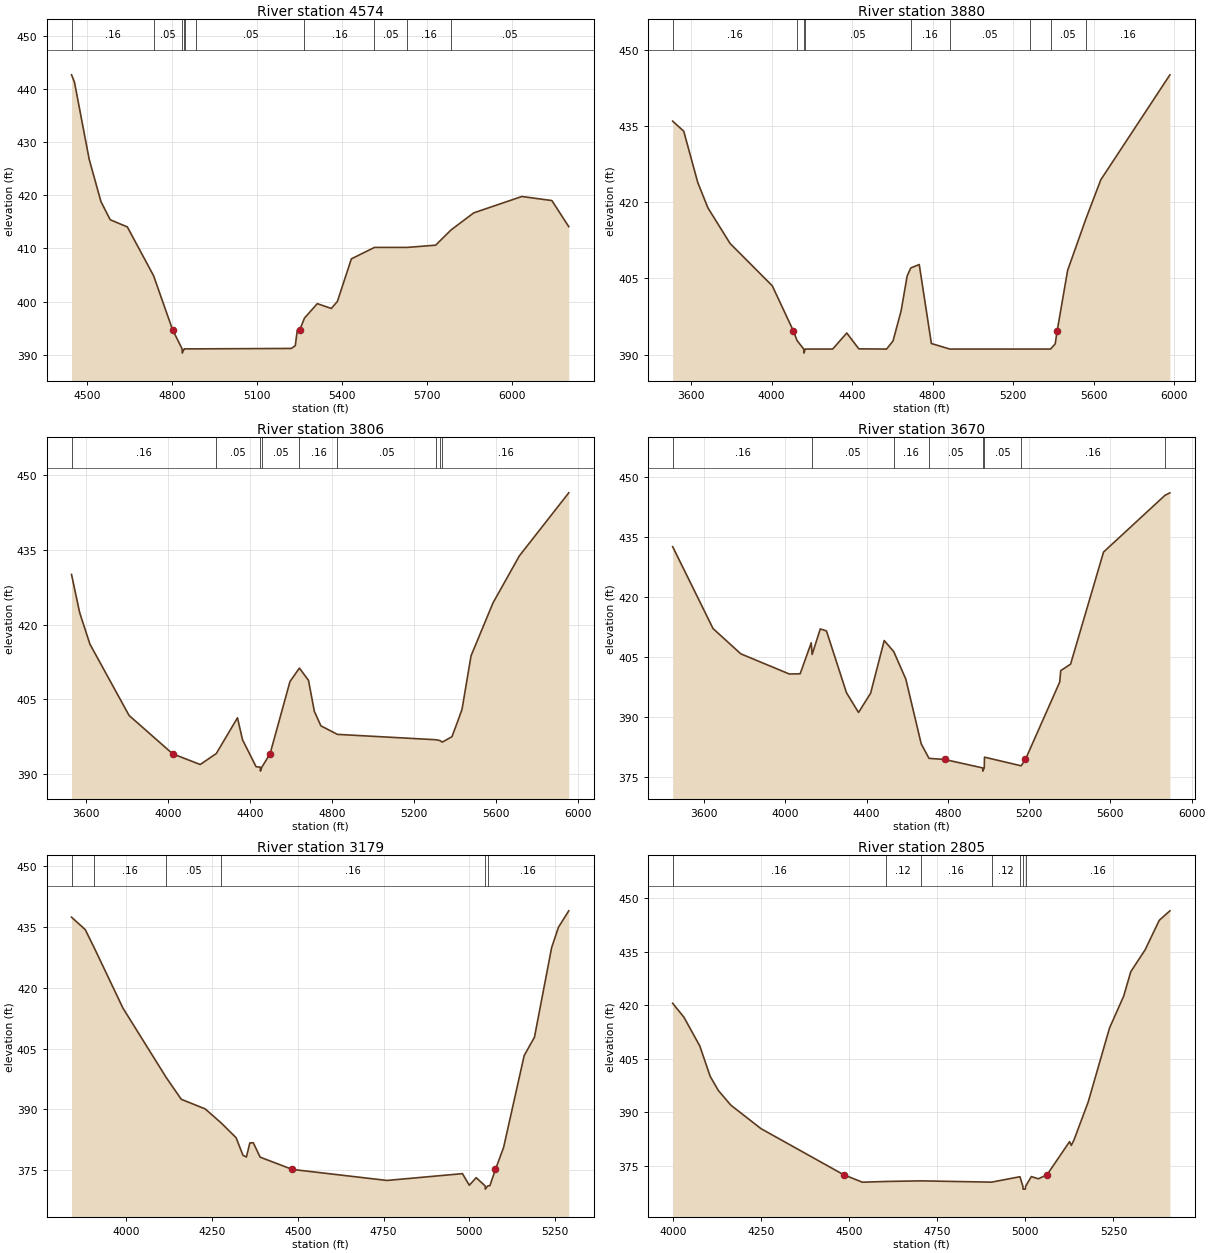
Type RM Length L Ch R = 1,4574,694,694,694
BEGIN DESCRIPTION:
RED BRANCH 8.0
END DESCRIPTION:
XS GIS Cut Line= 3
      2943275.04      6957974.99      2942725.00      6958125.00
      2941909.61      6958983.86
#Sta/Elev= 30
  4444.9  442.62  4455.3  441.25  4507.1  426.77  4548.6  418.81  4581.4  415.38
  4641.9  414.03  4734.6  404.84  4801.2  394.74  4835.1  391.11  4835.7  390.31
  4842.5  391.11  4844.8  391.11  4885.6  391.11  5220.3  391.19  5234.4  391.71
  5241.3  394.59  5250.7  394.74  5266.7  396.89  5312.1  399.61  5361.5  398.71
  5382.9  400.02  5432.3  408.03  5513.8  410.18  5629.1  410.18  5729.6  410.60
  5784.1  413.47  5863.9  416.67  6033.7  419.75  6139.7  418.99  6199.3  414.08
#Mann=10,-1,0
  4444.9    0.16       0  4734.6    0.05       0  4835.1   0.033       0
  4842.5    0.05       0  4844.8    0.07       0  4885.6    0.05       0
  5266.7    0.16       0  5513.8    0.05       0  5629.1    0.16       0
  5784.1    0.05       0
Bank Sta=4801.2,5250.7
Exp/Cntr=0.3,0.1

Type RM Length L Ch R = 1,3880,74,74,74
BEGIN DESCRIPTION:
Mapping XS 287a2642
END DESCRIPTION:
XS GIS Cut Line= 4
      2943680.00      6957716.93      2942477.78      6957686.55
      2941870.14      6957747.31      2941232.11      6957907.90
#Sta/Elev= 30
  3508.1  435.95  3563.1  433.97  3633.1  423.85  3683.2  418.90  3793.2  411.90
  4003.3  403.55  4107.7  394.71  4126.0  392.81  4159.5  391.11  4160.1  390.31
  4167.1  391.11  4303.3  391.11  4373.4  394.27  4433.4  391.15  4571.2  391.11
  4603.4  392.72  4643.5  398.63  4673.5  405.50  4691.6  407.07  4733.6  407.74
  4793.9  392.20  4885.5  391.11  5284.5  391.11  5386.1  391.11  5409.2  392.13
  5419.2  394.71  5471.0  406.59  5561.0  416.63  5636.0  424.42  5979.3  445.06
#Mann=9,-1,0
  3508.1    0.16       0  4126.0    0.05       0  4159.5   0.033       0
  4167.1    0.05       0  4691.6    0.16       0  4885.5    0.05       0
  5284.5    0.16       0  5386.1    0.05       0  5561.0    0.16       0
Bank Sta=4107.7,5419.2
Exp/Cntr=0.3,0.1

Type RM Length L Ch R = 1,3806,136,136,136
BEGIN DESCRIPTION:
Mapping XS 3e36400d
END DESCRIPTION:
XS GIS Cut Line= 4
      2943594.14      6957511.19      2942413.55      6957641.41
      2941853.65      6957697.83      2941193.91      6957841.06
#Sta/Elev= 30
  3529.3  430.07  3568.7  422.45  3619.0  416.07  3810.1  401.73  4022.6  394.02
  4157.1  391.87  4235.6  394.08  4338.8  401.26  4363.5  396.84  4429.7  391.42
  4450.2  391.34  4450.8  390.54  4457.8  391.34  4497.8  394.02  4594.9  408.54
  4640.9  411.25  4685.4  408.78  4713.8  402.56  4745.7  399.65  4826.1  397.93
  5306.6  396.85  5325.9  396.70  5337.8  396.37  5385.1  397.46  5411.4  400.35
  5434.2  402.96  5478.2  413.72  5585.4  424.36  5713.8  433.80  5954.9  446.48
#Mann=9,-1,0
  3529.3    0.16       0  4235.6    0.05       0  4450.2    0.03       0
  4457.8    0.05       0  4640.9    0.16       0  4826.1    0.05       0
  5306.6    0.16       0  5325.9    0.05       0  5337.8    0.16       0
Bank Sta=4022.6,4497.8
Exp/Cntr=0.3,0.1

Type RM Length L Ch R = 1,3670,491,491,491
BEGIN DESCRIPTION:
Mapping XS 8f37de7a
END DESCRIPTION:
XS GIS Cut Line= 4
      2943550.74      6957372.30      2942409.21      6957571.96
      2941892.71      6957611.02      2941133.12      6957741.24
#Sta/Elev= 30
  3445.4  432.62  3644.1  412.10  3780.7  405.76  4019.7  400.70  4073.0  400.76
  4127.4  408.52  4132.0  405.59  4172.0  412.00  4202.5  411.49  4300.8  396.03
  4360.3  391.06  4419.7  395.88  4486.7  409.09  4533.6  406.32  4593.1  399.42
  4668.7  383.22  4707.1  379.56  4784.8  379.28  4971.5  377.16  4972.1  376.36
  4979.1  377.16  4980.3  379.86  5161.0  377.69  5181.7  379.28  5350.5  398.68
  5355.6  401.55  5404.0  403.17  5566.3  431.27  5868.6  445.48  5892.9  446.11
#Mann=8,-1,0
  3445.4    0.16       0  4132.0    0.05       0  4533.6    0.16       0
  4707.1    0.05       0  4971.5    0.03       0  4979.1    0.05       0
  5161.0    0.16       0  5868.6    0.05       0
Bank Sta=4784.8,5181.7
Exp/Cntr=0.3,0.1

Type RM Length L Ch R = 1,3179,374,374,374
BEGIN DESCRIPTION:
RED BRANCH 6.0
END DESCRIPTION:
XS GIS Cut Line= 3
      2942875.00      6957275.00      2942125.00      6957275.00
      2941425.00      6957275.00
#Sta/Elev= 30
  3839.9  437.43  3879.9  434.37  3906.1  429.88  3989.9  415.00  4116.3  397.85
  4159.9  392.51  4229.9  390.13  4276.7  386.65  4319.9  383.02  4339.9  378.69
  4349.9  378.28  4359.9  381.75  4369.9  381.79  4389.9  378.24  4483.8  375.21
  4759.9  372.49  4979.9  374.17  4999.9  371.31  5019.9  373.18  5046.1  371.15
  5046.7  370.35  5053.7  371.15  5059.9  371.20  5076.1  375.21  5099.9  380.64
  5159.9  403.30  5189.9  407.83  5239.9  429.91  5259.9  434.96  5289.9  439.00
#Mann=6,-1,0
  3839.9    0.05       0  3906.1    0.16       0  4116.3    0.05       0
  4276.7    0.16       0  5046.1    0.07       0  5053.7    0.16       0
Bank Sta=4483.8,5076.1
Exp/Cntr=0.3,0.1

Type RM Length L Ch R = 1,2805,467,467,467
BEGIN DESCRIPTION:
RED BRANCH 5.0
END DESCRIPTION:
XS GIS Cut Line= 3
      2942675.02      6957125.01      2942125.00      6956875.00
      2941325.00      6956975.00
#Sta/Elev= 30
  3999.6  420.56  4031.5  416.67  4076.5  408.60  4106.2  400.02  4129.2  396.09
  4164.4  391.99  4250.1  385.38  4484.6  372.44  4537.9  370.34  4603.9  370.55
  4704.0  370.72  4904.1  370.36  4984.7  371.88  4993.0  369.20  4993.6  368.40
  5000.0  368.40  5000.7  369.20  5017.0  371.92  5037.1  371.30  5061.6  372.44
  5125.3  381.72  5130.3  380.68  5137.9  382.19  5178.2  392.84  5238.7  413.61
  5279.0  422.60  5299.1  429.45  5339.5  435.53  5379.8  443.86  5410.0  446.52
#Mann=7,-1,0
  3999.6    0.16       0  4603.9    0.12       0  4704.0    0.16       0
  4904.1    0.12       0  4984.7    0.16       0  4993.0    0.07       0
  5000.7    0.16       0
Bank Sta=4484.6,5061.6
Exp/Cntr=0.3,0.1