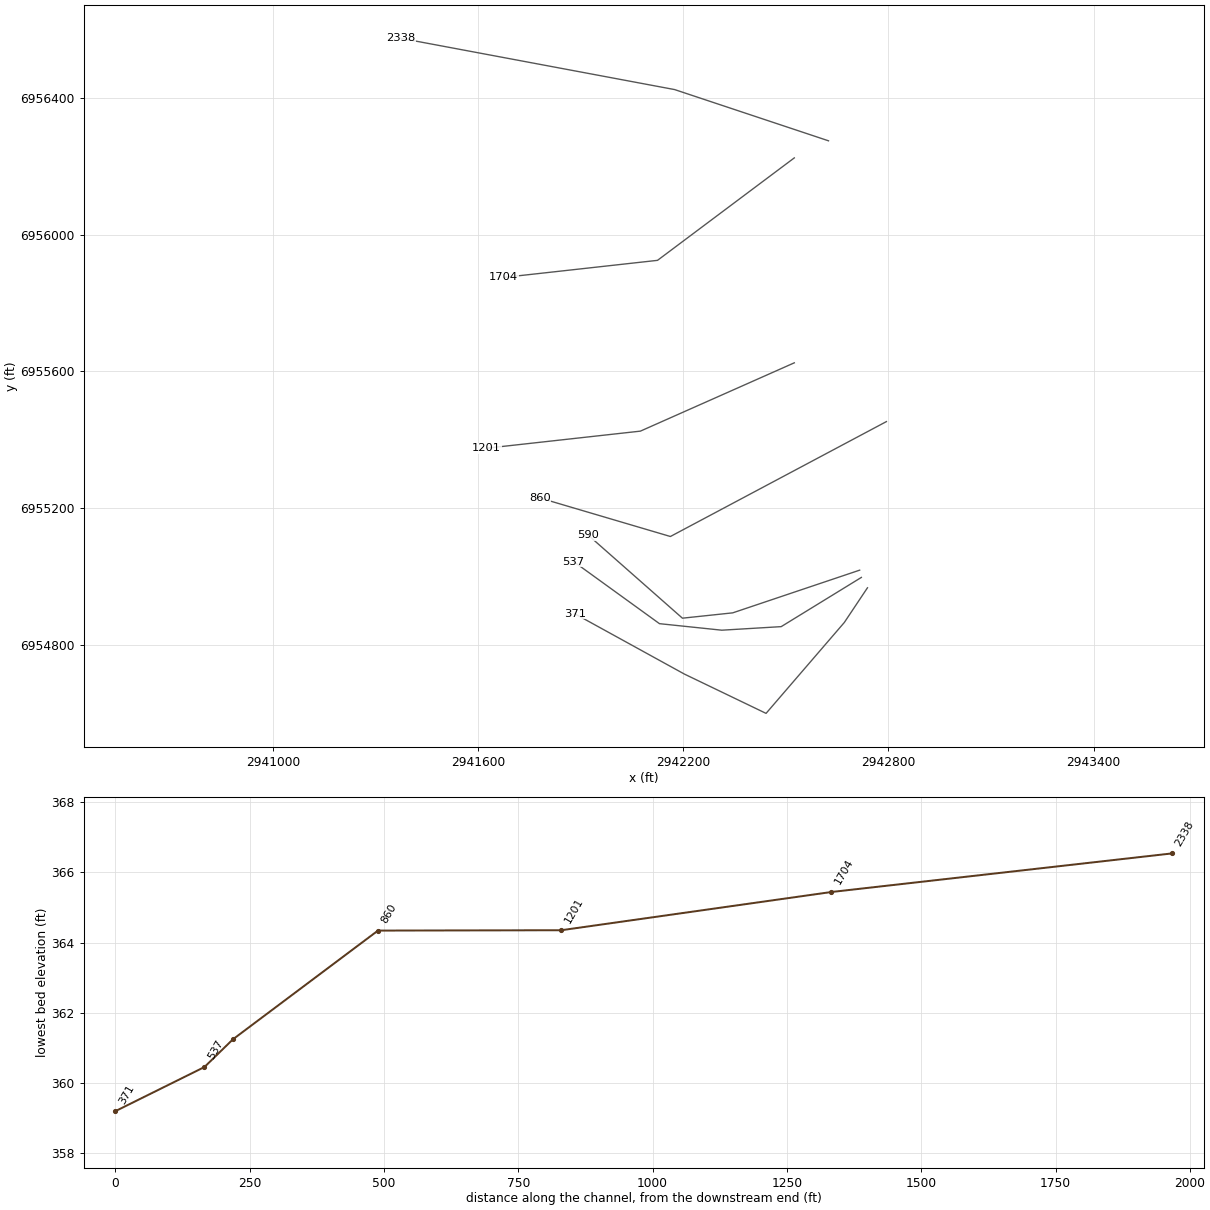
HEC-RAS study RED BRANCH.prj: RED BRANCH Base Level Engineering

--- RED BRANCH.g01 (geometry) --- (continued)

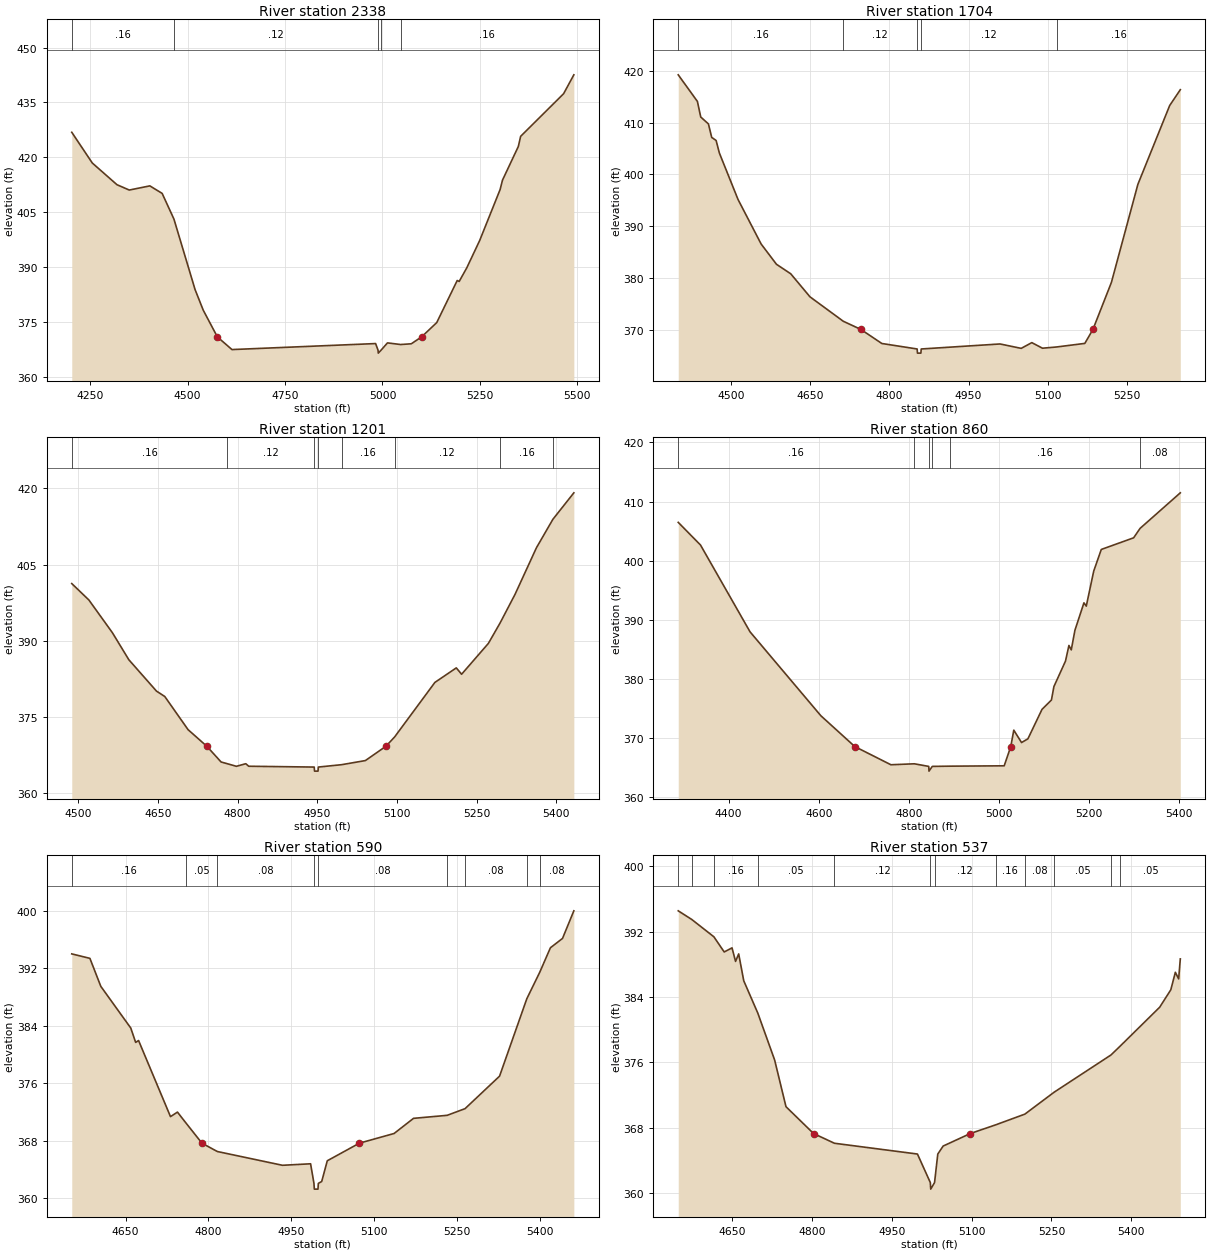
Type RM Length L Ch R = 1,2338,634,634,634
BEGIN DESCRIPTION:
RED BRANCH 4.0
END DESCRIPTION:
XS GIS Cut Line= 3
      2942625.03      6956274.99      2942175.00      6956425.00
      2941375.02      6956575.00
#Sta/Elev= 30
  4202.8  426.86  4255.5  418.46  4318.8  412.54  4350.4  411.08  4403.1  412.22
  4434.7  410.17  4465.0  403.14  4519.1  383.93  4540.1  378.28  4576.4  370.97
  4613.9  367.51  4982.4  369.15  4988.7  367.34  4989.3  366.54  4996.4  367.34
  5012.9  369.34  5046.6  368.89  5074.0  369.09  5100.4  370.97  5139.3  374.88
  5191.8  386.37  5196.9  386.12  5216.4  389.84  5249.5  397.30  5302.0  411.24
  5308.0  413.78  5348.7  422.99  5354.6  425.75  5464.8  437.39  5491.1  442.55
#Mann=5,-1,0
  4202.8    0.16       0  4465.0    0.12       0  4988.7    0.07       0
  4996.4    0.12       0  5046.6    0.16       0
Bank Sta=4576.4,5100.4
Exp/Cntr=0.3,0.1

Type RM Length L Ch R = 1,1704,503,503,503
BEGIN DESCRIPTION:
RED BRANCH 3.0
END DESCRIPTION:
XS GIS Cut Line= 3
      2942524.99      6956224.99      2942125.00      6955925.00
      2941674.95      6955874.99
#Sta/Elev= 30
  4399.1  419.22  4435.5  414.08  4441.8  411.07  4456.4  409.73  4462.6  407.13
  4471.0  406.53  4477.2  404.10  4512.6  395.13  4556.4  386.53  4585.5  382.61
  4612.6  380.77  4649.1  376.32  4712.3  371.60  4745.7  370.02  4785.5  367.30
  4852.5  366.24  4853.1  365.44  4859.6  365.44  4860.2  366.24  5009.8  367.21
  5050.0  366.36  5070.1  367.47  5090.3  366.39  5117.4  366.63  5170.7  367.32
  5186.1  370.02  5221.1  379.09  5271.4  398.06  5331.7  413.28  5351.9  416.35
#Mann=5,-1,0
  4399.1    0.16       0  4712.3    0.12       0  4852.5    0.07       0
  4860.2    0.12       0  5117.4    0.16       0
Bank Sta=4745.7,5186.1
Exp/Cntr=0.3,0.1

Type RM Length L Ch R = 1,1201,341,341,341
BEGIN DESCRIPTION:
RED BRANCH 2.0
END DESCRIPTION:
XS GIS Cut Line= 3
      2942525.02      6955625.01      2942075.00      6955425.00
      2941625.04      6955375.00
#Sta/Elev= 30
  4487.7  401.27  4519.9  398.04  4564.3  391.58  4595.1  386.28  4647.1  380.11
  4662.8  379.04  4706.6  372.52  4742.0  369.24  4768.8  366.15  4780.1  365.82
  4797.6  365.30  4815.3  365.81  4820.8  365.31  4944.1  365.15  4944.7  364.35
  4951.3  364.35  4951.9  365.15  4995.9  365.62  5040.5  366.43  5079.1  369.24
  5095.3  371.05  5171.3  381.81  5211.6  384.67  5221.6  383.42  5272.0  389.49
  5294.1  393.52  5322.3  399.17  5362.5  408.32  5393.4  413.91  5432.9  419.13
#Mann=8,-1,0
  4487.7    0.16       0  4780.1    0.12       0  4944.1    0.07       0
  4951.9    0.12       0  4995.9    0.16       0  5095.3    0.12       0
  5294.1    0.16       0  5393.4    0.08       0
Bank Sta=4742,5079.1
Exp/Cntr=0.3,0.1

Type RM Length L Ch R = 1,860,270,270,270
BEGIN DESCRIPTION:
Mapping XS 30492713
END DESCRIPTION:
XS GIS Cut Line= 3
      2942794.26      6955452.91      2942162.71      6955116.52
      2941780.78      6955229.37
#Sta/Elev= 30
  4288.3  406.47  4337.7  402.63  4447.6  387.93  4604.7  373.72  4680.0  368.50
  4760.1  365.42  4812.2  365.58  4844.0  365.14  4844.6  364.34  4851.9  365.14
  4892.0  365.18  5011.4  365.24  5026.0  368.50  5032.7  371.28  5049.9  369.18
  5064.0  369.81  5095.3  374.80  5116.2  376.38  5121.7  378.66  5147.4  382.98
  5155.0  385.62  5160.2  384.87  5168.3  388.19  5188.3  392.84  5193.5  392.28
  5210.0  398.21  5226.8  401.88  5298.5  403.85  5312.9  405.45  5402.1  411.47
#Mann=6,-1,0
  4288.3    0.16       0  4812.2    0.07       0  4844.0    0.07       0
  4851.9    0.07       0  4892.0    0.16       0  5312.9    0.08       0
Bank Sta=4680,5026
Exp/Cntr=0.3,0.1

Type RM Length L Ch R = 1,590,53,53,53
BEGIN DESCRIPTION:
Mapping XS 050c5814
END DESCRIPTION:
XS GIS Cut Line= 4
      2942716.11      6955018.00      2942345.00      6954893.00
      2942197.87      6954877.37      2941921.78      6955121.05
#Sta/Elev= 30
  4552.8  394.01  4585.6  393.39  4605.3  389.49  4659.5  383.68  4668.3  381.68
  4673.6  381.94  4731.3  371.34  4743.9  371.97  4758.6  370.52  4788.2  367.64
  4816.0  366.48  4933.8  364.56  4984.6  364.77  4990.7  362.04  4991.4  361.24
  4998.0  361.24  4998.6  362.04  5004.7  362.30  5014.8  365.19  5072.8  367.64
  5135.6  368.99  5170.7  371.10  5231.5  371.52  5263.9  372.45  5326.3  376.98
  5375.6  387.77  5398.7  391.41  5418.3  394.87  5440.1  396.16  5460.6  400.01
#Mann=9,-1,0
  4552.8    0.16       0  4758.6    0.05       0  4816.0    0.08       0
  4990.7    0.07       0  4998.6    0.08       0  5231.5    0.16       0
  5263.9    0.08       0  5375.6    0.16       0  5398.7    0.08       0
Bank Sta=4788.2,5072.8
Exp/Cntr=0.3,0.1

Type RM Length L Ch R = 1,537,166,166,166
BEGIN DESCRIPTION:
Mapping XS d91f9ff3
END DESCRIPTION:
XS GIS Cut Line= 5
      2942721.07      6954996.74      2942486.66      6954852.63
      2942313.05      6954842.21      2942130.76      6954861.31
      2941879.50      6955043.26
#Sta/Elev= 30
  4549.3  394.55  4574.5  393.50  4616.2  391.37  4635.6  389.51  4650.3  390.01
  4656.9  388.35  4662.8  389.27  4672.3  385.98  4698.8  382.00  4730.3  376.27
  4751.6  370.55  4803.4  367.26  4842.6  366.07  4998.4  364.75  5022.6  361.25
  5023.3  360.45  5030.5  361.25  5036.6  364.75  5046.7  365.73  5097.6  367.26
  5145.0  368.32  5200.1  369.64  5255.1  372.33  5361.8  376.89  5379.4  378.00
  5453.2  382.74  5474.1  384.88  5482.6  387.02  5488.8  386.21  5491.9  388.66
#Mann=12,-1,0
  4549.3    0.16       0  4574.5    0.08       0  4616.2    0.16       0
  4698.8    0.05       0  4842.6    0.12       0  5022.6    0.07       0
  5030.5    0.12       0  5145.0    0.16       0  5200.1    0.08       0
  5255.1    0.05       0  5361.8    0.08       0  5379.4    0.05       0
Bank Sta=4803.4,5097.6
Exp/Cntr=0.3,0.1

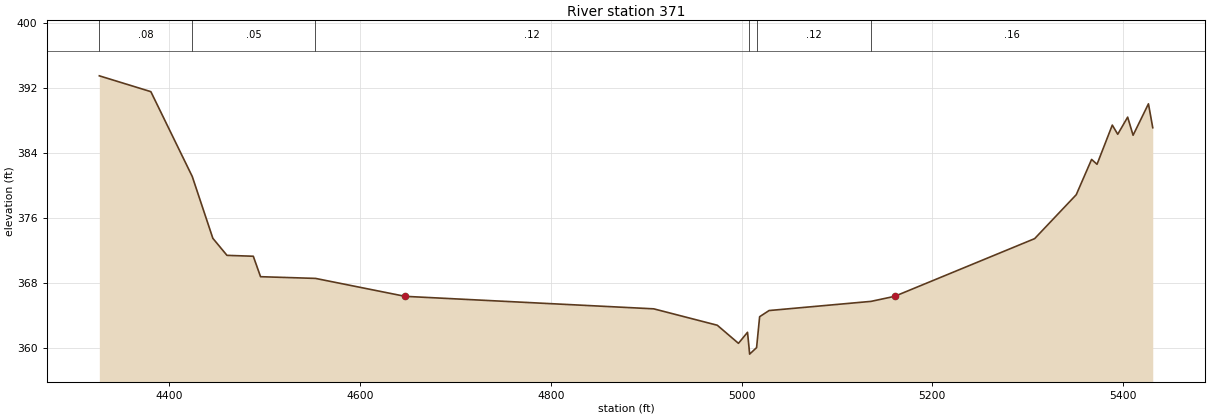
Type RM Length L Ch R = 1,371,0,0,0
BEGIN DESCRIPTION:
Mapping XS e516eb62
END DESCRIPTION:
XS GIS Cut Line= 5
      2942738.94      6954966.37      2942671.21      6954864.78
      2942442.41      6954598.68      2942203.70      6954713.70
      2941882.87      6954890.43
#Sta/Elev= 30
  4326.8  393.48  4380.8  391.53  4424.2  381.08  4445.8  373.46  4460.6  371.36
  4488.2  371.25  4495.8  368.73  4553.4  368.52  4647.3  366.31  4908.0  364.77
  4974.6  362.75  4996.8  360.52  5006.3  361.88  5007.9  359.99  5008.5  359.19
  5015.8  359.99  5019.0  363.80  5028.9  364.56  5135.8  365.69  5160.5  366.31
  5307.3  373.42  5350.9  378.83  5367.0  383.18  5372.7  382.58  5388.7  387.41
  5394.4  386.28  5404.8  388.39  5410.5  386.16  5426.6  390.03  5431.1  387.09
#Mann=6,-1,0
  4326.8    0.08       0  4424.2    0.05       0  4553.4    0.12       0
  5007.9    0.07       0  5015.8    0.12       0  5135.8    0.16       0
Bank Sta=4647.3,5160.5
Exp/Cntr=0.3,0.1

Chan Stop Cuts=-1