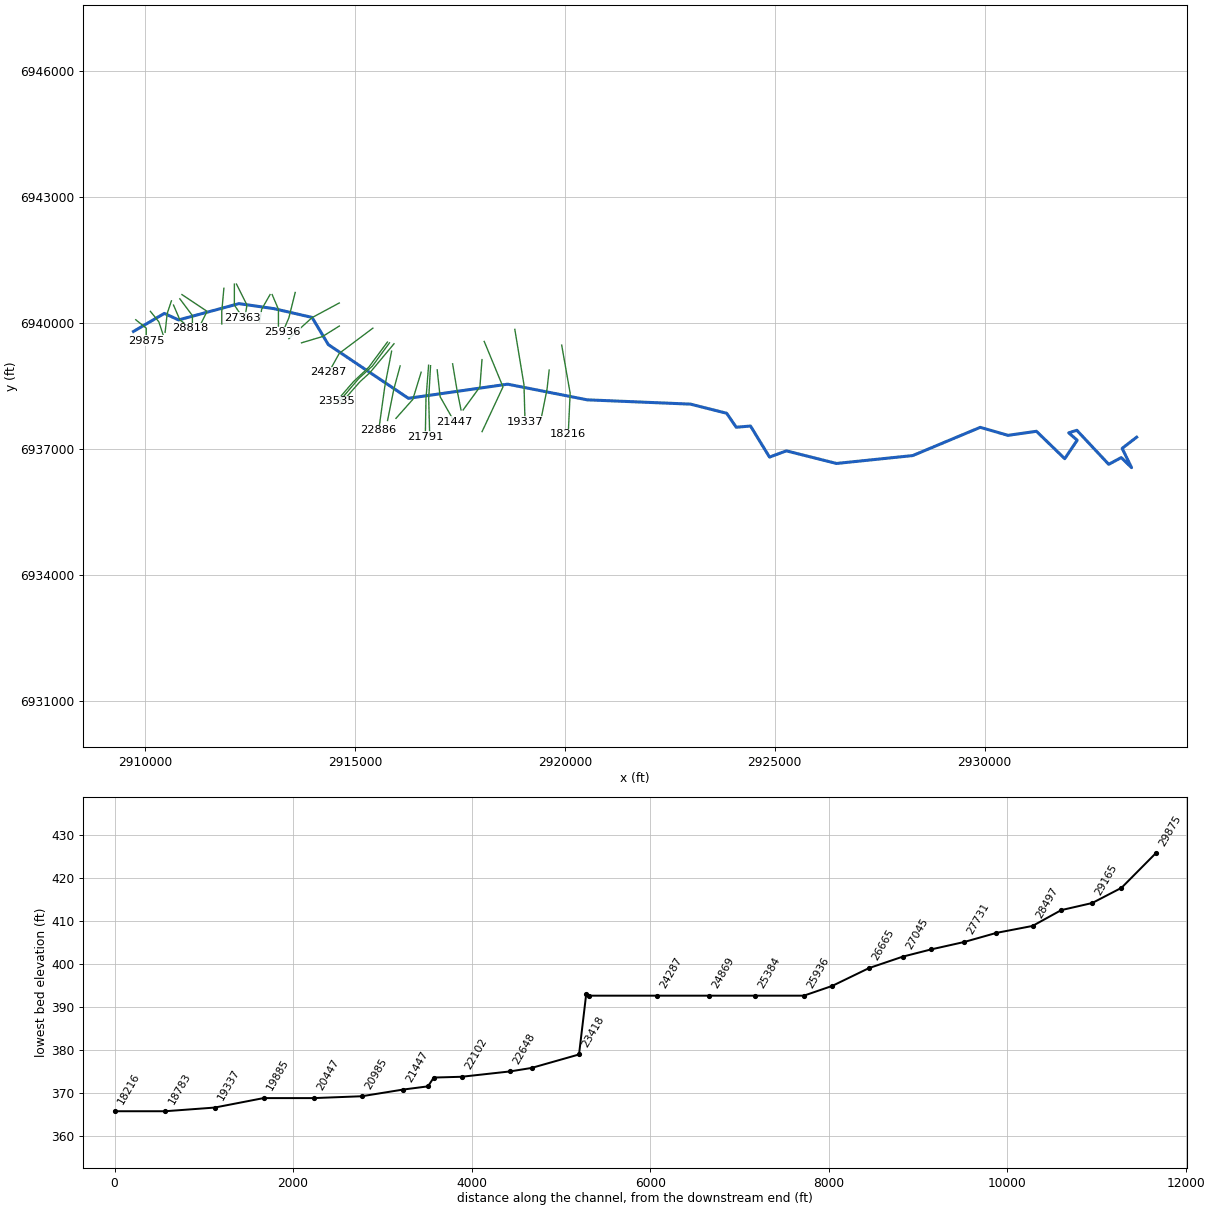
--- ROCK FALLS CREEK.prj (project) ---

Proj Title=ROCK FALLS CREEK Base Level Engineering
Current Plan=p01
Default Exp/Contr=0.3,0.1
English Units
Geom File=g01
Flow File=f01
Plan File=p01
BEGIN DESCRIPTION:
ROCK FALLS CREEK
END DESCRIPTION:

--- ROCK FALLS CREEK.p01 (plan) ---

Plan Title=Multiple Run
Short Identifier=Multiple
Geom File=g01
Flow File=f01
Subcritical Flow
K Sum by GR= 0
Std Step Tol= 0.01
Critical Tol= 0.01
Num of Std Step Trials= 20
Max Error Tol= 0.3
Flow Tol Ratio= 0.001
Split Flow NTrial= 30
Split Flow Tol= 0.02
Split Flow Ratio= 0.02
Log Output Level= 0
Friction Slope Method= 1
Unsteady Friction Slope Method= 2
Unsteady Bridges Friction Slope Method= 1
Parabolic Critical Depth
Global Vel Dist=  1 , 1 , 1
Global Log Level= 0
CheckData=True
Encroach Param= -1, 0, 0, 0
BEGIN DESCRIPTION:
Multiple Run
END DESCRIPTION:

--- ROCK FALLS CREEK.f01 (steady flow) ---

Flow Title=Multiple
Number of Profiles=7
Profile Names=10-year,25-year,50-year,1pct_min,100-year,1pct_plu,500-year
River Rch & RM= ROCK FALLS CREEK,Reach-1,29875
     601     814     990     600    1197    2389    1750
River Rch & RM= ROCK FALLS CREEK,Reach-1,25384
     936    1299    1604     984    1964    3918    2949
River Rch & RM= ROCK FALLS CREEK,Reach-1,21791
    1220    1711    2129    1315    2623    5234    3993
River Rch & RM= ROCK FALLS CREEK,Reach-1,19337
    1401    1969    2454    1516    3026    6037    4610
River Rch & RM= ROCK FALLS CREEK,Reach-1,15372
    1664    2358    2953    1833    3657    7297    5624
River Rch & RM= ROCK FALLS CREEK,Reach-1,7927
    1641    2313    2886    1784    3559    7101    5426
Boundary for River Rch & Prof#=ROCK FALLS CREEK,Reach-1,1
Up Type=0
Dn Type=3
Dn Slope=0.005
Boundary for River Rch & Prof#=ROCK FALLS CREEK,Reach-1,2
Up Type=0
Dn Type=3
Dn Slope=0.005
Boundary for River Rch & Prof#=ROCK FALLS CREEK,Reach-1,3
Up Type=0
Dn Type=3
Dn Slope=0.005
Boundary for River Rch & Prof#=ROCK FALLS CREEK,Reach-1,4
Up Type=0
Dn Type=3
Dn Slope=0.005
Boundary for River Rch & Prof#=ROCK FALLS CREEK,Reach-1,5
Up Type=0
Dn Type=3
Dn Slope=0.005
Boundary for River Rch & Prof#=ROCK FALLS CREEK,Reach-1,6
Up Type=0
Dn Type=3
Dn Slope=0.005
Boundary for River Rch & Prof#=ROCK FALLS CREEK,Reach-1,7
Up Type=0
Dn Type=3
Dn Slope=0.005

--- ROCK FALLS CREEK.g01 (geometry) ---

Geom Title=Existing Conditions

River Reach=ROCK FALLS CREEK,Reach-1
Reach XY= 30
      2909720.59      6939795.71      2910456.31      6940225.95
      2910796.02      6940070.70      2912236.05      6940459.45
      2913069.71      6940338.58      2913975.59      6940130.71
      2914362.57      6939483.15      2916271.48      6938202.79
      2918635.04      6938539.43      2920531.11      6938166.48
      2922991.63      6938064.25      2923853.54      6937846.93
      2924081.49      6937513.40      2924421.68      6937542.68
      2924874.86      6936801.68      2925276.54      6936950.78
      2926470.45      6936650.20      2928287.44      6936838.31
      2929895.74      6937511.07      2930555.73      6937320.47
      2931234.49      6937416.90      2931908.39      6936764.12
      2932205.27      6937203.36      2932003.88      6937380.44
      2932196.59      6937441.21      2932956.71      6936629.57
      2933255.01      6936790.33      2933500.72      6936550.86
      2933276.48      6937010.21      2933622.29      6937276.59

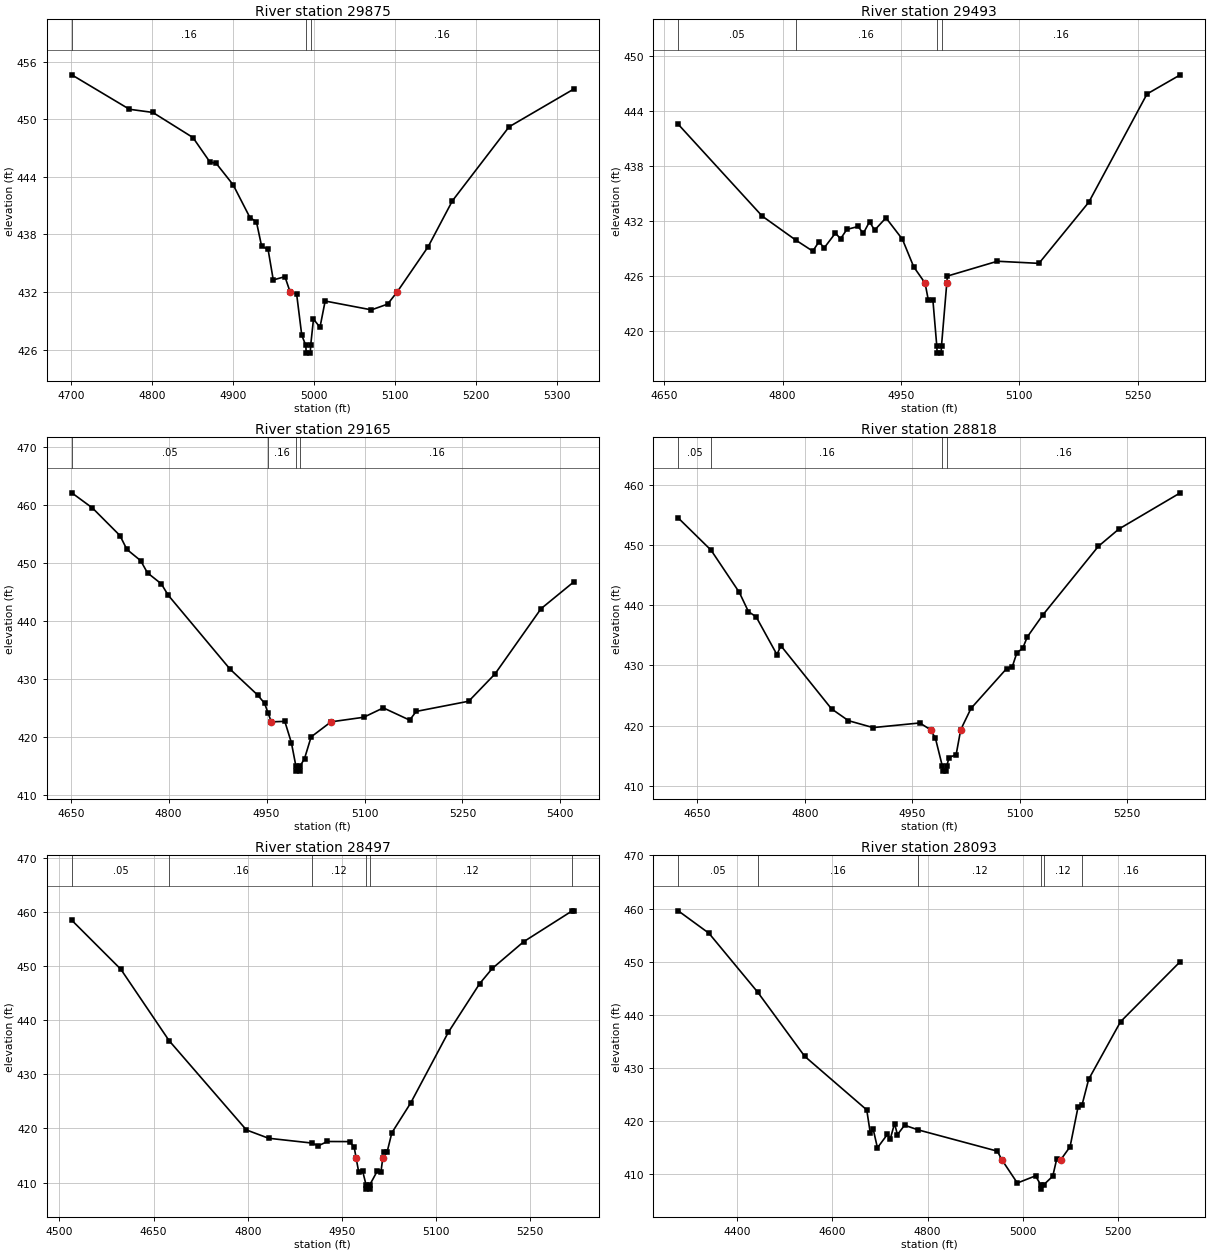
Type RM Length L Ch R = 1,29875,382,382,382
BEGIN DESCRIPTION:
ROCK FALLS CREEK 48.0
END DESCRIPTION:
XS GIS Cut Line= 3
      2909775.00      6940075.00      2910025.00      6939875.00
      2910025.00      6939574.96
#Sta/Elev= 30
  4700.6  454.64  4771.8  451.05  4800.7  450.72  4850.3  448.10  4871.1  445.57
  4879.1  445.40  4899.9  443.18  4920.7  439.76  4928.7  439.32  4935.1  436.78
  4943.1  436.44  4949.5  433.26  4963.9  433.60  4970.2  432.04  4978.3  431.84
  4984.7  427.50  4989.7  426.43  4990.2  425.63  4995.2  425.63  4995.7  426.43
  4999.2  429.18  5007.2  428.32  5013.6  431.06  5070.8  430.14  5090.8  430.74
  5102.8  432.04  5140.8  436.72  5170.8  441.51  5240.8  449.22  5320.8  453.16
#Mann=3,-1,0
  4700.6    0.16       0  4989.7    0.07       0  4995.7    0.16       0
Bank Sta=4970.2,5102.8
Exp/Cntr=0.3,0.1

Type RM Length L Ch R = 1,29493,328,328,328
BEGIN DESCRIPTION:
ROCK FALLS CREEK 47.0
END DESCRIPTION:
XS GIS Cut Line= 3
      2910125.00      6940275.00      2910325.00      6940025.00
      2910425.01      6939724.98
#Sta/Elev= 30
  4667.8  442.52  4774.2  432.54  4816.8  429.93  4838.3  428.73  4846.3  429.76
  4852.7  429.07  4867.1  430.70  4873.5  430.06  4881.5  431.09  4895.9  431.41
  4902.3  430.65  4910.3  431.93  4916.7  431.01  4931.1  432.35  4951.9  430.03
  4966.3  427.02  4980.7  425.25  4984.8  423.40  4990.6  423.40  4995.5  418.44
  4996.0  417.64  5001.0  417.64  5001.5  418.44  5008.2  425.25  5009.0  426.02
  5072.3  427.63  5125.0  427.40  5188.2  434.05  5262.0  445.82  5304.2  447.90
#Mann=4,-1,0
  4667.8    0.05       0  4816.8    0.16       0  4995.5    0.07       0
  5001.5    0.16       0
Bank Sta=4980.7,5008.2
Exp/Cntr=0.3,0.1

Type RM Length L Ch R = 1,29165,347,347,347
BEGIN DESCRIPTION:
ROCK FALLS CREEK 46.0
END DESCRIPTION:
XS GIS Cut Line= 3
      2910625.01      6940525.03      2910525.00      6940225.00
      2910475.00      6939775.03
#Sta/Elev= 30
  4651.6  462.16  4683.3  459.54  4725.4  454.78  4736.0  452.39  4757.0  450.46
  4767.6  448.34  4788.7  446.45  4799.2  444.50  4894.1  431.71  4936.2  427.26
  4946.8  425.84  4952.0  424.23  4957.2  422.62  4977.9  422.70  4988.0  419.01
  4995.0  414.91  4995.5  414.11  5000.5  414.11  5001.0  414.91  5008.1  416.28
  5018.2  420.02  5048.7  422.62  5098.7  423.41  5128.8  425.03  5169.1  422.92
  5179.2  424.42  5259.6  426.18  5299.9  430.90  5370.3  442.15  5420.6  446.79
#Mann=4,-1,0
  4651.6    0.05       0  4952.0    0.16       0  4995.0    0.07       0
  5001.0    0.16       0
Bank Sta=4957.2,5048.7
Exp/Cntr=0.3,0.1

Type RM Length L Ch R = 1,28818,321,321,321
BEGIN DESCRIPTION:
ROCK FALLS CREEK 45.0
END DESCRIPTION:
XS GIS Cut Line= 3
      2910674.99      6940425.03      2910825.00      6940075.00
      2911075.01      6939874.99
#Sta/Elev= 30
  4623.3  454.45  4669.2  449.10  4708.6  442.10  4721.3  438.92  4732.1  438.05
  4761.1  431.79  4766.6  433.26  4837.3  422.79  4860.9  420.83  4895.3  419.68
  4960.6  420.45  4975.6  419.32  4982.4  417.91  4992.1  413.26  4992.6  412.46
  4997.6  412.46  4998.1  413.26  5001.4  414.72  5011.3  415.19  5017.7  419.33
  5032.1  422.87  5081.8  429.47  5089.8  429.81  5096.2  432.13  5104.2  432.81
  5110.6  434.71  5132.2  438.34  5209.8  449.74  5238.6  452.62  5324.3  458.62
#Mann=4,-1,0
  4623.3    0.05       0  4669.2    0.16       0  4992.1    0.07       0
  4998.1    0.16       0
Bank Sta=4975.6,5017.7
Exp/Cntr=0.3,0.1

Type RM Length L Ch R = 1,28497,404,404,404
BEGIN DESCRIPTION:
ROCK FALLS CREEK 44.0
END DESCRIPTION:
XS GIS Cut Line= 3
      2910824.98      6940575.02      2911125.00      6940175.00
      2911125.00      6939875.03
#Sta/Elev= 30
  4519.6  458.47  4597.8  449.41  4674.7  436.22  4797.8  419.73  4833.2  418.19
  4902.4  417.30  4912.3  416.79  4926.9  417.59  4962.3  417.57  4969.6  416.54
  4972.8  414.47  4976.9  411.88  4983.2  412.06  4988.5  409.59  4989.0  408.79
  4994.0  408.79  4994.5  409.59  5006.1  412.07  5012.3  412.02  5015.1  414.47
  5016.5  415.67  5022.1  415.67  5029.6  419.20  5059.6  424.70  5119.6  437.77
  5169.6  446.77  5189.6  449.56  5239.6  454.50  5316.1  460.14  5319.6  460.21
#Mann=6,-1,0
  4519.6    0.05       0  4674.7    0.16       0  4902.4    0.12       0
  4988.5    0.07       0  4994.5    0.12       0  5316.1    0.16       0
Bank Sta=4972.8,5015.1
Exp/Cntr=0.3,0.1

Type RM Length L Ch R = 1,28093,362,362,362
BEGIN DESCRIPTION:
ROCK FALLS CREEK 43.0
END DESCRIPTION:
XS GIS Cut Line= 3
      2910874.96      6940675.03      2911475.00      6940275.00
      2911324.99      6939974.97
#Sta/Elev= 30
  4275.4  459.58  4340.0  455.36  4442.5  444.28  4541.4  432.20  4672.1  422.10
  4679.6  417.72  4685.6  418.50  4694.6  414.96  4715.6  417.49  4721.6  416.62
  4730.6  419.53  4736.7  417.44  4751.7  419.21  4780.9  418.32  4947.0  414.33
  4956.2  412.74  4989.0  408.33  5027.3  409.68  5038.3  407.98  5038.8  407.18
  5044.3  407.98  5063.6  409.62  5072.0  412.90  5080.6  412.74  5100.0  415.16
  5116.7  422.60  5125.0  422.96  5139.1  427.85  5206.2  438.70  5332.0  450.03
#Mann=6,-1,0
  4275.4    0.05       0  4442.5    0.16       0  4780.9    0.12       0
  5038.3    0.07       0  5044.3    0.12       0  5125.0    0.16       0
Bank Sta=4956.2,5080.6
Exp/Cntr=0.3,0.1

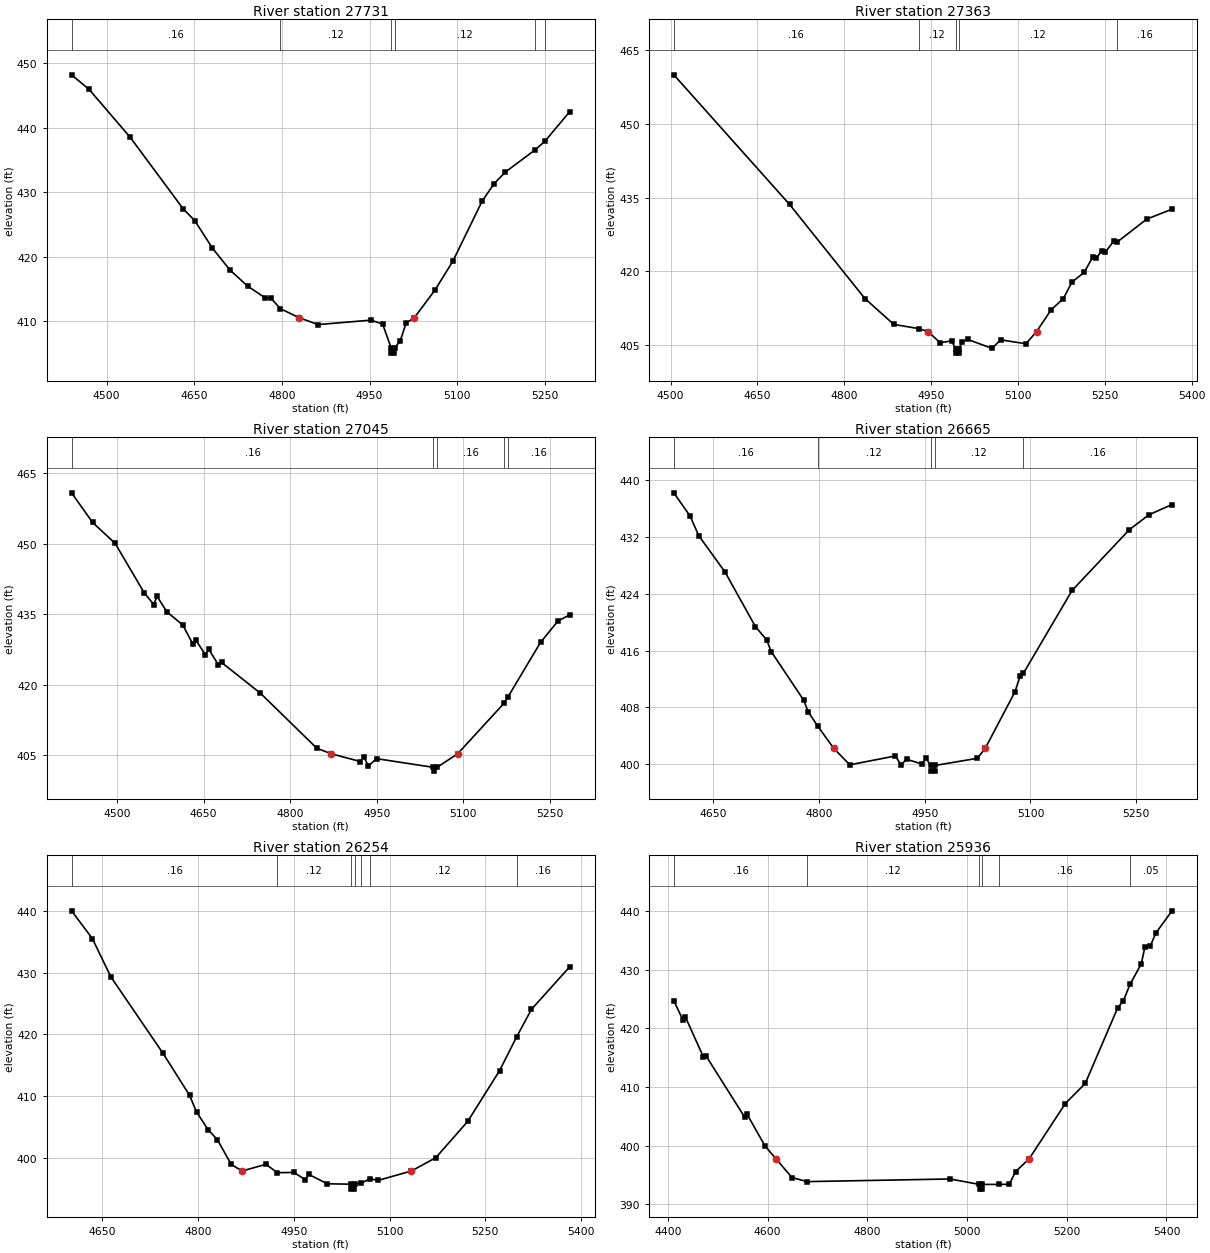
Type RM Length L Ch R = 1,27731,368,368,368
BEGIN DESCRIPTION:
ROCK FALLS CREEK 42.0
END DESCRIPTION:
XS GIS Cut Line= 3
      2911875.00      6940824.95      2911825.00      6940275.00
      2911825.00      6939975.02
#Sta/Elev= 30
  4440.2  448.16  4470.3  445.89  4540.6  438.47  4630.9  427.43  4651.0  425.57
  4681.1  421.32  4711.3  417.91  4741.4  415.44  4771.5  413.61  4781.6  413.53
  4797.1  411.96  4829.1  410.56  4861.9  409.48  4952.3  410.17  4972.3  409.56
  4986.9  405.86  4987.4  405.06  4992.4  405.06  4992.9  405.86  5002.4  406.97
  5012.4  409.70  5026.7  410.56  5062.4  414.90  5092.4  419.30  5142.4  428.58
  5162.4  431.24  5182.4  433.12  5233.5  436.56  5250.3  437.91  5292.4  442.47
#Mann=6,-1,0
  4440.2    0.16       0  4797.1    0.12       0  4986.9    0.07       0
  4992.9    0.12       0  5233.5    0.16       0  5250.3    0.12       0
Bank Sta=4829.1,5026.7
Exp/Cntr=0.3,0.1

Type RM Length L Ch R = 1,27363,318,318,318
BEGIN DESCRIPTION:
ROCK FALLS CREEK 41.0
END DESCRIPTION:
XS GIS Cut Line= 3
      2912125.00      6940925.04      2912125.00      6940425.00
      2912325.00      6940125.00
#Sta/Elev= 30
  4505.5  459.95  4705.5  433.58  4835.5  414.46  4885.5  409.19  4928.8  408.33
  4945.0  407.71  4965.5  405.46  4985.5  405.85  4992.5  404.15  4993.0  403.35
  4998.0  403.35  4998.5  404.15  5003.0  405.69  5013.1  406.14  5055.1  404.32
  5070.1  406.05  5113.7  405.26  5132.0  407.71  5157.3  412.17  5178.3  414.43
  5193.3  417.80  5214.4  419.78  5229.4  422.93  5235.4  422.62  5244.4  424.17
  5250.4  423.83  5265.4  426.11  5270.9  425.90  5322.5  430.61  5366.1  432.62
#Mann=5,-1,0
  4505.5    0.16       0  4928.8    0.12       0  4992.5    0.07       0
  4998.5    0.12       0  5270.9    0.16       0
Bank Sta=4945,5132
Exp/Cntr=0.3,0.1

Type RM Length L Ch R = 1,27045,380,380,380
BEGIN DESCRIPTION:
ROCK FALLS CREEK 40.0
END DESCRIPTION:
XS GIS Cut Line= 3
      2912175.01      6940924.99      2912425.00      6940425.00
      2912375.01      6940125.04
#Sta/Elev= 30
  4421.2  460.79  4457.5  454.51  4496.7  450.04  4547.0  439.56  4563.7  437.06
  4569.3  438.82  4586.1  435.53  4614.0  432.69  4630.8  428.77  4636.4  429.54
  4653.2  426.35  4658.8  427.56  4675.5  424.28  4681.1  424.75  4748.2  418.24
  4846.0  406.54  4871.4  405.34  4921.5  403.71  4927.1  404.76  4935.5  402.76
  4949.5  404.32  5048.2  402.47  5048.7  401.67  5054.2  402.47  5090.0  405.34
  5170.7  416.13  5177.5  417.49  5233.6  429.01  5264.1  433.59  5284.3  434.87
#Mann=5,-1,0
  4421.2    0.16       0  5048.2    0.07       0  5054.2    0.16       0
  5170.7    0.12       0  5177.5    0.16       0
Bank Sta=4871.4,5090
Exp/Cntr=0.3,0.1

Type RM Length L Ch R = 1,26665,411,411,411
BEGIN DESCRIPTION:
ROCK FALLS CREEK 39.0
END DESCRIPTION:
XS GIS Cut Line= 3
      2912975.02      6940675.03      2912775.00      6940325.00
      2912725.00      6940024.99
#Sta/Elev= 30
  4593.7  438.25  4616.8  434.98  4629.0  432.22  4666.4  427.08  4709.6  419.37
  4725.5  417.51  4731.9  415.87  4778.0  409.02  4784.5  407.36  4797.9  405.36
  4820.6  402.23  4843.5  399.89  4908.3  401.14  4916.2  399.87  4924.1  400.68
  4945.7  400.01  4951.5  400.81  4958.6  399.80  4959.1  399.00  4964.1  399.00
  4964.6  399.80  5024.7  400.81  5035.9  402.23  5078.0  410.18  5085.6  412.47
  5090.0  412.80  5159.1  424.48  5240.2  433.03  5268.0  435.14  5301.0  436.60
#Mann=5,-1,0
  4593.7    0.16       0  4797.9    0.12       0  4958.6    0.07       0
  4964.6    0.12       0  5090.0    0.16       0
Bank Sta=4820.6,5035.9
Exp/Cntr=0.3,0.1

Type RM Length L Ch R = 1,26254,318,318,318
BEGIN DESCRIPTION:
ROCK FALLS CREEK 38.0
END DESCRIPTION:
XS GIS Cut Line= 3
      2913025.00      6940674.99      2913175.00      6940325.00
      2913175.00      6939924.98
#Sta/Elev= 30
  4601.7  440.06  4634.3  435.55  4663.3  429.33  4744.9  416.94  4786.6  410.11
  4797.5  407.41  4815.7  404.52  4830.2  402.90  4851.9  398.89  4868.9  397.81
  4906.3  398.90  4924.3  397.54  4949.8  397.58  4968.0  396.42  4973.4  397.26
  5002.5  395.74  5039.5  395.67  5040.0  394.87  5045.0  394.87  5045.5  395.67
  5055.5  395.83  5069.2  396.55  5082.5  396.30  5134.2  397.81  5172.5  399.97
  5222.5  405.86  5272.5  414.11  5299.4  419.63  5322.5  424.07  5382.5  430.98
#Mann=7,-1,0
  4601.7    0.16       0  4924.3    0.12       0  5039.5    0.07       0
  5045.5    0.12       0  5055.5    0.16       0  5069.2    0.12       0
  5299.4    0.16       0
Bank Sta=4868.9,5134.2
Exp/Cntr=0.3,0.1

Type RM Length L Ch R = 1,25936,552,552,552
BEGIN DESCRIPTION:
ROCK FALLS CREEK 37.0
END DESCRIPTION:
XS GIS Cut Line= 3
      2913575.01      6940725.04      2913425.00      6940125.00
      2913275.00      6939775.00
#Sta/Elev= 30
  4411.8  424.72  4429.9  421.43  4435.0  421.93  4471.1  415.13  4476.3  415.31
  4553.6  404.90  4558.7  405.36  4594.8  399.94  4616.8  397.75  4648.9  394.57
  4679.3  393.88  4965.9  394.33  5024.7  393.40  5025.2  392.60  5030.2  392.60
  5030.7  393.40  5064.3  393.40  5084.7  393.43  5097.4  395.60  5124.4  397.75
  5197.1  407.19  5237.0  410.60  5302.3  423.53  5313.2  424.63  5326.8  427.49
  5349.4  430.97  5356.7  433.85  5367.6  434.02  5378.5  436.22  5411.1  440.02
#Mann=6,-1,0
  4411.8    0.16       0  4679.3    0.12       0  5024.7    0.07       0
  5030.7    0.12       0  5064.3    0.16       0  5326.8    0.05       0
Bank Sta=4616.8,5124.4
Exp/Cntr=0.3,0.1

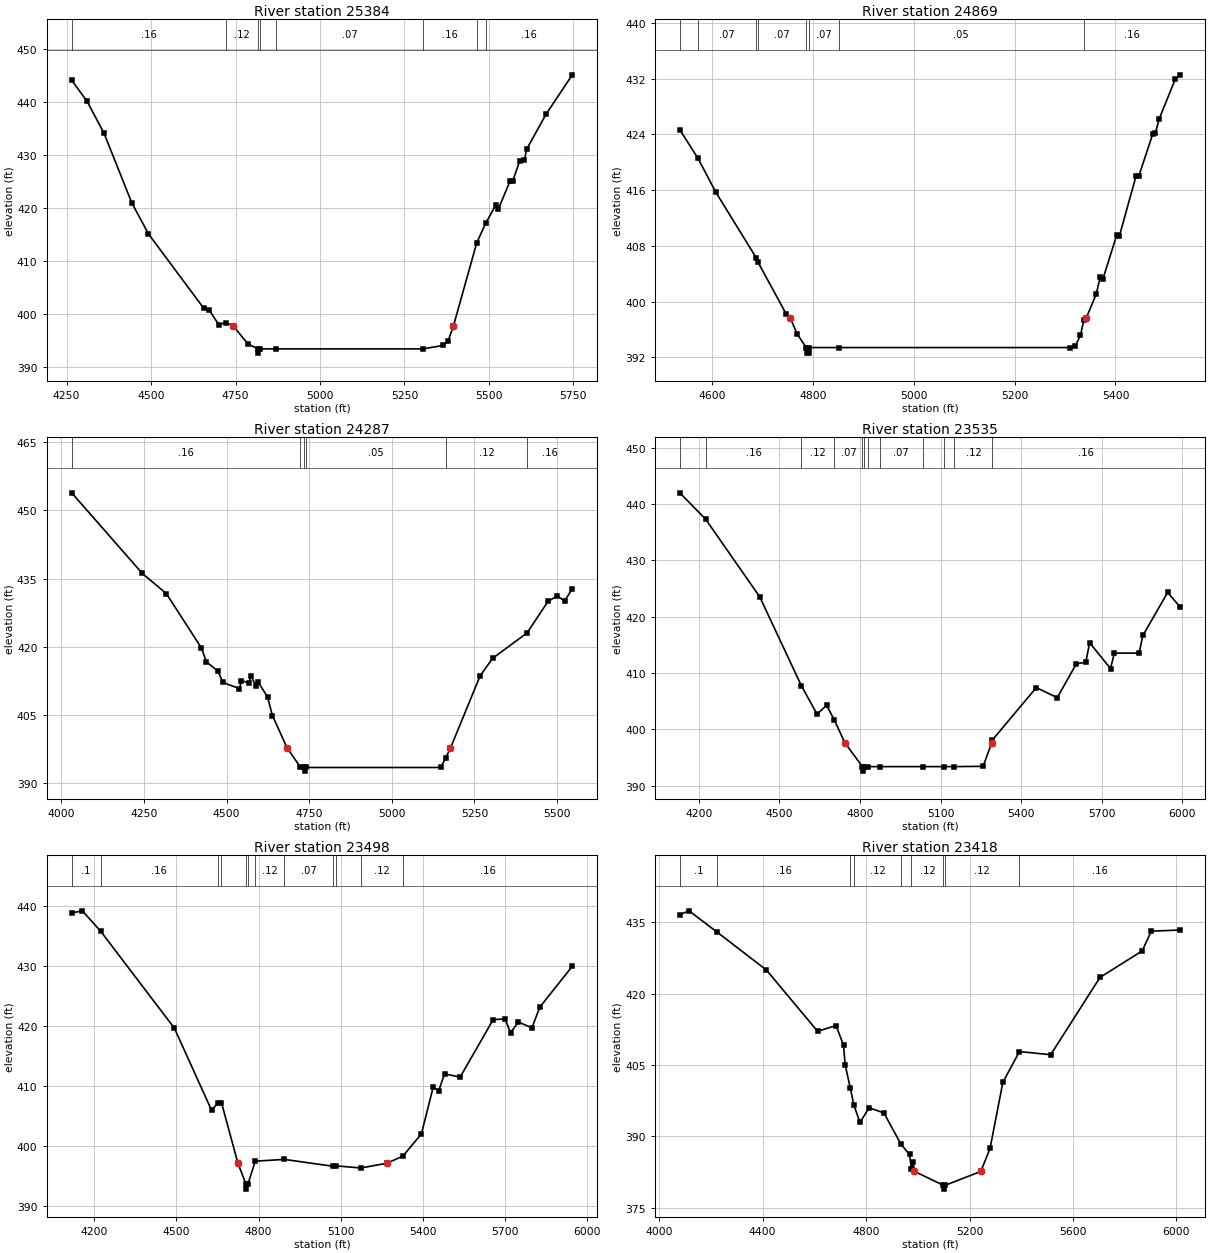
Type RM Length L Ch R = 1,25384,515,515,515
BEGIN DESCRIPTION:
ROCK FALLS CREEK 36.0
END DESCRIPTION:
XS GIS Cut Line= 3
      2914624.99      6940474.99      2913975.00      6940125.00
      2913425.02      6939625.02
#Sta/Elev= 30
  4265.2  444.11  4310.6  440.15  4360.9  434.11  4442.8  421.01  4492.3  415.11
  4656.2  401.05  4672.4  400.72  4700.0  398.00  4721.4  398.35  4743.3  397.71
  4787.6  394.29  4817.1  393.40  4817.6  392.60  4823.1  393.40  4869.9  393.40
  5304.5  393.40  5364.6  394.05  5378.8  394.85  5394.9  397.71  5463.9  413.43
  5491.4  417.24  5520.0  420.54  5527.5  419.73  5562.6  425.12  5570.0  425.01
  5591.0  428.89  5605.2  429.12  5611.9  431.13  5668.7  437.67  5746.7  445.14
#Mann=8,-1,0
  4265.2    0.16       0  4721.4    0.12       0  4817.1    0.07       0
  4823.1    0.12       0  4869.9    0.07       0  5304.5    0.16       0
  5463.9    0.12       0  5491.4    0.16       0
Bank Sta=4743.3,5394.9
Exp/Cntr=0.3,0.1

Type RM Length L Ch R = 1,24869,582,582,582
BEGIN DESCRIPTION:
ROCK FALLS CREEK 35.0
END DESCRIPTION:
XS GIS Cut Line= 3
      2914624.99      6939924.99      2914225.00      6939675.00
      2913725.00      6939525.00
#Sta/Elev= 30
  4535.1  424.67  4571.4  420.54  4606.4  415.73  4686.5  406.32  4689.6  405.75
  4746.8  398.16  4754.2  397.69  4768.0  395.36  4786.2  393.40  4786.7  392.60
  4791.8  392.60  4792.3  393.40  4850.2  393.40  5309.6  393.40  5320.0  393.59
  5330.4  395.15  5337.1  397.30  5342.3  397.69  5361.8  401.09  5369.6  403.53
  5374.8  403.20  5402.6  409.59  5407.9  409.45  5440.9  418.05  5446.1  417.98
  5474.0  424.06  5479.2  424.21  5487.0  426.28  5518.4  431.88  5528.8  432.55
#Mann=8,-1,0
  4535.1    0.16       0  4571.4    0.07       0  4686.5    0.12       0
  4689.6    0.07       0  4786.2   0.033       0  4792.3    0.07       0
  4850.2    0.05       0  5337.1    0.16       0
Bank Sta=4754.2,5342.3
Exp/Cntr=0.3,0.1

Type RM Length L Ch R = 1,24287,752,752,752
BEGIN DESCRIPTION:
ROCK FALLS CREEK 34.0
END DESCRIPTION:
XS GIS Cut Line= 3
      2915425.03      6939875.02      2914625.00      6939275.00
      2914375.01      6938825.01
#Sta/Elev= 30
  4031.5  453.87  4245.1  436.13  4318.0  431.67  4424.2  419.70  4438.8  416.68
  4474.2  414.59  4488.8  412.13  4538.8  410.77  4545.1  412.48  4568.0  412.06
  4574.2  413.54  4588.8  411.36  4595.1  412.26  4624.2  408.93  4638.8  404.84
  4683.7  397.67  4722.5  393.59  4735.8  393.40  4736.3  392.60  4741.9  393.40
  5148.2  393.40  5163.1  395.50  5177.6  397.67  5267.2  413.54  5304.9  417.42
  5409.5  423.03  5473.1  430.00  5500.6  431.15  5523.4  430.06  5546.3  432.79
#Mann=6,-1,0
  4031.5    0.16       0  4722.5    0.05       0  4735.8   0.033       0
  4741.9    0.05       0  5163.1    0.12       0  5409.5    0.16       0
Bank Sta=4683.7,5177.6
Exp/Cntr=0.3,0.1

Type RM Length L Ch R = 1,23535,37,37,37
BEGIN DESCRIPTION:
Mapping XS dc65ecbe
END DESCRIPTION:
XS GIS Cut Line= 4
      2915771.92      6939544.25      2915324.01      6938940.08
      2914964.63      6938601.54      2914559.18      6938133.71
#Sta/Elev= 30
  4128.7  441.97  4224.7  437.31  4426.5  423.52  4581.8  407.74  4640.0  402.70
  4675.5  404.28  4704.3  401.68  4743.7  397.62  4809.2  393.40  4809.7  392.60
  4815.6  393.40  4828.2  393.40  4874.4  393.40  5033.3  393.40  5111.4  393.40
  5152.0  393.40  5258.7  393.45  5290.7  397.62  5293.0  398.11  5456.9  407.42
  5534.8  405.63  5606.1  411.65  5641.2  411.90  5655.4  415.39  5733.3  410.79
  5747.6  413.53  5839.7  413.54  5853.9  416.67  5946.1  424.30  5993.6  421.67
#Mann=12,-1,0
  4128.7     0.1       0  4224.7    0.16       0  4581.8    0.12       0
  4704.3    0.07       0  4809.2    0.07       0  4815.6    0.07       0
  4828.2    0.12       0  4874.4    0.07       0  5033.3    0.12       0
  5111.4    0.07       0  5152.0    0.12       0  5293.0    0.16       0
Bank Sta=4743.7,5290.7
Exp/Cntr=0.3,0.1

Type RM Length L Ch R = 1,23498,80,80,80
BEGIN DESCRIPTION:
Mapping XS 08076b1c
END DESCRIPTION:
XS GIS Cut Line= 4
      2915820.62      6939524.62      2915415.14      6938972.87
      2915091.79      6938677.75      2914632.90      6938139.39
#Sta/Elev= 30
  4117.1  438.79  4156.0  439.14  4222.5  435.78  4492.4  419.64  4628.2  406.00
  4651.6  407.17  4664.6  407.27  4724.6  397.19  4754.6  393.68  4755.1  392.88
  4761.0  393.68  4788.1  397.53  4894.8  397.82  5074.0  396.67  5083.3  396.75
  5174.1  396.39  5269.8  397.19  5327.7  398.37  5395.4  402.05  5438.3  409.80
  5459.1  409.26  5479.9  412.04  5537.1  411.50  5657.9  421.07  5700.7  421.16
  5721.5  418.91  5750.1  420.65  5799.5  419.69  5828.0  423.12  5947.0  429.92
#Mann=12,-1,0
  4117.1     0.1       0  4222.5    0.16       0  4651.6    0.12       0
  4664.6    0.07       0  4754.6    0.07       0  4761.0    0.07       0
  4788.1    0.12       0  4894.8    0.07       0  5074.0    0.12       0
  5083.3    0.07       0  5174.1    0.12       0  5327.7    0.16       0
Bank Sta=4724.6,5269.8
Exp/Cntr=0.3,0.1

Type RM Length L Ch R = 1,23418,532,532,532
BEGIN DESCRIPTION:
Mapping XS b4c88a20
END DESCRIPTION:
XS GIS Cut Line= 4
      2915928.16      6939502.56      2915355.26      6938815.08
      2915120.88      6938601.54      2914641.75      6938059.91
#Sta/Elev= 30
  4080.0  436.57  4115.9  437.36  4225.0  432.86  4414.8  424.94  4612.6  412.08
  4684.2  413.27  4712.9  409.15  4719.4  405.01  4738.9  400.24  4752.9  396.57
  4776.6  392.95  4811.8  396.02  4869.1  394.94  4935.0  388.38  4968.0  386.22
  4975.4  383.25  4982.2  384.64  4987.1  382.67  5099.3  379.75  5099.8  378.95
  5105.7  379.75  5243.8  382.67  5279.5  387.52  5328.8  401.36  5392.9  407.82
  5513.7  407.16  5704.4  423.39  5867.5  428.94  5902.6  433.09  6015.1  433.34
#Mann=9,-1,0
  4080.0     0.1       0  4225.0    0.16       0  4738.9    0.07       0
  4752.9    0.12       0  4935.0    0.07       0  4975.4    0.12       0
  5099.3    0.07       0  5105.7    0.12       0  5392.9    0.16       0
Bank Sta=4987.1,5243.8
Exp/Cntr=0.3,0.1

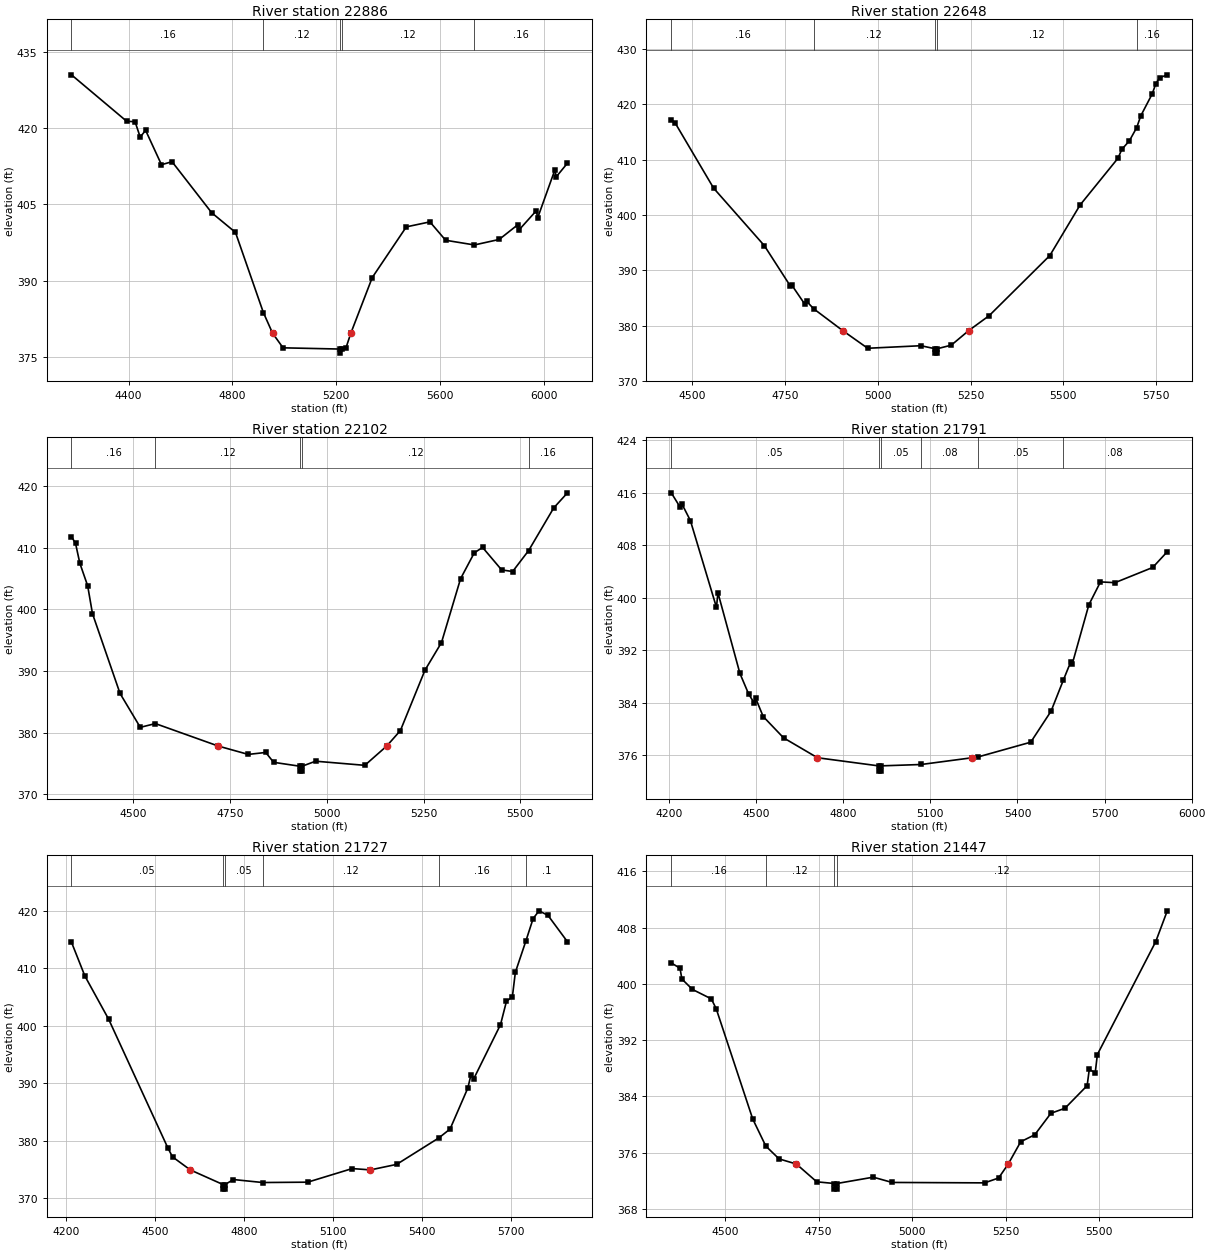
Type RM Length L Ch R = 1,22886,238,238,238
BEGIN DESCRIPTION:
Mapping XS 5c5ae6b3
END DESCRIPTION:
XS GIS Cut Line= 3
      2915870.89      6939325.54      2915709.42      6938486.96
      2915563.59      6937440.05
#Sta/Elev= 30
  4180.0  430.44  4392.8  421.32  4425.0  421.24  4444.7  418.23  4465.7  419.54
  4526.8  412.80  4567.5  413.39  4720.3  403.37  4811.9  399.51  4919.3  383.79
  4954.8  379.73  4995.2  376.86  5214.4  376.62  5214.9  375.82  5220.9  376.62
  5237.9  376.90  5256.3  379.73  5338.9  390.66  5470.1  400.60  5561.0  401.58
  5621.6  397.97  5732.5  397.05  5827.8  398.13  5899.4  401.01  5904.4  400.01
  5971.0  403.77  5976.0  402.35  6042.5  411.79  6047.6  410.41  6091.0  413.11
#Mann=5,-1,0
  4180.0    0.16       0  4919.3    0.12       0  5214.4    0.07       0
  5220.9    0.12       0  5732.5    0.16       0
Bank Sta=4954.8,5256.3
Exp/Cntr=0.3,0.1

Type RM Length L Ch R = 1,22648,546,546,546
BEGIN DESCRIPTION:
ROCK FALLS CREEK 31.0
END DESCRIPTION:
XS GIS Cut Line= 3
      2916074.99      6938974.98      2915925.00      6938425.00
      2915775.00      6937675.02
#Sta/Elev= 30
  4444.6  417.12  4454.9  416.67  4558.6  404.86  4695.1  394.46  4764.2  387.25
  4769.4  387.28  4803.9  383.88  4809.1  384.38  4827.9  383.04  4906.1  379.09
  4973.2  375.90  5116.6  376.36  5154.2  375.82  5154.7  375.02  5160.2  375.02
  5160.7  375.82  5198.2  376.46  5245.0  379.09  5300.2  381.80  5463.4  392.67
  5545.0  401.83  5646.9  410.28  5657.1  411.87  5677.5  413.42  5697.2  415.81
  5708.1  417.93  5738.7  421.88  5748.9  423.78  5759.1  424.84  5779.5  425.36
#Mann=5,-1,0
  4444.6    0.16       0  4827.9    0.12       0  5154.2    0.07       0
  5160.7    0.12       0  5697.2    0.16       0
Bank Sta=4906.1,5245
Exp/Cntr=0.3,0.1

Type RM Length L Ch R = 1,22102,311,311,311
BEGIN DESCRIPTION:
ROCK FALLS CREEK 30.0
END DESCRIPTION:
XS GIS Cut Line= 3
      2916575.00      6938825.01      2916375.00      6938175.00
      2915974.97      6937724.97
#Sta/Elev= 30
  4339.7  411.80  4350.2  410.71  4361.3  407.49  4381.6  403.82  4394.0  399.31
  4465.3  386.36  4517.6  380.87  4556.6  381.48  4719.5  377.83  4796.8  376.48
  4841.9  376.80  4862.2  375.20  4929.6  374.57  4930.1  373.77  4935.6  373.77
  4936.1  374.57  4970.7  375.38  5098.0  374.71  5154.5  377.83  5190.0  380.35
  5253.5  390.14  5296.2  394.62  5345.5  404.97  5381.0  409.17  5402.4  410.05
  5451.7  406.40  5480.1  406.14  5521.4  409.53  5586.3  416.45  5621.9  418.90
#Mann=5,-1,0
  4339.7    0.16       0  4556.6    0.12       0  4929.6    0.07       0
  4936.1    0.12       0  5521.4    0.16       0
Bank Sta=4719.5,5154.5
Exp/Cntr=0.3,0.1

Type RM Length L Ch R = 1,21791,64,64,64
BEGIN DESCRIPTION:
Mapping XS 023452e4
END DESCRIPTION:
XS GIS Cut Line= 3
      2916752.41      6938990.64      2916689.91      6938185.99
      2916674.29      6937284.90
#Sta/Elev= 30
  4207.7  415.99  4238.6  413.78  4243.6  414.36  4273.5  411.77  4363.4  398.53
  4368.4  400.78  4444.1  388.48  4474.1  385.35  4493.1  383.98  4498.2  384.70
  4524.3  381.91  4594.5  378.66  4711.2  375.63  4922.1  374.39  4922.6  373.59
  4928.4  373.59  4928.9  374.39  5068.3  374.60  5244.0  375.63  5264.1  375.75
  5445.8  378.00  5515.8  382.73  5557.9  387.44  5583.7  390.26  5588.7  389.91
  5645.9  398.93  5685.9  402.42  5735.9  402.30  5865.9  404.62  5916.0  407.02
#Mann=6,-1,0
  4207.7    0.05       0  4922.1    0.04       0  4928.9    0.05       0
  5068.3    0.08       0  5264.1    0.05       0  5557.9    0.08       0
Bank Sta=4711.2,5244
Exp/Cntr=0.3,0.1

Type RM Length L Ch R = 1,21727,280,280,280
BEGIN DESCRIPTION:
Mapping XS 3e5d6664
END DESCRIPTION:
XS GIS Cut Line= 3
      2916799.29      6938980.27      2916755.02      6938199.01
      2916778.43      6937309.23
#Sta/Elev= 30
  4219.2  414.56  4264.5  408.66  4344.7  401.13  4545.0  378.64  4560.1  377.16
  4619.8  374.90  4730.2  372.35  4730.7  371.55  4736.5  371.55  4737.0  372.35
  4765.3  373.22  4864.1  372.70  5015.7  372.76  5165.8  375.13  5227.4  374.90
  5315.8  375.86  5458.0  380.47  5495.9  382.02  5555.9  389.17  5565.9  391.38
  5576.1  390.81  5665.9  400.19  5686.0  404.25  5706.0  405.07  5716.0  409.30
  5751.6  414.78  5776.0  418.68  5796.0  420.02  5826.0  419.23  5891.8  414.63
#Mann=6,-1,0
  4219.2    0.05       0  4730.2    0.07       0  4737.0    0.05       0
  4864.1    0.12       0  5458.0    0.16       0  5751.6     0.1       0
Bank Sta=4619.8,5227.4
Exp/Cntr=0.3,0.1

Type RM Length L Ch R = 1,21447,462,462,462
BEGIN DESCRIPTION:
ROCK FALLS CREEK 29.0
END DESCRIPTION:
XS GIS Cut Line= 3
      2916957.28      6938881.26      2917026.60      6938241.71
      2917363.14      6937649.33
#Sta/Elev= 30
  4356.7  402.97  4380.0  402.22  4385.1  400.68  4413.3  399.20  4463.6  397.86
  4476.7  396.46  4574.2  380.78  4609.2  376.92  4644.6  375.10  4690.8  374.37
  4745.2  371.84  4792.1  371.60  4792.6  370.80  4798.4  370.80  4798.9  371.60
  4896.1  372.50  4946.4  371.75  5193.3  371.69  5230.8  372.38  5256.6  374.37
  5289.9  377.54  5327.4  378.53  5370.6  381.59  5408.1  382.30  5467.3  385.52
  5473.0  387.82  5488.9  387.36  5494.6  389.94  5650.4  405.99  5681.3  410.38
#Mann=4,-1,0
  4356.7    0.16       0  4609.2    0.12       0  4792.1    0.07       0
  4798.9    0.12       0
Bank Sta=4690.8,5256.6
Exp/Cntr=0.3,0.1

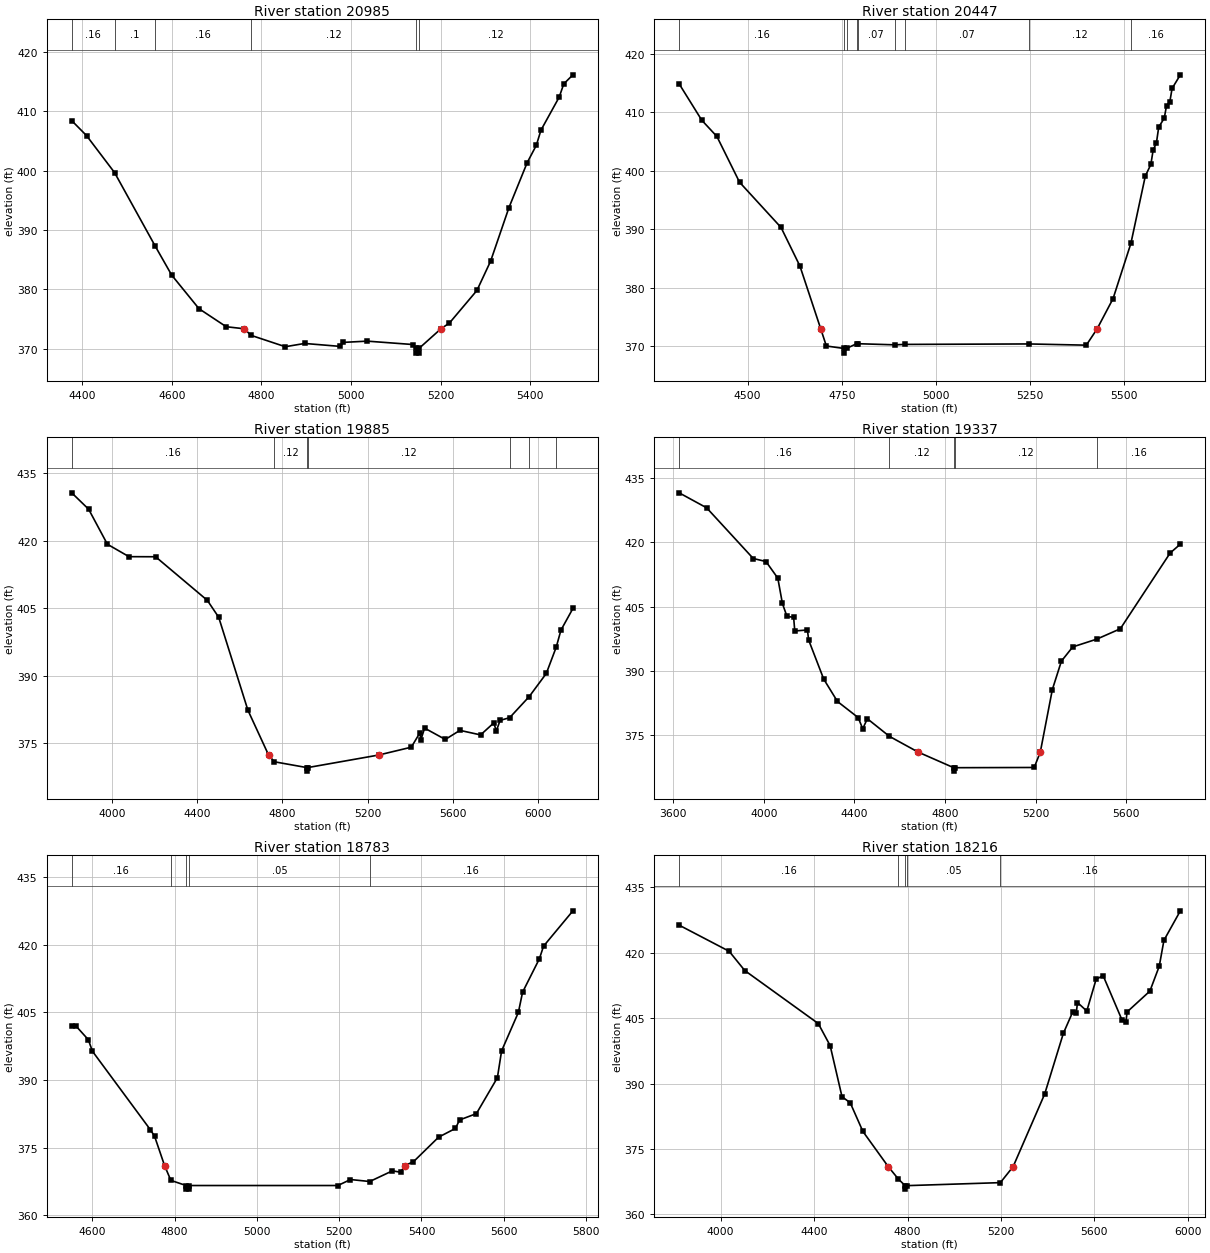
Type RM Length L Ch R = 1,20985,538,538,538
BEGIN DESCRIPTION:
ROCK FALLS CREEK 28.0
END DESCRIPTION:
XS GIS Cut Line= 3
      2917325.00      6939025.02      2917425.00      6938425.00
      2917525.00      6937924.99
#Sta/Elev= 30
  4376.9  408.43  4409.9  405.91  4472.5  399.67  4563.4  387.25  4600.0  382.39
  4660.8  376.74  4721.6  373.70  4762.3  373.35  4776.5  372.26  4853.4  370.33
  4896.5  370.88  4975.1  370.39  4982.7  371.06  5036.2  371.27  5138.2  370.70
  5144.9  370.05  5145.4  369.25  5151.3  369.25  5151.8  370.05  5200.6  373.35
  5219.7  374.33  5280.9  379.81  5311.5  384.76  5352.3  393.76  5393.1  401.36
  5413.5  404.28  5423.7  406.81  5464.5  412.40  5474.7  414.63  5495.1  416.15
#Mann=6,-1,0
  4376.9    0.16       0  4472.5     0.1       0  4563.4    0.16       0
  4776.5    0.12       0  5144.9    0.07       0  5151.8    0.12       0
Bank Sta=4762.3,5200.6
Exp/Cntr=0.3,0.1

Type RM Length L Ch R = 1,20447,562,562,562
BEGIN DESCRIPTION:
ROCK FALLS CREEK 27.0
END DESCRIPTION:
XS GIS Cut Line= 3
      2918025.00      6939125.05      2917975.00      6938475.00
      2917575.02      6937925.03
#Sta/Elev= 30
  4318.0  414.85  4378.2  408.63  4418.3  405.86  4478.5  398.04  4588.8  390.30
  4639.0  383.70  4694.3  372.96  4709.2  370.04  4755.9  369.62  4756.4  368.82
  4762.8  369.62  4790.2  370.45  4792.3  370.43  4890.6  370.24  4917.1  370.31
  5247.0  370.39  5400.0  370.18  5428.7  372.96  5471.1  378.13  5518.5  387.57
  5556.9  399.10  5571.6  401.08  5577.8  403.58  5586.3  404.72  5592.5  407.47
  5607.2  408.98  5613.3  411.15  5621.8  411.70  5628.0  414.07  5650.0  416.40
#Mann=9,-1,0
  4318.0    0.16       0  4755.9    0.07       0  4762.8    0.16       0
  4790.2    0.12       0  4792.3    0.07       0  4890.6    0.12       0
  4917.1    0.07       0  5247.0    0.12       0  5518.5    0.16       0
Bank Sta=4694.3,5428.7
Exp/Cntr=0.3,0.1

Type RM Length L Ch R = 1,19885,548,548,548
BEGIN DESCRIPTION:
ROCK FALLS CREEK 26.0
END DESCRIPTION:
XS GIS Cut Line= 3
      2918077.80      6939558.36      2918525.00      6938475.00
      2918026.35      6937408.66
#Sta/Elev= 30
  3812.6  430.68  3891.8  427.04  3979.8  419.25  4080.9  416.49  4205.7  416.47
  4448.2  406.78  4501.5  403.02  4638.4  382.36  4735.3  372.40  4762.1  370.90
  4913.2  369.62  4913.7  368.82  4920.2  369.62  5251.6  372.40  5404.1  374.14
  5443.9  377.27  5449.4  375.85  5466.7  378.38  5563.6  375.86  5632.1  377.88
  5729.0  376.87  5790.5  379.52  5803.1  377.78  5820.4  380.10  5865.3  380.70
  5956.9  385.39  6037.0  390.53  6083.8  396.41  6105.6  400.15  6161.8  404.98
#Mann=7,-1,0
  3812.6    0.16       0  4762.1    0.12       0  4913.2    0.07       0
  4920.2    0.12       0  5865.3    0.16       0  5956.9    0.12       0
  6083.8    0.16       0
Bank Sta=4735.3,5251.6
Exp/Cntr=0.3,0.1

Type RM Length L Ch R = 1,19337,554,554,554
BEGIN DESCRIPTION:
ROCK FALLS CREEK 25.0
END DESCRIPTION:
XS GIS Cut Line= 3
      2918806.98      6939844.77      2919025.00      6938525.00
      2919050.00      6937650.01
#Sta/Elev= 30
  3626.5  431.53  3747.9  428.03  3953.7  416.21  4009.8  415.51  4062.1  411.63
  4082.4  405.72  4102.6  402.69  4131.9  402.51  4137.0  399.31  4193.0  399.54
  4198.1  397.22  4264.8  388.08  4325.6  382.86  4416.8  379.11  4437.1  376.50
  4457.4  378.84  4554.7  374.74  4681.0  371.08  4838.7  367.42  4839.3  366.62
  4846.3  367.42  5194.3  367.47  5221.2  371.08  5274.3  385.65  5314.3  392.28
  5364.3  395.59  5470.7  397.41  5574.4  399.82  5794.5  417.50  5839.5  419.56
#Mann=5,-1,0
  3626.5    0.16       0  4554.7    0.12       0  4838.7    0.07       0
  4846.3    0.12       0  5470.7    0.16       0
Bank Sta=4681,5221.2
Exp/Cntr=0.3,0.1

Type RM Length L Ch R = 1,18783,567,567,567
BEGIN DESCRIPTION:
ROCK FALLS CREEK 24.0
END DESCRIPTION:
XS GIS Cut Line= 3
      2919625.00      6938875.02      2919575.00      6938425.00
      2919425.01      6937675.05
#Sta/Elev= 30
  4550.3  401.88  4560.4  401.98  4590.6  398.92  4600.6  396.36  4741.5  378.93
  4751.6  377.49  4775.9  370.98  4791.1  367.71  4828.2  366.57  4828.8  365.77
  4835.3  365.77  4835.9  366.57  5196.9  366.57  5227.5  367.90  5274.3  367.46
  5329.4  369.83  5349.8  369.51  5358.9  370.98  5380.4  371.84  5441.6  377.30
  5482.4  379.23  5492.6  381.12  5533.4  382.52  5584.4  390.49  5594.6  396.43
  5635.4  404.98  5645.6  409.46  5686.4  416.87  5696.6  419.68  5767.9  427.51
#Mann=5,-1,0
  4550.3    0.16       0  4791.1    0.05       0  4828.2   0.033       0
  4835.9    0.05       0  5274.3    0.16       0
Bank Sta=4775.9,5358.9
Exp/Cntr=0.3,0.1

Type RM Length L Ch R = 1,18216,535,535,535
BEGIN DESCRIPTION:
ROCK FALLS CREEK 23.0
END DESCRIPTION:
XS GIS Cut Line= 3
      2919923.00      6939471.56      2920125.00      6938325.00
      2920079.25      6937344.79
#Sta/Elev= 30
  3822.3  426.34  4036.3  420.35  4103.1  415.93  4417.9  403.76  4468.7  398.69
  4519.4  386.98  4554.6  385.58  4608.8  379.01  4717.4  370.93  4760.8  368.07
  4789.7  366.57  4790.3  365.77  4797.5  366.57  5197.3  367.26  5251.9  370.93
  5387.0  387.59  5467.0  401.53  5507.1  406.43  5522.4  406.27  5527.4  408.59
  5567.2  406.64  5607.2  413.92  5637.2  414.76  5717.3  404.67  5734.8  404.12
  5739.8  406.43  5837.4  411.21  5877.5  416.93  5897.5  422.86  5967.8  429.63
#Mann=5,-1,0
  3822.3    0.16       0  4760.8    0.05       0  4789.7   0.033       0
  4797.5    0.05       0  5197.3    0.16       0
Bank Sta=4717.4,5251.9
Exp/Cntr=0.3,0.1