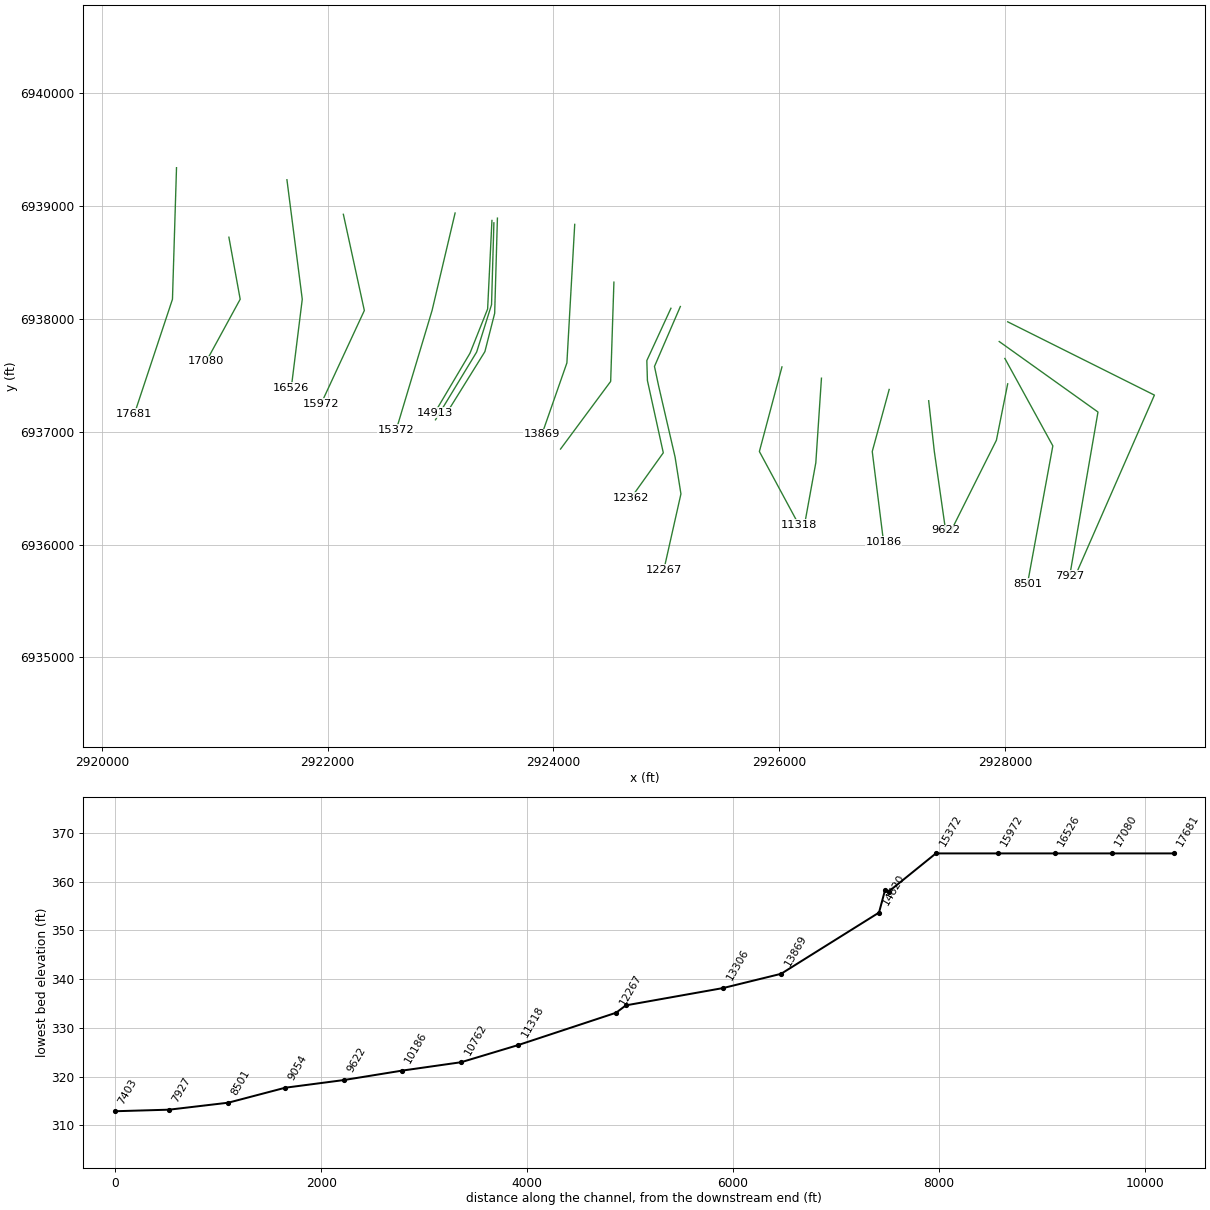
HEC-RAS study ROCK FALLS CREEK.prj: ROCK FALLS CREEK Base Level Engineering

--- ROCK FALLS CREEK.g01 (geometry) --- (continued)

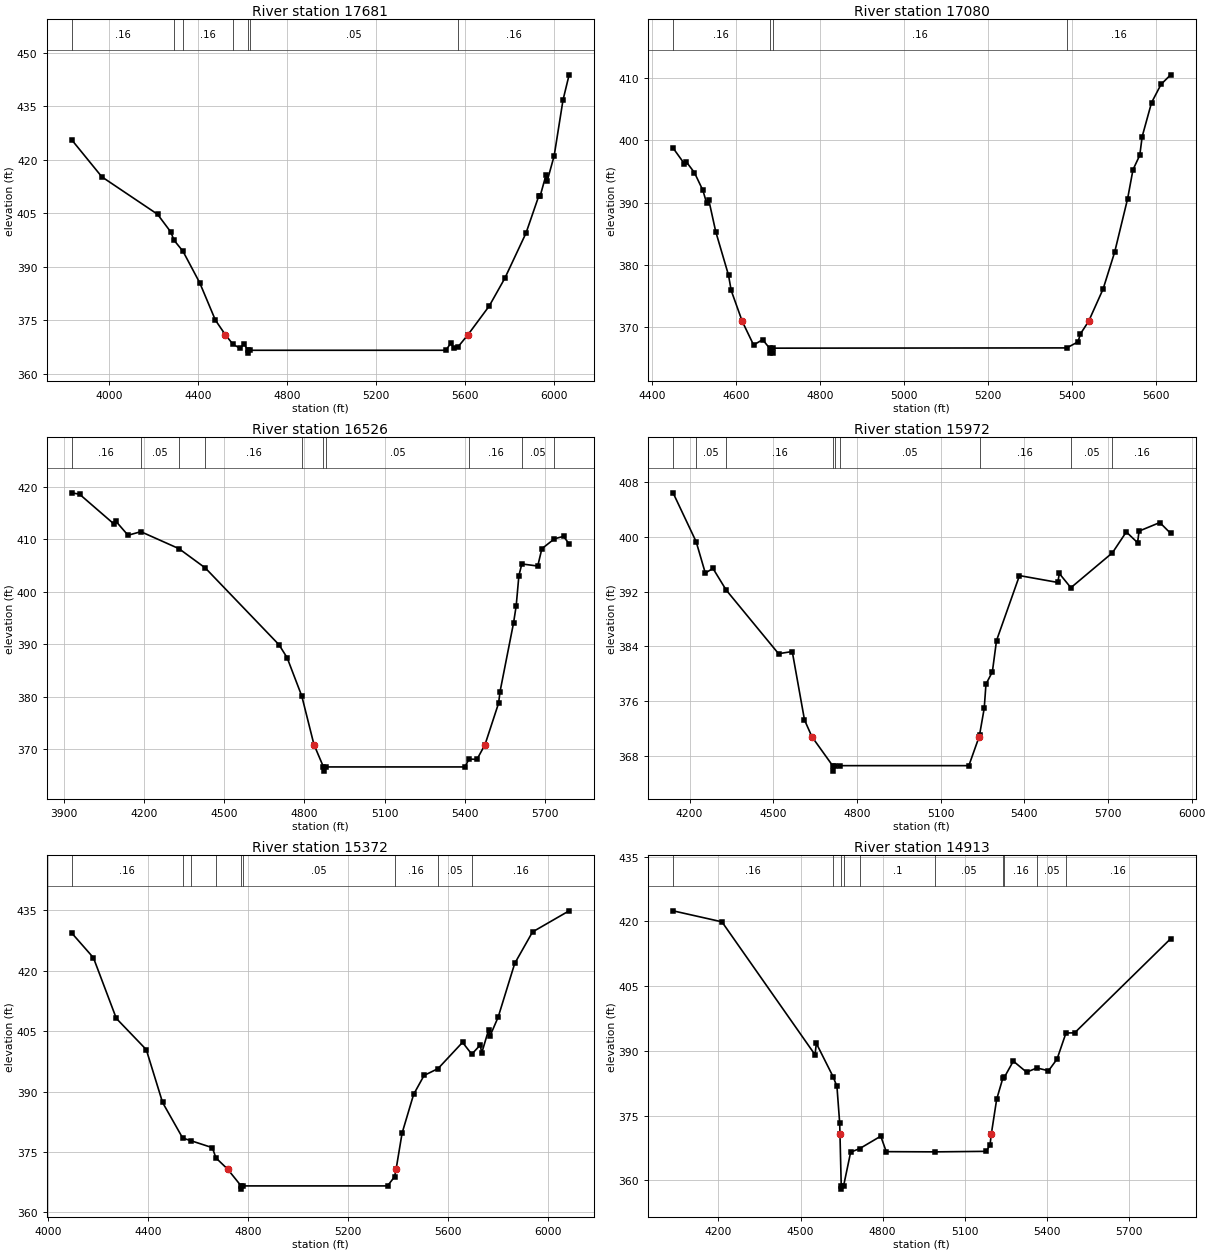
Type RM Length L Ch R = 1,17681,601,601,601
BEGIN DESCRIPTION:
ROCK FALLS CREEK 22.0
END DESCRIPTION:
XS GIS Cut Line= 3
      2920660.85      6939341.38      2920625.00      6938175.00
      2920287.89      6937159.10
#Sta/Elev= 30
  3832.5  425.67  3968.9  415.22  4219.1  404.73  4279.1  399.73  4292.7  397.49
  4333.6  394.34  4409.1  385.47  4479.2  375.04  4524.1  370.92  4558.3  368.26
  4589.2  367.17  4609.2  368.23  4625.3  366.57  4626.0  365.77  4633.2  366.57
  5515.7  366.57  5536.8  368.48  5553.8  367.11  5570.8  367.57  5614.9  370.92
  5710.6  378.99  5780.9  386.80  5875.9  399.44  5934.0  409.97  5939.3  409.77
  5965.7  415.70  5970.9  413.98  6002.6  421.15  6042.5  436.83  6069.8  443.85
#Mann=7,-1,0
  3832.5    0.16       0  4292.7    0.05       0  4333.6    0.16       0
  4558.3    0.05       0  4625.3   0.033       0  4633.2    0.05       0
  5570.8    0.16       0
Bank Sta=4524.1,5614.9
Exp/Cntr=0.3,0.1

Type RM Length L Ch R = 1,17080,554,554,554
BEGIN DESCRIPTION:
ROCK FALLS CREEK 21.0
END DESCRIPTION:
XS GIS Cut Line= 3
      2921125.00      6938725.01      2921225.00      6938175.00
      2920925.01      6937625.03
#Sta/Elev= 30
  4449.6  398.79  4476.3  396.28  4481.4  396.54  4500.4  394.84  4520.8  391.96
  4529.7  389.88  4534.7  390.42  4551.3  385.32  4581.7  378.33  4588.1  375.86
  4614.4  370.89  4641.5  367.08  4663.1  367.94  4679.4  366.57  4680.1  365.77
  4686.7  365.77  4687.3  366.57  5387.5  366.61  5414.4  367.58  5420.1  368.86
  5439.7  370.89  5474.2  376.09  5501.8  382.04  5532.6  390.63  5545.4  395.29
  5561.6  397.63  5567.3  400.63  5589.6  406.09  5612.3  409.04  5635.1  410.57
#Mann=4,-1,0
  4449.6    0.16       0  4679.4   0.033       0  4687.3    0.16       0
  5387.5    0.16       0
Bank Sta=4614.4,5439.7
Exp/Cntr=0.3,0.1

Type RM Length L Ch R = 1,16526,554,554,554
BEGIN DESCRIPTION:
ROCK FALLS CREEK 20.0
END DESCRIPTION:
XS GIS Cut Line= 3
      2921639.15      6939234.54      2921775.00      6938175.00
      2921677.50      6937388.64
#Sta/Elev= 30
  3929.5  418.91  3959.3  418.65  4089.4  412.90  4094.4  413.53  4140.8  410.81
  4188.7  411.49  4331.1  408.25  4429.5  404.57  4705.3  389.90  4735.6  387.43
  4790.6  380.08  4836.0  370.83  4871.5  366.57  4872.2  365.77  4880.0  366.57
  5400.8  366.57  5415.5  368.08  5445.4  368.01  5475.6  370.83  5526.4  378.75
  5531.8  380.96  5582.2  394.04  5592.2  397.33  5602.3  403.11  5613.3  405.33
  5672.8  404.93  5688.2  408.24  5735.2  410.13  5769.2  410.60  5790.1  409.16
#Mann=10,-1,0
  3929.5    0.16       0  4188.7    0.05       0  4331.1    0.08       0
  4429.5    0.16       0  4790.6    0.05       0  4871.5   0.033       0
  4880.0    0.05       0  5415.5    0.16       0  5613.3    0.05       0
  5735.2    0.16       0
Bank Sta=4836,5475.6
Exp/Cntr=0.3,0.1

Type RM Length L Ch R = 1,15972,600,600,600
BEGIN DESCRIPTION:
ROCK FALLS CREEK 19.0
END DESCRIPTION:
XS GIS Cut Line= 3
      2922139.14      6938927.99      2922325.00      6938075.00
      2921941.84      6937248.72
#Sta/Elev= 30
  4140.8  406.42  4223.6  399.28  4256.4  394.70  4283.9  395.38  4331.2  392.22
  4519.0  382.92  4568.1  383.24  4612.0  373.25  4638.5  370.80  4712.8  366.57
  4713.5  365.77  4721.3  366.57  4741.0  366.57  5201.2  366.57  5238.1  370.80
  5239.7  371.08  5256.3  374.94  5262.6  378.48  5285.5  380.27  5300.4  384.84
  5382.7  394.33  5520.1  393.33  5525.6  394.64  5566.9  392.56  5715.9  397.66
  5765.7  400.71  5806.0  399.14  5811.5  400.83  5885.8  402.08  5924.6  400.50
#Mann=9,-1,0
  4140.8    0.16       0  4223.6    0.05       0  4331.2    0.16       0
  4712.8   0.033       0  4721.3    0.16       0  4741.0    0.05       0
  5239.7    0.16       0  5566.9    0.05       0  5715.9    0.16       0
Bank Sta=4638.5,5238.1
Exp/Cntr=0.3,0.1

Type RM Length L Ch R = 1,15372,459,459,459
BEGIN DESCRIPTION:
ROCK FALLS CREEK 18.0
END DESCRIPTION:
XS GIS Cut Line= 3
      2923129.08      6938939.45      2922925.00      6938075.00
      2922608.16      6937019.13
#Sta/Elev= 30
  4094.5  429.44  4182.0  423.25  4273.7  408.17  4393.5  400.42  4458.7  387.29
  4539.2  378.45  4571.1  377.82  4657.7  376.07  4672.2  373.52  4718.7  370.75
  4772.8  366.57  4773.6  365.77  4781.6  366.57  5358.6  366.57  5387.0  368.87
  5393.0  370.75  5416.8  379.66  5463.0  389.30  5504.7  394.00  5560.7  395.71
  5658.7  402.23  5695.7  399.28  5730.0  401.61  5735.2  399.52  5763.1  405.36
  5768.3  403.76  5801.3  408.51  5867.4  421.82  5938.8  429.66  6085.1  434.90
#Mann=9,-1,0
  4094.5    0.16       0  4539.2    0.05       0  4571.1    0.08       0
  4672.2    0.05       0  4772.8   0.033       0  4781.6    0.05       0
  5387.0    0.16       0  5560.7    0.05       0  5695.7    0.16       0
Bank Sta=4718.7,5393
Exp/Cntr=0.3,0.1

Type RM Length L Ch R = 1,14913,35,35,35
BEGIN DESCRIPTION:
Mapping XS 2d9502a1
END DESCRIPTION:
XS GIS Cut Line= 4
      2923455.47      6938873.43      2923417.27      6938088.74
      2923261.02      6937696.38      2922949.70      6937170.58
#Sta/Elev= 30
  4033.9  422.46  4212.5  419.91  4552.8  389.10  4557.8  391.72  4618.7  384.03
  4633.0  381.75  4643.1  373.20  4644.1  370.68  4648.7  358.73  4649.5  357.93
  4657.5  358.73  4683.1  366.49  4716.8  367.35  4793.2  370.21  4813.3  366.62
  4992.9  366.57  5178.8  366.69  5192.7  368.19  5197.3  370.68  5217.0  378.78
  5239.8  383.73  5244.8  383.84  5277.8  387.61  5326.5  385.04  5363.9  386.03
  5406.4  385.37  5437.7  388.09  5470.3  394.13  5502.0  394.17  5852.9  415.99
#Mann=10,-1,0
  4033.9    0.16       0  4618.7    0.08       0  4648.7   0.033       0
  4657.5    0.08       0  4716.8     0.1       0  4992.9    0.05       0
  5239.8    0.08       0  5244.8    0.16       0  5363.9    0.05       0
  5470.3    0.16       0
Bank Sta=4644.1,5197.3
Exp/Cntr=0.3,0.1

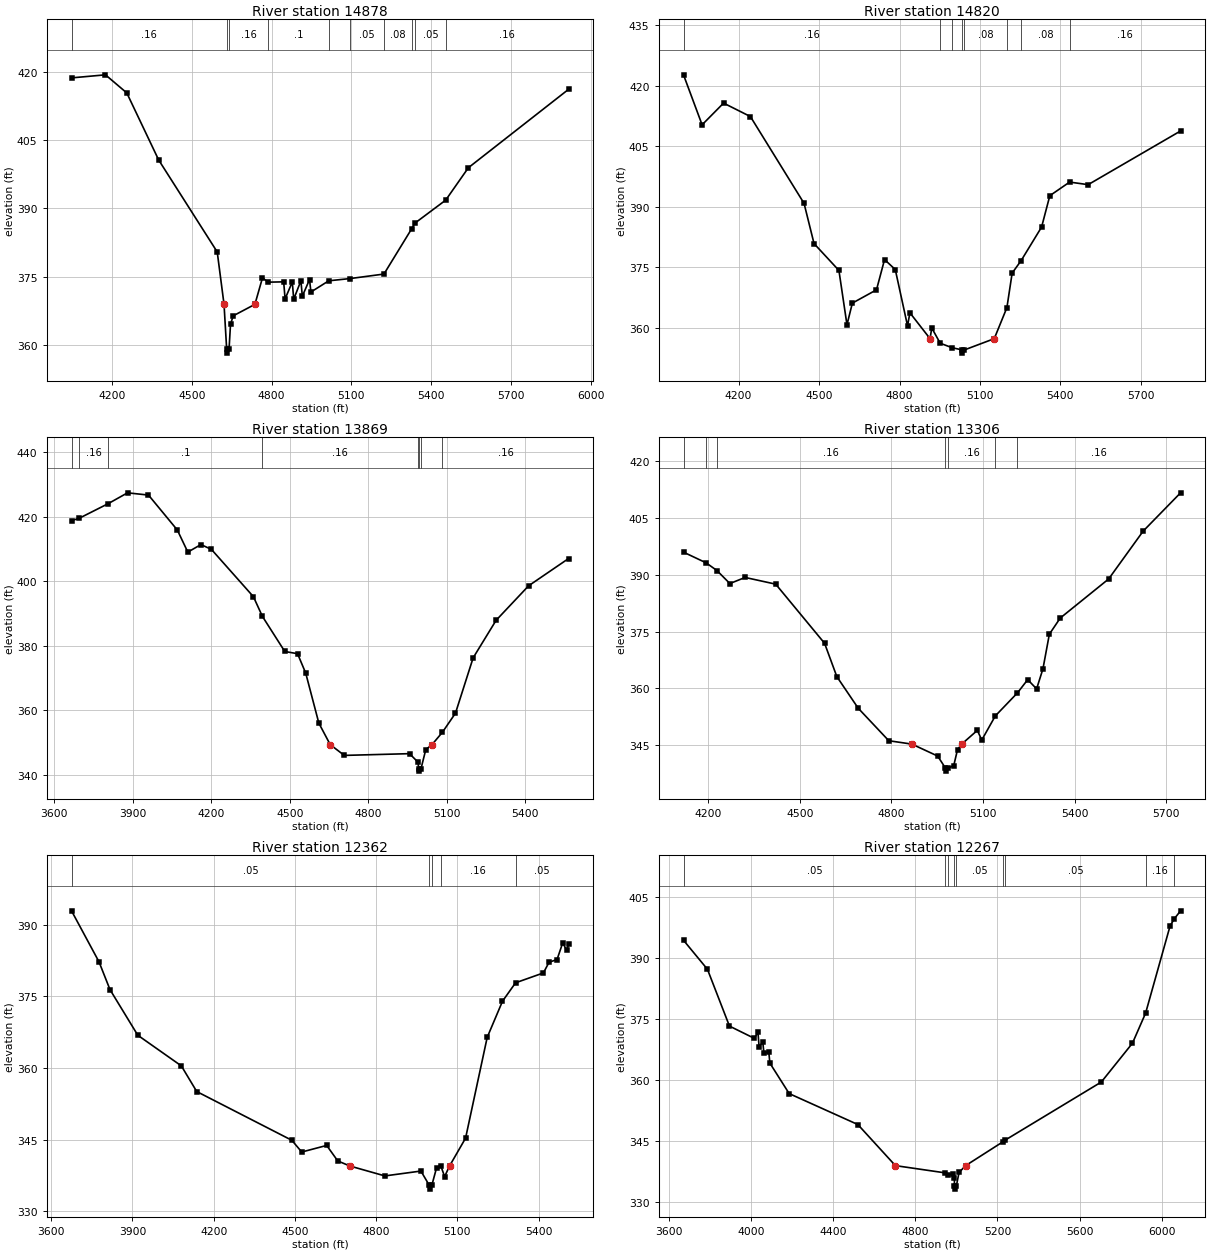
Type RM Length L Ch R = 1,14878,58,58,58
BEGIN DESCRIPTION:
Mapping XS 97b2327d
END DESCRIPTION:
XS GIS Cut Line= 4
      2923472.83      6938852.67      2923452.00      6938126.93
      2923320.05      6937706.79      2922955.46      6937106.08
#Sta/Elev= 30
  4047.6  418.61  4175.3  419.28  4255.4  415.31  4375.4  400.59  4595.5  380.42
  4621.1  368.92  4631.1  359.02  4631.9  358.22  4639.9  359.02  4645.5  364.56
  4655.5  366.40  4737.2  368.92  4765.6  374.73  4787.5  373.79  4845.4  373.86
  4850.7  370.12  4877.8  373.83  4883.1  370.05  4910.2  374.09  4915.5  370.71
  4942.6  374.35  4947.9  371.63  5014.9  374.09  5095.3  374.58  5222.5  375.57
  5326.9  385.52  5339.6  386.77  5454.7  391.79  5539.8  398.89  5916.7  416.10
#Mann=10,-1,0
  4047.6    0.16       0  4631.1    0.07       0  4639.9    0.16       0
  4787.5     0.1       0  5014.9    0.08       0  5095.3    0.05       0
  5222.5    0.08       0  5326.9    0.16       0  5339.6    0.05       0
  5454.7    0.16       0
Bank Sta=4621.1,4737.2
Exp/Cntr=0.3,0.1

Type RM Length L Ch R = 1,14820,951,951,951
BEGIN DESCRIPTION:
Mapping XS 2102875f
END DESCRIPTION:
XS GIS Cut Line= 4
      2923504.08      6938894.29      2923479.77      6938050.54
      2923392.97      6937710.26      2923045.72      6937151.20
#Sta/Elev= 30
  3994.6  422.74  4063.9  410.33  4144.0  415.72  4244.0  412.38  4444.1  390.82
  4481.3  380.84  4574.1  374.17  4604.1  360.68  4624.2  366.06  4714.2  369.36
  4744.2  376.87  4784.2  374.40  4830.0  360.41  4838.7  363.66  4913.9  357.23
  4920.3  359.89  4951.7  356.10  4995.9  354.99  5033.3  354.44  5034.1  353.64
  5042.1  354.44  5153.3  357.23  5200.5  364.95  5220.0  373.51  5253.5  376.61
  5329.8  384.94  5360.5  392.73  5434.3  396.11  5503.4  395.47  5848.0  408.80
#Mann=8,-1,0
  3994.6    0.16       0  4951.7     0.1       0  4995.9    0.08       0
  5033.3    0.07       0  5042.1    0.08       0  5200.5    0.16       0
  5253.5    0.08       0  5434.3    0.16       0
Bank Sta=4913.9,5153.3
Exp/Cntr=0.3,0.1

Type RM Length L Ch R = 1,13869,563,563,563
BEGIN DESCRIPTION:
ROCK FALLS CREEK 16.0
END DESCRIPTION:
XS GIS Cut Line= 3
      2924188.98      6938838.77      2924119.53      6937610.44
      2923898.74      6936978.38
#Sta/Elev= 30
  3666.0  418.83  3694.3  419.50  3806.6  424.10  3880.1  427.44  3960.2  426.74
  4070.4  415.90  4110.5  409.05  4160.6  411.38  4200.6  409.90  4361.2  395.21
  4395.5  389.11  4481.1  378.21  4529.9  377.52  4561.2  371.48  4611.3  355.98
  4654.8  349.30  4708.6  345.96  4957.9  346.50  4990.2  343.87  4992.8  341.88
  4993.7  341.08  5001.9  341.88  5020.0  347.75  5043.8  349.30  5083.9  353.17
  5133.6  359.08  5201.0  376.23  5288.9  387.89  5413.1  398.59  5565.8  407.05
#Mann=8,-1,0
  3666.0     0.1       0  3694.3    0.16       0  3806.6     0.1       0
  4395.5    0.16       0  4990.2    0.12       0  4992.8    0.07       0
  5001.9    0.12       0  5083.9    0.16       0
Bank Sta=4654.8,5043.8
Exp/Cntr=0.3,0.1

Type RM Length L Ch R = 1,13306,944,944,944
BEGIN DESCRIPTION:
ROCK FALLS CREEK 15.0
END DESCRIPTION:
XS GIS Cut Line= 3
      2924536.20      6938326.60      2924507.38      6937446.47
      2924063.11      6936846.56
#Sta/Elev= 30
  4119.4  395.99  4193.4  393.17  4228.8  391.14  4271.1  387.70  4321.1  389.31
  4421.2  387.54  4581.2  371.92  4621.3  363.12  4691.3  354.77  4791.4  346.19
  4867.2  345.29  4951.4  342.14  4976.9  338.96  4977.7  338.16  4986.1  338.96
  5004.0  339.63  5016.4  343.85  5029.9  345.29  5081.2  348.92  5095.8  346.38
  5140.1  352.74  5212.5  358.82  5246.1  362.32  5275.3  359.88  5296.1  365.21
  5317.0  374.32  5352.5  378.58  5511.1  388.91  5624.0  401.54  5746.5  411.66
#Mann=7,-1,0
  4119.4    0.16       0  4193.4    0.05       0  4228.8    0.16       0
  4976.9    0.07       0  4986.1    0.16       0  5140.1    0.12       0
  5212.5    0.16       0
Bank Sta=4867.2,5029.9
Exp/Cntr=0.3,0.1

Type RM Length L Ch R = 1,12362,95,95,95
BEGIN DESCRIPTION:
Mapping XS 115d32fe
END DESCRIPTION:
XS GIS Cut Line= 5
      2925041.40      6938094.81      2924827.86      6937631.27
      2924833.07      6937454.19      2924973.70      6936813.56
      2924687.26      6936412.55
#Sta/Elev= 30
  3674.8  392.96  3776.5  382.25  3816.9  376.44  3919.7  366.87  4080.5  360.45
  4137.4  355.07  4488.7  344.85  4525.3  342.39  4617.4  343.77  4658.4  340.52
  4703.5  339.45  4832.4  337.38  4965.5  338.40  4996.5  335.41  4997.4  334.61
  5005.8  335.41  5023.6  339.13  5039.2  339.46  5053.1  337.24  5071.2  339.45
  5130.5  345.30  5210.4  366.43  5266.9  374.01  5315.2  377.87  5418.0  379.94
  5438.9  382.18  5468.4  382.75  5489.3  386.23  5504.1  384.69  5511.0  385.90
#Mann=5,-1,0
  3674.8    0.05       0  4996.5    0.03       0  5005.8    0.05       0
  5039.2    0.16       0  5315.2    0.05       0
Bank Sta=4703.5,5071.2
Exp/Cntr=0.3,0.1

Type RM Length L Ch R = 1,12267,949,949,949
BEGIN DESCRIPTION:
Mapping XS c19873fc
END DESCRIPTION:
XS GIS Cut Line= 6
      2925124.73      6938110.43      2924895.57      6937579.19
      2924932.03      6937407.31      2925077.86      6936777.10
      2925129.95      6936448.98      2924979.23      6935778.57
#Sta/Elev= 30
  3671.2  394.29  3787.8  387.15  3894.9  373.19  4015.8  370.18  4033.8  371.65
  4039.3  368.11  4057.3  369.26  4062.8  366.51  4086.3  366.91  4091.8  364.08
  4185.8  356.59  4520.2  348.98  4703.0  338.88  4945.2  337.10  4957.7  336.69
  4982.1  336.80  4990.2  335.83  4990.6  333.90  4991.5  333.10  4999.9  333.90
  5012.9  337.19  5045.1  338.88  5225.7  344.71  5236.9  345.13  5705.9  359.44
  5857.4  368.98  5921.5  376.38  6040.8  397.84  6061.7  399.61  6091.7  401.53
#Mann=9,-1,0
  3671.2    0.05       0  4945.2    0.16       0  4957.7    0.05       0
  4990.6    0.03       0  4999.9    0.05       0  5225.7    0.16       0
  5236.9    0.05       0  5921.5    0.16       0  6061.7    0.05       0
Bank Sta=4703,5045.1
Exp/Cntr=0.3,0.1

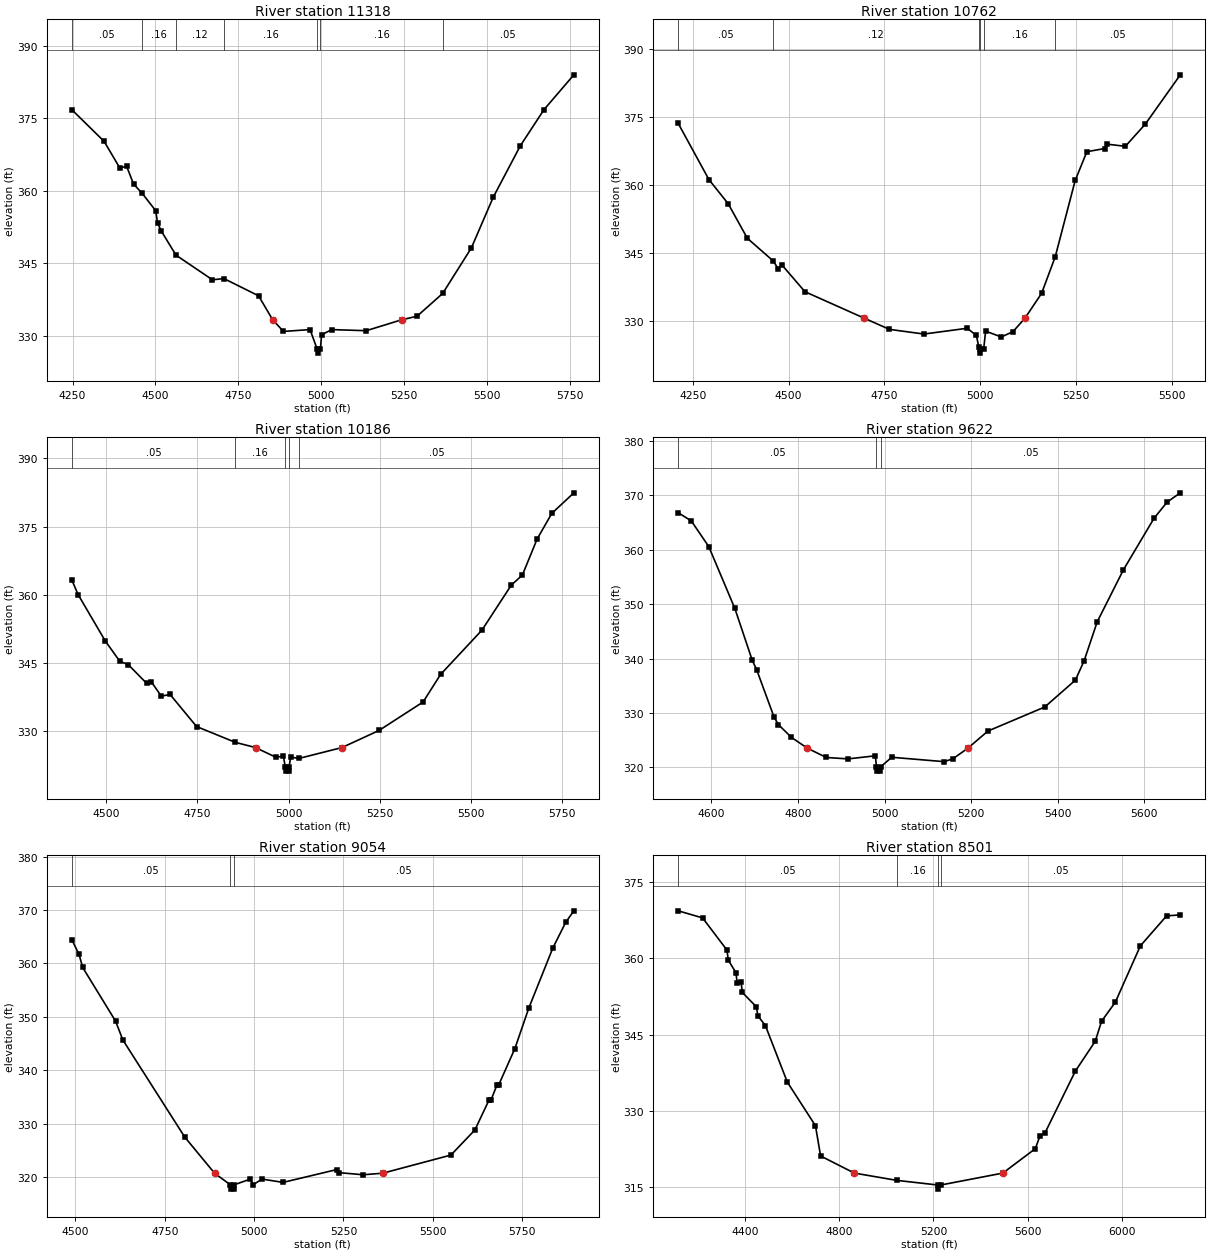
Type RM Length L Ch R = 1,11318,556,556,556
BEGIN DESCRIPTION:
ROCK FALLS CREEK 11.0
END DESCRIPTION:
XS GIS Cut Line= 3
      2926025.01      6937575.04      2925825.00      6936825.00
      2926175.00      6936174.99
#Sta/Elev= 30
  4247.5  376.76  4345.2  370.20  4392.4  364.71  4413.1  365.06  4433.8  361.40
  4459.9  359.48  4500.5  355.91  4506.3  353.39  4516.6  351.80  4561.8  346.72
  4671.9  341.62  4706.3  341.88  4810.9  338.32  4853.6  333.36  4886.0  330.96
  4966.2  331.34  4987.9  327.28  4988.9  326.48  4997.5  327.28  5001.1  330.28
  5031.9  331.34  5135.7  331.11  5242.3  333.36  5289.0  334.10  5366.3  338.80
  5452.9  348.21  5518.6  358.64  5600.6  369.30  5671.9  376.76  5762.0  383.95
#Mann=7,-1,0
  4247.5    0.05       0  4459.9    0.16       0  4561.8    0.12       0
  4706.3    0.16       0  4987.9    0.07       0  4997.5    0.16       0
  5366.3    0.05       0
Bank Sta=4853.6,5242.3
Exp/Cntr=0.3,0.1

Type RM Length L Ch R = 1,10762,576,576,576
BEGIN DESCRIPTION:
ROCK FALLS CREEK 10.0
END DESCRIPTION:
XS GIS Cut Line= 3
      2926375.00      6937475.04      2926325.00      6936725.00
      2926225.00      6936175.02
#Sta/Elev= 30
  4212.0  373.51  4292.2  361.14  4342.3  355.85  4392.4  348.23  4460.6  343.19
  4472.6  341.53  4482.6  342.37  4542.8  336.47  4696.8  330.67  4763.3  328.18
  4853.5  327.15  4966.2  328.42  4990.4  326.85  4996.4  324.36  4999.6  323.75
  5000.5  322.95  5009.2  323.75  5014.5  327.79  5055.2  326.51  5085.7  327.66
  5117.4  330.67  5160.6  336.11  5196.2  344.17  5248.3  360.97  5278.8  367.29
  5325.8  367.99  5330.9  368.96  5379.2  368.47  5431.2  373.35  5522.7  384.21
#Mann=6,-1,0
  4212.0    0.05       0  4460.6    0.12       0  4996.4    0.16       0
  4999.6    0.07       0  5009.2    0.16       0  5196.2    0.05       0
Bank Sta=4696.8,5117.4
Exp/Cntr=0.3,0.1

Type RM Length L Ch R = 1,10186,564,564,564
BEGIN DESCRIPTION:
ROCK FALLS CREEK 9.0
END DESCRIPTION:
XS GIS Cut Line= 3
      2926975.01      6937375.05      2926825.00      6936825.00
      2926925.00      6936024.96
#Sta/Elev= 30
  4405.7  363.29  4423.0  360.06  4497.3  349.88  4537.0  345.42  4561.2  344.59
  4611.3  340.50  4623.4  340.92  4651.1  337.71  4675.2  338.08  4747.8  331.03
  4854.0  327.55  4909.6  326.40  4965.5  324.26  4985.9  324.53  4991.1  322.02
  4992.0  321.22  4999.9  321.22  5000.9  322.02  5006.1  324.31  5028.3  324.01
  5146.3  326.40  5247.9  330.16  5368.9  336.43  5416.7  342.48  5530.1  352.22
  5610.7  362.14  5641.0  364.34  5681.3  372.25  5721.6  377.90  5782.1  382.43
#Mann=5,-1,0
  4405.7    0.05       0  4854.0    0.16       0  4991.1    0.07       0
  5000.9    0.16       0  5028.3    0.05       0
Bank Sta=4909.6,5146.3
Exp/Cntr=0.3,0.1

Type RM Length L Ch R = 1,9622,568,568,568
BEGIN DESCRIPTION:
ROCK FALLS CREEK 8.0
END DESCRIPTION:
XS GIS Cut Line= 3
      2927325.00      6937275.03      2927375.00      6936825.00
      2927475.00      6936125.01
#Sta/Elev= 30
  4523.3  366.82  4553.5  365.31  4593.8  360.60  4654.1  349.21  4694.4  339.65
  4704.4  337.96  4744.7  329.22  4754.7  327.85  4784.9  325.49  4821.8  323.50
  4865.4  321.80  4915.7  321.54  4978.6  322.11  4981.3  320.09  4982.3  319.29
  4990.2  319.29  4991.1  320.09  5016.5  321.84  5137.7  321.03  5157.9  321.56
  5192.3  323.50  5238.7  326.66  5370.1  331.09  5440.8  336.03  5461.0  339.59
  5491.3  346.77  5551.9  356.34  5622.6  365.81  5652.9  368.79  5683.2  370.48
#Mann=3,-1,0
  4523.3    0.05       0  4981.3    0.03       0  4991.1    0.05       0
Bank Sta=4821.8,5192.3
Exp/Cntr=0.3,0.1

Type RM Length L Ch R = 1,9054,553,553,553
BEGIN DESCRIPTION:
ROCK FALLS CREEK 7.0
END DESCRIPTION:
XS GIS Cut Line= 3
      2928025.01      6937425.03      2927925.00      6936925.00
      2927524.98      6936124.96
#Sta/Elev= 30
  4490.0  364.45  4510.4  361.66  4520.6  359.22  4612.4  349.19  4632.8  345.66
  4806.2  327.45  4889.5  320.70  4933.8  318.52  4934.8  317.72  4942.7  317.72
  4943.7  318.52  4989.7  319.60  4997.4  318.55  5022.3  319.60  5081.0  318.98
  5231.9  321.39  5237.5  320.81  5304.6  320.41  5359.8  320.70  5550.6  324.10
  5617.6  328.80  5656.8  334.35  5662.4  334.37  5679.1  337.17  5684.7  337.30
  5729.4  344.03  5768.6  351.66  5835.7  362.88  5872.0  367.72  5894.4  369.83
#Mann=3,-1,0
  4490.0    0.05       0  4933.8    0.03       0  4943.7    0.05       0
Bank Sta=4889.5,5359.8
Exp/Cntr=0.3,0.1

Type RM Length L Ch R = 1,8501,574,574,574
BEGIN DESCRIPTION:
ROCK FALLS CREEK 6.0
END DESCRIPTION:
XS GIS Cut Line= 3
      2927999.98      6937650.03      2928425.00      6936875.00
      2928200.00      6935650.01
#Sta/Elev= 30
  4117.5  369.30  4220.8  367.91  4324.2  361.59  4329.9  359.60  4362.1  357.16
  4367.8  355.08  4383.9  355.25  4389.6  353.27  4449.3  350.42  4455.0  348.70
  4487.2  346.76  4580.1  335.67  4699.5  327.10  4721.3  321.16  4864.4  317.80
  5044.4  316.37  5220.1  315.45  5221.1  314.65  5230.0  315.45  5494.3  317.80
  5631.8  322.59  5652.1  325.15  5672.5  325.64  5801.8  337.83  5886.0  343.68
  5913.1  347.63  5971.3  351.36  6077.5  362.42  6188.7  368.31  6246.9  368.50
#Mann=4,-1,0
  4117.5    0.05       0  5044.4    0.16       0  5220.1    0.03       0
  5230.0    0.05       0
Bank Sta=4864.4,5494.3
Exp/Cntr=0.3,0.1

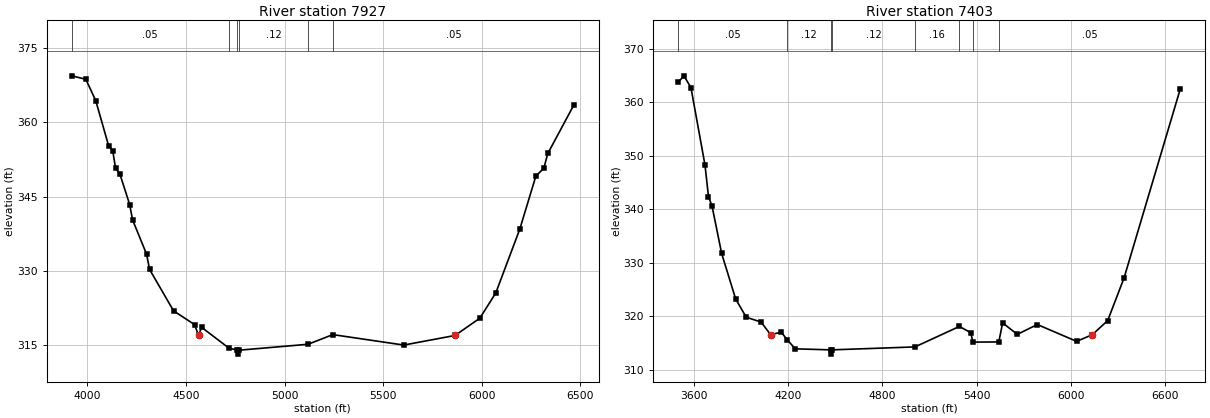
Type RM Length L Ch R = 1,7927,524,524,524
BEGIN DESCRIPTION:
ROCK FALLS CREEK 5.0
END DESCRIPTION:
XS GIS Cut Line= 3
      2927950.00      6937800.00      2928825.00      6937175.00
      2928575.00      6935724.99
#Sta/Elev= 30
  3920.7  369.42  3992.0  368.72  4042.4  364.40  4107.5  355.31  4128.4  354.29
  4143.1  350.71  4164.0  349.68  4214.4  343.43  4229.2  340.32  4300.4  333.38
  4315.2  330.34  4436.8  321.97  4543.8  319.17  4563.6  316.99  4579.4  318.63
  4717.4  314.45  4761.2  314.02  4762.2  313.22  4771.2  314.02  5119.1  315.21
  5244.8  317.16  5604.8  315.05  5864.7  316.99  5990.5  320.47  6071.6  325.58
  6193.4  338.49  6274.6  349.16  6315.2  350.78  6335.5  353.75  6467.4  363.53
#Mann=6,-1,0
  3920.7    0.05       0  4717.4    0.12       0  4761.2    0.07       0
  4771.2    0.12       0  5119.1    0.16       0  5244.8    0.05       0
Bank Sta=4563.6,5864.7
Exp/Cntr=0.3,0.1

Type RM Length L Ch R = 1,7403,556,556,556
BEGIN DESCRIPTION:
ROCK FALLS CREEK 4.0
END DESCRIPTION:
XS GIS Cut Line= 3
      2928025.01      6937975.00      2929325.00      6937325.00
      2928624.98      6935724.96
#Sta/Elev= 30
  3498.2  363.81  3534.5  364.99  3579.2  362.79  3668.7  348.30  3691.0  342.38
  3713.4  340.63  3774.9  331.74  3864.3  323.21  3931.4  319.81  4026.5  318.90
  4086.8  316.54  4155.0  317.01  4193.4  315.55  4244.5  313.89  4468.7  313.70
  4469.7  312.90  4478.7  313.70  5006.8  314.25  5290.0  318.08  5362.1  316.92
  5376.8  315.15  5541.3  315.18  5565.6  318.75  5659.2  316.60  5787.0  318.44
  6037.3  315.29  6137.2  316.54  6235.3  319.18  6339.8  327.18  6698.1  362.56
#Mann=8,-1,0
  3498.2    0.05       0  4193.4    0.12       0  4468.7    0.07       0
  4478.7    0.12       0  5006.8    0.16       0  5290.0    0.05       0
  5376.8    0.16       0  5541.3    0.05       0
Bank Sta=4086.8,6137.2
Exp/Cntr=0.3,0.1