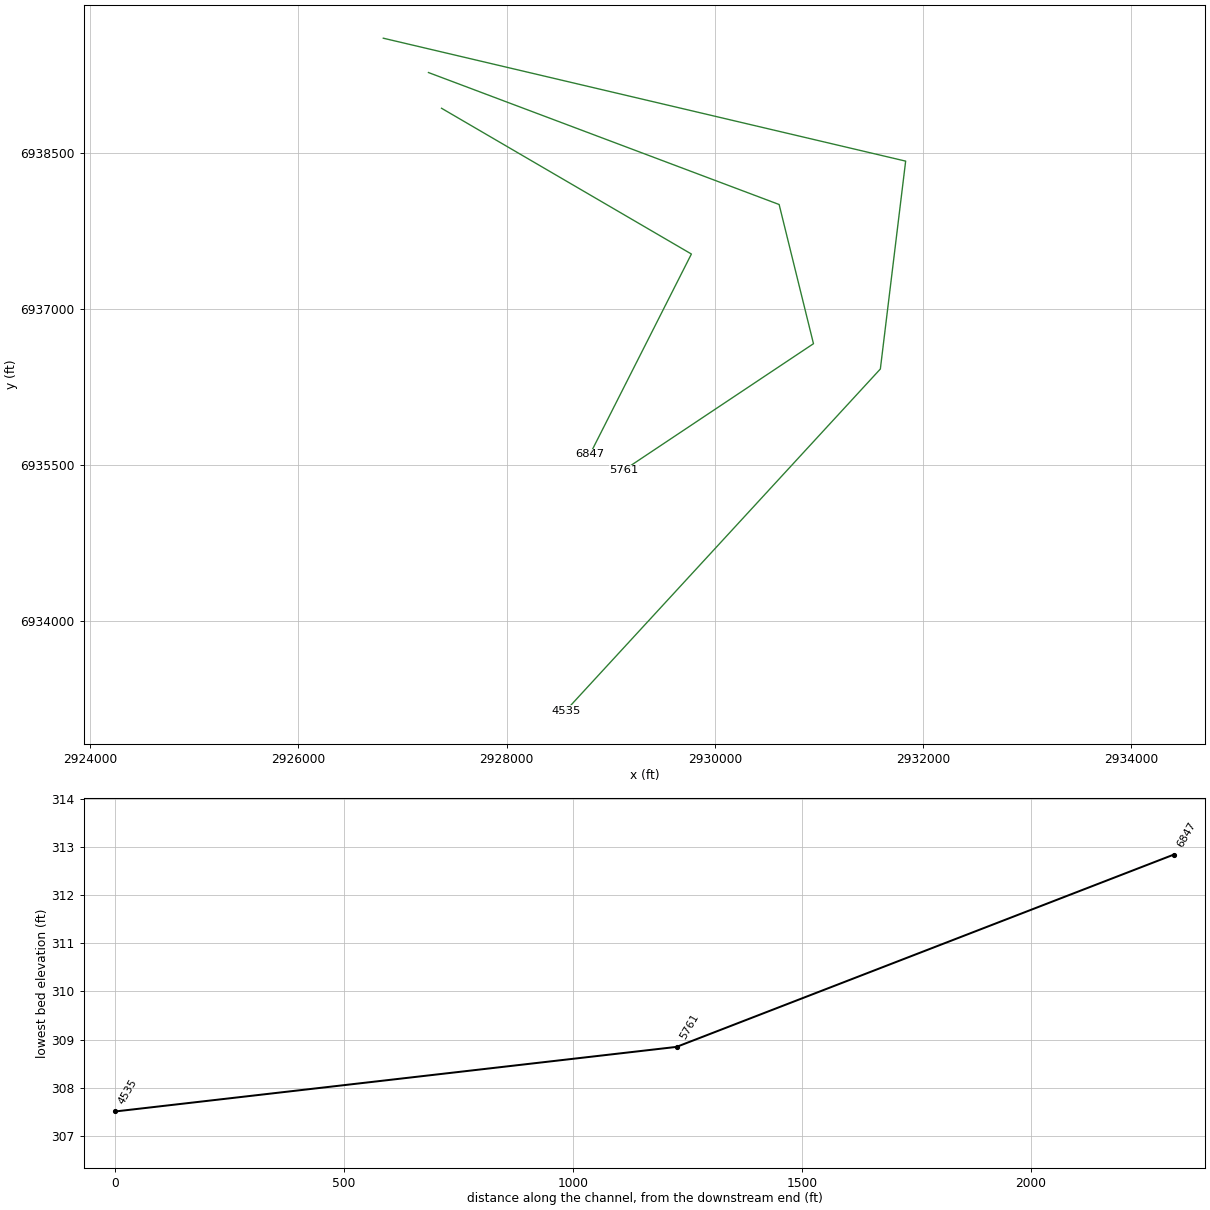
HEC-RAS study ROCK FALLS CREEK.prj: ROCK FALLS CREEK Base Level Engineering

--- ROCK FALLS CREEK.g01 (geometry) --- (continued)

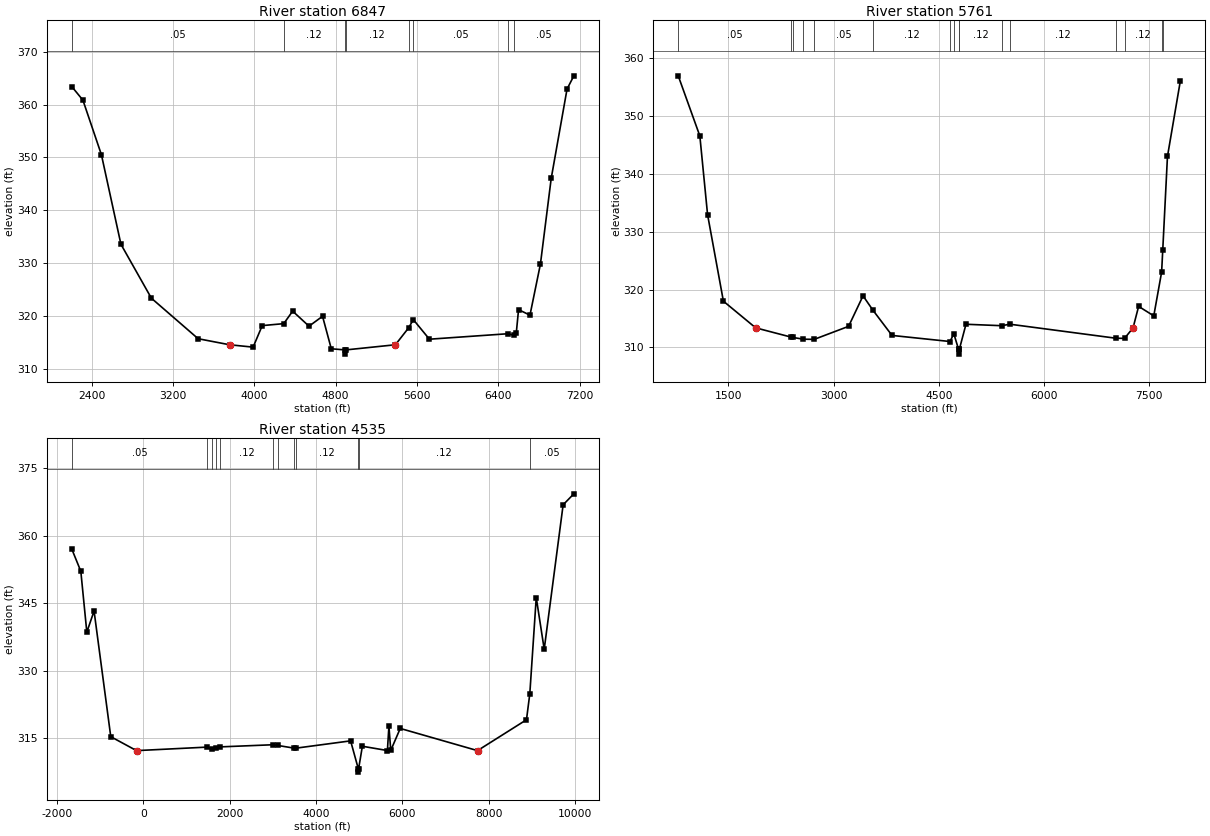
Type RM Length L Ch R = 1,6847,1086,1086,1086
BEGIN DESCRIPTION:
ROCK FALLS CREEK 3.0
END DESCRIPTION:
XS GIS Cut Line= 3
      2927374.99      6938925.00      2929775.00      6937525.00
      2928800.01      6935600.03
#Sta/Elev= 30
  2205.6  363.40  2315.2  360.83  2497.1  350.52  2688.9  333.60  2988.3  323.41
  3448.1  315.75  3757.4  314.61  3988.5  314.16  4078.2  318.23  4289.5  318.60
  4377.5  320.96  4538.0  318.12  4671.1  319.99  4757.1  313.85  4891.0  313.64
  4892.0  312.84  4901.0  313.64  5387.4  314.61  5518.5  317.83  5563.6  319.36
  5721.9  315.66  6498.9  316.70  6552.4  316.37  6575.9  316.83  6598.3  321.25
  6710.4  320.20  6813.4  329.87  6919.2  346.03  7075.1  362.93  7141.9  365.43
#Mann=8,-1,0
  2205.6    0.05       0  4289.5    0.12       0  4891.0    0.07       0
  4901.0    0.12       0  5518.5    0.16       0  5563.6    0.05       0
  6498.9    0.16       0  6552.4    0.05       0
Bank Sta=3757.4,5387.4
Exp/Cntr=0.3,0.1

Type RM Length L Ch R = 1,5761,1226,1226,1226
BEGIN DESCRIPTION:
Mapping XS 2503bb43
END DESCRIPTION:
XS GIS Cut Line= 4
      2927249.70      6939268.00      2930617.79      6938000.63
      2930947.66      6936663.82      2929125.84      6935449.28
#Sta/Elev= 30
   782.9  356.93  1091.3  346.54  1201.5  332.95  1427.3  318.00  1888.0  313.39
  2394.2  311.79  2414.9  311.74  2568.8  311.43  2723.1  311.40  3213.9  313.65
  3420.1  318.92  3561.3  316.44  3833.7  312.08  4660.7  311.03  4716.4  312.36
  4784.0  309.65  4785.0  308.85  4794.0  309.65  4889.3  314.01  5399.8  313.76
  5514.7  314.02  7027.1  311.60  7152.0  311.57  7273.8  313.39  7352.9  317.10
  7569.3  315.46  7681.3  323.03  7697.1  326.76  7764.6  343.00  7948.0  356.02
#Mann=16,-1,0
   782.9    0.05       0  2394.2    0.07       0  2414.9    0.05       0
  2568.8    0.07       0  2723.1    0.05       0  3561.3    0.12       0
  4660.7    0.07       0  4716.4    0.12       0  4784.0    0.07       0
  4794.0    0.12       0  5399.8    0.16       0  5514.7    0.12       0
  7027.1    0.16       0  7152.0    0.12       0  7681.3    0.16       0
  7697.1    0.05       0
Bank Sta=1888,7273.8
Exp/Cntr=0.3,0.1

Type RM Length L Ch R = 1,4535,0,0,0
BEGIN DESCRIPTION:
ROCK FALLS CREEK 2.0
END DESCRIPTION:
XS GIS Cut Line= 4
      2926815.72      6939597.85      2931833.07      6938417.30
      2931590.02      6936420.77      2928569.78      6933140.17
#Sta/Elev= 30
 -1654.1  357.11 -1444.7  352.16 -1305.6  338.62 -1137.8  343.33  -751.3  315.39
  -154.3  312.29  1479.5  313.07  1581.7  312.56  1682.9  312.84  1782.4  313.12
  3013.6  313.60  3115.8  313.44  3494.0  312.84  3530.6  312.83  4802.1  314.46
  4978.4  308.31  4979.4  307.51  4988.5  308.31  5074.1  313.26  5653.9  312.31
  5689.0  317.72  5731.5  312.33  5951.0  317.22  7740.6  312.29  8873.9  319.15
  8951.1  324.93  9100.1  346.32  9284.5  334.82  9722.8  366.94  9970.7  369.37
#Mann=12,-1,0
 -1654.1    0.05       0  1479.5    0.07       0  1581.7    0.12       0
  1682.9    0.07       0  1782.4    0.12       0  3013.6    0.05       0
  3115.8    0.12       0  3494.0    0.07       0  3530.6    0.12       0
  4978.4    0.07       0  4988.5    0.12       0  8951.1    0.05       0
Bank Sta=-154.3,7740.6
Exp/Cntr=0.3,0.1

Chan Stop Cuts=-1