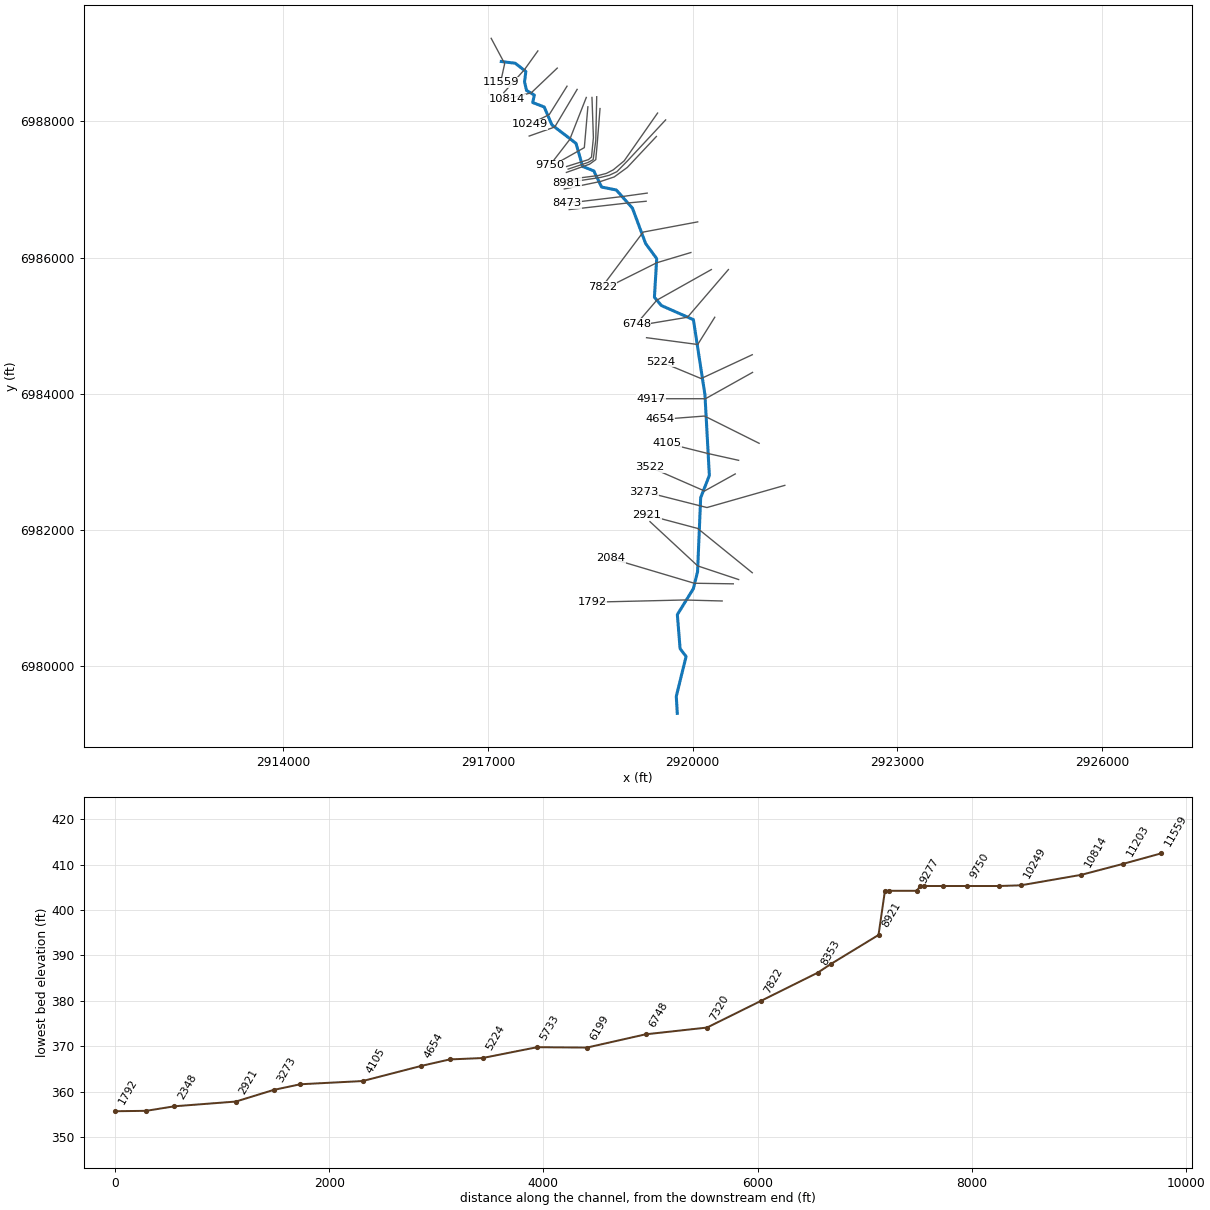
--- SHILOH BRANCH.prj (project) ---

Proj Title=SHILOH BRANCH Base Level Engineering
Current Plan=p01
Default Exp/Contr=0.3,0.1
English Units
Geom File=g01
Flow File=f01
Plan File=p01
BEGIN DESCRIPTION:
SHILOH BRANCH
END DESCRIPTION:

--- SHILOH BRANCH.p01 (plan) ---

Plan Title=Multiple Run
Short Identifier=Multiple
Geom File=g01
Flow File=f01
Subcritical Flow
K Sum by GR= 0
Std Step Tol= 0.01
Critical Tol= 0.01
Num of Std Step Trials= 20
Max Error Tol= 0.3
Flow Tol Ratio= 0.001
Split Flow NTrial= 30
Split Flow Tol= 0.02
Split Flow Ratio= 0.02
Log Output Level= 0
Friction Slope Method= 1
Unsteady Friction Slope Method= 2
Unsteady Bridges Friction Slope Method= 1
Parabolic Critical Depth
Global Vel Dist=  1 , 1 , 1
Global Log Level= 0
CheckData=True
Encroach Param= -1, 0, 0, 0
BEGIN DESCRIPTION:
Multiple Run
END DESCRIPTION:

--- SHILOH BRANCH.f01 (steady flow) ---

Flow Title=Multiple
Number of Profiles=7
Profile Names=10-year,25-year,50-year,1pct_min,100-year,1pct_plu,500-year
River Rch & RM= SHILOH BRANCH,Reach-1,11559
     551     740     894     538    1073    2141    1547
River Rch & RM= SHILOH BRANCH,Reach-1,7822
     669     905    1100     664    1326    2645    1929
River Rch & RM= SHILOH BRANCH,Reach-1,4105
     985    1360    1674    1023    2041    4073    3041
River Rch & RM= SHILOH BRANCH,Reach-1,1247
    1029    1423    1753    1072    2140    4269    3193
Boundary for River Rch & Prof#=SHILOH BRANCH,Reach-1,1
Up Type=0
Dn Type=3
Dn Slope=0.005
Boundary for River Rch & Prof#=SHILOH BRANCH,Reach-1,2
Up Type=0
Dn Type=3
Dn Slope=0.005
Boundary for River Rch & Prof#=SHILOH BRANCH,Reach-1,3
Up Type=0
Dn Type=3
Dn Slope=0.005
Boundary for River Rch & Prof#=SHILOH BRANCH,Reach-1,4
Up Type=0
Dn Type=3
Dn Slope=0.005
Boundary for River Rch & Prof#=SHILOH BRANCH,Reach-1,5
Up Type=0
Dn Type=3
Dn Slope=0.005
Boundary for River Rch & Prof#=SHILOH BRANCH,Reach-1,6
Up Type=0
Dn Type=3
Dn Slope=0.005
Boundary for River Rch & Prof#=SHILOH BRANCH,Reach-1,7
Up Type=0
Dn Type=3
Dn Slope=0.005

--- SHILOH BRANCH.g01 (geometry) ---

Geom Title=Existing Conditions

River Reach=SHILOH BRANCH,Reach-1
Reach XY= 30
      2917195.07      6988878.91      2917400.04      6988853.11
      2917555.51      6988732.24      2917536.06      6988580.15
      2917565.28      6988453.94      2917679.87      6988385.88
      2917655.56      6988276.86      2917825.14      6988210.81
      2917937.09      6987949.18      2918290.97      6987677.18
      2918386.90      6987338.49      2918551.39      6987273.53
      2918665.98      6987036.03      2918882.10      6986992.68
      2919117.87      6986726.94      2919310.89      6986208.12
      2919473.86      6985985.22      2919440.28      6985417.99
      2919543.16      6985296.46      2920011.77      6985089.55
      2920181.18      6983985.57      2920245.67      6982803.92
      2920118.42      6982475.25      2920072.81      6981391.86
      2920011.81      6981142.27      2919776.58      6980760.30
      2919816.65      6980261.15      2919904.58      6980145.78
      2919760.78      6979559.80      2919775.59      6979310.71

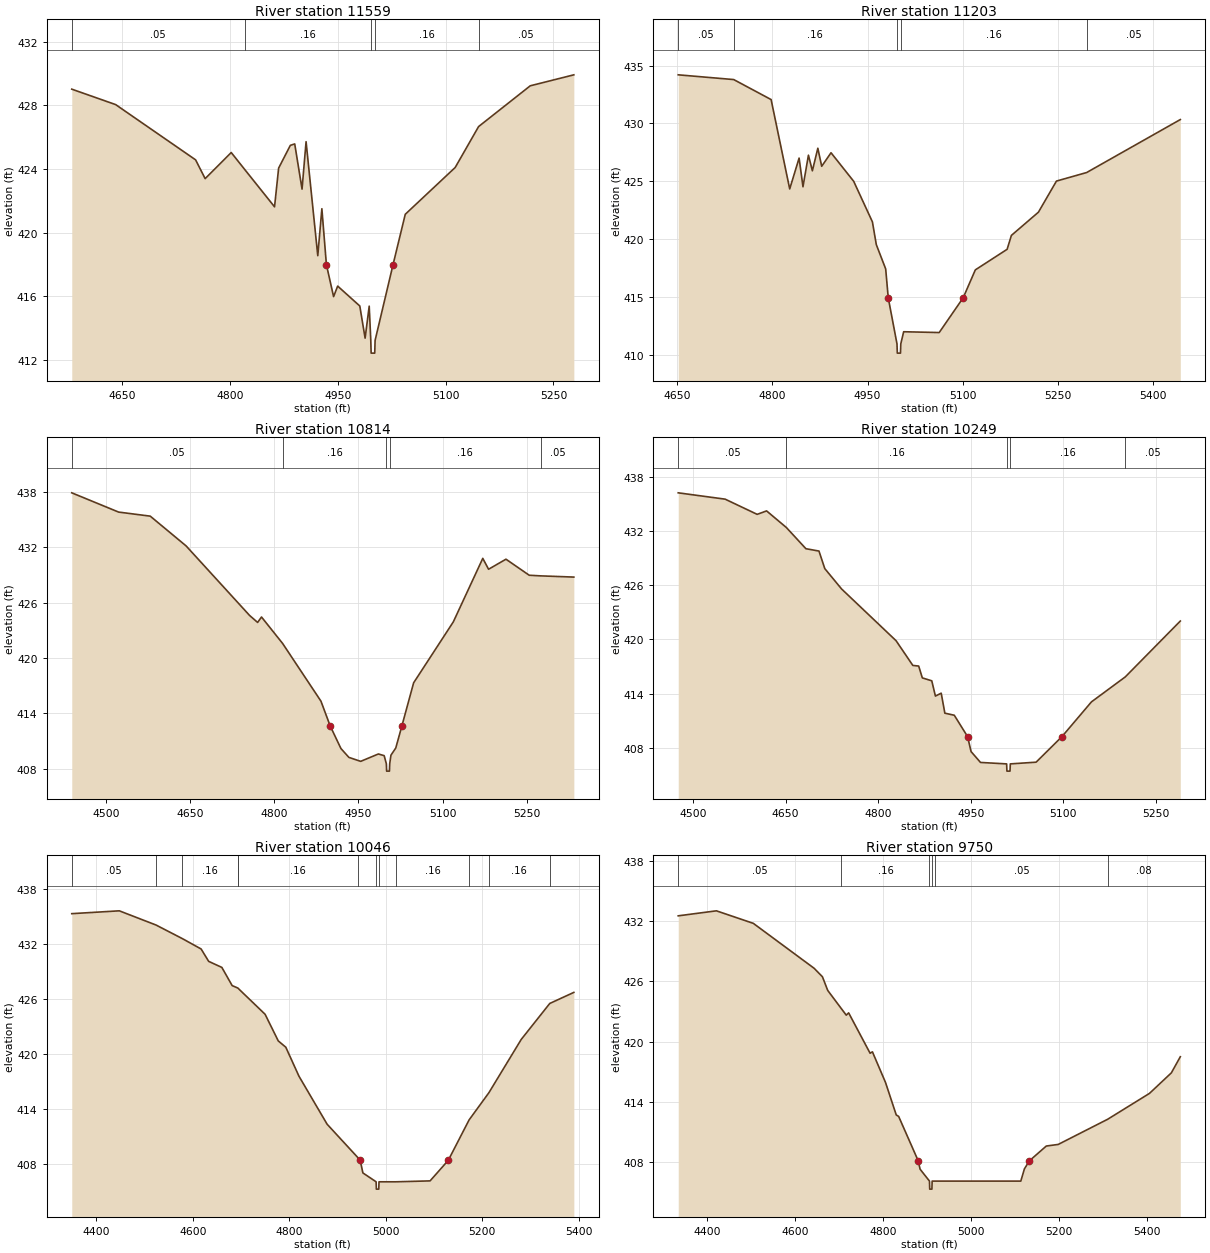
Type RM Length L Ch R = 1,11559,356,356,356
BEGIN DESCRIPTION:
SHILOH BRANCH 18.0
END DESCRIPTION:
XS GIS Cut Line= 3
      2917047.23      6989218.96      2917244.88      6988847.69
      2917185.25      6988575.75
#Sta/Elev= 30
  4579.4  429.02  4640.5  428.05  4751.8  424.58  4765.1  423.40  4801.4  425.04
  4819.9  423.99  4861.7  421.63  4867.4  424.06  4883.7  425.49  4889.8  425.58
  4900.0  422.74  4905.6  425.72  4921.9  418.56  4927.6  421.51  4933.9  418.00
  4943.9  415.99  4949.6  416.65  4980.4  415.40  4987.8  413.38  4993.5  415.39
  4995.7  413.24  4996.2  412.44  5001.2  412.44  5001.7  413.24  5026.7  418.00
  5043.7  421.16  5113.2  424.10  5145.8  426.67  5217.7  429.23  5278.4  429.92
#Mann=5,-1,0
  4579.4    0.05       0  4819.9    0.16       0  4995.7    0.07       0
  5001.7    0.16       0  5145.8    0.05       0
Bank Sta=4933.9,5026.7
Exp/Cntr=0.3,0.1

Type RM Length L Ch R = 1,11203,389,389,389
BEGIN DESCRIPTION:
Mapping XS 64bd9a23
END DESCRIPTION:
XS GIS Cut Line= 3
      2917731.24      6989034.06      2917535.94      6988760.64
      2917232.12      6988422.09
#Sta/Elev= 30
  4651.8  434.20  4739.2  433.79  4798.1  432.06  4827.4  424.33  4842.2  427.00
  4848.3  424.52  4856.9  427.25  4863.1  425.90  4871.7  427.85  4877.8  426.29
  4892.5  427.46  4928.2  424.99  4957.7  421.48  4963.8  419.52  4978.6  417.41
  4982.6  414.92  4996.4  410.93  4996.9  410.13  5001.9  410.13  5002.4  410.93
  5006.9  411.98  5062.9  411.91  5100.7  414.92  5119.8  417.33  5169.9  419.11
  5176.6  420.31  5219.2  422.32  5247.6  425.01  5295.2  425.75  5442.7  430.33
#Mann=5,-1,0
  4651.8    0.05       0  4739.2    0.16       0  4996.4    0.07       0
  5002.4    0.16       0  5295.2    0.05       0
Bank Sta=4982.6,5100.7
Exp/Cntr=0.3,0.1

Type RM Length L Ch R = 1,10814,565,565,565
BEGIN DESCRIPTION:
Mapping XS 3c27e363
END DESCRIPTION:
XS GIS Cut Line= 3
      2918015.74      6988782.11      2917635.55      6988420.14
      2917278.06      6988326.88
#Sta/Elev= 30
  4439.4  437.92  4522.9  435.83  4579.2  435.39  4643.1  432.16  4756.3  424.61
  4770.5  423.86  4777.4  424.45  4814.9  421.59  4883.3  415.32  4899.7  412.64
  4918.9  410.18  4933.1  409.22  4954.1  408.79  4985.6  409.59  4995.9  409.41
  4999.8  408.53  5000.3  407.73  5005.3  407.73  5005.8  408.53  5008.0  409.46
  5016.6  410.24  5027.5  412.64  5048.4  417.31  5119.1  423.92  5171.6  430.81
  5181.9  429.63  5212.9  430.72  5254.3  428.98  5274.9  428.91  5333.8  428.78
#Mann=5,-1,0
  4439.4    0.05       0  4814.9    0.16       0  4999.8    0.07       0
  5005.8    0.16       0  5274.9    0.05       0
Bank Sta=4899.7,5027.5
Exp/Cntr=0.3,0.1

Type RM Length L Ch R = 1,10249,203,203,203
BEGIN DESCRIPTION:
Mapping XS 50a7d40b
END DESCRIPTION:
XS GIS Cut Line= 3
      2918158.99      6988516.49      2917898.57      6988099.83
      2917609.73      6987956.71
#Sta/Elev= 30
  4476.0  436.20  4552.0  435.50  4603.9  433.82  4619.2  434.20  4651.3  432.36
  4682.9  430.02  4704.1  429.76  4713.5  427.82  4740.7  425.57  4829.1  419.84
  4856.2  417.11  4865.7  417.04  4871.6  415.73  4886.9  415.41  4892.8  413.72
  4902.2  414.04  4908.1  411.83  4923.4  411.60  4945.0  409.23  4950.6  407.58
  4965.9  406.38  5008.2  406.22  5008.7  405.42  5013.7  405.42  5014.2  406.22
  5056.0  406.41  5097.8  409.23  5145.7  413.08  5200.5  415.84  5289.7  422.02
#Mann=5,-1,0
  4476.0    0.05       0  4651.3    0.16       0  5008.2    0.07       0
  5014.2    0.16       0  5200.5    0.05       0
Bank Sta=4945,5097.8
Exp/Cntr=0.3,0.1

Type RM Length L Ch R = 1,10046,296,296,296
BEGIN DESCRIPTION:
Mapping XS a86945fd
END DESCRIPTION:
XS GIS Cut Line= 3
      2918307.42      6988469.62      2917979.30      6987917.54
      2917604.26      6987784.71
#Sta/Elev= 30
  4349.5  435.36  4448.0  435.67  4524.0  434.12  4578.4  432.64  4617.5  431.50
  4633.1  430.15  4660.4  429.49  4681.8  427.50  4693.8  427.23  4694.2  427.20
  4750.0  424.37  4777.3  421.46  4792.9  420.77  4820.2  417.60  4878.5  412.36
  4942.6  408.69  4947.0  408.42  4952.6  407.04  4980.0  406.07  4980.5  405.27
  4985.5  405.27  4986.0  406.07  5020.8  406.07  5091.8  406.17  5129.5  408.42
  5172.6  412.83  5213.6  415.80  5280.7  421.63  5339.7  425.55  5389.6  426.76
#Mann=12,-1,0
  4349.5    0.05       0  4524.0    0.08       0  4578.4    0.16       0
  4693.8    0.05       0  4694.2    0.16       0  4942.6    0.05       0
  4980.0   0.035       0  4986.0    0.05       0  5020.8    0.16       0
  5172.6    0.05       0  5213.6    0.16       0  5339.7    0.05       0
Bank Sta=4947,5129.5
Exp/Cntr=0.3,0.1

Type RM Length L Ch R = 1,9750,225,225,225
BEGIN DESCRIPTION:
Mapping XS 8185b9d3
END DESCRIPTION:
XS GIS Cut Line= 3
      2918441.53      6988351.44      2918198.46      6987733.35
      2917906.79      6987354.87
#Sta/Elev= 30
  4334.3  432.54  4421.1  433.04  4505.1  431.79  4643.3  427.31  4662.3  426.46
  4674.3  425.10  4705.5  423.27  4716.5  422.63  4721.9  422.86  4770.7  418.83
  4776.0  418.97  4805.8  415.91  4830.2  412.67  4835.6  412.53  4880.2  408.09
  4884.4  407.26  4905.8  406.07  4906.3  405.27  4911.3  405.27  4911.8  406.07
  4918.4  406.07  5113.5  406.07  5121.7  407.29  5132.9  408.09  5171.5  409.57
  5198.6  409.73  5311.0  412.24  5406.1  414.82  5455.9  416.87  5476.3  418.48
#Mann=6,-1,0
  4334.3    0.05       0  4705.5    0.16       0  4905.8   0.033       0
  4911.8    0.16       0  4918.4    0.05       0  5311.0    0.08       0
Bank Sta=4880.2,5132.9
Exp/Cntr=0.3,0.1

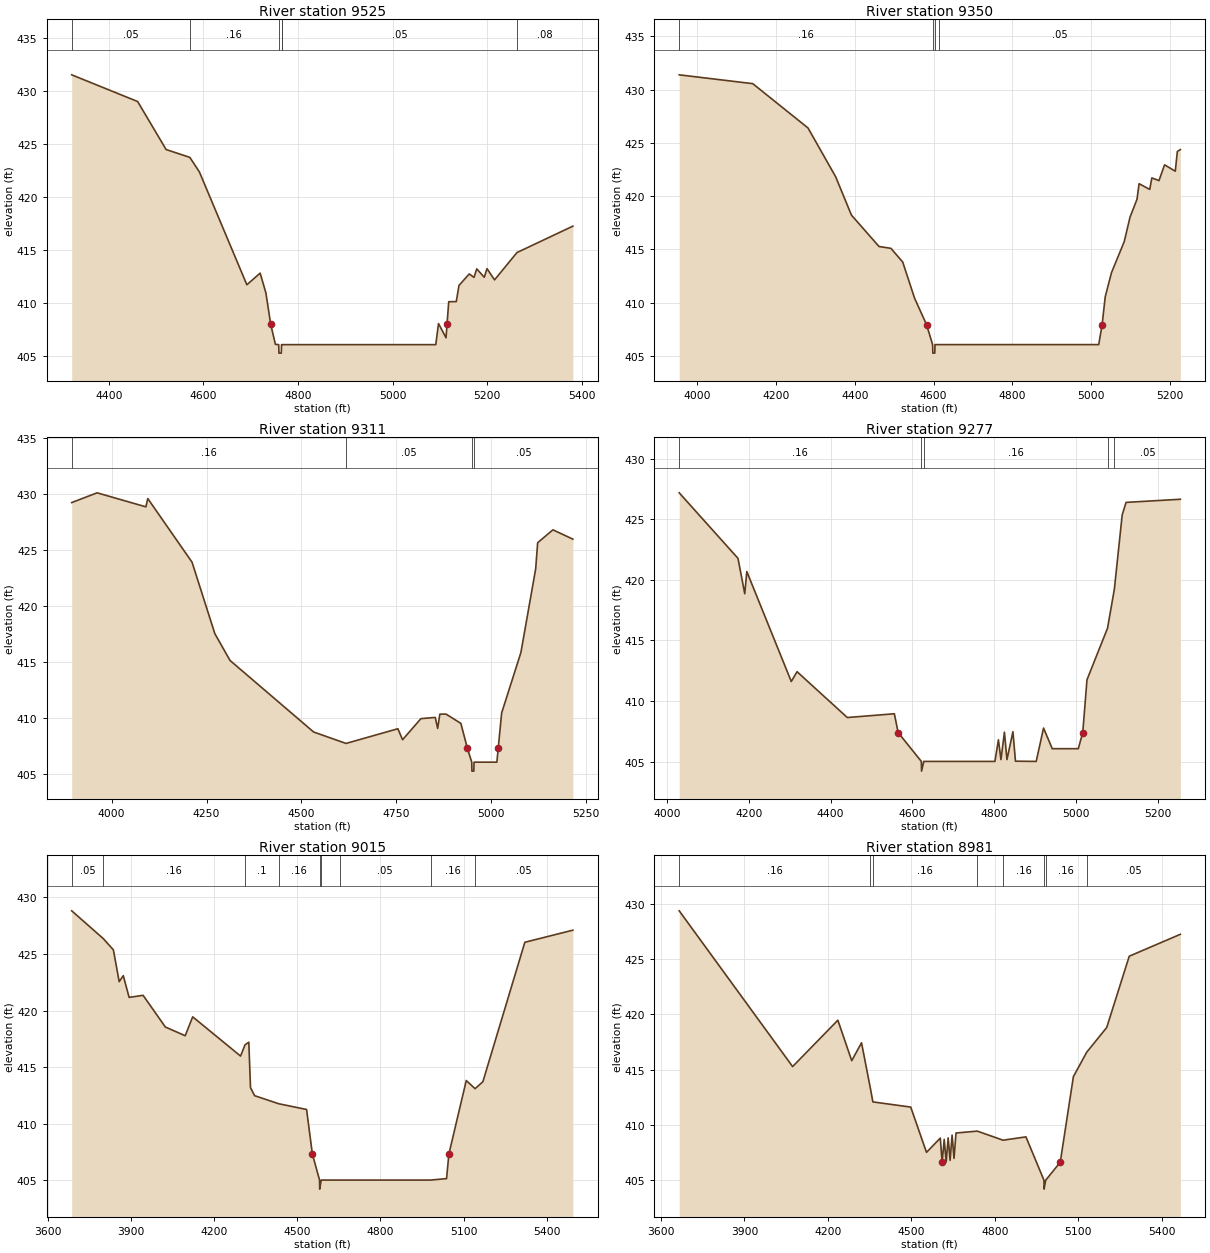
Type RM Length L Ch R = 1,9525,175,175,175
BEGIN DESCRIPTION:
Mapping XS dcf565cb
END DESCRIPTION:
XS GIS Cut Line= 3
      2918464.76      6988213.75      2918412.68      6987614.80
      2918014.14      6987389.54
#Sta/Elev= 30
  4321.8  431.53  4461.1  429.01  4521.3  424.48  4571.4  423.74  4591.6  422.37
  4691.9  411.72  4720.0  412.82  4732.1  410.96  4742.3  407.99  4752.2  406.10
  4759.2  406.07  4759.7  405.27  4764.7  405.27  4765.2  406.07  4766.8  406.07
  5091.1  406.07  5096.9  408.06  5112.8  406.72  5114.9  407.99  5118.5  410.12
  5134.4  410.13  5140.2  411.66  5161.8  412.74  5172.0  412.42  5177.7  413.22
  5193.6  412.43  5199.4  413.24  5215.3  412.18  5262.7  414.76  5380.8  417.25
#Mann=6,-1,0
  4321.8    0.05       0  4571.4    0.16       0  4759.2   0.033       0
  4765.2    0.16       0  4766.8    0.05       0  5262.7    0.08       0
Bank Sta=4742.3,5114.9
Exp/Cntr=0.3,0.1

Type RM Length L Ch R = 1,9350,39,39,39
BEGIN DESCRIPTION:
Mapping XS 6224c503
END DESCRIPTION:
XS GIS Cut Line= 5
      2918524.85      6988351.42      2918545.68      6987761.13
      2918517.91      6987476.41      2918472.77      6987438.21
      2918153.32      6987337.52
#Sta/Elev= 30
  3955.0  431.40  4141.5  430.57  4281.6  426.41  4351.7  421.83  4391.7  418.23
  4461.7  415.28  4491.8  415.11  4521.8  413.82  4551.8  410.43  4582.2  407.94
  4597.6  406.07  4598.1  405.27  4603.1  405.27  4603.6  406.07  4614.4  406.07
  5018.8  406.07  5027.4  407.94  5035.3  410.56  5051.1  412.82  5083.5  415.74
  5098.2  418.04  5115.9  419.72  5121.1  421.18  5148.2  420.64  5153.5  421.72
  5171.6  421.47  5185.8  422.95  5212.9  422.35  5218.2  424.21  5225.8  424.38
#Mann=4,-1,0
  3955.0    0.16       0  4597.6    0.04       0  4603.6    0.16       0
  4614.4    0.05       0
Bank Sta=4582.2,5027.4
Exp/Cntr=0.3,0.1

Type RM Length L Ch R = 1,9311,34,34,34
BEGIN DESCRIPTION:
Mapping XS 91a5f165
END DESCRIPTION:
XS GIS Cut Line= 5
      2918594.30      6988361.81      2918580.41      6987719.46
      2918542.21      6987438.21      2918465.82      6987396.55
      2918175.18      6987299.67
#Sta/Elev= 30
  3895.0  429.22  3961.8  430.09  4090.3  428.84  4095.3  429.58  4211.9  423.90
  4271.9  417.53  4311.9  415.14  4532.0  408.76  4617.3  407.74  4753.9  409.05
  4766.3  408.07  4814.5  409.95  4852.3  410.06  4858.7  409.08  4864.4  410.35
  4880.5  410.36  4919.7  409.53  4937.1  407.29  4948.4  406.07  4948.9  405.27
  4953.9  405.27  4954.4  406.07  5014.6  406.07  5018.1  407.29  5027.2  410.46
  5077.9  415.85  5116.8  423.31  5122.0  425.64  5162.2  426.79  5214.7  425.96
#Mann=4,-1,0
  3895.0    0.16       0  4617.3    0.05       0  4948.4    0.04       0
  4954.4    0.05       0
Bank Sta=4937.1,5018.1
Exp/Cntr=0.3,0.1

Type RM Length L Ch R = 1,9277,262,262,262
BEGIN DESCRIPTION:
Mapping XS ff89c26b
END DESCRIPTION:
XS GIS Cut Line= 5
      2918642.91      6988188.22      2918601.24      6987667.38
      2918580.41      6987438.21      2918490.13      6987372.24
      2918149.91      6987250.73
#Sta/Elev= 30
  4029.7  427.17  4173.4  421.77  4190.0  418.85  4195.0  420.68  4303.8  411.61
  4317.9  412.42  4440.8  408.64  4555.9  408.95  4565.2  407.40  4621.9  405.02
  4622.4  404.22  4627.9  405.02  4801.9  405.02  4810.4  406.80  4816.6  405.17
  4825.1  407.43  4831.3  405.17  4845.9  407.47  4852.1  405.04  4902.8  405.02
  4920.8  407.77  4942.1  406.07  5005.8  406.07  5016.7  407.40  5027.0  411.75
  5077.3  416.01  5094.0  419.23  5113.1  425.34  5122.6  426.38  5255.4  426.64
#Mann=5,-1,0
  4029.7    0.16       0  4621.9    0.04       0  4627.9    0.16       0
  5077.3    0.08       0  5094.0    0.05       0
Bank Sta=4565.2,5016.7
Exp/Cntr=0.3,0.1

Type RM Length L Ch R = 1,9015,34,34,34
BEGIN DESCRIPTION:
Mapping XS 157e2ae6
END DESCRIPTION:
XS GIS Cut Line= 6
      2919486.67      6988122.26      2918997.07      6987420.85
      2918837.35      6987288.91      2918736.66      6987236.82
      2918618.60      6987205.57      2918113.20      6987139.80
#Sta/Elev= 30
  3686.7  428.82  3799.9  426.38  3837.0  425.37  3857.9  422.56  3872.7  423.09
  3893.7  421.17  3944.2  421.35  4024.5  418.55  4096.0  417.78  4123.1  419.45
  4295.8  415.98  4311.7  416.97  4325.5  417.21  4331.6  413.19  4346.4  412.48
  4433.0  411.77  4533.9  411.26  4554.8  407.32  4580.7  405.02  4581.2  404.22
  4586.7  405.02  4654.7  405.02  4981.0  405.02  5038.8  405.15  5047.2  407.32
  5109.9  413.82  5141.7  413.10  5169.9  413.72  5321.2  426.04  5494.4  427.11
#Mann=9,-1,0
  3686.7    0.05       0  3799.9    0.16       0  4311.7     0.1       0
  4433.0    0.16       0  4580.7    0.07       0  4586.7    0.16       0
  4654.7    0.05       0  4981.0    0.16       0  5141.7    0.05       0
Bank Sta=4554.8,5047.2
Exp/Cntr=0.3,0.1

Type RM Length L Ch R = 1,8981,60,60,60
BEGIN DESCRIPTION:
Mapping XS 8622e8fc
END DESCRIPTION:
XS GIS Cut Line= 6
      2919604.69      6988021.52      2919045.68      6987420.85
      2918889.43      6987261.13      2918778.32      6987209.05
      2918653.32      6987177.80      2918153.37      6987101.41
#Sta/Elev= 30
  3665.7  429.36  4073.3  415.29  4235.9  419.48  4285.8  415.82  4321.0  417.44
  4352.8  413.33  4361.8  412.10  4497.9  411.63  4554.5  407.54  4604.1  408.83
  4610.7  406.65  4618.2  408.71  4625.2  406.67  4632.4  408.85  4639.3  406.82
  4646.5  409.10  4653.5  407.00  4660.6  409.29  4737.2  409.46  4829.6  408.64
  4912.0  408.94  4976.8  405.02  4977.3  404.22  4982.8  405.02  5035.3  406.65
  5082.5  414.38  5130.2  416.58  5202.3  418.82  5283.3  425.26  5467.0  427.24
#Mann=8,-1,0
  3665.7    0.16       0  4352.8     0.1       0  4361.8    0.16       0
  4737.2    0.05       0  4829.6    0.16       0  4976.8    0.07       0
  4982.8    0.16       0  5130.2    0.05       0
Bank Sta=4610.7,5035.3
Exp/Cntr=0.3,0.1

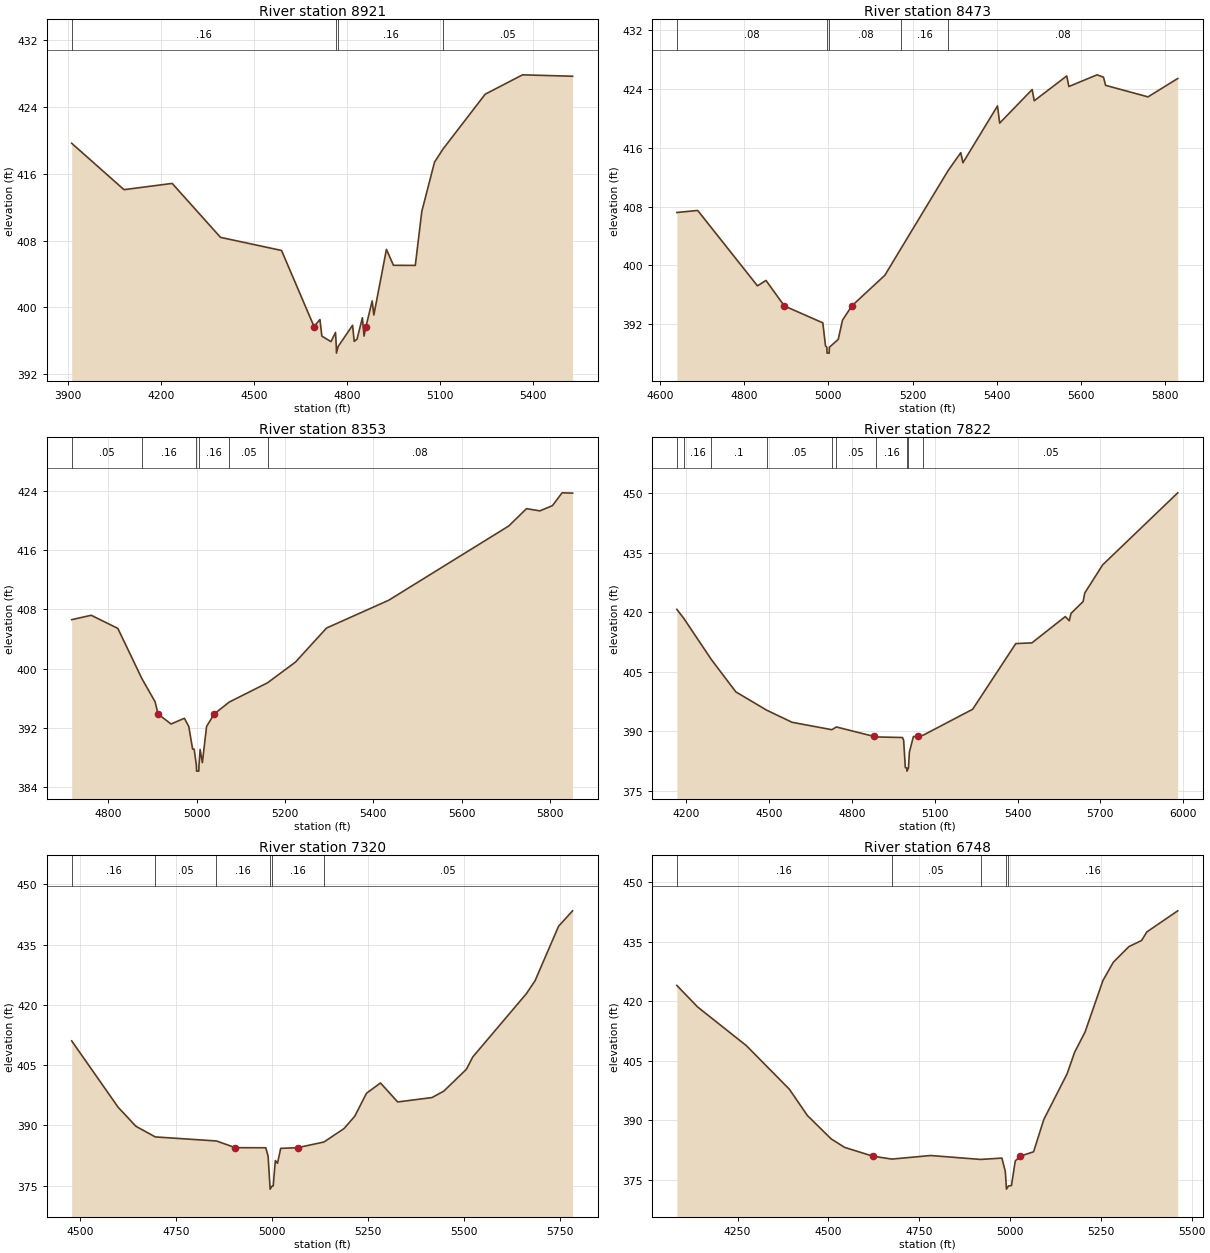
Type RM Length L Ch R = 1,8921,448,448,448
BEGIN DESCRIPTION:
Mapping XS 7e197721
END DESCRIPTION:
XS GIS Cut Line= 5
      2919469.33      6987778.52      2919042.21      6987323.63
      2918851.24      6987184.74      2918653.32      6987118.77
      2918119.28      6987007.80
#Sta/Elev= 30
  3913.3  419.66  4081.8  414.10  4237.1  414.85  4392.9  408.38  4589.5  406.81
  4694.3  397.69  4713.3  398.53  4719.5  396.54  4748.9  395.88  4763.5  396.98
  4766.0  395.30  4766.5  394.50  4772.0  395.30  4818.5  397.84  4823.7  395.91
  4832.7  396.16  4850.1  398.74  4855.4  396.54  4861.6  397.69  4881.7  400.76
  4887.0  399.07  4927.6  406.94  4950.2  405.03  5020.6  405.02  5041.6  411.50
  5082.5  417.39  5109.5  418.95  5245.9  425.55  5366.3  427.87  5527.5  427.70
#Mann=4,-1,0
  3913.3    0.16       0  4766.0    0.07       0  4772.0    0.16       0
  5109.5    0.05       0
Bank Sta=4694.3,4861.6
Exp/Cntr=0.3,0.1

Type RM Length L Ch R = 1,8473,120,120,120
BEGIN DESCRIPTION:
Mapping XS 2bcd5e94
END DESCRIPTION:
XS GIS Cut Line= 3
      2919334.55      6986947.41      2918977.80      6986897.93
      2918154.90      6986798.98
#Sta/Elev= 30
  4640.5  407.20  4690.0  407.48  4831.9  397.22  4852.1  397.96  4895.7  394.49
  4987.0  392.19  4993.4  389.06  4996.6  388.87  4997.1  388.07  5002.1  388.07
  5002.6  388.87  5023.6  389.94  5033.7  392.55  5055.8  394.49  5134.4  398.67
  5173.4  402.38  5284.4  412.90  5314.5  415.34  5319.6  413.97  5401.7  421.70
  5406.8  419.36  5483.9  423.93  5488.9  422.40  5566.1  425.78  5571.1  424.34
  5638.0  425.93  5653.3  425.61  5658.3  424.50  5758.9  422.93  5829.5  425.43
#Mann=5,-1,0
  4640.5    0.08       0  4996.6    0.07       0  5002.6    0.08       0
  5173.4    0.16       0  5284.4    0.08       0
Bank Sta=4895.7,5055.8
Exp/Cntr=0.3,0.1

Type RM Length L Ch R = 1,8353,531,531,531
BEGIN DESCRIPTION:
Mapping XS 70882cd1
END DESCRIPTION:
XS GIS Cut Line= 3
      2919318.99      6986827.63      2919042.91      6986801.58
      2918191.35      6986705.23
#Sta/Elev= 30
  4717.0  406.61  4761.2  407.20  4821.5  405.43  4876.1  398.65  4905.8  395.55
  4912.5  393.90  4942.0  392.55  4972.1  393.32  4982.2  392.21  4990.8  389.17
  4994.3  389.17  4999.3  387.00  4999.8  386.20  5004.8  386.20  5005.3  387.00
  5007.8  389.12  5012.9  387.34  5022.4  392.22  5039.7  393.90  5073.6  395.50
  5160.4  398.10  5223.7  400.89  5294.1  405.48  5435.0  409.23  5706.7  419.23
  5747.0  421.57  5777.2  421.27  5805.6  421.97  5827.5  423.70  5851.3  423.66
#Mann=6,-1,0
  4717.0    0.05       0  4876.1    0.16       0  4999.3    0.07       0
  5005.3    0.16       0  5073.6    0.05       0  5160.4    0.08       0
Bank Sta=4912.5,5039.7
Exp/Cntr=0.3,0.1

Type RM Length L Ch R = 1,7822,502,502,502
BEGIN DESCRIPTION:
SHILOH BRANCH 14.0
END DESCRIPTION:
XS GIS Cut Line= 3
      2920075.02      6986525.00      2919275.00      6986375.00
      2918674.98      6985574.97
#Sta/Elev= 30
  4166.1  420.75  4190.6  418.56  4290.9  408.13  4379.8  399.96  4491.5  395.35
  4583.3  392.30  4727.4  390.43  4743.9  391.12  4880.4  388.73  4887.8  388.61
  4983.2  388.46  4987.4  387.81  4993.6  380.87  4998.9  380.79  4999.4  379.99
  5004.9  380.79  5008.2  384.76  5022.8  388.71  5040.6  388.73  5058.9  389.07
  5237.4  395.58  5393.6  412.14  5451.9  412.31  5572.8  418.94  5587.4  417.89
  5593.6  419.74  5637.4  422.73  5643.6  424.91  5708.2  431.97  5980.1  450.13
#Mann=10,-1,0
  4166.1    0.05       0  4190.6    0.16       0  4290.9     0.1       0
  4491.5    0.05       0  4727.4    0.16       0  4743.9    0.05       0
  4887.8    0.16       0  4998.9    0.07       0  5004.9    0.16       0
  5058.9    0.05       0
Bank Sta=4880.4,5040.6
Exp/Cntr=0.3,0.1

Type RM Length L Ch R = 1,7320,572,572,572
BEGIN DESCRIPTION:
SHILOH BRANCH 13.0
END DESCRIPTION:
XS GIS Cut Line= 3
      2919975.04      6986075.01      2919475.00      6985925.00
      2918774.98      6985574.99
#Sta/Elev= 30
  4478.9  411.02  4599.9  394.51  4646.0  389.79  4696.5  387.13  4856.0  386.12
  4905.3  384.45  4984.4  384.43  4990.5  382.34  4995.3  374.94  4995.8  374.14
  5001.3  374.94  5003.8  374.94  5009.3  381.25  5014.9  380.57  5023.3  384.28
  5067.1  384.45  5135.9  385.86  5188.2  389.20  5216.2  392.28  5246.9  398.01
  5283.3  400.55  5328.0  395.83  5417.4  396.92  5448.2  398.53  5506.9  403.95
  5523.6  407.02  5663.4  422.79  5685.8  425.98  5747.2  439.56  5783.6  443.38
#Mann=6,-1,0
  4478.9    0.16       0  4696.5    0.05       0  4856.0    0.16       0
  4995.3    0.07       0  5001.3    0.16       0  5135.9    0.05       0
Bank Sta=4905.3,5067.1
Exp/Cntr=0.3,0.1

Type RM Length L Ch R = 1,6748,549,549,549
BEGIN DESCRIPTION:
SHILOH BRANCH 12.0
END DESCRIPTION:
XS GIS Cut Line= 3
      2920275.00      6985825.00      2919475.00      6985375.00
      2919174.97      6985024.97
#Sta/Elev= 30
  4082.8  423.98  4140.2  418.54  4274.3  408.80  4392.6  397.83  4442.0  391.23
  4507.3  385.34  4544.6  383.18  4622.5  380.96  4674.6  380.23  4781.7  381.13
  4919.0  380.14  4977.7  380.48  4987.0  377.14  4989.7  373.46  4990.2  372.66
  4995.8  373.46  5004.0  373.56  5014.4  379.75  5027.8  380.96  5064.9  382.07
  5092.9  390.18  5157.1  401.71  5177.9  407.16  5206.5  412.23  5255.9  425.24
  5284.4  429.83  5327.2  433.76  5362.3  435.31  5376.6  437.46  5461.7  442.78
#Mann=5,-1,0
  4082.8    0.16       0  4674.6    0.05       0  4919.0    0.16       0
  4989.7    0.07       0  4995.8    0.16       0
Bank Sta=4622.5,5027.8
Exp/Cntr=0.3,0.1

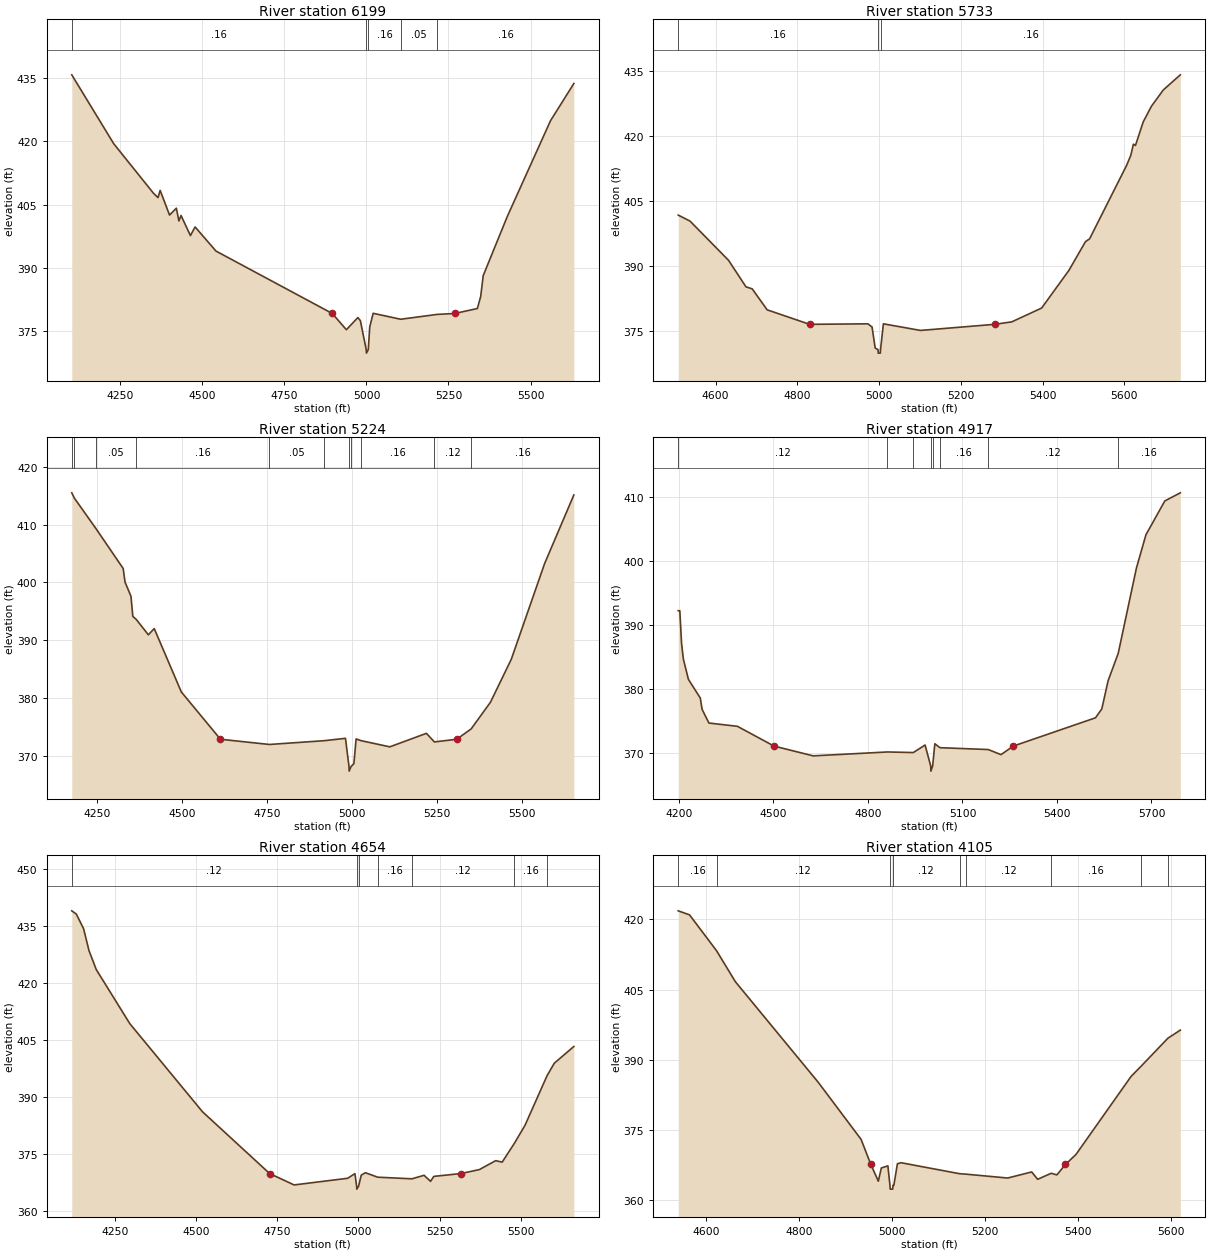
Type RM Length L Ch R = 1,6199,466,466,466
BEGIN DESCRIPTION:
SHILOH BRANCH 11.0
END DESCRIPTION:
XS GIS Cut Line= 3
      2920524.99      6985824.98      2919925.00      6985125.00
      2919325.01      6985025.00
#Sta/Elev= 30
  4101.9  435.79  4229.7  419.45  4350.5  407.73  4364.7  406.65  4371.3  408.36
  4399.9  402.51  4420.7  404.14  4428.4  401.11  4435.0  402.40  4463.5  397.64
  4477.8  399.68  4541.5  393.96  4895.8  379.15  4938.8  375.30  4973.9  378.18
  4981.6  377.43  4999.4  370.54  4999.9  369.74  5005.5  370.54  5010.1  375.98
  5020.5  379.19  5104.4  377.78  5215.6  378.93  5269.5  379.15  5338.1  380.33
  5348.2  383.18  5355.9  388.14  5429.4  402.19  5561.1  424.91  5632.1  433.73
#Mann=5,-1,0
  4101.9    0.16       0  4999.4    0.07       0  5005.5    0.16       0
  5104.4    0.05       0  5215.6    0.16       0
Bank Sta=4895.8,5269.5
Exp/Cntr=0.3,0.1

Type RM Length L Ch R = 1,5733,509,509,509
BEGIN DESCRIPTION:
SHILOH BRANCH 10.0
END DESCRIPTION:
XS GIS Cut Line= 3
      2920324.99      6985124.98      2920075.00      6984725.00
      2919325.01      6984825.00
#Sta/Elev= 30
  4508.7  401.75  4537.6  400.36  4631.9  391.28  4674.4  385.16  4689.7  384.69
  4726.2  379.84  4830.1  376.48  4972.7  376.60  4982.9  375.86  4990.5  371.00
  4997.5  370.62  4998.0  369.82  5003.1  369.82  5003.6  370.62  5010.6  376.60
  5101.4  375.07  5282.8  376.48  5324.6  377.05  5397.8  380.25  5464.6  388.98
  5505.0  395.61  5515.1  396.26  5605.9  413.31  5615.9  415.58  5622.3  418.16
  5627.3  417.87  5646.2  423.30  5666.4  426.94  5695.4  430.70  5737.0  434.20
#Mann=3,-1,0
  4508.7    0.16       0  4997.5    0.07       0  5003.6    0.16       0
Bank Sta=4830.1,5282.8
Exp/Cntr=0.3,0.1

Type RM Length L Ch R = 1,5224,307,307,307
BEGIN DESCRIPTION:
SHILOH BRANCH 9.0
END DESCRIPTION:
XS GIS Cut Line= 3
      2920874.97      6984574.99      2920125.00      6984225.00
      2919525.02      6984474.99
#Sta/Elev= 30
  4175.5  415.47  4183.1  414.56  4246.3  409.33  4326.8  402.41  4332.3  400.06
  4349.7  397.62  4355.2  394.15  4365.3  393.62  4400.9  390.97  4418.2  392.04
  4497.9  381.11  4613.1  372.94  4757.2  372.04  4917.9  372.69  4981.0  373.10
  4991.4  368.24  4991.9  367.44  4997.5  368.24  5005.8  368.73  5012.3  373.00
  5026.0  372.71  5111.5  371.63  5219.2  373.96  5242.7  372.48  5308.5  372.94
  5351.0  374.73  5407.7  379.33  5469.0  386.74  5567.0  403.25  5653.1  415.10
#Mann=11,-1,0
  4175.5    0.05       0  4183.1    0.16       0  4246.3    0.05       0
  4365.3    0.16       0  4757.2    0.05       0  4917.9    0.12       0
  4991.4    0.07       0  4997.5    0.12       0  5026.0    0.16       0
  5242.7    0.12       0  5351.0    0.16       0
Bank Sta=4613.1,5308.5
Exp/Cntr=0.3,0.1

Type RM Length L Ch R = 1,4917,263,263,263
BEGIN DESCRIPTION:
Mapping XS 8e353a28
END DESCRIPTION:
XS GIS Cut Line= 3
      2920878.83      6984315.46      2920188.74      6983929.18
      2919385.78      6983929.18
#Sta/Elev= 30
  4197.8  392.25  4202.8  392.25  4208.4  387.12  4214.2  384.65  4230.1  381.50
  4267.8  378.58  4273.5  376.81  4295.2  374.66  4385.5  374.15  4502.0  371.05
  4626.2  369.52  4861.7  370.13  4944.1  370.04  4981.4  371.22  4999.3  367.93
  4999.8  367.13  5005.4  367.93  5012.4  371.41  5028.7  370.80  5182.0  370.51
  5222.4  369.71  5261.4  371.05  5522.4  375.48  5542.4  376.87  5562.4  381.28
  5594.5  385.57  5652.4  398.95  5682.4  404.13  5742.4  409.44  5791.6  410.71
#Mann=8,-1,0
  4197.8    0.12       0  4861.7    0.16       0  4944.1    0.12       0
  4999.3    0.07       0  5005.4    0.12       0  5028.7    0.16       0
  5182.0    0.12       0  5594.5    0.16       0
Bank Sta=4502,5261.4
Exp/Cntr=0.3,0.1

Type RM Length L Ch R = 1,4654,549,549,549
BEGIN DESCRIPTION:
SHILOH BRANCH 8.0
END DESCRIPTION:
XS GIS Cut Line= 3
      2920975.03      6983274.98      2920175.00      6983675.00
      2919524.98      6983625.00
#Sta/Elev= 30
  4117.2  438.88  4131.2  438.03  4153.6  434.18  4170.3  428.41  4192.7  423.43
  4296.1  409.21  4519.7  386.07  4726.7  369.81  4802.0  366.82  4966.9  368.57
  4989.3  369.79  4994.6  366.52  4995.1  365.72  5000.7  366.52  5008.9  369.41
  5021.7  370.03  5059.4  368.86  5165.0  368.43  5202.2  369.36  5222.3  367.76
  5232.3  369.07  5315.8  369.81  5372.7  370.86  5422.9  373.20  5442.9  372.82
  5480.0  377.70  5513.1  382.48  5581.1  395.54  5603.4  398.82  5663.6  403.22
#Mann=7,-1,0
  4117.2    0.12       0  4994.6    0.07       0  5000.7    0.12       0
  5059.4    0.16       0  5165.0    0.12       0  5480.0    0.16       0
  5581.1    0.12       0
Bank Sta=4726.7,5315.8
Exp/Cntr=0.3,0.1

Type RM Length L Ch R = 1,4105,583,583,583
BEGIN DESCRIPTION:
SHILOH BRANCH 7.0
END DESCRIPTION:
XS GIS Cut Line= 3
      2920674.96      6983025.01      2920225.00      6983125.00
      2919625.00      6983275.00
#Sta/Elev= 30
  4539.8  421.82  4564.1  420.96  4622.1  413.31  4662.7  406.67  4840.7  385.21
  4932.9  373.01  4953.9  367.65  4970.0  364.08  4976.4  366.89  4990.5  367.35
  4995.0  363.18  4995.5  362.38  5000.9  362.38  5001.4  363.18  5003.3  363.18
  5011.0  367.80  5018.8  368.02  5144.9  365.67  5157.9  365.58  5248.1  364.75
  5299.7  366.05  5312.5  364.48  5341.7  365.77  5353.8  365.42  5372.3  367.65
  5395.0  369.80  5513.5  386.47  5534.9  388.63  5592.5  394.61  5619.2  396.34
#Mann=9,-1,0
  4539.8    0.16       0  4622.1    0.12       0  4995.0    0.07       0
  5001.4    0.12       0  5144.9    0.16       0  5157.9    0.12       0
  5341.7    0.16       0  5534.9    0.12       0  5592.5    0.16       0
Bank Sta=4953.9,5372.3
Exp/Cntr=0.3,0.1

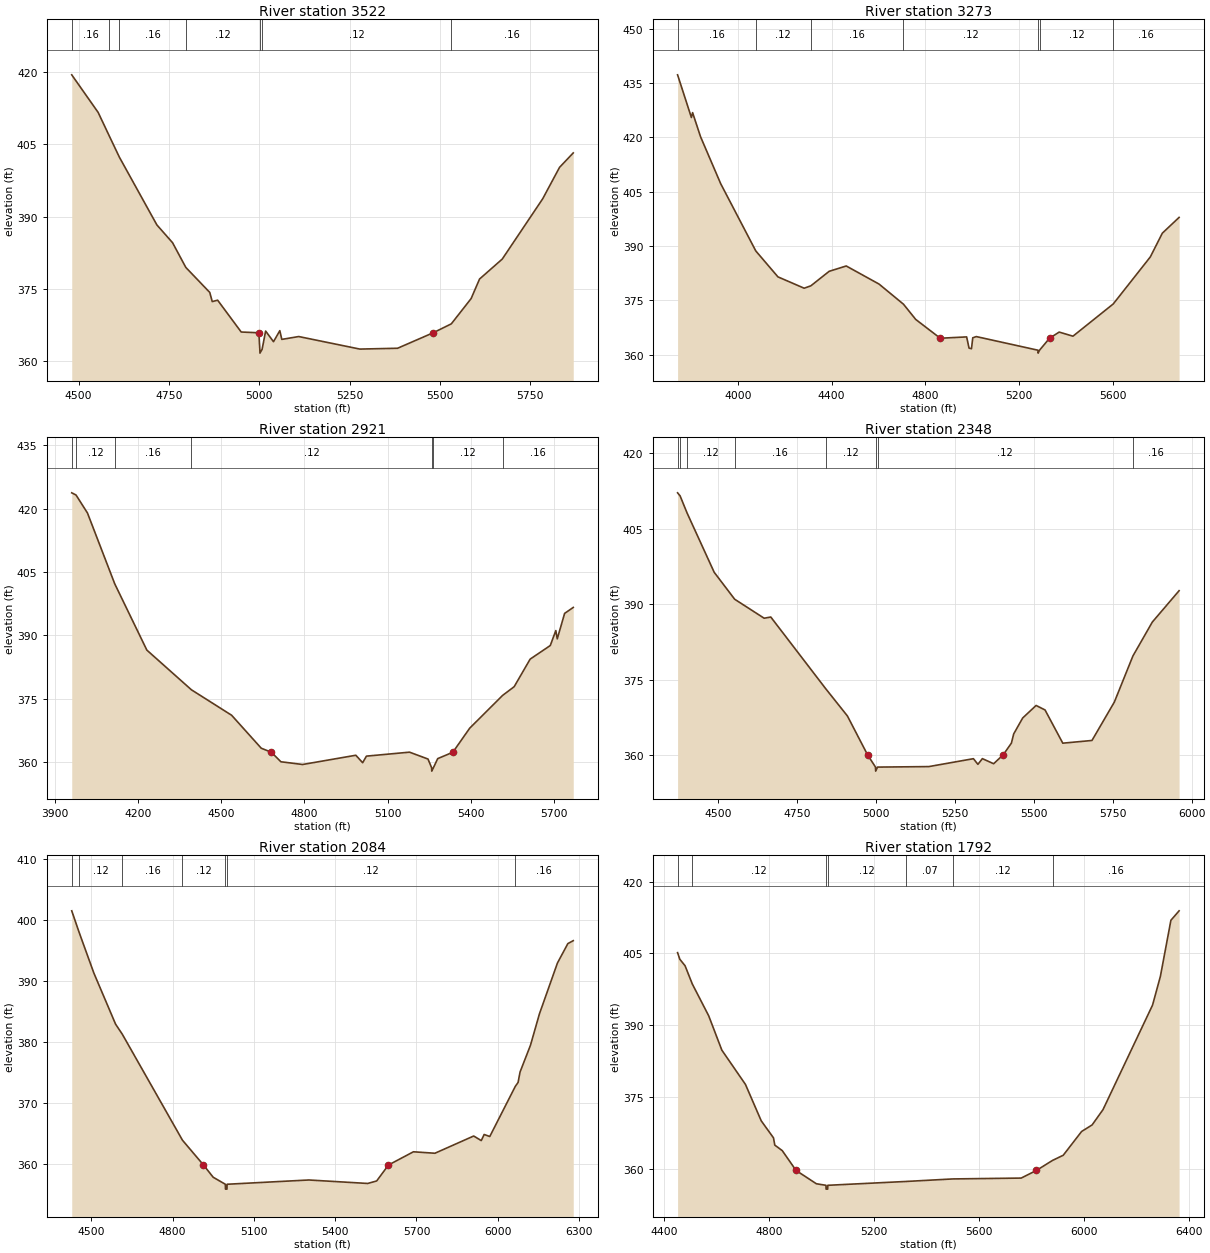
Type RM Length L Ch R = 1,3522,249,249,249
BEGIN DESCRIPTION:
SHILOH BRANCH 6.0
END DESCRIPTION:
XS GIS Cut Line= 3
      2920624.97      6982824.98      2920175.00      6982575.00
      2919374.96      6982925.02
#Sta/Elev= 30
  4481.1  419.40  4554.3  411.59  4585.5  406.64  4613.0  402.31  4716.7  388.27
  4760.2  384.57  4796.8  379.45  4863.1  374.26  4870.0  372.36  4884.9  372.65
  4950.1  366.05  4999.0  365.89  5001.6  362.47  5002.1  361.67  5008.0  362.47
  5017.7  366.25  5039.5  364.04  5057.0  366.33  5062.5  364.52  5109.3  365.11
  5278.5  362.51  5382.9  362.68  5481.4  365.89  5531.6  367.74  5586.4  372.98
  5609.8  377.04  5672.6  381.18  5784.5  393.68  5831.2  400.21  5869.1  403.20
#Mann=7,-1,0
  4481.1    0.16       0  4585.5    0.12       0  4613.0    0.16       0
  4796.8    0.12       0  5001.6    0.07       0  5008.0    0.12       0
  5531.6    0.16       0
Bank Sta=4999,5481.4
Exp/Cntr=0.3,0.1

Type RM Length L Ch R = 1,3273,352,352,352
BEGIN DESCRIPTION:
Mapping XS 74f719b4
END DESCRIPTION:
XS GIS Cut Line= 3
      2921351.98      6982657.50      2920210.44      6982331.96
      2919285.94      6982566.34
#Sta/Elev= 30
  3742.8  437.28  3801.7  425.50  3806.9  426.84  3840.8  420.19  3926.8  407.22
  4076.7  388.64  4171.2  381.48  4283.1  378.35  4311.5  379.00  4389.8  383.01
  4462.7  384.49  4602.8  379.49  4707.1  373.93  4759.3  369.73  4864.1  364.53
  4976.7  364.90  4987.0  361.81  4997.4  361.63  5002.9  364.66  5018.0  364.99
  5281.4  361.22  5281.9  360.42  5287.8  361.22  5330.5  364.53  5371.7  366.23
  5430.6  365.10  5602.6  374.01  5760.8  386.99  5812.1  393.55  5883.6  397.90
#Mann=7,-1,0
  3742.8    0.16       0  4076.7    0.12       0  4311.5    0.16       0
  4707.1    0.12       0  5281.4    0.07       0  5287.8    0.12       0
  5602.6    0.16       0
Bank Sta=4864.1,5330.5
Exp/Cntr=0.3,0.1

Type RM Length L Ch R = 1,2921,573,573,573
BEGIN DESCRIPTION:
SHILOH BRANCH 5.0
END DESCRIPTION:
XS GIS Cut Line= 3
      2920875.00      6981375.00      2920075.00      6982025.00
      2919324.98      6982225.01
#Sta/Elev= 30
  3961.7  423.77  3977.2  423.25  4018.4  418.99  4116.6  402.23  4232.3  386.53
  4392.7  377.14  4537.8  371.10  4644.6  363.29  4681.0  362.34  4715.2  360.09
  4793.5  359.44  4985.3  361.63  5009.9  359.86  5023.5  361.42  5178.8  362.36
  5245.4  360.73  5258.4  358.67  5258.9  357.87  5264.8  358.67  5280.3  360.83
  5334.9  362.34  5395.5  368.03  5514.0  375.79  5555.9  377.87  5613.4  384.39
  5685.9  387.61  5705.9  391.15  5711.1  389.19  5737.6  395.22  5768.7  396.63
#Mann=7,-1,0
  3961.7    0.08       0  3977.2    0.12       0  4116.6    0.16       0
  4392.7    0.12       0  5258.4    0.07       0  5264.8    0.12       0
  5514.0    0.16       0
Bank Sta=4681,5334.9
Exp/Cntr=0.3,0.1

Type RM Length L Ch R = 1,2348,264,264,264
BEGIN DESCRIPTION:
SHILOH BRANCH 4.0
END DESCRIPTION:
XS GIS Cut Line= 3
      2920674.98      6981275.01      2920075.00      6981475.00
      2919374.99      6982125.01
#Sta/Elev= 30
  4372.6  412.10  4380.6  411.49  4402.9  408.06  4488.5  396.32  4553.3  390.97
  4646.6  387.20  4667.7  387.43  4841.8  373.18  4910.2  367.79  4974.0  360.07
  4999.2  357.63  4999.7  356.83  5005.7  357.63  5168.0  357.73  5309.2  359.30
  5323.4  358.18  5337.5  359.31  5373.2  358.30  5403.5  360.07  5429.4  362.39
  5436.7  364.22  5465.1  367.38  5507.6  369.87  5535.9  368.98  5592.1  362.38
  5684.5  362.92  5755.3  370.54  5814.2  379.71  5875.5  386.43  5960.3  392.66
#Mann=8,-1,0
  4372.6    0.08       0  4380.6    0.16       0  4402.9    0.12       0
  4553.3    0.16       0  4841.8    0.12       0  4999.2    0.07       0
  5005.7    0.12       0  5814.2    0.16       0
Bank Sta=4974,5403.5
Exp/Cntr=0.3,0.1

Type RM Length L Ch R = 1,2084,292,292,292
BEGIN DESCRIPTION:
Mapping XS 3ce7b47d
END DESCRIPTION:
XS GIS Cut Line= 3
      2920596.74      6981212.17      2920023.81      6981220.85
      2918799.94      6981585.41
#Sta/Elev= 30
  4428.3  401.52  4455.2  398.03  4510.0  391.29  4590.1  382.91  4615.0  381.25
  4836.8  363.86  4914.3  359.79  4950.1  357.78  4994.9  356.63  4995.4  355.83
  5000.9  355.83  5001.4  356.63  5302.6  357.33  5520.1  356.76  5553.1  357.17
  5596.7  359.79  5688.7  361.96  5768.0  361.72  5911.1  364.55  5939.0  363.80
  5949.6  364.80  5970.4  364.47  6064.7  372.71  6074.8  373.34  6082.1  375.06
  6120.5  379.45  6153.7  384.62  6220.0  392.95  6258.4  396.14  6278.3  396.62
#Mann=7,-1,0
  4428.3    0.16       0  4455.2    0.12       0  4615.0    0.16       0
  4836.8    0.12       0  4994.9    0.07       0  5001.4    0.12       0
  6064.7    0.16       0
Bank Sta=4914.3,5596.7
Exp/Cntr=0.3,0.1

Type RM Length L Ch R = 1,1792,545,545,545
BEGIN DESCRIPTION:
SHILOH BRANCH 3.0
END DESCRIPTION:
XS GIS Cut Line= 3
      2920433.54      6980960.43      2919875.00      6980975.00
      2918523.80      6980943.07
#Sta/Elev= 30
  4451.7  405.17  4460.2  403.79  4480.2  402.43  4507.7  398.63  4570.3  391.96
  4620.3  384.79  4710.3  377.62  4770.3  370.02  4817.0  366.46  4822.0  364.94
  4850.4  363.79  4903.1  359.64  4980.4  356.86  5016.9  356.54  5017.4  355.74
  5023.4  355.74  5023.9  356.54  5321.3  357.34  5499.9  357.87  5760.6  358.05
  5818.3  359.64  5880.2  361.75  5920.7  362.82  5990.7  367.79  6030.7  369.16
  6072.2  372.36  6260.8  394.19  6290.8  400.22  6330.8  411.93  6362.0  413.91
#Mann=7,-1,0
  4451.7    0.16       0  4507.7    0.12       0  5016.9    0.07       0
  5023.9    0.12       0  5321.3    0.07       0  5499.9    0.12       0
  5880.2    0.16       0
Bank Sta=4903.1,5818.3
Exp/Cntr=0.3,0.1