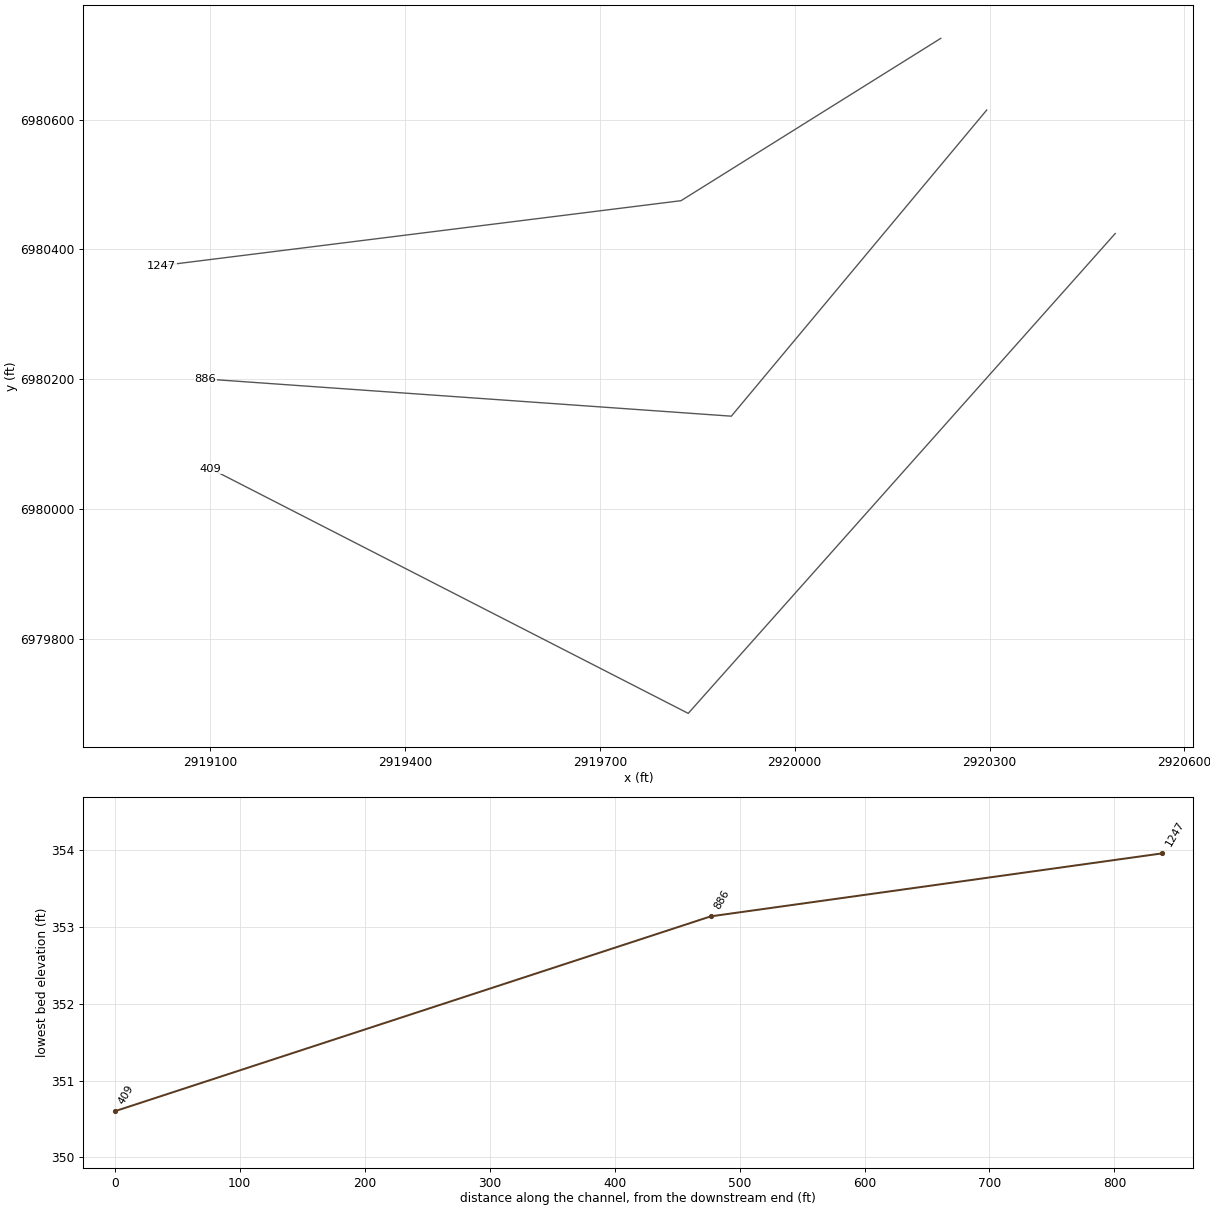
HEC-RAS study SHILOH BRANCH.prj: SHILOH BRANCH Base Level Engineering

--- SHILOH BRANCH.g01 (geometry) --- (continued)

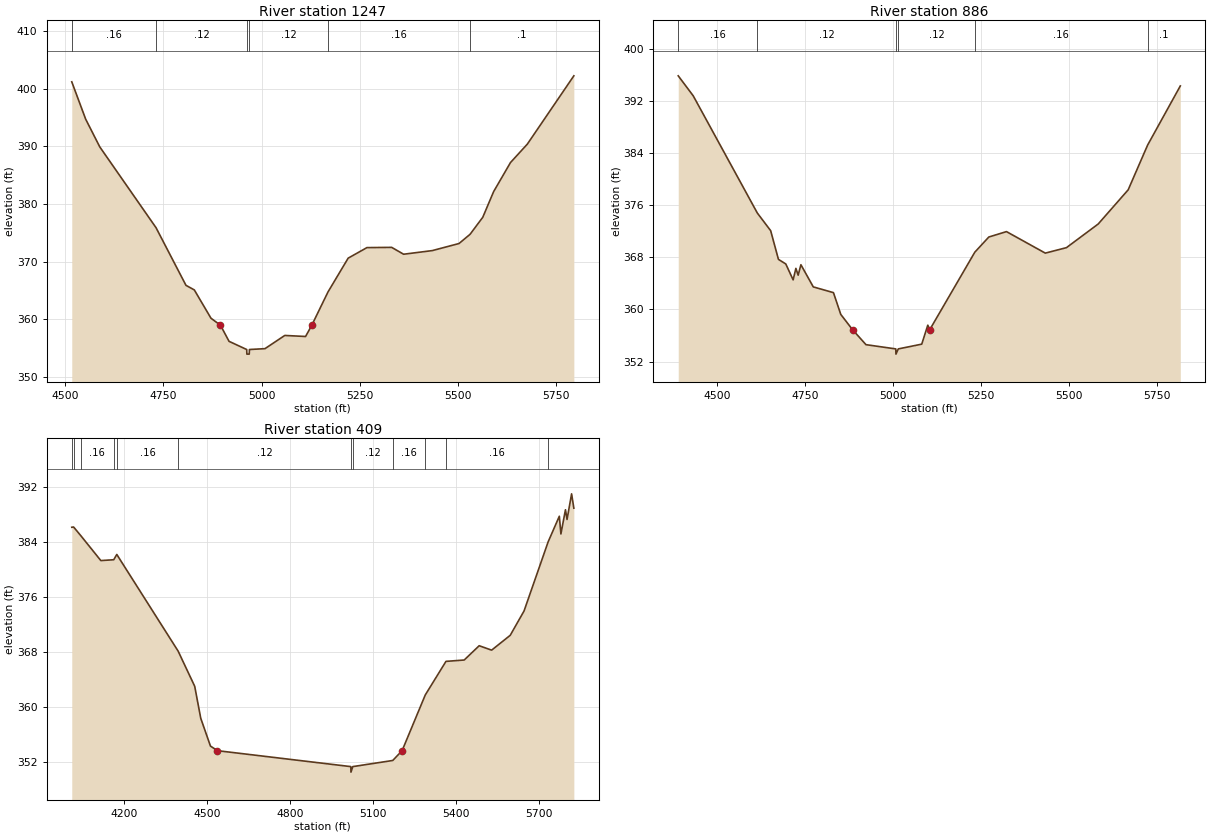
Type RM Length L Ch R = 1,1247,361,361,361
BEGIN DESCRIPTION:
SHILOH BRANCH 2.0
END DESCRIPTION:
XS GIS Cut Line= 3
      2920224.99      6980724.99      2919825.00      6980475.00
      2919025.01      6980375.00
#Sta/Elev= 30
  4516.7  401.20  4552.1  394.72  4588.0  389.91  4731.3  375.88  4807.4  365.89
  4828.6  365.10  4871.0  360.19  4895.2  358.97  4917.0  356.18  4961.9  354.76
  4962.4  353.96  4968.4  353.96  4968.9  354.76  5008.5  354.91  5058.9  357.20
  5111.8  357.02  5127.6  358.97  5168.9  364.75  5220.2  370.61  5268.0  372.44
  5331.0  372.48  5361.3  371.29  5434.3  371.92  5502.4  373.15  5530.5  374.75
  5562.8  377.70  5590.5  382.16  5633.4  387.20  5676.2  390.39  5794.6  402.24
#Mann=6,-1,0
  4516.7    0.16       0  4731.3    0.12       0  4961.9    0.07       0
  4968.9    0.12       0  5168.9    0.16       0  5530.5     0.1       0
Bank Sta=4895.2,5127.6
Exp/Cntr=0.3,0.1

Type RM Length L Ch R = 1,886,477,477,477
BEGIN DESCRIPTION:
Mapping XS 7286bb34
END DESCRIPTION:
XS GIS Cut Line= 3
      2920295.67      6980614.53      2919902.43      6980143.16
      2919092.52      6980200.45
#Sta/Elev= 30
  4389.5  395.82  4432.0  392.76  4614.1  374.78  4652.0  372.07  4674.1  367.67
  4694.9  366.97  4715.8  364.53  4723.6  366.29  4730.1  365.25  4737.9  366.85
  4773.0  363.45  4830.3  362.57  4851.1  359.23  4884.5  356.89  4922.7  354.59
  5007.3  353.94  5007.8  353.14  5014.4  353.94  5081.0  354.67  5098.2  357.58
  5103.8  356.89  5231.7  368.77  5271.5  371.10  5321.6  371.93  5431.9  368.63
  5492.0  369.47  5582.2  373.10  5667.3  378.34  5722.4  385.19  5815.3  394.27
#Mann=6,-1,0
  4389.5    0.16       0  4614.1    0.12       0  5007.3    0.07       0
  5014.4    0.12       0  5231.7    0.16       0  5722.4     0.1       0
Bank Sta=4884.5,5103.8
Exp/Cntr=0.3,0.1

Type RM Length L Ch R = 1,409,0,0,0
BEGIN DESCRIPTION:
SHILOH BRANCH 1.0
END DESCRIPTION:
XS GIS Cut Line= 3
      2920493.58      6980424.42      2919836.05      6979685.52
      2919100.37      6980062.42
#Sta/Elev= 30
  4010.9  386.11  4017.5  386.15  4043.8  384.88  4116.0  381.28  4162.7  381.40
  4173.7  382.17  4395.7  368.14  4455.5  363.05  4477.3  358.42  4512.4  354.38
  4537.8  353.71  5020.1  351.40  5020.6  350.60  5027.2  351.40  5171.7  352.29
  5205.5  353.71  5289.3  361.79  5364.1  366.66  5430.1  366.86  5484.3  368.93
  5529.3  368.29  5596.5  370.44  5646.5  373.97  5733.8  384.01  5774.1  387.71
  5779.8  385.14  5796.3  388.65  5802.0  387.24  5818.5  390.96  5826.6  388.88
#Mann=12,-1,0
  4010.9    0.08       0  4017.5    0.05       0  4043.8    0.16       0
  4162.7    0.12       0  4173.7    0.16       0  4395.7    0.12       0
  5020.1    0.07       0  5027.2    0.12       0  5171.7    0.16       0
  5289.3    0.12       0  5364.1    0.16       0  5733.8     0.1       0
Bank Sta=4537.8,5205.5
Exp/Cntr=0.3,0.1

Chan Stop Cuts=-1