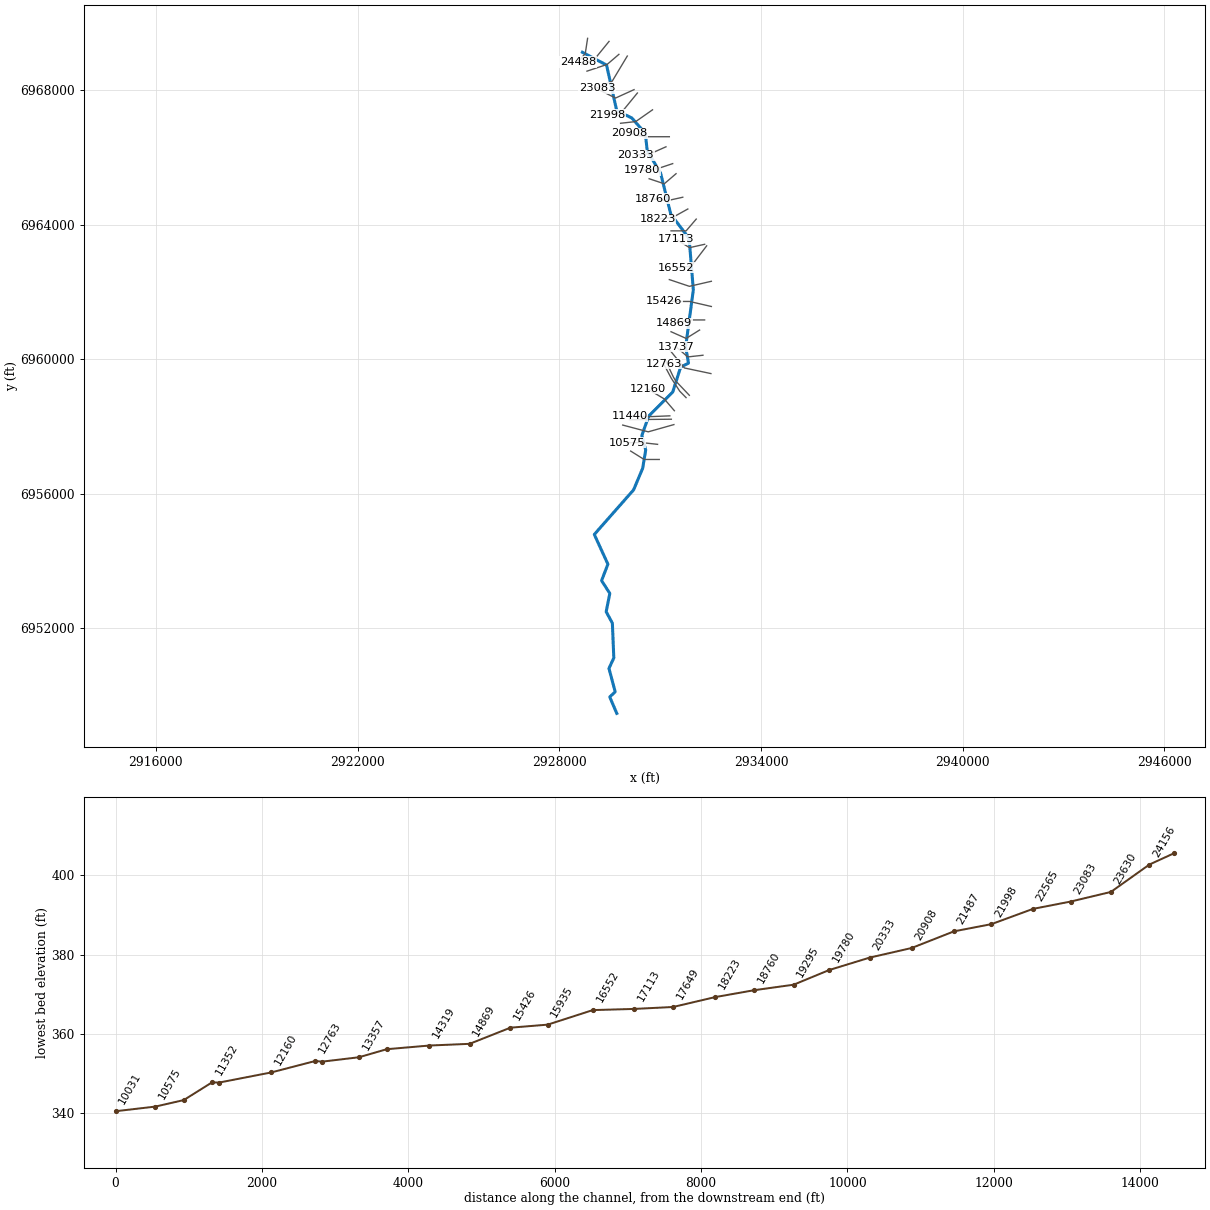
--- STEWART BRANCH.prj (project) ---

Proj Title=STEWART BRANCH Base Level Engineering
Current Plan=p01
Default Exp/Contr=0.3,0.1
English Units
Geom File=g01
Flow File=f01
Plan File=p01
BEGIN DESCRIPTION:
STEWART BRANCH
END DESCRIPTION:

--- STEWART BRANCH.p01 (plan) ---

Plan Title=Multiple Run
Short Identifier=Multiple
Geom File=g01
Flow File=f01
Subcritical Flow
K Sum by GR= 0
Std Step Tol= 0.01
Critical Tol= 0.01
Num of Std Step Trials= 20
Max Error Tol= 0.3
Flow Tol Ratio= 0.001
Split Flow NTrial= 30
Split Flow Tol= 0.02
Split Flow Ratio= 0.02
Log Output Level= 0
Friction Slope Method= 1
Unsteady Friction Slope Method= 2
Unsteady Bridges Friction Slope Method= 1
Parabolic Critical Depth
Global Vel Dist=  1 , 1 , 1
Global Log Level= 0
CheckData=True
Encroach Param= -1, 0, 0, 0
BEGIN DESCRIPTION:
Multiple Run
END DESCRIPTION:

--- STEWART BRANCH.f01 (steady flow) ---

Flow Title=Multiple
Program Version=5.07
Number of Profiles= 7
Profile Names=10-year,25-year,50-year,1pct_min,100-year,1pct_plu,500-year
River Rch & RM=STEWART BRANCH,Reach-1         ,24488
     732    1009    1242     761    1518    3029    2272
River Rch & RM=STEWART BRANCH,Reach-1         ,23630
    1052    1471    1827    1127    2249    4486    3414
River Rch & RM=STEWART BRANCH,Reach-1         ,15935
    1496    2122    2660    1654    3300    6585    5092
River Rch & RM=STEWART BRANCH,Reach-1         ,8437
    1658    2354    2952    1835    3661    7305    5647
Boundary for River Rch & Prof#=STEWART BRANCH,Reach-1         , 1
Up Type= 0
Dn Type= 3
Dn Slope=0.005
Boundary for River Rch & Prof#=STEWART BRANCH,Reach-1         , 2
Up Type= 0
Dn Type= 3
Dn Slope=0.005
Boundary for River Rch & Prof#=STEWART BRANCH,Reach-1         , 3
Up Type= 0
Dn Type= 3
Dn Slope=0.005
Boundary for River Rch & Prof#=STEWART BRANCH,Reach-1         , 4
Up Type= 0
Dn Type= 3
Dn Slope=0.005
Boundary for River Rch & Prof#=STEWART BRANCH,Reach-1         , 5
Up Type= 0
Dn Type= 3
Dn Slope=0.005
Boundary for River Rch & Prof#=STEWART BRANCH,Reach-1         , 6
Up Type= 0
Dn Type= 3
Dn Slope=0.005
Boundary for River Rch & Prof#=STEWART BRANCH,Reach-1         , 7
Up Type= 0
Dn Type= 3
Dn Slope=0.005
DSS Import GetInterval= 0
DSS Import GetPeak= 0
DSS Import FillOption= 0

--- STEWART BRANCH.g01 (geometry) ---

Geom Title=Existing Conditions

River Reach=STEWART BRANCH,Reach-1
Reach XY= 30
      2928688.71      6969136.57      2929407.74      6968757.04
      2929709.10      6967403.56      2930163.79      6967177.93
      2930560.42      6966723.21      2930617.82      6966206.16
      2931014.13      6965545.11      2931318.22      6964321.80
      2931864.40      6963595.28      2931988.66      6962069.11
      2931760.36      6960370.23      2931845.59      6959890.71
      2931611.93      6959772.14      2931374.95      6959028.65
      2930661.41      6958315.11      2930456.66      6957736.95
      2930571.98      6957305.56      2930481.25      6956761.45
      2930212.51      6956121.77      2929043.25      6954794.24
      2929447.74      6953910.90      2929259.99      6953421.81
      2929505.05      6953040.80      2929396.76      6952495.55
      2929580.92      6952155.19      2929623.38      6951121.14
      2929479.22      6950810.79      2929664.41      6950115.69
      2929502.77      6949960.42      2929712.30      6949472.77

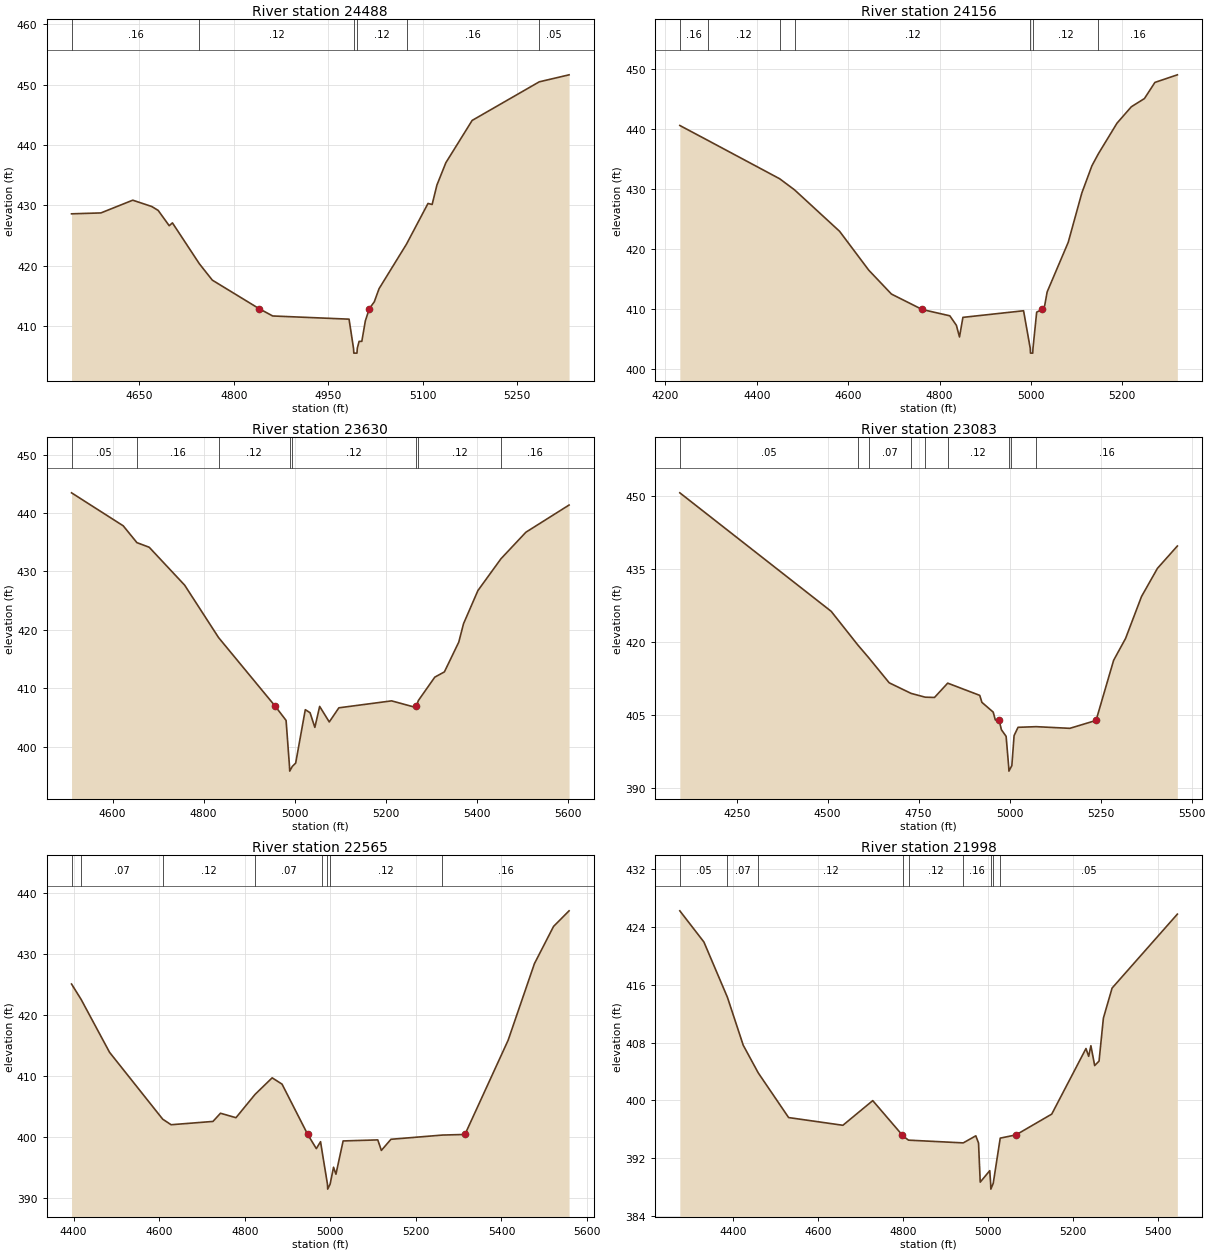
Type RM Length L Ch R = 1,24488,332,332,332
BEGIN DESCRIPTION:
STEWART BRANCH 39.0
END DESCRIPTION:
XS GIS Cut Line= 3
      2928843.84      6969551.14      2928774.64      6969098.39
      2928553.96      6968849.03
#Sta/Elev= 30
  4542.0  428.60  4588.7  428.75  4639.3  430.86  4669.6  429.81  4679.7  429.17
  4697.3  426.63  4702.4  427.10  4745.3  420.31  4765.8  417.61  4840.2  412.88
  4861.8  411.67  4983.2  411.14  4990.3  406.31  4990.8  405.51  4995.8  405.51
  4996.3  406.31  4999.2  407.46  5003.5  407.46  5009.1  410.85  5015.4  412.88
  5023.3  414.01  5030.9  416.19  5074.6  423.59  5108.7  430.32  5115.3  430.15
  5122.9  433.37  5137.1  437.07  5178.9  444.08  5285.6  450.48  5333.0  451.64
#Mann=6,-1,0
  4542.0    0.16       0  4745.3    0.12       0  4990.3    0.07       0
  4996.3    0.12       0  5074.6    0.16       0  5285.6    0.05       0
Bank Sta=4840.2,5015.4
Exp/Cntr=0.3,0.1

Type RM Length L Ch R = 1,24156,526,526,526
BEGIN DESCRIPTION:
Mapping XS d7a7395b
END DESCRIPTION:
XS GIS Cut Line= 3
      2929481.85      6969459.96      2929065.19      6968947.81
      2928674.73      6968769.94
#Sta/Elev= 30
  4231.4  440.58  4293.3  438.08  4450.1  431.71  4482.7  429.86  4581.2  422.97
  4645.1  416.50  4694.7  412.53  4762.0  409.96  4822.5  408.91  4836.9  407.33
  4843.7  405.39  4851.2  408.65  4984.0  409.75  4998.6  403.50  4999.1  402.70
  5004.1  402.70  5004.6  403.50  5012.7  409.52  5024.3  409.96  5030.1  410.56
  5035.6  412.88  5081.7  421.13  5111.6  429.36  5133.6  433.87  5147.5  435.84
  5188.5  440.96  5220.0  443.70  5248.6  445.06  5271.6  447.75  5320.7  449.01
#Mann=7,-1,0
  4231.4    0.16       0  4293.3    0.12       0  4450.1    0.16       0
  4482.7    0.12       0  4998.6    0.07       0  5004.6    0.12       0
  5147.5    0.16       0
Bank Sta=4762,5024.3
Exp/Cntr=0.3,0.1

Type RM Length L Ch R = 1,23630,547,547,547
BEGIN DESCRIPTION:
STEWART BRANCH 38.0
END DESCRIPTION:
XS GIS Cut Line= 3
      2929774.99      6969074.99      2929425.00      6968775.00
      2928825.02      6968575.01
#Sta/Elev= 30
  4509.8  443.45  4623.4  437.80  4653.5  434.92  4680.5  434.13  4758.4  427.64
  4833.0  418.66  4957.9  406.87  4981.3  404.48  4988.8  396.60  4989.3  395.80
  4994.9  396.60  5002.4  397.18  5023.5  406.32  5034.0  405.80  5044.5  403.29
  5055.1  406.88  5076.2  404.22  5097.3  406.64  5213.2  407.83  5266.3  406.70
  5267.1  406.87  5272.1  407.90  5308.1  411.89  5329.2  412.79  5360.8  417.89
  5371.3  421.05  5402.9  426.72  5453.5  432.16  5508.4  436.71  5603.2  441.36
#Mann=8,-1,0
  4509.8    0.05       0  4653.5    0.16       0  4833.0    0.12       0
  4988.8    0.07       0  4994.9    0.12       0  5266.3    0.16       0
  5272.1    0.12       0  5453.5    0.16       0
Bank Sta=4957.9,5267.1
Exp/Cntr=0.3,0.1

Type RM Length L Ch R = 1,23083,518,518,518
BEGIN DESCRIPTION:
STEWART BRANCH 37.0
END DESCRIPTION:
XS GIS Cut Line= 3
      2930024.98      6969024.96      2929575.00      6968275.00
      2929125.03      6968075.02
#Sta/Elev= 30
  4093.8  450.74  4509.7  426.32  4582.5  419.42  4613.4  416.70  4669.1  411.59
  4729.2  409.41  4767.8  408.63  4793.5  408.57  4829.8  411.52  4917.9  409.00
  4923.7  407.57  4954.8  405.55  4960.6  403.95  4971.3  403.84  4977.3  401.93
  4990.3  400.56  4997.5  394.19  4998.0  393.39  5003.6  394.19  5006.0  394.49
  5012.2  400.71  5023.1  402.42  5072.8  402.55  5165.4  402.21  5237.4  403.84
  5285.7  416.23  5318.6  420.75  5362.3  429.37  5406.1  435.18  5460.8  439.78
#Mann=9,-1,0
  4093.8    0.05       0  4582.5    0.12       0  4613.4    0.07       0
  4729.2    0.12       0  4767.8    0.07       0  4829.8    0.12       0
  4997.5    0.07       0  5003.6    0.12       0  5072.8    0.16       0
Bank Sta=4971.3,5237.4
Exp/Cntr=0.3,0.1

Type RM Length L Ch R = 1,22565,567,567,567
BEGIN DESCRIPTION:
STEWART BRANCH 36.0
END DESCRIPTION:
XS GIS Cut Line= 3
      2930224.97      6968024.99      2929675.00      6967775.00
      2929175.03      6968024.99
#Sta/Elev= 30
  4395.0  425.07  4417.2  422.58  4483.9  413.90  4608.1  402.97  4627.8  402.06
  4725.6  402.60  4743.2  403.94  4779.4  403.21  4824.0  407.02  4864.0  409.73
  4887.1  408.70  4947.1  400.47  4967.3  398.15  4977.1  399.29  4981.2  397.49
  4993.3  392.33  4993.8  391.53  4999.4  392.33  5007.5  395.11  5013.1  393.97
  5029.9  399.41  5110.9  399.58  5119.3  397.86  5141.7  399.68  5261.8  400.37
  5314.7  400.47  5415.6  415.87  5477.1  428.40  5521.8  434.49  5558.1  437.04
#Mann=8,-1,0
  4395.0    0.05       0  4417.2    0.07       0  4608.1    0.12       0
  4824.0    0.07       0  4981.2    0.12       0  4993.3    0.07       0
  4999.4    0.12       0  5261.8    0.16       0
Bank Sta=4947.1,5314.7
Exp/Cntr=0.3,0.1

Type RM Length L Ch R = 1,21998,511,511,511
BEGIN DESCRIPTION:
STEWART BRANCH 35.0
END DESCRIPTION:
XS GIS Cut Line= 3
      2930324.97      6967924.97      2929875.00      6967375.00
      2929424.97      6967274.99
#Sta/Elev= 30
  4273.9  426.27  4330.6  421.95  4386.0  414.28  4423.2  407.64  4458.5  403.81
  4530.1  397.61  4657.9  396.54  4728.2  399.96  4797.4  395.21  4798.7  395.08
  4812.4  394.48  4941.3  394.10  4970.9  395.08  4977.3  394.08  4981.3  388.66
  5003.7  390.25  5005.8  388.49  5006.3  387.69  5011.9  388.49  5028.4  394.76
  5065.5  395.21  5149.7  398.09  5230.3  407.18  5236.7  406.10  5241.9  407.57
  5250.8  404.82  5261.1  405.44  5271.3  411.39  5291.8  415.56  5445.5  425.81
#Mann=9,-1,0
  4273.9    0.05       0  4386.0    0.07       0  4458.5    0.12       0
  4798.7    0.16       0  4812.4    0.12       0  4941.3    0.16       0
  5005.8    0.07       0  5011.9    0.16       0  5028.4    0.05       0
Bank Sta=4797.4,5065.5
Exp/Cntr=0.3,0.1

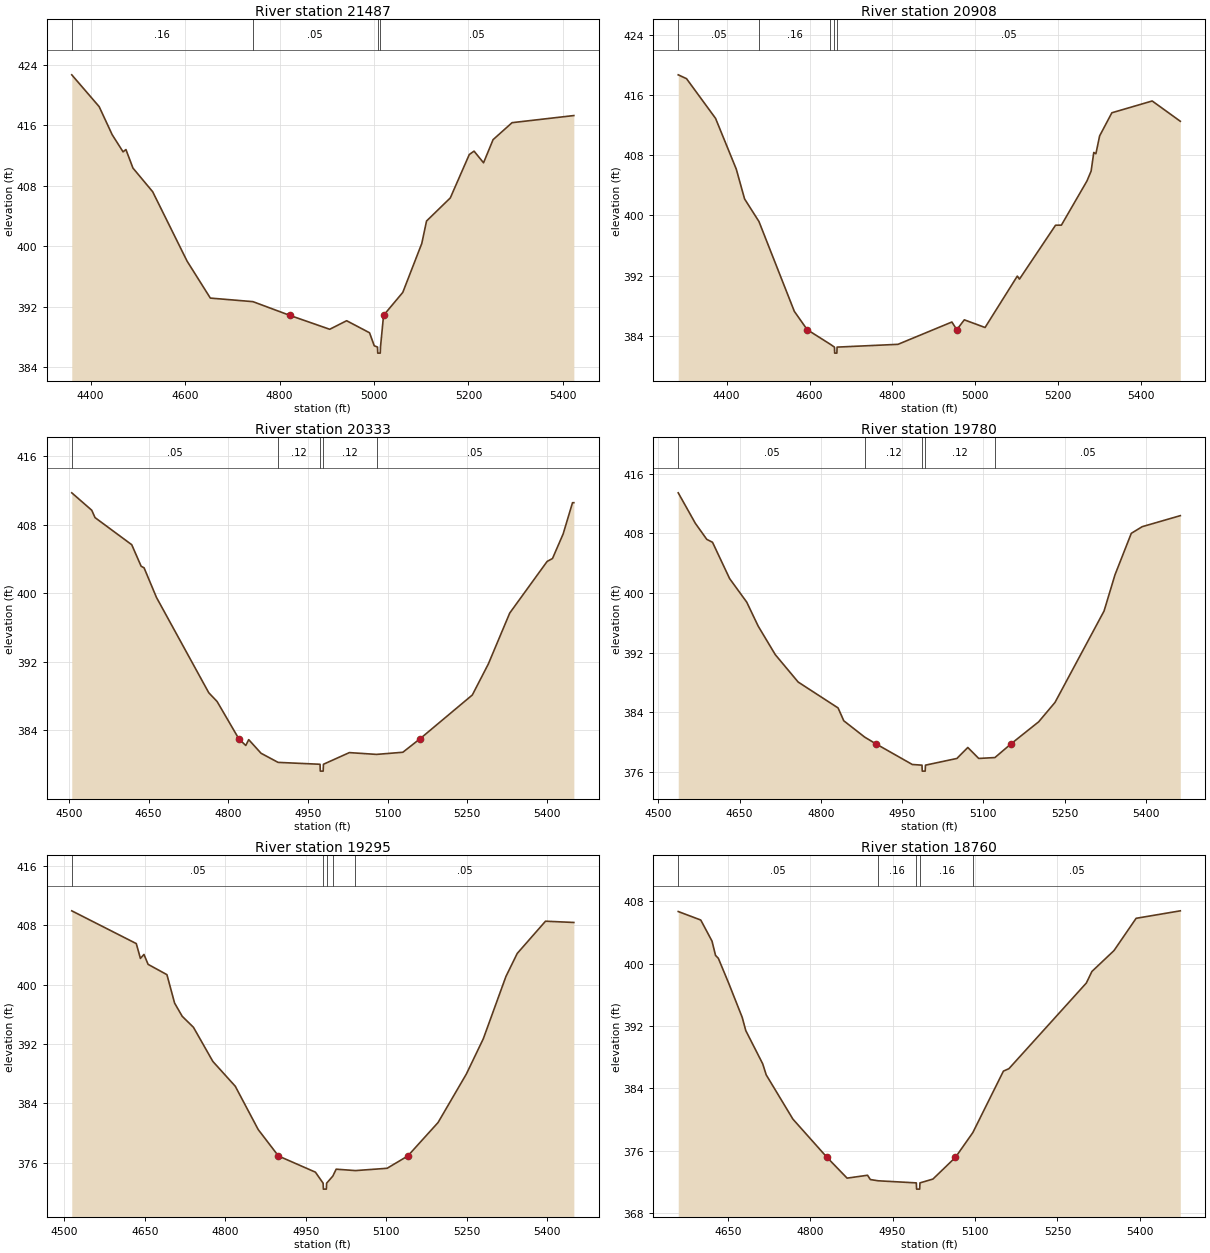
Type RM Length L Ch R = 1,21487,579,579,579
BEGIN DESCRIPTION:
STEWART BRANCH 34.0
END DESCRIPTION:
XS GIS Cut Line= 3
      2930775.01      6967425.00      2930275.00      6967075.00
      2929825.00      6967025.00
#Sta/Elev= 30
  4360.1  422.64  4418.1  418.44  4445.6  414.74  4468.7  412.47  4474.8  412.77
  4489.6  410.33  4531.4  407.20  4604.2  398.04  4653.5  393.15  4743.7  392.68
  4821.6  390.87  4906.3  389.03  4942.1  390.16  4990.6  388.57  5000.6  386.85
  5007.5  386.68  5008.0  385.88  5013.3  385.88  5013.8  386.68  5020.3  390.87
  5061.0  393.90  5101.2  400.36  5111.3  403.33  5161.6  406.38  5201.8  412.11
  5211.9  412.56  5232.0  411.02  5252.2  414.08  5292.4  416.32  5423.2  417.26
#Mann=4,-1,0
  4360.1    0.16       0  4743.7    0.05       0  5007.5    0.03       0
  5013.8    0.05       0
Bank Sta=4821.6,5020.3
Exp/Cntr=0.3,0.1

Type RM Length L Ch R = 1,20908,575,575,575
BEGIN DESCRIPTION:
STEWART BRANCH 33.0
END DESCRIPTION:
XS GIS Cut Line= 3
      2931274.97      6966625.00      2930525.00      6966625.00
      2930075.04      6966724.99
#Sta/Elev= 30
  4283.3  418.71  4303.3  418.20  4373.3  412.92  4423.3  406.16  4443.3  402.20
  4478.0  399.19  4563.3  387.24  4594.4  384.80  4649.7  382.87  4660.1  382.48
  4660.6  381.68  4665.9  381.68  4666.4  382.48  4813.3  382.85  4943.3  385.82
  4955.1  384.80  4973.3  386.11  5023.3  385.09  5101.1  391.93  5106.3  391.53
  5193.3  398.70  5207.4  398.71  5268.9  404.57  5279.1  405.90  5285.5  408.38
  5290.6  408.21  5299.6  410.58  5329.1  413.66  5426.4  415.23  5494.2  412.53
#Mann=5,-1,0
  4283.3    0.05       0  4478.0    0.16       0  4649.7    0.05       0
  4660.1    0.03       0  4666.4    0.05       0
Bank Sta=4594.4,4955.1
Exp/Cntr=0.3,0.1

Type RM Length L Ch R = 1,20333,553,553,553
BEGIN DESCRIPTION:
STEWART BRANCH 32.0
END DESCRIPTION:
XS GIS Cut Line= 3
      2931175.01      6966325.01      2930725.00      6966125.00
      2930275.03      6966075.00
#Sta/Elev= 30
  4505.4  411.70  4543.0  409.67  4549.2  408.81  4618.3  405.65  4636.0  403.14
  4641.5  402.96  4664.8  399.51  4763.3  388.39  4779.0  387.37  4820.1  383.00
  4833.0  382.24  4838.5  382.92  4861.8  381.33  4893.8  380.27  4972.8  380.05
  4973.3  379.25  4978.7  379.25  4979.2  380.05  5028.0  381.41  5079.1  381.20
  5128.7  381.45  5160.6  383.00  5259.5  388.13  5289.6  391.74  5329.9  397.68
  5400.3  403.70  5410.4  404.04  5430.5  406.91  5448.1  410.55  5450.6  410.55
#Mann=5,-1,0
  4505.4    0.05       0  4893.8    0.12       0  4972.8    0.07       0
  4979.2    0.12       0  5079.1    0.05       0
Bank Sta=4820.1,5160.6
Exp/Cntr=0.3,0.1

Type RM Length L Ch R = 1,19780,485,485,485
BEGIN DESCRIPTION:
STEWART BRANCH 31.0
END DESCRIPTION:
XS GIS Cut Line= 3
      2931375.02      6965825.01      2930925.00      6965675.00
      2930475.03      6965625.00
#Sta/Elev= 30
  4536.7  413.44  4568.3  409.35  4589.4  407.20  4600.0  406.81  4631.6  401.94
  4663.2  398.78  4684.3  395.57  4715.9  391.74  4758.1  388.07  4831.9  384.59
  4842.4  382.87  4881.2  380.67  4901.2  379.80  4968.9  377.01  4986.8  376.92
  4987.3  376.12  4992.7  376.12  4993.2  376.92  5051.3  377.82  5071.4  379.29
  5091.6  377.82  5121.5  377.94  5151.6  379.80  5202.2  382.73  5232.4  385.33
  5323.0  397.59  5343.1  402.43  5373.3  408.01  5393.4  408.90  5463.8  410.38
#Mann=5,-1,0
  4536.7    0.05       0  4881.2    0.12       0  4986.8    0.07       0
  4993.2    0.12       0  5121.5    0.05       0
Bank Sta=4901.2,5151.6
Exp/Cntr=0.3,0.1

Type RM Length L Ch R = 1,19295,535,535,535
BEGIN DESCRIPTION:
STEWART BRANCH 30.0
END DESCRIPTION:
XS GIS Cut Line= 3
      2931475.03      6965525.02      2931125.00      6965225.00
      2930674.96      6965375.01
#Sta/Elev= 30
  4514.1  409.97  4634.3  405.55  4642.0  403.55  4648.6  404.09  4656.3  402.75
  4691.4  401.36  4705.7  397.52  4719.9  395.74  4740.8  394.26  4777.0  389.65
  4818.7  386.31  4861.5  380.46  4899.2  376.90  4968.0  374.72  4982.4  373.23
  4982.9  372.43  4988.4  372.43  4988.9  373.23  5000.5  374.19  5006.7  375.12
  5042.7  374.93  5101.6  375.24  5140.1  376.90  5196.5  381.41  5249.2  387.95
  5280.8  392.71  5323.0  401.12  5344.0  404.22  5396.7  408.57  5449.5  408.40
#Mann=5,-1,0
  4514.1    0.05       0  4982.4    0.03       0  4988.9    0.05       0
  5000.5    0.12       0  5042.7    0.05       0
Bank Sta=4899.2,5140.1
Exp/Cntr=0.3,0.1

Type RM Length L Ch R = 1,18760,537,537,537
BEGIN DESCRIPTION:
STEWART BRANCH 29.0
END DESCRIPTION:
XS GIS Cut Line= 3
      2931675.00      6964825.00      2931225.00      6964725.00
      2930775.05      6964774.99
#Sta/Elev= 30
  4560.0  406.67  4601.0  405.58  4621.5  402.87  4627.9  401.04  4633.0  400.67
  4652.2  397.41  4676.5  393.08  4682.9  391.40  4713.7  387.14  4720.1  385.72
  4768.7  380.04  4830.8  375.13  4867.3  372.47  4904.5  372.84  4909.6  372.29
  4923.8  372.13  4993.3  371.86  4993.8  371.06  4999.4  371.06  4999.9  371.86
  5023.5  372.35  5064.4  375.13  5096.1  378.31  5151.8  386.20  5161.8  386.51
  5302.7  397.50  5312.8  398.98  5353.0  401.66  5393.3  405.80  5473.7  406.76
#Mann=5,-1,0
  4560.0    0.05       0  4923.8    0.16       0  4993.3    0.07       0
  4999.9    0.16       0  5096.1    0.05       0
Bank Sta=4830.8,5064.4
Exp/Cntr=0.3,0.1

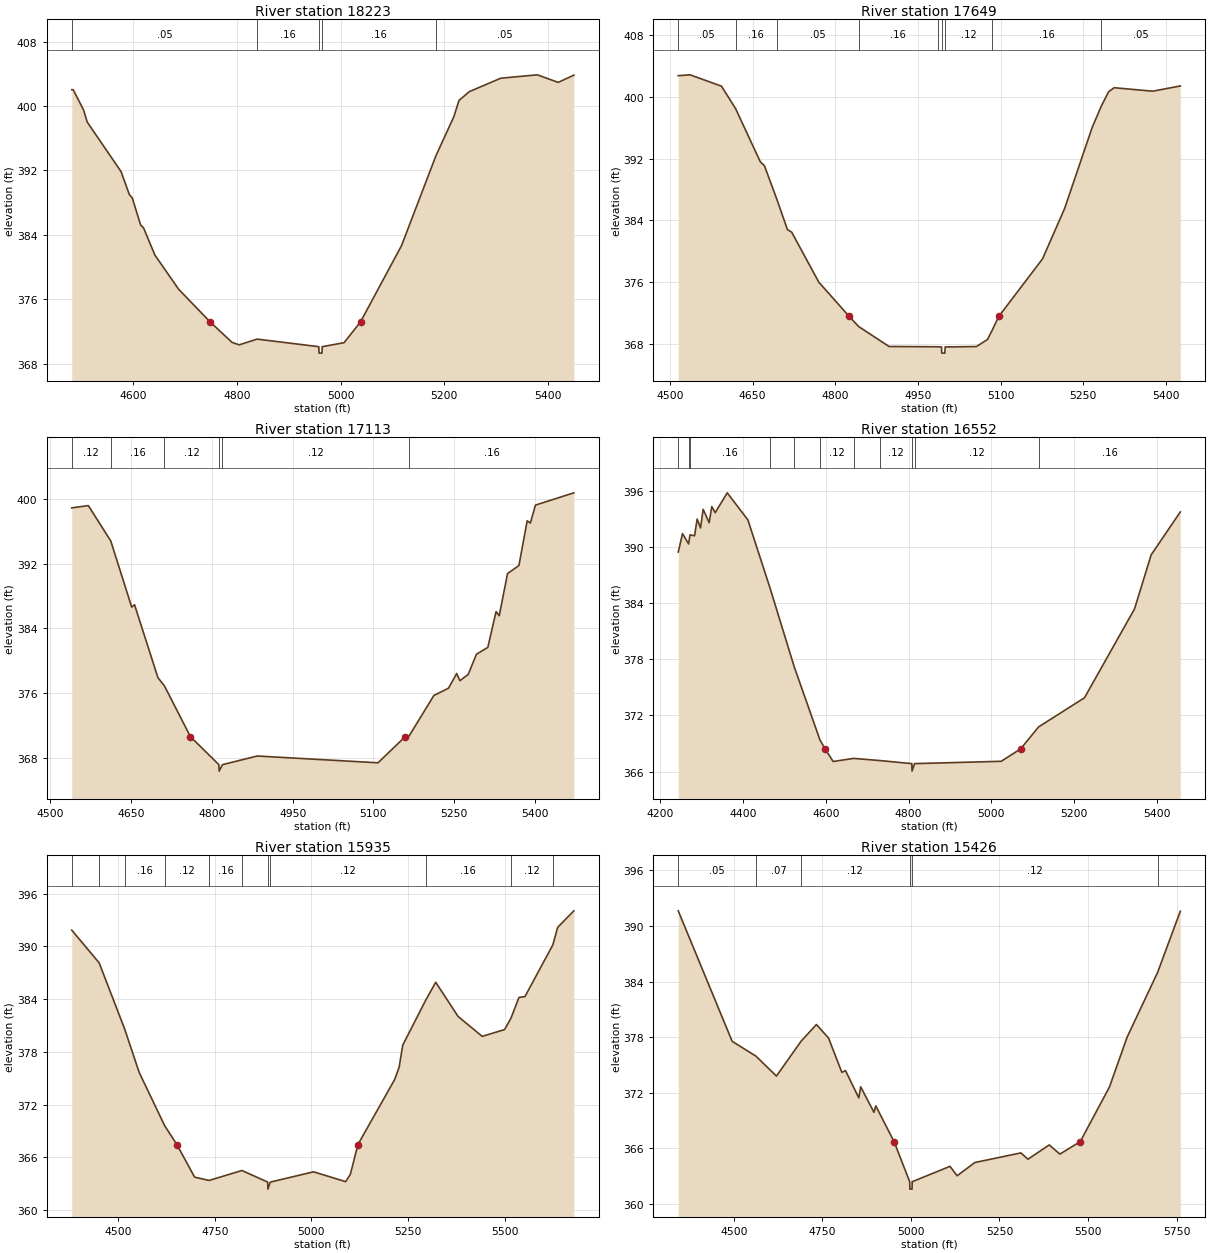
Type RM Length L Ch R = 1,18223,574,574,574
BEGIN DESCRIPTION:
STEWART BRANCH 28.0
END DESCRIPTION:
XS GIS Cut Line= 3
      2931824.99      6964474.99      2931375.00      6964225.00
      2930925.03      6964175.00
#Sta/Elev= 30
  4482.1  402.03  4484.9  402.03  4505.0  399.49  4511.8  398.02  4577.0  391.87
  4593.0  389.02  4598.8  388.57  4614.8  385.23  4620.5  384.86  4642.2  381.50
  4688.0  377.25  4748.7  373.19  4791.0  370.64  4804.7  370.34  4839.2  371.05
  4958.1  370.11  4958.6  369.31  4964.2  369.31  4964.7  370.11  5006.9  370.61
  5038.5  373.19  5117.6  382.67  5183.9  393.84  5218.2  398.65  5228.3  400.70
  5248.4  401.80  5308.8  403.46  5379.2  403.88  5419.5  402.94  5449.6  403.84
#Mann=5,-1,0
  4482.1    0.05       0  4839.2    0.16       0  4958.1    0.07       0
  4964.7    0.16       0  5183.9    0.05       0
Bank Sta=4748.7,5038.5
Exp/Cntr=0.3,0.1

Type RM Length L Ch R = 1,17649,536,536,536
BEGIN DESCRIPTION:
STEWART BRANCH 27.0
END DESCRIPTION:
XS GIS Cut Line= 3
      2932075.03      6964175.04      2931775.00      6963825.00
      2931325.02      6963825.00
#Sta/Elev= 30
  4515.0  402.73  4536.5  402.84  4593.5  401.37  4619.2  398.45  4663.8  391.60
  4671.5  391.06  4694.1  386.70  4713.2  382.80  4720.8  382.48  4770.2  375.99
  4825.3  371.57  4842.2  370.27  4897.5  367.68  4985.6  367.64  4992.7  367.62
  4993.2  366.82  4998.8  366.82  4999.3  367.62  5056.0  367.67  5076.0  368.58
  5084.7  369.79  5096.6  371.57  5176.0  379.02  5216.0  385.52  5266.0  396.01
  5282.7  398.80  5296.0  400.66  5306.0  401.17  5376.0  400.72  5426.0  401.40
#Mann=9,-1,0
  4515.0    0.05       0  4619.2    0.16       0  4694.1    0.05       0
  4842.2    0.16       0  4985.6    0.12       0  4992.7    0.07       0
  4999.3    0.12       0  5084.7    0.16       0  5282.7    0.05       0
Bank Sta=4825.3,5096.6
Exp/Cntr=0.3,0.1

Type RM Length L Ch R = 1,17113,561,561,561
BEGIN DESCRIPTION:
STEWART BRANCH 26.0
END DESCRIPTION:
XS GIS Cut Line= 3
      2932325.03      6963425.01      2931875.00      6963325.00
      2931475.01      6963575.00
#Sta/Elev= 30
  4539.6  398.90  4570.4  399.18  4612.0  394.81  4651.0  386.62  4656.2  386.92
  4699.7  377.89  4711.8  376.87  4760.1  370.59  4812.9  367.13  4813.4  366.33
  4819.5  367.13  4884.1  368.20  5108.5  367.36  5159.0  370.59  5166.1  370.66
  5212.3  375.69  5239.4  376.59  5254.7  378.41  5260.6  377.52  5276.0  378.29
  5291.3  380.78  5312.5  381.64  5327.8  386.06  5333.7  385.55  5349.1  390.77
  5370.3  391.77  5385.6  397.30  5391.5  397.02  5401.0  399.24  5472.3  400.76
#Mann=6,-1,0
  4539.6    0.12       0  4612.0    0.16       0  4711.8    0.12       0
  4812.9    0.07       0  4819.5    0.12       0  5166.1    0.16       0
Bank Sta=4760.1,5159
Exp/Cntr=0.3,0.1

Type RM Length L Ch R = 1,16552,617,617,617
BEGIN DESCRIPTION:
STEWART BRANCH 25.0
END DESCRIPTION:
XS GIS Cut Line= 3
      2932385.47      6963379.20      2931925.00      6962775.00
      2931475.04      6962725.00
#Sta/Elev= 30
  4243.9  389.45  4254.2  391.42  4269.0  390.32  4272.3  391.29  4283.3  391.19
  4289.6  392.98  4297.8  392.03  4304.1  394.02  4318.6  392.59  4324.9  394.31
  4333.2  393.66  4362.2  395.78  4412.1  392.89  4465.2  385.66  4524.2  377.16
  4586.1  369.38  4598.6  368.41  4618.0  367.07  4667.5  367.40  4730.7  367.17
  4808.0  366.84  4808.5  366.04  4814.6  366.84  5023.7  367.09  5070.6  368.41
  5114.0  370.76  5224.9  373.88  5345.7  383.37  5385.9  389.15  5456.3  393.74
#Mann=11,-1,0
  4243.9    0.16       0  4269.0    0.12       0  4272.3    0.16       0
  4465.2    0.12       0  4524.2    0.16       0  4586.1    0.12       0
  4667.5    0.16       0  4730.7    0.12       0  4808.0    0.07       0
  4814.6    0.12       0  5114.0    0.16       0
Bank Sta=4598.6,5070.6
Exp/Cntr=0.3,0.1

Type RM Length L Ch R = 1,15935,509,509,509
BEGIN DESCRIPTION:
Double STEWART BRANCH 24.0
END DESCRIPTION:
XS GIS Cut Line= 3
      2932525.04      6962325.01      2931872.21      6962174.85
      2931275.03      6962374.99
#Sta/Elev= 30
  4379.6  391.85  4450.5  388.13  4516.4  380.61  4554.1  375.66  4620.0  369.60
  4651.6  367.45  4697.7  363.73  4735.2  363.36  4820.1  364.49  4886.8  363.17
  4887.3  362.37  4893.5  363.17  5005.6  364.34  5088.7  363.22  5100.8  364.06
  5120.4  367.45  5215.3  374.83  5227.1  376.26  5236.4  378.76  5295.3  383.83
  5321.7  385.92  5379.6  382.03  5442.0  379.76  5500.0  380.53  5516.7  381.85
  5537.3  384.19  5552.8  384.29  5625.0  390.18  5637.3  392.16  5679.3  394.05
#Mann=11,-1,0
  4379.6    0.05       0  4450.5    0.12       0  4516.4    0.16       0
  4620.0    0.12       0  4735.2    0.16       0  4820.1    0.12       0
  4886.8    0.07       0  4893.5    0.12       0  5295.3    0.16       0
  5516.7    0.12       0  5625.0    0.16       0
Bank Sta=4651.6,5120.4
Exp/Cntr=0.3,0.1

Type RM Length L Ch R = 1,15426,557,557,557
BEGIN DESCRIPTION:
STEWART BRANCH 23.0
END DESCRIPTION:
XS GIS Cut Line= 3
      2932525.01      6961575.00      2931875.00      6961725.00
      2931124.99      6961725.00
#Sta/Elev= 30
  4343.3  391.64  4495.5  377.56  4562.6  375.96  4620.4  373.81  4689.9  377.56
  4733.3  379.37  4767.5  377.92  4805.1  374.21  4815.4  374.40  4853.0  371.45
  4858.2  372.65  4895.8  369.90  4900.9  370.59  4952.6  366.73  4996.6  362.41
  4997.1  361.61  5003.2  361.61  5003.7  362.41  5110.4  364.07  5130.4  363.05
  5180.4  364.48  5310.4  365.52  5330.4  364.84  5390.4  366.38  5420.4  365.39
  5477.9  366.73  5560.4  372.63  5610.4  378.02  5696.1  384.97  5760.4  391.60
#Mann=6,-1,0
  4343.3    0.05       0  4562.6    0.07       0  4689.9    0.12       0
  4996.6    0.07       0  5003.7    0.12       0  5696.1    0.16       0
Bank Sta=4952.6,5477.9
Exp/Cntr=0.3,0.1

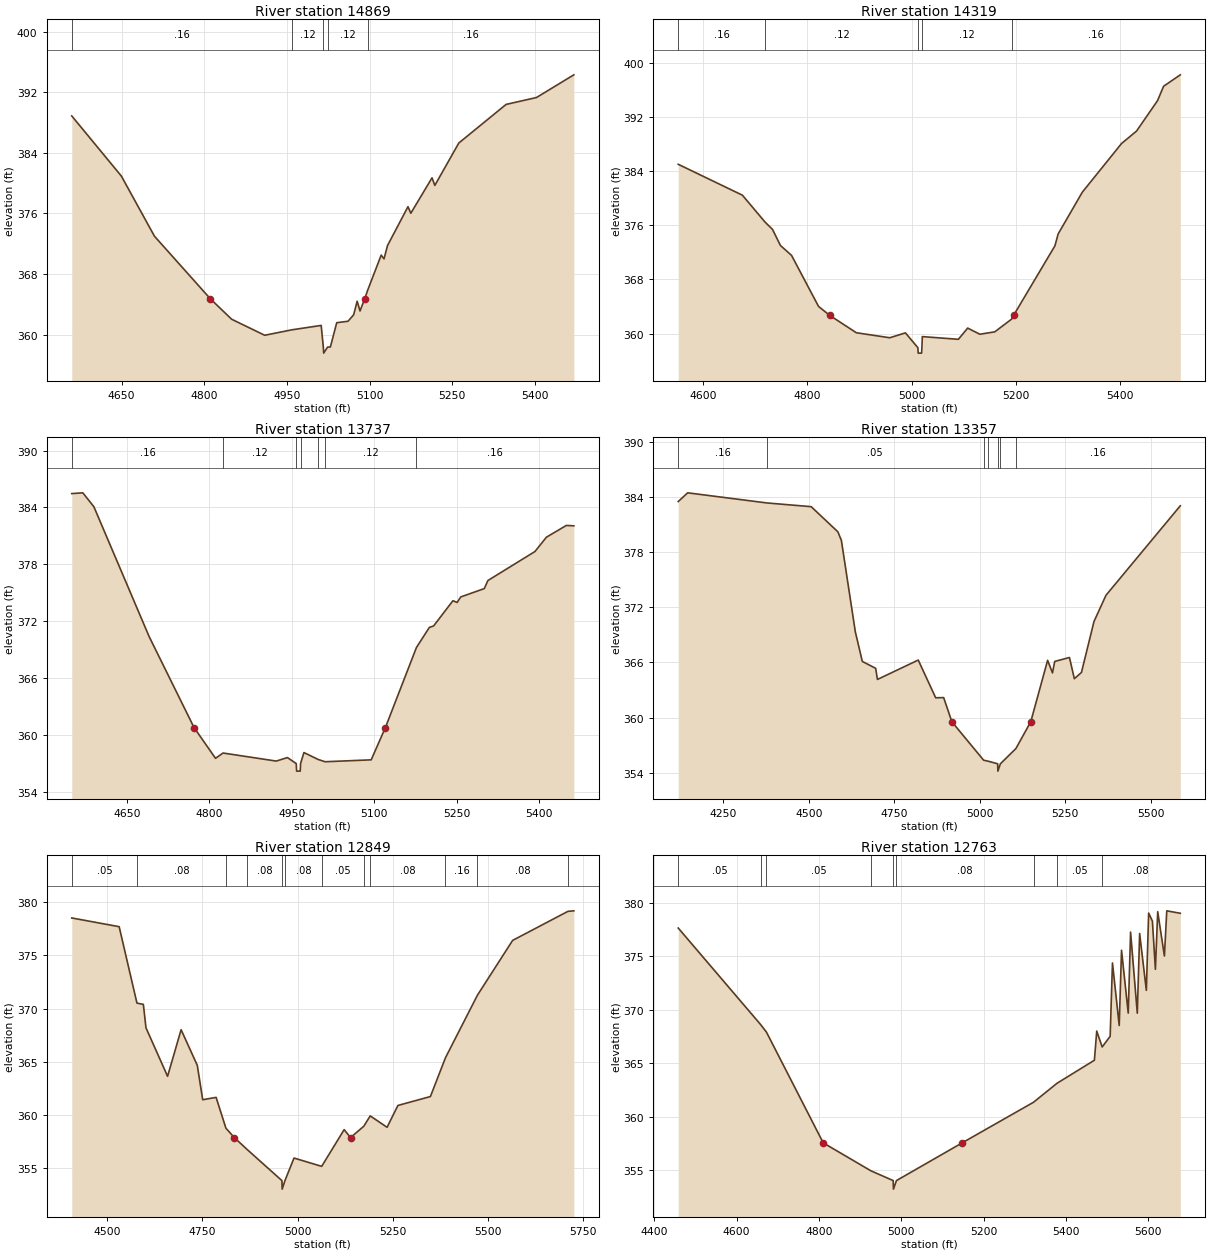
Type RM Length L Ch R = 1,14869,550,550,550
BEGIN DESCRIPTION:
STEWART BRANCH 22.0
END DESCRIPTION:
XS GIS Cut Line= 3
      2932324.97      6961175.00      2931875.00      6961175.00
      2931425.04      6961075.01
#Sta/Elev= 30
  4559.5  388.88  4649.5  380.93  4709.5  372.99  4810.9  364.72  4849.5  362.02
  4909.5  359.90  4958.9  360.62  5012.0  361.20  5015.9  358.34  5016.5  357.54
  5023.6  358.34  5028.7  358.35  5040.2  361.56  5060.7  361.75  5070.9  362.60
  5077.3  364.40  5082.5  363.11  5091.0  364.72  5096.4  365.86  5120.9  370.49
  5126.0  369.99  5132.4  371.76  5169.5  376.89  5174.6  376.02  5213.1  380.70
  5218.2  379.70  5261.7  385.30  5347.5  390.40  5402.6  391.31  5470.4  394.31
#Mann=5,-1,0
  4559.5    0.16       0  4958.9    0.12       0  5015.9    0.07       0
  5023.6    0.12       0  5096.4    0.16       0
Bank Sta=4810.9,5091
Exp/Cntr=0.3,0.1

Type RM Length L Ch R = 1,14319,582,582,582
BEGIN DESCRIPTION:
STEWART BRANCH 21.0
END DESCRIPTION:
XS GIS Cut Line= 3
      2932174.99      6960874.99      2931775.00      6960625.00
      2931325.03      6960824.99
#Sta/Elev= 30
  4552.0  384.99  4675.2  380.43  4718.8  376.45  4733.0  375.38  4748.3  373.00
  4769.6  371.54  4821.4  364.01  4842.6  362.70  4894.0  360.12  4958.2  359.38
  4988.3  360.10  5012.2  357.91  5012.8  357.11  5019.3  357.11  5019.9  357.91
  5020.7  359.55  5090.0  359.15  5107.8  360.81  5131.1  359.90  5159.8  360.25
  5192.3  362.14  5196.1  362.70  5275.4  372.96  5281.5  374.70  5328.0  380.88
  5403.3  388.06  5432.0  389.89  5472.4  394.39  5484.0  396.51  5516.1  398.20
#Mann=5,-1,0
  4552.0    0.16       0  4718.8    0.12       0  5012.2    0.07       0
  5019.9    0.12       0  5192.3    0.16       0
Bank Sta=4842.6,5196.1
Exp/Cntr=0.3,0.1

Type RM Length L Ch R = 1,13737,380,380,380
BEGIN DESCRIPTION:
STEWART BRANCH 20.0
END DESCRIPTION:
XS GIS Cut Line= 3
      2932274.96      6960125.00      2931825.00      6960075.00
      2931475.01      6960374.99
#Sta/Elev= 30
  4549.7  385.46  4569.8  385.54  4589.9  384.08  4690.5  370.38  4772.2  360.79
  4811.3  357.54  4825.0  358.10  4921.9  357.25  4942.1  357.62  4958.2  356.99
  4958.9  356.19  4965.5  356.19  4966.1  356.99  4972.2  358.15  4998.1  357.42
  5010.7  357.18  5094.6  357.38  5120.5  360.79  5176.9  369.22  5200.5  371.35
  5208.2  371.50  5243.3  374.16  5251.0  373.98  5257.6  374.56  5300.4  375.44
  5307.0  376.29  5392.6  379.35  5413.5  380.86  5449.7  382.10  5463.4  382.06
#Mann=7,-1,0
  4549.7    0.16       0  4825.0    0.12       0  4958.2    0.07       0
  4966.1    0.12       0  4998.1    0.07       0  5010.7    0.12       0
  5176.9    0.16       0
Bank Sta=4772.2,5120.5
Exp/Cntr=0.3,0.1

Type RM Length L Ch R = 1,13357,508,508,508
BEGIN DESCRIPTION:
Mapping XS 8dc36ce8
END DESCRIPTION:
XS GIS Cut Line= 3
      2932512.06      6959579.79      2931723.85      6959746.46
      2931303.85      6960260.18
#Sta/Elev= 30
  4117.9  383.53  4145.6  384.48  4376.8  383.38  4507.0  382.97  4585.1  380.23
  4595.3  379.30  4636.2  369.32  4656.6  366.11  4695.7  365.36  4700.8  364.15
  4820.2  366.26  4871.3  362.15  4894.6  362.17  4918.6  359.54  5011.6  355.35
  5024.9  355.24  5052.6  354.96  5053.3  354.16  5060.6  354.96  5106.0  356.62
  5149.5  359.54  5198.8  366.23  5213.1  364.86  5219.6  366.11  5262.7  366.54
  5277.0  364.23  5297.8  364.91  5334.5  370.46  5369.6  373.32  5587.1  383.07
#Mann=7,-1,0
  4117.9    0.16       0  4376.8    0.05       0  5011.6    0.07       0
  5024.9    0.12       0  5052.6    0.04       0  5060.6    0.12       0
  5106.0    0.16       0
Bank Sta=4918.6,5149.5
Exp/Cntr=0.3,0.1

Type RM Length L Ch R = 1,12849,86,86,86
BEGIN DESCRIPTION:
Mapping XS 23f07b47
END DESCRIPTION:
XS GIS Cut Line= 4
      2931869.67      6958933.97      2931470.37      6959354.10
      2931393.99      6959479.10      2931140.49      6960013.86
#Sta/Elev= 30
  4407.3  378.52  4531.7  377.70  4578.4  370.52  4595.2  370.40  4602.1  368.20
  4658.8  363.64  4694.3  368.02  4736.8  364.67  4751.0  361.44  4786.2  361.66
  4811.9  358.77  4834.0  357.88  4867.2  356.78  4958.9  353.84  4959.6  353.04
  4966.9  353.84  4990.7  355.96  5063.3  355.18  5122.3  358.63  5139.1  357.88
  5174.1  358.96  5190.7  359.92  5235.0  358.85  5263.3  360.90  5348.7  361.74
  5388.3  365.39  5472.1  371.26  5564.5  376.41  5709.7  379.14  5725.2  379.19
#Mann=12,-1,0
  4407.3    0.05       0  4578.4    0.08       0  4811.9    0.16       0
  4867.2    0.08       0  4958.9    0.07       0  4966.9    0.08       0
  5063.3    0.05       0  5174.1    0.12       0  5190.7    0.08       0
  5388.3    0.16       0  5472.1    0.08       0  5709.7    0.05       0
Bank Sta=4834,5139.1
Exp/Cntr=0.3,0.1

Type RM Length L Ch R = 1,12763,603,603,603
BEGIN DESCRIPTION:
Mapping XS 057799ff
END DESCRIPTION:
XS GIS Cut Line= 5
      2931772.47      6958864.50      2931584.96      6959055.49
      2931442.60      6959274.24      2931334.96      6959437.43
      2931102.34      6959874.89
#Sta/Elev= 30
  4458.1  377.66  4658.2  368.63  4672.4  367.92  4810.3  357.56  4926.3  354.94
  4980.2  354.03  4980.9  353.23  4988.2  354.03  5147.8  357.56  5321.2  361.36
  5378.4  363.14  5469.0  365.29  5474.7  368.02  5487.9  366.53  5507.3  367.53
  5512.9  374.39  5529.3  368.54  5534.9  375.58  5551.2  369.70  5556.9  377.28
  5573.2  369.69  5578.9  377.15  5595.2  371.83  5600.8  379.06  5609.9  378.31
  5617.2  373.80  5622.8  379.19  5639.1  375.04  5644.8  379.27  5677.7  379.04
#Mann=9,-1,0
  4458.1    0.05       0  4658.2    0.08       0  4672.4    0.05       0
  4926.3    0.08       0  4980.2    0.07       0  4988.2    0.08       0
  5321.2    0.16       0  5378.4    0.05       0  5487.9    0.08       0
Bank Sta=4810.3,5147.8
Exp/Cntr=0.3,0.1

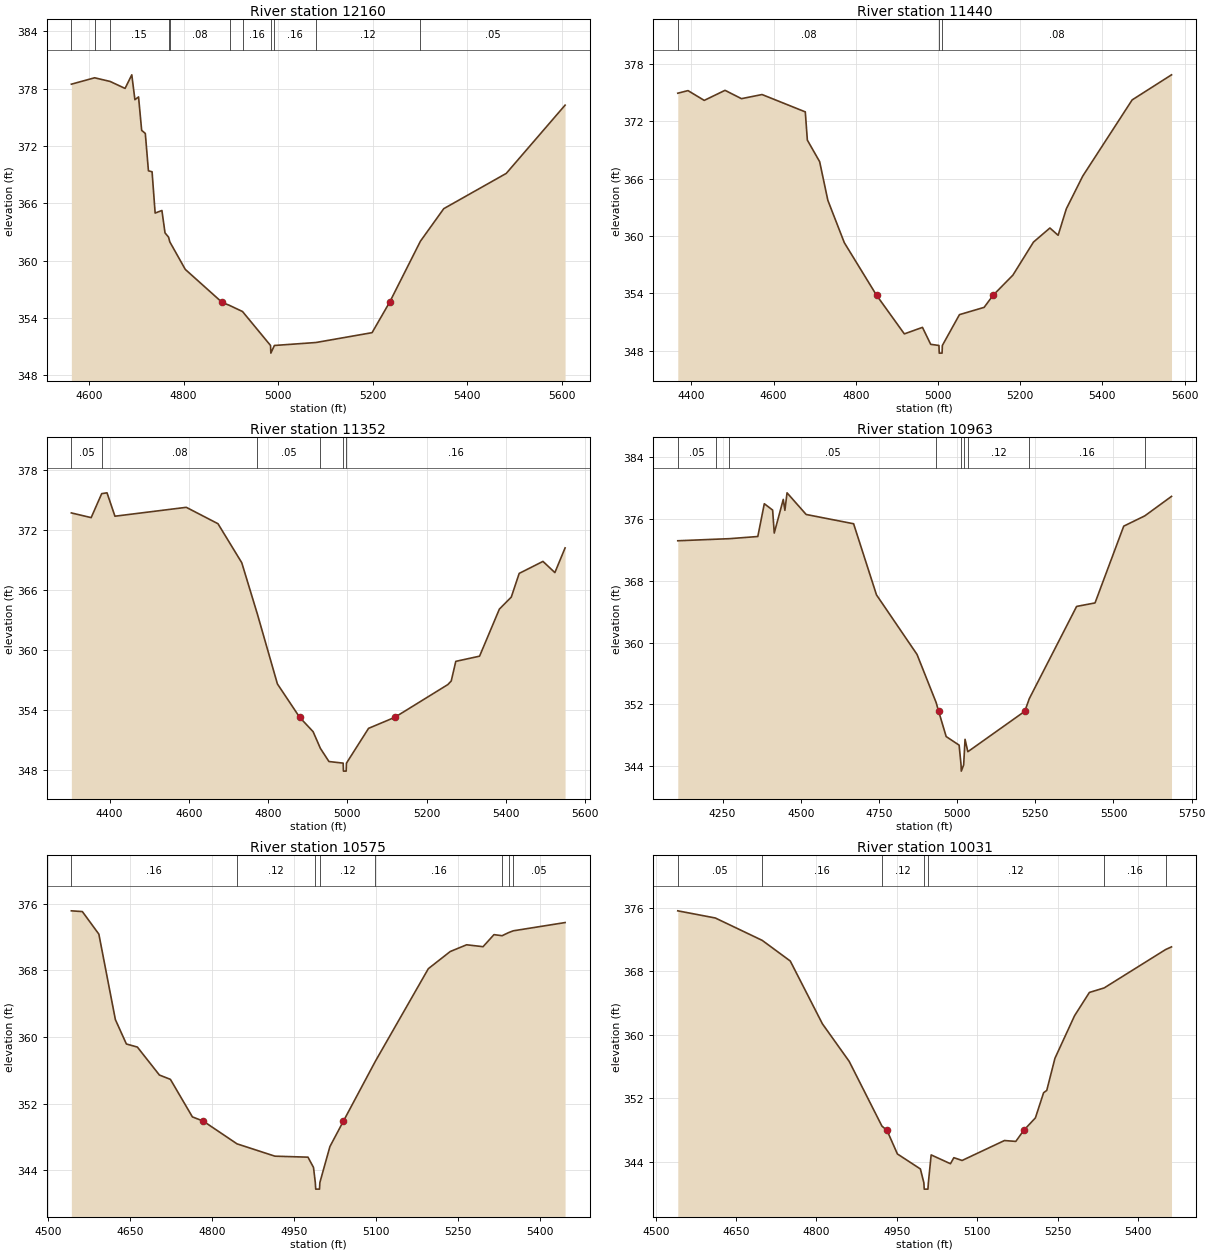
Type RM Length L Ch R = 1,12160,720,720,720
BEGIN DESCRIPTION:
STEWART BRANCH 17.0
END DESCRIPTION:
XS GIS Cut Line= 3
      2931424.99      6958475.01      2931125.00      6958825.00
      2930624.96      6959125.02
#Sta/Elev= 30
  4562.8  378.47  4612.0  379.14  4644.6  378.76  4676.4  378.03  4690.6  379.45
  4697.2  376.85  4704.9  377.14  4711.5  373.64  4719.2  373.32  4725.8  369.41
  4733.5  369.31  4740.0  364.99  4754.3  365.26  4760.9  362.92  4768.4  362.47
  4771.0  361.98  4803.7  359.10  4881.3  355.66  4897.4  355.33  4924.8  354.69
  4984.0  351.14  4984.7  350.34  4992.2  351.14  5080.0  351.45  5198.7  352.48
  5235.8  355.66  5300.9  362.04  5350.3  365.45  5482.5  369.14  5606.9  376.28
#Mann=11,-1,0
  4562.8    0.08       0  4612.0     0.1       0  4644.6    0.15       0
  4768.4    0.07       0  4771.0    0.08       0  4897.4    0.05       0
  4924.8    0.16       0  4984.0    0.07       0  4992.2    0.16       0
  5080.0    0.12       0  5300.9    0.05       0
Bank Sta=4881.3,5235.8
Exp/Cntr=0.3,0.1

Type RM Length L Ch R = 1,11440,88,88,88
BEGIN DESCRIPTION:
Mapping XS 9b47c437
END DESCRIPTION:
XS GIS Cut Line= 3
      2931289.86      6958322.85      2930703.01      6958298.54
      2930089.21      6958315.88
#Sta/Elev= 30
  4366.9  374.91  4391.8  375.18  4431.3  374.16  4481.9  375.21  4521.9  374.34
  4571.9  374.77  4677.2  372.96  4682.2  370.01  4712.1  367.76  4732.1  363.72
  4772.1  359.30  4850.5  353.81  4918.2  349.77  4962.3  350.45  4982.3  348.68
  5002.4  348.56  5003.1  347.76  5010.0  347.76  5010.7  348.56  5052.3  351.78
  5112.3  352.54  5134.3  353.81  5182.4  355.91  5232.4  359.36  5272.4  360.83
  5292.4  360.07  5312.4  362.84  5352.4  366.26  5472.5  374.21  5568.3  376.83
#Mann=3,-1,0
  4366.9    0.08       0  5002.4    0.07       0  5010.7    0.08       0
Bank Sta=4850.5,5134.3
Exp/Cntr=0.3,0.1

Type RM Length L Ch R = 1,11352,389,389,389
BEGIN DESCRIPTION:
Mapping XS d44052eb
END DESCRIPTION:
XS GIS Cut Line= 3
      2931335.00      6958222.16      2930657.87      6958215.21
      2930089.23      6958204.81
#Sta/Elev= 30
  4303.5  373.69  4353.5  373.22  4380.1  375.62  4393.5  375.70  4413.5  373.36
  4593.5  374.25  4673.5  372.61  4733.5  368.71  4772.7  363.60  4823.5  356.58
  4879.7  353.24  4913.5  351.81  4931.9  350.14  4953.5  348.82  4989.4  348.66
  4990.1  347.86  4997.0  347.86  4997.7  348.66  5053.5  352.14  5119.6  353.24
  5253.6  356.52  5262.1  356.88  5273.6  358.84  5333.6  359.36  5383.6  364.07
  5413.6  365.27  5433.6  367.64  5493.6  368.84  5523.6  367.72  5549.4  370.19
#Mann=6,-1,0
  4303.5    0.05       0  4380.1    0.08       0  4772.7    0.05       0
  4931.9    0.16       0  4989.4    0.07       0  4997.7    0.16       0
Bank Sta=4879.7,5119.6
Exp/Cntr=0.3,0.1

Type RM Length L Ch R = 1,10963,388,388,388
BEGIN DESCRIPTION:
Mapping XS 9eaa3b05
END DESCRIPTION:
XS GIS Cut Line= 3
      2931411.32      6958062.43      2930647.46      6957847.15
      2929888.54      6958048.15
#Sta/Elev= 30
  4106.9  373.16  4228.3  373.36  4271.7  373.43  4362.8  373.71  4383.6  377.95
  4410.2  377.13  4415.4  374.16  4444.2  378.51  4449.4  377.10  4456.3  379.36
  4517.4  376.56  4669.1  375.36  4742.3  366.16  4871.9  358.46  4933.1  352.23
  4941.0  351.11  4965.1  347.84  5006.5  346.73  5012.7  344.17  5013.4  343.37
  5021.0  344.17  5025.4  347.48  5034.4  345.88  5216.5  351.11  5230.7  352.73
  5382.2  364.67  5441.0  365.12  5532.8  375.05  5600.1  376.38  5685.6  378.90
#Mann=9,-1,0
  4106.9    0.05       0  4228.3    0.16       0  4271.7    0.05       0
  4933.1    0.16       0  5012.7    0.07       0  5021.0    0.16       0
  5034.4    0.12       0  5230.7    0.16       0  5600.1    0.05       0
Bank Sta=4941,5216.5
Exp/Cntr=0.3,0.1

Type RM Length L Ch R = 1,10575,544,544,544
BEGIN DESCRIPTION:
STEWART BRANCH 14.0
END DESCRIPTION:
XS GIS Cut Line= 3
      2930924.97      6957475.00      2930475.00      6957525.00
      2930025.04      6957525.00
#Sta/Elev= 30
  4542.6  375.17  4562.7  375.08  4592.9  372.37  4623.1  362.10  4643.2  359.17
  4663.3  358.80  4703.6  355.44  4723.7  354.92  4763.9  350.41  4783.8  349.90
  4845.5  347.17  4914.8  345.69  4975.2  345.57  4985.3  344.34  4988.6  342.53
  4989.4  341.73  4996.3  341.73  4997.0  342.53  5015.3  346.84  5040.0  349.90
  5098.3  357.08  5195.3  368.22  5235.3  370.28  5265.3  371.09  5295.3  370.86
  5315.3  372.31  5330.2  372.18  5341.9  372.55  5350.7  372.77  5445.3  373.76
#Mann=8,-1,0
  4542.6    0.16       0  4845.5    0.12       0  4988.6    0.07       0
  4997.0    0.12       0  5098.3    0.16       0  5330.2    0.12       0
  5341.9    0.16       0  5350.7    0.05       0
Bank Sta=4783.8,5040
Exp/Cntr=0.3,0.1

Type RM Length L Ch R = 1,10031,555,555,555
BEGIN DESCRIPTION:
STEWART BRANCH 13.0
END DESCRIPTION:
XS GIS Cut Line= 3
      2930975.00      6957025.00      2930525.00      6957025.00
      2930125.00      6957275.00
#Sta/Elev= 30
  4541.1  375.61  4611.1  374.71  4698.7  371.89  4751.1  369.29  4811.1  361.38
  4861.1  356.65  4922.2  348.50  4931.6  347.97  4951.1  344.99  4994.0  343.10
  5000.5  341.36  5001.2  340.56  5008.1  340.56  5008.9  341.36  5014.1  344.87
  5050.1  343.76  5056.5  344.52  5071.9  344.17  5150.9  346.68  5172.1  346.57
  5187.0  347.97  5208.7  349.53  5224.0  352.70  5229.9  352.99  5245.2  357.04
  5281.8  362.40  5309.5  365.33  5337.1  365.90  5451.7  370.73  5462.8  371.07
#Mann=7,-1,0
  4541.1    0.05       0  4698.7    0.16       0  4922.2    0.12       0
  5000.5    0.07       0  5008.9    0.12       0  5337.1    0.16       0
  5451.7    0.12       0
Bank Sta=4931.6,5187
Exp/Cntr=0.3,0.1