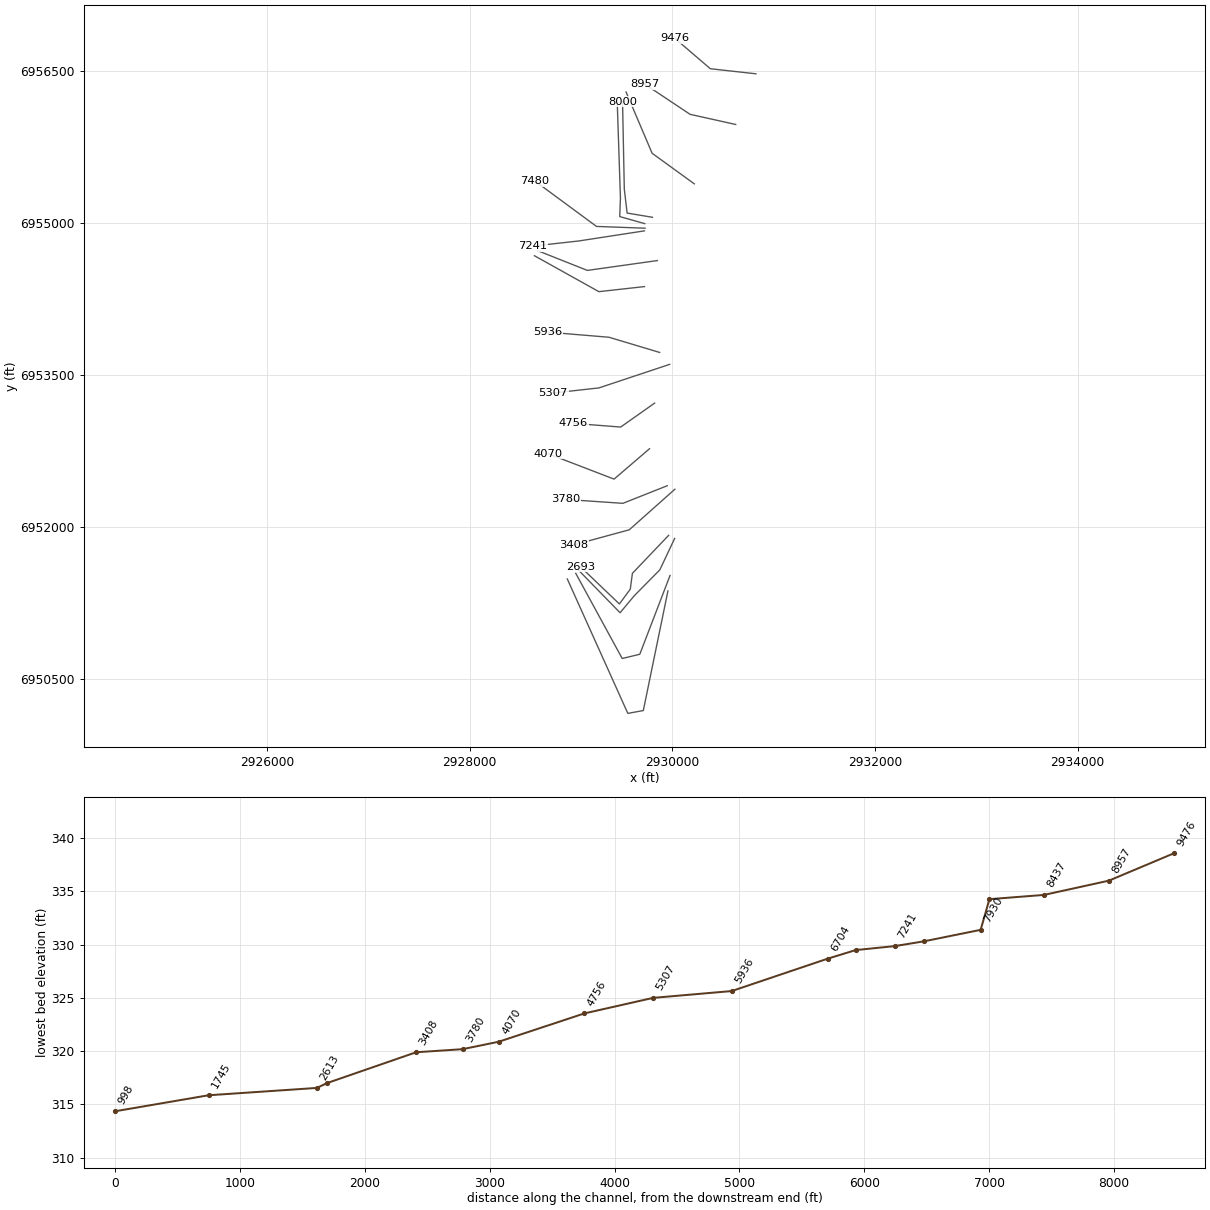
HEC-RAS study STEWART BRANCH.prj: STEWART BRANCH Base Level Engineering

--- STEWART BRANCH.g01 (geometry) --- (continued)

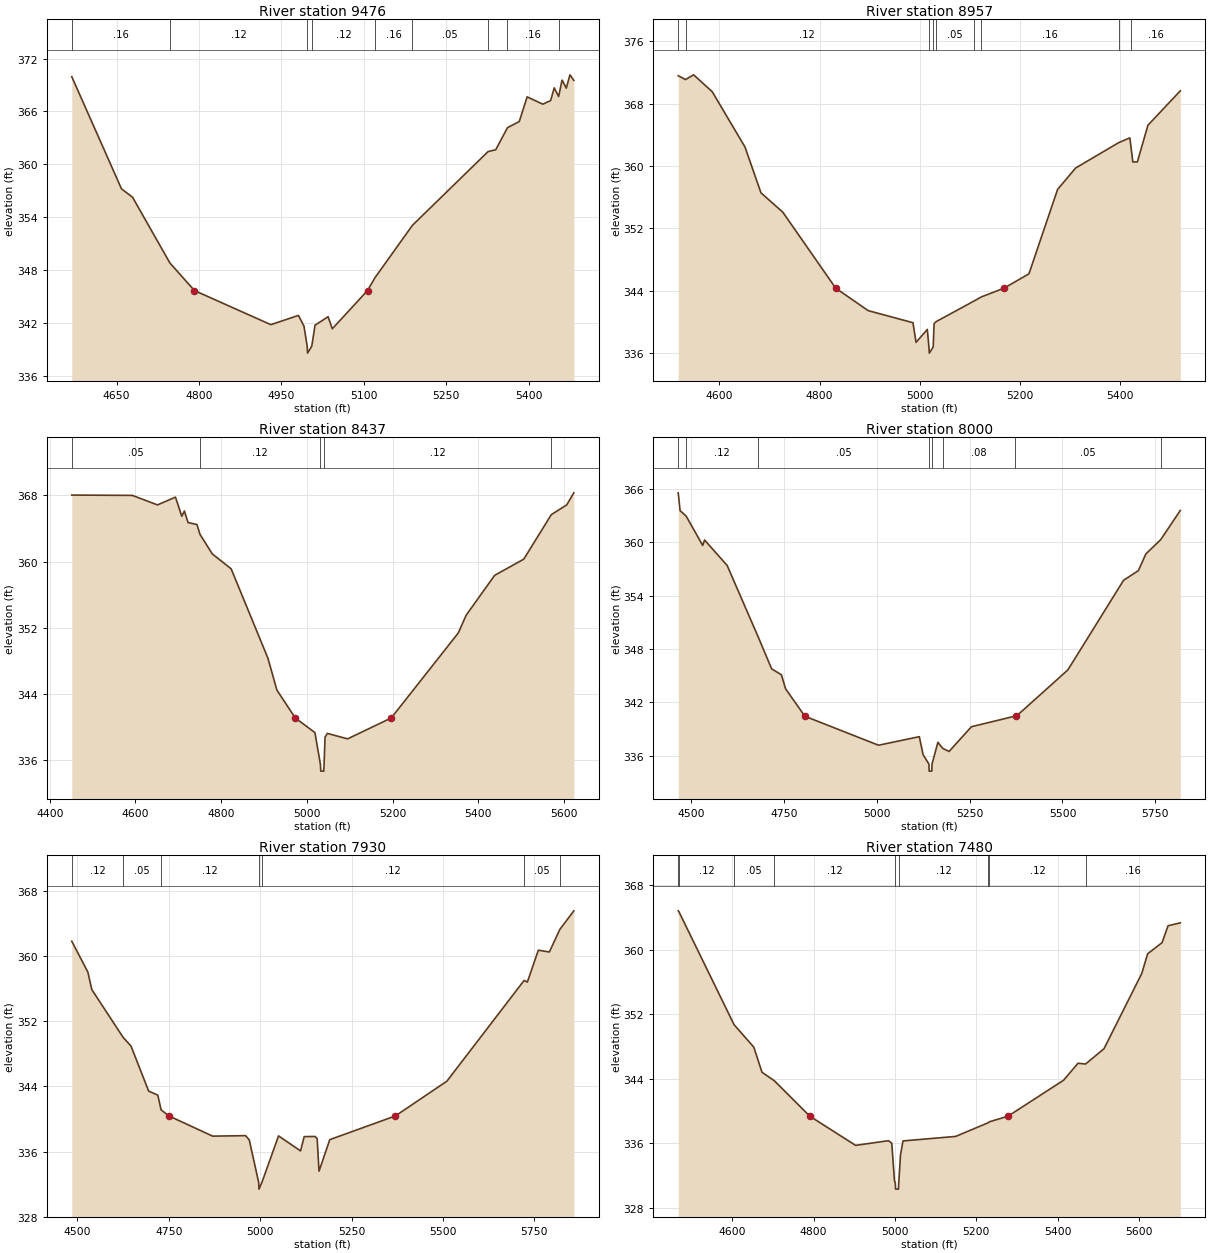
Type RM Length L Ch R = 1,9476,519,519,519
BEGIN DESCRIPTION:
STEWART BRANCH 12.0
END DESCRIPTION:
XS GIS Cut Line= 3
      2930824.97      6956475.00      2930375.00      6956525.00
      2930025.01      6956824.99
#Sta/Elev= 30
  4568.5  369.94  4659.0  357.21  4679.1  356.26  4747.2  348.79  4791.8  345.67
  4930.7  341.80  4981.0  342.85  4991.1  341.63  4996.9  339.37  4997.6  338.57
  5005.3  339.37  5011.2  341.74  5035.0  342.70  5042.6  341.33  5106.7  345.67
  5120.3  347.13  5188.4  353.07  5326.1  361.44  5340.1  361.65  5361.4  364.15
  5382.9  364.85  5397.2  367.65  5425.7  366.82  5440.0  367.23  5446.5  368.67
  5454.5  367.69  5460.8  369.55  5468.5  368.64  5475.1  370.15  5482.2  369.52
#Mann=9,-1,0
  4568.5    0.16       0  4747.2    0.12       0  4996.9    0.07       0
  5005.3    0.12       0  5120.3    0.16       0  5188.4    0.05       0
  5326.1    0.08       0  5361.4    0.16       0  5454.5    0.05       0
Bank Sta=4791.8,5106.7
Exp/Cntr=0.3,0.1

Type RM Length L Ch R = 1,8957,520,520,520
BEGIN DESCRIPTION:
STEWART BRANCH 11.0
END DESCRIPTION:
XS GIS Cut Line= 3
      2930624.95      6955975.01      2930175.00      6956075.00
      2929724.97      6956375.02
#Sta/Elev= 30
  4518.0  371.58  4532.5  371.08  4548.7  371.69  4585.8  369.53  4651.1  362.45
  4683.1  356.56  4726.7  354.08  4832.2  344.34  4897.0  341.46  4986.4  339.91
  4992.5  337.39  5015.0  339.05  5018.2  336.81  5019.0  336.01  5026.7  336.81
  5028.5  339.79  5032.9  340.06  5108.8  342.71  5122.9  343.22  5168.1  344.34
  5217.8  346.18  5274.9  356.99  5310.9  359.74  5396.7  362.99  5419.1  363.61
  5422.3  361.96  5425.1  360.52  5434.1  360.52  5455.2  365.23  5519.8  369.64
#Mann=9,-1,0
  4518.0    0.05       0  4532.5    0.12       0  5018.2    0.07       0
  5026.7    0.12       0  5032.9    0.05       0  5108.8    0.12       0
  5122.9    0.16       0  5396.7    0.12       0  5422.3    0.16       0
Bank Sta=4832.2,5168.1
Exp/Cntr=0.3,0.1

Type RM Length L Ch R = 1,8437,437,437,437
BEGIN DESCRIPTION:
Mapping XS 0736394e
END DESCRIPTION:
XS GIS Cut Line= 3
      2930216.90      6955388.82      2929800.24      6955690.90
      2929543.29      6956295.08
#Sta/Elev= 30
  4451.4  368.05  4592.7  368.01  4651.4  366.86  4693.3  367.80  4708.0  365.49
  4714.1  366.12  4722.7  364.72  4743.5  364.49  4750.4  363.31  4779.1  360.94
  4823.2  359.13  4909.0  348.32  4929.9  344.47  4972.8  341.10  5018.6  339.33
  5031.5  335.47  5032.2  334.67  5039.2  334.67  5040.0  335.47  5042.2  338.78
  5047.7  339.23  5094.9  338.57  5196.7  341.10  5353.1  351.38  5371.3  353.51
  5437.8  358.34  5505.8  360.30  5570.0  365.68  5605.8  366.85  5622.6  368.32
#Mann=5,-1,0
  4451.4    0.05       0  4750.4    0.12       0  5031.5    0.07       0
  5040.0    0.12       0  5570.0    0.08       0
Bank Sta=4972.8,5196.7
Exp/Cntr=0.3,0.1

Type RM Length L Ch R = 1,8000,70,70,70
BEGIN DESCRIPTION:
Mapping XS b8f0e8a8
END DESCRIPTION:
XS GIS Cut Line= 4
      2929803.71      6955058.96      2929553.71      6955100.63
      2929525.93      6955336.74      2929508.57      6956197.88
#Sta/Elev= 30
  4465.0  365.54  4470.0  363.54  4486.3  362.93  4530.9  359.63  4535.9  360.24
  4596.8  357.38  4681.1  349.28  4716.5  345.77  4743.0  345.09  4754.1  343.53
  4806.1  340.44  5004.5  337.18  5114.5  338.14  5124.5  336.13  5140.2  335.07
  5141.0  334.27  5148.0  334.27  5148.7  335.07  5164.5  337.51  5177.7  336.82
  5194.5  336.48  5254.9  339.26  5373.3  340.46  5375.7  340.44  5514.6  345.64
  5664.6  355.71  5704.6  356.80  5724.6  358.67  5764.7  360.28  5817.5  363.56
#Mann=8,-1,0
  4465.0    0.05       0  4486.3    0.12       0  4681.1    0.05       0
  5140.2    0.04       0  5148.7    0.05       0  5177.7    0.08       0
  5373.3    0.05       0  5764.7    0.08       0
Bank Sta=4806.1,5375.7
Exp/Cntr=0.3,0.1

Type RM Length L Ch R = 1,7930,450,450,450
BEGIN DESCRIPTION:
Mapping XS 60d2220a
END DESCRIPTION:
XS GIS Cut Line= 4
      2929727.35      6954996.45      2929480.79      6955065.90
      2929487.74      6955249.93      2929456.55      6956182.00
#Sta/Elev= 30
  4484.9  361.80  4528.9  358.02  4539.7  355.87  4625.6  349.99  4646.9  348.94
  4695.1  343.42  4720.2  342.92  4729.2  341.11  4750.5  340.37  4870.2  337.89
  4960.3  337.95  4970.3  337.43  4996.1  332.19  4996.8  331.39  5004.6  332.19
  5050.3  337.92  5110.4  336.08  5120.4  337.83  5150.4  337.85  5156.0  337.55
  5161.0  333.59  5190.4  337.46  5369.9  340.37  5510.6  344.63  5721.8  356.99
  5730.7  356.79  5760.7  360.70  5790.8  360.48  5819.7  363.26  5857.8  365.53
#Mann=7,-1,0
  4484.9    0.12       0  4625.6    0.05       0  4729.2    0.12       0
  4996.1    0.07       0  5004.6    0.12       0  5721.8    0.05       0
  5819.7    0.16       0
Bank Sta=4750.5,5369.9
Exp/Cntr=0.3,0.1

Type RM Length L Ch R = 1,7480,239,239,239
BEGIN DESCRIPTION:
Mapping XS 818dc7bb
END DESCRIPTION:
XS GIS Cut Line= 3
      2929730.79      6954951.32      2929251.62      6954968.68
      2928643.96      6955416.62
#Sta/Elev= 30
  4467.0  364.85  4468.3  364.78  4604.2  350.73  4652.9  347.93  4672.9  344.82
  4703.4  343.76  4790.5  339.37  4903.1  335.75  4984.1  336.33  4992.0  336.01
  4998.7  331.32  5000.6  331.12  5001.4  330.32  5008.4  330.32  5009.2  331.12
  5013.4  334.54  5019.6  336.30  5149.1  336.86  5228.8  338.55  5231.8  338.67
  5277.8  339.37  5414.4  343.83  5449.9  345.94  5468.5  345.84  5513.8  347.74
  5606.5  357.06  5621.1  359.52  5656.6  360.90  5671.2  363.00  5701.4  363.36
#Mann=9,-1,0
  4467.0    0.05       0  4468.3    0.12       0  4604.2    0.05       0
  4703.4    0.12       0  5000.6    0.07       0  5009.2    0.12       0
  5228.8    0.05       0  5231.8    0.12       0  5468.5    0.16       0
Bank Sta=4790.5,5277.8
Exp/Cntr=0.3,0.1

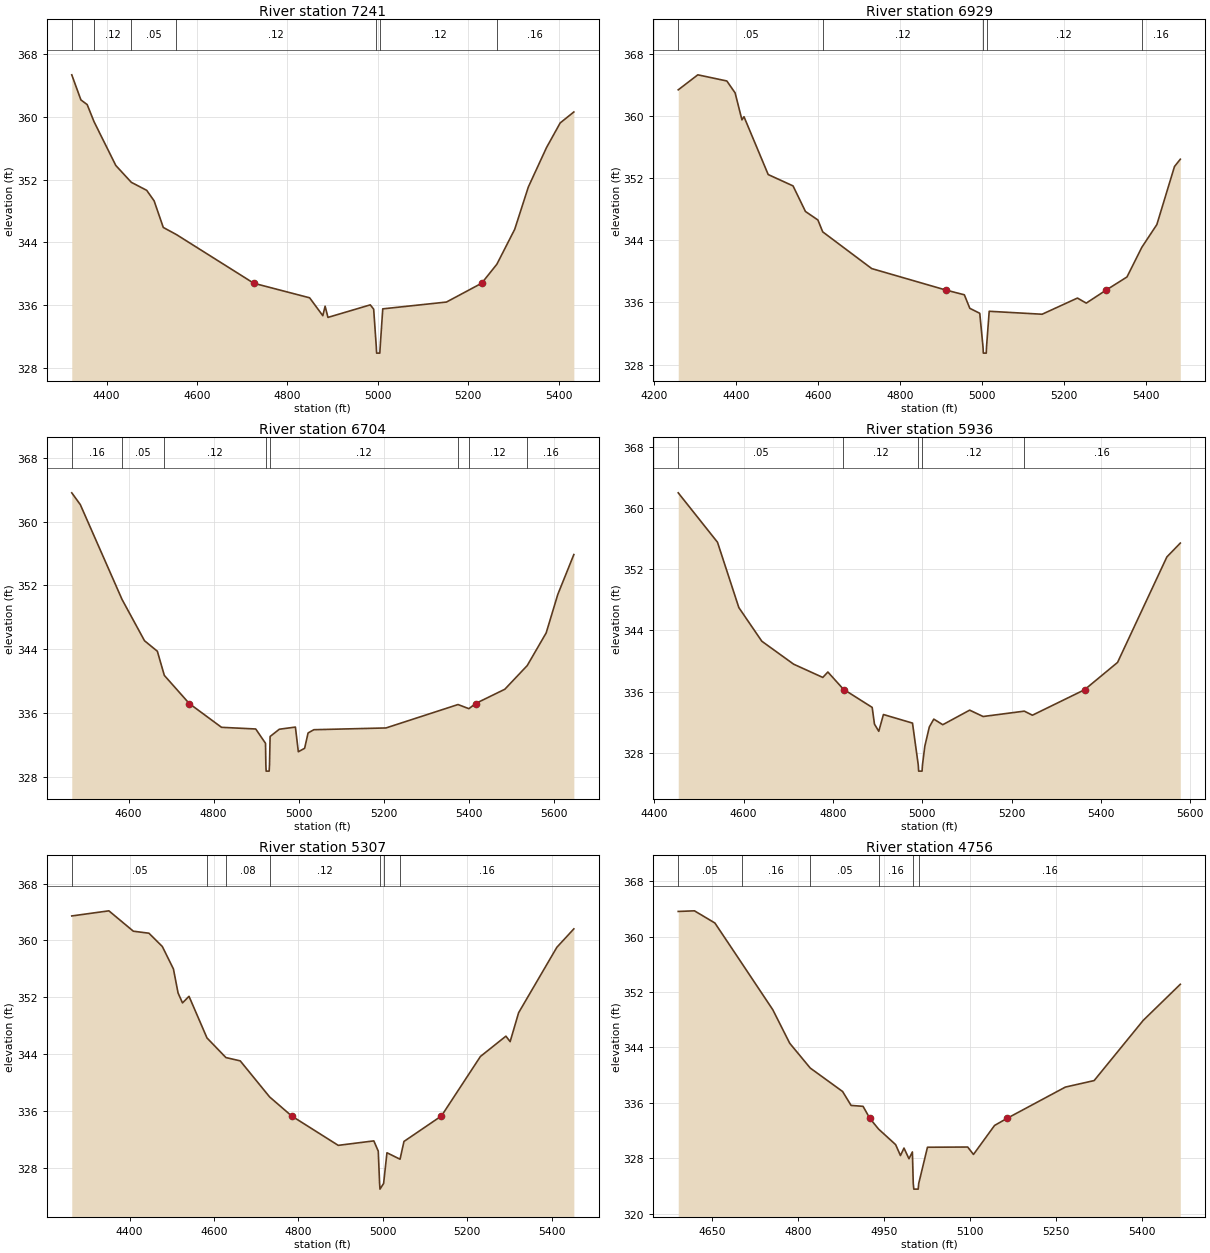
Type RM Length L Ch R = 1,7241,312,312,312
BEGIN DESCRIPTION:
STEWART BRANCH 8.0
END DESCRIPTION:
XS GIS Cut Line= 3
      2929725.00      6954925.00      2929075.00      6954825.00
      2928625.02      6954775.00
#Sta/Elev= 30
  4322.9  365.38  4343.1  362.18  4357.0  361.58  4372.3  359.38  4420.3  353.81
  4454.6  351.66  4488.6  350.64  4505.0  349.30  4525.3  345.90  4554.4  344.99
  4725.4  338.78  4849.0  336.92  4878.1  334.64  4883.2  335.85  4889.5  334.42
  4983.1  336.02  4990.6  335.47  4996.4  330.66  4997.1  329.86  5004.2  329.86
  5005.0  330.66  5010.7  335.51  5151.6  336.38  5229.4  338.78  5263.1  341.21
  5302.5  345.66  5332.7  351.07  5372.9  356.10  5403.1  359.24  5433.3  360.64
#Mann=7,-1,0
  4322.9    0.05       0  4372.3    0.12       0  4454.6    0.05       0
  4554.4    0.12       0  4996.4    0.07       0  5005.0    0.12       0
  5263.1    0.16       0
Bank Sta=4725.4,5229.4
Exp/Cntr=0.3,0.1

Type RM Length L Ch R = 1,6929,225,225,225
BEGIN DESCRIPTION:
Mapping XS 87bc330c
END DESCRIPTION:
XS GIS Cut Line= 3
      2929852.30      6954631.87      2929161.35      6954534.65
      2928671.80      6954729.08
#Sta/Elev= 30
  4259.3  363.34  4307.1  365.27  4377.8  364.48  4398.0  362.95  4414.7  359.48
  4419.7  359.88  4478.7  352.45  4539.3  350.99  4569.6  347.70  4599.9  346.61
  4611.7  345.08  4731.2  340.36  4912.7  337.59  4957.1  336.99  4970.4  335.25
  4994.7  334.61  5002.6  330.29  5003.4  329.49  5010.5  329.49  5011.2  330.29
  5017.7  334.87  5146.8  334.49  5232.9  336.57  5254.4  335.92  5302.8  337.59
  5353.7  339.28  5390.0  343.10  5426.6  346.02  5469.6  353.48  5483.8  354.42
#Mann=5,-1,0
  4259.3    0.05       0  4611.7    0.12       0  5002.6    0.07       0
  5011.2    0.12       0  5390.0    0.16       0
Bank Sta=4912.7,5302.8
Exp/Cntr=0.3,0.1

Type RM Length L Ch R = 1,6704,768,768,768
BEGIN DESCRIPTION:
STEWART BRANCH 7.0
END DESCRIPTION:
XS GIS Cut Line= 3
      2929725.02      6954375.00      2929275.00      6954325.00
      2928638.97      6954679.41
#Sta/Elev= 30
  4466.4  363.62  4486.5  362.14  4584.7  350.23  4637.5  345.05  4667.7  343.73
  4684.1  340.70  4742.7  337.17  4818.6  334.18  4899.1  333.97  4922.1  332.17
  4922.9  329.48  4923.6  328.68  4930.7  328.68  4931.5  329.48  4932.9  333.03
  4954.6  333.94  4992.4  334.21  4999.3  331.11  5014.1  331.55  5022.2  333.47
  5035.8  333.88  5205.4  334.10  5374.9  337.04  5400.5  336.52  5416.3  337.17
  5485.0  338.96  5537.6  341.93  5582.2  346.03  5609.6  350.87  5647.3  355.87
#Mann=8,-1,0
  4466.4    0.16       0  4584.7    0.05       0  4684.1    0.12       0
  4922.9    0.07       0  4931.5    0.12       0  5374.9    0.16       0
  5400.5    0.12       0  5537.6    0.16       0
Bank Sta=4742.7,5416.3
Exp/Cntr=0.3,0.1

Type RM Length L Ch R = 1,5936,629,629,629
BEGIN DESCRIPTION:
STEWART BRANCH 6.0
END DESCRIPTION:
XS GIS Cut Line= 3
      2929875.02      6953724.99      2929375.00      6953875.00
      2928775.02      6953925.00
#Sta/Elev= 30
  4453.7  361.97  4541.6  355.52  4589.4  346.99  4640.8  342.60  4712.1  339.60
  4777.4  337.87  4788.7  338.58  4823.7  336.32  4825.5  336.26  4887.9  333.96
  4893.1  331.77  4902.7  330.84  4913.1  333.03  4978.2  331.91  4991.1  326.44
  4992.0  325.64  4999.6  325.64  5000.5  326.44  5005.8  328.90  5015.9  331.41
  5025.9  332.43  5046.0  331.70  5106.2  333.60  5136.3  332.77  5228.5  333.47
  5246.7  332.94  5363.3  336.26  5437.3  339.83  5547.7  353.60  5577.8  355.41
#Mann=5,-1,0
  4453.7    0.05       0  4823.7    0.12       0  4991.1    0.07       0
  5000.5    0.12       0  5228.5    0.16       0
Bank Sta=4825.5,5363.3
Exp/Cntr=0.3,0.1

Type RM Length L Ch R = 1,5307,551,551,551
BEGIN DESCRIPTION:
STEWART BRANCH 5.0
END DESCRIPTION:
XS GIS Cut Line= 3
      2929973.89      6953607.59      2929275.00      6953375.00
      2928825.04      6953325.00
#Sta/Elev= 30
  4263.0  363.45  4350.9  364.17  4408.9  361.30  4445.8  361.02  4477.5  359.15
  4503.8  355.99  4514.8  352.61  4525.3  351.21  4540.7  352.14  4583.3  346.28
  4628.1  343.52  4662.1  343.05  4731.6  337.98  4783.8  335.30  4894.2  331.16
  4978.5  331.79  4989.0  330.35  4992.2  325.80  4993.1  325.00  5001.7  325.80
  5009.6  330.12  5040.6  329.21  5049.9  331.71  5138.7  335.30  5231.0  343.67
  5291.4  346.53  5301.4  345.76  5321.5  349.83  5412.1  359.04  5452.3  361.63
#Mann=7,-1,0
  4263.0    0.05       0  4583.3    0.16       0  4628.1    0.08       0
  4731.6    0.12       0  4992.2    0.07       0  5001.7    0.12       0
  5040.6    0.16       0
Bank Sta=4783.8,5138.7
Exp/Cntr=0.3,0.1

Type RM Length L Ch R = 1,4756,686,686,686
BEGIN DESCRIPTION:
STEWART BRANCH 4.0
END DESCRIPTION:
XS GIS Cut Line= 3
      2929825.01      6953225.01      2929490.24      6952988.83
      2929025.04      6953025.00
#Sta/Elev= 30
  4590.3  363.65  4618.6  363.74  4654.3  361.98  4701.5  356.14  4755.3  349.46
  4784.9  344.61  4820.7  341.03  4877.2  337.64  4892.0  335.63  4912.9  335.50
  4924.8  333.75  4939.9  332.22  4969.7  329.97  4978.2  328.39  4984.3  329.47
  4993.0  327.93  4999.0  328.91  5000.5  324.34  5001.5  323.54  5009.1  323.54
  5010.0  324.34  5025.3  329.59  5095.5  329.62  5105.6  328.55  5142.4  332.74
  5163.9  333.75  5266.0  338.28  5316.2  339.22  5401.8  347.91  5466.6  353.13
#Mann=6,-1,0
  4590.3    0.05       0  4701.5    0.16       0  4820.7    0.05       0
  4939.9    0.16       0  5000.5    0.07       0  5010.0    0.16       0
Bank Sta=4924.8,5163.9
Exp/Cntr=0.3,0.1

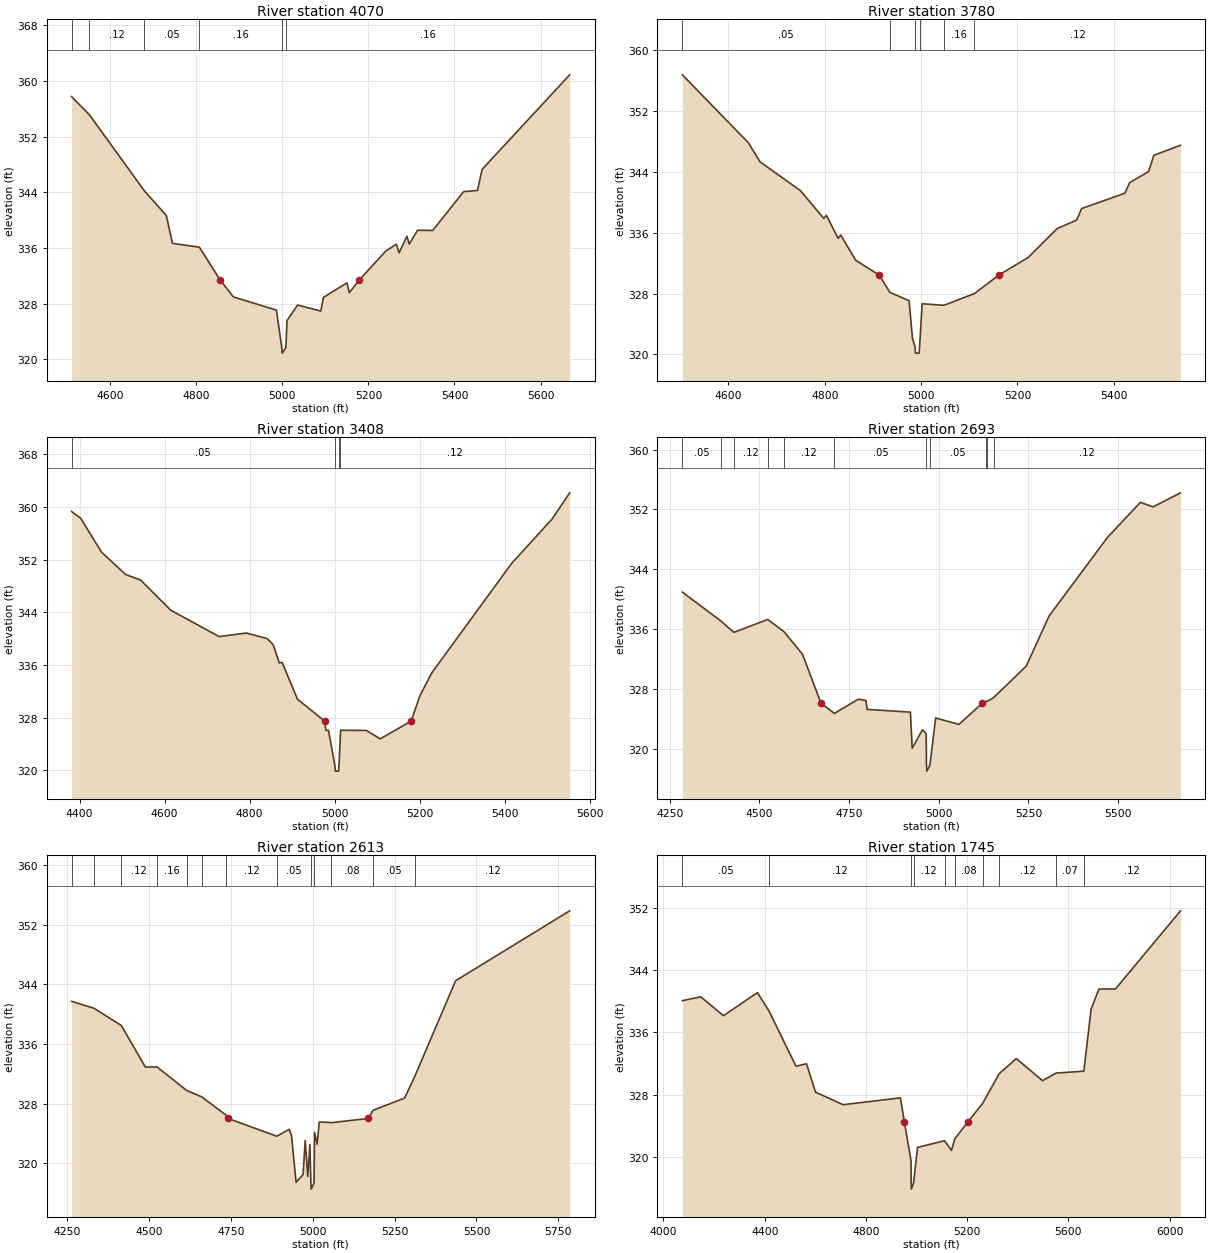
Type RM Length L Ch R = 1,4070,290,290,290
BEGIN DESCRIPTION:
STEWART BRANCH 3.0
END DESCRIPTION:
XS GIS Cut Line= 3
      2929775.03      6952775.02      2929425.00      6952475.00
      2928775.03      6952724.99
#Sta/Elev= 30
  4510.3  357.75  4551.5  355.16  4679.4  344.21  4730.4  340.67  4744.7  336.66
  4807.3  336.10  4855.4  331.41  4886.3  328.96  4986.3  327.06  4998.7  321.68
  4999.6  320.88  5008.2  321.68  5011.0  325.57  5035.6  327.79  5089.2  326.93
  5095.6  328.89  5150.2  330.98  5155.6  329.56  5179.1  331.41  5240.2  335.54
  5264.9  336.53  5271.3  335.30  5289.5  337.68  5294.9  336.56  5314.2  338.54
  5349.5  338.51  5421.3  344.09  5453.4  344.26  5464.2  347.29  5667.7  360.88
#Mann=6,-1,0
  4510.3    0.05       0  4551.5    0.12       0  4679.4    0.05       0
  4807.3    0.16       0  4998.7    0.07       0  5008.2    0.16       0
Bank Sta=4855.4,5179.1
Exp/Cntr=0.3,0.1

Type RM Length L Ch R = 1,3780,372,372,372
BEGIN DESCRIPTION:
Mapping XS 0adcaffa
END DESCRIPTION:
XS GIS Cut Line= 3
      2929949.52      6952409.65      2929512.04      6952236.04
      2928949.80      6952274.22
#Sta/Elev= 30
  4504.4  356.76  4641.4  347.83  4665.7  345.32  4749.4  341.54  4798.0  337.88
  4803.4  338.29  4827.7  335.26  4833.1  335.71  4864.3  332.38  4913.3  330.43
  4935.1  328.17  4975.1  327.07  4982.1  322.12  4987.4  320.98  4988.3  320.18
  4996.0  320.18  4996.9  320.98  5002.2  326.67  5047.6  326.47  5110.8  328.01
  5161.4  330.43  5222.7  332.77  5282.8  336.57  5322.9  337.66  5333.3  339.18
  5423.1  341.20  5433.2  342.60  5472.3  344.04  5483.3  346.19  5538.6  347.50
#Mann=6,-1,0
  4504.4    0.05       0  4935.1    0.12       0  4987.4    0.07       0
  4996.9    0.12       0  5047.6    0.16       0  5110.8    0.12       0
Bank Sta=4913.3,5161.4
Exp/Cntr=0.3,0.1

Type RM Length L Ch R = 1,3408,715,715,715
BEGIN DESCRIPTION:
STEWART BRANCH 2.0
END DESCRIPTION:
XS GIS Cut Line= 3
      2930024.96      6952374.97      2929575.00      6951975.00
      2929025.02      6951825.00
#Sta/Elev= 30
  4381.2  359.32  4402.5  358.31  4451.8  353.14  4508.7  349.74  4543.8  348.90
  4614.9  344.32  4728.6  340.32  4792.2  340.87  4841.5  340.02  4855.7  339.08
  4869.9  336.32  4876.6  336.41  4912.6  330.83  4976.4  327.50  4979.9  326.08
  4985.8  326.08  5000.9  320.69  5001.8  319.89  5009.5  319.89  5010.4  320.69
  5011.8  322.63  5014.3  326.10  5074.8  326.07  5107.6  324.79  5180.4  327.50
  5200.9  331.34  5228.5  334.79  5416.8  351.45  5511.9  358.18  5553.3  362.16
#Mann=4,-1,0
  4381.2    0.05       0  5000.9    0.04       0  5010.4    0.05       0
  5011.8    0.12       0
Bank Sta=4976.4,5180.4
Exp/Cntr=0.3,0.1

Type RM Length L Ch R = 1,2693,80,80,80
BEGIN DESCRIPTION:
Mapping XS b02d6fbd
END DESCRIPTION:
XS GIS Cut Line= 5
      2929963.44      6951920.09      2929605.79      6951545.07
      2929584.96      6951388.82      2929477.32      6951242.99
      2929092.43      6951610.54
#Sta/Elev= 30
  4285.0  340.94  4391.4  337.11  4428.7  335.55  4523.0  337.28  4568.8  335.63
  4620.0  332.62  4671.6  326.07  4708.9  324.71  4775.7  326.61  4796.8  326.45
  4800.2  325.25  4921.0  324.88  4926.0  320.05  4954.6  322.53  4965.0  321.99
  4965.7  317.79  4966.7  316.99  4975.3  317.79  4991.4  324.10  5056.1  323.24
  5121.7  326.07  5131.9  326.35  5135.4  326.33  5153.5  326.84  5244.1  331.04
  5307.9  337.75  5470.5  348.25  5562.4  352.95  5597.9  352.34  5674.3  354.22
#Mann=11,-1,0
  4285.0    0.05       0  4391.4    0.16       0  4428.7    0.12       0
  4523.0    0.16       0  4568.8    0.12       0  4708.9    0.05       0
  4965.7    0.04       0  4975.3    0.05       0  5131.9    0.08       0
  5135.4    0.05       0  5153.5    0.12       0
Bank Sta=4671.6,5121.7
Exp/Cntr=0.3,0.1

Type RM Length L Ch R = 1,2613,868,868,868
BEGIN DESCRIPTION:
Mapping XS 618d9c81
END DESCRIPTION:
XS GIS Cut Line= 5
      2930022.46      6951888.83      2929876.62      6951579.79
      2929623.15      6951322.85      2929484.26      6951156.18
      2929064.11      6951586.76
#Sta/Elev= 30
  4263.5  341.74  4332.0  340.81  4415.3  338.50  4488.9  332.92  4524.7  332.93
  4614.8  329.78  4660.7  328.93  4735.1  326.48  4741.4  326.02  4890.4  323.64
  4928.0  324.56  4935.0  323.79  4949.1  317.46  4970.5  318.50  4977.0  323.06
  4984.8  318.25  4991.3  322.53  4994.3  317.34  4995.2  316.54  5003.9  317.34
  5005.6  324.15  5013.4  322.56  5019.9  325.55  5057.0  325.46  5169.8  326.02
  5184.3  327.12  5280.7  328.76  5312.9  331.79  5436.3  344.50  5784.7  353.88
#Mann=13,-1,0
  4263.5    0.05       0  4332.0    0.16       0  4415.3    0.12       0
  4524.7    0.16       0  4614.8    0.12       0  4660.7    0.16       0
  4735.1    0.12       0  4890.4    0.05       0  4994.3    0.04       0
  5003.9    0.05       0  5057.0    0.08       0  5184.3    0.05       0
  5312.9    0.12       0
Bank Sta=4741.4,5169.8
Exp/Cntr=0.3,0.1

Type RM Length L Ch R = 1,1745,747,747,747
BEGIN DESCRIPTION:
Mapping XS bbbeef32
END DESCRIPTION:
XS GIS Cut Line= 4
      2929977.31      6951524.21      2929678.71      6950746.46
      2929505.10      6950704.79      2929046.76      6951545.08
#Sta/Elev= 30
  4074.7  340.09  4147.2  340.59  4237.2  338.16  4371.3  341.13  4417.9  338.71
  4523.7  331.66  4565.3  331.98  4600.7  328.33  4710.0  326.71  4936.4  327.59
  4952.5  324.43  4978.4  319.48  4978.8  316.65  4979.8  315.85  4988.4  316.65
  5004.2  321.22  5110.9  322.08  5138.3  320.83  5151.1  322.30  5201.7  324.43
  5261.2  326.87  5326.8  330.70  5394.6  332.64  5498.1  329.80  5552.1  330.78
  5661.3  331.02  5690.3  339.02  5721.1  341.59  5786.6  341.60  6043.5  351.65
#Mann=10,-1,0
  4074.7    0.05       0  4417.9    0.12       0  4978.8    0.07       0
  4988.4    0.12       0  5110.9    0.05       0  5151.1    0.08       0
  5261.2    0.05       0  5326.8    0.12       0  5552.1    0.07       0
  5661.3    0.12       0
Bank Sta=4952.5,5201.7
Exp/Cntr=0.3,0.1

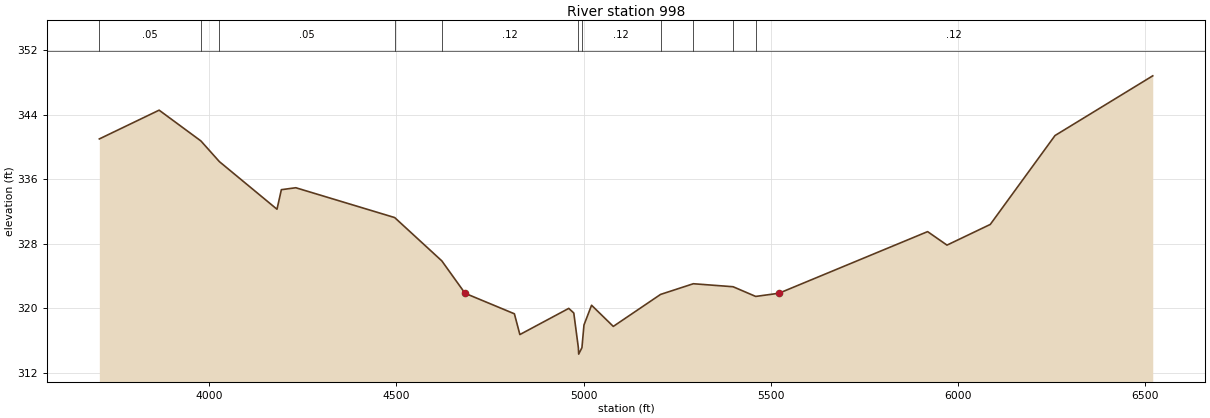
Type RM Length L Ch R = 1,998,313,313,313
BEGIN DESCRIPTION:
Mapping XS 446a2421
END DESCRIPTION:
XS GIS Cut Line= 4
      2929956.49      6951371.48      2929713.43      6950190.90
      2929560.65      6950163.13      2928963.41      6951489.56
#Sta/Elev= 30
  3706.0  340.98  3865.8  344.54  3977.5  340.73  4026.9  338.17  4180.8  332.28
  4192.5  334.70  4231.1  334.94  4495.3  331.25  4621.3  325.89  4683.4  321.88
  4815.3  319.34  4829.9  316.77  4960.6  320.01  4974.0  319.44  4986.2  315.15
  4987.1  314.35  4995.8  315.15  5001.2  317.95  5021.5  320.40  5079.6  317.78
  5206.0  321.74  5293.5  323.06  5399.7  322.69  5460.2  321.49  5522.0  321.88
  5919.6  329.51  5971.4  327.84  6087.1  330.40  6260.1  341.40  6521.3  348.79
#Mann=11,-1,0
  3706.0    0.05       0  3977.5    0.12       0  4026.9    0.05       0
  4495.3    0.16       0  4621.3    0.12       0  4986.2    0.07       0
  4995.8    0.12       0  5206.0    0.08       0  5293.5    0.05       0
  5399.7    0.08       0  5460.2    0.12       0
Bank Sta=4683.4,5522
Exp/Cntr=0.3,0.1