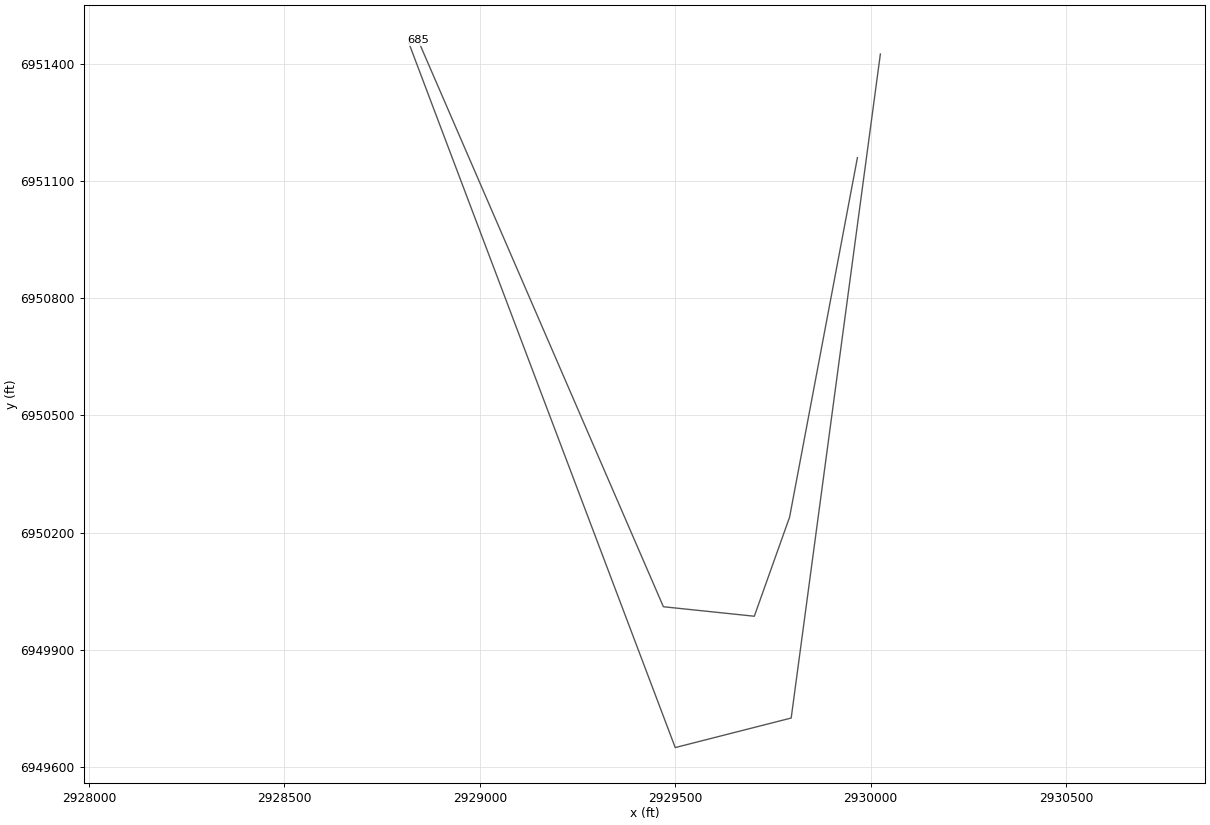
HEC-RAS study STEWART BRANCH.prj: STEWART BRANCH Base Level Engineering

--- STEWART BRANCH.g01 (geometry) --- (continued)

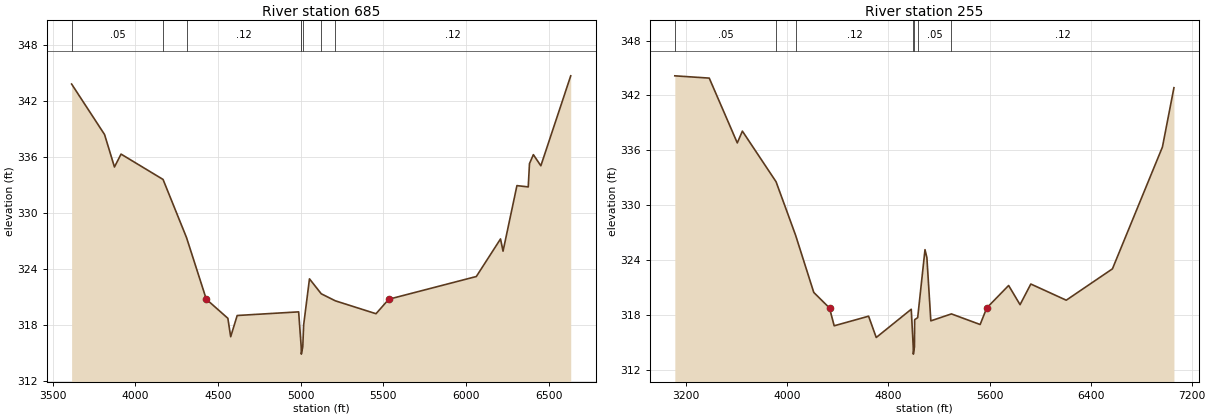
Type RM Length L Ch R = 1,685,430,430,430
BEGIN DESCRIPTION:
Mapping XS 35c4274d
END DESCRIPTION:
XS GIS Cut Line= 5
      2929966.26      6951159.75      2929792.64      6950239.59
      2929702.36      6949986.12      2929469.72      6950010.42
      2928841.64      6951460.90
#Sta/Elev= 30
  3613.5  343.79  3812.9  338.39  3872.7  334.92  3912.6  336.30  4166.7  333.59
  4308.8  327.37  4428.5  320.78  4558.9  318.74  4576.0  316.77  4615.3  319.04
  4987.2  319.43  5000.7  316.16  5002.6  315.71  5003.5  314.91  5012.2  315.71
  5017.4  318.02  5052.7  322.96  5124.1  321.36  5209.3  320.61  5455.2  319.23
  5532.6  320.78  6062.3  323.21  6208.7  327.23  6223.9  325.92  6308.0  332.93
  6376.4  332.79  6383.9  335.28  6407.4  336.24  6452.7  335.05  6633.5  344.67
#Mann=8,-1,0
  3613.5    0.05       0  4166.7    0.16       0  4308.8    0.12       0
  5000.7    0.05       0  5002.6    0.07       0  5012.2    0.05       0
  5124.1    0.08       0  5209.3    0.12       0
Bank Sta=4428.5,5532.6
Exp/Cntr=0.3,0.1

Type RM Length L Ch R = 1,255,0,0,0
BEGIN DESCRIPTION:
STEWART BRANCH 1.0
END DESCRIPTION:
XS GIS Cut Line= 4
      2930024.99      6951424.96      2929796.76      6949725.63
      2929500.00      6949650.00      2928817.61      6951454.76
#Sta/Elev= 30
  3109.0  344.15  3381.4  343.90  3603.4  336.81  3643.7  338.10  3910.3  332.56
  4064.6  326.72  4208.7  320.45  4333.2  318.75  4370.2  316.80  4642.6  317.85
  4703.1  315.52  4980.2  318.61  4996.0  314.50  4996.9  313.70  5005.6  314.50
  5007.2  317.47  5031.1  317.69  5089.0  325.13  5104.0  324.26  5135.2  317.34
  5298.2  318.10  5525.5  316.94  5577.7  318.75  5750.9  321.21  5841.4  319.11
  5926.6  321.37  6207.0  319.60  6572.5  323.03  6968.2  336.36  7059.3  342.85
#Mann=7,-1,0
  3109.0    0.05       0  3910.3    0.16       0  4064.6    0.12       0
  4996.0    0.07       0  5005.6    0.12       0  5031.1    0.05       0
  5298.2    0.12       0
Bank Sta=4333.2,5577.7
Exp/Cntr=0.3,0.1

Chan Stop Cuts=-1