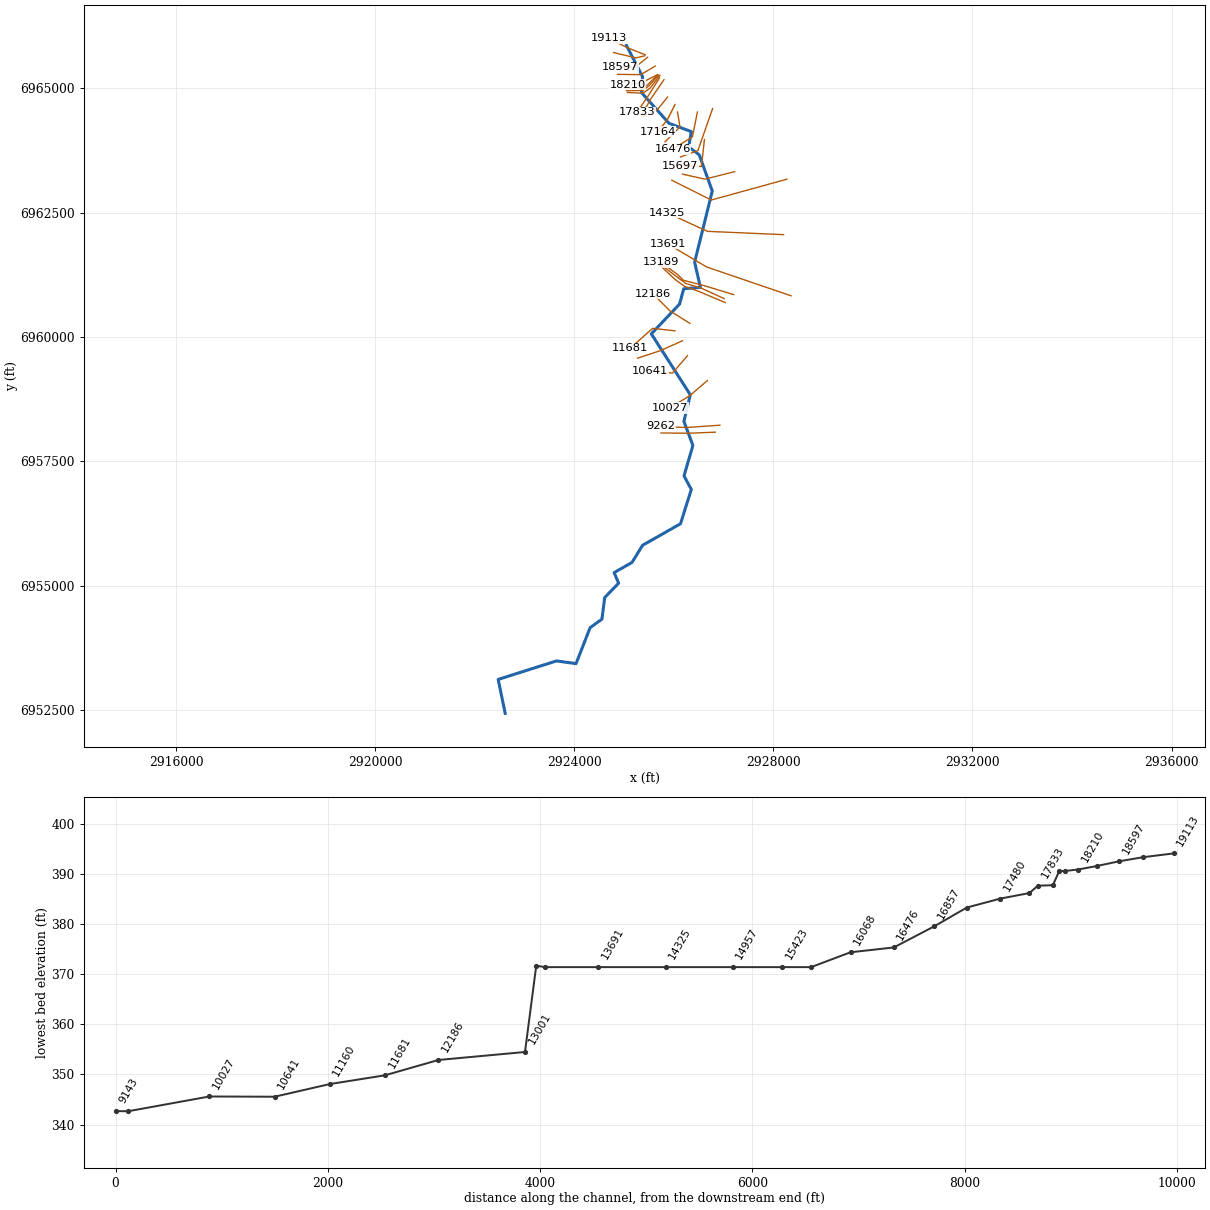
--- STEWART CREEK.prj (project) ---

Proj Title=STEWART CREEK Base Level Engineering
Current Plan=p01
Default Exp/Contr=0.3,0.1
English Units
Geom File=g01
Flow File=f01
Plan File=p01
BEGIN DESCRIPTION:
STEWART CREEK
END DESCRIPTION:

--- STEWART CREEK.p01 (plan) ---

Plan Title=Multiple Run
Short Identifier=Multiple
Geom File=g01
Flow File=f01
Subcritical Flow
K Sum by GR= 0
Std Step Tol= 0.01
Critical Tol= 0.01
Num of Std Step Trials= 20
Max Error Tol= 0.3
Flow Tol Ratio= 0.001
Split Flow NTrial= 30
Split Flow Tol= 0.02
Split Flow Ratio= 0.02
Log Output Level= 0
Friction Slope Method= 1
Unsteady Friction Slope Method= 2
Unsteady Bridges Friction Slope Method= 1
Parabolic Critical Depth
Global Vel Dist=  1 , 1 , 1
Global Log Level= 0
CheckData=True
Encroach Param= -1, 0, 0, 0
BEGIN DESCRIPTION:
Multiple Run
END DESCRIPTION:

--- STEWART CREEK.f01 (steady flow) ---

Flow Title=Multiple
Program Version=5.07
Number of Profiles= 7
Profile Names=10-year,25-year,50-year,1pct_min,100-year,1pct_plu,500-year
River Rch & RM=STEWART CREEK,Reach-1         ,19113
     402     531     634     378     754    1505    1066
River Rch & RM=STEWART CREEK,Reach-1         ,15423
    1085    1512    1873    1152    2298    4585    3468
River Rch & RM=STEWART CREEK,Reach-1         ,6549
    1160    1618    2004    1232    2459    4905    3708
Boundary for River Rch & Prof#=STEWART CREEK,Reach-1         , 1
Up Type= 0
Dn Type= 3
Dn Slope=0.005
Boundary for River Rch & Prof#=STEWART CREEK,Reach-1         , 2
Up Type= 0
Dn Type= 3
Dn Slope=0.005
Boundary for River Rch & Prof#=STEWART CREEK,Reach-1         , 3
Up Type= 0
Dn Type= 3
Dn Slope=0.005
Boundary for River Rch & Prof#=STEWART CREEK,Reach-1         , 4
Up Type= 0
Dn Type= 3
Dn Slope=0.005
Boundary for River Rch & Prof#=STEWART CREEK,Reach-1         , 5
Up Type= 0
Dn Type= 3
Dn Slope=0.005
Boundary for River Rch & Prof#=STEWART CREEK,Reach-1         , 6
Up Type= 0
Dn Type= 3
Dn Slope=0.005
Boundary for River Rch & Prof#=STEWART CREEK,Reach-1         , 7
Up Type= 0
Dn Type= 3
Dn Slope=0.005
DSS Import GetInterval= 0
DSS Import GetPeak= 0
DSS Import FillOption= 0

--- STEWART CREEK.g01 (geometry) ---

Geom Title=Existing Conditions

River Reach=STEWART CREEK,Reach-1
Reach XY= 30
      2925049.29      6965862.74      2925373.18      6965234.97
      2925355.58      6964910.63      2925904.14      6964296.62
      2926353.38      6964129.81      2926299.18      6963822.18
      2926512.56      6963662.50      2926773.69      6962935.17
      2926419.52      6961504.61      2926535.00      6960999.74
      2926200.23      6960970.76      2926117.40      6960664.22
      2925549.43      6960064.20      2926332.41      6958839.37
      2926203.94      6958305.52      2926384.14      6957821.13
      2926206.17      6957208.63      2926352.68      6956936.75
      2926135.40      6956246.51      2925373.63      6955814.16
      2925161.22      6955468.90      2924801.37      6955263.28
      2924892.14      6955052.40      2924612.13      6954763.19
      2924556.85      6954328.95      2924319.46      6954157.73
      2924037.35      6953435.08      2923644.55      6953489.33
      2922472.63      6953117.47      2922613.71      6952434.78

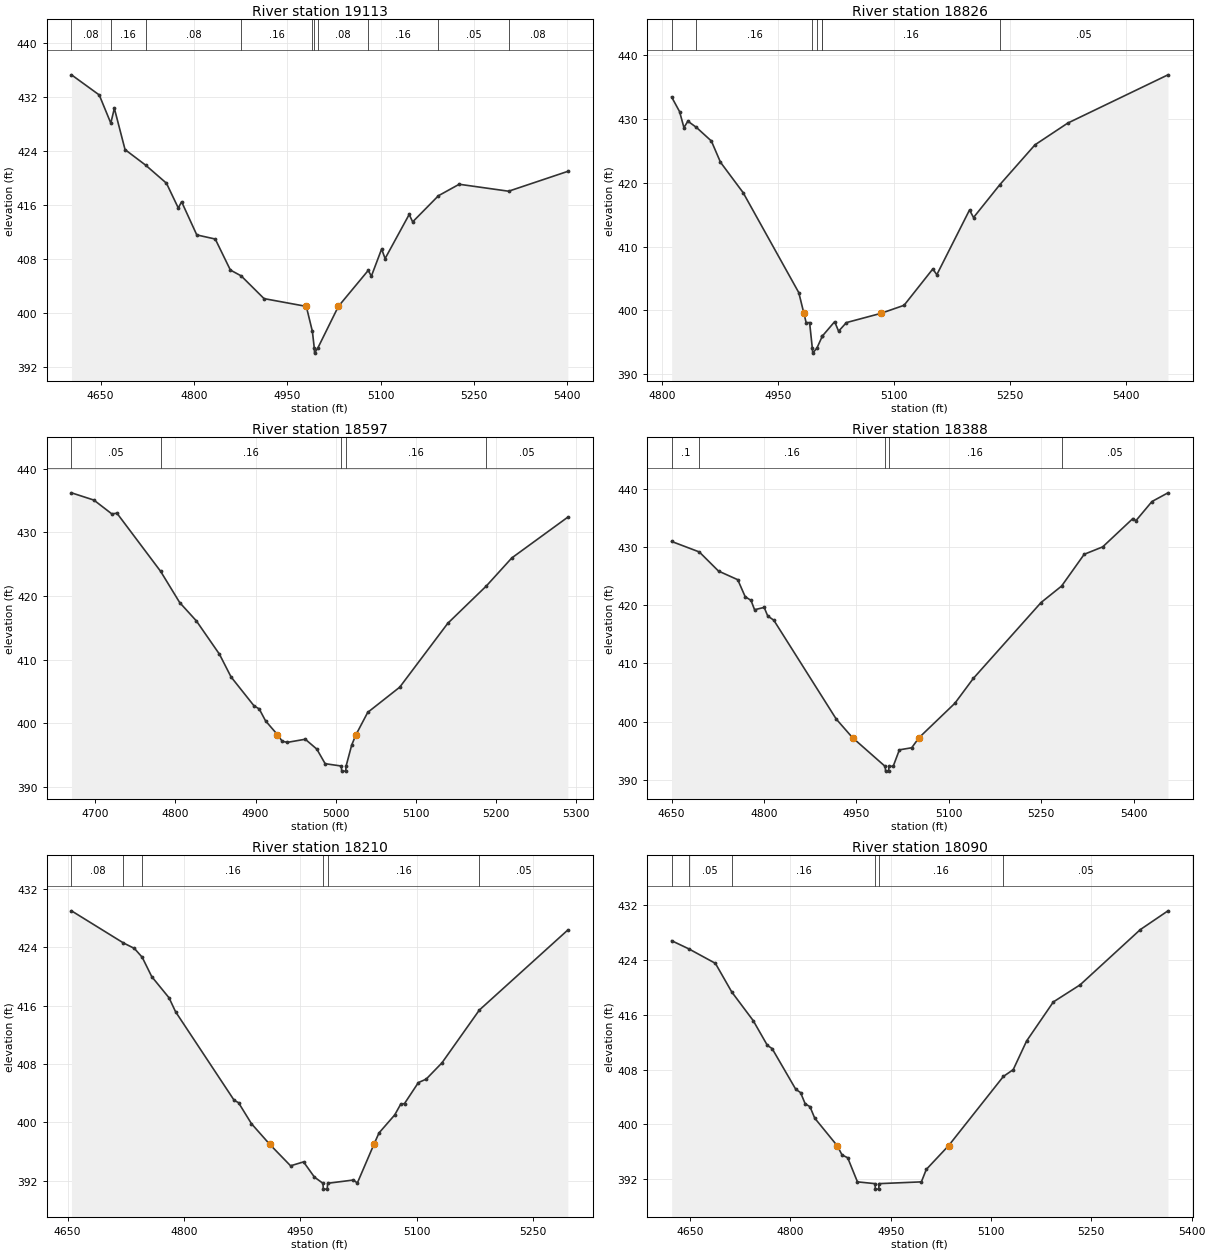
Type RM Length L Ch R = 1,19113,287,287,287
BEGIN DESCRIPTION:
STEWART CREEK 34.0
END DESCRIPTION:
XS GIS Cut Line= 3
      2925425.02      6965674.99      2925056.18      6965821.03
      2924699.90      6966005.29
#Sta/Elev= 30
  4603.3  435.25  4647.9  432.27  4666.5  428.10  4672.2  430.29  4689.4  424.18
  4722.6  421.87  4756.0  419.20  4775.0  415.53  4780.3  416.46  4804.7  411.55
  4834.4  410.94  4858.7  406.35  4876.0  405.49  4912.8  402.12  4980.7  400.97
  4990.5  397.28  4993.5  394.85  4994.0  394.05  4999.5  394.85  5032.3  400.97
  5080.3  406.30  5085.3  405.44  5101.8  409.46  5107.4  408.05  5146.1  414.58
  5151.7  413.48  5193.1  417.35  5226.5  419.05  5305.9  418.02  5401.1  420.96
#Mann=10,-1,0
  4603.3    0.08       0  4666.5    0.16       0  4722.6    0.08       0
  4876.0    0.16       0  4990.5    0.08       0  4993.5    0.07       0
  4999.5    0.08       0  5080.3    0.16       0  5193.1    0.05       0
  5305.9    0.08       0
Bank Sta=4980.7,5032.3
Exp/Cntr=0.3,0.1

Type RM Length L Ch R = 1,18826,229,229,229
BEGIN DESCRIPTION:
Mapping XS 37590bd0
END DESCRIPTION:
XS GIS Cut Line= 3
      2925415.01      6965653.76      2925241.38      6965612.53
      2924789.99      6965718.87
#Sta/Elev= 30
  4812.5  433.47  4822.8  431.17  4828.4  428.67  4833.5  429.68  4844.6  428.70
  4863.9  426.57  4875.7  423.24  4905.0  418.47  4977.0  402.79  4983.6  399.54
  4986.5  398.09  4991.0  398.09  4994.5  394.10  4995.0  393.30  5000.5  394.10
  5007.4  395.95  5007.5  395.98  5023.4  398.23  5028.5  396.74  5038.6  398.09
  5083.3  399.54  5113.2  400.80  5150.4  406.50  5155.6  405.60  5197.9  415.75
  5203.1  414.57  5237.2  419.73  5282.6  425.97  5325.0  429.38  5454.7  436.95
#Mann=7,-1,0
  4812.5    0.08       0  4844.6    0.16       0  4994.5    0.07       0
  5000.5    0.16       0  5007.4    0.08       0  5007.5    0.16       0
  5237.2    0.05       0
Bank Sta=4983.6,5083.3
Exp/Cntr=0.3,0.1

Type RM Length L Ch R = 1,18597,209,209,209
BEGIN DESCRIPTION:
STEWART CREEK 33.0
END DESCRIPTION:
XS GIS Cut Line= 3
      2925474.98      6965624.98      2925225.00      6965425.00
      2924925.03      6965425.00
#Sta/Elev= 30
  4670.1  436.19  4698.1  435.05  4720.5  432.88  4726.9  432.99  4781.5  423.85
  4805.3  418.95  4826.2  416.06  4855.0  410.83  4869.4  407.28  4898.2  402.72
  4904.6  402.25  4912.6  400.36  4927.4  398.21  4933.4  397.16  4939.8  396.99
  4962.2  397.48  4976.6  395.93  4987.0  393.64  5007.2  393.27  5007.7  392.47
  5012.7  392.47  5013.2  393.27  5020.2  396.58  5025.6  398.21  5040.2  401.70
  5080.2  405.66  5140.2  415.69  5188.5  421.57  5220.2  425.96  5290.2  432.37
#Mann=5,-1,0
  4670.1    0.05       0  4781.5    0.16       0  5007.2    0.07       0
  5013.2    0.16       0  5188.5    0.05       0
Bank Sta=4927.4,5025.6
Exp/Cntr=0.3,0.1

Type RM Length L Ch R = 1,18388,178,178,178
BEGIN DESCRIPTION:
Mapping XS 3dd84acf
END DESCRIPTION:
XS GIS Cut Line= 3
      2925627.64      6965447.58      2925339.04      6965276.16
      2924869.03      6965280.49
#Sta/Elev= 30
  4650.1  430.92  4695.0  429.12  4726.2  425.84  4757.4  424.36  4769.5  421.44
  4778.9  420.82  4784.7  419.21  4800.3  419.61  4806.1  418.13  4815.9  417.42
  4917.2  400.47  4943.7  397.27  4996.8  392.33  4997.3  391.53  5002.3  391.53
  5002.8  392.33  5009.8  392.38  5019.8  395.18  5039.8  395.54  5051.7  397.27
  5109.8  403.16  5139.8  407.43  5249.8  420.45  5283.1  423.27  5319.8  428.72
  5349.8  429.99  5398.8  434.85  5403.8  434.49  5429.8  437.77  5455.8  439.26
#Mann=5,-1,0
  4650.1     0.1       0  4695.0    0.16       0  4996.8    0.07       0
  5002.8    0.16       0  5283.1    0.05       0
Bank Sta=4943.7,5051.7
Exp/Cntr=0.3,0.1

Type RM Length L Ch R = 1,18210,120,120,120
BEGIN DESCRIPTION:
STEWART CREEK 32.0
END DESCRIPTION:
XS GIS Cut Line= 3
      2925674.96      6965274.98      2925375.00      6965125.00
      2925075.00      6965075.00
#Sta/Elev= 30
  4655.0  429.03  4721.8  424.63  4736.0  423.87  4746.1  422.66  4758.4  420.00
  4780.7  417.09  4789.1  415.18  4864.6  403.02  4870.2  402.70  4886.9  399.81
  4910.6  396.96  4937.3  394.03  4954.0  394.57  4968.0  392.48  4979.0  391.63
  4979.5  390.83  4984.5  390.83  4985.0  391.63  5018.2  392.08  5023.3  391.67
  5044.6  396.96  5051.2  398.54  5071.5  401.02  5079.1  402.48  5084.1  402.58
  5101.9  405.45  5112.0  405.93  5132.3  408.16  5180.5  415.41  5294.5  426.40
#Mann=6,-1,0
  4655.0    0.08       0  4721.8    0.05       0  4746.1    0.16       0
  4979.0    0.07       0  4985.0    0.16       0  5180.5    0.05       0
Bank Sta=4910.6,5044.6
Exp/Cntr=0.3,0.1

Type RM Length L Ch R = 1,18090,56,56,56
BEGIN DESCRIPTION:
Mapping XS 73c8b342
END DESCRIPTION:
XS GIS Cut Line= 4
      2925658.03      6965254.43      2925475.76      6965072.16
      2925384.61      6965004.89      2925013.57      6965007.06
#Sta/Elev= 30
  4622.5  426.79  4648.2  425.60  4687.9  423.49  4712.4  419.31  4744.4  415.14
  4765.7  411.51  4772.7  411.06  4808.1  405.11  4815.2  404.64  4822.2  402.99
  4829.3  402.58  4836.4  400.91  4870.1  396.88  4877.3  395.53  4885.7  395.13
  4900.3  391.61  4926.6  391.35  4927.1  390.55  4932.1  390.55  4932.6  391.35
  4995.9  391.61  5003.2  393.42  5036.5  396.88  5118.5  406.99  5133.2  407.98
  5153.2  412.16  5193.2  417.86  5233.2  420.35  5323.2  428.41  5364.6  431.15
#Mann=6,-1,0
  4622.5    0.08       0  4648.2    0.05       0  4712.4    0.16       0
  4926.6    0.07       0  4932.6    0.16       0  5118.5    0.05       0
Bank Sta=4870.1,5036.5
Exp/Cntr=0.3,0.1

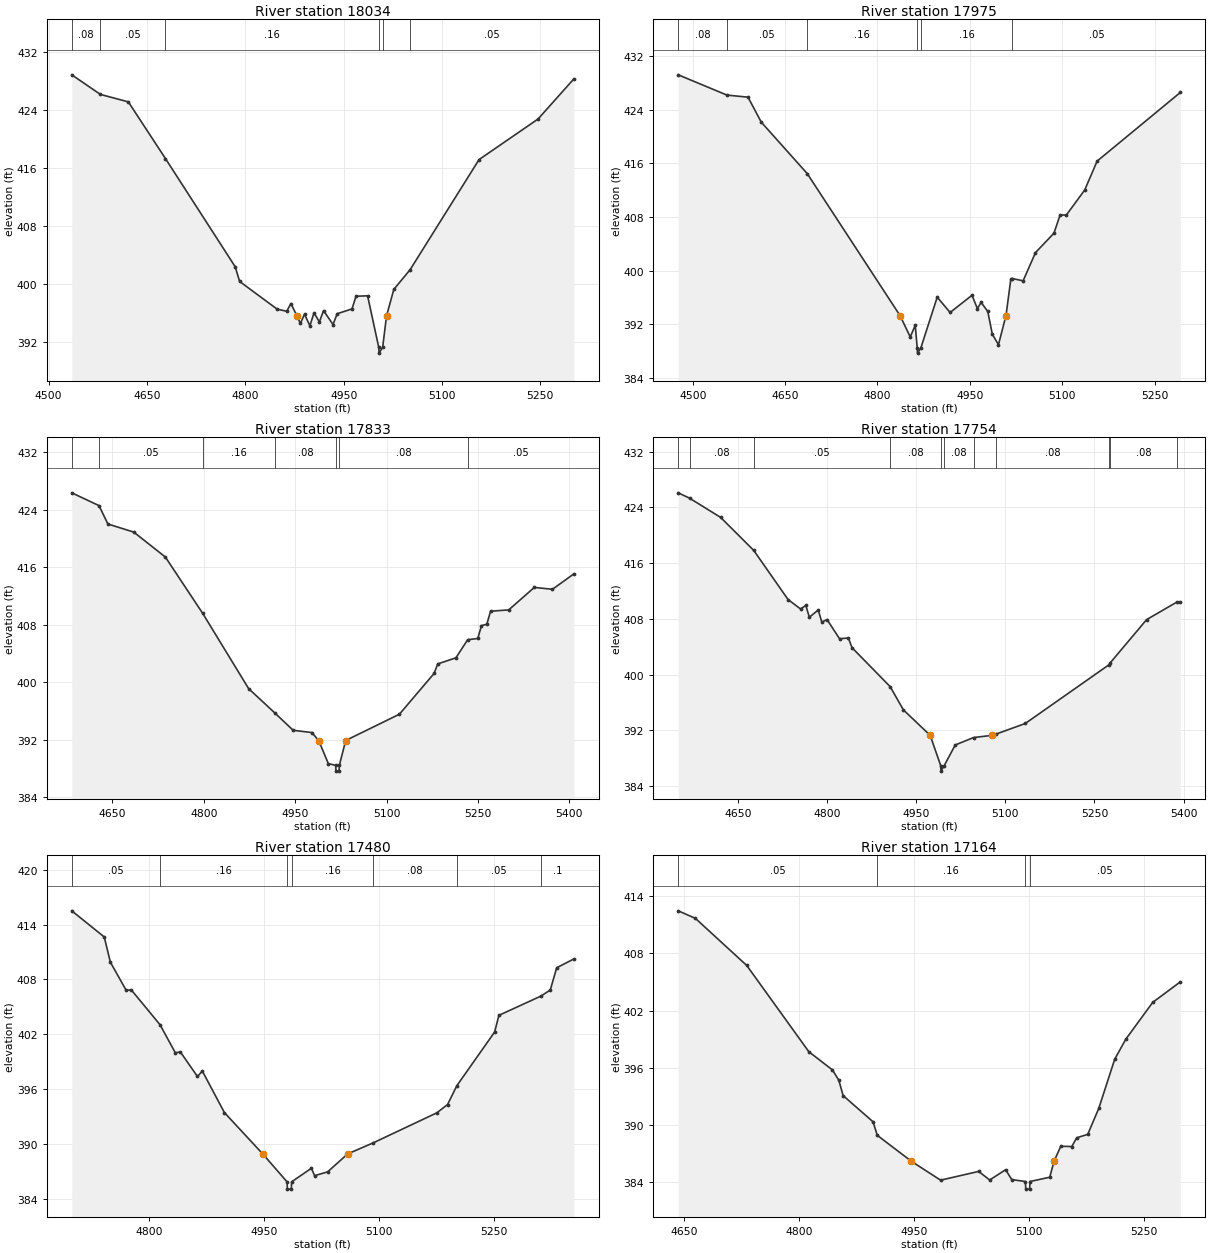
Type RM Length L Ch R = 1,18034,59,59,59
BEGIN DESCRIPTION:
Mapping XS db1a1351
END DESCRIPTION:
XS GIS Cut Line= 4
      2925690.59      6965260.95      2925506.14      6965054.80
      2925380.27      6964957.15      2925050.43      6964952.81
#Sta/Elev= 30
  4535.3  428.87  4579.0  426.17  4621.6  425.14  4678.2  417.33  4784.6  402.42
  4791.3  400.40  4848.7  396.57  4863.2  396.29  4869.5  397.35  4878.8  395.65
  4884.0  394.61  4890.3  395.89  4898.5  394.29  4904.8  396.07  4913.0  394.82
  4919.3  396.38  4933.8  394.46  4940.1  395.95  4962.7  396.61  4968.9  398.36
  4986.5  398.42  5003.5  391.32  5004.0  390.52  5009.5  391.32  5015.4  395.65
  5026.5  399.30  5051.3  402.01  5156.5  417.19  5246.5  422.78  5301.1  428.31
#Mann=6,-1,0
  4535.3    0.08       0  4579.0    0.05       0  4678.2    0.16       0
  5003.5    0.07       0  5009.5    0.16       0  5051.3    0.05       0
Bank Sta=4878.8,5015.4
Exp/Cntr=0.3,0.1

Type RM Length L Ch R = 1,17975,142,142,142
BEGIN DESCRIPTION:
Mapping XS bf8bfca8
END DESCRIPTION:
XS GIS Cut Line= 4
      2925723.15      6965265.30      2925525.67      6965004.89
      2925382.44      6964902.89      2925069.97      6964915.91
#Sta/Elev= 30
  4476.4  429.19  4555.5  426.17  4589.7  425.86  4611.3  422.13  4685.9  414.47
  4836.6  393.31  4853.2  390.12  4861.3  391.86  4864.5  388.51  4865.0  387.71
  4870.5  388.51  4897.0  396.05  4917.9  393.77  4953.5  396.33  4962.2  394.36
  4968.3  395.27  4979.1  393.92  4986.5  390.52  4996.5  388.97  5008.7  393.31
  5016.5  398.70  5019.1  398.82  5036.5  398.49  5056.6  402.69  5086.6  405.59
  5096.6  408.31  5106.6  408.28  5136.6  412.03  5156.7  416.33  5291.8  426.56
#Mann=6,-1,0
  4476.4    0.08       0  4555.5    0.05       0  4685.9    0.16       0
  4864.5    0.07       0  4870.5    0.16       0  5019.1    0.05       0
Bank Sta=4836.6,5008.7
Exp/Cntr=0.3,0.1

Type RM Length L Ch R = 1,17833,79,79,79
BEGIN DESCRIPTION:
Mapping XS f7d14417
END DESCRIPTION:
XS GIS Cut Line= 3
      2925712.32      6965208.90      2925486.61      6964848.64
      2925261.32      6964519.36
#Sta/Elev= 30
  4583.3  426.33  4628.0  424.55  4642.6  421.99  4685.0  420.87  4736.9  417.40
  4798.2  409.56  4873.6  399.09  4917.4  395.64  4946.7  393.29  4977.3  392.98
  4988.6  391.87  5004.4  388.66  5016.5  388.41  5017.0  387.61  5022.0  387.61
  5022.5  388.41  5032.9  391.87  5121.1  395.53  5178.0  401.20  5184.0  402.53
  5213.8  403.37  5233.1  405.89  5249.7  406.07  5255.8  407.85  5264.6  408.05
  5270.7  409.86  5300.5  410.04  5342.5  413.17  5372.3  412.91  5407.4  415.05
#Mann=7,-1,0
  4583.3    0.08       0  4628.0    0.05       0  4798.2    0.16       0
  4917.4    0.08       0  5016.5    0.07       0  5022.5    0.08       0
  5233.1    0.05       0
Bank Sta=4988.6,5032.9
Exp/Cntr=0.3,0.1

Type RM Length L Ch R = 1,17754,274,274,274
BEGIN DESCRIPTION:
Mapping XS 09c3833a
END DESCRIPTION:
XS GIS Cut Line= 3
      2925803.48      6965174.20      2925547.37      6964800.90
      2925352.08      6964460.21
#Sta/Elev= 30
  4549.1  426.09  4568.2  425.32  4620.4  422.57  4676.2  417.83  4734.1  410.77
  4755.0  409.43  4763.9  409.93  4769.9  408.24  4784.8  409.27  4790.9  407.54
  4799.7  407.90  4820.7  405.15  4835.6  405.26  4841.7  403.87  4905.9  398.28
  4928.3  394.93  4973.3  391.29  4991.0  386.95  4991.5  386.15  4997.0  386.95
  5015.5  389.90  5046.4  390.97  5078.0  391.29  5084.8  391.48  5133.5  392.99
  5275.0  401.45  5276.2  401.66  5337.7  407.89  5389.3  410.44  5394.5  410.44
#Mann=11,-1,0
  4549.1    0.05       0  4568.2    0.08       0  4676.2    0.05       0
  4905.9    0.08       0  4991.0    0.07       0  4997.0    0.08       0
  5046.4    0.16       0  5084.8    0.08       0  5275.0    0.05       0
  5276.2    0.08       0  5389.3     0.1       0
Bank Sta=4973.3,5078
Exp/Cntr=0.3,0.1

Type RM Length L Ch R = 1,17480,316,316,316
BEGIN DESCRIPTION:
STEWART CREEK 30.0
END DESCRIPTION:
XS GIS Cut Line= 3
      2925875.00      6964825.00      2925675.00      6964575.00
      2925374.98      6964424.99
#Sta/Elev= 30
  4698.7  415.50  4741.1  412.64  4749.1  409.88  4769.9  406.78  4776.3  406.86
  4813.9  403.04  4834.0  399.95  4840.4  400.07  4862.8  397.37  4869.2  397.96
  4898.0  393.42  4948.1  388.89  4979.8  385.84  4980.3  385.04  4985.3  385.04
  4985.8  385.84  5011.7  387.33  5015.7  386.51  5032.8  386.93  5058.9  388.89
  5092.2  390.10  5175.4  393.39  5189.4  394.30  5201.6  396.37  5250.9  402.24
  5256.4  404.06  5311.1  406.16  5323.5  406.83  5331.9  409.27  5354.3  410.23
#Mann=7,-1,0
  4698.7    0.05       0  4813.9    0.16       0  4979.8    0.07       0
  4985.8    0.16       0  5092.2    0.08       0  5201.6    0.05       0
  5311.1     0.1       0
Bank Sta=4948.1,5058.9
Exp/Cntr=0.3,0.1

Type RM Length L Ch R = 1,17164,307,307,307
BEGIN DESCRIPTION:
STEWART CREEK 29.0
END DESCRIPTION:
XS GIS Cut Line= 3
      2926025.02      6964675.03      2925875.00      6964375.00
      2925675.00      6964125.00
#Sta/Elev= 30
  4642.0  412.48  4664.4  411.69  4731.5  406.74  4812.5  397.69  4843.3  395.78
  4851.7  394.69  4857.3  393.08  4896.4  390.33  4901.9  388.91  4946.5  386.18
  4984.6  384.20  5034.3  385.12  5048.7  384.22  5069.5  385.30  5077.5  384.26
  5095.3  384.06  5095.8  383.26  5100.8  383.26  5101.3  384.06  5127.1  384.51
  5132.7  386.18  5141.5  387.76  5155.9  387.73  5162.3  388.65  5176.7  389.01
  5191.1  391.73  5212.0  396.91  5226.4  399.00  5261.6  402.87  5297.6  405.02
#Mann=4,-1,0
  4642.0    0.05       0  4901.9    0.16       0  5095.3    0.07       0
  5101.3    0.05       0
Bank Sta=4946.5,5132.7
Exp/Cntr=0.3,0.1

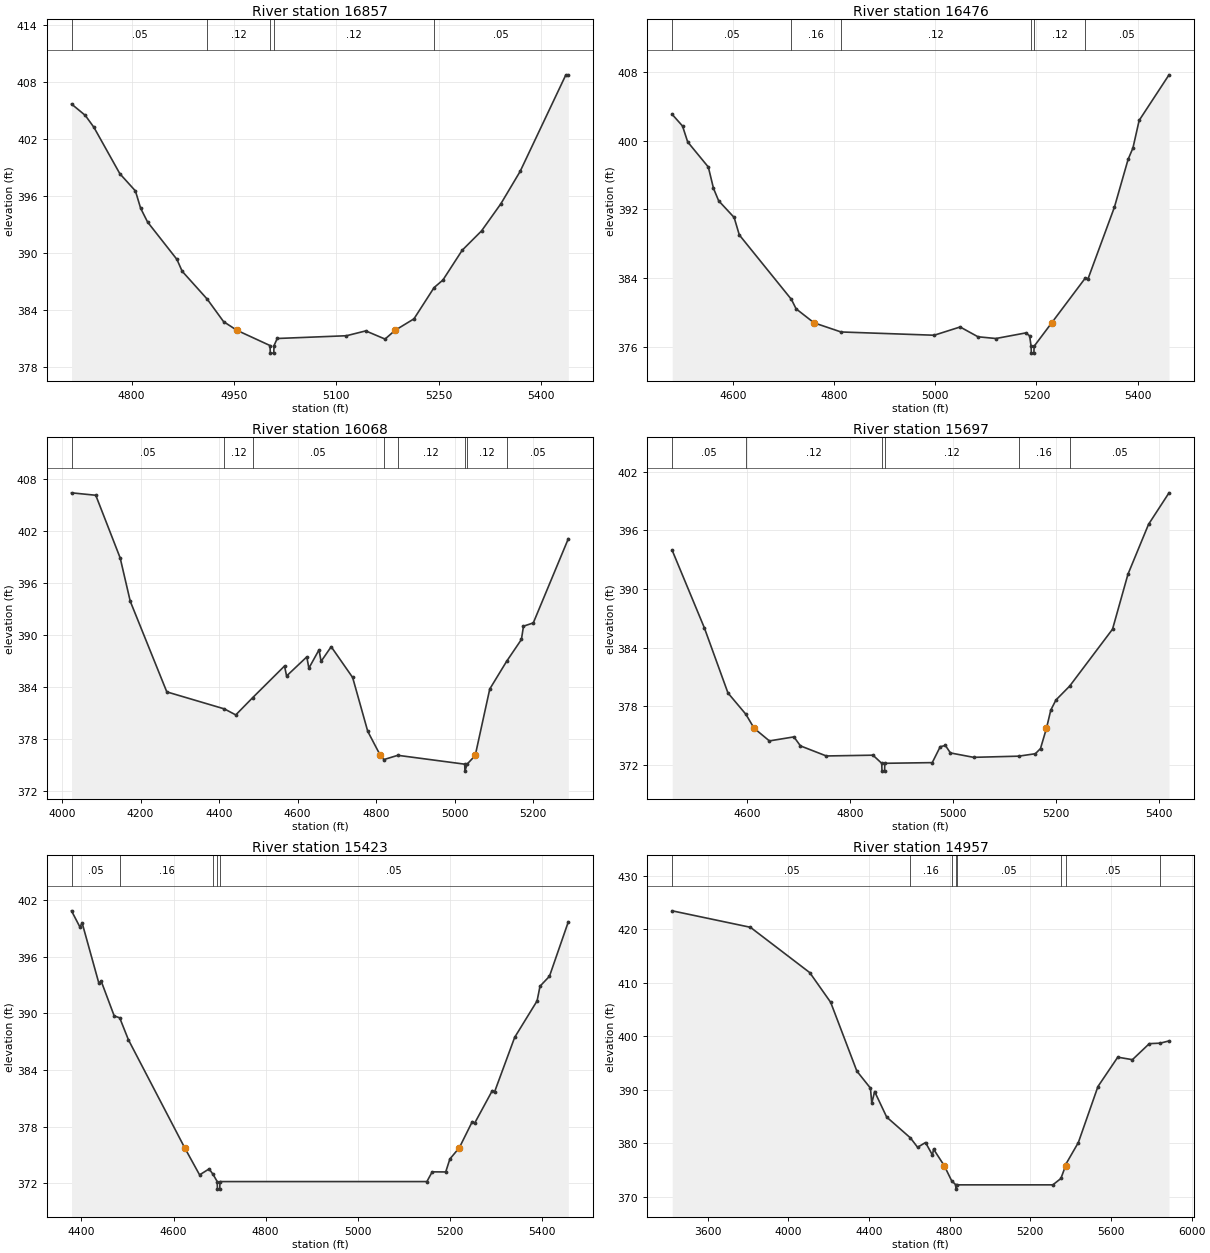
Type RM Length L Ch R = 1,16857,381,381,381
BEGIN DESCRIPTION:
STEWART CREEK 28.0
END DESCRIPTION:
XS GIS Cut Line= 3
      2926075.01      6964524.97      2926125.00      6964225.00
      2925824.98      6963924.98
#Sta/Elev= 30
  4711.9  405.73  4732.1  404.53  4744.8  403.27  4782.8  398.39  4805.6  396.58
  4813.2  394.77  4823.4  393.31  4866.5  389.37  4874.1  388.13  4910.9  385.19
  4934.9  382.82  4954.5  381.91  5002.9  380.31  5003.4  379.51  5008.4  379.51
  5008.9  380.31  5013.5  381.05  5115.0  381.34  5143.3  381.85  5171.6  380.99
  5186.3  381.91  5214.0  383.12  5243.5  386.41  5256.4  387.20  5284.7  390.34
  5313.0  392.37  5341.3  395.22  5369.6  398.63  5436.7  408.80  5440.3  408.80
#Mann=5,-1,0
  4711.9    0.05       0  4910.9    0.12       0  5002.9    0.07       0
  5008.9    0.12       0  5243.5    0.05       0
Bank Sta=4954.5,5186.3
Exp/Cntr=0.3,0.1

Type RM Length L Ch R = 1,16476,408,408,408
BEGIN DESCRIPTION:
STEWART CREEK 27.0
END DESCRIPTION:
XS GIS Cut Line= 3
      2926475.00      6964525.00      2926375.00      6964025.00
      2925975.00      6963775.00
#Sta/Elev= 30
  4480.3  403.05  4500.7  401.70  4510.9  399.85  4551.7  396.93  4561.9  394.45
  4572.1  393.01  4602.7  391.07  4612.9  389.04  4715.9  381.54  4725.1  380.45
  4760.6  378.82  4813.9  377.76  4997.9  377.38  5049.2  378.34  5084.5  377.20
  5119.9  377.00  5178.9  377.65  5186.5  377.31  5189.4  376.10  5189.9  375.30
  5194.9  375.30  5195.4  376.10  5230.1  378.82  5296.3  384.01  5302.1  383.97
  5354.0  392.26  5381.1  397.83  5390.6  399.14  5402.9  402.35  5461.9  407.65
#Mann=6,-1,0
  4480.3    0.05       0  4715.9    0.16       0  4813.9    0.12       0
  5189.4    0.07       0  5195.4    0.12       0  5296.3    0.05       0
Bank Sta=4760.6,5230.1
Exp/Cntr=0.3,0.1

Type RM Length L Ch R = 1,16068,371,371,371
BEGIN DESCRIPTION:
STEWART CREEK 26.0
END DESCRIPTION:
XS GIS Cut Line= 3
      2926779.56      6964590.78      2926485.31      6963749.68
      2926134.48      6963619.75
#Sta/Elev= 30
  4024.2  406.37  4086.0  406.09  4148.1  398.88  4173.8  393.89  4266.9  383.46
  4413.6  381.50  4442.5  380.81  4485.2  382.78  4566.7  386.44  4571.9  385.29
  4623.4  387.49  4628.7  386.19  4654.5  388.30  4659.8  386.97  4685.5  388.66
  4740.1  385.12  4778.6  378.92  4810.8  376.14  4819.7  375.67  4855.2  376.16
  5025.6  375.14  5026.1  374.34  5031.6  375.14  5052.3  376.14  5089.3  383.79
  5132.3  386.98  5169.9  389.49  5175.2  391.02  5200.2  391.40  5289.4  401.09
#Mann=8,-1,0
  4024.2    0.05       0  4413.6    0.12       0  4485.2    0.05       0
  4819.7    0.16       0  4855.2    0.12       0  5025.6    0.07       0
  5031.6    0.12       0  5132.3    0.05       0
Bank Sta=4810.8,5052.3
Exp/Cntr=0.3,0.1

Type RM Length L Ch R = 1,15697,274,274,274
BEGIN DESCRIPTION:
STEWART CREEK 25.0
END DESCRIPTION:
XS GIS Cut Line= 3
      2926616.98      6963972.66      2926555.43      6963430.64
      2926135.24      6963433.64
#Sta/Elev= 30
  4454.5  393.95  4517.0  386.03  4562.9  379.37  4597.6  377.20  4613.8  375.76
  4643.4  374.47  4691.1  374.88  4703.8  373.96  4754.1  372.93  4844.7  373.01
  4861.8  372.18  4862.3  371.38  4867.3  371.38  4867.8  372.18  4960.0  372.25
  4975.5  373.88  4985.6  374.00  4995.3  373.24  5040.4  372.79  5128.2  372.91
  5160.4  373.16  5170.4  373.69  5182.0  375.76  5190.4  377.62  5200.4  378.65
  5227.2  380.08  5310.4  385.89  5340.4  391.51  5380.4  396.61  5420.2  399.83
#Mann=6,-1,0
  4454.5    0.05       0  4597.6    0.12       0  4861.8    0.07       0
  4867.8    0.12       0  5128.2    0.16       0  5227.2    0.05       0
Bank Sta=4613.8,5182
Exp/Cntr=0.3,0.1

Type RM Length L Ch R = 1,15423,466,466,466
BEGIN DESCRIPTION:
double STEWART CREEK 24.0
END DESCRIPTION:
XS GIS Cut Line= 3
      2927225.03      6963325.01      2926625.00      6963175.00
      2926174.98      6963275.01
#Sta/Elev= 30
  4378.3  400.85  4396.4  399.15  4401.5  399.55  4437.6  393.21  4442.8  393.40
  4471.1  389.72  4483.0  389.52  4502.0  387.19  4624.2  375.76  4656.6  372.89
  4677.3  373.52  4685.9  372.94  4694.9  372.18  4695.4  371.38  4700.4  371.38
  4700.9  372.18  5150.5  372.18  5162.0  373.21  5191.4  373.20  5200.4  374.57
  5220.9  375.76  5249.1  378.53  5254.2  378.36  5292.6  381.81  5297.7  381.70
  5341.2  387.45  5389.9  391.31  5396.3  392.87  5416.8  393.92  5457.8  399.69
#Mann=5,-1,0
  4378.3    0.05       0  4483.0    0.16       0  4685.9    0.05       0
  4694.9   0.033       0  4700.9    0.05       0
Bank Sta=4624.2,5220.9
Exp/Cntr=0.3,0.1

Type RM Length L Ch R = 1,14957,632,632,632
BEGIN DESCRIPTION:
STEWART CREEK 23.0
END DESCRIPTION:
XS GIS Cut Line= 3
      2928272.51      6963173.33      2926753.64      6962754.72
      2925960.05      6963152.50
#Sta/Elev= 30
  3424.5  423.45  3812.2  420.37  4106.5  411.89  4210.3  406.33  4340.1  393.46
  4407.3  390.28  4414.1  387.46  4428.1  389.64  4488.0  384.86  4605.8  380.96
  4641.1  379.21  4680.6  380.10  4715.0  377.74  4720.2  378.87  4773.8  375.74
  4809.9  372.95  4830.7  372.18  4831.2  371.38  4836.7  372.18  5311.7  372.18
  5351.6  373.37  5374.8  375.74  5376.9  376.09  5438.1  380.09  5535.4  390.58
  5633.6  396.07  5706.2  395.60  5790.0  398.60  5843.8  398.69  5887.7  399.11
#Mann=8,-1,0
  3424.5    0.05       0  4605.8    0.16       0  4809.9    0.05       0
  4830.7   0.033       0  4836.7    0.05       0  5351.6    0.16       0
  5376.9    0.05       0  5843.8    0.08       0
Bank Sta=4773.8,5374.8
Exp/Cntr=0.3,0.1

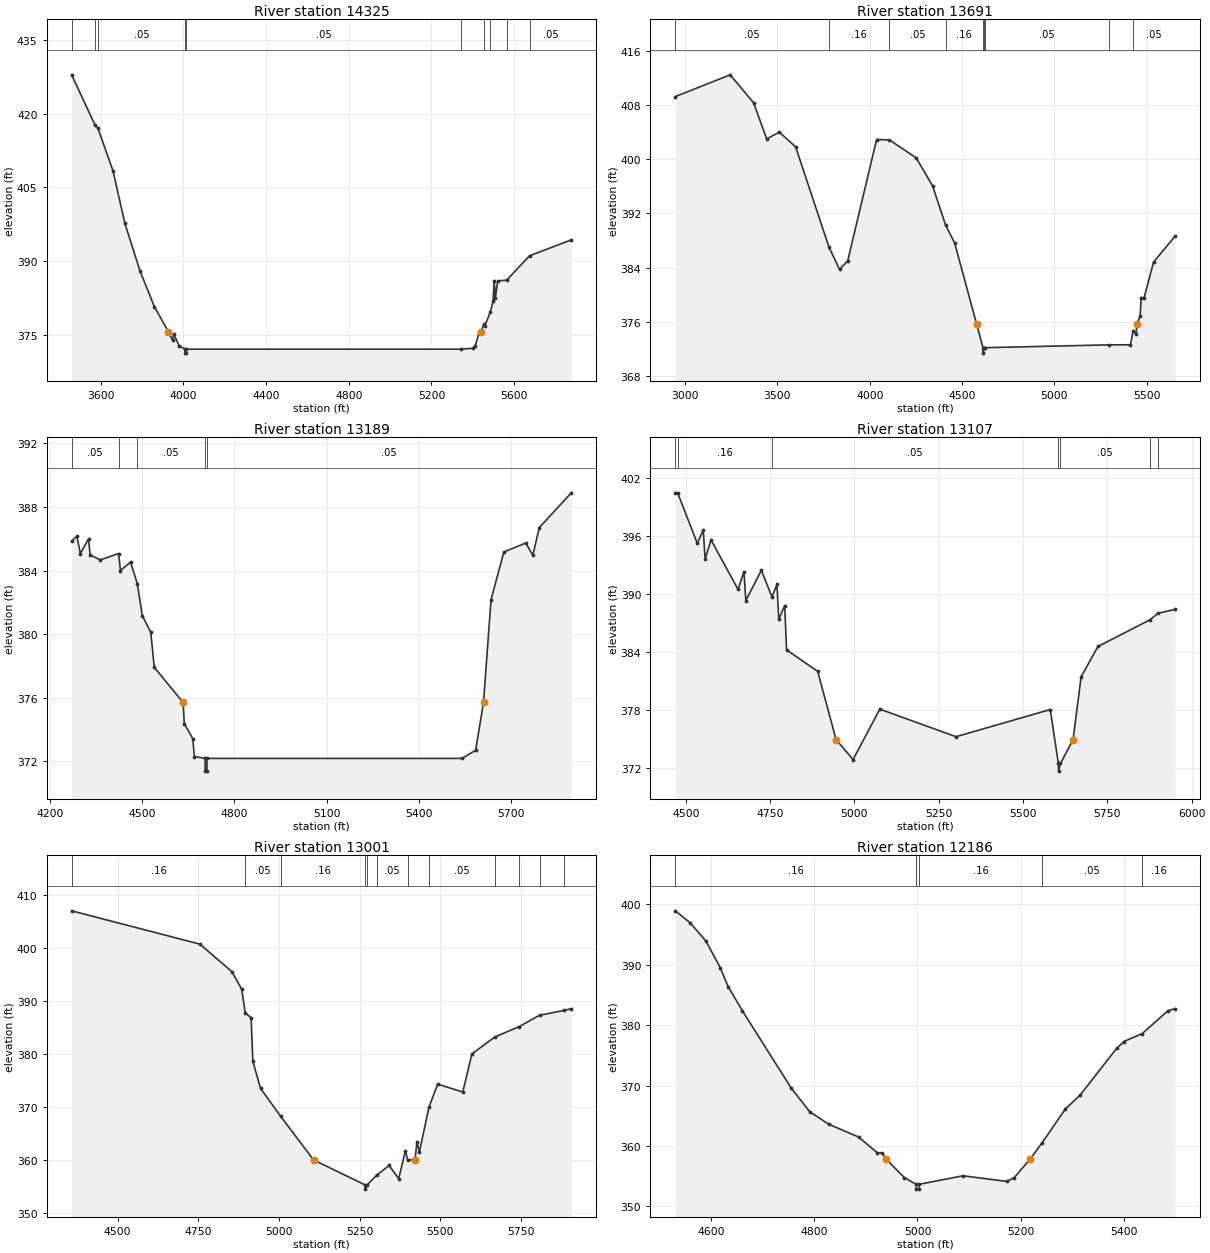
Type RM Length L Ch R = 1,14325,634,634,634
BEGIN DESCRIPTION:
STEWART CREEK 22.0
END DESCRIPTION:
XS GIS Cut Line= 3
      2928204.86      6962058.76      2926675.00      6962125.00
      2925871.52      6962496.25
#Sta/Elev= 30
  3460.0  427.85  3572.9  417.68  3586.7  417.06  3660.0  408.37  3717.5  397.70
  3790.2  388.11  3860.2  380.81  3928.1  375.73  3948.2  373.96  3953.2  375.25
  3980.3  372.88  4007.3  372.18  4007.8  371.38  4012.9  371.38  4013.4  372.18
  5343.8  372.18  5398.9  372.36  5412.0  372.86  5429.4  375.37  5439.9  375.73
  5454.0  377.32  5457.8  376.89  5484.9  379.69  5498.0  381.87  5503.7  386.08
  5509.2  382.50  5520.1  386.01  5564.3  386.20  5674.5  391.13  5876.4  394.36
#Mann=10,-1,0
  3460.0    0.05       0  3572.9    0.16       0  3586.7    0.05       0
  4007.3   0.033       0  4013.4    0.05       0  5343.8    0.16       0
  5454.0    0.08       0  5484.9    0.16       0  5564.3     0.1       0
  5674.5    0.05       0
Bank Sta=3928.1,5439.9
Exp/Cntr=0.3,0.1

Type RM Length L Ch R = 1,13691,502,502,502
BEGIN DESCRIPTION:
STEWART CREEK 21.0
END DESCRIPTION:
XS GIS Cut Line= 3
      2928355.90      6960829.58      2926663.17      6961407.72
      2925875.01      6961874.99
#Sta/Elev= 30
  2948.0  409.23  3244.8  412.43  3371.6  408.29  3442.3  402.97  3510.2  403.98
  3598.9  401.81  3778.9  387.05  3836.6  383.72  3880.8  384.99  4037.4  402.89
  4106.6  402.83  4251.4  400.19  4340.1  396.07  4410.8  390.27  4460.1  387.61
  4578.3  375.71  4613.6  372.18  4614.1  371.38  4619.8  372.18  4621.8  372.18
  5296.0  372.60  5411.3  372.61  5426.5  374.68  5442.5  374.20  5446.3  375.71
  5464.0  376.82  5469.8  379.56  5485.4  379.53  5536.8  384.81  5653.0  388.62
#Mann=9,-1,0
  2948.0    0.05       0  3778.9    0.16       0  4106.6    0.05       0
  4410.8    0.16       0  4613.6   0.033       0  4619.8    0.16       0
  4621.8    0.05       0  5296.0    0.16       0  5426.5    0.05       0
Bank Sta=4578.3,5446.3
Exp/Cntr=0.3,0.1

Type RM Length L Ch R = 1,13189,82,82,82
BEGIN DESCRIPTION:
Mapping XS 7cd31263
END DESCRIPTION:
XS GIS Cut Line= 5
      2927202.21      6960853.90      2926608.48      6961034.45
      2926191.81      6961142.09      2926073.76      6961260.15
      2925743.87      6961499.75
#Sta/Elev= 30
  4270.3  385.85  4287.2  386.16  4298.7  385.07  4325.2  385.99  4330.5  384.98
  4363.3  384.67  4423.1  385.07  4429.1  384.00  4461.9  384.53  4484.1  383.16
  4500.0  381.16  4527.7  380.12  4539.1  377.91  4633.1  375.70  4636.7  374.37
  4664.3  373.43  4669.6  372.30  4704.5  372.18  4705.0  371.38  4710.3  371.38
  4710.8  372.18  5540.6  372.18  5584.7  372.69  5610.4  375.70  5634.9  382.17
  5676.7  385.17  5747.8  385.73  5770.9  384.96  5791.8  386.70  5895.9  388.89
#Mann=5,-1,0
  4270.3    0.05       0  4423.1    0.16       0  4484.1    0.05       0
  4704.5    0.04       0  4710.8    0.05       0
Bank Sta=4633.1,5610.4
Exp/Cntr=0.3,0.1

Type RM Length L Ch R = 1,13107,106,106,106
BEGIN DESCRIPTION:
Mapping XS 418f55e9
END DESCRIPTION:
XS GIS Cut Line= 5
      2927011.27      6960774.03      2926545.98      6960985.84
      2926243.90      6961076.12      2926056.40      6961215.01
      2925721.09      6961470.81
#Sta/Elev= 30
  4469.1  400.42  4475.7  400.45  4534.1  395.22  4551.7  396.59  4557.2  393.60
  4574.7  395.58  4654.9  390.46  4672.4  392.31  4677.9  389.31  4724.0  392.44
  4755.4  389.68  4770.2  390.97  4775.6  387.38  4793.2  388.78  4798.7  384.21
  4890.9  381.99  4945.6  374.92  4995.9  372.87  5075.3  378.08  5301.3  375.23
  5580.7  378.04  5604.7  372.47  5605.2  371.67  5611.0  372.47  5648.4  374.92
  5672.2  381.42  5722.1  384.56  5876.0  387.31  5900.6  388.00  5950.7  388.39
#Mann=7,-1,0
  4469.1    0.05       0  4475.7    0.16       0  4755.4    0.05       0
  5604.7    0.04       0  5611.0    0.05       0  5876.0    0.08       0
  5900.6    0.05       0
Bank Sta=4945.6,5648.4
Exp/Cntr=0.3,0.1

Type RM Length L Ch R = 1,13001,815,815,815
BEGIN DESCRIPTION:
Mapping XS 18cbac3a
END DESCRIPTION:
XS GIS Cut Line= 5
      2927032.12      6960694.16      2926480.01      6960926.81
      2926216.12      6961020.56      2926035.56      6961149.04
      2925709.59      6961454.20
#Sta/Elev= 30
  4357.9  406.93  4755.0  400.65  4853.9  395.48  4884.5  392.17  4895.4  387.68
  4913.7  386.76  4919.1  378.57  4942.8  373.46  5005.4  368.17  5107.2  359.96
  5266.7  355.26  5267.2  354.46  5273.0  355.26  5302.2  357.07  5341.2  358.92
  5370.7  356.42  5391.6  361.70  5398.3  360.00  5421.3  359.96  5427.3  363.43
  5434.8  361.47  5464.6  369.93  5491.5  374.25  5569.2  372.77  5597.5  379.95
  5668.2  383.13  5744.1  385.11  5806.9  387.24  5883.8  388.16  5905.2  388.49
#Mann=12,-1,0
  4357.9    0.16       0  4895.4    0.05       0  5005.4    0.16       0
  5266.7    0.04       0  5273.0    0.16       0  5302.2    0.05       0
  5398.3    0.16       0  5464.6    0.05       0  5668.2    0.08       0
  5744.1    0.05       0  5806.9    0.08       0  5883.8    0.05       0
Bank Sta=5107.2,5421.3
Exp/Cntr=0.3,0.1

Type RM Length L Ch R = 1,12186,505,505,505
BEGIN DESCRIPTION:
STEWART CREEK 18.0
END DESCRIPTION:
XS GIS Cut Line= 3
      2926325.04      6960274.98      2925925.00      6960525.00
      2925575.01      6960874.99
#Sta/Elev= 30
  4531.6  398.93  4560.5  396.92  4590.6  393.93  4618.3  389.54  4633.6  386.39
  4661.4  382.36  4755.7  369.59  4791.7  365.67  4828.2  363.61  4886.0  361.50
  4922.6  358.86  4932.0  358.87  4938.4  357.91  4974.5  354.78  4997.2  353.67
  4997.7  352.87  5003.0  352.87  5003.5  353.67  5088.2  355.08  5173.0  354.14
  5187.2  354.77  5218.5  357.91  5241.0  360.52  5286.2  366.14  5314.5  368.41
  5385.2  376.15  5399.3  377.30  5434.8  378.60  5484.2  382.37  5498.3  382.75
#Mann=5,-1,0
  4531.6    0.16       0  4997.2    0.07       0  5003.5    0.16       0
  5241.0    0.05       0  5434.8    0.16       0
Bank Sta=4938.4,5218.5
Exp/Cntr=0.3,0.1

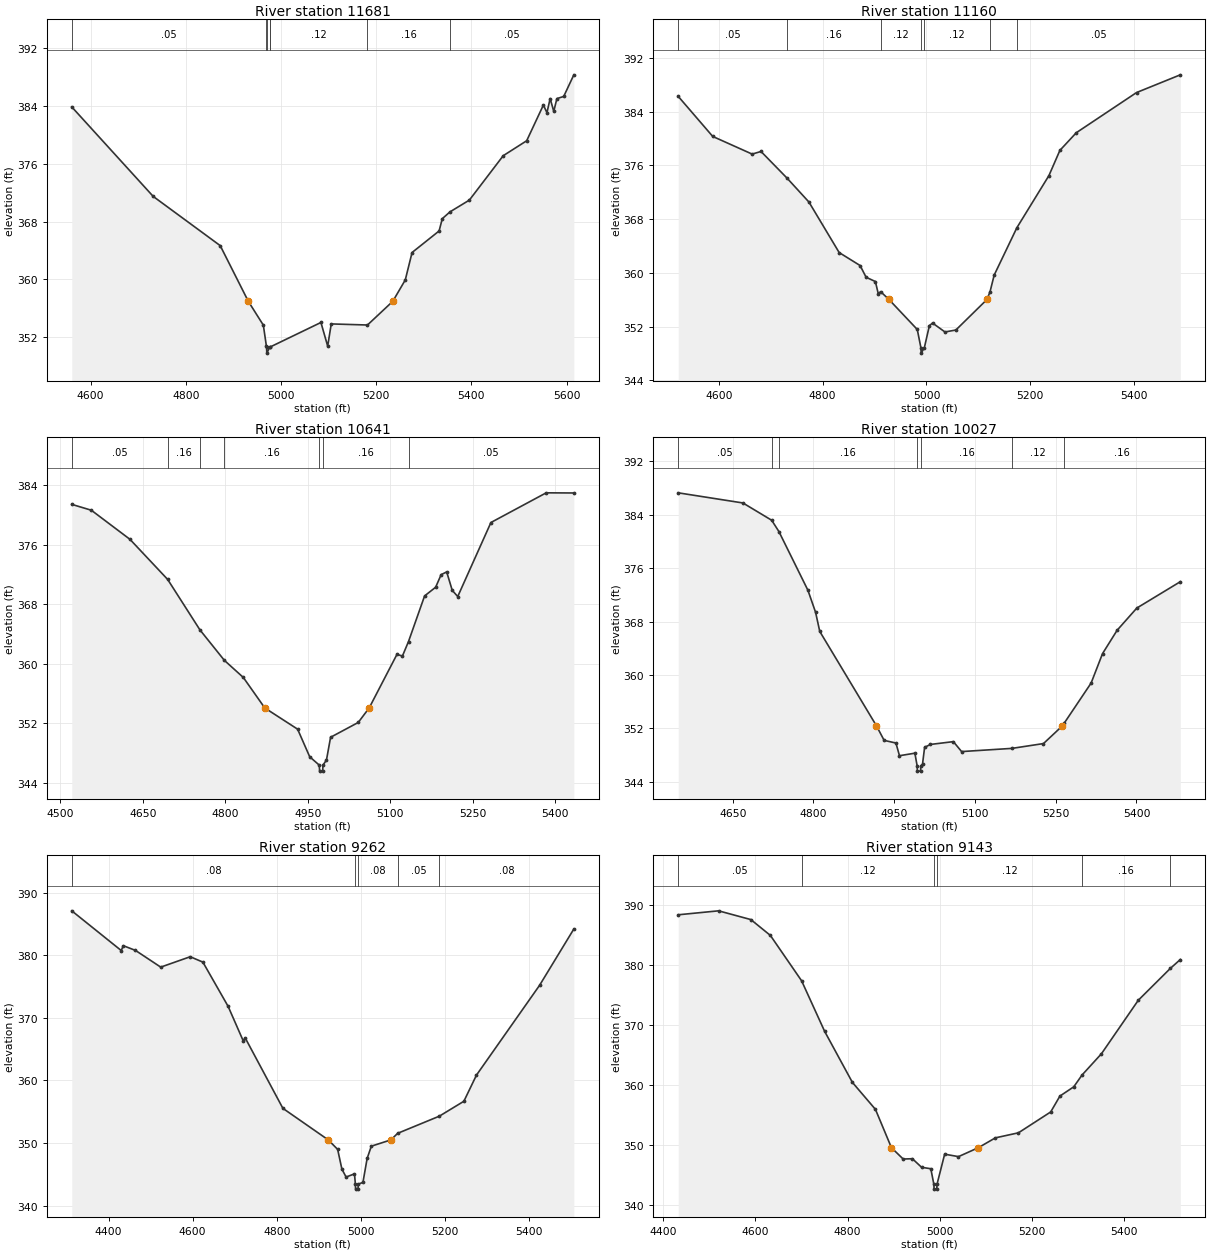
Type RM Length L Ch R = 1,11681,521,521,521
BEGIN DESCRIPTION:
STEWART CREEK 17.0
END DESCRIPTION:
XS GIS Cut Line= 3
      2926025.04      6960125.00      2925575.00      6960175.00
      2925124.99      6959774.99
#Sta/Elev= 30
  4560.5  383.87  4731.6  371.49  4872.4  364.68  4931.4  356.98  4963.0  353.68
  4969.4  350.79  4969.8  350.61  4970.3  349.81  4976.4  350.61  4976.7  350.64
  5084.0  354.05  5098.2  350.78  5105.7  353.85  5181.8  353.70  5235.0  356.98
  5261.2  359.93  5275.5  363.73  5332.3  366.71  5339.0  368.41  5355.1  369.35
  5395.9  370.98  5467.0  377.12  5516.3  379.19  5551.4  384.13  5558.9  383.07
  5565.6  385.03  5573.2  383.26  5579.8  385.02  5594.1  385.32  5615.4  388.31
#Mann=7,-1,0
  4560.5    0.05       0  4969.4    0.16       0  4969.8    0.07       0
  4976.4    0.16       0  4976.7    0.12       0  5181.8    0.16       0
  5355.1    0.05       0
Bank Sta=4931.4,5235
Exp/Cntr=0.3,0.1

Type RM Length L Ch R = 1,11160,519,519,519
BEGIN DESCRIPTION:
STEWART CREEK 16.0
END DESCRIPTION:
XS GIS Cut Line= 3
      2926175.03      6959925.01      2925725.00      6959725.00
      2925275.02      6959575.01
#Sta/Elev= 30
  4522.0  386.28  4588.4  380.32  4664.3  377.69  4681.4  378.08  4731.8  374.09
  4773.7  370.55  4831.9  363.03  4872.2  361.10  4883.8  359.35  4901.6  358.72
  4907.1  356.93  4911.8  357.21  4927.6  356.06  4982.3  351.58  4989.3  348.86
  4989.8  348.06  4995.9  348.86  5005.6  352.15  5011.7  352.54  5035.6  351.21
  5056.6  351.50  5116.7  356.06  5122.5  357.23  5130.4  359.68  5174.1  366.73
  5235.8  374.49  5256.9  378.24  5288.5  380.87  5404.5  386.85  5488.8  389.49
#Mann=7,-1,0
  4522.0    0.05       0  4731.8    0.16       0  4911.8    0.12       0
  4989.3    0.07       0  4995.9    0.12       0  5122.5    0.16       0
  5174.1    0.05       0
Bank Sta=4927.6,5116.7
Exp/Cntr=0.3,0.1

Type RM Length L Ch R = 1,10641,614,614,614
BEGIN DESCRIPTION:
STEWART CREEK 15.0
END DESCRIPTION:
XS GIS Cut Line= 3
      2926274.98      6959624.98      2925975.00      6959275.00
      2925525.02      6959325.00
#Sta/Elev= 30
  4520.7  381.40  4556.3  380.61  4626.6  376.70  4695.2  371.31  4753.9  364.53
  4798.4  360.43  4832.9  358.13  4872.0  354.03  4931.7  351.18  4953.7  347.47
  4971.2  346.34  4971.7  345.54  4977.3  345.54  4977.8  346.34  4984.2  347.03
  4991.7  350.09  5042.0  352.08  5061.9  354.03  5112.4  361.22  5122.5  361.02
  5133.5  362.96  5162.8  369.09  5182.9  370.26  5192.9  371.95  5203.0  372.32
  5213.1  369.84  5223.1  369.01  5283.5  378.96  5384.1  382.95  5434.4  382.93
#Mann=7,-1,0
  4520.7    0.05       0  4695.2    0.16       0  4753.9    0.12       0
  4798.4    0.16       0  4971.2    0.07       0  4977.8    0.16       0
  5133.5    0.05       0
Bank Sta=4872,5061.9
Exp/Cntr=0.3,0.1

Type RM Length L Ch R = 1,10027,765,765,765
BEGIN DESCRIPTION:
STEWART CREEK 14.0
END DESCRIPTION:
XS GIS Cut Line= 3
      2926674.99      6959124.99      2926325.00      6958825.00
      2925924.97      6958574.98
#Sta/Elev= 30
  4548.8  387.30  4669.0  385.78  4722.4  383.19  4735.8  381.50  4789.7  372.70
  4804.0  369.38  4811.7  366.53  4917.1  352.37  4931.3  350.20  4953.2  349.80
  4959.8  347.90  4988.4  348.28  4992.6  346.39  4993.1  345.59  4998.9  345.59
  4999.4  346.39  5002.6  346.64  5006.5  349.16  5017.4  349.59  5059.9  350.01
  5075.2  348.52  5168.8  349.00  5227.3  349.72  5262.4  352.37  5265.5  352.74
  5315.8  358.79  5337.0  363.20  5364.1  366.70  5400.7  370.03  5481.5  373.98
#Mann=7,-1,0
  4548.8    0.05       0  4722.4    0.12       0  4735.8    0.16       0
  4992.6    0.07       0  4999.4    0.16       0  5168.8    0.12       0
  5265.5    0.16       0
Bank Sta=4917.1,5262.4
Exp/Cntr=0.3,0.1

Type RM Length L Ch R = 1,9262,119,119,119
BEGIN DESCRIPTION:
Mapping XS 625f9a57
END DESCRIPTION:
XS GIS Cut Line= 3
      2926926.24      6958228.21      2926249.10      6958181.33
      2925733.48      6958202.16
#Sta/Elev= 30
  4312.3  387.09  4430.0  380.75  4435.0  381.52  4463.9  380.77  4524.0  378.10
  4594.2  379.76  4624.3  378.90  4684.4  371.83  4720.1  366.36  4725.1  366.79
  4814.7  355.55  4922.7  350.51  4945.0  349.00  4955.1  345.85  4965.1  344.58
  4985.1  345.09  4987.2  343.45  4987.7  342.65  4993.5  342.65  4994.0  343.45
  5005.2  343.72  5015.2  347.55  5025.2  349.51  5071.6  350.51  5087.8  351.56
  5187.0  354.30  5245.4  356.68  5275.4  360.86  5425.5  375.19  5507.1  384.19
#Mann=5,-1,0
  4312.3    0.08       0  4987.2    0.07       0  4994.0    0.08       0
  5087.8    0.05       0  5187.0    0.08       0
Bank Sta=4922.7,5071.6
Exp/Cntr=0.3,0.1

Type RM Length L Ch R = 1,9143,380,380,380
BEGIN DESCRIPTION:
Mapping XS df359994
END DESCRIPTION:
XS GIS Cut Line= 3
      2926832.40      6958087.58      2926290.77      6958066.74
      2925743.93      6958071.95
#Sta/Elev= 30
  4432.5  388.43  4520.0  389.09  4590.0  387.63  4632.3  384.99  4700.0  377.43
  4750.1  368.98  4810.2  360.48  4860.2  355.98  4894.9  349.59  4920.3  347.70
  4940.3  347.75  4960.3  346.32  4980.3  346.08  4986.9  343.48  4987.4  342.68
  4993.2  342.68  4993.7  343.48  5010.3  348.51  5040.3  348.10  5083.4  349.59
  5120.3  351.23  5170.3  352.07  5240.3  355.55  5260.3  358.20  5290.3  359.74
  5308.3  361.71  5350.3  365.25  5430.3  374.18  5499.8  379.49  5521.4  380.97
#Mann=6,-1,0
  4432.5    0.05       0  4700.0    0.12       0  4986.9    0.07       0
  4993.7    0.12       0  5308.3    0.16       0  5499.8    0.05       0
Bank Sta=4894.9,5083.4
Exp/Cntr=0.3,0.1