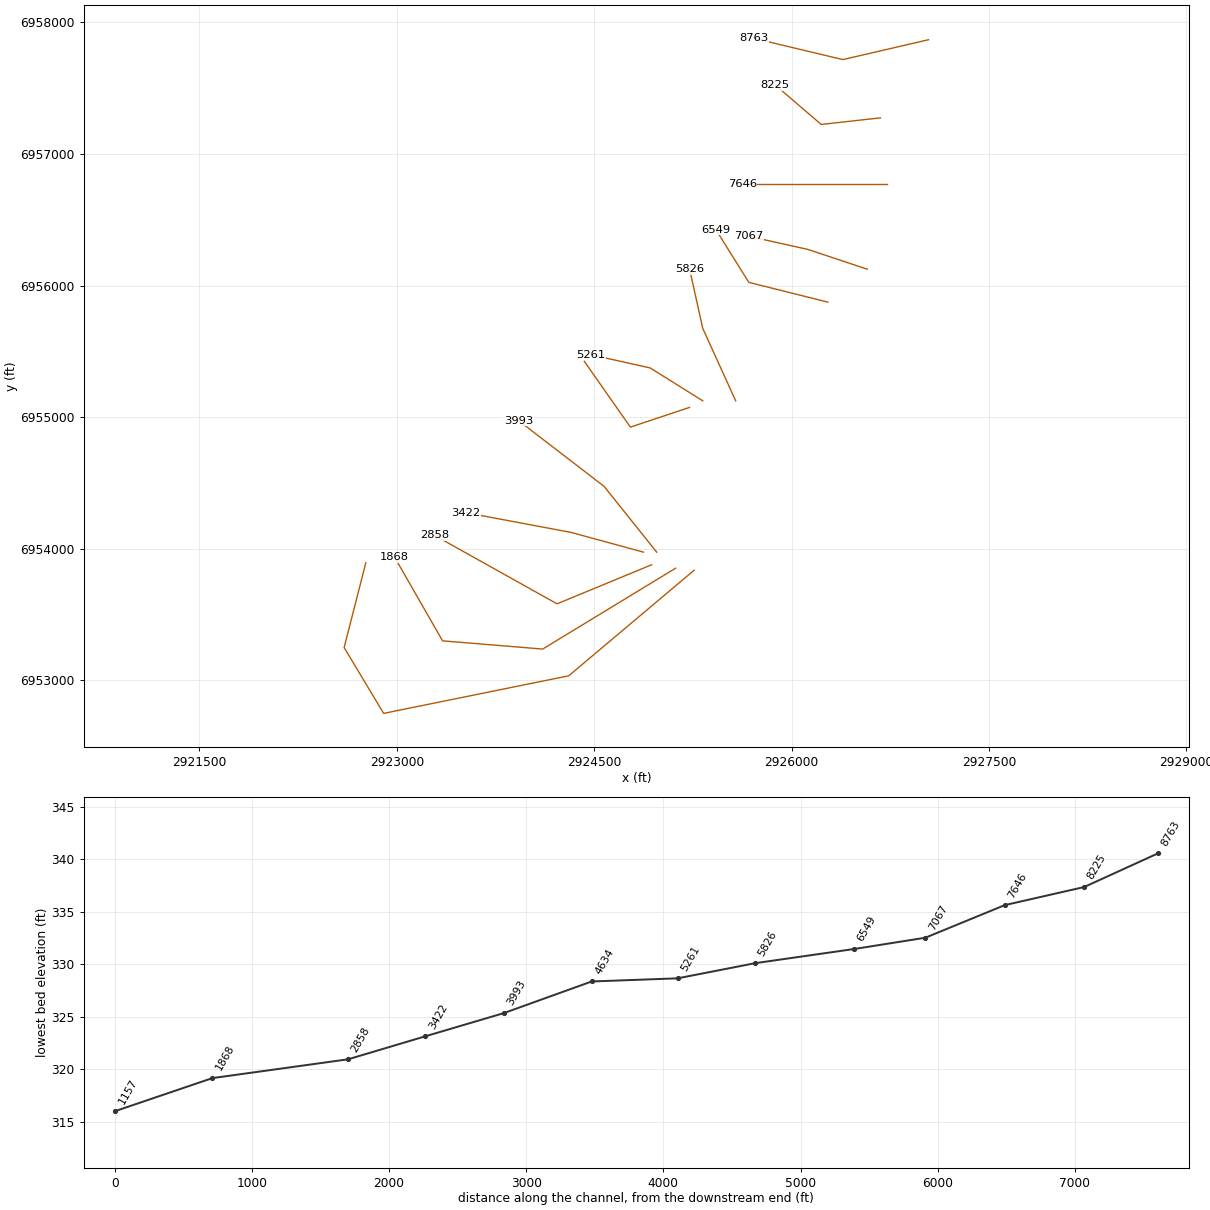
HEC-RAS study STEWART CREEK.prj: STEWART CREEK Base Level Engineering

--- STEWART CREEK.g01 (geometry) --- (continued)

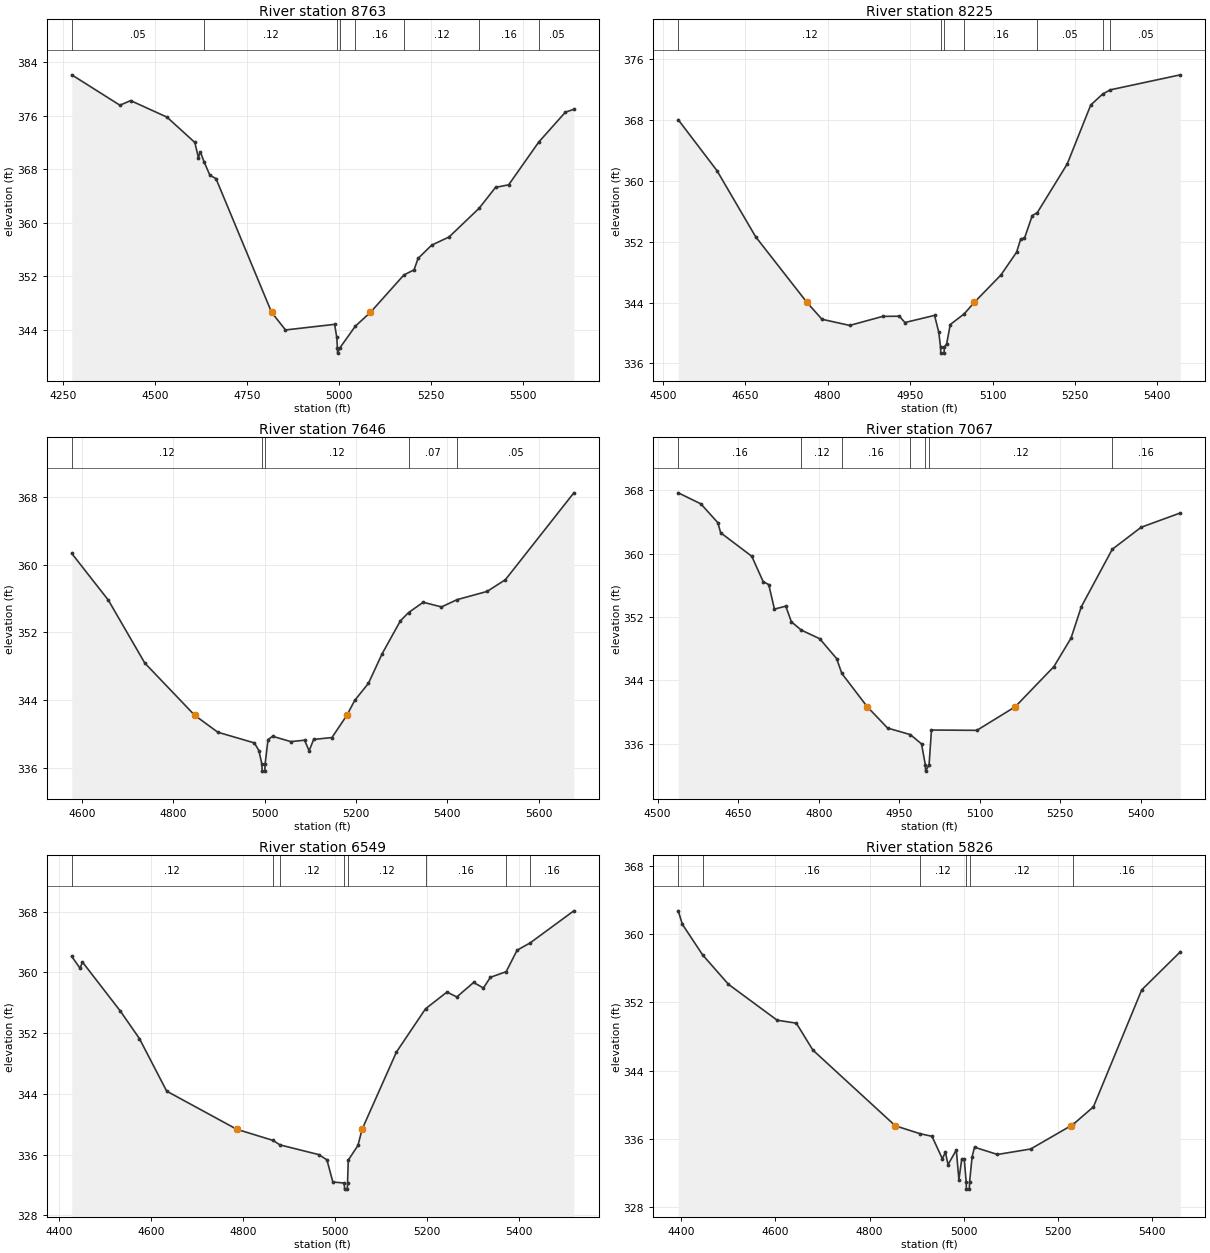
Type RM Length L Ch R = 1,8763,538,538,538
BEGIN DESCRIPTION:
Mapping XS 73200b94
END DESCRIPTION:
XS GIS Cut Line= 3
      2927040.73      6957868.82      2926389.73      6957717.79
      2925712.61      6957879.25
#Sta/Elev= 30
  4274.4  382.12  4405.3  377.58  4434.3  378.27  4533.2  375.80  4608.8  372.02
  4618.5  369.76  4623.7  370.63  4633.7  369.16  4649.8  367.12  4666.3  366.62
  4817.4  346.65  4855.2  344.01  4988.7  344.85  4994.6  342.89  4996.3  341.35
  4996.8  340.55  5003.2  341.35  5045.2  344.59  5086.2  346.65  5176.8  352.22
  5204.6  352.99  5215.4  354.69  5252.4  356.68  5299.7  357.90  5381.6  362.20
  5426.0  365.31  5461.6  365.69  5543.6  372.09  5615.8  376.54  5638.8  376.97
#Mann=8,-1,0
  4274.4    0.05       0  4633.7    0.12       0  4996.3    0.07       0
  5003.2    0.12       0  5045.2    0.16       0  5176.8    0.12       0
  5381.6    0.16       0  5543.6    0.05       0
Bank Sta=4817.4,5086.2
Exp/Cntr=0.3,0.1

Type RM Length L Ch R = 1,8225,579,579,579
BEGIN DESCRIPTION:
STEWART CREEK 11.0
END DESCRIPTION:
XS GIS Cut Line= 3
      2926675.05      6957275.01      2926225.00      6957225.00
      2925875.00      6957525.00
#Sta/Elev= 30
  4528.0  368.02  4598.5  361.33  4668.9  352.64  4762.3  344.01  4789.6  341.80
  4840.0  340.99  4900.3  342.18  4930.5  342.20  4940.6  341.37  4994.5  342.31
  5002.2  340.10  5005.4  338.15  5005.9  337.35  5011.8  337.35  5012.3  338.15
  5016.5  338.56  5023.1  341.11  5048.5  342.51  5066.7  344.01  5115.3  347.62
  5143.8  350.61  5151.5  352.38  5158.1  352.43  5172.3  355.42  5181.6  355.82
  5236.0  362.21  5278.8  369.96  5300.7  371.41  5314.6  371.95  5441.8  373.92
#Mann=7,-1,0
  4528.0    0.12       0  5005.4    0.07       0  5012.3    0.12       0
  5048.5    0.16       0  5181.6    0.05       0  5300.7    0.16       0
  5314.6    0.05       0
Bank Sta=4762.3,5066.7
Exp/Cntr=0.3,0.1

Type RM Length L Ch R = 1,7646,579,579,579
BEGIN DESCRIPTION:
STEWART CREEK 10.0
END DESCRIPTION:
XS GIS Cut Line= 3
      2926725.01      6956775.00      2926275.00      6956775.00
      2925625.01      6956775.00
#Sta/Elev= 30
  4577.3  361.31  4657.3  355.81  4737.3  348.38  4846.6  342.22  4897.3  340.22
  4977.3  338.96  4987.3  338.06  4993.9  336.43  4994.4  335.63  5000.3  335.63
  5000.8  336.43  5007.3  339.35  5017.3  339.74  5057.3  339.11  5087.3  339.28
  5097.3  338.03  5107.3  339.37  5147.3  339.59  5180.0  342.22  5197.3  343.98
  5227.3  345.99  5257.3  349.48  5297.3  353.36  5315.3  354.34  5347.3  355.55
  5387.3  355.00  5421.6  355.86  5487.3  356.83  5527.3  358.21  5677.3  368.46
#Mann=5,-1,0
  4577.3    0.12       0  4993.9    0.07       0  5000.8    0.12       0
  5315.3    0.07       0  5421.6    0.05       0
Bank Sta=4846.6,5180
Exp/Cntr=0.3,0.1

Type RM Length L Ch R = 1,7067,518,518,518
BEGIN DESCRIPTION:
STEWART CREEK 9.0
END DESCRIPTION:
XS GIS Cut Line= 3
      2926574.99      6956125.00      2926125.00      6956275.00
      2925675.00      6956375.00
#Sta/Elev= 30
  4538.3  367.67  4580.4  366.28  4612.1  363.90  4617.3  362.63  4675.3  359.66
  4696.4  356.47  4706.9  356.08  4717.5  352.99  4738.6  353.36  4749.1  351.38
  4767.5  350.34  4801.8  349.25  4833.4  346.74  4843.0  344.87  4890.4  340.66
  4928.3  337.97  4970.7  337.14  4991.5  335.97  4998.6  333.33  4999.1  332.53
  5005.6  333.33  5010.0  337.72  5094.6  337.68  5166.1  340.66  5238.0  345.72
  5270.0  349.32  5289.2  353.29  5346.8  360.54  5400.6  363.32  5473.6  365.13
#Mann=7,-1,0
  4538.3    0.16       0  4767.5    0.12       0  4843.0    0.16       0
  4970.7    0.12       0  4998.6    0.07       0  5005.6    0.12       0
  5346.8    0.16       0
Bank Sta=4890.4,5166.1
Exp/Cntr=0.3,0.1

Type RM Length L Ch R = 1,6549,723,723,723
BEGIN DESCRIPTION:
STEWART CREEK 8.0
END DESCRIPTION:
XS GIS Cut Line= 3
      2926274.99      6955875.00      2925675.00      6956025.00
      2925424.98      6956425.04
#Sta/Elev= 30
  4428.2  362.09  4446.2  360.54  4451.4  361.36  4533.8  354.89  4575.1  351.28
  4634.3  344.36  4786.5  339.34  4864.9  337.88  4880.5  337.28  4964.2  336.01
  4982.2  335.32  4995.1  332.40  5020.0  332.26  5020.5  331.46  5026.5  331.46
  5027.0  332.26  5028.6  335.28  5049.6  337.21  5058.6  339.34  5133.3  349.52
  5196.3  355.20  5243.0  357.41  5264.2  356.76  5300.8  358.67  5322.0  357.94
  5337.3  359.35  5371.5  360.09  5395.1  362.91  5423.8  363.89  5518.4  368.10
#Mann=8,-1,0
  4428.2    0.12       0  4864.9    0.16       0  4880.5    0.12       0
  5020.0    0.07       0  5027.0    0.12       0  5196.3    0.16       0
  5371.5    0.12       0  5423.8    0.16       0
Bank Sta=4786.5,5058.6
Exp/Cntr=0.3,0.1

Type RM Length L Ch R = 1,5826,565,565,565
BEGIN DESCRIPTION:
STEWART CREEK 7.0
END DESCRIPTION:
XS GIS Cut Line= 3
      2925575.01      6955124.99      2925325.00      6955675.00
      2925225.01      6956124.96
#Sta/Elev= 30
  4394.1  362.71  4402.9  361.13  4446.1  357.53  4500.7  354.10  4603.9  349.90
  4644.6  349.55  4679.7  346.40  4854.6  337.53  4907.3  336.60  4932.4  336.30
  4954.3  333.68  4960.9  334.43  4966.4  332.98  4984.0  334.69  4989.5  331.21
  4995.5  333.63  5000.8  333.63  5005.0  330.91  5005.5  330.11  5011.6  330.11
  5012.1  330.91  5017.5  333.89  5022.6  335.02  5071.3  334.17  5141.7  334.81
  5227.0  337.53  5232.0  337.70  5274.9  339.75  5377.3  353.45  5459.2  357.91
#Mann=6,-1,0
  4394.1    0.05       0  4446.1    0.16       0  4907.3    0.12       0
  5005.0    0.07       0  5012.1    0.12       0  5232.0    0.16       0
Bank Sta=4854.6,5227
Exp/Cntr=0.3,0.1

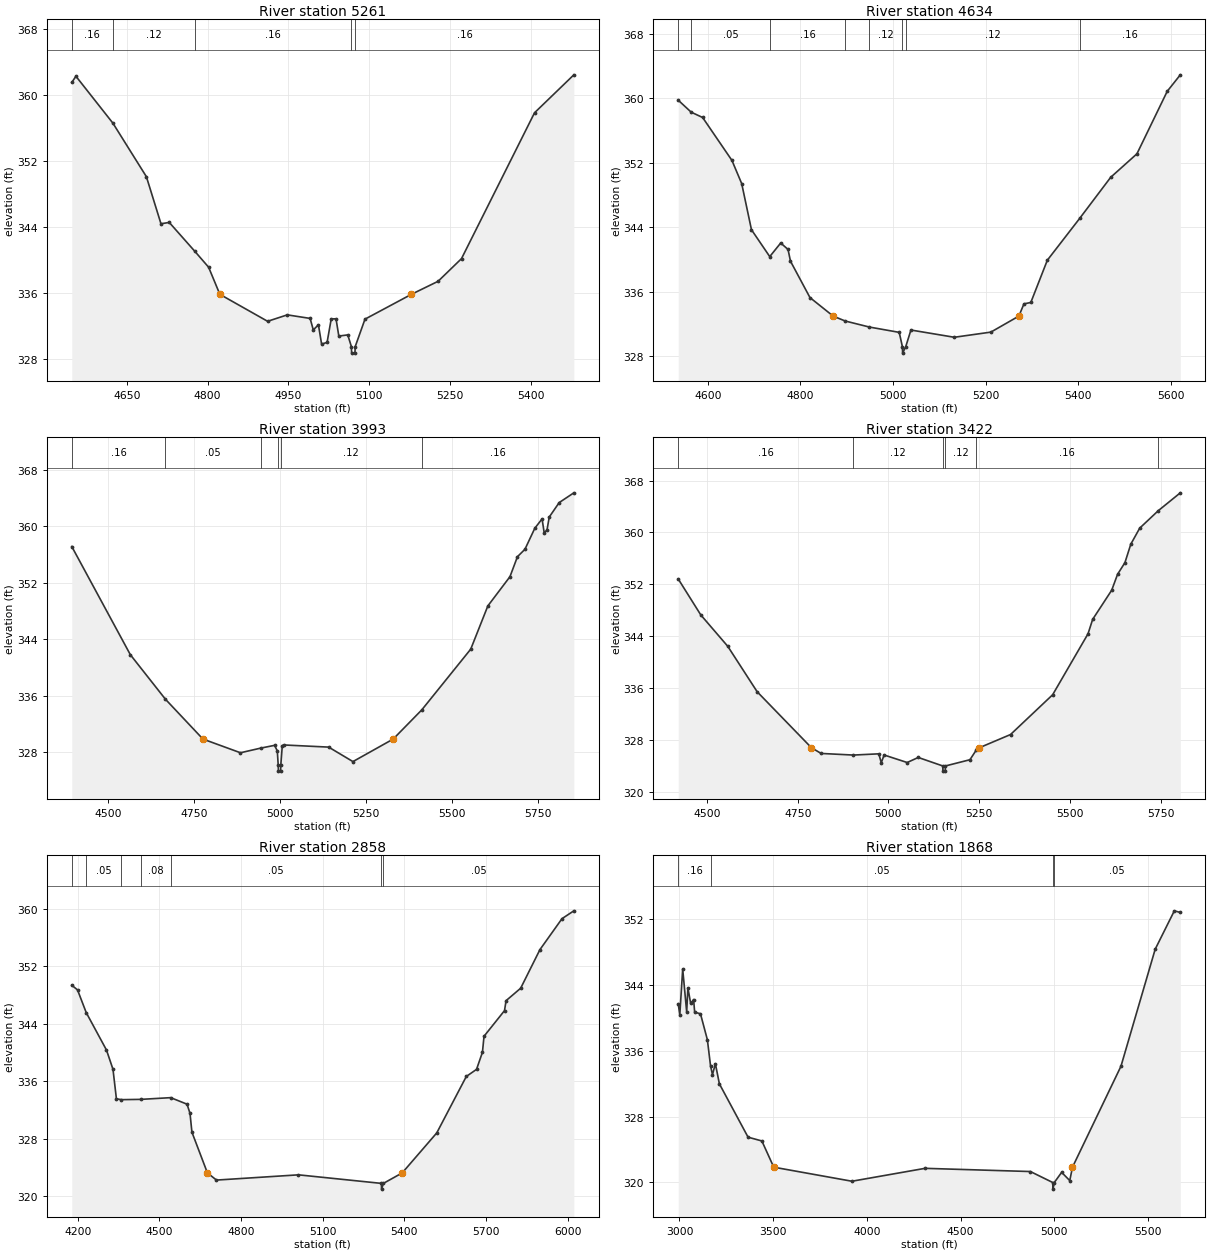
Type RM Length L Ch R = 1,5261,627,627,627
BEGIN DESCRIPTION:
STEWART CREEK 6.0
END DESCRIPTION:
XS GIS Cut Line= 3
      2925325.03      6955124.98      2924925.00      6955375.00
      2924475.01      6955475.00
#Sta/Elev= 30
  4547.6  361.49  4555.3  362.25  4624.0  356.56  4686.2  350.07  4713.3  344.36
  4728.7  344.52  4776.3  341.01  4801.8  339.09  4822.7  335.80  4911.4  332.53
  4948.0  333.31  4990.4  332.88  4996.3  331.48  5005.8  332.11  5011.7  329.77
  5021.9  329.97  5029.6  332.82  5038.5  332.83  5043.7  330.74  5060.3  330.88
  5067.0  329.47  5067.5  328.67  5073.6  328.67  5074.2  329.47  5092.3  332.79
  5178.5  335.80  5228.1  337.38  5271.6  340.13  5407.3  357.82  5480.3  362.42
#Mann=5,-1,0
  4547.6    0.16       0  4624.0    0.12       0  4776.3    0.16       0
  5067.0    0.07       0  5074.2    0.16       0
Bank Sta=4822.7,5178.5
Exp/Cntr=0.3,0.1

Type RM Length L Ch R = 1,4634,641,641,641
BEGIN DESCRIPTION:
STEWART CREEK 5.0
END DESCRIPTION:
XS GIS Cut Line= 3
      2925225.04      6955075.01      2924775.00      6954925.00
      2924425.01      6955424.99
#Sta/Elev= 30
  4536.0  359.79  4564.0  358.30  4588.7  357.64  4652.0  352.31  4673.1  349.43
  4694.2  343.70  4733.7  340.36  4757.4  342.05  4773.2  341.25  4778.5  339.79
  4820.6  335.27  4870.7  332.97  4896.7  332.36  4948.9  331.61  5013.4  330.95
  5020.3  329.17  5020.8  328.37  5027.5  329.17  5038.7  331.24  5132.4  330.34
  5211.4  330.98  5271.9  332.97  5282.9  334.49  5297.7  334.66  5333.4  339.91
  5403.2  345.10  5470.3  350.21  5527.0  353.13  5592.4  360.89  5620.7  362.94
#Mann=8,-1,0
  4536.0    0.16       0  4564.0    0.05       0  4733.7    0.16       0
  4896.7    0.05       0  4948.9    0.12       0  5020.3    0.07       0
  5027.5    0.12       0  5403.2    0.16       0
Bank Sta=4870.7,5271.9
Exp/Cntr=0.3,0.1

Type RM Length L Ch R = 1,3993,571,571,571
BEGIN DESCRIPTION:
STEWART CREEK 4.0
END DESCRIPTION:
XS GIS Cut Line= 3
      2924974.97      6953975.04      2924575.00      6954475.00
      2923925.02      6954974.98
#Sta/Elev= 30
  4395.2  357.16  4565.6  341.84  4667.6  335.54  4776.7  329.90  4885.8  327.96
  4944.9  328.62  4985.0  329.01  4993.0  328.23  4995.7  326.16  4996.3  325.36
  5002.5  325.36  5003.1  326.16  5007.5  328.98  5013.9  329.06  5142.4  328.76
  5213.0  326.71  5330.1  329.90  5413.4  334.04  5555.6  342.63  5605.4  348.75
  5669.7  352.89  5691.5  355.72  5713.3  356.77  5742.0  359.75  5763.1  361.07
  5769.4  359.06  5777.6  359.54  5783.9  361.33  5812.9  363.38  5855.5  364.76
#Mann=6,-1,0
  4395.2    0.16       0  4667.6    0.05       0  4944.9    0.12       0
  4995.7    0.07       0  5003.1    0.12       0  5413.4    0.16       0
Bank Sta=4776.7,5330.1
Exp/Cntr=0.3,0.1

Type RM Length L Ch R = 1,3422,564,564,564
BEGIN DESCRIPTION:
STEWART CREEK 3.0
END DESCRIPTION:
XS GIS Cut Line= 3
      2924874.98      6953975.01      2924325.00      6954125.00
      2923525.00      6954275.00
#Sta/Elev= 30
  4420.6  352.82  4482.8  347.27  4557.1  342.43  4638.2  335.41  4787.8  326.77
  4814.5  325.89  4903.4  325.64  4973.4  325.83  4980.3  324.46  4988.1  325.65
  5051.7  324.49  5082.2  325.27  5149.8  323.96  5150.3  323.16  5156.6  323.16
  5157.2  323.96  5224.7  324.92  5241.4  326.35  5250.6  326.77  5336.6  328.81
  5452.7  334.95  5550.2  344.36  5563.0  346.59  5615.5  351.09  5631.6  353.54
  5652.0  355.35  5668.1  358.19  5692.7  360.67  5744.0  363.37  5804.6  366.12
#Mann=6,-1,0
  4420.6    0.16       0  4903.4    0.12       0  5149.8    0.07       0
  5157.2    0.12       0  5241.4    0.16       0  5744.0    0.05       0
Bank Sta=4787.8,5250.6
Exp/Cntr=0.3,0.1

Type RM Length L Ch R = 1,2858,990,990,990
BEGIN DESCRIPTION:
Mapping XS a60df535
END DESCRIPTION:
XS GIS Cut Line= 3
      2924936.64      6953879.26      2924217.85      6953582.37
      2923285.56      6954103.20
#Sta/Elev= 30
  4177.6  349.37  4198.7  348.72  4230.7  345.56  4305.2  340.34  4329.1  337.66
  4341.7  333.55  4359.8  333.43  4431.4  333.47  4541.3  333.71  4601.3  332.80
  4612.2  331.53  4619.3  328.90  4676.2  323.23  4709.5  322.23  5011.0  322.96
  5315.7  321.77  5316.3  320.97  5323.1  321.77  5392.3  323.23  5519.3  328.80
  5627.9  336.66  5665.5  337.65  5687.2  340.03  5693.0  342.26  5768.3  345.83
  5774.1  347.22  5827.7  348.95  5898.6  354.33  5979.7  358.64  6023.2  359.73
#Mann=7,-1,0
  4177.6    0.16       0  4230.7    0.05       0  4359.8     0.1       0
  4431.4    0.08       0  4541.3    0.05       0  5315.7    0.03       0
  5323.1    0.05       0
Bank Sta=4676.2,5392.3
Exp/Cntr=0.3,0.1

Type RM Length L Ch R = 1,1868,711,711,711
BEGIN DESCRIPTION:
Mapping XS 5b1421e2
END DESCRIPTION:
XS GIS Cut Line= 4
      2925118.90      6953853.21      2924108.48      6953238.62
      2923348.06      6953301.12      2922983.49      6953936.52
#Sta/Elev= 30
  2993.6  341.73  3001.9  340.37  3017.4  345.96  3038.7  340.73  3045.0  343.68
  3060.0  341.77  3075.5  342.25  3081.3  340.71  3112.3  340.51  3149.1  337.35
  3166.0  334.16  3176.3  333.11  3191.7  334.44  3213.1  331.99  3366.1  325.50
  3439.7  325.04  3503.1  321.85  3920.2  320.14  4310.2  321.71  4872.1  321.32
  4991.9  319.98  4992.5  319.18  4999.4  319.98  5038.8  321.22  5082.1  320.22
  5096.6  321.85  5355.2  334.13  5537.8  348.37  5639.9  353.04  5671.8  352.84
#Mann=4,-1,0
  2993.6    0.16       0  3166.0    0.05       0  4991.9    0.03       0
  4999.4    0.05       0
Bank Sta=3503.1,5096.6
Exp/Cntr=0.3,0.1

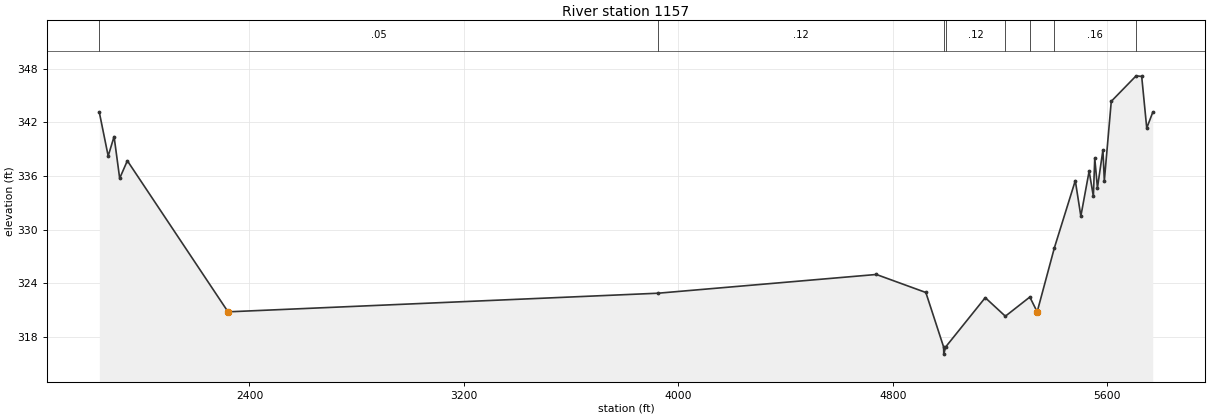
Type RM Length L Ch R = 1,1157,0,0,0
BEGIN DESCRIPTION:
STEWART CREEK 2.0
END DESCRIPTION:
XS GIS Cut Line= 5
      2925259.53      6953837.59      2924306.40      6953035.49
      2922900.00      6952750.00      2922600.00      6953250.00
      2922764.73      6953894.89
#Sta/Elev= 30
  1840.0  343.13  1873.0  338.24  1895.0  340.42  1915.9  335.74  1944.5  337.71
  2320.1  320.77  3924.5  322.86  4738.5  324.96  4923.1  322.94  4989.4  316.83
  4990.0  316.03  4996.9  316.83  5144.7  322.36  5219.7  320.28  5311.0  322.43
  5338.4  320.77  5402.6  327.95  5480.6  335.48  5501.3  331.50  5532.2  336.54
  5548.0  333.72  5553.2  338.00  5563.2  334.67  5583.7  338.92  5588.9  335.46
  5614.8  344.37  5707.5  347.23  5728.3  347.16  5747.1  341.37  5769.5  343.14
#Mann=8,-1,0
  1840.0    0.05       0  3924.5    0.12       0  4989.4    0.07       0
  4996.9    0.12       0  5219.7    0.16       0  5311.0    0.12       0
  5402.6    0.16       0  5707.5    0.08       0
Bank Sta=2320.1,5338.4
Exp/Cntr=0.3,0.1

Chan Stop Cuts=-1