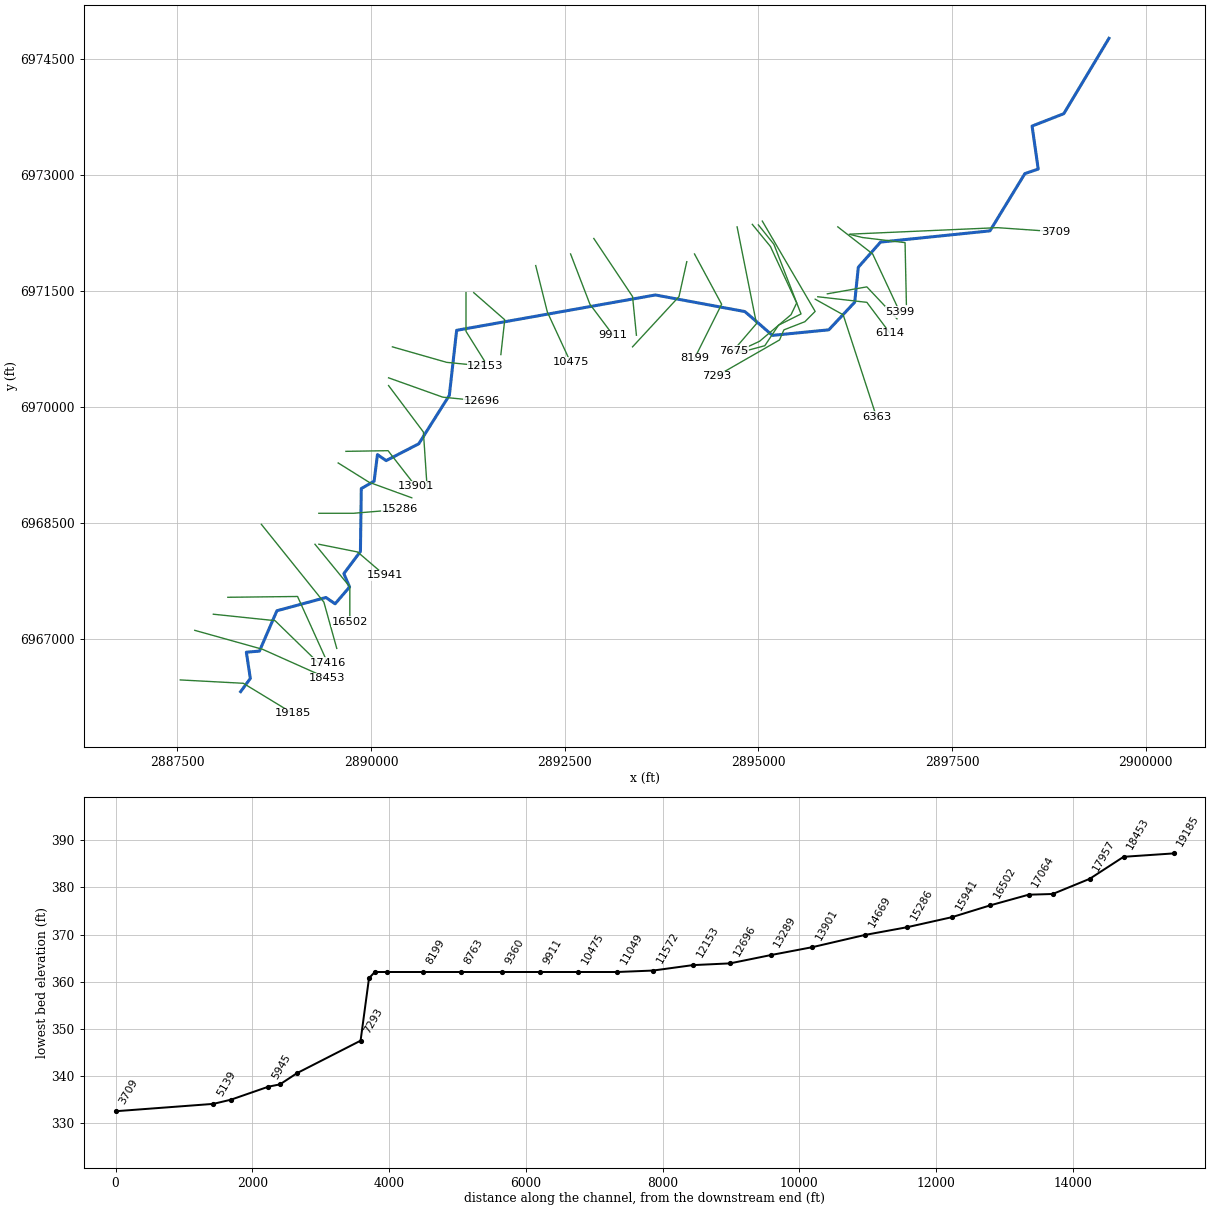
--- TURMAN BRANCH.prj (project) ---

Proj Title=TURMAN BRANCH Base Level Engineering
Current Plan=p01
Default Exp/Contr=0.3,0.1
English Units
Geom File=g01
Flow File=f01
Plan File=p01
BEGIN DESCRIPTION:
TURMAN BRANCH
END DESCRIPTION:

--- TURMAN BRANCH.p01 (plan) ---

Plan Title=Multiple Run
Short Identifier=Multiple
Geom File=g01
Flow File=f01
Subcritical Flow
K Sum by GR= 0
Std Step Tol= 0.01
Critical Tol= 0.01
Num of Std Step Trials= 20
Max Error Tol= 0.3
Flow Tol Ratio= 0.001
Split Flow NTrial= 30
Split Flow Tol= 0.02
Split Flow Ratio= 0.02
Log Output Level= 0
Friction Slope Method= 1
Unsteady Friction Slope Method= 2
Unsteady Bridges Friction Slope Method= 1
Parabolic Critical Depth
Global Vel Dist=  1 , 1 , 1
Global Log Level= 0
CheckData=True
Encroach Param= -1, 0, 0, 0
BEGIN DESCRIPTION:
Multiple Run
END DESCRIPTION:

--- TURMAN BRANCH.f01 (steady flow) ---

Flow Title=Multiple
Program Version=5.07
Number of Profiles= 7
Profile Names=10-year,25-year,50-year,1pct_min,100-year,1pct_plu,500-year
River Rch & RM=TURMAN BRANCH,Reach-1         ,19185
     525     705     851     512    1022    2040    1476
River Rch & RM=TURMAN BRANCH,Reach-1         ,17064
     858    1181    1451     886    1767    3525    2625
River Rch & RM=TURMAN BRANCH,Reach-1         ,11572
    1033    1431    1766    1081    2158    4305    3228
River Rch & RM=TURMAN BRANCH,Reach-1         ,6363
    1616    2289    2865    1777    3546    7076    5447
River Rch & RM=TURMAN BRANCH,Reach-1         ,3709
    1741    2468    3092    1918    3828    7638    5884
Boundary for River Rch & Prof#=TURMAN BRANCH,Reach-1         , 1
Up Type= 0
Dn Type= 3
Dn Slope=0.005
Boundary for River Rch & Prof#=TURMAN BRANCH,Reach-1         , 2
Up Type= 0
Dn Type= 3
Dn Slope=0.005
Boundary for River Rch & Prof#=TURMAN BRANCH,Reach-1         , 3
Up Type= 0
Dn Type= 3
Dn Slope=0.005
Boundary for River Rch & Prof#=TURMAN BRANCH,Reach-1         , 4
Up Type= 0
Dn Type= 3
Dn Slope=0.005
Boundary for River Rch & Prof#=TURMAN BRANCH,Reach-1         , 5
Up Type= 0
Dn Type= 3
Dn Slope=0.005
Boundary for River Rch & Prof#=TURMAN BRANCH,Reach-1         , 6
Up Type= 0
Dn Type= 3
Dn Slope=0.005
Boundary for River Rch & Prof#=TURMAN BRANCH,Reach-1         , 7
Up Type= 0
Dn Type= 3
Dn Slope=0.005
DSS Import GetInterval= 0
DSS Import GetPeak= 0
DSS Import FillOption= 0

--- TURMAN BRANCH.g01 (geometry) ---

Geom Title=Existing Conditions

River Reach=TURMAN BRANCH,Reach-1
Reach XY= 30
      2888315.59      6966320.71      2888440.58      6966491.31
      2888389.20      6966830.09      2888558.22      6966844.31
      2888783.69      6967365.57      2889416.21      6967536.76
      2889534.96      6967455.34      2889721.81      6967673.11
      2889647.74      6967845.16      2889861.96      6968131.98
      2889873.10      6968944.19      2890038.71      6969038.86
      2890081.67      6969382.24      2890194.36      6969305.26
      2890615.02      6969522.49      2891009.74      6970148.64
      2891104.00      6970988.69      2893669.80      6971445.17
      2894825.59      6971230.71      2895181.12      6970923.23
      2895908.67      6970994.85      2896243.09      6971351.59
      2896289.76      6971803.73      2896576.58      6972128.31
      2897989.31      6972273.49      2898440.32      6973013.44
      2898612.13      6973071.67      2898533.06      6973627.36
      2898942.20      6973787.16      2899525.59      6974760.71

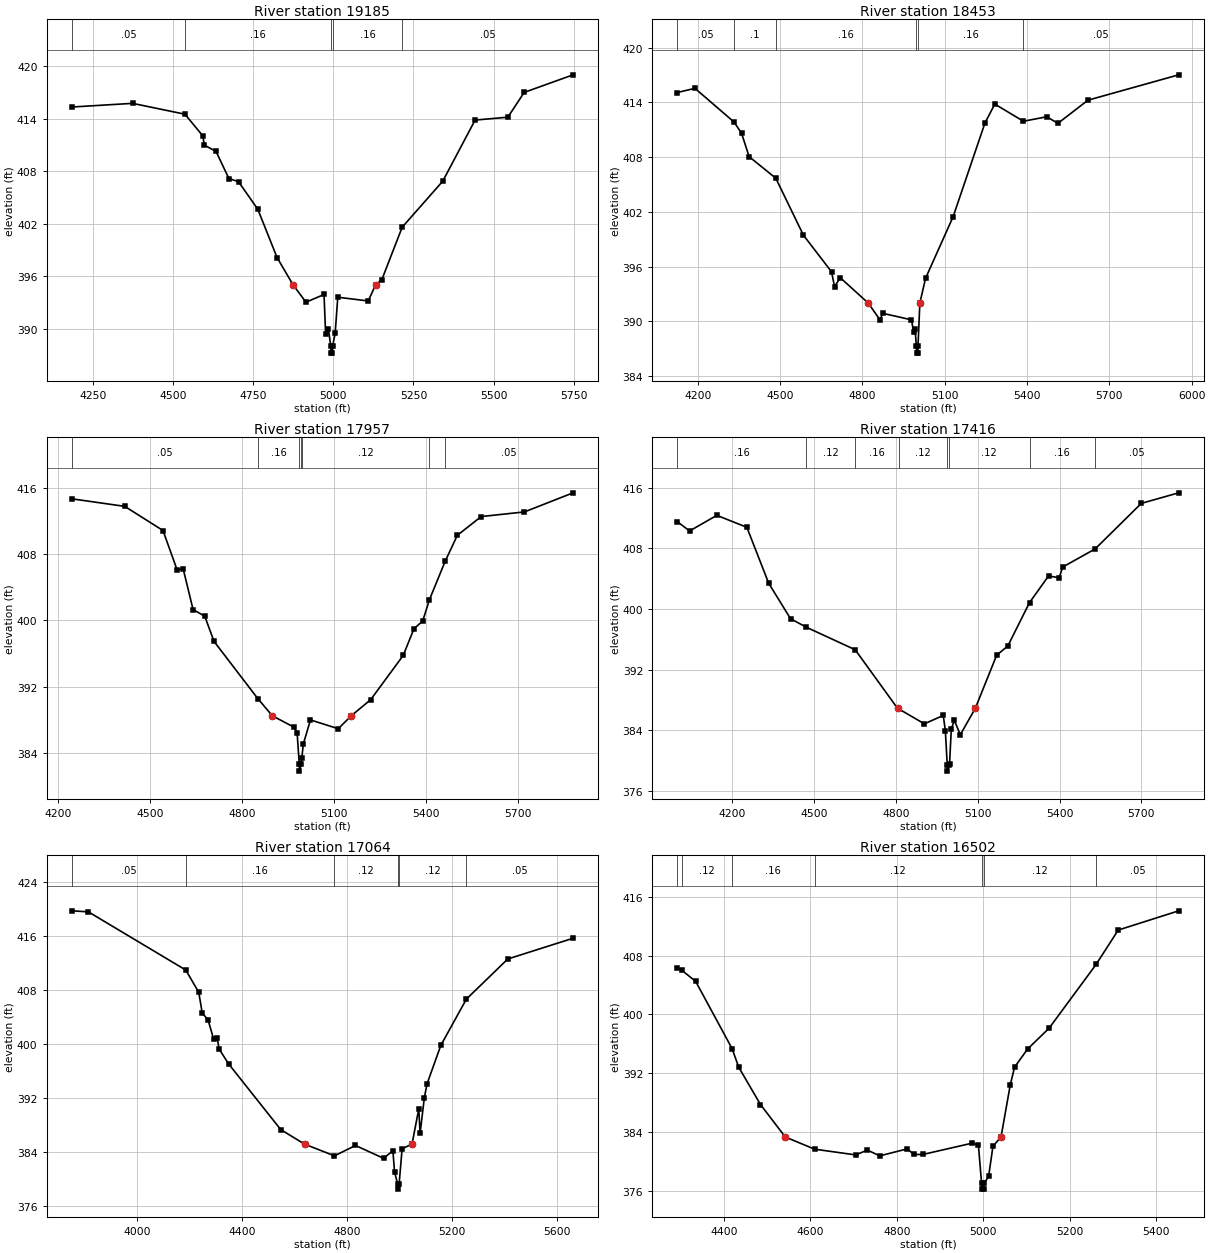
Type RM Length L Ch R = 1,19185,732,732,732
BEGIN DESCRIPTION:
TURMAN BRANCH 24.0
END DESCRIPTION:
XS GIS Cut Line= 3
      2887535.74      6966471.96      2888349.98      6966428.53
      2888988.59      6966039.84
#Sta/Elev= 30
  4184.6  415.34  4374.1  415.76  4537.6  414.52  4593.2  412.05  4598.2  410.98
  4634.5  410.27  4674.6  407.17  4704.6  406.81  4764.7  403.66  4824.8  398.14
  4874.7  395.02  4914.9  393.04  4971.2  393.92  4976.2  389.41  4985.0  390.00
  4992.0  388.02  4992.5  387.22  4997.5  387.22  4998.0  388.02  5005.9  389.49
  5014.1  393.61  5109.0  393.18  5131.9  395.02  5151.6  395.63  5214.9  401.61
  5341.4  406.87  5442.2  413.85  5544.4  414.18  5595.2  417.01  5747.6  419.02
#Mann=5,-1,0
  4184.6    0.05       0  4537.6    0.16       0  4992.0    0.07       0
  4998.0    0.16       0  5214.9    0.05       0
Bank Sta=4874.7,5131.9
Exp/Cntr=0.3,0.1

Type RM Length L Ch R = 1,18453,496,496,496
BEGIN DESCRIPTION:
Mapping XS 6b40fb25
END DESCRIPTION:
XS GIS Cut Line= 3
      2887723.24      6967112.59      2888598.26      6966867.79
      2889436.81      6966492.78
#Sta/Elev= 30
  4125.6  415.08  4189.7  415.54  4332.2  411.84  4359.5  410.62  4387.0  408.05
  4484.4  405.68  4585.1  399.43  4687.5  395.42  4698.5  393.79  4719.3  394.77
  4821.3  391.99  4864.7  390.12  4873.7  390.87  4978.9  390.15  4986.5  388.82
  4991.7  389.17  4996.7  387.30  4997.2  386.50  5002.2  386.50  5002.7  387.30
  5009.4  391.99  5030.1  394.70  5130.7  401.46  5246.8  411.75  5282.6  413.81
  5386.9  411.93  5472.0  412.42  5512.6  411.70  5622.2  414.24  5952.8  417.02
#Mann=6,-1,0
  4125.6    0.05       0  4332.2     0.1       0  4484.4    0.16       0
  4996.7    0.07       0  5002.7    0.16       0  5386.9    0.05       0
Bank Sta=4821.3,5009.4
Exp/Cntr=0.3,0.1

Type RM Length L Ch R = 1,17957,541,541,541
BEGIN DESCRIPTION:
Mapping XS 196335eb
END DESCRIPTION:
XS GIS Cut Line= 3
      2887962.85      6967320.91      2888759.71      6967237.58
      2889358.68      6966654.24
#Sta/Elev= 30
  4243.9  414.64  4417.0  413.73  4541.9  410.82  4587.9  406.09  4608.0  406.18
  4640.2  401.30  4678.4  400.49  4708.6  397.46  4852.0  390.55  4899.0  388.50
  4970.0  387.12  4980.0  386.44  4987.1  382.63  4987.6  381.83  4993.1  382.63
  4995.2  383.36  5000.2  385.09  5023.6  388.00  5114.3  386.94  5156.9  388.50
  5220.3  390.44  5326.5  395.77  5361.8  399.00  5390.1  399.91  5412.2  402.49
  5463.4  407.10  5503.2  410.24  5581.1  412.50  5722.5  413.06  5881.2  415.36
#Mann=7,-1,0
  4243.9    0.05       0  4852.0    0.16       0  4987.1    0.07       0
  4993.1    0.16       0  4995.2    0.12       0  5412.2    0.16       0
  5463.4    0.05       0
Bank Sta=4899,5156.9
Exp/Cntr=0.3,0.1

Type RM Length L Ch R = 1,17416,352,352,352
BEGIN DESCRIPTION:
Mapping XS 8935786c
END DESCRIPTION:
XS GIS Cut Line= 3
      2888150.34      6967539.66      2889050.00      6967550.00
      2889436.79      6966695.92
#Sta/Elev= 30
  3999.4  411.51  4044.1  410.29  4144.1  412.35  4254.1  410.77  4334.1  403.39
  4414.1  398.72  4471.6  397.60  4651.1  394.62  4806.2  386.90  4810.1  386.83
  4904.6  384.85  4973.9  385.95  4981.5  383.96  4988.5  379.41  4989.0  378.61
  4994.5  379.41  4997.0  379.61  5003.4  384.16  5014.4  385.31  5036.3  383.41
  5091.4  386.90  5169.7  393.91  5210.4  395.11  5290.0  400.84  5359.9  404.36
  5398.6  404.11  5411.6  405.53  5530.5  407.92  5699.8  413.93  5836.7  415.32
#Mann=8,-1,0
  3999.4    0.16       0  4471.6    0.12       0  4651.1    0.16       0
  4810.1    0.12       0  4988.5    0.07       0  4994.5    0.12       0
  5290.0    0.16       0  5530.5    0.05       0
Bank Sta=4806.2,5091.4
Exp/Cntr=0.3,0.1

Type RM Length L Ch R = 1,17064,562,562,562
BEGIN DESCRIPTION:
Mapping XS d7c1ed80
END DESCRIPTION:
XS GIS Cut Line= 3
      2888582.62      6968482.38      2889389.92      6967477.16
      2889556.33      6966879.14
#Sta/Elev= 30
  3750.1  419.77  3813.5  419.62  4184.6  410.98  4234.1  407.67  4247.2  404.61
  4269.5  403.58  4290.4  400.77  4304.8  400.88  4311.2  399.28  4348.0  397.04
  4546.4  387.30  4637.1  385.14  4751.2  383.40  4831.2  384.94  4938.4  383.03
  4973.6  384.16  4980.0  381.06  4991.3  379.26  4991.8  378.46  4997.5  379.26
  5008.8  384.45  5046.6  385.14  5072.3  390.36  5077.4  386.75  5093.5  392.04
  5103.9  394.09  5156.3  399.80  5253.8  406.67  5411.4  412.62  5660.1  415.70
#Mann=6,-1,0
  3750.1    0.05       0  4184.6    0.16       0  4751.2    0.12       0
  4991.3    0.07       0  4997.5    0.12       0  5253.8    0.05       0
Bank Sta=4637.1,5046.6
Exp/Cntr=0.3,0.1

Type RM Length L Ch R = 1,16502,561,561,561
BEGIN DESCRIPTION:
TURMAN BRANCH 23.0
END DESCRIPTION:
XS GIS Cut Line= 3
      2889275.00      6968225.00      2889725.00      6967675.00
      2889725.00      6967225.03
#Sta/Elev= 30
  4291.8  406.37  4302.2  405.99  4334.2  404.48  4418.4  395.34  4433.9  392.79
  4484.2  387.72  4541.6  383.30  4609.5  381.64  4704.5  380.86  4731.8  381.51
  4760.5  380.73  4824.4  381.69  4838.8  380.92  4860.3  380.92  4974.4  382.46
  4988.8  382.15  4996.1  377.00  4996.6  376.20  5001.8  376.20  5002.3  377.00
  5012.4  377.95  5022.4  382.04  5041.1  383.30  5062.4  390.37  5072.4  392.80
  5102.4  395.26  5152.4  398.11  5261.3  406.80  5312.4  411.47  5452.4  414.09
#Mann=7,-1,0
  4291.8    0.05       0  4302.2    0.12       0  4418.4    0.16       0
  4609.5    0.12       0  4996.1    0.07       0  5002.3    0.12       0
  5261.3    0.05       0
Bank Sta=4541.6,5041.1
Exp/Cntr=0.3,0.1

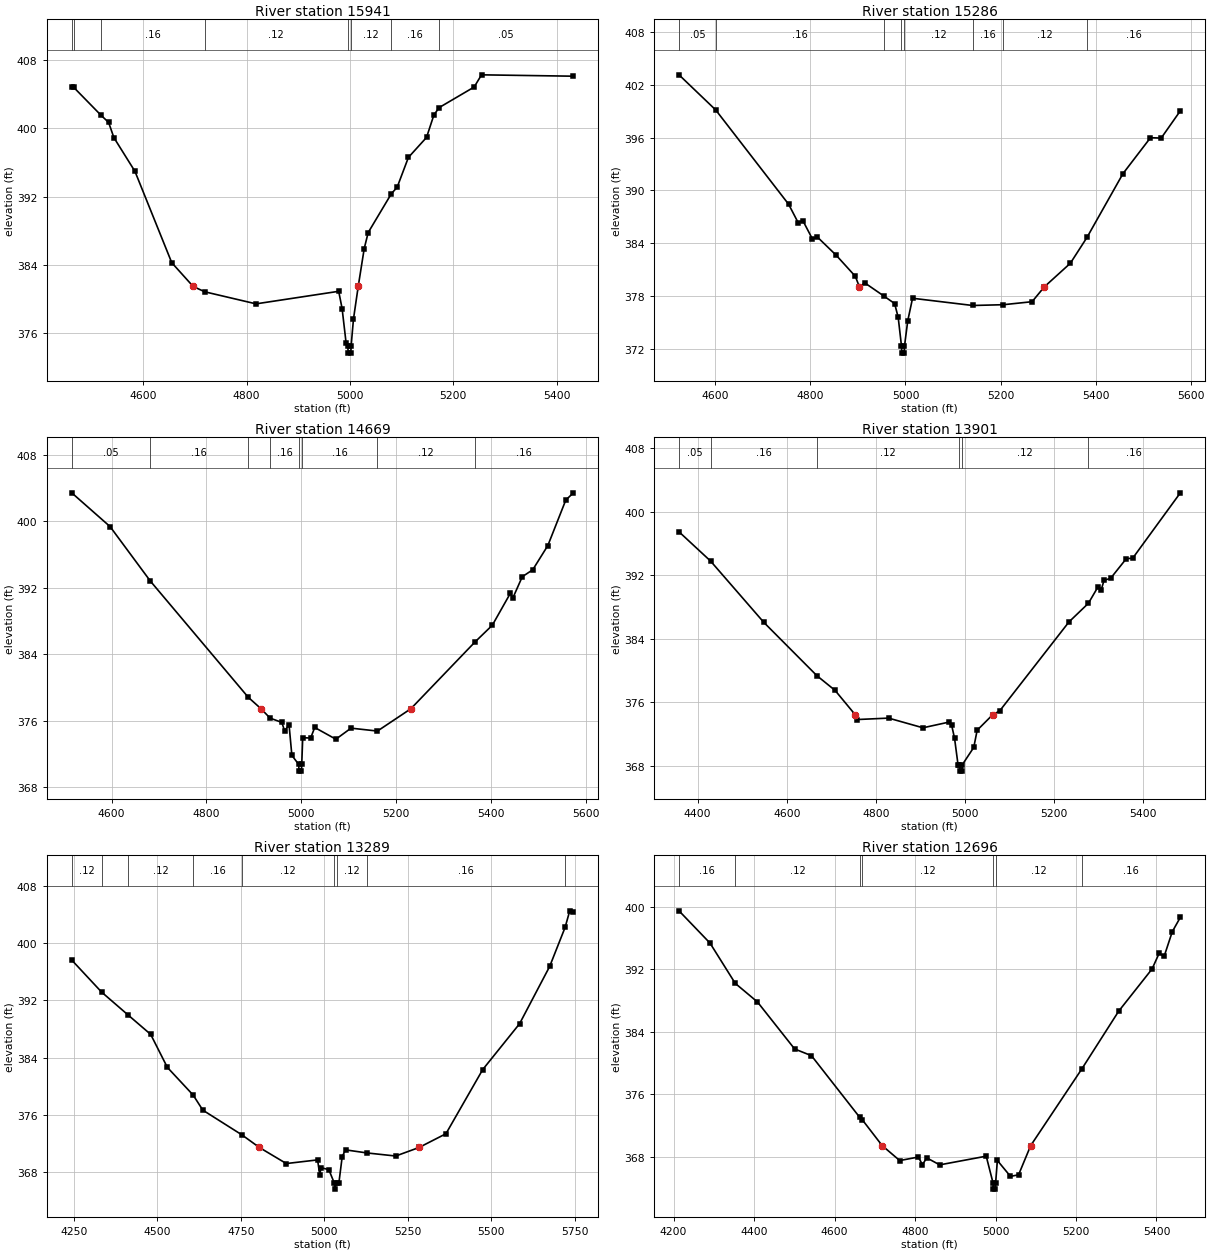
Type RM Length L Ch R = 1,15941,655,655,655
BEGIN DESCRIPTION:
TURMAN BRANCH 22.0
END DESCRIPTION:
XS GIS Cut Line= 3
      2889325.02      6968225.00      2889825.00      6968125.00
      2890175.03      6967824.97
#Sta/Elev= 30
  4461.2  404.89  4465.1  404.81  4518.0  401.54  4532.6  400.71  4542.8  398.93
  4583.6  394.98  4654.9  384.28  4696.3  381.50  4718.9  380.87  4818.1  379.46
  4978.2  380.93  4984.8  378.91  4992.5  374.89  4996.0  374.49  4996.5  373.69
  5001.7  373.69  5002.2  374.49  5006.8  377.68  5016.0  381.50  5027.6  385.93
  5035.3  387.81  5080.4  392.38  5091.3  393.10  5113.2  396.61  5148.3  398.95
  5162.6  401.59  5172.9  402.45  5240.5  404.85  5254.8  406.28  5432.1  406.12
#Mann=8,-1,0
  4461.2    0.05       0  4465.1    0.12       0  4518.0    0.16       0
  4718.9    0.12       0  4996.0    0.07       0  5002.2    0.12       0
  5080.4    0.16       0  5172.9    0.05       0
Bank Sta=4696.3,5016
Exp/Cntr=0.3,0.1

Type RM Length L Ch R = 1,15286,617,617,617
BEGIN DESCRIPTION:
TURMAN BRANCH 21.0
END DESCRIPTION:
XS GIS Cut Line= 3
      2889324.99      6968625.00      2889775.00      6968625.00
      2890375.01      6968675.00
#Sta/Elev= 30
  4524.8  403.11  4601.8  399.13  4754.8  388.44  4774.8  386.36  4784.8  386.57
  4804.8  384.50  4814.8  384.74  4854.8  382.65  4894.8  380.27  4903.4  379.07
  4914.8  379.52  4954.5  378.04  4977.3  377.18  4984.8  375.61  4991.7  372.36
  4992.2  371.56  4997.5  371.56  4998.0  372.36  5004.9  375.24  5014.9  377.78
  5141.1  376.96  5205.6  377.05  5265.8  377.39  5291.4  379.07  5346.1  381.75
  5381.0  384.68  5456.5  391.91  5514.2  395.98  5536.7  395.94  5576.9  399.03
#Mann=8,-1,0
  4524.8    0.05       0  4601.8    0.16       0  4954.5    0.12       0
  4991.7    0.07       0  4998.0    0.12       0  5141.1    0.16       0
  5205.6    0.12       0  5381.0    0.16       0
Bank Sta=4903.4,5291.4
Exp/Cntr=0.3,0.1

Type RM Length L Ch R = 1,14669,768,768,768
BEGIN DESCRIPTION:
TURMAN BRANCH 20.0
END DESCRIPTION:
XS GIS Cut Line= 3
      2889574.96      6969275.02      2889975.00      6969025.00
      2890525.02      6968824.99
#Sta/Elev= 30
  4515.9  403.40  4596.7  399.34  4681.7  392.78  4888.1  378.80  4915.1  377.42
  4934.0  376.30  4958.8  375.78  4964.7  374.77  4974.1  375.48  4980.0  371.82
  4994.5  370.72  4995.0  369.92  5000.3  369.92  5000.8  370.72  5002.9  373.94
  5019.6  373.90  5028.2  375.17  5072.8  373.76  5104.7  375.09  5160.4  374.74
  5230.8  377.42  5365.8  385.44  5402.6  387.47  5440.5  391.30  5445.9  390.75
  5465.8  393.31  5487.8  394.14  5519.7  397.06  5557.6  402.54  5572.9  403.36
#Mann=8,-1,0
  4515.9    0.05       0  4681.7    0.16       0  4888.1    0.12       0
  4934.0    0.16       0  4994.5    0.07       0  5000.8    0.16       0
  5160.4    0.12       0  5365.8    0.16       0
Bank Sta=4915.1,5230.8
Exp/Cntr=0.3,0.1

Type RM Length L Ch R = 1,13901,612,612,612
BEGIN DESCRIPTION:
TURMAN BRANCH 19.0
END DESCRIPTION:
XS GIS Cut Line= 3
      2889674.96      6969425.00      2890218.79      6969433.61
      2890575.01      6968974.99
#Sta/Elev= 30
  4358.2  397.48  4428.9  393.80  4548.3  386.08  4667.6  379.35  4708.3  377.50
  4753.1  374.46  4758.3  373.83  4828.3  374.01  4905.4  372.79  4963.3  373.50
  4969.6  373.16  4976.3  371.47  4984.1  368.14  4987.3  368.13  4987.8  367.33
  4993.1  367.33  4993.6  368.13  5019.4  370.32  5027.0  372.48  5062.3  374.46
  5077.3  374.90  5233.0  386.13  5276.5  388.47  5297.3  390.47  5305.4  390.19
  5311.7  391.38  5326.2  391.61  5361.5  394.09  5376.0  394.16  5482.8  402.39
#Mann=6,-1,0
  4358.2    0.05       0  4428.9    0.16       0  4667.6    0.12       0
  4987.3    0.07       0  4993.6    0.12       0  5276.5    0.16       0
Bank Sta=4753.1,5062.3
Exp/Cntr=0.3,0.1

Type RM Length L Ch R = 1,13289,593,593,593
BEGIN DESCRIPTION:
TURMAN BRANCH 18.0
END DESCRIPTION:
XS GIS Cut Line= 3
      2890225.03      6970274.97      2890675.00      6969675.00
      2890725.00      6968925.02
#Sta/Elev= 30
  4243.8  397.61  4333.0  393.15  4412.4  389.95  4480.2  387.24  4530.2  382.63
  4607.4  378.77  4636.5  376.66  4753.6  373.21  4805.9  371.45  4886.5  369.21
  4980.2  369.72  4986.5  367.65  4990.6  368.63  5013.8  368.36  5030.6  366.44
  5031.1  365.64  5037.1  366.44  5043.9  366.48  5053.9  370.18  5063.9  371.12
  5128.0  370.69  5214.2  370.26  5284.0  371.45  5364.6  373.37  5474.8  382.33
  5585.1  388.72  5675.3  396.72  5721.5  402.17  5735.4  404.48  5745.4  404.26
#Mann=9,-1,0
  4243.8    0.12       0  4333.0    0.16       0  4412.4    0.12       0
  4607.4    0.16       0  4753.6    0.12       0  5030.6    0.07       0
  5037.1    0.12       0  5128.0    0.16       0  5721.5    0.05       0
Bank Sta=4805.9,5284
Exp/Cntr=0.3,0.1

Type RM Length L Ch R = 1,12696,543,543,543
BEGIN DESCRIPTION:
TURMAN BRANCH 17.0
END DESCRIPTION:
XS GIS Cut Line= 3
      2890224.96      6970375.01      2890925.00      6970125.00
      2891424.97      6970075.00
#Sta/Elev= 30
  4213.5  399.45  4290.5  395.33  4353.3  390.18  4408.4  387.81  4500.8  381.80
  4542.7  380.94  4662.6  373.06  4668.7  372.77  4718.4  369.45  4762.0  367.54
  4808.2  367.99  4818.3  367.03  4829.4  367.88  4861.3  366.99  4976.9  368.10
  4993.8  364.69  4994.3  363.89  4999.8  363.89  5000.3  364.69  5004.6  367.55
  5037.2  365.52  5057.3  365.72  5087.4  369.45  5214.1  379.22  5306.1  386.63
  5389.0  392.02  5406.6  394.02  5419.1  393.64  5439.2  396.78  5459.3  398.62
#Mann=7,-1,0
  4213.5    0.16       0  4353.3    0.12       0  4662.6    0.16       0
  4668.7    0.12       0  4993.8    0.07       0  5000.3    0.12       0
  5214.1    0.16       0
Bank Sta=4718.4,5087.4
Exp/Cntr=0.3,0.1

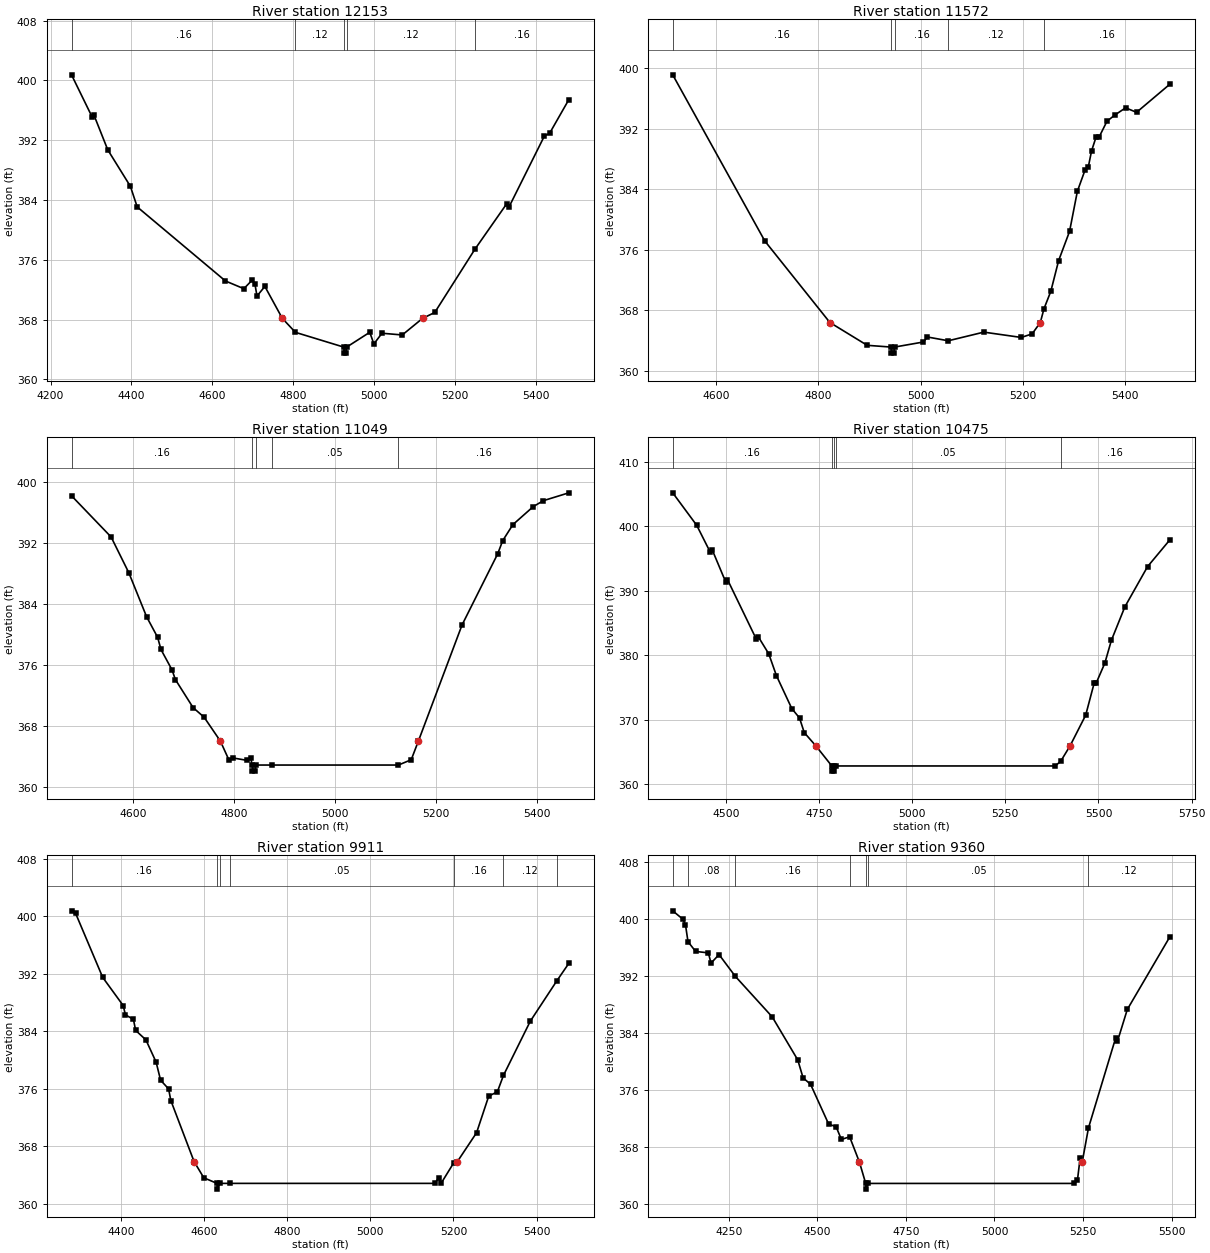
Type RM Length L Ch R = 1,12153,581,581,581
BEGIN DESCRIPTION:
TURMAN BRANCH 16.0
END DESCRIPTION:
XS GIS Cut Line= 3
      2890275.01      6970775.00      2890975.00      6970575.00
      2891475.01      6970525.00
#Sta/Elev= 30
  4251.8  400.75  4302.5  395.14  4307.7  395.31  4341.5  390.71  4397.4  385.84
  4414.3  383.08  4632.7  373.17  4678.2  372.14  4699.0  373.30  4705.5  372.80
  4710.7  371.16  4730.2  372.44  4773.4  368.17  4805.8  366.30  4925.8  364.32
  4926.3  363.52  4931.9  363.52  4932.4  364.32  4989.8  366.31  4999.9  364.75
  5020.0  366.18  5070.2  365.95  5120.4  368.17  5150.6  368.96  5249.6  377.39
  5329.0  383.53  5334.1  383.05  5422.0  392.58  5434.6  392.91  5482.3  397.43
#Mann=5,-1,0
  4251.8    0.16       0  4805.8    0.12       0  4925.8    0.07       0
  4932.4    0.12       0  5249.6    0.16       0
Bank Sta=4773.4,5120.4
Exp/Cntr=0.3,0.1

Type RM Length L Ch R = 1,11572,523,523,523
BEGIN DESCRIPTION:
TURMAN BRANCH 15.0
END DESCRIPTION:
XS GIS Cut Line= 3
      2891225.00      6971475.01      2891225.00      6970975.00
      2891474.99      6970575.01
#Sta/Elev= 30
  4515.6  399.09  4695.6  377.16  4822.7  366.41  4895.6  363.40  4942.2  363.17
  4942.7  362.37  4948.5  362.37  4949.0  363.17  5005.6  363.84  5013.1  364.50
  5054.0  364.00  5123.5  365.14  5196.6  364.44  5217.9  364.91  5233.9  366.41
  5240.9  368.20  5254.4  370.53  5269.7  374.59  5291.0  378.43  5306.3  383.73
  5321.6  386.59  5327.5  386.89  5334.0  389.05  5342.9  390.90  5348.8  390.89
  5364.1  392.96  5379.4  393.78  5400.6  394.74  5421.9  394.14  5487.3  397.87
#Mann=5,-1,0
  4515.6    0.16       0  4942.2    0.07       0  4949.0    0.16       0
  5054.0    0.12       0  5240.9    0.16       0
Bank Sta=4822.7,5233.9
Exp/Cntr=0.3,0.1

Type RM Length L Ch R = 1,11049,574,574,574
BEGIN DESCRIPTION:
TURMAN BRANCH 14.0
END DESCRIPTION:
XS GIS Cut Line= 3
      2891324.97      6971475.02      2891725.00      6971125.00
      2891675.00      6970675.01
#Sta/Elev= 30
  4478.7  398.25  4557.0  392.84  4592.2  388.12  4627.3  382.35  4649.1  379.65
  4655.7  378.05  4677.6  375.37  4684.2  374.10  4719.3  370.41  4741.2  369.14
  4773.2  366.02  4790.5  363.49  4797.6  363.80  4825.6  363.48  4833.2  363.80
  4836.4  362.86  4836.9  362.06  4842.8  362.06  4843.3  362.86  4875.7  362.86
  5125.8  362.86  5151.1  363.56  5165.3  366.02  5251.7  381.28  5322.2  390.62
  5332.2  392.36  5352.3  394.46  5392.6  396.83  5412.7  397.61  5463.0  398.64
#Mann=5,-1,0
  4478.7    0.16       0  4836.4   0.033       0  4843.3    0.16       0
  4875.7    0.05       0  5125.8    0.16       0
Bank Sta=4773.2,5165.3
Exp/Cntr=0.3,0.1

Type RM Length L Ch R = 1,10475,564,564,564
BEGIN DESCRIPTION:
TURMAN BRANCH 13.0
END DESCRIPTION:
XS GIS Cut Line= 3
      2892125.00      6971825.00      2892275.00      6971225.00
      2892575.02      6970574.96
#Sta/Elev= 30
  4357.5  405.15  4421.9  400.12  4458.0  395.98  4463.2  396.36  4499.2  391.41
  4504.4  391.72  4581.7  382.50  4586.9  382.88  4615.2  380.22  4635.8  376.84
  4677.0  371.75  4697.7  370.29  4710.5  368.02  4741.9  365.95  4784.4  362.86
  4784.9  362.06  4790.9  362.06  4791.4  362.86  4794.7  362.86  5383.5  362.86
  5398.3  363.56  5423.5  365.95  5465.6  370.72  5488.6  375.74  5494.1  375.73
  5517.0  378.78  5534.5  382.30  5570.7  387.49  5631.7  393.73  5691.9  397.90
#Mann=5,-1,0
  4357.5    0.16       0  4784.4   0.033       0  4791.4    0.16       0
  4794.7    0.05       0  5398.3    0.16       0
Bank Sta=4741.9,5423.5
Exp/Cntr=0.3,0.1

Type RM Length L Ch R = 1,9911,551,551,551
BEGIN DESCRIPTION:
TURMAN BRANCH 12.0
END DESCRIPTION:
XS GIS Cut Line= 3
      2892575.01      6971974.98      2892825.00      6971325.00
      2893125.00      6970925.00
#Sta/Elev= 30
  4281.1  400.78  4290.7  400.46  4356.1  391.52  4405.4  387.60  4410.7  386.32
  4430.0  385.67  4435.4  384.14  4460.0  382.83  4484.6  379.73  4495.4  377.21
  4514.6  376.01  4520.0  374.39  4575.9  365.90  4599.3  363.64  4631.1  362.86
  4631.6  362.06  4638.2  362.86  4662.1  362.86  5155.6  362.86  5164.0  363.61
  5170.2  362.86  5200.1  365.67  5209.5  365.90  5255.6  369.91  5284.8  375.00
  5305.6  375.60  5320.3  377.89  5384.8  385.42  5449.0  391.07  5477.5  393.47
#Mann=7,-1,0
  4281.1    0.16       0  4631.1   0.033       0  4638.2    0.16       0
  4662.1    0.05       0  5200.1    0.16       0  5320.3    0.12       0
  5449.0    0.16       0
Bank Sta=4575.9,5209.5
Exp/Cntr=0.3,0.1

Type RM Length L Ch R = 1,9360,597,597,597
BEGIN DESCRIPTION:
TURMAN BRANCH 11.0
END DESCRIPTION:
XS GIS Cut Line= 3
      2892875.01      6972174.98      2893375.00      6971425.00
      2893425.00      6970924.96
#Sta/Elev= 30
  4091.6  401.13  4120.1  399.96  4127.6  399.17  4134.7  396.80  4156.2  395.43
  4192.2  395.23  4199.7  393.78  4222.3  394.99  4268.2  391.94  4372.5  386.24
  4444.6  380.20  4459.6  377.68  4480.7  376.78  4531.8  371.19  4552.8  370.82
  4567.8  369.03  4591.0  369.41  4618.7  365.85  4636.4  362.86  4636.9  362.06
  4643.5  362.86  5224.1  362.86  5234.2  363.32  5241.7  366.42  5247.6  365.85
  5265.3  370.65  5342.2  383.31  5347.2  382.82  5374.9  387.28  5495.5  397.52
#Mann=7,-1,0
  4091.6    0.05       0  4134.7    0.08       0  4268.2    0.16       0
  4591.0    0.05       0  4636.4   0.033       0  4643.5    0.05       0
  5265.3    0.12       0
Bank Sta=4618.7,5247.6
Exp/Cntr=0.3,0.1

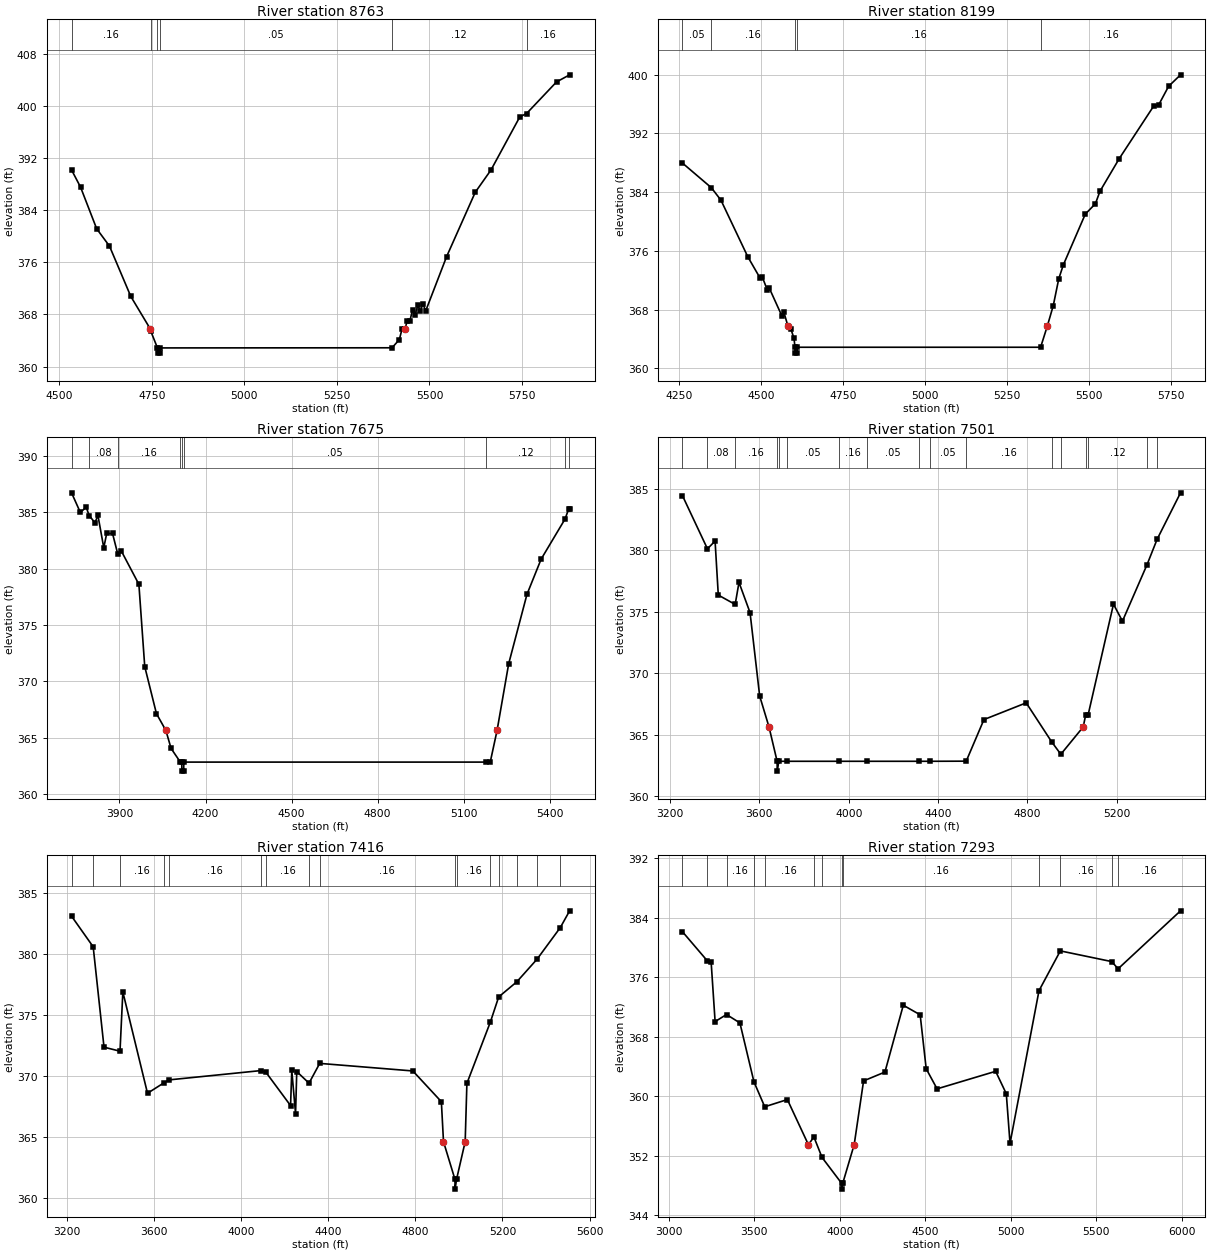
Type RM Length L Ch R = 1,8763,564,564,564
BEGIN DESCRIPTION:
TURMAN BRANCH 10.0
END DESCRIPTION:
XS GIS Cut Line= 3
      2894074.99      6971874.97      2893975.00      6971425.00
      2893375.02      6970775.02
#Sta/Elev= 30
  4533.1  390.19  4557.4  387.55  4600.9  381.16  4635.5  378.50  4693.1  370.77
  4745.5  365.80  4746.9  365.46  4765.1  362.86  4765.6  362.06  4771.7  362.06
  4772.3  362.86  5398.9  362.88  5418.5  364.14  5425.8  365.75  5434.0  365.80
  5440.0  367.05  5446.8  366.92  5454.2  368.73  5461.0  367.88  5468.4  369.40
  5475.2  368.51  5482.6  369.67  5489.4  368.49  5546.1  376.86  5623.7  386.77
  5666.3  390.20  5744.0  398.34  5762.2  398.85  5843.2  403.71  5878.6  404.80
#Mann=6,-1,0
  4533.1    0.16       0  4746.9    0.05       0  4765.1   0.033       0
  4772.3    0.05       0  5398.9    0.12       0  5762.2    0.16       0
Bank Sta=4745.5,5434
Exp/Cntr=0.3,0.1

Type RM Length L Ch R = 1,8199,524,524,524
BEGIN DESCRIPTION:
TURMAN BRANCH 9.0
END DESCRIPTION:
XS GIS Cut Line= 3
      2894175.01      6971974.97      2894525.00      6971325.00
      2894175.02      6970625.03
#Sta/Elev= 30
  4259.7  387.95  4347.8  384.60  4377.3  382.89  4459.2  375.19  4497.4  372.23
  4503.0  372.49  4519.3  370.60  4525.0  370.90  4563.1  367.15  4568.8  367.72
  4582.1  365.70  4590.7  365.36  4600.4  364.06  4603.3  362.86  4603.8  362.06
  4609.9  362.06  4610.5  362.86  5353.3  362.86  5373.5  365.70  5392.0  368.54
  5408.8  372.20  5422.8  374.09  5489.8  381.00  5520.6  382.41  5534.6  384.11
  5593.3  388.55  5699.5  395.78  5713.5  395.85  5744.2  398.41  5780.5  399.97
#Mann=5,-1,0
  4259.7    0.05       0  4347.8    0.16       0  4603.3   0.033       0
  4610.5    0.16       0  5353.3    0.16       0
Bank Sta=4582.1,5373.5
Exp/Cntr=0.3,0.1

Type RM Length L Ch R = 1,7675,174,174,174
BEGIN DESCRIPTION:
TURMAN BRANCH 8.0
END DESCRIPTION:
XS GIS Cut Line= 3
      2894724.99      6972325.05      2894975.00      6971075.00
      2894674.99      6970724.98
#Sta/Elev= 30
  3733.2  386.70  3763.8  384.96  3784.2  385.43  3794.5  384.69  3814.8  384.05
  3825.0  384.71  3845.4  381.84  3855.6  383.10  3876.0  383.10  3893.9  381.31
  3906.6  381.55  3967.8  378.60  3988.2  371.32  4029.0  367.15  4061.9  365.66
  4080.0  364.07  4112.3  362.86  4117.1  362.86  4117.7  362.06  4123.9  362.06
  4124.4  362.86  5178.2  362.86  5192.4  362.87  5216.1  365.66  5256.6  371.57
  5320.3  377.71  5369.7  380.83  5453.0  384.38  5466.0  385.29  5469.0  385.29
#Mann=9,-1,0
  3733.2    0.16       0  3794.5    0.08       0  3893.9    0.16       0
  4112.3    0.05       0  4117.1   0.033       0  4124.4    0.05       0
  5178.2    0.12       0  5453.0    0.16       0  5466.0    0.12       0
Bank Sta=4061.9,5216.1
Exp/Cntr=0.3,0.1

Type RM Length L Ch R = 1,7501,85,85,85
BEGIN DESCRIPTION:
Mapping XS cfbc5547
END DESCRIPTION:
XS GIS Cut Line= 6
      2894921.15      6972357.40      2895155.55      6972070.91
      2895494.09      6971341.75      2895421.17      6971190.71
      2895014.92      6970846.96      2894702.40      6970701.11
#Sta/Elev= 30
  3256.0  384.45  3367.8  380.13  3402.0  380.76  3416.4  376.37  3491.9  375.61
  3509.0  377.40  3558.5  374.94  3601.5  368.17  3643.3  365.65  3679.6  362.86
  3680.2  362.06  3686.9  362.86  3724.1  362.86  3958.0  362.86  4082.0  362.86
  4313.8  362.86  4364.5  362.86  4525.8  362.87  4605.1  366.25  4794.2  367.61
  4907.4  364.46  4949.1  363.43  5049.2  365.65  5060.1  366.60  5071.6  366.66
  5184.7  375.63  5224.9  374.25  5335.1  378.85  5379.9  380.90  5484.7  384.68
#Mann=17,-1,0
  3256.0    0.16       0  3367.8    0.08       0  3491.9    0.16       0
  3679.6    0.07       0  3686.9    0.16       0  3724.1    0.05       0
  3958.0    0.16       0  4082.0    0.05       0  4313.8    0.16       0
  4364.5    0.05       0  4525.8    0.16       0  4907.4    0.05       0
  4949.1    0.16       0  5060.1    0.05       0  5071.6    0.12       0
  5335.1    0.16       0  5379.9    0.12       0
Bank Sta=3643.3,5049.2
Exp/Cntr=0.3,0.1

Type RM Length L Ch R = 1,7416,123,123,123
BEGIN DESCRIPTION:
TURMAN BRANCH 7.0
END DESCRIPTION:
XS GIS Cut Line= 6
      2895000.00      6972350.01      2895200.00      6972100.00
      2895550.00      6971200.00      2895259.71      6971055.29
      2895082.63      6970789.66      2894750.01      6970700.00
#Sta/Elev= 30
  3222.4  383.12  3321.6  380.61  3371.3  372.38  3444.7  372.05  3457.7  376.91
  3570.9  368.60  3648.4  369.48  3671.2  369.70  4091.5  370.46  4114.9  370.31
  4227.5  367.59  4233.1  370.47  4250.4  366.92  4255.9  370.38  4312.2  369.43
  4361.3  371.05  4788.8  370.43  4919.6  367.91  4929.4  364.63  4982.0  361.54
  4982.6  360.74  4989.3  361.54  5028.9  364.63  5036.8  369.41  5144.9  374.46
  5182.7  376.50  5265.9  377.74  5359.0  379.60  5465.6  382.19  5508.3  383.56
#Mann=16,-1,0
  3222.4    0.16       0  3321.6    0.08       0  3444.7    0.16       0
  3648.4    0.12       0  3671.2    0.16       0  4091.5    0.05       0
  4114.9    0.16       0  4312.2    0.05       0  4361.3    0.16       0
  4982.0    0.07       0  4989.3    0.16       0  5144.9    0.12       0
  5182.7    0.16       0  5265.9    0.12       0  5359.0    0.16       0
  5465.6    0.12       0
Bank Sta=4929.4,5028.9
Exp/Cntr=0.3,0.1

Type RM Length L Ch R = 1,7293,930,930,930
BEGIN DESCRIPTION:
double TURMAN BRANCH 6.0
END DESCRIPTION:
XS GIS Cut Line= 6
      2895050.02      6972399.96      2895732.55      6971233.01
      2895600.00      6971100.00      2895328.90      6970994.29
      2895272.48      6970864.08      2894455.41      6970394.61
#Sta/Elev= 30
  3079.1  382.12  3225.1  378.19  3247.0  378.04  3270.2  370.03  3336.9  370.98
  3415.4  369.85  3497.5  361.93  3560.6  358.57  3693.1  359.54  3816.2  353.47
  3848.4  354.51  3896.1  351.75  4010.1  348.29  4010.6  347.49  4017.4  348.29
  4084.3  353.49  4139.1  362.05  4264.1  363.24  4371.5  372.23  4470.3  370.94
  4505.6  363.68  4569.3  360.98  4912.1  363.34  4974.4  360.32  4996.2  353.65
  5165.8  374.19  5290.6  379.54  5591.7  378.10  5628.7  377.13  5994.0  384.93
#Mann=13,-1,0
  3079.1    0.16       0  3225.1    0.08       0  3336.9    0.16       0
  3497.5    0.12       0  3560.6    0.16       0  3848.4    0.12       0
  3896.1    0.16       0  4010.1    0.07       0  4017.4    0.16       0
  5165.8    0.12       0  5290.6    0.16       0  5591.7    0.12       0
  5628.7    0.16       0
Bank Sta=3816.2,4084.3
Exp/Cntr=0.3,0.1

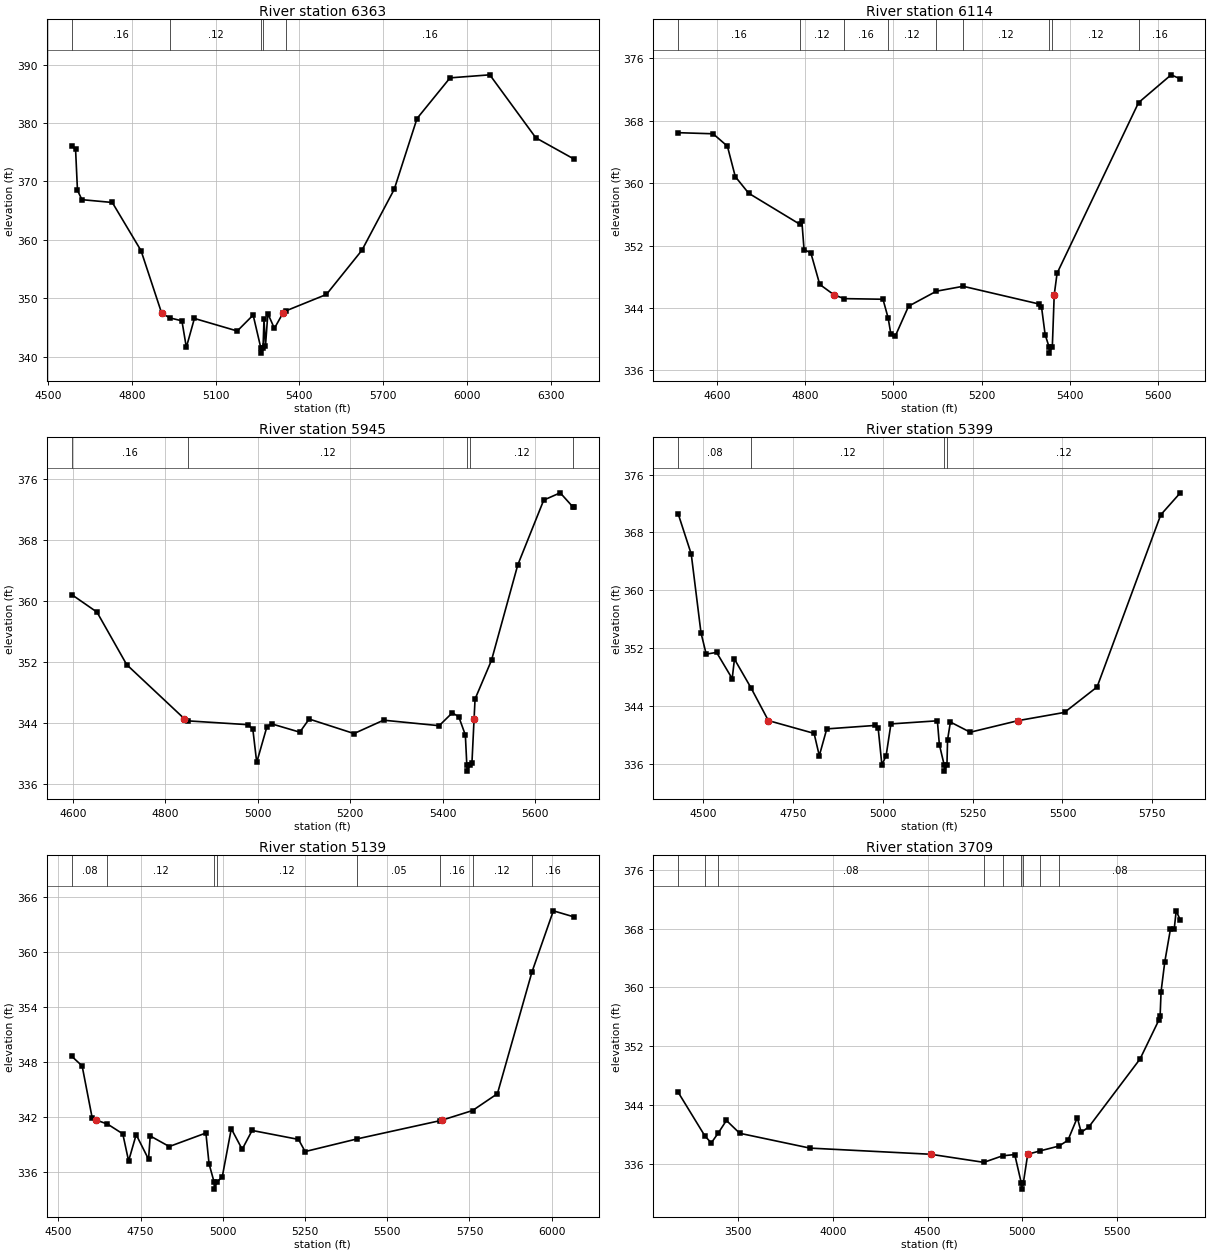
Type RM Length L Ch R = 1,6363,249,249,249
BEGIN DESCRIPTION:
Mapping XS 0aef71f9
END DESCRIPTION:
XS GIS Cut Line= 3
      2895733.20      6971390.55      2896094.31      6971189.16
      2896523.12      6969873.76
#Sta/Elev= 30
  4585.3  376.02  4598.8  375.59  4605.7  368.48  4621.7  366.88  4730.3  366.40
  4833.2  358.15  4907.4  347.39  4937.7  346.62  4979.5  346.13  4995.4  341.59
  5024.2  346.54  5177.6  344.39  5234.5  347.12  5262.4  341.40  5263.0  340.60
  5269.8  341.40  5273.3  346.38  5278.6  341.82  5287.1  347.37  5310.5  344.84
  5340.4  347.39  5352.3  347.85  5496.7  350.65  5623.7  358.21  5739.4  368.65
  5821.0  380.78  5939.2  387.74  6081.5  388.26  6246.3  377.47  6382.3  373.85
#Mann=5,-1,0
  4585.3    0.16       0  4937.7    0.12       0  5262.4    0.07       0
  5269.8    0.12       0  5352.3    0.16       0
Bank Sta=4907.4,5340.4
Exp/Cntr=0.3,0.1

Type RM Length L Ch R = 1,6114,169,169,169
BEGIN DESCRIPTION:
Mapping XS a69391f8
END DESCRIPTION:
XS GIS Cut Line= 3
      2895766.51      6971422.32      2896400.00      6971350.00
      2896700.00      6970950.00
#Sta/Elev= 30
  4512.4  366.45  4591.4  366.31  4623.8  364.72  4641.7  360.82  4671.9  358.70
  4788.3  354.71  4792.5  355.09  4797.5  351.47  4812.8  351.07  4833.0  347.02
  4865.5  345.68  4888.2  345.20  4976.3  345.12  4988.1  342.70  4994.0  340.71
  5004.1  340.39  5034.3  344.23  5097.3  346.15  5158.0  346.78  5329.2  344.52
  5335.4  344.19  5343.7  340.59  5352.6  339.02  5353.2  338.22  5360.0  339.02
  5364.3  345.68  5370.8  348.45  5555.4  370.30  5629.2  373.86  5650.0  373.34
#Mann=9,-1,0
  4512.4    0.16       0  4788.3    0.12       0  4888.2    0.16       0
  4988.1    0.12       0  5097.3    0.16       0  5158.0    0.12       0
  5352.6    0.07       0  5360.0    0.12       0  5555.4    0.16       0
Bank Sta=4865.5,5364.3
Exp/Cntr=0.3,0.1

Type RM Length L Ch R = 1,5945,546,546,546
BEGIN DESCRIPTION:
double TURMAN BRANCH 5.0
END DESCRIPTION:
XS GIS Cut Line= 3
      2895889.45      6971460.00      2896400.00      6971550.00
      2896788.79      6971137.05
#Sta/Elev= 30
  4597.7  360.84  4652.2  358.55  4716.5  351.67  4840.9  344.60  4849.1  344.31
  4979.0  343.81  4989.2  343.22  4997.6  338.87  5019.7  343.56  5029.8  343.92
  5090.7  342.83  5111.0  344.55  5208.0  342.65  5271.9  344.40  5392.1  343.68
  5420.4  345.36  5434.5  344.85  5448.7  342.46  5451.9  338.53  5452.5  337.73
  5459.3  338.53  5462.9  338.73  5467.6  344.60  5469.7  347.17  5505.3  352.25
  5562.0  364.72  5618.2  373.22  5653.8  374.17  5681.3  372.32  5683.3  372.32
#Mann=5,-1,0
  4597.7    0.16       0  4849.1    0.12       0  5451.9    0.07       0
  5459.3    0.12       0  5681.3    0.16       0
Bank Sta=4840.9,5467.6
Exp/Cntr=0.3,0.1

Type RM Length L Ch R = 1,5399,260,260,260
BEGIN DESCRIPTION:
double TURMAN BRANCH 4.0
END DESCRIPTION:
XS GIS Cut Line= 3
      2896025.02      6972324.99      2896475.00      6971975.00
      2896824.99      6971225.01
#Sta/Elev= 30
  4430.3  370.54  4466.5  365.00  4493.6  354.13  4508.1  351.16  4537.1  351.40
  4580.5  347.77  4586.8  350.47  4632.5  346.53  4681.2  341.97  4808.5  340.20
  4823.0  337.11  4843.8  340.82  4978.6  341.30  4986.8  340.96  4997.2  335.85
  5009.0  337.10  5022.4  341.51  5151.7  341.94  5157.2  338.66  5170.9  335.78
  5171.5  334.98  5178.3  335.78  5180.1  339.33  5188.0  341.77  5243.1  340.36
  5377.1  341.97  5505.6  343.10  5596.3  346.62  5773.6  370.43  5828.0  373.47
#Mann=4,-1,0
  4430.3    0.08       0  4632.5    0.12       0  5170.9    0.07       0
  5178.3    0.12       0
Bank Sta=4681.2,5377.1
Exp/Cntr=0.3,0.1

Type RM Length L Ch R = 1,5139,1430,1430,1430
BEGIN DESCRIPTION:
Mapping XS dd2d46c7
END DESCRIPTION:
XS GIS Cut Line= 4
      2896174.39      6972228.91      2896344.54      6972187.24
      2896893.15      6972121.27      2896910.51      6971322.69
#Sta/Elev= 30
  4540.8  348.61  4572.3  347.56  4603.2  341.81  4614.6  341.64  4649.4  341.20
  4695.9  340.13  4713.6  337.16  4736.6  340.04  4774.2  337.35  4779.3  339.90
  4837.3  338.74  4948.6  340.22  4958.2  336.85  4973.3  334.88  4974.3  334.08
  4983.3  334.88  4998.5  335.45  5025.8  340.69  5058.9  338.44  5089.1  340.50
  5230.1  339.52  5250.3  338.19  5408.8  339.58  5661.6  341.58  5667.5  341.64
  5759.4  342.68  5834.9  344.52  5939.8  357.82  6005.0  364.53  6067.3  363.87
#Mann=8,-1,0
  4540.8    0.08       0  4649.4    0.12       0  4973.3    0.07       0
  4983.3    0.12       0  5408.8    0.05       0  5661.6    0.16       0
  5759.4    0.12       0  5939.8    0.16       0
Bank Sta=4614.6,5667.5
Exp/Cntr=0.3,0.1

Type RM Length L Ch R = 1,3709,78,78,78
BEGIN DESCRIPTION:
Mapping XS 4a2d1d70
END DESCRIPTION:
XS GIS Cut Line= 3
      2896191.02      6972231.41      2898086.81      6972314.74
      2898836.78      6972262.66
#Sta/Elev= 30
  3183.7  345.70  3324.0  339.78  3357.9  338.81  3396.1  340.21  3437.9  341.88
  3508.0  340.13  3878.4  338.11  4515.8  337.27  4796.2  336.17  4895.2  337.06
  4959.4  337.23  4994.3  333.32  4995.3  332.52  5004.5  333.32  5027.9  337.27
  5093.3  337.73  5192.7  338.39  5239.9  339.17  5289.5  342.26  5310.1  340.26
  5350.2  340.99  5620.8  350.26  5721.1  355.62  5726.6  356.14  5731.6  359.44
  5751.1  363.48  5781.2  367.97  5801.2  368.02  5811.3  370.44  5833.1  369.18
#Mann=9,-1,0
  3183.7    0.08       0  3324.0    0.05       0  3396.1    0.08       0
  4796.2    0.05       0  4895.2    0.08       0  4994.3    0.07       0
  5004.5    0.08       0  5093.3    0.05       0  5192.7    0.08       0
Bank Sta=4515.8,5027.9
Exp/Cntr=0.3,0.1