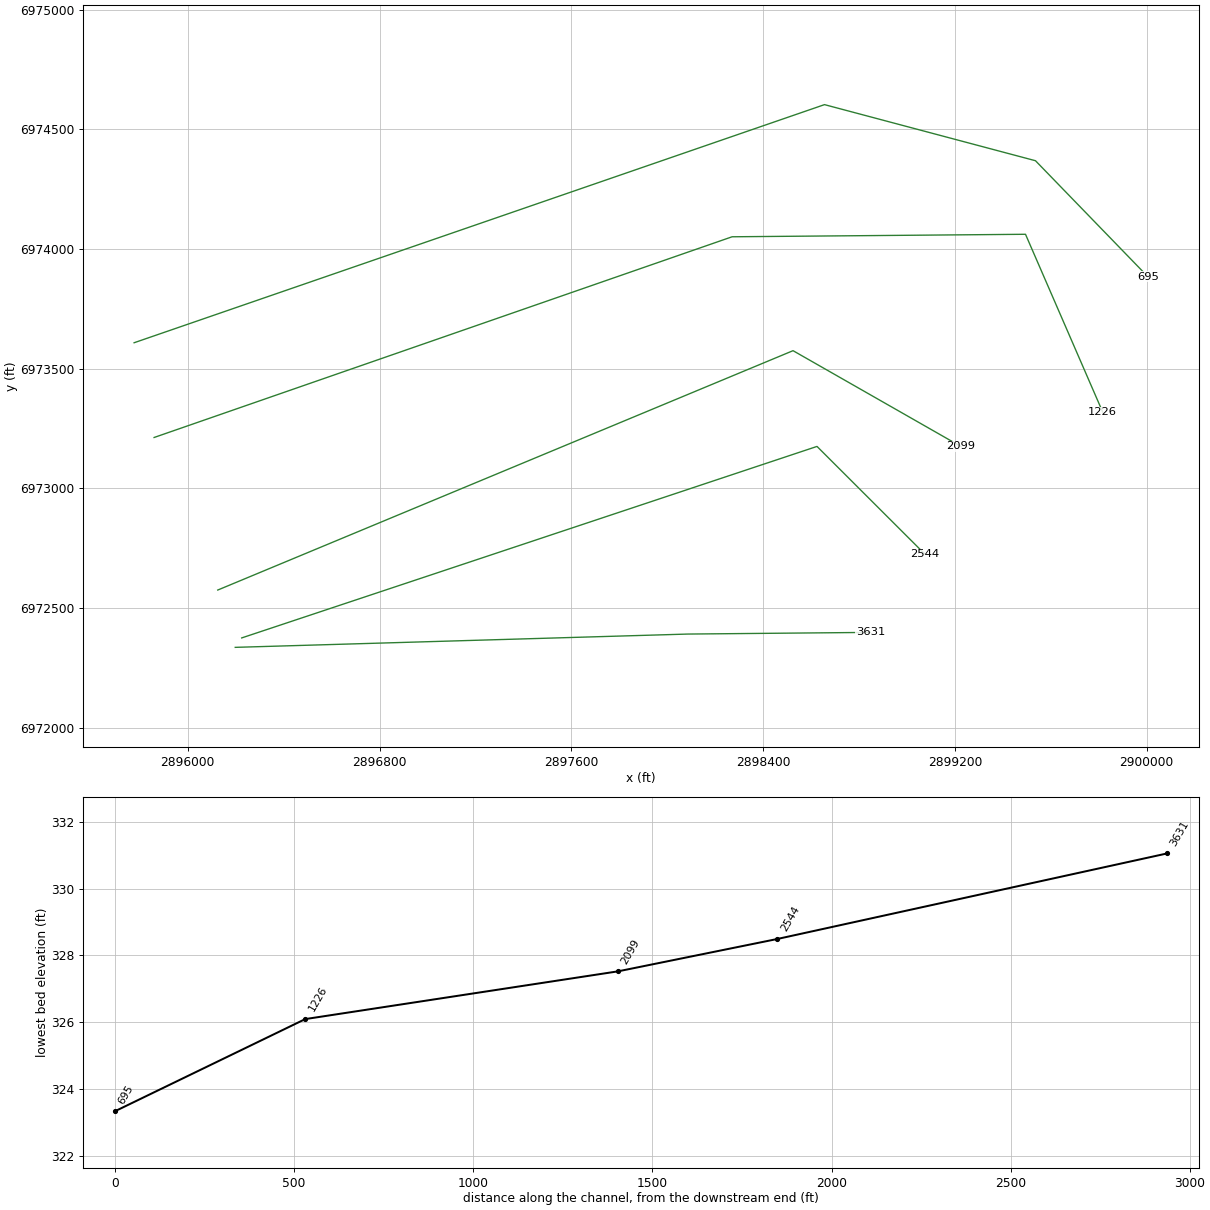
HEC-RAS study TURMAN BRANCH.prj: TURMAN BRANCH Base Level Engineering

--- TURMAN BRANCH.g01 (geometry) --- (continued)

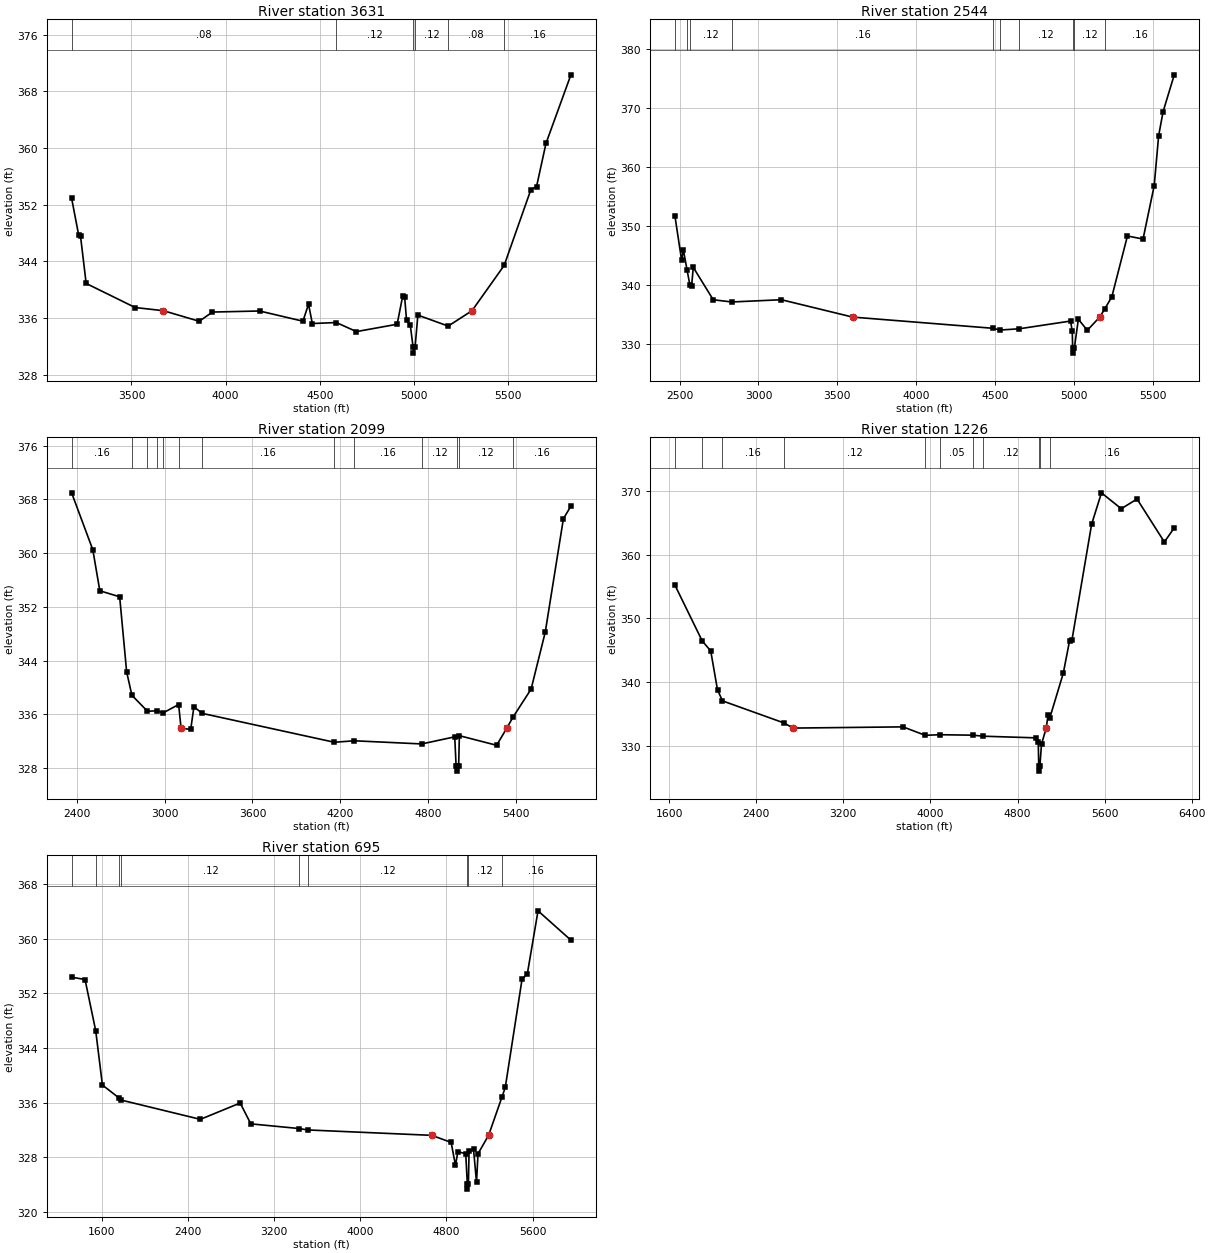
Type RM Length L Ch R = 1,3631,1087,1087,1087
BEGIN DESCRIPTION:
Mapping XS 3a209994
END DESCRIPTION:
XS GIS Cut Line= 3
      2896197.96      6972335.57      2898086.81      6972391.13
      2898847.21      6972398.07
#Sta/Elev= 30
  3182.5  352.91  3219.6  347.76  3229.6  347.59  3259.6  340.89  3519.7  337.49
  3669.8  337.04  3859.8  335.55  3929.9  336.85  4180.0  337.00  4410.1  335.56
  4440.1  337.96  4460.1  335.23  4587.3  335.37  4694.4  334.09  4910.3  335.13
  4940.3  339.18  4950.3  338.92  4960.3  335.70  4980.3  334.97  4995.2  331.85
  4996.2  331.05  5005.4  331.85  5020.3  336.42  5181.3  334.87  5307.8  337.04
  5478.3  343.43  5620.4  354.15  5650.4  354.58  5700.4  360.67  5832.6  370.35
#Mann=6,-1,0
  3182.5    0.08       0  4587.3    0.12       0  4995.2    0.07       0
  5005.4    0.12       0  5181.3    0.08       0  5478.3    0.16       0
Bank Sta=3669.8,5307.8
Exp/Cntr=0.3,0.1

Type RM Length L Ch R = 1,2544,445,445,445
BEGIN DESCRIPTION:
TURMAN BRANCH 3.0
END DESCRIPTION:
XS GIS Cut Line= 3
      2896224.96      6972374.99      2898625.00      6973175.00
      2899075.03      6972724.97
#Sta/Elev= 30
  2470.5  351.62  2512.7  344.17  2523.2  346.03  2547.1  342.54  2564.5  340.09
  2576.0  339.92  2586.5  343.00  2713.0  337.52  2831.1  337.15  3145.2  337.53
  3597.1  334.59  4488.9  332.69  4532.6  332.40  4653.3  332.61  4979.3  333.92
  4989.8  332.18  4992.6  329.29  4993.6  328.49  5002.8  329.29  5028.6  334.23
  5085.2  332.35  5164.0  334.59  5194.7  335.91  5240.8  338.02  5339.8  348.32
  5438.8  347.80  5509.5  356.83  5537.8  365.30  5566.0  369.37  5636.8  375.60
#Mann=10,-1,0
  2470.5    0.08       0  2547.1    0.16       0  2564.5    0.12       0
  2831.1    0.16       0  4488.9    0.12       0  4532.6    0.16       0
  4653.3    0.12       0  4992.6    0.07       0  5002.8    0.12       0
  5194.7    0.16       0
Bank Sta=3597.1,5164
Exp/Cntr=0.3,0.1

Type RM Length L Ch R = 1,2099,873,873,873
BEGIN DESCRIPTION:
TURMAN BRANCH 2.0
END DESCRIPTION:
XS GIS Cut Line= 3
      2896125.00      6972575.00      2898525.00      6973575.00
      2899224.97      6973175.02
#Sta/Elev= 30
  2366.3  368.98  2510.9  360.49  2558.6  354.39  2694.0  353.49  2741.7  342.30
  2777.5  338.82  2883.8  336.44  2949.2  336.51  2990.0  336.19  3096.3  337.44
  3112.9  333.91  3178.8  333.74  3200.5  337.10  3258.0  336.12  4158.8  331.82
  4295.2  332.04  4755.2  331.57  4980.0  332.63  4989.3  328.33  4996.4  328.32
  4997.3  327.52  5006.7  328.32  5011.7  332.80  5265.8  331.37  5334.7  333.91
  5377.6  335.56  5501.1  339.74  5597.6  348.23  5721.4  365.12  5772.5  367.00
#Mann=13,-1,0
  2366.3    0.16       0  2777.5    0.12       0  2883.8    0.16       0
  2949.2    0.12       0  2990.0    0.16       0  3096.3    0.12       0
  3258.0    0.16       0  4158.8    0.12       0  4295.2    0.16       0
  4755.2    0.12       0  4996.4    0.07       0  5006.7    0.12       0
  5377.6    0.16       0
Bank Sta=3112.9,5334.7
Exp/Cntr=0.3,0.1

Type RM Length L Ch R = 1,1226,531,531,531
BEGIN DESCRIPTION:
Mapping XS 854e0bc3
END DESCRIPTION:
XS GIS Cut Line= 4
      2895859.43      6973212.32      2898270.84      6974050.85
      2899494.80      6974061.27      2899816.95      6973318.25
#Sta/Elev= 30
  1653.3  355.19  1903.2  346.48  1981.6  344.91  2043.8  338.81  2089.6  337.09
  2655.2  333.63  2737.7  332.83  3748.6  333.02  3951.7  331.70  4087.2  331.79
  4390.0  331.72  4482.7  331.56  4970.5  331.30  4990.5  330.72  4995.3  326.89
  4996.3  326.09  5005.7  326.89  5020.5  330.31  5063.8  332.83  5080.5  334.83
  5096.7  334.42  5220.5  341.42  5278.6  346.53  5300.5  346.64  5480.8  364.74
  5571.3  369.67  5753.3  367.18  5898.2  368.70  6149.2  361.97  6240.2  364.19
#Mann=11,-1,0
  1653.3    0.16       0  1903.2    0.12       0  2089.6    0.16       0
  2655.2    0.12       0  3951.7    0.16       0  4087.2    0.05       0
  4390.0    0.07       0  4482.7    0.12       0  4995.3    0.07       0
  5005.7    0.12       0  5096.7    0.16       0
Bank Sta=2737.7,5063.8
Exp/Cntr=0.3,0.1

Type RM Length L Ch R = 1,695,0,0,0
BEGIN DESCRIPTION:
TURMAN BRANCH 1.0
END DESCRIPTION:
XS GIS Cut Line= 4
      2895776.01      6973608.13      2898656.26      6974602.93
      2899536.46      6974368.56      2900005.19      6973884.21
#Sta/Elev= 30
  1322.2  354.34  1446.6  354.00  1545.9  346.48  1607.8  338.56  1758.5  336.71
  1784.6  336.35  2516.6  333.54  2885.9  335.93  2984.7  332.88  3436.0  332.19
  3510.7  331.99  4663.2  331.20  4843.1  330.17  4883.2  326.83  4906.2  328.81
  4978.7  328.51  4993.2  324.13  4994.1  323.33  5003.6  324.13  5009.7  328.98
  5051.1  329.13  5078.7  324.31  5092.5  328.51  5190.8  331.20  5313.8  336.76
  5345.4  338.20  5501.0  354.03  5550.4  354.85  5649.4  364.05  5954.3  359.76
#Mann=9,-1,0
  1322.2    0.16       0  1545.9    0.12       0  1758.5    0.16       0
  1784.6    0.12       0  3436.0    0.16       0  3510.7    0.12       0
  4993.2    0.07       0  5003.6    0.12       0  5313.8    0.16       0
Bank Sta=4663.2,5190.8
Exp/Cntr=0.3,0.1

Chan Stop Cuts=-1