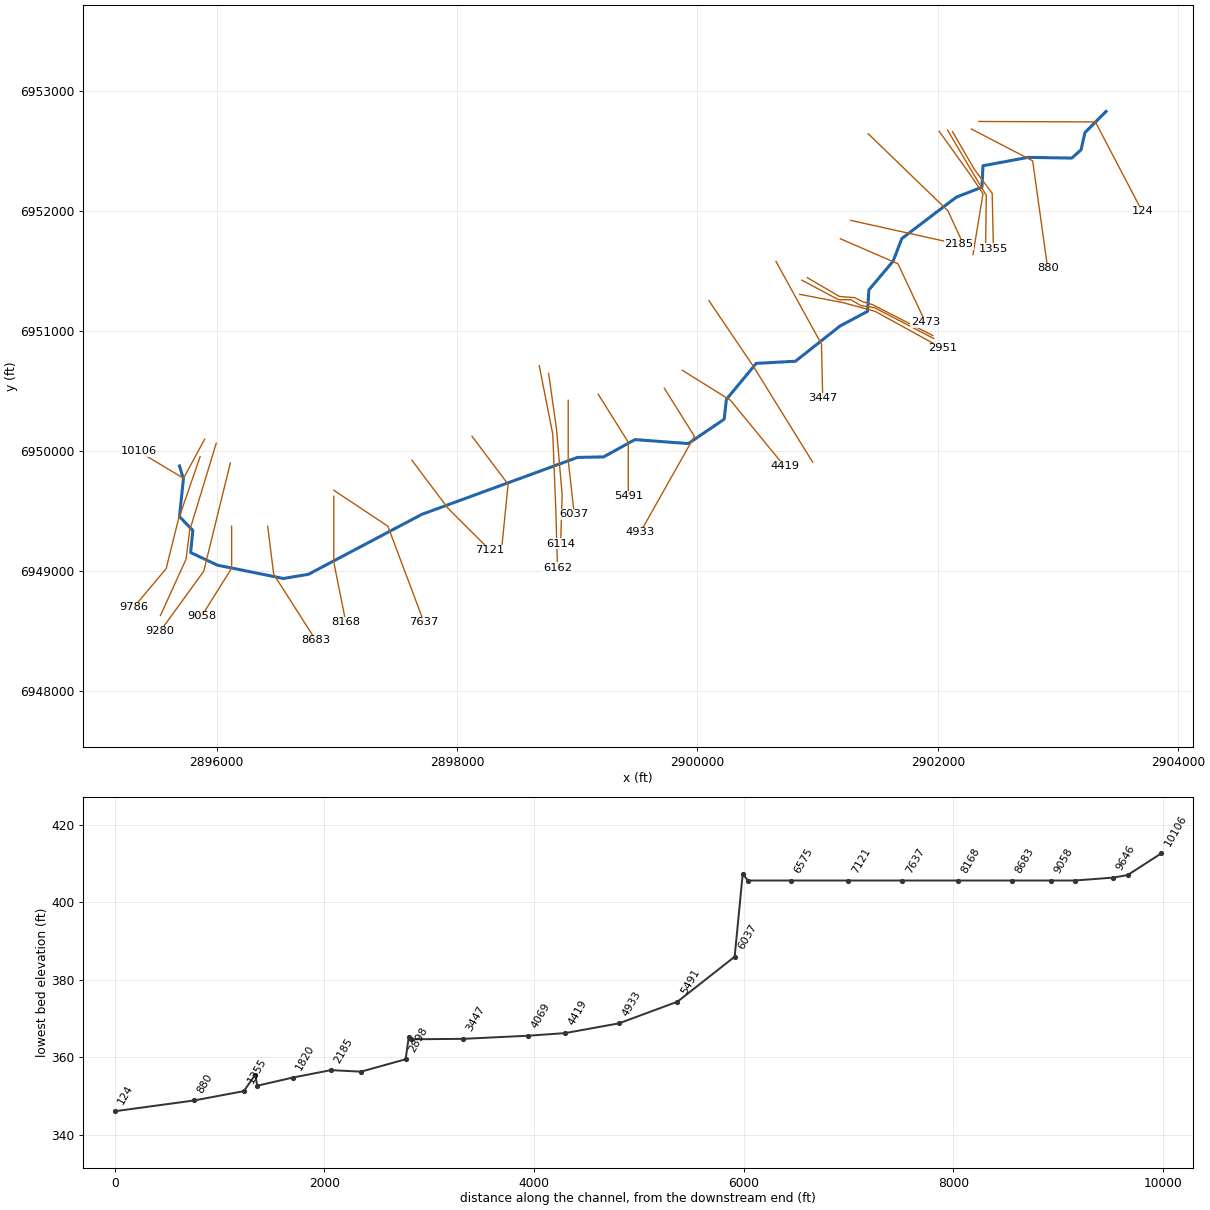
--- TWOMILE BRANCH.prj (project) ---

Proj Title=TWOMILE BRANCH Base Level Engineering
Current Plan=p01
Default Exp/Contr=0.3,0.1
English Units
Geom File=g01
Flow File=f01
Plan File=p01
BEGIN DESCRIPTION:
TWOMILE BRANCH
END DESCRIPTION:

--- TWOMILE BRANCH.p01 (plan) ---

Plan Title=Multiple Run
Short Identifier=Multiple
Geom File=g01
Flow File=f01
Subcritical Flow
K Sum by GR= 0
Std Step Tol= 0.01
Critical Tol= 0.01
Num of Std Step Trials= 20
Max Error Tol= 0.3
Flow Tol Ratio= 0.001
Split Flow NTrial= 30
Split Flow Tol= 0.02
Split Flow Ratio= 0.02
Log Output Level= 0
Friction Slope Method= 1
Unsteady Friction Slope Method= 2
Unsteady Bridges Friction Slope Method= 1
Parabolic Critical Depth
Global Vel Dist=  1 , 1 , 1
Global Log Level= 0
CheckData=True
Encroach Param= -1, 0, 0, 0
BEGIN DESCRIPTION:
Multiple Run
END DESCRIPTION:

--- TWOMILE BRANCH.f01 (steady flow) ---

Flow Title=Multiple
Number of Profiles=7
Profile Names=10-year,25-year,50-year,1pct_min,100-year,1pct_plu,500-year
River Rch & RM= TWOMILE BRANCH,Reach-1,10106
     383     505     603     359     716    1429    1011
River Rch & RM= TWOMILE BRANCH,Reach-1,9786
     791    1087    1334     814    1624    3239    2409
River Rch & RM= TWOMILE BRANCH,Reach-1,6114
    1111    1558    1938    1197    2389    4766    3638
River Rch & RM= TWOMILE BRANCH,Reach-1,2473
    1147    1610    2005    1239    2472    4933    3769
River Rch & RM= TWOMILE BRANCH,Reach-1,1355
    1155    1620    2016    1245    2484    4957    3783
Boundary for River Rch & Prof#=TWOMILE BRANCH,Reach-1,1
Up Type=0
Dn Type=3
Dn Slope=0.005
Boundary for River Rch & Prof#=TWOMILE BRANCH,Reach-1,2
Up Type=0
Dn Type=3
Dn Slope=0.005
Boundary for River Rch & Prof#=TWOMILE BRANCH,Reach-1,3
Up Type=0
Dn Type=3
Dn Slope=0.005
Boundary for River Rch & Prof#=TWOMILE BRANCH,Reach-1,4
Up Type=0
Dn Type=3
Dn Slope=0.005
Boundary for River Rch & Prof#=TWOMILE BRANCH,Reach-1,5
Up Type=0
Dn Type=3
Dn Slope=0.005
Boundary for River Rch & Prof#=TWOMILE BRANCH,Reach-1,6
Up Type=0
Dn Type=3
Dn Slope=0.005
Boundary for River Rch & Prof#=TWOMILE BRANCH,Reach-1,7
Up Type=0
Dn Type=3
Dn Slope=0.005

--- TWOMILE BRANCH.g01 (geometry) ---

Geom Title=Existing Conditions

River Reach=TWOMILE BRANCH,Reach-1
Reach XY= 30
      2895691.27      6949877.86      2895723.82      6949769.36
      2895691.27      6949455.77      2895802.10      6949339.37
      2895784.04      6949156.02      2896006.37      6949050.74
      2896554.98      6948939.62      2896763.31      6948974.35
      2897707.76      6949474.35      2899001.53      6949948.71
      2899219.77      6949953.12      2899480.13      6950097.62
      2899924.12      6950064.24      2900222.26      6950267.29
      2900241.15      6950433.32      2900489.09      6950732.71
      2900815.59      6950750.71      2901186.06      6951044.23
      2901415.73      6951166.74      2901426.24      6951345.19
      2901627.66      6951584.57      2901700.34      6951773.63
      2902153.06      6952118.15      2902366.74      6952201.43
      2902375.50      6952380.30      2902750.32      6952450.21
      2903114.15      6952444.27      2903191.53      6952512.96
      2903223.77      6952657.27      2903398.99      6952832.61

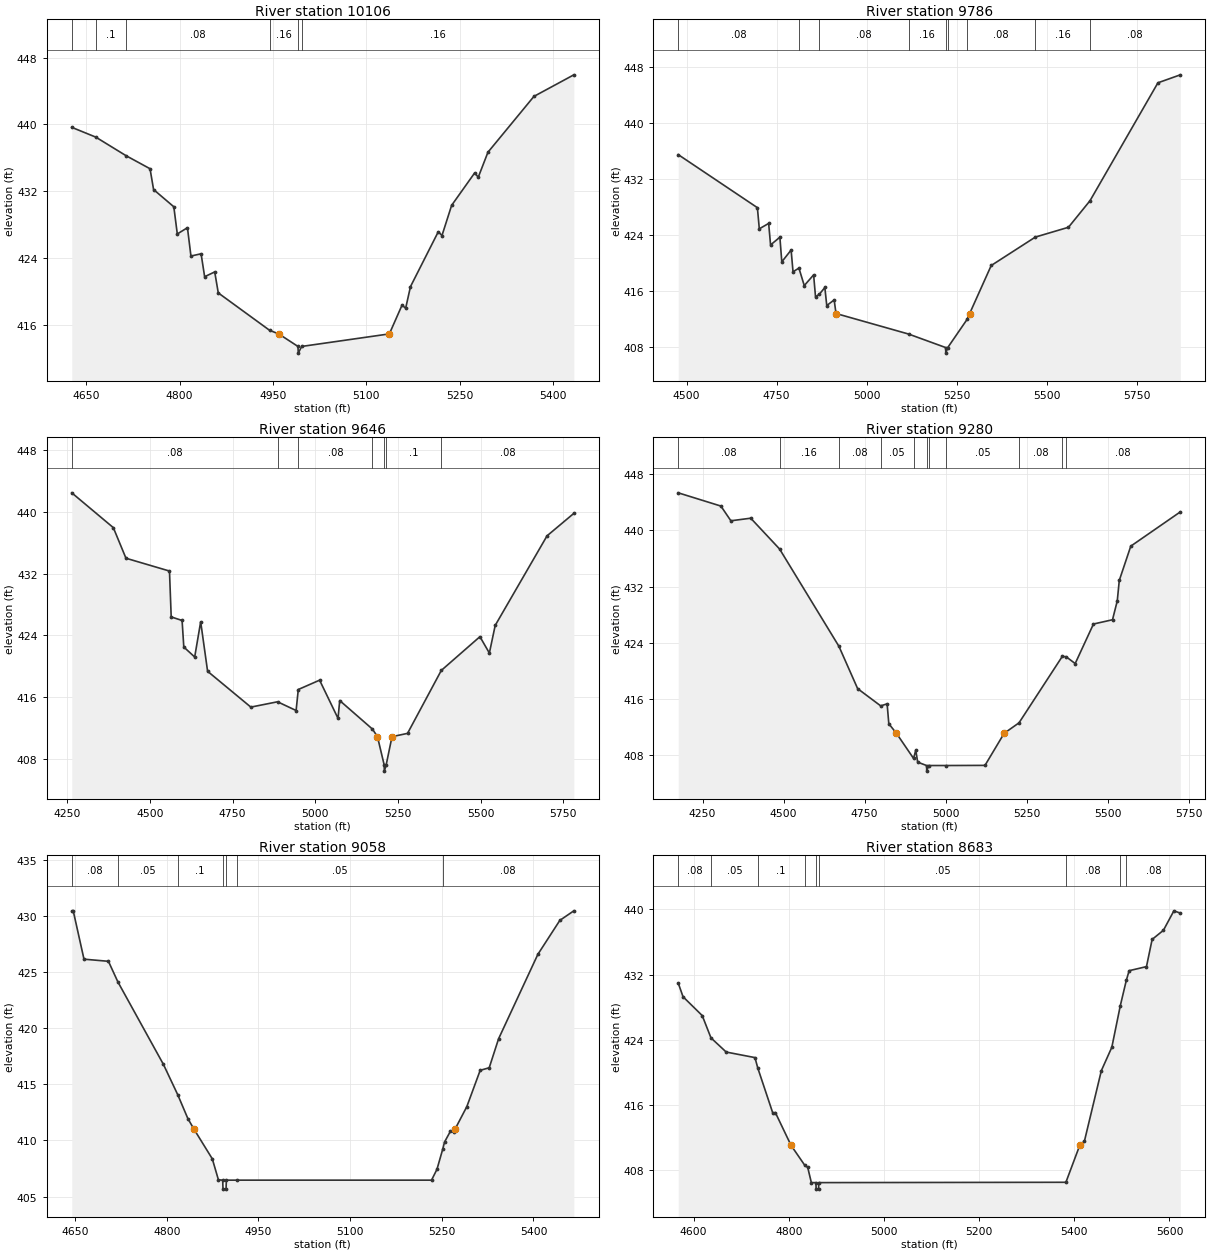
Type RM Length L Ch R = 1,10106,320,320,320
BEGIN DESCRIPTION:
TWOMILE BRANCH 19.0
END DESCRIPTION:
XS GIS Cut Line= 3
      2895900.00      6950099.99      2895725.00      6949775.00
      2895350.03      6949999.98
#Sta/Elev= 30
  4626.8  439.66  4665.4  438.49  4714.0  436.27  4752.5  434.71  4758.2  432.22
  4790.7  430.16  4796.3  426.91  4812.6  427.66  4818.2  424.27  4834.5  424.54
  4840.2  421.80  4856.4  422.37  4862.1  419.86  4944.7  415.38  4959.2  414.96
  4990.1  413.46  4990.6  412.66  4996.1  413.46  5136.9  414.96  5157.2  418.39
  5163.1  418.04  5170.8  420.61  5215.5  427.18  5221.4  426.72  5236.9  430.33
  5273.9  434.21  5279.7  433.70  5295.2  436.68  5369.1  443.36  5433.2  445.94
#Mann=6,-1,0
  4626.8    0.08       0  4665.4     0.1       0  4714.0    0.08       0
  4944.7    0.16       0  4990.1    0.07       0  4996.1    0.16       0
Bank Sta=4959.2,5136.9
Exp/Cntr=0.3,0.1

Type RM Length L Ch R = 1,9786,140,140,140
BEGIN DESCRIPTION:
Mapping XS f90fc2dd
END DESCRIPTION:
XS GIS Cut Line= 4
      2895862.65      6949954.91      2895680.37      6949425.44
      2895580.55      6949021.80      2895311.44      6948700.60
#Sta/Elev= 30
  4476.6  435.43  4696.5  427.85  4701.8  424.83  4727.8  425.60  4733.1  422.53
  4759.0  423.63  4764.3  420.11  4790.2  421.80  4795.5  418.69  4811.9  419.22
  4826.7  416.72  4852.7  418.25  4858.0  415.11  4868.8  415.49  4883.9  416.45
  4889.2  413.87  4909.8  414.67  4914.9  412.73  5116.3  409.80  5219.4  407.87
  5219.9  407.07  5225.4  407.87  5279.2  411.90  5286.2  412.73  5346.1  419.59
  5468.7  423.65  5560.7  425.05  5620.6  428.85  5809.2  445.69  5871.4  446.83
#Mann=9,-1,0
  4476.6    0.08       0  4811.9    0.16       0  4868.8    0.08       0
  5116.3    0.16       0  5219.4    0.07       0  5225.4    0.16       0
  5279.2    0.08       0  5468.7    0.16       0  5620.6    0.08       0
Bank Sta=4914.9,5286.2
Exp/Cntr=0.3,0.1

Type RM Length L Ch R = 1,9646,366,366,366
BEGIN DESCRIPTION:
Mapping XS 8911544c
END DESCRIPTION:
XS GIS Cut Line= 4
      2895997.22      6950067.82      2895775.86      6949338.64
      2895745.48      6949099.92      2895532.82      6948631.20
#Sta/Elev= 30
  4264.2  442.45  4389.8  437.94  4428.0  433.98  4559.5  432.32  4564.7  426.38
  4597.6  425.92  4602.8  422.48  4635.7  421.19  4653.8  425.75  4674.7  419.34
  4805.4  414.70  4886.1  415.39  4942.2  414.26  4948.8  416.98  5013.2  418.19
  5068.9  413.24  5074.0  415.55  5173.0  411.85  5188.1  410.87  5208.4  407.21
  5208.9  406.41  5214.4  407.21  5232.0  410.87  5279.0  411.30  5381.0  419.45
  5497.7  423.82  5526.3  421.70  5543.9  425.28  5700.6  436.88  5781.6  439.79
#Mann=7,-1,0
  4264.2    0.08       0  4886.1     0.1       0  4948.8    0.08       0
  5173.0     0.1       0  5208.4    0.07       0  5214.4     0.1       0
  5381.0    0.08       0
Bank Sta=5188.1,5232
Exp/Cntr=0.3,0.1

Type RM Length L Ch R = 1,9280,222,222,222
BEGIN DESCRIPTION:
Mapping XS f11f98a6
END DESCRIPTION:
XS GIS Cut Line= 3
      2896114.40      6949902.87      2895893.05      6949000.09
      2895529.25      6948497.70
#Sta/Elev= 30
  4174.9  445.37  4306.6  443.48  4337.4  441.38  4398.7  441.75  4487.8  437.35
  4670.9  423.47  4728.7  417.43  4799.9  414.97  4819.7  415.26  4824.9  412.42
  4848.4  411.06  4901.3  407.47  4908.1  408.65  4914.0  406.94  4941.5  406.46
  4942.0  405.66  4947.5  406.46  5002.6  406.46  5121.8  406.48  5181.0  411.06
  5226.8  412.55  5360.4  422.03  5372.3  421.98  5400.2  421.01  5456.6  426.65
  5515.4  427.26  5530.1  429.95  5536.3  432.87  5571.8  437.76  5724.7  442.65
#Mann=11,-1,0
  4174.9    0.08       0  4487.8    0.16       0  4670.9    0.08       0
  4799.9    0.05       0  4901.3     0.1       0  4941.5    0.07       0
  4947.5     0.1       0  5002.6    0.05       0  5226.8    0.08       0
  5360.4     0.1       0  5372.3    0.08       0
Bank Sta=4848.4,5181
Exp/Cntr=0.3,0.1

Type RM Length L Ch R = 1,9058,375,375,375
BEGIN DESCRIPTION:
TWOMILE BRANCH 16.0
END DESCRIPTION:
XS GIS Cut Line= 3
      2896125.00      6949375.05      2896125.00      6949025.00
      2895875.02      6948625.04
#Sta/Elev= 30
  4644.4  430.44  4646.9  430.44  4664.4  426.16  4704.4  425.97  4719.9  424.13
  4794.4  416.78  4817.8  414.08  4834.4  411.95  4843.9  411.05  4874.4  408.36
  4884.4  406.49  4891.4  406.46  4891.9  405.66  4896.9  405.66  4897.4  406.46
  4915.6  406.46  5233.2  406.46  5242.1  407.43  5251.5  409.22  5254.5  409.86
  5263.9  410.80  5269.8  410.74  5272.1  411.05  5291.0  413.02  5312.8  416.25
  5327.6  416.48  5342.9  419.06  5407.2  426.59  5443.2  429.62  5466.1  430.47
#Mann=7,-1,0
  4644.4    0.08       0  4719.9    0.05       0  4817.8     0.1       0
  4891.4   0.033       0  4897.4     0.1       0  4915.6    0.05       0
  5251.5    0.08       0
Bank Sta=4843.9,5272.1
Exp/Cntr=0.3,0.1

Type RM Length L Ch R = 1,8683,515,515,515
BEGIN DESCRIPTION:
TWOMILE BRANCH 15.0
END DESCRIPTION:
XS GIS Cut Line= 3
      2896425.00      6949375.00      2896475.00      6948975.00
      2896824.98      6948425.03
#Sta/Elev= 30
  4567.8  430.96  4577.9  429.28  4618.2  426.97  4636.6  424.23  4668.6  422.49
  4729.0  421.81  4734.9  420.54  4766.8  414.95  4771.9  415.06  4804.8  411.04
  4833.3  408.62  4839.9  408.32  4847.5  406.46  4857.1  406.46  4857.6  405.66
  4862.6  405.66  4863.1  406.46  5382.4  406.50  5411.5  411.04  5421.3  411.55
  5456.9  420.21  5478.9  423.08  5496.7  428.18  5509.4  431.31  5515.3  432.48
  5551.7  432.98  5563.6  436.32  5587.3  437.44  5609.3  439.83  5622.8  439.55
#Mann=9,-1,0
  4567.8    0.08       0  4636.6    0.05       0  4734.9     0.1       0
  4833.3    0.05       0  4857.1   0.033       0  4863.1    0.05       0
  5382.4    0.08       0  5496.7    0.16       0  5509.4    0.08       0
Bank Sta=4804.8,5411.5
Exp/Cntr=0.3,0.1

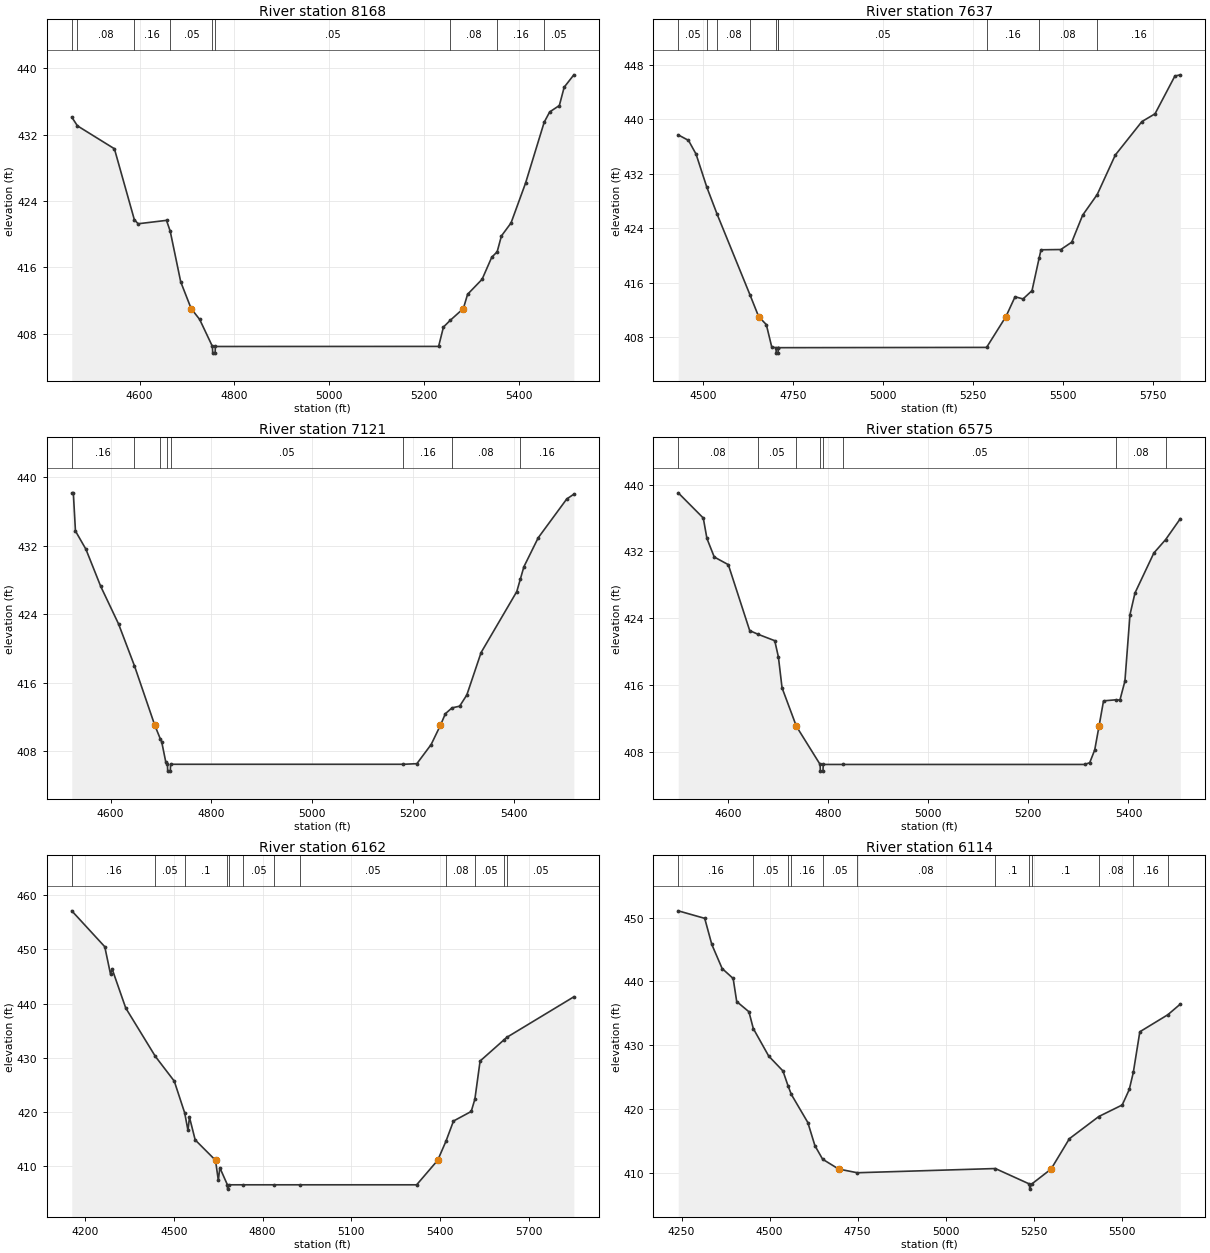
Type RM Length L Ch R = 1,8168,531,531,531
BEGIN DESCRIPTION:
TWOMILE BRANCH 14.0
END DESCRIPTION:
XS GIS Cut Line= 3
      2896975.00      6949625.02      2896975.00      6949075.00
      2897075.00      6948575.02
#Sta/Elev= 30
  4456.8  434.10  4468.8  433.05  4546.8  430.29  4588.8  421.76  4596.8  421.25
  4656.8  421.66  4664.6  420.36  4686.8  414.25  4708.8  411.03  4726.8  409.72
  4753.8  406.46  4754.3  405.66  4759.4  405.66  4759.9  406.46  5231.2  406.47
  5241.4  408.80  5255.5  409.60  5283.4  411.03  5292.4  412.75  5323.0  414.56
  5343.4  417.22  5354.8  417.87  5363.8  419.78  5384.1  421.35  5414.7  426.14
  5454.1  433.49  5465.7  434.73  5486.1  435.50  5496.3  437.71  5516.7  439.20
#Mann=9,-1,0
  4456.8    0.05       0  4468.8    0.08       0  4588.8    0.16       0
  4664.6    0.05       0  4753.8   0.033       0  4759.9    0.05       0
  5255.5    0.08       0  5354.8    0.16       0  5454.1    0.05       0
Bank Sta=4708.8,5283.4
Exp/Cntr=0.3,0.1

Type RM Length L Ch R = 1,7637,516,516,516
BEGIN DESCRIPTION:
TWOMILE BRANCH 13.0
END DESCRIPTION:
XS GIS Cut Line= 3
      2896975.02      6949674.98      2897425.00      6949375.00
      2897725.00      6948575.00
#Sta/Elev= 30
  4431.4  437.68  4459.9  436.87  4480.9  434.86  4510.6  430.04  4539.4  426.05
  4631.4  414.13  4654.8  411.03  4676.2  409.84  4691.3  406.55  4703.2  406.46
  4703.7  405.66  4708.8  405.66  4709.3  406.46  4709.8  406.46  5288.3  406.50
  5342.1  411.03  5367.4  413.93  5389.6  413.61  5414.5  414.83  5434.4  419.63
  5439.5  420.82  5494.6  420.86  5524.9  421.94  5555.2  425.90  5595.7  428.93
  5645.9  434.72  5719.8  439.63  5756.3  440.77  5811.5  446.31  5826.6  446.49
#Mann=10,-1,0
  4431.4    0.05       0  4510.6    0.16       0  4539.4    0.08       0
  4631.4    0.16       0  4703.2   0.033       0  4709.3    0.16       0
  4709.8    0.05       0  5288.3    0.16       0  5434.4    0.08       0
  5595.7    0.16       0
Bank Sta=4654.8,5342.1
Exp/Cntr=0.3,0.1

Type RM Length L Ch R = 1,7121,546,546,546
BEGIN DESCRIPTION:
TWOMILE BRANCH 12.0
END DESCRIPTION:
XS GIS Cut Line= 3
      2897624.99      6949925.02      2897925.00      6949525.00
      2898275.00      6949175.00
#Sta/Elev= 30
  4523.1  438.18  4526.2  438.18  4530.4  433.72  4551.2  431.58  4580.4  427.26
  4615.8  422.86  4647.3  417.97  4687.6  411.02  4698.9  409.38  4701.2  409.12
  4709.6  406.67  4712.7  406.46  4713.2  405.66  4718.4  405.66  4718.9  406.46
  5180.3  406.46  5207.0  406.53  5235.3  408.77  5253.7  411.02  5263.5  412.37
  5276.6  413.05  5291.8  413.25  5306.0  414.56  5334.3  419.52  5405.0  426.64
  5411.9  428.06  5419.1  429.54  5447.4  432.92  5504.0  437.46  5518.1  438.02
#Mann=8,-1,0
  4523.1    0.16       0  4647.3    0.08       0  4698.9    0.05       0
  4712.7   0.033       0  4718.9    0.05       0  5180.3    0.16       0
  5276.6    0.08       0  5411.9    0.16       0
Bank Sta=4687.6,5253.7
Exp/Cntr=0.3,0.1

Type RM Length L Ch R = 1,6575,413,413,413
BEGIN DESCRIPTION:
TWOMILE BRANCH 11.0
END DESCRIPTION:
XS GIS Cut Line= 3
      2898125.01      6950124.99      2898425.00      6949725.00
      2898375.00      6949224.98
#Sta/Elev= 30
  4501.0  439.01  4551.0  435.99  4558.3  433.54  4572.9  431.32  4601.0  430.40
  4643.7  422.50  4660.3  422.06  4693.7  421.29  4701.0  419.34  4708.3  415.64
  4736.3  411.13  4737.1  411.01  4784.3  406.46  4784.8  405.66  4790.0  405.66
  4790.5  406.46  4830.6  406.46  5312.5  406.46  5322.6  406.67  5332.6  408.20
  5341.1  411.01  5350.2  414.08  5375.5  414.21  5382.9  414.17  5392.9  416.45
  5403.0  424.41  5413.0  427.01  5450.7  431.80  5474.1  433.40  5503.5  435.91
#Mann=8,-1,0
  4501.0    0.08       0  4660.3    0.05       0  4736.3     0.1       0
  4784.3   0.033       0  4790.5     0.1       0  4830.6    0.05       0
  5375.5    0.08       0  5474.1    0.05       0
Bank Sta=4737.1,5341.1
Exp/Cntr=0.3,0.1

Type RM Length L Ch R = 1,6162,48,48,48
BEGIN DESCRIPTION:
Mapping XS e8525f50
END DESCRIPTION:
XS GIS Cut Line= 4
      2898683.84      6950714.53      2898796.69      6950141.59
      2898822.74      6949490.55      2898835.70      6949028.04
#Sta/Elev= 30
  4154.7  457.15  4266.3  450.51  4285.8  445.42  4290.9  446.44  4337.2  439.17
  4437.5  430.21  4501.4  425.64  4536.7  419.75  4547.7  416.53  4552.8  418.96
  4572.1  414.77  4640.9  411.00  4650.4  407.28  4655.5  409.63  4681.1  406.46
  4681.6  405.66  4687.4  406.46  4735.3  406.46  4838.3  406.46  4926.6  406.46
  5321.2  406.46  5392.4  411.00  5420.4  414.53  5445.8  418.26  5505.8  420.03
  5518.2  422.32  5535.8  429.36  5616.0  433.25  5626.1  433.74  5852.9  441.24
#Mann=12,-1,0
  4154.7    0.16       0  4437.5    0.05       0  4536.7     0.1       0
  4681.1   0.033       0  4687.4     0.1       0  4735.3    0.05       0
  4838.3     0.1       0  4926.6    0.05       0  5420.4    0.08       0
  5518.2    0.05       0  5616.0    0.16       0  5626.1    0.05       0
Bank Sta=4640.9,5392.4
Exp/Cntr=0.3,0.1

Type RM Length L Ch R = 1,6114,77,77,77
BEGIN DESCRIPTION:
Mapping XS 8ea1af7d
END DESCRIPTION:
XS GIS Cut Line= 4
      2898761.97      6950649.44      2898827.08      6950189.33
      2898874.82      6949633.77      2898861.80      6949230.08
#Sta/Elev= 30
  4240.4  451.08  4315.6  449.90  4335.8  445.80  4365.1  442.03  4396.4  440.47
  4406.5  436.85  4441.2  435.25  4453.6  432.62  4497.4  428.30  4537.8  425.97
  4552.1  423.67  4561.6  422.29  4608.5  417.88  4628.7  414.24  4650.6  412.12
  4696.1  410.58  4748.9  410.00  5141.1  410.66  5238.2  408.23  5238.7  407.43
  5244.5  408.23  5299.5  410.58  5351.5  415.34  5435.1  418.82  5501.6  420.63
  5521.6  423.06  5533.1  425.74  5551.6  432.11  5631.1  434.78  5666.6  436.45
#Mann=12,-1,0
  4240.4    0.16       0  4453.6    0.05       0  4552.1     0.1       0
  4561.6    0.16       0  4650.6    0.05       0  4748.9    0.08       0
  5141.1     0.1       0  5238.2    0.07       0  5244.5     0.1       0
  5435.1    0.08       0  5533.1    0.16       0  5631.1    0.05       0
Bank Sta=4696.1,5299.5
Exp/Cntr=0.3,0.1

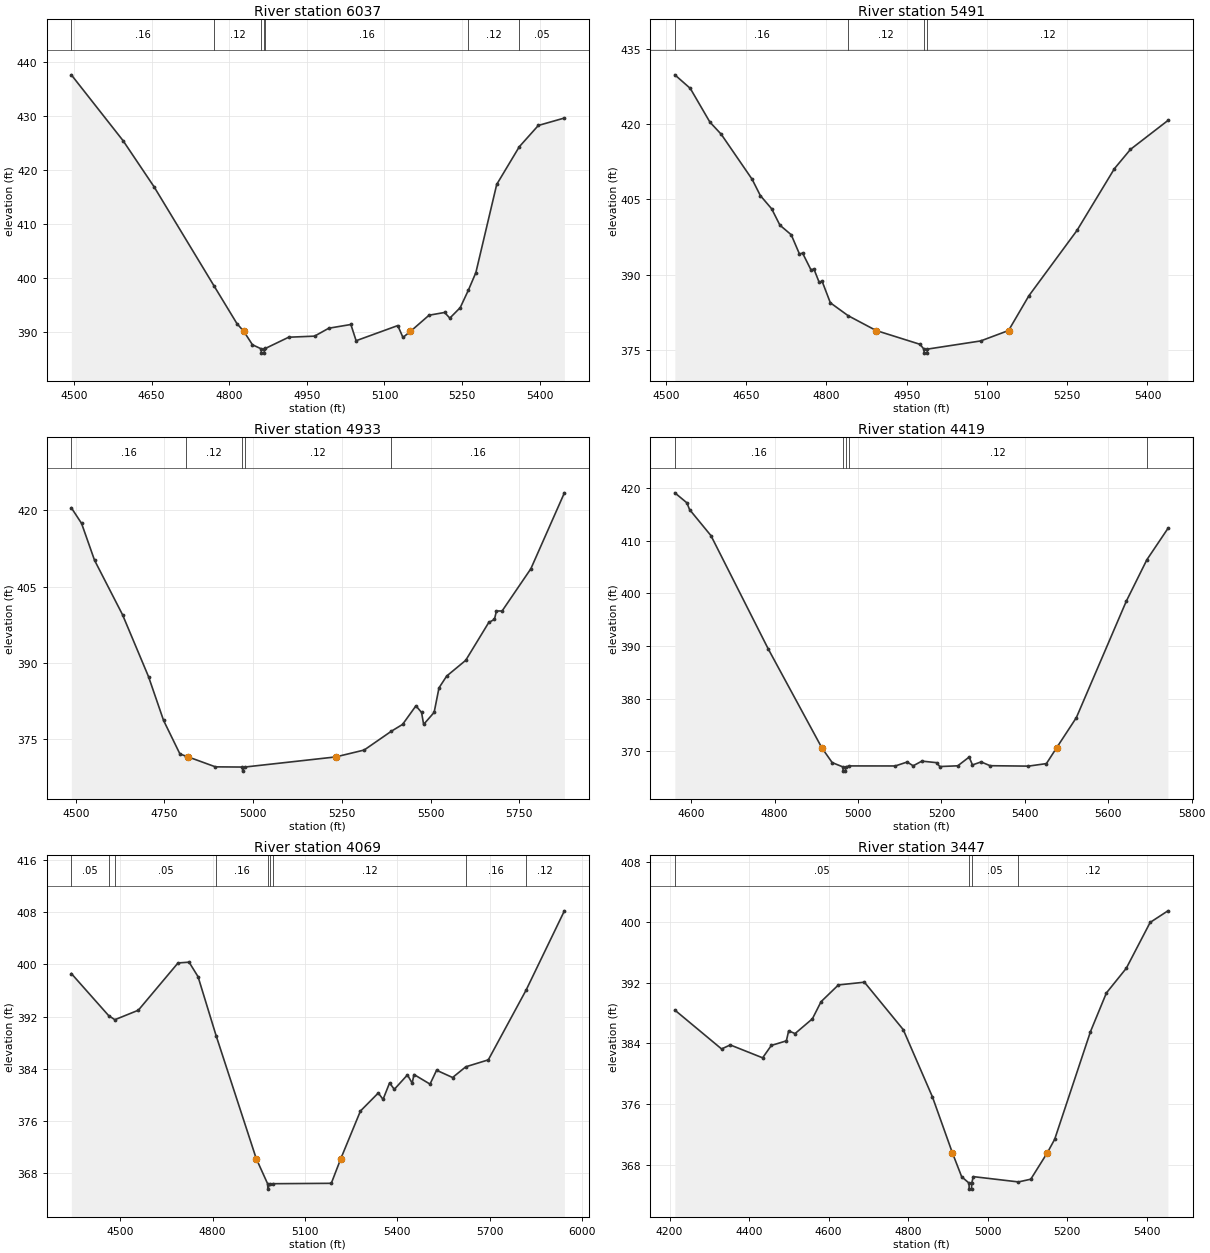
Type RM Length L Ch R = 1,6037,546,546,546
BEGIN DESCRIPTION:
TWOMILE BRANCH 10.0
END DESCRIPTION:
XS GIS Cut Line= 3
      2898925.00      6950424.99      2898925.00      6949925.00
      2898975.00      6949474.96
#Sta/Elev= 30
  4494.9  437.60  4594.9  425.39  4654.9  416.82  4770.6  398.47  4814.9  391.47
  4828.3  390.01  4844.9  387.54  4861.7  386.79  4862.2  385.99  4867.5  385.99
  4868.0  386.79  4869.9  386.86  4914.9  388.94  4964.9  389.14  4992.4  390.61
  5035.1  391.30  5045.2  388.29  5125.7  391.10  5135.7  388.90  5150.1  390.01
  5186.1  393.02  5216.2  393.53  5226.3  392.48  5246.4  394.43  5262.3  397.70
  5276.6  400.92  5316.9  417.28  5360.5  424.26  5397.3  428.21  5447.7  429.59
#Mann=7,-1,0
  4494.9    0.16       0  4770.6    0.12       0  4861.7    0.07       0
  4868.0    0.12       0  4869.9    0.16       0  5262.3    0.12       0
  5360.5    0.05       0
Bank Sta=4828.3,5150.1
Exp/Cntr=0.3,0.1

Type RM Length L Ch R = 1,5491,558,558,558
BEGIN DESCRIPTION:
TWOMILE BRANCH 9.0
END DESCRIPTION:
XS GIS Cut Line= 3
      2899174.98      6950475.03      2899425.00      6950075.00
      2899425.00      6949625.03
#Sta/Elev= 30
  4516.6  429.85  4545.5  427.14  4582.1  420.43  4603.3  418.00  4661.1  409.02
  4676.4  405.78  4697.6  403.14  4713.0  399.88  4734.2  397.96  4749.5  394.14
  4755.4  394.31  4770.8  391.02  4776.7  391.10  4786.1  388.56  4792.0  388.66
  4807.3  384.40  4840.6  381.83  4892.8  378.88  4974.8  376.13  4982.2  375.17
  4982.7  374.37  4988.1  374.37  4988.6  375.17  5088.3  376.80  5140.4  378.88
  5178.3  385.79  5268.3  398.83  5338.3  411.15  5368.3  414.99  5438.3  420.75
#Mann=4,-1,0
  4516.6    0.16       0  4840.6    0.12       0  4982.2    0.07       0
  4988.6    0.12       0
Bank Sta=4892.8,5140.4
Exp/Cntr=0.3,0.1

Type RM Length L Ch R = 1,4933,514,514,514
BEGIN DESCRIPTION:
TWOMILE BRANCH 8.0
END DESCRIPTION:
XS GIS Cut Line= 3
      2899725.02      6950524.97      2899975.00      6950125.00
      2899525.02      6949325.04
#Sta/Elev= 30
  4487.6  420.52  4516.5  417.44  4553.0  410.21  4632.0  399.49  4705.1  387.35
  4747.6  378.73  4793.6  372.16  4811.0  371.71  4817.0  371.57  4893.8  369.62
  4969.8  369.58  4970.3  368.78  4976.2  369.58  5232.5  371.57  5312.7  372.92
  5389.5  376.62  5421.1  377.96  5458.7  381.61  5474.6  380.30  5480.4  377.96
  5510.0  380.32  5523.7  385.14  5545.4  387.46  5598.9  390.54  5663.9  397.98
  5679.9  398.59  5685.6  400.24  5701.5  400.24  5782.5  408.53  5877.1  423.45
#Mann=5,-1,0
  4487.6    0.16       0  4811.0    0.12       0  4969.8    0.07       0
  4976.2    0.12       0  5389.5    0.16       0
Bank Sta=4817,5232.5
Exp/Cntr=0.3,0.1

Type RM Length L Ch R = 1,4419,350,350,350
BEGIN DESCRIPTION:
TWOMILE BRANCH 7.0
END DESCRIPTION:
XS GIS Cut Line= 3
      2899875.02      6950674.98      2900275.00      6950425.00
      2900725.00      6949875.00
#Sta/Elev= 30
  4560.8  419.12  4589.7  417.22  4596.1  415.94  4647.4  410.99  4784.8  389.46
  4913.4  370.67  4938.1  367.88  4963.8  367.06  4964.3  366.26  4969.7  366.26
  4970.2  367.06  4979.1  367.25  5089.2  367.24  5117.9  367.99  5132.2  367.27
  5153.1  368.16  5188.2  367.87  5196.1  367.13  5239.2  367.27  5266.5  368.93
  5274.4  367.44  5295.2  368.01  5316.7  367.29  5408.6  367.21  5451.7  367.69
  5476.0  370.67  5523.5  376.42  5643.3  398.54  5692.6  406.41  5743.1  412.36
#Mann=5,-1,0
  4560.8    0.16       0  4963.8    0.07       0  4970.2    0.16       0
  4979.1    0.12       0  5692.6    0.16       0
Bank Sta=4913.4,5476
Exp/Cntr=0.3,0.1

Type RM Length L Ch R = 1,4069,622,622,622
BEGIN DESCRIPTION:
TWOMILE BRANCH 6.0
END DESCRIPTION:
XS GIS Cut Line= 3
      2900095.40      6951255.92      2900464.11      6950710.09
      2900959.05      6949908.47
#Sta/Elev= 30
  4341.3  398.60  4462.6  392.15  4482.6  391.53  4558.8  392.98  4687.7  400.22
  4723.6  400.34  4752.7  398.12  4811.4  389.08  4941.7  370.26  4978.8  366.39
  4979.3  365.59  4985.2  366.39  4997.2  366.42  5185.3  366.48  5216.2  370.26
  5279.9  377.55  5337.9  380.31  5353.3  379.33  5374.5  381.85  5389.9  380.87
  5432.5  383.08  5447.9  381.81  5453.7  383.14  5505.8  381.67  5527.1  383.79
  5579.1  382.68  5621.9  384.32  5695.0  385.38  5817.7  396.06  5942.1  408.20
#Mann=9,-1,0
  4341.3    0.05       0  4462.6    0.16       0  4482.6    0.05       0
  4811.4    0.16       0  4978.8    0.07       0  4985.2    0.16       0
  4997.2    0.12       0  5621.9    0.16       0  5817.7    0.12       0
Bank Sta=4941.7,5216.2
Exp/Cntr=0.3,0.1

Type RM Length L Ch R = 1,3447,496,496,496
BEGIN DESCRIPTION:
TWOMILE BRANCH 5.0
END DESCRIPTION:
XS GIS Cut Line= 3
      2900653.34      6951582.72      2901031.93      6950893.11
      2901042.25      6950440.33
#Sta/Elev= 30
  4213.3  388.41  4330.8  383.28  4352.6  383.81  4434.0  382.11  4455.8  383.74
  4493.7  384.35  4499.4  385.67  4515.5  385.31  4559.1  387.26  4580.9  389.52
  4624.5  391.73  4689.9  392.09  4787.5  385.83  4860.9  376.95  4910.9  369.59
  4934.4  366.41  4952.8  365.58  4953.3  364.78  4959.1  364.78  4959.6  365.58
  4963.6  366.43  5077.2  365.73  5108.1  366.09  5149.8  369.59  5168.2  371.36
  5258.2  385.57  5298.2  390.67  5348.2  393.93  5408.2  399.98  5452.9  401.51
#Mann=4,-1,0
  4213.3    0.05       0  4952.8   0.035       0  4959.6    0.05       0
  5077.2    0.12       0
Bank Sta=4910.9,5149.8
Exp/Cntr=0.3,0.1

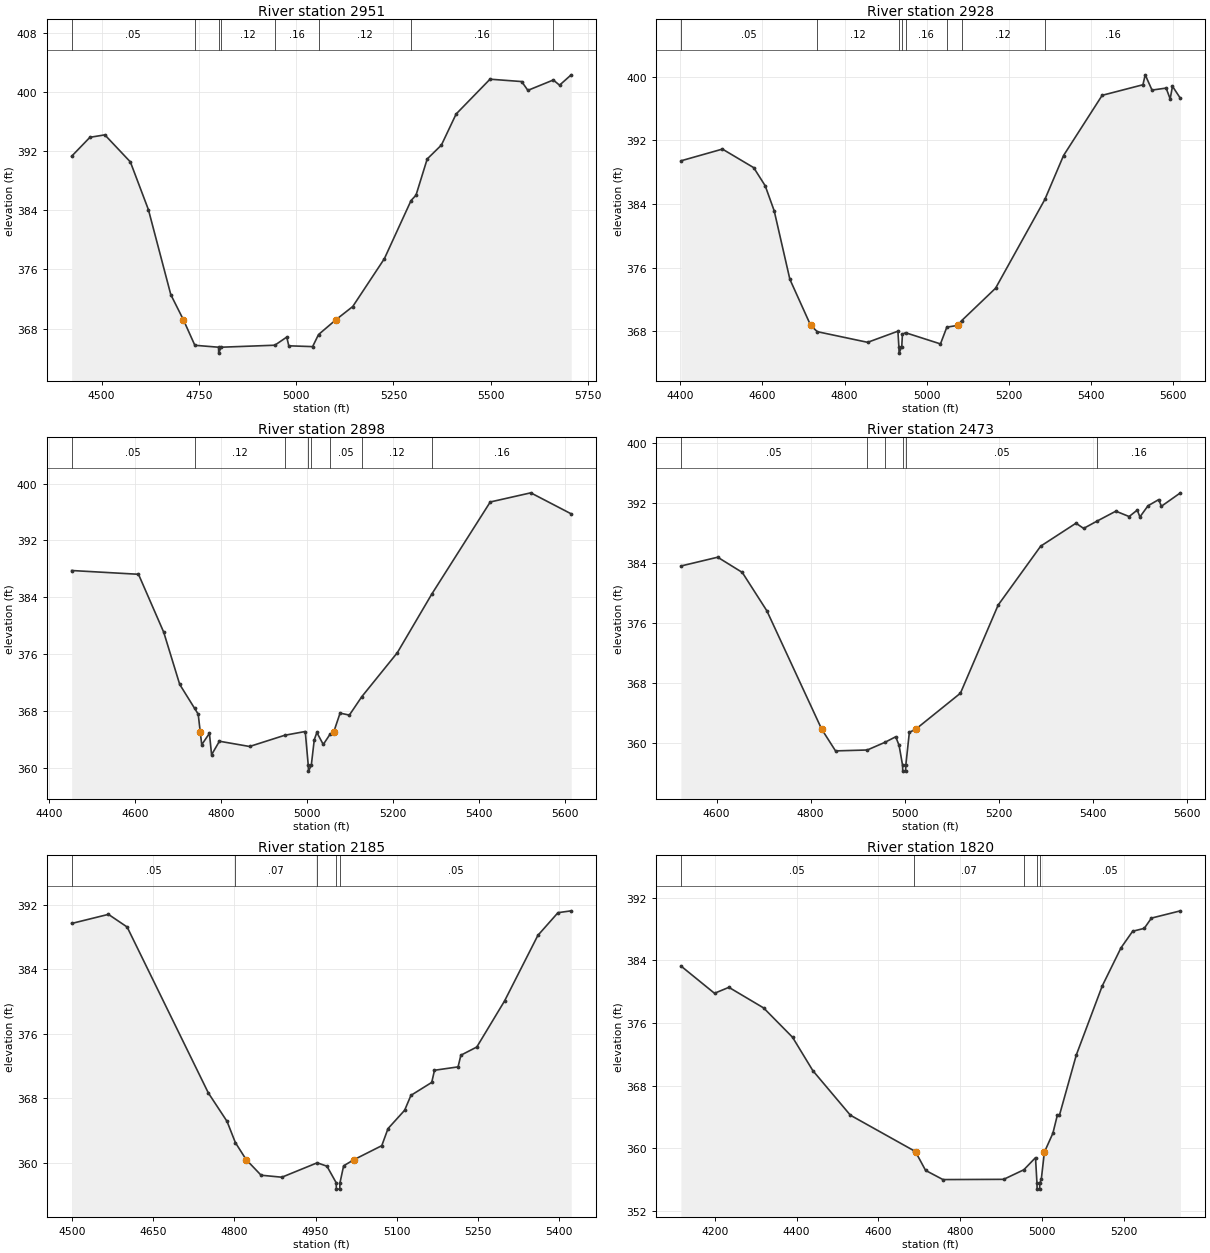
Type RM Length L Ch R = 1,2951,23,23,23
BEGIN DESCRIPTION:
Mapping XS d50e9a6a
END DESCRIPTION:
XS GIS Cut Line= 5
      2900851.24      6951308.39      2901212.39      6951238.94
      2901326.97      6951207.69      2901479.75      6951166.02
      2902038.82      6950856.97
#Sta/Elev= 30
  4423.2  391.30  4470.2  393.86  4508.5  394.19  4574.1  390.53  4620.5  384.07
  4678.0  372.58  4710.3  369.19  4739.8  365.73  4800.6  365.47  4801.1  364.67
  4807.4  365.47  4945.3  365.74  4976.0  366.84  4981.2  365.66  5042.4  365.55
  5057.6  367.18  5102.4  369.19  5145.5  370.97  5226.8  377.44  5295.4  385.31
  5308.1  386.03  5336.9  390.93  5373.4  392.81  5411.2  397.01  5498.3  401.72
  5579.6  401.40  5595.6  400.21  5660.9  401.61  5677.0  400.91  5706.9  402.31
#Mann=8,-1,0
  4423.2    0.05       0  4739.8    0.12       0  4800.6    0.07       0
  4807.4    0.12       0  4945.3    0.16       0  5057.6    0.12       0
  5295.4    0.16       0  5660.9    0.05       0
Bank Sta=4710.3,5102.4
Exp/Cntr=0.3,0.1

Type RM Length L Ch R = 1,2928,30,30,30
BEGIN DESCRIPTION:
Mapping XS ad1bbd06
END DESCRIPTION:
XS GIS Cut Line= 6
      2900868.65      6951426.44      2901174.20      6951263.25
      2901278.36      6951263.25      2901358.22      6951214.63
      2901472.81      6951197.27      2901965.83      6950940.35
#Sta/Elev= 30
  4401.7  389.43  4502.8  390.91  4579.0  388.57  4606.9  386.29  4628.8  383.14
  4667.0  374.51  4717.6  368.71  4733.8  367.92  4856.3  366.58  4929.9  367.98
  4932.3  366.02  4932.8  365.22  4939.3  366.02  4940.9  367.60  4948.5  367.79
  5033.5  366.38  5049.0  368.49  5075.3  368.71  5085.1  369.31  5167.6  373.39
  5287.6  384.57  5333.1  390.10  5427.1  397.68  5526.3  399.01  5531.9  400.26
  5548.4  398.34  5582.8  398.59  5592.6  397.22  5598.2  398.82  5617.6  397.29
#Mann=8,-1,0
  4401.7    0.05       0  4733.8    0.12       0  4932.3    0.07       0
  4939.3    0.12       0  4948.5    0.16       0  5049.0    0.05       0
  5085.1    0.12       0  5287.6    0.16       0
Bank Sta=4717.6,5075.3
Exp/Cntr=0.3,0.1

Type RM Length L Ch R = 1,2898,425,425,425
BEGIN DESCRIPTION:
Mapping XS a05afef5
END DESCRIPTION:
XS GIS Cut Line= 6
      2900913.74      6951447.30      2901181.14      6951291.02
      2901309.61      6951280.61      2901368.64      6951249.36
      2901458.92      6951221.58      2901958.91      6950964.64
#Sta/Elev= 30
  4452.5  387.76  4608.0  387.23  4666.7  379.07  4703.9  371.72  4738.7  368.33
  4746.9  367.53  4751.6  365.05  4755.1  363.23  4773.0  364.83  4778.0  361.81
  4796.2  363.72  4866.4  362.98  4948.2  364.56  4995.9  365.09  5002.9  360.31
  5003.4  359.51  5009.9  360.31  5016.9  363.94  5022.9  364.95  5037.8  363.26
  5053.4  364.69  5062.3  365.05  5076.9  367.68  5098.5  367.40  5127.5  370.00
  5210.0  376.18  5289.9  384.41  5426.2  397.41  5520.5  398.70  5614.5  395.74
#Mann=8,-1,0
  4452.5    0.05       0  4738.7    0.12       0  4948.2    0.16       0
  5002.9    0.07       0  5009.9    0.16       0  5053.4    0.05       0
  5127.5    0.12       0  5289.9    0.16       0
Bank Sta=4751.6,5062.3
Exp/Cntr=0.3,0.1

Type RM Length L Ch R = 1,2473,288,288,288
BEGIN DESCRIPTION:
Mapping XS eac2e1b1
END DESCRIPTION:
XS GIS Cut Line= 3
      2901189.08      6951771.60      2901668.29      6951563.25
      2901897.46      6951073.67
#Sta/Elev= 30
  4523.9  383.58  4602.2  384.75  4654.5  382.73  4706.9  377.62  4823.6  361.88
  4853.0  359.00  4920.6  359.12  4957.8  360.13  4981.1  360.88  4988.3  359.72
  4995.6  357.11  4996.1  356.31  5002.1  356.31  5002.6  357.11  5010.1  361.47
  5023.6  361.88  5118.8  366.67  5199.1  378.39  5289.6  386.22  5364.7  389.27
  5381.0  388.58  5409.8  389.56  5449.5  390.87  5477.8  390.16  5495.2  391.02
  5500.7  390.10  5518.0  391.59  5540.8  392.41  5546.4  391.52  5587.0  393.31
#Mann=6,-1,0
  4523.9    0.05       0  4920.6    0.07       0  4957.8    0.05       0
  4995.6    0.03       0  5002.6    0.05       0  5409.8    0.16       0
Bank Sta=4823.6,5023.6
Exp/Cntr=0.3,0.1

Type RM Length L Ch R = 1,2185,365,365,365
BEGIN DESCRIPTION:
TWOMILE BRANCH 3.0
END DESCRIPTION:
XS GIS Cut Line= 3
      2901274.99      6951925.00      2901725.00      6951825.00
      2902175.04      6951724.99
#Sta/Elev= 30
  4499.9  389.71  4567.8  390.84  4602.3  389.27  4752.2  368.65  4786.7  365.12
  4802.1  362.48  4822.0  360.37  4849.5  358.43  4887.9  358.18  4953.1  359.97
  4971.1  359.55  4988.1  357.50  4988.6  356.70  4994.7  356.70  4995.2  357.50
  5001.9  359.60  5021.3  360.37  5072.3  362.10  5083.8  364.22  5114.5  366.50
  5126.1  368.35  5164.5  369.96  5169.6  371.47  5213.1  371.89  5218.3  373.34
  5247.7  374.36  5298.9  380.08  5360.4  388.23  5397.5  391.05  5421.9  391.28
#Mann=5,-1,0
  4499.9    0.05       0  4802.1    0.07       0  4953.1    0.05       0
  4988.1    0.03       0  4995.2    0.05       0
Bank Sta=4822,5021.3
Exp/Cntr=0.3,0.1

Type RM Length L Ch R = 1,1820,337,337,337
BEGIN DESCRIPTION:
Mapping XS 975538e9
END DESCRIPTION:
XS GIS Cut Line= 3
      2901420.72      6952646.93      2902083.92      6952004.56
      2902208.93      6951733.71
#Sta/Elev= 30
  4116.9  383.27  4199.1  379.78  4234.3  380.54  4319.2  377.91  4390.0  374.16
  4439.6  369.90  4531.4  364.21  4686.0  359.70  4691.2  359.49  4715.3  357.16
  4757.8  355.99  4906.2  356.02  4955.5  357.24  4984.1  358.79  4987.6  355.57
  4988.1  354.77  4994.2  354.77  4994.7  355.57  4998.3  356.05  5005.8  359.49
  5026.6  361.91  5037.5  364.22  5042.7  364.22  5083.9  371.91  5147.2  380.71
  5193.1  385.58  5221.6  387.70  5250.0  388.07  5267.5  389.38  5338.5  390.31
#Mann=5,-1,0
  4116.9    0.05       0  4686.0    0.07       0  4955.5    0.05       0
  4987.6    0.03       0  4994.7    0.05       0
Bank Sta=4691.2,5005.8
Exp/Cntr=0.3,0.1

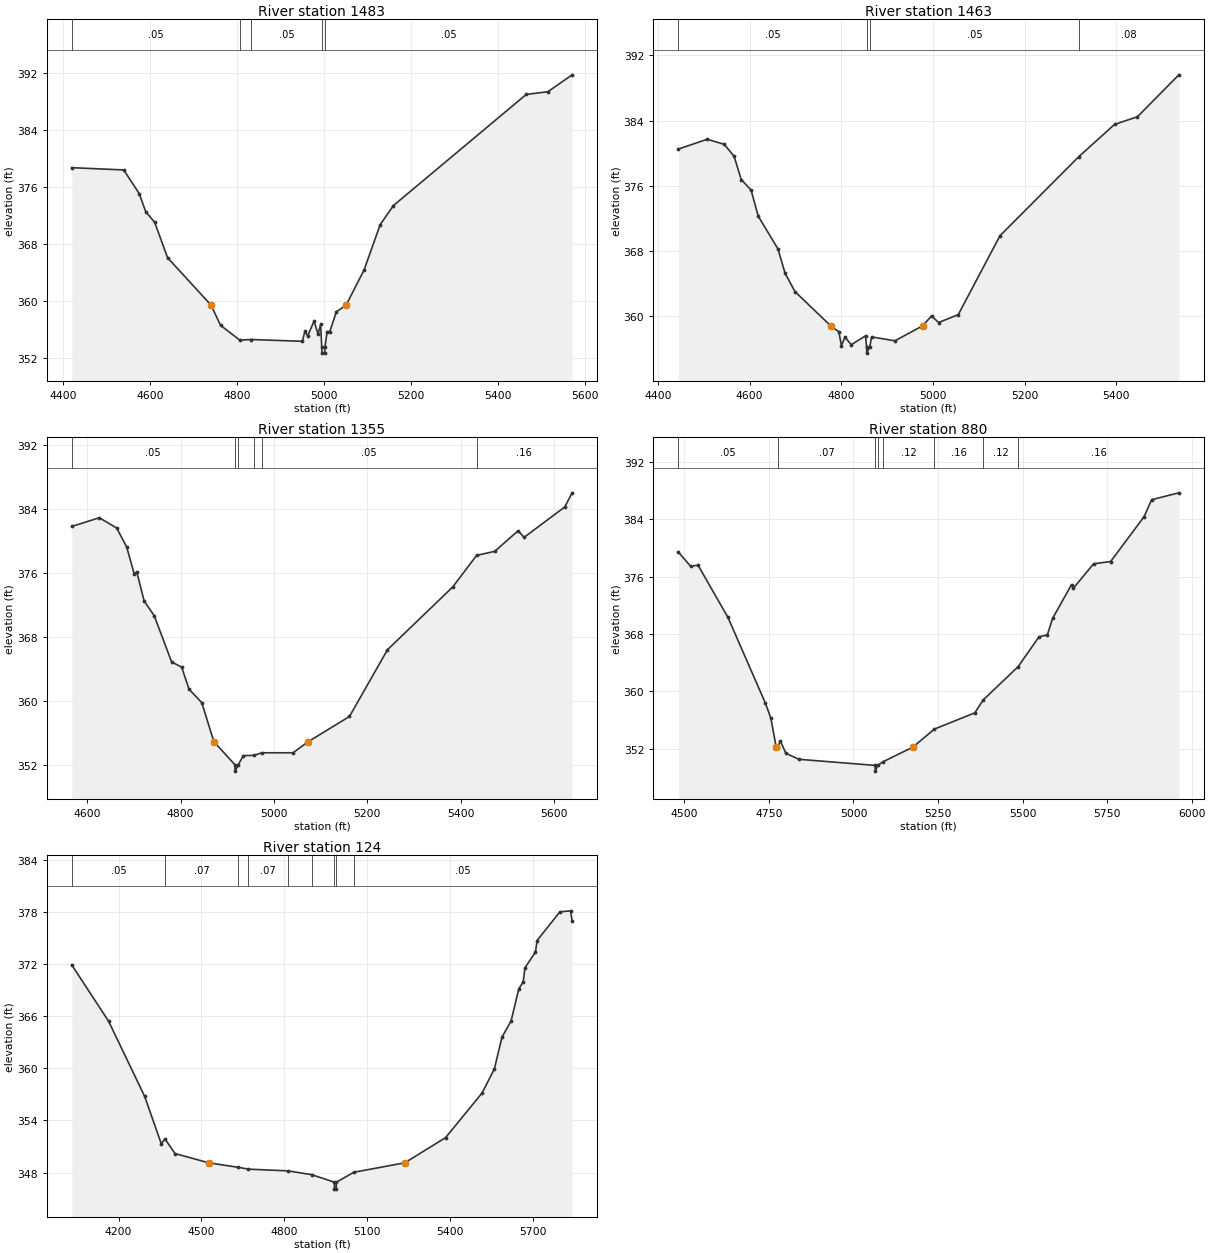
Type RM Length L Ch R = 1,1483,20,20,20
BEGIN DESCRIPTION:
Mapping XS afe12a3f
END DESCRIPTION:
XS GIS Cut Line= 4
      2902010.98      6952667.79      2902271.42      6952303.18
      2902375.59      6952146.93      2902292.26      6951640.00
#Sta/Elev= 30
  4419.9  378.69  4539.4  378.37  4575.0  375.06  4589.8  372.54  4610.6  371.02
  4640.1  366.07  4740.1  359.41  4761.8  356.58  4806.3  354.50  4831.7  354.59
  4949.7  354.34  4955.7  355.73  4961.9  355.10  4976.8  357.18  4985.8  355.34
  4991.8  356.72  4994.4  353.48  4994.9  352.68  5001.0  352.68  5001.6  353.48
  5006.8  355.70  5012.8  355.70  5027.9  358.47  5050.3  359.41  5091.7  364.36
  5128.7  370.71  5159.1  373.38  5464.1  388.96  5513.8  389.34  5569.5  391.71
#Mann=5,-1,0
  4419.9    0.05       0  4806.3    0.07       0  4831.7    0.05       0
  4994.4    0.03       0  5001.6    0.05       0
Bank Sta=4740.1,5050.3
Exp/Cntr=0.3,0.1

Type RM Length L Ch R = 1,1463,108,108,108
BEGIN DESCRIPTION:
Mapping XS 0798cd7d
END DESCRIPTION:
XS GIS Cut Line= 4
      2902080.46      6952678.15      2902254.06      6952383.04
      2902403.36      6952133.04      2902396.42      6951674.67
#Sta/Elev= 30
  4444.6  380.51  4507.5  381.71  4544.6  381.09  4566.1  379.63  4581.7  376.77
  4603.2  375.48  4618.8  372.28  4661.8  368.27  4677.4  365.28  4698.9  363.04
  4777.0  358.83  4794.6  358.12  4800.4  356.40  4808.0  357.46  4821.8  356.52
  4852.9  357.61  4855.2  356.29  4855.7  355.49  4862.4  356.29  4866.2  357.48
  4917.1  357.00  4977.3  358.83  4996.9  360.05  5012.5  359.24  5055.3  360.21
  5146.2  369.87  5318.6  379.59  5396.3  383.53  5446.3  384.47  5536.6  389.61
#Mann=4,-1,0
  4444.6    0.05       0  4855.2    0.03       0  4862.4    0.05       0
  5318.6    0.08       0
Bank Sta=4777,4977.3
Exp/Cntr=0.3,0.1

Type RM Length L Ch R = 1,1355,475,475,475
BEGIN DESCRIPTION:
Mapping XS d05f9182
END DESCRIPTION:
XS GIS Cut Line= 4
      2902122.13      6952664.26      2902302.67      6952351.79
      2902451.97      6952150.40      2902462.38      6951689.29
#Sta/Elev= 30
  4566.4  381.81  4625.6  382.90  4662.9  381.62  4684.4  379.23  4700.2  375.94
  4706.0  376.11  4721.8  372.50  4743.3  370.68  4780.6  364.91  4802.2  364.25
  4817.9  361.51  4845.2  359.83  4871.2  354.96  4916.3  352.08  4916.8  351.28
  4923.5  352.08  4934.5  353.22  4956.9  353.24  4974.0  353.57  5040.9  353.57
  5073.6  354.96  5161.9  358.10  5243.4  366.43  5383.4  374.27  5434.4  378.20
  5473.4  378.71  5523.5  381.28  5536.2  380.45  5623.5  384.25  5639.2  386.01
#Mann=6,-1,0
  4566.4    0.05       0  4916.3    0.03       0  4923.5    0.05       0
  4956.9    0.07       0  4974.0    0.05       0  5434.4    0.16       0
Bank Sta=4871.2,5073.6
Exp/Cntr=0.3,0.1

Type RM Length L Ch R = 1,880,756,756,756
BEGIN DESCRIPTION:
Mapping XS 07c98a26
END DESCRIPTION:
XS GIS Cut Line= 3
      2902278.40      6952686.84      2902788.78      6952421.23
      2902913.78      6951525.36
#Sta/Elev= 30
  4482.3  379.42  4518.3  377.46  4540.4  377.59  4628.9  370.31  4739.4  358.37
  4755.9  356.22  4771.5  352.21  4775.6  352.11  4783.6  353.09  4800.1  351.36
  4838.6  350.52  5064.1  349.67  5064.7  348.87  5071.3  349.67  5088.0  350.19
  5175.4  352.21  5239.6  354.74  5358.9  357.00  5383.5  358.79  5486.9  363.44
  5548.6  367.60  5573.4  367.88  5589.0  370.18  5644.9  374.89  5650.0  374.36
  5710.1  377.79  5760.6  378.11  5859.5  384.37  5881.8  386.73  5962.2  387.69
#Mann=8,-1,0
  4482.3    0.05       0  4775.6    0.07       0  5064.1    0.07       0
  5071.3    0.07       0  5088.0    0.12       0  5239.6    0.16       0
  5383.5    0.12       0  5486.9    0.16       0
Bank Sta=4771.5,5175.4
Exp/Cntr=0.3,0.1

Type RM Length L Ch R = 1,124,0,0,0
BEGIN DESCRIPTION:
TWOMILE BRANCH 1.0
END DESCRIPTION:
XS GIS Cut Line= 3
      2902340.87      6952749.36      2903310.56      6952745.73
      2903700.00      6952000.00
#Sta/Elev= 30
  4030.3  371.90  4164.4  365.38  4294.4  356.76  4354.4  351.32  4368.1  351.86
  4404.4  350.18  4526.1  349.12  4633.0  348.60  4669.2  348.39  4813.4  348.19
  4899.4  347.75  4980.8  346.89  4981.3  346.09  4987.5  346.09  4988.1  346.89
  5051.5  348.03  5235.9  349.12  5383.2  352.01  5515.7  357.16  5559.9  359.92
  5587.6  363.58  5620.5  365.44  5648.2  369.12  5664.6  369.97  5670.3  371.53
  5708.8  373.38  5714.4  374.69  5797.1  377.99  5835.7  378.11  5841.3  376.98
#Mann=9,-1,0
  4030.3    0.05       0  4368.1    0.07       0  4633.0    0.12       0
  4669.2    0.07       0  4813.4    0.12       0  4899.4    0.07       0
  4980.8    0.07       0  4988.1    0.07       0  5051.5    0.05       0
Bank Sta=4526.1,5235.9
Exp/Cntr=0.3,0.1

Chan Stop Cuts=-1