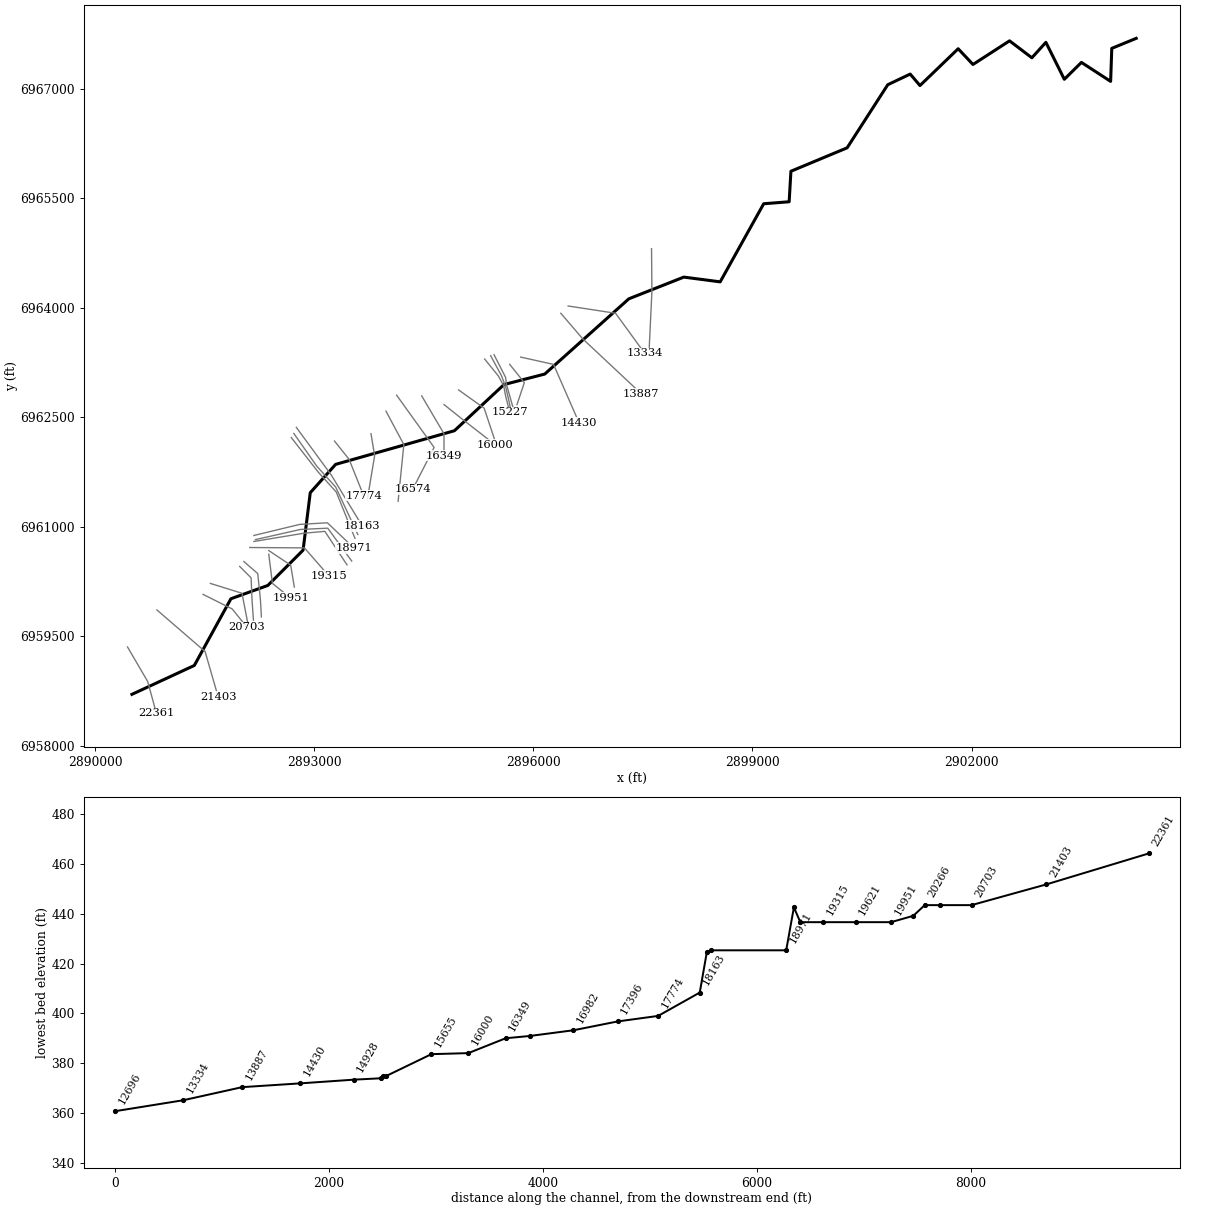
--- UNT 001 IN DRY CR WATERSHED.prj (project) ---

Proj Title=UNT 001 IN DRY CR WATERSHED Base Level Engineering
Current Plan=p01
Default Exp/Contr=0.3,0.1
English Units
Geom File=g01
Flow File=f01
Plan File=p01
Y Axis Title=Elevation
X Axis Title(PF)=Main Channel Distance
X Axis Title(XS)=Station
BEGIN DESCRIPTION:
UNT 001 IN DRY CR WATERSHED
END DESCRIPTION:
DSS Export Rating Curves= 0
DSS Export Rating Curve Sorted= 0
DSS Export Volume Flow Curves= 0
DXF OffsetX= 0
DXF OffsetY= 0
DXF ScaleX= 1
DXF ScaleY= 10

--- UNT 001 IN DRY CR WATERSHED.p01 (plan) ---

Plan Title=Multiple Run
Short Identifier=Multiple
Geom File=g01
Flow File=f01
Subcritical Flow
K Sum by GR= 0
Std Step Tol= 0.01
Critical Tol= 0.01
Num of Std Step Trials= 20
Max Error Tol= 0.3
Flow Tol Ratio= 0.001
Split Flow NTrial= 30
Split Flow Tol= 0.02
Split Flow Ratio= 0.02
Log Output Level= 0
Friction Slope Method= 1
Unsteady Friction Slope Method= 2
Unsteady Bridges Friction Slope Method= 1
Parabolic Critical Depth
Global Vel Dist=  1 , 1 , 1
Global Log Level= 0
CheckData=True
Encroach Param= -1, 0, 0, 0
BEGIN DESCRIPTION:
Multiple Run
END DESCRIPTION:

--- UNT 001 IN DRY CR WATERSHED.f01 (steady flow) ---

Flow Title=Multiple
Number of Profiles=7
Profile Names=10-year,25-year,50-year,1pct_min,100-year,1pct_plu,500-year
River Rch & RM= UNT 001 IN DRY C,Reach-1,22361
     399     527     630     376     749    1495    1061
River Rch & RM= UNT 001 IN DRY C,Reach-1,17774
     788    1085    1332     814    1624    3240    2416
River Rch & RM= UNT 001 IN DRY C,Reach-1,11964
    1027    1432    1773    1091    2176    4342    3286
River Rch & RM= UNT 001 IN DRY C,Reach-1,7682
    1370    1938    2425    1505    3003    5992    4620
River Rch & RM= UNT 001 IN DRY C,Reach-1,6996
    1530    2169    2718    1688    3368    6720    5186
Boundary for River Rch & Prof#=UNT 001 IN DRY C,Reach-1,1
Up Type=0
Dn Type=3
Dn Slope=0.005
Boundary for River Rch & Prof#=UNT 001 IN DRY C,Reach-1,2
Up Type=0
Dn Type=3
Dn Slope=0.005
Boundary for River Rch & Prof#=UNT 001 IN DRY C,Reach-1,3
Up Type=0
Dn Type=3
Dn Slope=0.005
Boundary for River Rch & Prof#=UNT 001 IN DRY C,Reach-1,4
Up Type=0
Dn Type=3
Dn Slope=0.005
Boundary for River Rch & Prof#=UNT 001 IN DRY C,Reach-1,5
Up Type=0
Dn Type=3
Dn Slope=0.005
Boundary for River Rch & Prof#=UNT 001 IN DRY C,Reach-1,6
Up Type=0
Dn Type=3
Dn Slope=0.005
Boundary for River Rch & Prof#=UNT 001 IN DRY C,Reach-1,7
Up Type=0
Dn Type=3
Dn Slope=0.005

--- UNT 001 IN DRY CR WATERSHED.g01 (geometry) ---

Geom Title=Existing Conditions
Program Version=5.07

River Reach=UNT 001 IN DRY C,Reach-1
Reach XY= 30
      2890500.59      6958705.71      2891355.33      6959101.41
      2891856.42      6960015.02      2892362.55      6960197.53
      2892844.69      6960680.28       2892943.1      6961467.43
      2893290.81      6961855.61      2894917.86      6962316.51
       2895596.5      6962948.51      2896154.99      6963092.62
      2897306.44      6964123.09      2898059.42      6964420.45
      2898557.64      6964355.54      2899153.57      6965425.13
      2899502.24      6965452.36      2899526.41      6965870.28
      2900296.42       6966191.2      2900852.77      6967055.29
      2901160.33      6967201.32      2901293.96      6967044.01
      2901817.12      6967548.06      2902019.98      6967332.64
      2902520.77      6967656.39      2902826.54      6967424.31
      2903018.56      6967635.97      2903270.99       6967129.8
      2903505.26      6967361.03       2903905.3      6967101.08
      2903920.98      6967553.35      2904255.59      6967690.71

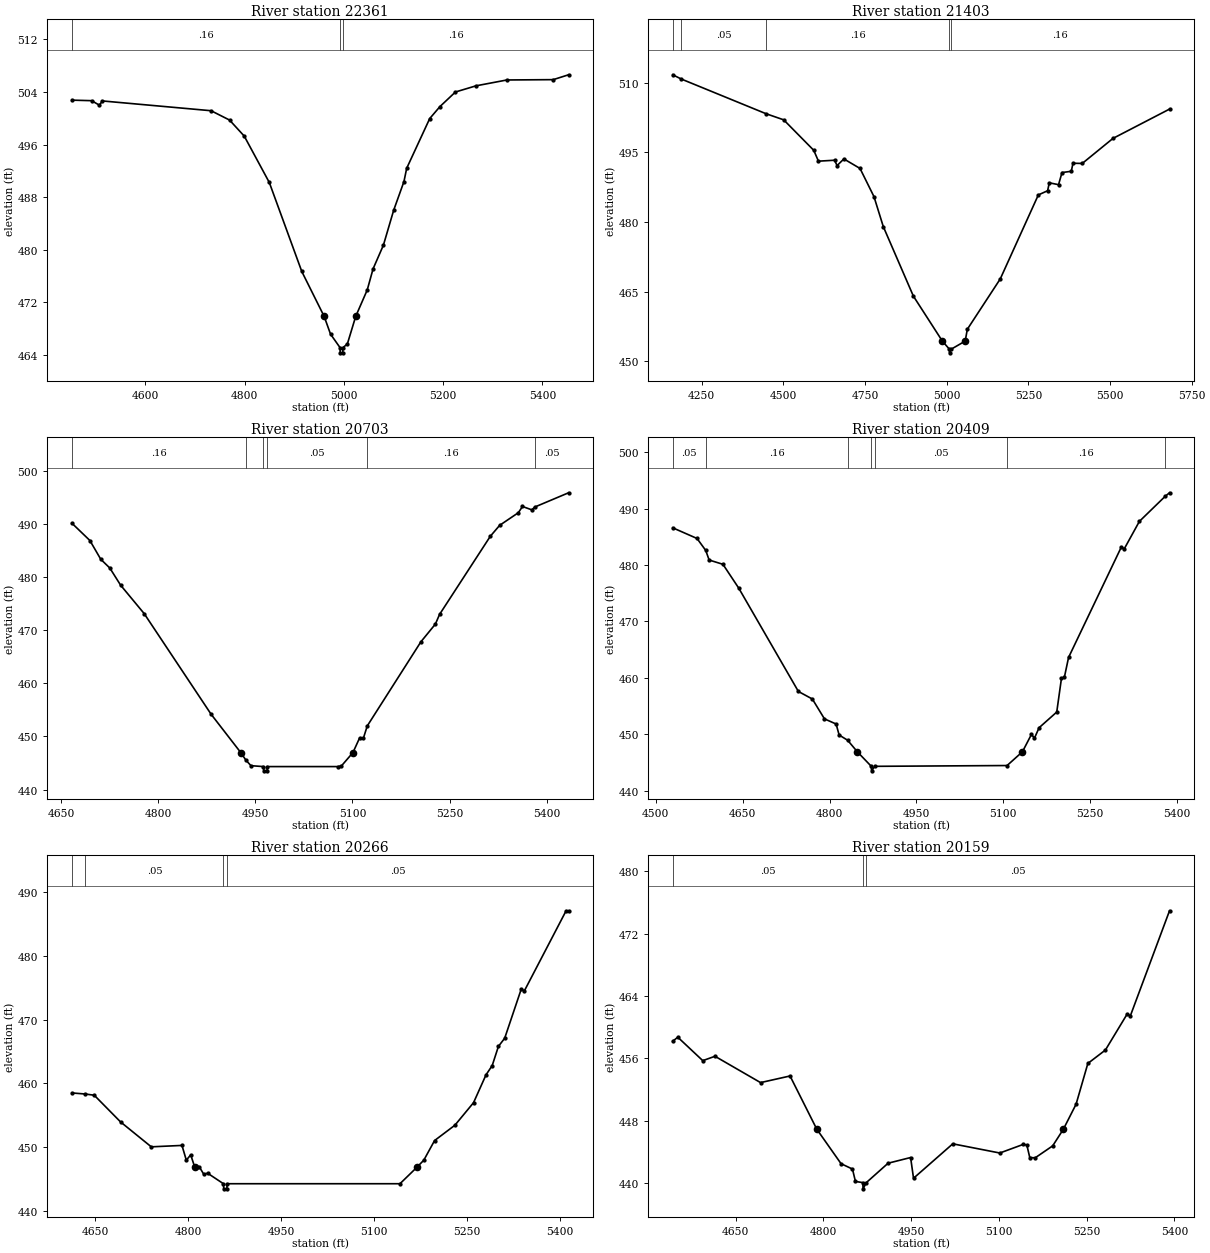
Type RM Length L Ch R = 1 ,22361   ,958,958,958
BEGIN DESCRIPTION:
UNT 001 IN DRY CR WATERSHED 40.0
END DESCRIPTION:
XS GIS Cut Line= 3
      2890440.09      6959354.89       2890716.6      6958881.76
      2890835.92      6958445.17
#Sta/Elev= 30
    4452  502.77  4491.9  502.69  4507.6     502  4513.4  502.65  4732.5  501.16
  4769.7  499.74  4799.3   497.3  4849.8  490.24  4915.2   476.7  4960.3  469.86
  4973.1  467.17  4992.2  465.12  4992.7  464.32  4997.7  464.32  4998.2  465.12
    5007  465.67  5023.8  469.86  5047.1   473.9  5058.8   477.1  5079.6   480.7
  5100.3  486.02    5121  490.38  5126.5   492.4  5172.9  499.97  5193.6   501.8
  5224.7  504.01  5266.2  504.95  5328.4  505.84  5421.7  505.89  5452.6  506.63
#Mann= 3 ,-1 , 0
    4452     .16       0  4992.2     .07       0  4998.2     .16       0
Bank Sta=4960.3,5023.8
XS Rating Curve= 0 ,0
Exp/Cntr=0.3,0.1

Type RM Length L Ch R = 1 ,21403   ,700,700,700
BEGIN DESCRIPTION:
Mapping XS 14fe0820
END DESCRIPTION:
XS GIS Cut Line= 3
      2890842.87      6959861.84      2891502.59       6959292.4
      2891682.77      6958668.69
#Sta/Elev= 30
  4161.5  511.73  4187.4  510.82  4447.3  503.34  4501.1  502.03  4593.2  495.46
  4607.5  493.13  4656.9  493.33  4664.5  492.18  4685.4  493.61  4734.8  491.56
  4777.5  485.49    4806  479.04  4898.2  464.06  4986.8  454.39  5008.2  452.66
  5008.7  451.86  5014.2  452.66  5056.8  454.39  5063.2  456.93  5164.1  467.78
  5280.6  485.86    5309  486.76  5314.2  488.47  5342.5  488.07  5353.1  490.68
  5381.5  490.95  5386.7  492.68  5415.1  492.64  5509.1  498.03  5682.2  504.34
#Mann= 5 ,-1 , 0
  4161.5     .16       0  4187.4     .05       0  4447.3     .16       0
  5008.2     .07       0  5014.2     .16       0
Bank Sta=4986.8,5056.8
XS Rating Curve= 0 ,0
Exp/Cntr=0.3,0.1

Type RM Length L Ch R = 1 ,20703   ,294,294,294
BEGIN DESCRIPTION:
UNT 001 IN DRY CR WATERSHED 39.0
END DESCRIPTION:
XS GIS Cut Line= 3
      2891475.03      6960074.98        2891875.        6959875.
      2892074.98      6959625.02
#Sta/Elev= 30
  4666.5  490.13  4694.4  486.86  4711.2  483.33  4725.2  481.68  4741.9  478.45
  4778.3   473.1  4881.7  454.16  4927.5  446.95  4935.4  445.53  4943.2  444.49
  4962.5  444.32    4963  443.52    4968  443.52  4968.5  444.32  5077.3  444.32
  5082.9  444.44  5100.7  446.95  5110.9  449.68  5116.9  449.68  5122.9  451.98
  5205.7   467.8  5228.1  471.14  5234.5  472.95    5313  487.67  5327.4  489.72
  5356.2  492.09  5362.6  493.26    5377  492.63  5381.8  493.17  5433.8  495.84
#Mann= 6 ,-1 , 0
  4666.5     .16       0  4935.4     .05       0  4962.5    .033       0
  4968.5     .05       0  5122.9     .16       0  5381.8     .05       0
Bank Sta=4927.5,5100.7
XS Rating Curve= 0 ,0
Exp/Cntr=0.3,0.1

Type RM Length L Ch R = 1 ,20409   ,143,143,143
BEGIN DESCRIPTION:
UNT 001 IN DRY CR WATERSHED 38.0
END DESCRIPTION:
XS GIS Cut Line= 3
        2891575.        6960225.      2892007.94      6960090.38
      2892085.06        6959694.
#Sta/Elev= 30
  4529.5   486.6  4571.4  484.71  4586.4  482.59  4592.3  480.89  4616.1  480.13
  4643.4   475.9  4746.3  457.59  4770.4  456.25  4791.3  452.73  4811.4  451.82
  4816.6  449.87  4831.3  448.94    4848   446.9  4872.1  444.32  4872.6  443.52
  4878.1  444.32  5106.4  444.46  5132.9   446.9  5148.5  449.99  5153.6   449.3
  5161.6  451.16  5192.1  453.94  5200.2  459.89  5205.3  460.12  5212.5  463.62
  5303.5  483.18  5308.6  482.87  5334.7  487.74  5379.5  492.21  5386.7  492.81
#Mann= 7 ,-1 , 0
  4529.5     .05       0  4586.4     .16       0  4831.3     .05       0
  4872.1    .033       0  4878.1     .05       0  5106.4     .16       0
  5379.5     .05       0
Bank Sta=4848,5132.9
XS Rating Curve= 0 ,0
Exp/Cntr=0.3,0.1

Type RM Length L Ch R = 1 ,20266   ,107,107,107
BEGIN DESCRIPTION:
Mapping XS 3ee2d1f3
END DESCRIPTION:
XS GIS Cut Line= 4
      2891976.58      6960457.83      2892132.81       6960301.6
      2892145.83      6959993.44      2892165.37      6959722.12
#Sta/Elev= 30
  4612.7  458.52  4634.5  458.35  4648.9  458.16  4691.4  453.98  4740.9  450.09
  4790.4  450.31  4797.4  448.01  4804.5  448.83  4811.1  446.89  4818.6  446.92
  4825.7  445.78  4831.7  445.97  4857.3  444.32  4857.8  443.52  4862.8  443.52
  4863.3  444.32  5142.1  444.32  5169.4  446.89  5180.6  448.01  5197.9  451.07
  5230.7  453.47  5260.8     457  5280.9  461.35  5290.9   462.8  5300.9   465.8
    5311  467.07  5337.7  474.75  5342.7  474.47  5410.1  487.01  5414.1  487.01
#Mann= 4 ,-1 , 0
  4612.7     .16       0  4634.5     .05       0  4857.3    .033       0
  4863.3     .05       0
Bank Sta=4811.1,5169.4
XS Rating Curve= 0 ,0
Exp/Cntr=0.3,0.1

Type RM Length L Ch R = 1 ,20159   ,208,208,208
BEGIN DESCRIPTION:
Mapping XS b50c5b8a
END DESCRIPTION:
XS GIS Cut Line= 4
      2892032.97      6960525.13      2892223.96      6960360.19
      2892260.85      6959999.95      2892273.87      6959765.58
#Sta/Elev= 30
  4542.6  458.18  4551.2   458.7  4593.9  455.69  4614.8  456.25  4692.7  452.87
  4743.1  453.72  4788.8  446.89  4830.3  442.46  4849.8  441.77  4854.9  440.18
  4867.5  440.03    4868  439.23  4873.5  440.03  4910.7  442.52  4949.2  443.25
  4954.2  440.59  5021.3  445.01  5101.7  443.83  5141.9  444.94  5147.9  444.86
  5152.9  443.25  5162.1  443.21  5192.1  444.75  5210.4  446.89  5232.1   450.1
  5252.2  455.33  5282.2  457.05  5319.7  461.71  5324.7  461.41  5391.8  474.93
#Mann= 3 ,-1 , 0
  4542.6     .05       0  4867.5    .033       0  4873.5     .05       0
Bank Sta=4788.8,5210.4
XS Rating Curve= 0 ,0
Exp/Cntr=0.3,0.1

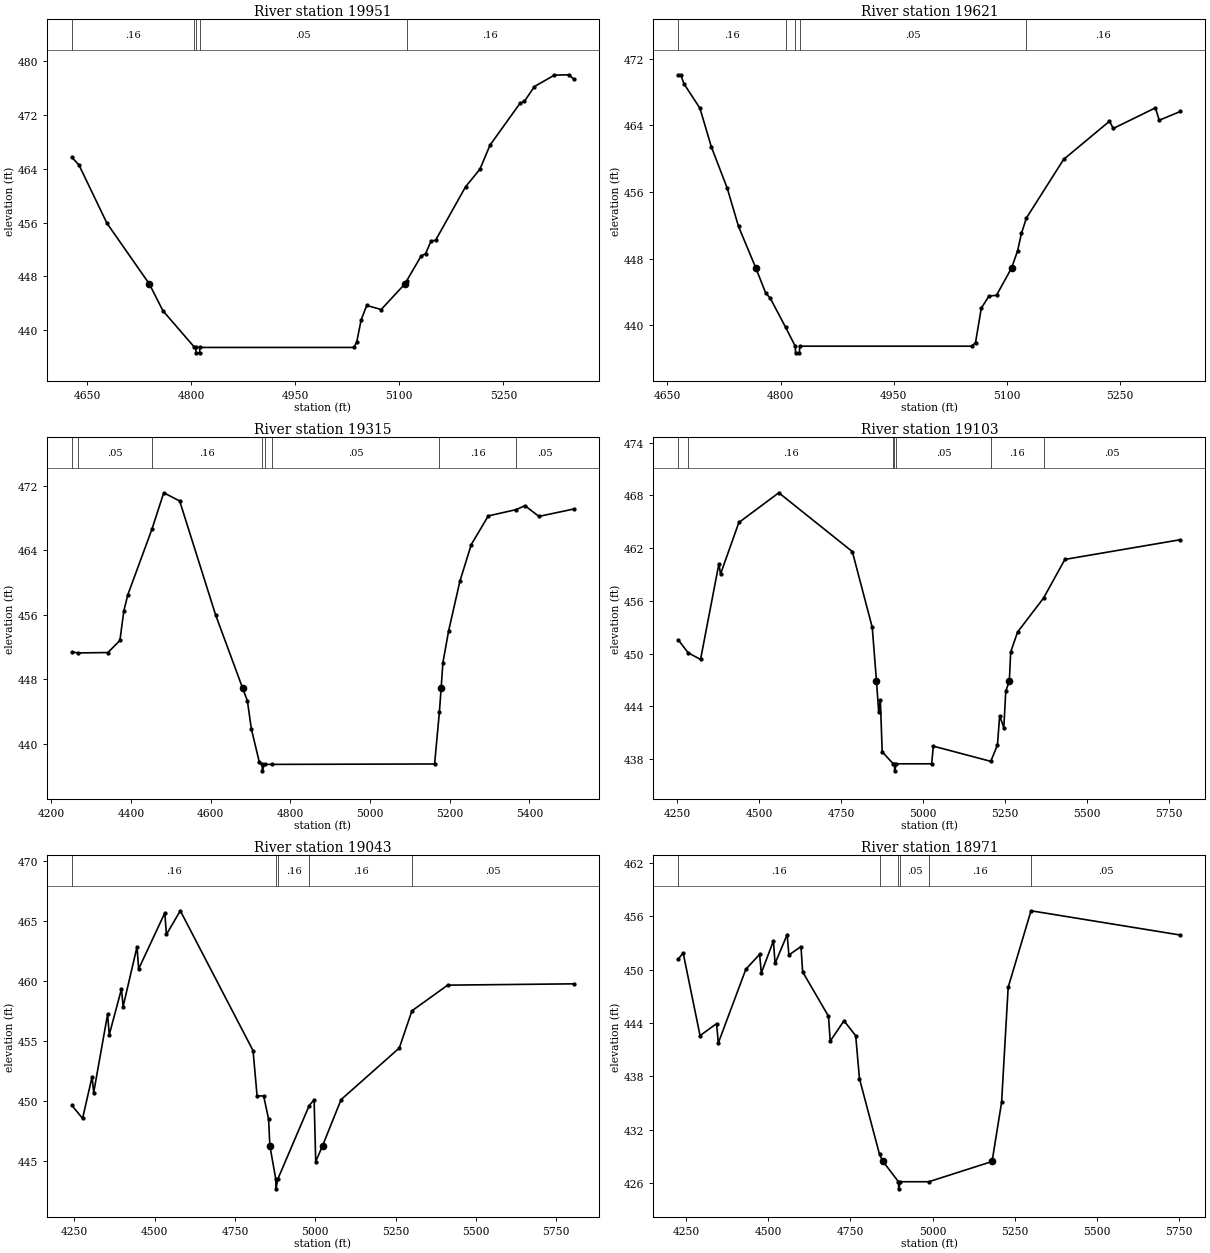
Type RM Length L Ch R = 1 ,19951   ,330,330,330
BEGIN DESCRIPTION:
UNT 001 IN DRY CR WATERSHED 37.0
END DESCRIPTION:
XS GIS Cut Line= 3
      2892374.99      6960625.04        2892425.        6960225.
      2892674.99      6960025.01
#Sta/Elev= 30
  4628.3  465.66  4638.4  464.53  4678.7   455.9  4739.8  446.89  4759.4  442.91
  4804.5  437.54  4806.7  437.47  4807.2  436.67  4812.2  436.67  4812.7  437.47
  5034.7  437.47  5038.7  438.28  5045.1  441.57  5053.1   443.7  5073.9  443.09
  5108.1  446.89  5110.7  447.36  5131.5  451.03  5137.9  451.38  5145.9  453.27
  5152.3  453.36  5195.5  461.29  5216.3  463.92  5230.8  467.48    5274  473.68
  5280.4  473.98  5294.8  476.17  5323.6  477.86  5344.4  477.91  5351.6  477.24
#Mann= 5 ,-1 , 0
  4628.3     .16       0  4804.5     .05       0  4806.7    .033       0
  4812.7     .05       0  5110.7     .16       0
Bank Sta=4739.8,5108.1
XS Rating Curve= 0 ,0
Exp/Cntr=0.3,0.1

Type RM Length L Ch R = 1 ,19621   ,306,306,306
BEGIN DESCRIPTION:
UNT 001 IN DRY CR WATERSHED 36.0
END DESCRIPTION:
XS GIS Cut Line= 3
      2892375.03      6960674.98        2892675.        6960475.
      2892725.01      6960174.95
#Sta/Elev= 30
  4664.8  470.07  4667.8  470.07  4672.3  468.97  4693.3  466.05  4708.3  461.44
  4729.4  456.46  4744.4  451.85  4767.2  446.89  4780.4  443.85  4786.4  443.24
  4806.8  439.73  4819.5  437.47    4820  436.67    4825  436.67  4825.5  437.47
  5053.2  437.47  5058.3  437.91  5065.9  442.03    5076  443.48  5086.1  443.59
  5106.2  446.89    5114  448.93  5119.1  451.02  5125.7  452.87  5174.9   459.9
  5235.7  464.49  5240.7  463.62  5296.5   466.1  5301.6  464.61  5329.5  465.66
#Mann= 5 ,-1 , 0
  4664.8     .16       0  4806.8     .05       0  4819.5    .033       0
  4825.5     .05       0  5125.7     .16       0
Bank Sta=4767.2,5106.2
XS Rating Curve= 0 ,0
Exp/Cntr=0.3,0.1

Type RM Length L Ch R = 1 ,19315   ,212,212,212
BEGIN DESCRIPTION:
UNT 001 IN DRY CR WATERSHED 35.0
END DESCRIPTION:
XS GIS Cut Line= 3
      2892114.55      6960716.88      2892863.14      6960711.72
      2893199.64      6960326.24
#Sta/Elev= 30
  4251.4  451.41  4266.4  451.29  4341.8  451.34  4371.8  452.84  4381.8  456.53
  4391.8  458.52    4452   466.6  4481.9  471.15  4521.9  470.13  4611.9  456.04
  4680.2  446.89  4691.9  445.36  4701.9  441.87  4721.9  437.75  4728.9  437.47
  4729.4  436.67  4734.9  437.47  4753.6  437.47    5162  437.52  5174.1  443.98
  5178.4  446.89  5182.9  450.09  5197.2  454.02  5225.6  460.19  5254.1  464.73
  5296.8  468.28  5366.7  469.06  5388.9  469.55    5424  468.22  5511.7  469.14
#Mann= 8 ,-1 , 0
  4251.4     .16       0  4266.4     .05       0    4452     .16       0
  4728.9    .033       0  4734.9     .16       0  4753.6     .05       0
  5174.1     .16       0  5366.7     .05       0
Bank Sta=4680.2,5178.4
XS Rating Curve= 0 ,0
Exp/Cntr=0.3,0.1

Type RM Length L Ch R = 1 ,19103   ,60,60,60
BEGIN DESCRIPTION:
Mapping XS 0f14b038
END DESCRIPTION:
XS GIS Cut Line= 4
      2892170.97      6960799.34      2892852.41      6960912.19
      2893143.21      6960938.23      2893446.41       6960479.1
#Sta/Elev= 30
    4253  451.55  4282.7   450.1  4320.6  449.34  4376.6  460.21  4381.6  459.05
  4437.6  464.92  4559.6   468.3  4784.2  461.61    4845  452.99  4857.9  446.89
  4864.7  443.34  4869.7  444.75  4875.4  438.83  4909.1  437.47  4912.9  437.47
  4913.4  436.67  4918.9  437.47  5026.5  437.47  5031.5  439.48    5207  437.75
  5227.4  439.61  5234.1  442.93  5246.8  441.58  5252.8  445.72  5263.7  446.89
  5267.8  450.19  5288.9  452.46  5368.1  456.32  5433.4  460.72  5785.9  462.96
#Mann= 7 ,-1 , 0
    4253     .05       0  4282.7     .16       0  4909.1     .05       0
  4912.9    .035       0  4918.9     .05       0    5207     .16       0
  5368.1     .05       0
Bank Sta=4857.9,5263.7
XS Rating Curve= 0 ,0
Exp/Cntr=0.3,0.1

Type RM Length L Ch R = 1 ,19043   ,72,72,72
BEGIN DESCRIPTION:
Mapping XS d97cd8ca
END DESCRIPTION:
XS GIS Cut Line= 4
      2892192.71      6960825.39      2892809.01      6960964.27
      2893182.27      6960981.63      2893511.08      6960531.69
#Sta/Elev= 30
  4242.2  449.59  4275.3  448.51  4304.8  451.97  4309.9  450.67  4353.2  457.19
  4358.3  455.48  4396.4   459.3  4401.5  457.84  4444.8  462.81  4449.9  460.97
  4531.3  465.64  4536.4  463.85  4579.6  465.82  4806.1  454.16  4818.6  450.39
  4839.1  450.38  4854.5  448.44  4858.4  446.23  4876.9  443.44  4877.4  442.64
  4882.9  443.44  4980.9  449.58  4996.2  450.07  5001.2  444.91  5022.3  446.22
  5080.2  450.08  5261.4  454.38  5300.7  457.48    5412  459.62  5804.9  459.73
#Mann= 5 ,-1 , 0
  4242.2     .16       0  4876.9     .07       0  4882.9     .16       0
  4980.9     .16       0  5300.7     .05       0
Bank Sta=4858.4,5022.3
XS Rating Curve= 0 ,0
Exp/Cntr=0.3,0.1

Type RM Length L Ch R = 1 ,18971   ,701,701,701
BEGIN DESCRIPTION:
Mapping XS 6dfb08ce
END DESCRIPTION:
XS GIS Cut Line= 4
      2892171.02      6960881.82      2892800.33      6961033.72
      2893177.93      6961055.42      2893540.29      6960710.32
#Sta/Elev= 30
  4227.2  451.22  4241.6   451.9    4293  442.59  4343.3  443.94  4348.5  441.76
  4432.2  450.06  4474.1  451.74  4479.2  449.64    4516  453.24  4521.1  450.71
  4557.9  453.97    4563  451.66  4599.8  452.61  4604.9  449.77  4683.5  444.77
  4688.7  441.97  4730.6  444.26  4766.2  442.58  4777.6  437.76  4838.6  429.23
  4849.2  428.43  4896.3  426.15  4896.8  425.35  4902.3  426.15  4988.6  426.15
  5180.9  428.43  5209.8  435.09  5229.8  448.03  5299.3  456.64  5753.2  453.91
#Mann= 6 ,-1 , 0
  4227.2     .16       0  4838.6     .05       0  4896.3     .07       0
  4902.3     .05       0  4988.6     .16       0  5299.3     .05       0
Bank Sta=4849.2,5180.9
XS Rating Curve= 0 ,0
Exp/Cntr=0.3,0.1

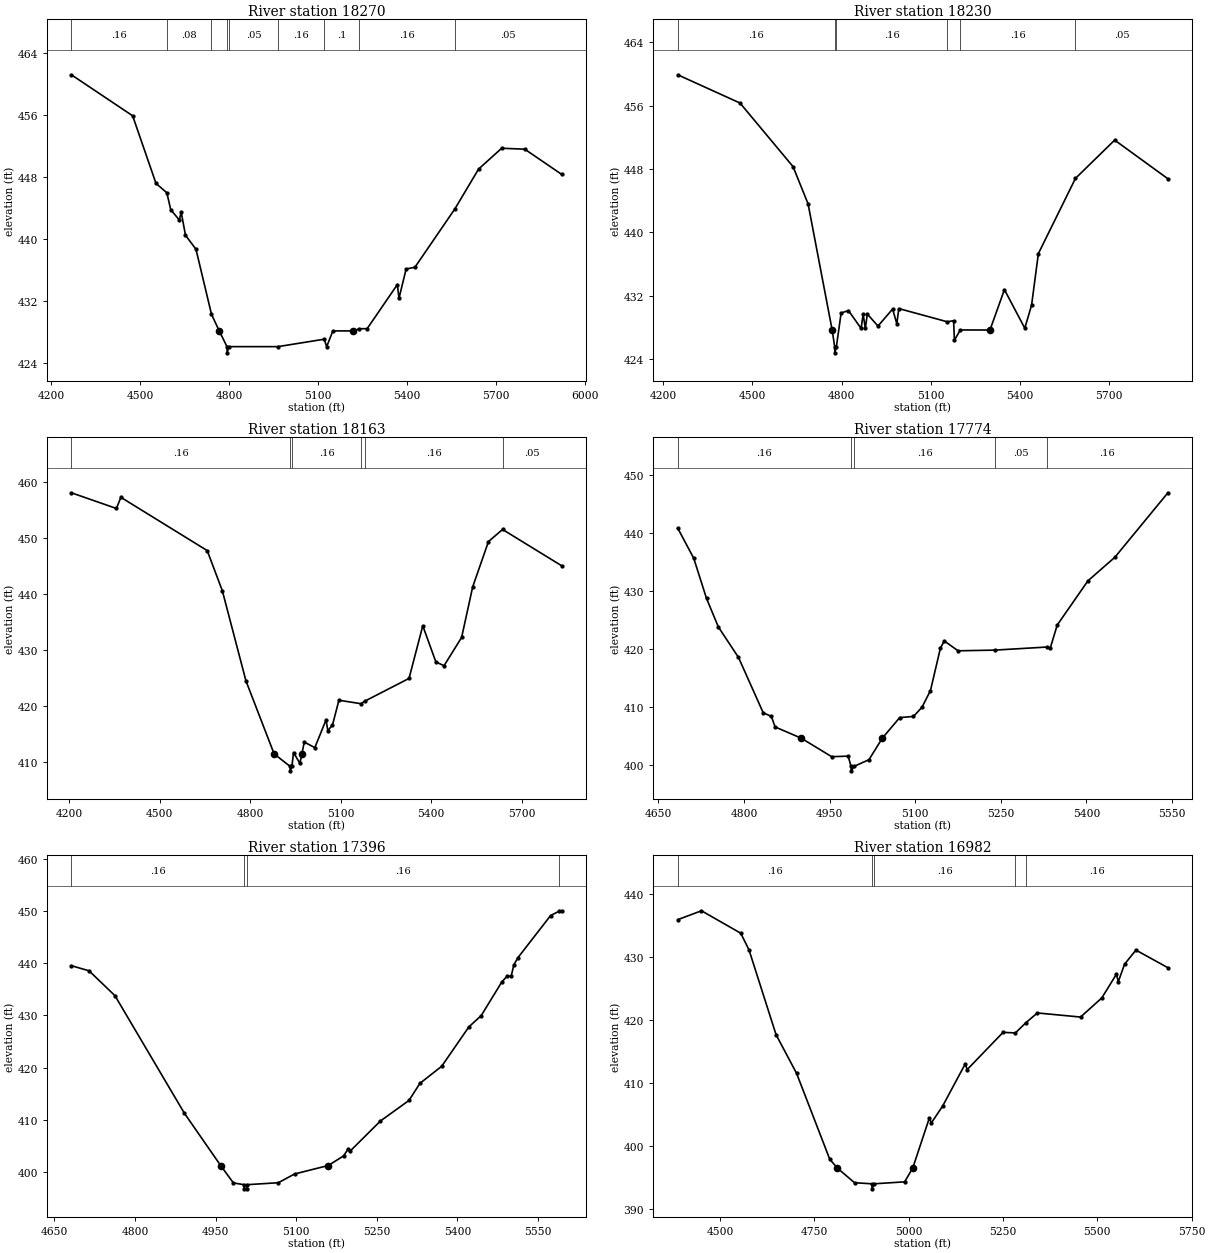
Type RM Length L Ch R = 1 ,18270   ,40,40,40
BEGIN DESCRIPTION:
Mapping XS ed9280c4
END DESCRIPTION:
XS GIS Cut Line= 4
      2892683.13      6962222.96      2893052.07      6961749.86
      2893299.46      6961476.43      2893555.55       6960842.7
#Sta/Elev= 30
  4268.7  461.23  4475.2  455.94  4553.9  447.22  4590.6     446  4603.6  443.83
  4632.6  442.49  4638.9  443.51  4653.4  440.52  4688.7  438.72    4741  430.33
  4767.1  428.18  4793.3  426.15  4793.8  425.35  4799.3  426.15  4965.2  426.15
    5121  427.11  5129.3  426.15  5150.2  428.18  5219.4  428.18  5239.3  428.46
  5265.7  428.47  5367.6  434.16    5373  432.38  5397.1  436.17  5426.7  436.39
  5561.5  443.93  5641.3  449.06  5719.1  451.75  5796.9  451.63  5920.9  448.39
#Mann= 9 ,-1 , 0
  4268.7     .16       0  4590.6     .08       0    4741     .05       0
  4793.3     .07       0  4799.3     .05       0  4965.2     .16       0
    5121      .1       0  5239.3     .16       0  5561.5     .05       0
Bank Sta=4767.1,5219.4
XS Rating Curve= 0 ,0
Exp/Cntr=0.3,0.1

Type RM Length L Ch R = 1 ,18230   ,67,67,67
BEGIN DESCRIPTION:
Mapping XS 4c222a29
END DESCRIPTION:
XS GIS Cut Line= 4
      2892717.86      6962279.38       2893034.7      6961827.99
      2893290.78      6961545.87      2893594.58      6960894.87
#Sta/Elev= 30
  4248.3  459.91  4458.1  456.34  4636.7  448.31  4687.3  443.61  4768.4  427.68
  4776.7   425.6  4777.2   424.8  4782.7   425.6  4798.6  429.83  4823.3  430.14
  4865.9  427.88  4872.7  429.67  4880.1  427.89  4886.8   429.7  4922.7  428.18
    4972  430.33  4986.2  428.47  4992.9  430.39  5156.3  428.72  5177.4  428.86
  5180.2  426.39    5200  427.69  5299.9  427.68  5348.6  432.78  5417.2  427.91
  5440.1  430.83  5462.9  437.33  5587.9  446.83  5719.9  451.66  5899.2  446.78
#Mann= 6 ,-1 , 0
  4248.3     .16       0  4776.7     .07       0  4782.7     .16       0
  5156.3      .1       0    5200     .16       0  5587.9     .05       0
Bank Sta=4768.4,5299.9
XS Rating Curve= 0 ,0
Exp/Cntr=0.3,0.1

Type RM Length L Ch R = 1 ,18163   ,389,389,389
BEGIN DESCRIPTION:
Mapping XS 8bf86b65
END DESCRIPTION:
XS GIS Cut Line= 3
      2892752.58      6962361.84      2893230.02       6961710.8
      2893655.36      6961012.02
#Sta/Elev= 30
  4207.3   458.1  4356.8  455.29  4371.4  457.29  4657.8  447.76  4707.9  440.58
  4786.2  424.46  4879.7  411.39  4932.6  409.16  4933.1  408.36  4938.6  409.16
  4944.1  411.64    4965   409.7  4971.8  411.39  4979.6  413.51  5014.6  412.51
  5051.9  417.48  5057.7  415.55  5073.2  416.55  5094.5  420.99  5167.7  420.37
  5181.6  420.86    5327  424.89  5372.6  434.31  5416.1  427.83  5443.2  427.17
  5501.4  432.22  5538.1  441.26  5590.4  449.37  5637.1  451.54  5832.7  445.06
#Mann= 6 ,-1 , 0
  4207.3     .16       0  4932.6     .07       0  4938.6     .16       0
  5167.7     .05       0  5181.6     .16       0  5637.1     .05       0
Bank Sta=4879.7,4971.8
XS Rating Curve= 0 ,0
Exp/Cntr=0.3,0.1

Type RM Length L Ch R = 1 ,17774   ,378,378,378
BEGIN DESCRIPTION:
UNT 001 IN DRY CR WATERSHED 31.0
END DESCRIPTION:
XS GIS Cut Line= 3
      2893275.01      6962174.99        2893475.        6961925.
      2893675.01      6961424.97
#Sta/Elev= 30
  4684.1  440.86  4712.1  435.67  4734.5  428.73  4755.3   423.8  4790.5  418.55
  4833.8     409  4848.2  408.36  4854.6  406.55  4900.4  404.61  4953.8  401.41
  4982.6  401.51  4987.6  399.77  4988.1  398.97  4993.6  399.77  5019.1  400.89
  5042.5  404.61  5072.9  408.16  5097.1  408.36    5112  409.95  5126.8  412.82
  5144.3  420.16    5151   421.4  5175.2  419.69  5239.4  419.81  5330.8  420.34
  5336.8  420.19  5348.9  424.14  5402.7  431.77  5449.9  435.84  5542.8  446.97
#Mann= 5 ,-1 , 0
  4684.1     .16       0  4987.6     .07       0  4993.6     .16       0
  5239.4     .05       0  5330.8     .16       0
Bank Sta=4900.4,5042.5
XS Rating Curve= 0 ,0
Exp/Cntr=0.3,0.1

Type RM Length L Ch R = 1 ,17396   ,414,414,414
BEGIN DESCRIPTION:
UNT 001 IN DRY CR WATERSHED 30.0
END DESCRIPTION:
XS GIS Cut Line= 3
      2893775.01      6962274.96        2893825.        6961975.
        2893725.      6961374.97
#Sta/Elev= 30
  4681.4  439.51  4714.3  438.53  4762.5  433.77  4891.7  411.25  4959.3  401.22
    4983  397.88  5002.8  397.55  5003.3  396.75  5008.3  396.75  5008.8  397.55
  5066.6  397.92    5097   399.6  5159.6  401.22  5188.3  403.07  5195.9   404.3
  5200.9  404.04  5256.7  409.75  5309.9  413.69  5330.2  416.96  5370.7  420.23
  5421.4  427.79  5444.2  429.93  5482.3  436.33  5492.4  437.51    5500  437.46
  5505.1  439.69  5512.7  441.05  5573.5  449.12  5589.9  449.98  5593.8  450.03
#Mann= 4 ,-1 , 0
  4681.4     .16       0  5002.8     .07       0  5008.8     .16       0
  5589.9     .05       0
Bank Sta=4959.3,5159.6
XS Rating Curve= 0 ,0
Exp/Cntr=0.3,0.1

Type RM Length L Ch R = 1 ,16982   ,408,408,408
BEGIN DESCRIPTION:
UNT 001 IN DRY CR WATERSHED 29.0
END DESCRIPTION:
XS GIS Cut Line= 3
      2893980.03      6962584.91      2894224.81       6962126.6
      2894146.69       6961350.6
#Sta/Elev= 30
  4387.5  435.93  4450.4  437.34  4554.5  433.78  4576.5  431.12  4648.1  417.68
  4702.5  411.54  4790.3  397.93    4810  396.53  4856.2  394.17  4902.2     394
  4902.7   393.2  4908.2     394  4989.1  394.31  5010.7  396.53  5054.7  404.47
  5059.7  403.65  5089.6  406.32  5149.8  413.04  5154.8  412.13    5250  418.04
  5282.7  417.95  5310.9  419.59  5340.9  421.12  5455.4  420.47  5511.7   423.5
  5550.5  427.27  5555.5  426.08    5572  428.85  5602.2   431.1    5687   428.3
#Mann= 5 ,-1 , 0
  4387.5     .16       0  4902.2     .07       0  4908.2     .16       0
  5282.7     .12       0  5310.9     .16       0
Bank Sta=4810,5010.7
XS Rating Curve= 0 ,0
Exp/Cntr=0.3,0.1

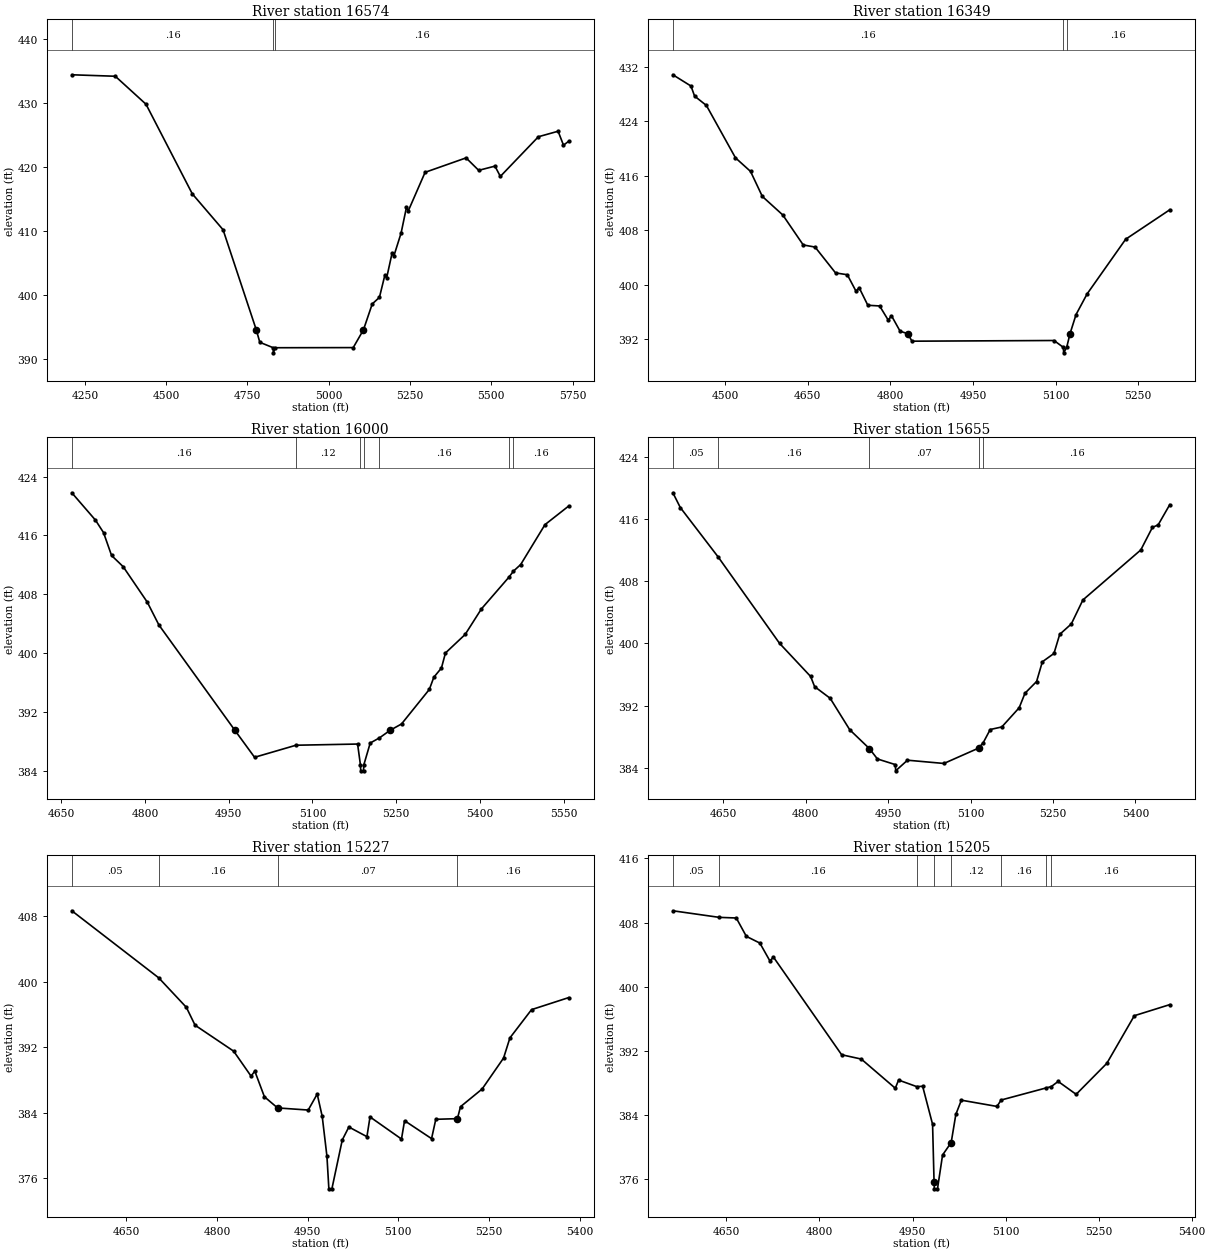
Type RM Length L Ch R = 1 ,16574   ,225,225,225
BEGIN DESCRIPTION:
UNT 001 IN DRY CR WATERSHED 28.0
END DESCRIPTION:
XS GIS Cut Line= 3
      2894125.87      6962803.66      2894639.54      6962087.69
       2894344.6      6961512.02
#Sta/Elev= 30
  4209.8  434.43  4343.5   434.2  4437.9  429.82  4580.3  415.79  4674.9  410.17
    4777  394.51  4787.9  392.55  4829.1   391.7  4829.6   390.9  4835.1   391.7
  5075.2  391.72  5106.7  394.51  5133.6  398.55  5155.8  399.59  5172.4  403.05
    5178  402.64  5194.6   406.5  5200.2  406.07  5222.4  409.65    5239  413.71
  5244.6  413.14  5296.2  419.16  5422.2  421.42    5461  419.47    5511  420.13
  5527.6  418.52  5644.6  424.73  5705.2  425.59  5721.8  423.41  5737.8  424.02
#Mann= 3 ,-1 , 0
  4209.8     .16       0  4829.1     .07       0  4835.1     .16       0
Bank Sta=4777,5106.7
XS Rating Curve= 0 ,0
Exp/Cntr=0.3,0.1

Type RM Length L Ch R = 1 ,16349   ,349,349,349
BEGIN DESCRIPTION:
UNT 001 IN DRY CR WATERSHED 27.0
END DESCRIPTION:
XS GIS Cut Line= 3
      2894469.61      6962793.25        2894775.        6962275.
        2894775.      6961975.04
#Sta/Elev= 30
  4405.6  430.79  4438.4  429.14    4445  427.66  4466.4  426.29  4519.2   418.6
  4546.5  416.61  4567.9  412.94    4605  410.22  4642.1  405.82  4663.6  405.51
  4700.7  401.72  4722.1  401.45  4737.8  399.04  4743.6  399.54  4759.3  396.97
  4780.7  396.87  4796.4  394.78  4802.2  395.44  4817.8  393.17  4831.9  392.79
  4839.3   391.7  5097.1   391.8  5114.1  390.79  5114.6  389.99  5120.1  390.79
  5126.1  392.79  5137.1  395.61  5157.1  398.63  5227.1  406.66  5307.1  410.98
#Mann= 3 ,-1 , 0
  4405.6     .16       0  5114.1     .07       0  5120.1     .16       0
Bank Sta=4831.9,5126.1
XS Rating Curve= 0 ,0
Exp/Cntr=0.3,0.1

Type RM Length L Ch R = 1 ,16000   ,345,345,345
BEGIN DESCRIPTION:
UNT 001 IN DRY CR WATERSHED 26.0
END DESCRIPTION:
XS GIS Cut Line= 3
      2894775.02      6962674.98        2895025.        6962475.
      2895474.99      6962125.01
#Sta/Elev= 30
  4668.9  421.79  4711.3  418.07  4725.7  416.38  4740.1  413.27  4760.9  411.75
  4804.1  406.93  4824.9  403.83  4961.1  389.51  4996.3  385.85  5070.5  387.49
  5180.9  387.65    5186  384.81  5186.5  384.01  5191.5  384.01    5192  384.81
  5203.5  387.79  5220.1  388.49    5239  389.51  5259.6  390.38  5309.4  395.07
  5317.5  396.73  5331.1  397.98  5338.3  400.02  5373.6  402.54  5402.6     406
  5452.2  410.34  5460.1  411.14  5473.1  412.04  5516.6  417.46  5559.1  419.99
#Mann= 7 ,-1 , 0
  4668.9     .16       0  5070.5     .12       0    5186     .07       0
    5192     .12       0  5220.1     .16       0  5452.2     .12       0
  5460.1     .16       0
Bank Sta=4961.1,5239
XS Rating Curve= 0 ,0
Exp/Cntr=0.3,0.1

Type RM Length L Ch R = 1 ,15655   ,428,428,428
BEGIN DESCRIPTION:
UNT 001 IN DRY CR WATERSHED 25.0
END DESCRIPTION:
XS GIS Cut Line= 3
      2894975.04      6962874.97        2895325.        6962625.
        2895475.      6962175.01
#Sta/Elev= 30
  4558.2  419.39  4571.7  417.49  4640.9   411.1  4752.3  400.01  4808.9  395.74
  4816.2  394.43  4844.5  392.93  4880.1  388.88  4915.8  386.46  4930.5  385.12
  4963.2  384.39  4963.7  383.59  4985.2  384.96  5051.5  384.54  5114.8  386.52
  5123.2  387.23  5135.8  388.91  5156.9  389.24  5188.5  391.71  5199.1  393.58
  5220.2  395.09  5230.7  397.63  5251.8   398.7  5262.3  401.16  5283.4   402.5
  5304.5  405.59  5409.9  412.03    5431  414.93  5441.5  415.26  5462.6  417.86
#Mann= 5 ,-1 , 0
  4558.2     .05       0  4640.9     .16       0  4915.8     .07       0
  5114.8     .12       0  5123.2     .16       0
Bank Sta=4915.8,5114.8
XS Rating Curve= 0 ,0
Exp/Cntr=0.3,0.1

Type RM Length L Ch R = 1 ,15227   ,22,22,22
BEGIN DESCRIPTION:
Mapping XS 22cc7259
END DESCRIPTION:
XS GIS Cut Line= 5
      2895331.48      6963298.34      2895520.26       6963065.3
      2895591.87      6962933.79      2895619.22      6962790.56
       2895675.2      6962570.54
#Sta/Elev= 30
  4559.5  408.64  4703.4  400.45  4749.1  396.85  4763.5  394.67  4827.4   391.5
  4856.2  388.45  4862.4  389.06  4878.3  385.93  4900.1  384.57  4950.8  384.31
  4965.7  386.26    4974  383.53  4981.8  378.67    4985  374.69    4990  374.69
  5007.2  380.66  5018.1  382.24    5048  381.06  5053.1  383.47  5105.2  380.77
  5110.3  383.01    5155  380.82    5162  383.18  5197.8  383.26  5202.9  384.72
  5238.7  386.88  5274.2  390.66  5284.7  393.12  5320.5  396.57    5382  398.04
#Mann= 4 ,-1 , 0
  4559.5     .05       0  4703.4     .16       0  4900.1     .07       0
  5197.8     .16       0
Bank Sta=4900.1,5197.8
XS Rating Curve= 0 ,0
Exp/Cntr=0.3,0.1

Type RM Length L Ch R = 1 ,15205   ,25,25,25
BEGIN DESCRIPTION:
Mapping XS a7e79b2c
END DESCRIPTION:
XS GIS Cut Line= 5
      2895413.47      6963343.99      2895560.62      6963073.11
      2895617.92      6962923.37      2895658.28       6962751.5
      2895690.83      6962599.18
#Sta/Elev= 30
  4563.7  409.47  4638.3  408.65  4665.9  408.57  4682.1  406.28  4703.9  405.44
  4720.1  403.21  4725.8  403.69  4835.7  391.51  4867.4  390.97  4922.2  387.33
  4927.5  388.35  4956.5  387.54  4966.3  387.57  4982.3  382.83  4984.7  375.58
  4985.2  374.78  4990.2  374.78  4998.4     379  5012.3  380.56  5019.8  384.07
  5028.7  385.84  5086.1  385.06  5092.8  385.86  5165.4  387.37  5173.7  387.54
  5184.7  388.18  5213.7  386.57  5263.2  390.44  5307.5  396.38  5364.6  397.76
#Mann= 8 ,-1 , 0
  4563.7     .05       0  4638.3     .16       0  4956.5     .12       0
  4985.2     .03       0  5012.3     .12       0  5092.8     .16       0
  5165.4     .12       0  5173.7     .16       0
Bank Sta=4984.7,5012.3
XS Rating Curve= 0 ,0
Exp/Cntr=0.3,0.1

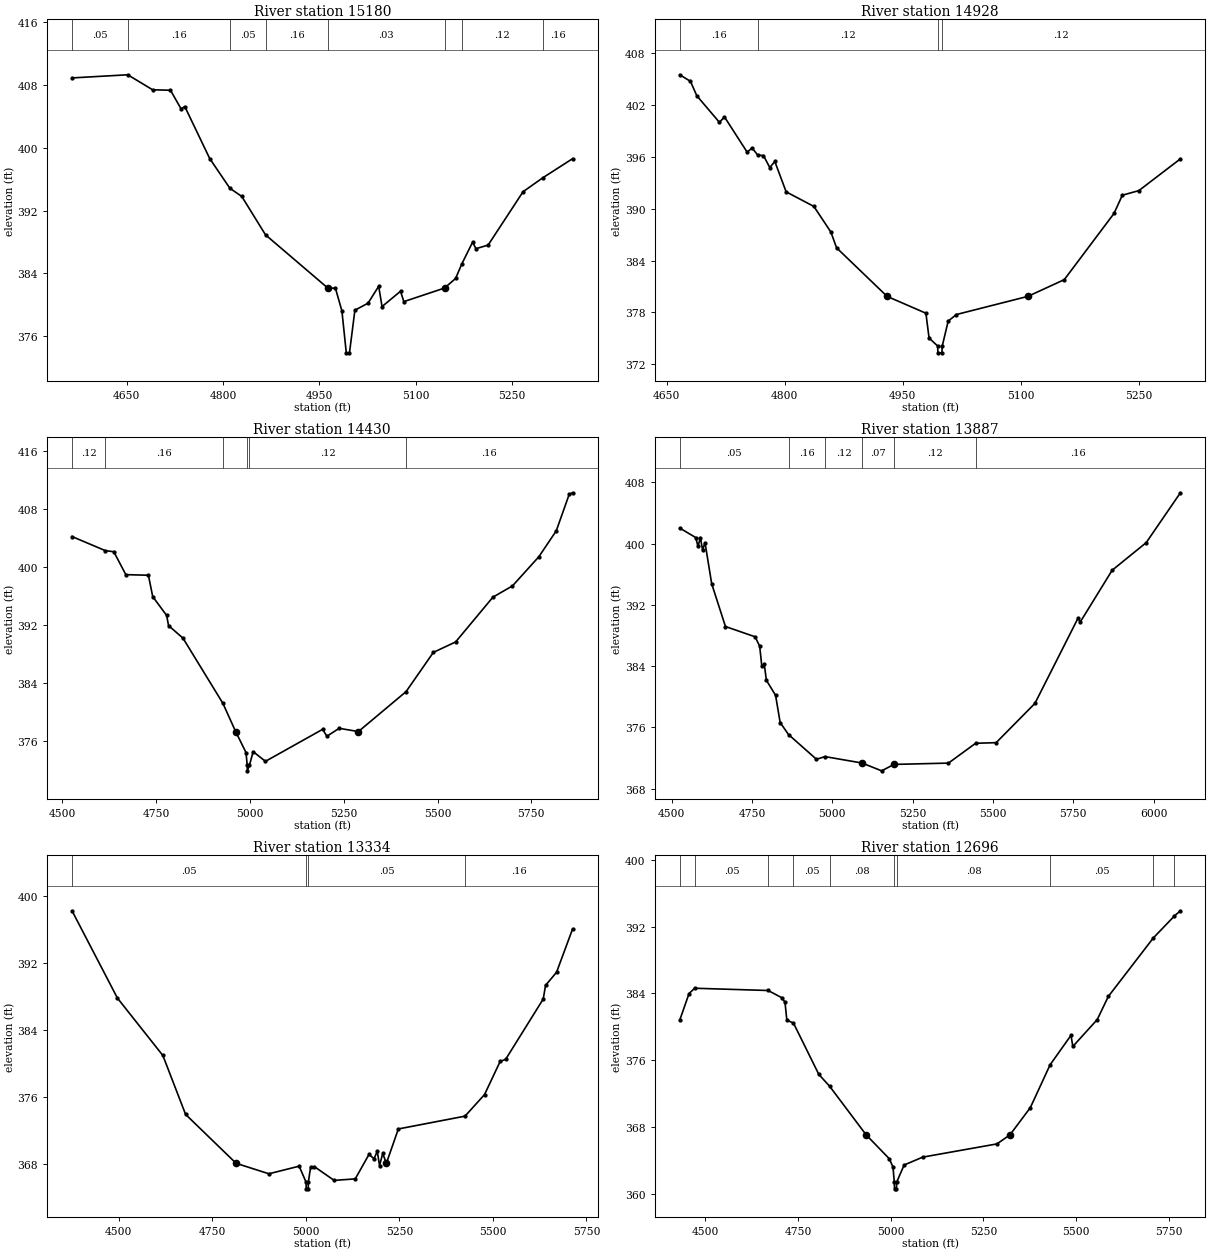
Type RM Length L Ch R = 1 ,15180   ,252,252,252
BEGIN DESCRIPTION:
Mapping XS 97a84cc4
END DESCRIPTION:
XS GIS Cut Line= 5
      2895460.38      6963356.93      2895617.92      6963048.37
      2895632.24      6962945.51       2895671.3      6962807.49
      2895721.59      6962628.25
#Sta/Elev= 30
  4564.6  408.89  4651.4  409.29  4690.2  407.38    4718  407.32  4734.6  404.94
  4740.3  405.25  4779.1  398.63  4810.6  394.84  4829.1   393.8  4866.1  388.91
  4963.1  382.14    4975  382.12  4985.1  379.22  4991.9  373.89  4996.9  373.89
  5005.3  379.32  5025.8  380.21  5042.4  382.37  5047.6  379.78  5076.4  381.73
  5081.6  380.41    5145  382.14  5162.2  383.36  5171.9  385.21  5188.7  387.98
  5193.9  387.15  5212.9  387.61  5267.3   394.4  5297.8  396.16  5344.5  398.61
#Mann= 8 ,-1 , 0
  4564.6     .05       0  4651.4     .16       0  4810.6     .05       0
  4866.1     .16       0  4963.1     .03       0    5145     .16       0
  5171.9     .12       0  5297.8     .16       0
Bank Sta=4963.1,5145
XS Rating Curve= 0 ,0
Exp/Cntr=0.3,0.1

Type RM Length L Ch R = 1 ,14928   ,498,498,498
BEGIN DESCRIPTION:
UNT 001 IN DRY CR WATERSHED 23.0
END DESCRIPTION:
XS GIS Cut Line= 3
      2895675.02      6963224.98        2895875.        6962975.
      2895774.99      6962674.96
#Sta/Elev= 30
  4666.7  405.47  4680.3  404.71  4688.3  403.05  4717.1  399.97  4723.5   400.6
  4752.3  396.53  4758.7  397.01  4765.7  396.19  4773.1  396.13  4781.1  394.75
  4787.5  395.45  4801.9  391.94  4837.2  390.25  4858.8  387.29    4866  385.47
  4930.2  379.86  4979.6  377.91  4983.6  375.04  4994.4  374.13  4994.9  373.33
  4999.9  373.33  5000.4  374.13  5007.9     377  5018.4  377.76  5109.3  379.86
  5155.5  381.79  5218.7  389.44  5229.3  391.55  5250.3  392.08  5303.1  395.75
#Mann= 4 ,-1 , 0
  4666.7     .16       0  4765.7     .12       0  4994.4     .07       0
  5000.4     .12       0
Bank Sta=4930.2,5109.3
XS Rating Curve= 0 ,0
Exp/Cntr=0.3,0.1

Type RM Length L Ch R = 1 ,14430   ,543,543,543
BEGIN DESCRIPTION:
UNT 001 IN DRY CR WATERSHED 22.0
END DESCRIPTION:
XS GIS Cut Line= 3
      2895825.04      6963324.99        2896275.        6963225.
      2896624.98      6962425.04
#Sta/Elev= 30
  4525.8  404.19  4614.4  402.25  4637.2  402.09  4669.2  398.93  4729.4  398.85
  4740.9   395.9    4778   393.3  4783.1   391.9  4821.6  390.16  4927.9  381.17
  4961.9  377.27  4989.5  374.38  4992.7  372.65  4993.2  371.85  4998.8  372.65
  5008.6   374.5  5041.3  373.16  5193.7  377.58    5205  376.62  5237.8  377.72
    5289  377.27  5416.2  382.79  5488.8   388.2  5548.1  389.64  5647.5  395.82
  5699.7  397.38  5769.9   401.4  5816.3  404.97    5851  410.04  5859.9  410.23
#Mann= 6 ,-1 , 0
  4525.8     .12       0  4614.4     .16       0  4927.9     .12       0
  4992.7     .07       0  4998.8     .12       0  5416.2     .16       0
Bank Sta=4961.9,5289
XS Rating Curve= 0 ,0
Exp/Cntr=0.3,0.1

Type RM Length L Ch R = 1 ,13887   ,553,553,553
BEGIN DESCRIPTION:
UNT 001 IN DRY CR WATERSHED 21.0
END DESCRIPTION:
XS GIS Cut Line= 3
      2896374.99      6963925.01        2896675.        6963575.
      2897475.02      6962824.98
#Sta/Elev= 30
  4525.5  402.04  4575.4  400.79    4582  399.64  4589.7   400.8  4596.3  399.19
    4604  400.13  4624.8  394.76  4667.6  389.18  4759.8  387.84  4774.1  386.61
  4780.7     384  4788.4  384.22    4795  382.15  4823.5   380.2  4837.8  376.64
  4863.8  375.07  4950.8  371.84  4977.3  372.19  5092.7  371.35  5153.6  370.33
  5191.9  371.17  5361.4  371.34    5446  373.93  5509.9  374.01  5630.5  379.14
  5764.8  390.29  5771.7  389.78  5870.8  396.53  5976.8  400.14  6083.1  406.65
#Mann= 6 ,-1 , 0
  4525.5     .05       0  4863.8     .16       0  4977.3     .12       0
  5092.7     .07       0  5191.9     .12       0    5446     .16       0
Bank Sta=5092.7,5191.9
XS Rating Curve= 0 ,0
Exp/Cntr=0.3,0.1

Type RM Length L Ch R = 1 ,13334   ,638,638,638
BEGIN DESCRIPTION:
UNT 001 IN DRY CR WATERSHED 20.0
END DESCRIPTION:
XS GIS Cut Line= 3
      2896475.03        6964025.        2897125.        6963925.
      2897525.01      6963374.99
#Sta/Elev= 30
  4375.2  398.29  4496.6  387.85    4618  380.99  4678.7  373.95  4813.8   368.1
  4901.3  366.85  4982.2  367.76  5000.6  365.85  5001.1  365.05  5006.3  365.05
  5006.8  365.85  5012.6  367.61  5022.7  367.71  5075.7  366.06  5132.1  366.24
  5168.8  369.16  5182.4  368.65  5190.9  369.55    5197  367.83  5205.5  369.28
  5215.2   368.1  5247.3  372.21  5425.4  373.74  5477.6  376.32  5519.3  380.28
    5534  380.53  5634.4  387.74  5640.6  389.37    5670  390.94  5712.9  396.12
#Mann= 4 ,-1 , 0
  4375.2     .05       0  5000.6     .03       0  5006.8     .05       0
  5425.4     .16       0
Bank Sta=4813.8,5215.2
XS Rating Curve= 0 ,0
Exp/Cntr=0.3,0.1

Type RM Length L Ch R = 1 ,12696   ,123,123,123
BEGIN DESCRIPTION:
Mapping XS 660e3a6b
END DESCRIPTION:
XS GIS Cut Line= 3
      2897617.43      6964809.92      2897622.64      6964226.58
      2897586.18      6963460.91
#Sta/Elev= 30
  4431.2  380.82  4456.1  383.98  4471.3  384.62  4669.5  384.35  4706.1  383.49
  4714.9  382.95  4719.9   380.8  4737.7  380.46  4806.1  374.32  4835.5  372.89
  4933.8  367.09  4996.1  364.24  5006.1  363.24  5009.7  361.44  5010.2  360.64
  5015.5  360.64    5016  361.44  5036.2  363.49  5086.2  364.43  5286.4  366.01
  5321.5  367.09  5376.5  370.35  5429.8  375.47  5486.1  378.99  5491.1  377.66
  5556.8  380.87  5586.8  383.64  5708.1  390.63  5764.8  393.25  5781.1  393.88
#Mann= 10 ,-1 , 0
  4431.2     .08       0  4471.3     .05       0  4669.5     .08       0
  4737.7     .05       0  4835.5     .08       0  5009.7     .07       0
    5016     .08       0  5429.8     .05       0  5708.1     .16       0
  5764.8     .08       0
Bank Sta=4933.8,5321.5
XS Rating Curve= 0 ,0
Exp/Cntr=0.3,0.1