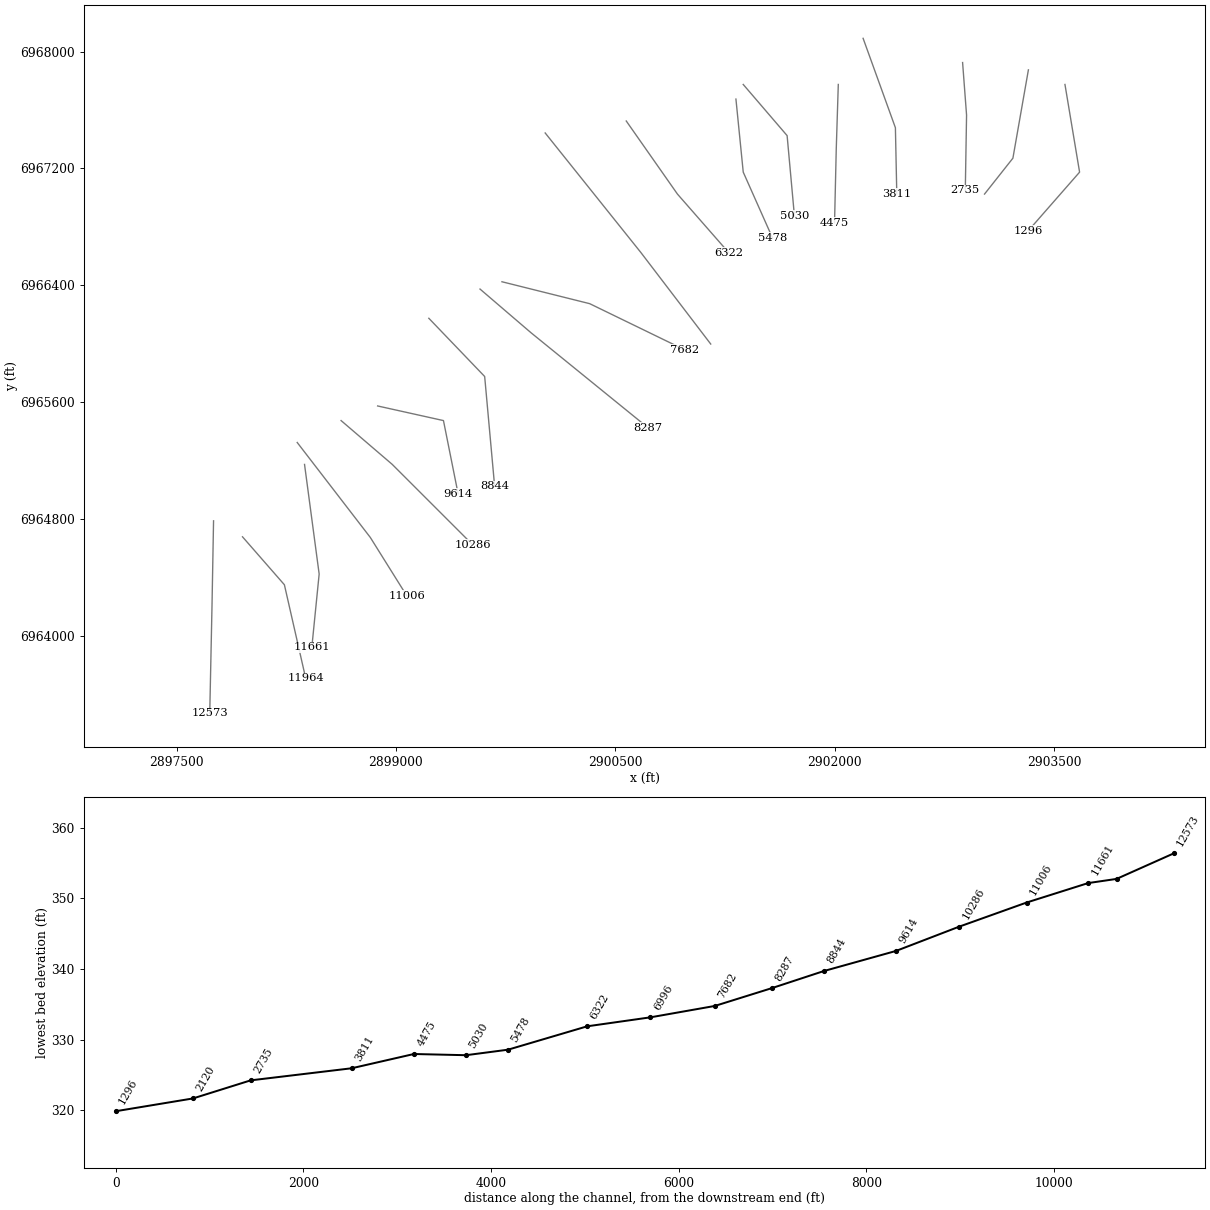
HEC-RAS study UNT 001 IN DRY CR WATERSHED.prj: UNT 001 IN DRY CR WATERSHED Base Level Engineering

--- UNT 001 IN DRY CR WATERSHED.g01 (geometry) --- (continued)

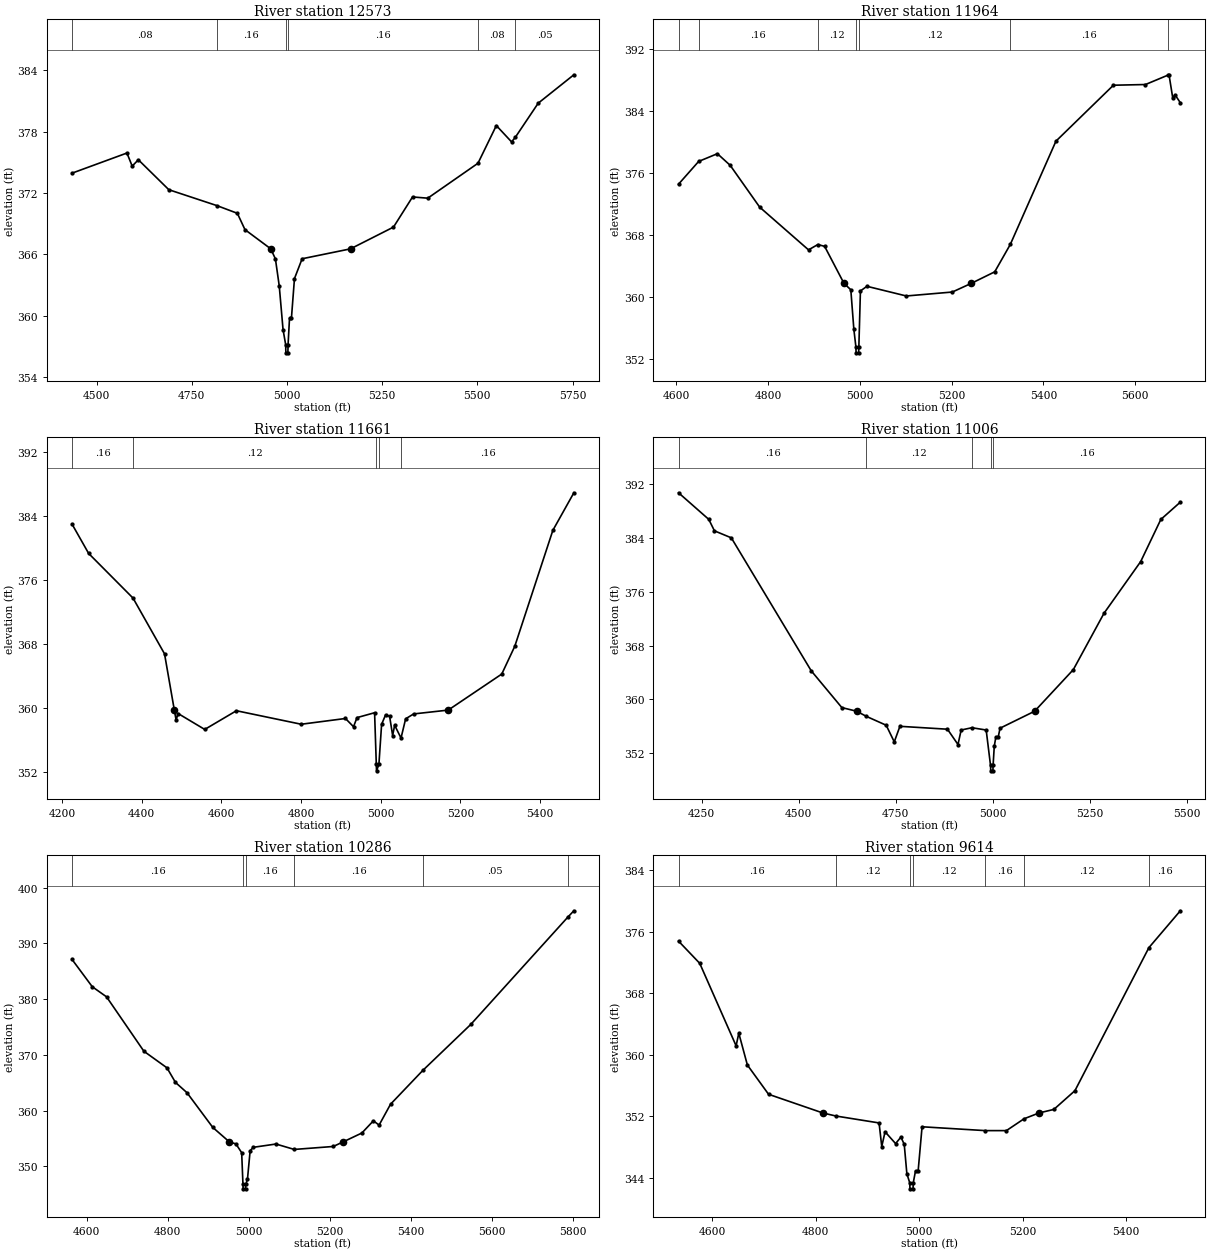
Type RM Length L Ch R = 1 ,12573   ,609,609,609
BEGIN DESCRIPTION:
Mapping XS 509fe7df
END DESCRIPTION:
XS GIS Cut Line= 3
      2897752.85      6964789.05      2897742.43      6964216.16
      2897726.81      6963471.41
#Sta/Elev= 30
  4435.6  373.94  4579.7  375.91  4593.5  374.63  4609.7  375.25  4689.7  372.32
  4816.2  370.76  4869.7  370.01  4889.7  368.41  4957.5  366.53  4969.7  365.54
  4979.7  362.91  4989.7  358.63  4996.6  357.15  4997.1  356.35  5002.4  356.35
  5002.9  357.15  5006.7  359.73  5011.7  359.73  5019.7  363.62  5039.8  365.56
  5166.9  366.53  5279.8  368.66  5329.8  371.61  5369.8  371.49  5501.7  374.91
  5549.9   378.6  5589.9     377  5599.6  377.44  5659.9  380.79  5753.5  383.57
#Mann= 6 ,-1 , 0
  4435.6     .08       0  4816.2     .16       0  4996.6     .07       0
  5002.9     .16       0  5501.7     .08       0  5599.6     .05       0
Bank Sta=4957.5,5166.9
XS Rating Curve= 0 ,0
Exp/Cntr=0.3,0.1

Type RM Length L Ch R = 1 ,11964   ,303,303,303
BEGIN DESCRIPTION:
Mapping XS bb8de396
END DESCRIPTION:
XS GIS Cut Line= 3
       2897950.8      6964679.67      2898237.23      6964351.58
      2898383.05      6963710.99
#Sta/Elev= 30
  4605.4  374.54  4649.2  377.48    4690  378.48  4717.8  376.98  4782.1  371.57
  4888.4  366.05  4908.8  366.74  4923.5   366.5  4965.5  361.73  4980.5  360.89
  4987.1  355.78  4991.5  353.54    4992  352.74  4997.5  352.74    4998  353.54
  5001.4  360.74  5015.6  361.34  5101.3  360.09  5201.5   360.6  5243.1  361.73
  5293.8  363.21  5327.7  366.75  5427.1   380.1  5552.2  387.33    5622  387.42
    5670  388.61  5673.3  388.68  5681.3  385.72  5686.4  386.09  5697.9  385.07
#Mann= 7 ,-1 , 0
  4605.4     .12       0  4649.2     .16       0  4908.8     .12       0
  4991.5     .07       0    4998     .12       0  5327.7     .16       0
    5670     .05       0
Bank Sta=4965.5,5243.1
XS Rating Curve= 0 ,0
Exp/Cntr=0.3,0.1

Type RM Length L Ch R = 1 ,11661   ,655,655,655
BEGIN DESCRIPTION:
UNT 001 IN DRY CR WATERSHED 17.0
END DESCRIPTION:
XS GIS Cut Line= 3
        2898375.        6965175.        2898475.        6964425.
        2898425.      6963925.03
#Sta/Elev= 30
  4225.5  383.01  4267.1  379.35  4378.5  373.76  4457.5  366.79  4482.1  359.75
  4486.5  358.52  4491.6  359.32  4558.4  357.33  4637.9  359.67  4800.5  357.98
  4911.5   358.7  4931.7  357.67  4940.5  358.81  4984.6  359.42  4988.9  352.95
  4989.4  352.15  4995.4  352.95  5002.2  357.97  5012.3  359.17  5022.3  358.97
  5029.9  356.56  5034.9  357.86  5050.9  356.25  5062.5  358.66  5082.6  359.27
  5169.4  359.75  5303.7  364.26  5336.4  367.74  5431.9  382.24  5484.6  386.94
#Mann= 5 ,-1 , 0
  4225.5     .16       0  4378.5     .12       0  4988.9     .07       0
  4995.4     .12       0  5050.9     .16       0
Bank Sta=4482.1,5169.4
XS Rating Curve= 0 ,0
Exp/Cntr=0.3,0.1

Type RM Length L Ch R = 1 ,11006   ,720,720,720
BEGIN DESCRIPTION:
UNT 001 IN DRY CR WATERSHED 16.0
END DESCRIPTION:
XS GIS Cut Line= 3
        2898325.        6965325.        2898825.        6964675.
      2899075.02      6964274.96
#Sta/Elev= 30
  4190.7  390.68  4268.6  386.73  4283.1  385.03  4326.6  383.99  4532.3  364.25
  4611.1  358.79  4649.3  358.25  4674.5  357.48  4725.3  356.17  4746.1   353.7
  4760.6  356.01    4883  355.58  4910.1  353.31  4918.3  355.46  4945.9   355.8
  4982.7  355.46  4993.9   350.2  4994.4   349.4    5000   349.4  5000.5   350.2
  5003.5  353.04  5007.6  354.42  5013.7  354.42  5018.4  355.73  5107.4  358.25
  5207.1  364.43  5286.1   372.8  5380.5  380.47  5432.3  386.72  5482.5  389.29
#Mann= 5 ,-1 , 0
  4190.7     .16       0  4674.5     .12       0  4945.9     .16       0
  4993.9     .07       0  5000.5     .16       0
Bank Sta=4649.3,5107.4
XS Rating Curve= 0 ,0
Exp/Cntr=0.3,0.1

Type RM Length L Ch R = 1 ,10286   ,672,672,672
BEGIN DESCRIPTION:
UNT 001 IN DRY CR WATERSHED 15.0
END DESCRIPTION:
XS GIS Cut Line= 3
        2898625.        6965475.        2898975.        6965175.
      2899525.01      6964624.99
#Sta/Elev= 30
  4563.8  387.13  4613.7  382.24  4648.9  380.43  4741.1  370.67  4798.1  367.69
    4819  365.08  4847.5  363.23  4911.2     357  4952.2   354.4  4968.3  354.04
  4982.5  352.47  4985.7  346.78  4986.2  345.98    4992  345.98  4992.5  346.78
  4996.8   347.7  5003.4  352.81  5011.1  353.43  5067.2  354.02  5112.3  353.05
  5208.6  353.58  5232.9   354.4  5279.3     356  5307.6  358.18  5321.8  357.42
    5350  361.16  5429.6  367.22    5548  375.47  5787.7  394.73  5802.6  395.87
#Mann= 6 ,-1 , 0
  4563.8     .16       0  4985.7     .07       0  4992.5     .16       0
  5112.3     .16       0  5429.6     .05       0  5787.7     .07       0
Bank Sta=4952.2,5232.9
XS Rating Curve= 0 ,0
Exp/Cntr=0.3,0.1

Type RM Length L Ch R = 1 ,9614    ,770,770,770
BEGIN DESCRIPTION:
UNT 001 IN DRY CR WATERSHED 14.0
END DESCRIPTION:
XS GIS Cut Line= 3
      2898874.95      6965575.01        2899325.        6965475.
      2899424.99      6964975.03
#Sta/Elev= 30
  4534.4   374.8  4575.4  371.91  4645.8  361.17    4651  362.81  4667.6  358.67
  4708.6  354.86  4813.5  352.43  4838.9  352.03  4922.4  351.13  4927.6  348.06
    4934  349.98  4954.4  348.44  4964.7  349.29  4971.1  348.34  4976.2  344.51
  4981.7  343.35  4982.2  342.55  4988.1  342.55  4988.6  343.35  4992.9  344.88
    4998  344.88  5005.6  350.63  5127.9  350.13  5168.8  350.13  5202.9  351.67
    5232  352.43  5260.6  352.89  5301.4  355.33  5444.5  373.95  5505.3  378.75
#Mann= 7 ,-1 , 0
  4534.4     .16       0  4838.9     .12       0  4981.7     .07       0
  4988.6     .12       0  5127.9     .16       0  5202.9     .12       0
  5444.5     .16       0
Bank Sta=4813.5,5232
XS Rating Curve= 0 ,0
Exp/Cntr=0.3,0.1

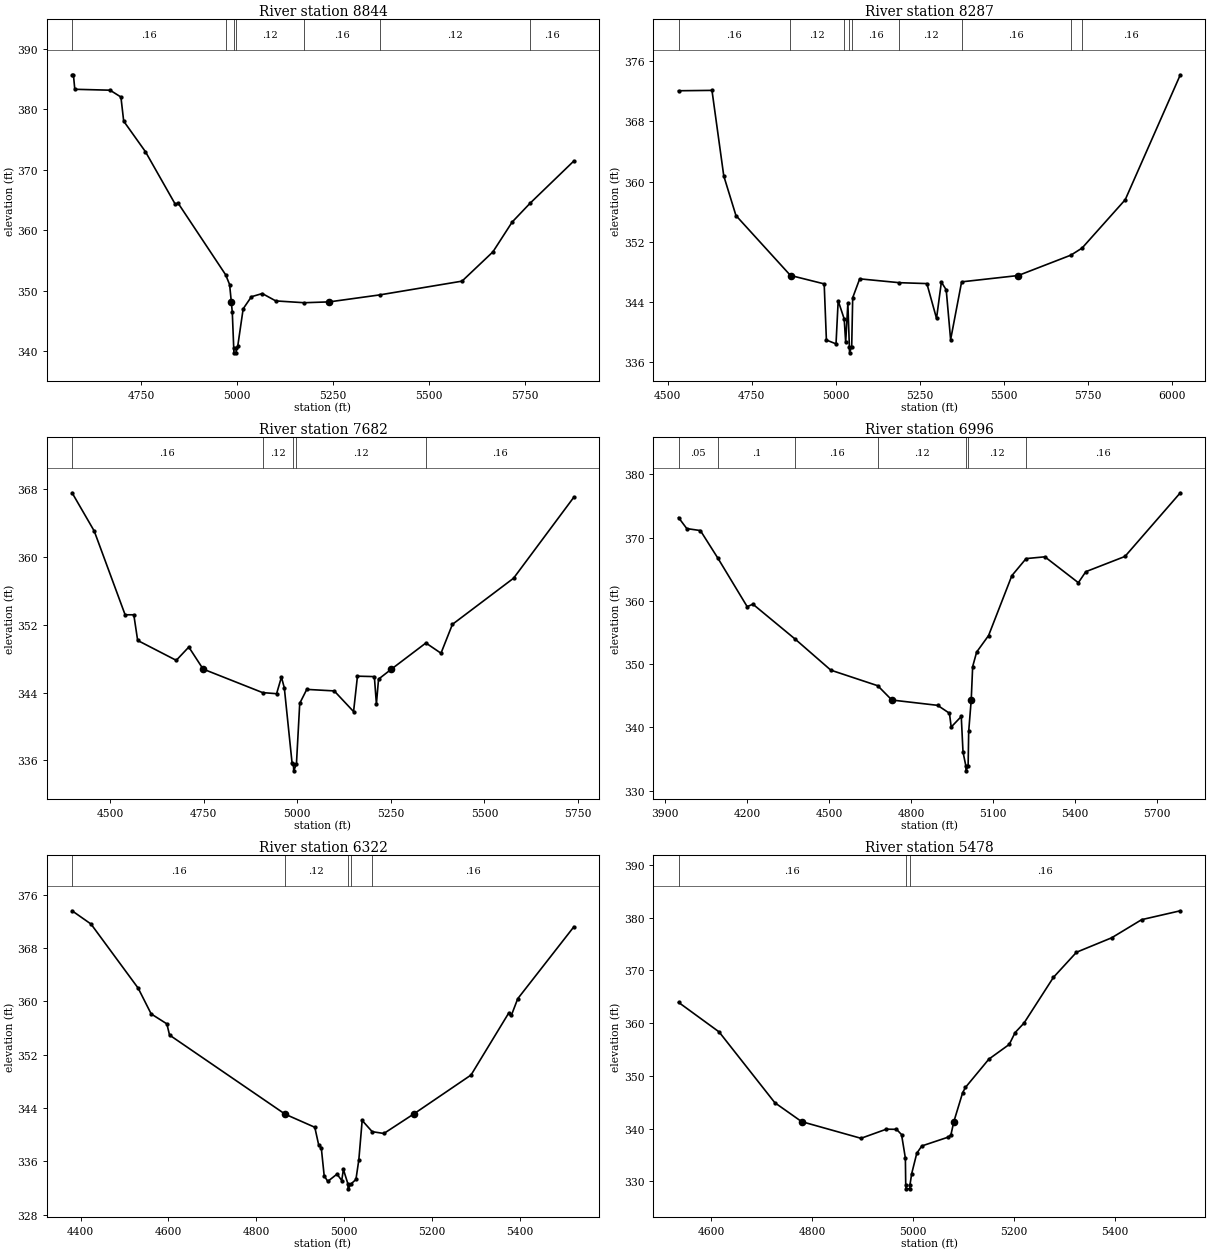
Type RM Length L Ch R = 1 ,8844    ,557,557,557
BEGIN DESCRIPTION:
UNT 001 IN DRY CR WATERSHED 13.0
END DESCRIPTION:
XS GIS Cut Line= 3
        2899225.        6966175.      2899606.82      6965776.68
        2899675.      6965025.03
#Sta/Elev= 30
  4570.2   385.7  4573.7   385.7  4577.3   383.3  4669.1  383.15  4697.4  382.02
  4704.6  378.03  4761.2  372.98  4838.9  364.28  4846.2  364.47  4970.1  352.61
  4980.4  350.99  4984.8  348.13  4987.4  346.39  4991.1   340.5  4991.6   339.7
  4997.5   339.7    4998   340.5  5001.5  340.78  5015.7  346.99  5037.1  348.98
  5065.4  349.51  5100.6  348.29  5174.6  347.99  5239.8  348.13  5370.7  349.28
  5585.5  351.56  5665.9   356.4  5716.1  361.34  5762.9  364.46  5876.7  371.44
#Mann= 7 ,-1 , 0
  4570.2     .16       0  4970.1     .12       0  4991.1     .07       0
    4998     .12       0  5174.6     .16       0  5370.7     .12       0
  5762.9     .16       0
Bank Sta=4984.8,5239.8
XS Rating Curve= 0 ,0
Exp/Cntr=0.3,0.1

Type RM Length L Ch R = 1 ,8287    ,605,605,605
BEGIN DESCRIPTION:
UNT 001 IN DRY CR WATERSHED 12.0
END DESCRIPTION:
XS GIS Cut Line= 3
      2899574.97      6966375.03        2899925.        6966075.
        2900725.        6965425.
#Sta/Elev= 30
  4532.2  372.05  4631.6   372.1  4666.7  360.74  4702.9  355.49  4862.7  347.65
  4865.9  347.53  4965.2  346.42  4971.8  338.97  5000.4  338.46  5006.8  344.18
  5024.7  341.77  5029.1  338.67  5035.6  343.84  5040.1  338.07  5040.6  337.27
    5047  338.07    5050  344.59  5070.8  347.09  5188.4  346.58  5270.5  346.46
  5299.2  341.84  5313.6  346.66    5328  345.63  5341.1  339.02  5373.8  346.69
    5542  347.53  5698.9  350.24  5731.8  351.17  5860.2  357.59    6024  374.17
#Mann= 9 ,-1 , 0
  4532.2     .16       0  4862.7     .12       0  5024.7     .16       0
  5040.1     .07       0    5047     .16       0  5188.4     .12       0
  5373.8     .16       0  5698.9     .12       0  5731.8     .16       0
Bank Sta=4865.9,5542
XS Rating Curve= 0 ,0
Exp/Cntr=0.3,0.1

Type RM Length L Ch R = 1 ,7682    ,686,686,686
BEGIN DESCRIPTION:
UNT 001 IN DRY CR WATERSHED 11.0
END DESCRIPTION:
XS GIS Cut Line= 3
      2899725.02      6966424.99        2900325.        6966275.
      2900974.16       6965959.3
#Sta/Elev= 30
  4398.5   367.6  4457.7  363.08  4540.2  353.19  4563.4  353.19  4573.7  350.16
  4676.8  347.81  4710.3  349.38  4748.5  346.78  4907.4     344  4944.8  343.87
  4957.7  345.83  4965.4  344.57    4986  335.74  4989.8  335.56  4990.5  334.76
  4997.8  335.56  5006.6  342.73  5025.4  344.38  5098.7   344.2  5150.4  341.76
  5160.8  345.94  5205.9  345.89  5211.4  342.66  5217.1  345.59  5251.7  346.78
  5343.6  349.86  5383.9  348.65  5414.4  352.06  5577.8  357.51  5738.8  367.08
#Mann= 5 ,-1 , 0
  4398.5     .16       0  4907.4     .12       0  4989.8     .07       0
  4997.8     .12       0  5343.6     .16       0
Bank Sta=4748.5,5251.7
XS Rating Curve= 0 ,0
Exp/Cntr=0.3,0.1

Type RM Length L Ch R = 1 ,6996    ,674,674,674
BEGIN DESCRIPTION:
UNT 001 IN DRY CR WATERSHED 10.0
END DESCRIPTION:
XS GIS Cut Line= 3
      2900020.66      6967443.02        2900675.        6966625.
      2901152.57      6965998.88
#Sta/Elev= 30
  3949.4  373.17  3979.6  371.43  4029.3  371.12  4093.8  366.72  4200.5  359.09
  4221.3  359.49  4375.8  353.97  4506.3  349.06  4677.9   346.6  4729.5  344.34
  4896.9   343.5  4940.1  342.25  4946.5  340.07  4983.3  341.74  4989.7  336.12
    5000  333.95  5000.8  333.15  5008.4  333.95  5010.5  339.39  5019.7  344.34
    5025  349.63  5039.6  351.92  5083.2  354.53  5168.4     364  5220.4  366.69
    5289  366.97  5411.5  362.88  5438.7  364.62    5582  367.03  5784.4  377.09
#Mann= 7 ,-1 , 0
  3949.4     .05       0  4093.8      .1       0  4375.8     .16       0
  4677.9     .12       0    5000     .07       0  5008.4     .12       0
  5220.4     .16       0
Bank Sta=4729.5,5019.7
XS Rating Curve= 0 ,0
Exp/Cntr=0.3,0.1

Type RM Length L Ch R = 1 ,6322    ,844,844,844
BEGIN DESCRIPTION:
UNT 001 IN DRY CR WATERSHED 9.0
END DESCRIPTION:
XS GIS Cut Line= 3
      2900575.03      6967524.96        2900925.        6967025.
      2901275.01      6966624.99
#Sta/Elev= 30
  4380.8  373.56  4423.9  371.57  4531.2  361.96  4560.8   358.1  4596.5  356.61
  4602.6  354.93    4865   343.1  4865.3  343.08  4933.1  341.11  4941.8  338.51
  4947.9  338.02  4954.5  333.82  4962.7     333  4983.7  334.09  4994.4  333.13
  4998.2  334.79  5008.2  332.68    5009  331.88  5016.6  332.68  5026.7  333.28
  5033.3  336.22  5040.9  342.13  5063.7  340.45  5090.3  340.18  5158.2   343.1
  5288.6  348.94    5374  358.19  5380.7  357.94  5394.9  360.38  5522.6  371.16
#Mann= 5 ,-1 , 0
  4380.8     .16       0  4865.3     .12       0  5008.2     .07       0
  5016.6     .12       0  5063.7     .16       0
Bank Sta=4865,5158.2
XS Rating Curve= 0 ,0
Exp/Cntr=0.3,0.1

Type RM Length L Ch R = 1 ,5478    ,448,448,448
BEGIN DESCRIPTION:
UNT 001 IN DRY CR WATERSHED 8.0
END DESCRIPTION:
XS GIS Cut Line= 3
        2901325.      6967675.03        2901375.        6967175.
      2901575.01      6966724.97
#Sta/Elev= 30
  4534.9  363.92  4615.3  358.32  4725.9  344.89    4779  341.31  4896.7  338.15
    4947  339.88  4967.1  339.85  4977.1  338.86  4984.7   334.4  4985.4  329.37
  4986.2  328.57  4993.2  328.57  4993.9  329.37  4997.2  331.44  5007.3  335.31
  5017.3   336.7  5069.6  338.37    5075   338.8  5080.8  341.31  5098.3  346.81
  5103.8  347.79  5150.3  353.16  5190.6  355.94  5202.3  358.19    5220     360
  5278.2  368.65    5324  373.42  5393.8  376.16  5453.3   379.6  5529.9  381.28
#Mann= 3 ,-1 , 0
  4534.9     .16       0  4985.4     .07       0  4993.9     .16       0
Bank Sta=4779,5080.8
XS Rating Curve= 0 ,0
Exp/Cntr=0.3,0.1

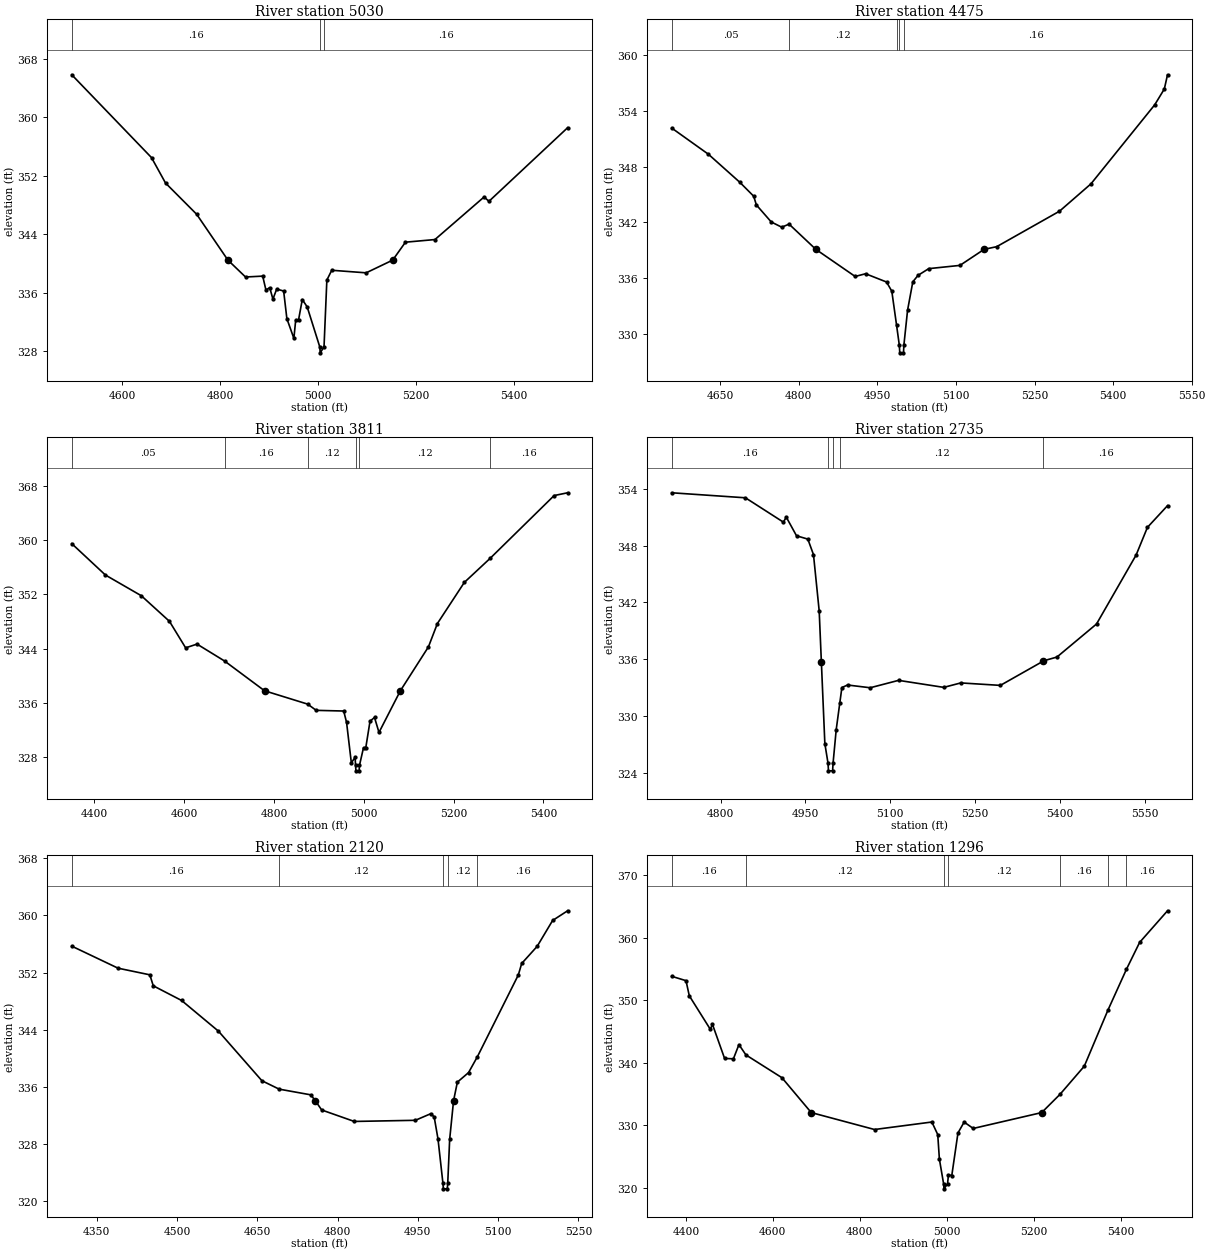
Type RM Length L Ch R = 1 ,5030    ,555,555,555
BEGIN DESCRIPTION:
UNT 001 IN DRY CR WATERSHED 7.0
END DESCRIPTION:
XS GIS Cut Line= 3
      2901374.97      6967775.03        2901675.        6967425.
        2901725.      6966874.99
#Sta/Elev= 30
  4496.4  365.81  4659.4  354.48    4688  351.01  4751.6  346.74  4815.5  340.47
  4851.5  338.16  4886.6  338.28  4893.2  336.38  4900.9   336.7  4907.5  335.14
  4915.2  336.51  4929.4  336.24    4936  332.46  4950.3  329.77  4954.1  332.31
  4959.9  332.31  4967.5  335.08  4977.5  334.07  5003.3  328.59  5004.1  327.79
  5011.9  328.59  5017.7  337.74  5027.7  339.08    5098  338.73  5152.3  340.47
  5178.3  342.92  5238.6  343.28    5339   349.1    5349  348.51  5509.7  358.57
#Mann= 3 ,-1 , 0
  4496.4     .16       0  5003.3     .07       0  5011.9     .16       0
Bank Sta=4815.5,5152.3
XS Rating Curve= 0 ,0
Exp/Cntr=0.3,0.1

Type RM Length L Ch R = 1 ,4475    ,664,664,664
BEGIN DESCRIPTION:
UNT 001 IN DRY CR WATERSHED 6.0
END DESCRIPTION:
XS GIS Cut Line= 3
        2902025.      6967775.03      2902011.01      6967332.65
      2901999.36      6966828.89
#Sta/Elev= 30
  4557.4  352.15  4627.5  349.33  4687.5  346.31    4714  344.81    4719  343.88
  4747.5  342.04  4767.5  341.48  4781.5  341.81  4832.5   339.1  4907.6  336.18
  4927.6  336.47  4967.6  335.58  4977.6  334.59  4986.6  330.97    4992  328.76
  4992.8  327.96  4999.9  327.96  5000.6  328.76  5007.7  332.55  5017.7   335.6
  5027.7   336.3  5048.1  337.02  5107.7  337.37  5153.9   339.1  5177.7  339.38
  5297.7   343.2  5357.7  346.14  5479.5  354.65  5497.8  356.35  5503.9  357.88
#Mann= 5 ,-1 , 0
  4557.4     .05       0  4781.5     .12       0  4986.6     .16       0
    4992     .07       0  5000.6     .16       0
Bank Sta=4832.5,5153.9
XS Rating Curve= 0 ,0
Exp/Cntr=0.3,0.1

Type RM Length L Ch R = 1 ,3811    ,1076,1076,1076
BEGIN DESCRIPTION:
UNT 001 IN DRY CR WATERSHED 5.0
END DESCRIPTION:
XS GIS Cut Line= 3
      2902194.65      6968090.69      2902415.51      6967478.94
        2902425.      6967025.03
#Sta/Elev= 30
  4349.6  359.48  4424.5  354.85  4504.5  351.79  4567.2  348.01  4603.2   344.1
  4628.6  344.65    4690  342.15    4779  337.76    4875  335.79    4894  334.87
  4955.3  334.77  4961.7  333.08  4972.3  327.12  4980.7  327.94  4981.7  326.74
  4982.5  325.94  4989.6  325.94  4990.4  326.74  4999.4  329.36  5004.5  329.36
  5013.9  333.27  5023.9  333.82  5033.9  331.61  5081.5  337.76    5144  344.24
    5164  347.69    5224  353.76  5281.3   357.3    5424  366.58    5454  366.99
#Mann= 6 ,-1 , 0
  4349.6     .05       0    4690     .16       0    4875     .12       0
  4981.7     .07       0  4990.4     .12       0  5281.3     .16       0
Bank Sta=4779,5081.5
XS Rating Curve= 0 ,0
Exp/Cntr=0.3,0.1

Type RM Length L Ch R = 1 ,2735    ,615,615,615
BEGIN DESCRIPTION:
UNT 001 IN DRY CR WATERSHED 4.0
END DESCRIPTION:
XS GIS Cut Line= 3
        2902875.      6967925.04      2902902.11      6967565.55
      2902893.44      6967049.53
#Sta/Elev= 30
  4713.6  353.58    4844  353.05  4911.1  350.48  4916.2  351.01  4934.3  349.04
  4954.3  348.69  4964.3  347.05  4974.4   341.1  4978.2  335.77  4984.4   327.1
    4990  325.03  4990.8  324.23  4998.1  324.23  4998.9  325.03  5004.5  328.59
  5010.9  331.43  5014.5  333.02  5024.5  333.29  5064.6     333  5114.7  333.78
  5194.6  333.04  5224.7  333.51  5294.7  333.25  5369.6  335.78  5370.9  335.84
  5394.7  336.24  5464.7  339.73  5534.7  347.01  5554.7  349.93  5590.2  352.22
#Mann= 5 ,-1 , 0
  4713.6     .16       0    4990     .07       0  4998.9     .16       0
  5010.9     .12       0  5370.9     .16       0
Bank Sta=4978.2,5369.6
XS Rating Curve= 0 ,0
Exp/Cntr=0.3,0.1

Type RM Length L Ch R = 1 ,2120    ,824,824,824
BEGIN DESCRIPTION:
UNT 001 IN DRY CR WATERSHED 3.0
END DESCRIPTION:
XS GIS Cut Line= 3
        2903325.      6967874.98      2903218.95      6967270.41
        2903025.        6967025.
#Sta/Elev= 30
  4303.3   355.7  4389.8  352.61  4449.2  351.68  4455.6  350.14  4508.6  348.08
  4577.4  343.78  4658.6  336.83  4690.8  335.65    4750  334.85  4758.3  334.04
  4770.3  332.73  4831.2  331.12  4945.4  331.28  4974.3  332.21  4980.6  331.74
  4987.7  328.66  4996.9  322.47  4997.8  321.67  5005.1  321.67  5005.9  322.47
  5009.5  328.61  5016.8  334.04  5023.9  336.63  5044.8  337.97  5061.5  340.22
  5137.8  351.66  5144.1  353.27    5173  355.67  5201.9   359.3  5229.9  360.66
#Mann= 5 ,-1 , 0
  4303.3     .16       0  4690.8     .12       0  4996.9     .07       0
  5005.9     .12       0  5061.5     .16       0
Bank Sta=4758.3,5016.8
XS Rating Curve= 0 ,0
Exp/Cntr=0.3,0.1

Type RM Length L Ch R = 1 ,1296    ,1189,1189,1189
BEGIN DESCRIPTION:
UNT 001 IN DRY CR WATERSHED 2.0
END DESCRIPTION:
XS GIS Cut Line= 3
        2903575.      6967774.99        2903675.        6967175.
      2903324.98      6966774.98
#Sta/Elev= 30
  4367.5  353.86  4400.4  353.16    4408  350.74  4456.2  345.39  4461.3  346.16
  4489.1  340.72  4509.4  340.66  4522.1  342.93  4538.2  341.28  4620.9  337.64
  4688.3  332.06  4833.8  329.35  4965.6  330.55  4979.1  328.54  4982.9  324.61
  4992.6  320.66  4993.5  319.86  5001.6  320.66  5003.8  322.11  5011.4  321.99
  5025.6   328.8  5039.8  330.54  5060.7  329.52  5218.1  332.06  5260.2  334.98
    5316  339.48  5370.3  348.44    5413     355  5443.2  359.28  5507.3  364.34
#Mann= 7 ,-1 , 0
  4367.5     .16       0  4538.2     .12       0  4992.6     .07       0
  5001.6     .12       0  5260.2     .16       0  5370.3     .12       0
    5413     .16       0
Bank Sta=4688.3,5218.1
XS Rating Curve= 0 ,0
Exp/Cntr=0.3,0.1