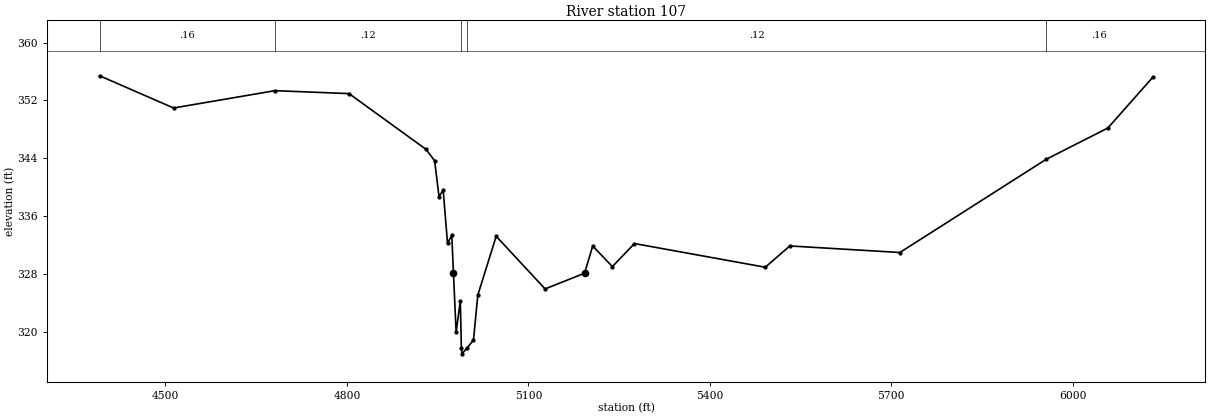
HEC-RAS study UNT 001 IN DRY CR WATERSHED.prj: UNT 001 IN DRY CR WATERSHED Base Level Engineering

--- UNT 001 IN DRY CR WATERSHED.g01 (geometry) --- (continued)

Type RM Length L Ch R = 1 ,107     ,0,0,0
BEGIN DESCRIPTION:
UNT 001 IN DRY CR WATERSHED 1.0
END DESCRIPTION:
XS GIS Cut Line= 3
      2903726.76      6968129.78      2904148.95      6967691.16
      2904317.04      6966571.61
#Sta/Elev= 30
  4391.2  355.42  4513.5  350.96  4681.2  353.36  4803.5  352.95  4930.8  345.23
    4945  343.65  4952.2  338.69  4959.1  339.59  4966.3  332.21  4973.3  333.35
  4976.1  328.08  4980.5  319.91  4987.4  324.22  4989.2  317.72  4990.1  316.92
  4998.5  317.72  5009.2  318.83  5016.3  325.03  5046.7   333.2  5127.6  325.91
  5192.8  328.08  5206.3  331.85  5238.8     329  5275.3  332.19  5491.6  328.91
  5532.1  331.86  5714.1  330.95  5955.8  343.85  6057.9  348.19  6132.1  355.21
#Mann= 5 ,-1 , 0
  4391.2     .16       0  4681.2     .12       0  4989.2     .07       0
  4998.5     .12       0  5955.8     .16       0
Bank Sta=4976.1,5192.8
XS Rating Curve= 0 ,0
Exp/Cntr=0.3,0.1
LCMann Table=0

Chan Stop Cuts=-1
Use User Specified Reach Order=0
Composite Channel Slope=5