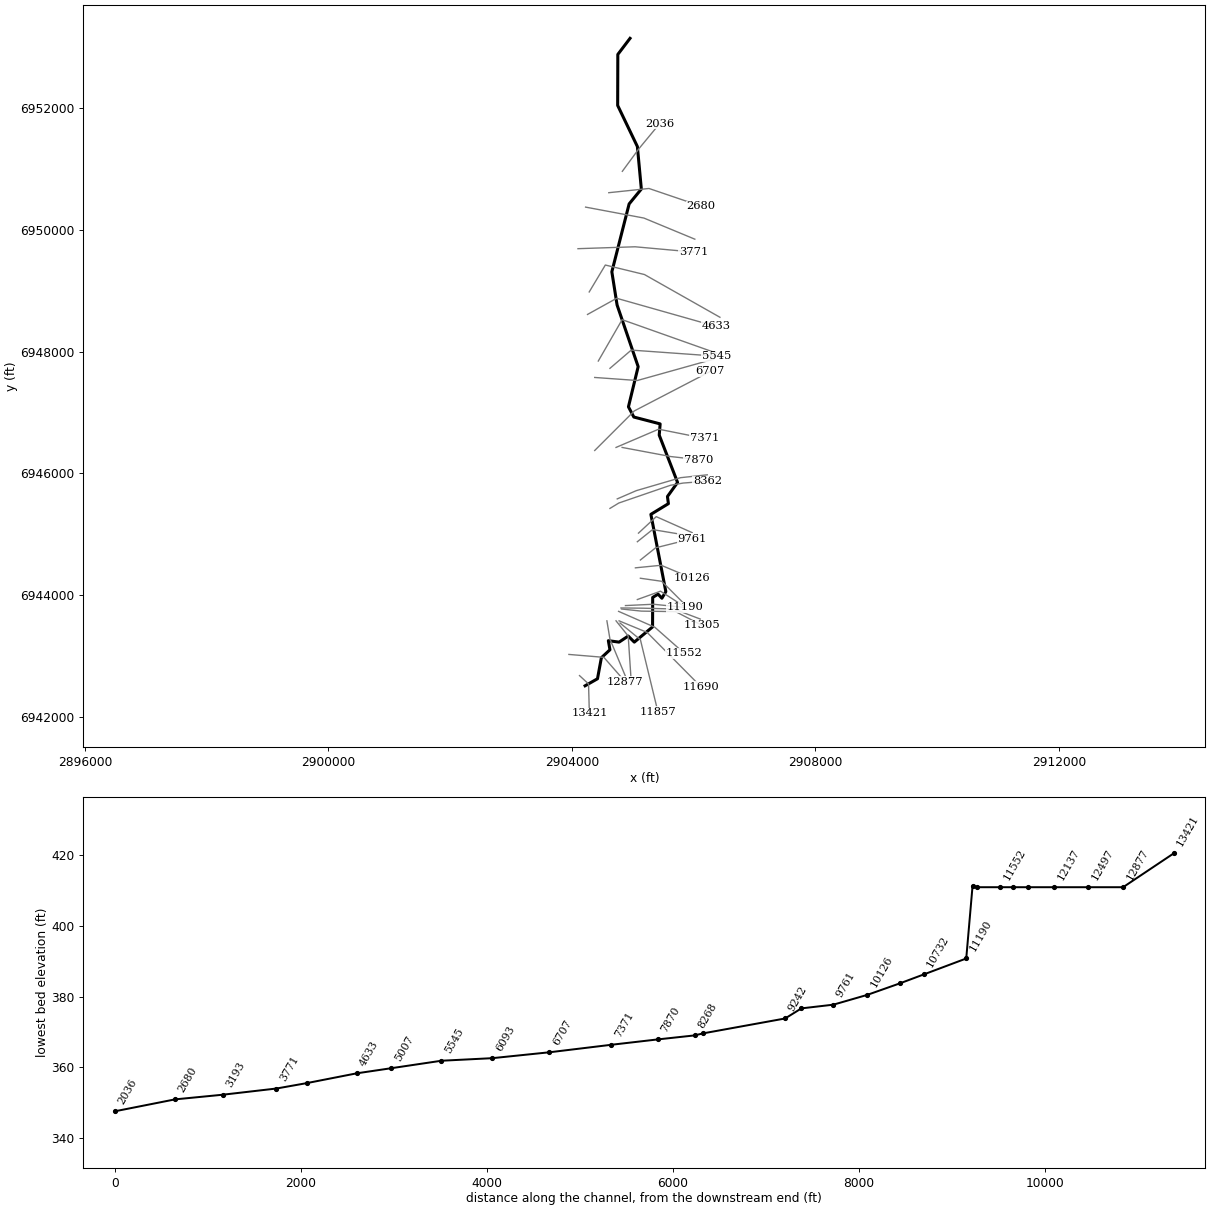
--- UNT 002 IN DRY CR WATERSHED.prj (project) ---

Proj Title=UNT 002 IN DRY CR WATERSHED Base Level Engineering
Current Plan=p01
Default Exp/Contr=0.3,0.1
English Units
Geom File=g01
Flow File=f01
Plan File=p01
BEGIN DESCRIPTION:
UNT 002 IN DRY CR WATERSHED
END DESCRIPTION:

--- UNT 002 IN DRY CR WATERSHED.p01 (plan) ---

Plan Title=Multiple Run
Short Identifier=Multiple
Geom File=g01
Flow File=f01
Subcritical Flow
K Sum by GR= 0
Std Step Tol= 0.01
Critical Tol= 0.01
Num of Std Step Trials= 20
Max Error Tol= 0.3
Flow Tol Ratio= 0.001
Split Flow NTrial= 30
Split Flow Tol= 0.02
Split Flow Ratio= 0.02
Log Output Level= 0
Friction Slope Method= 1
Unsteady Friction Slope Method= 2
Unsteady Bridges Friction Slope Method= 1
Parabolic Critical Depth
Global Vel Dist=  1 , 1 , 1
Global Log Level= 0
CheckData=True
Encroach Param= -1, 0, 0, 0
BEGIN DESCRIPTION:
Multiple Run
END DESCRIPTION:

--- UNT 002 IN DRY CR WATERSHED.f01 (steady flow) ---

Flow Title=Multiple
Program Version=5.07
Number of Profiles= 7
Profile Names=10-year,25-year,50-year,1pct_min,100-year,1pct_plu,500-year
River Rch & RM=UNT 002 IN DRY C,Reach-1         ,13421
     420     560     674     404     807    1609    1156
River Rch & RM=UNT 002 IN DRY C,Reach-1         ,9761
     726     994    1215     739    1475    2943    2176
River Rch & RM=UNT 002 IN DRY C,Reach-1         ,6707
    1029    1430    1768    1085    2166    4321    3255
River Rch & RM=UNT 002 IN DRY C,Reach-1         ,3771
    1183    1654    2052    1264    2522    5032    3817
Boundary for River Rch & Prof#=UNT 002 IN DRY C,Reach-1         , 1
Up Type= 0
Dn Type= 3
Dn Slope=0.005
Boundary for River Rch & Prof#=UNT 002 IN DRY C,Reach-1         , 2
Up Type= 0
Dn Type= 3
Dn Slope=0.005
Boundary for River Rch & Prof#=UNT 002 IN DRY C,Reach-1         , 3
Up Type= 0
Dn Type= 3
Dn Slope=0.005
Boundary for River Rch & Prof#=UNT 002 IN DRY C,Reach-1         , 4
Up Type= 0
Dn Type= 3
Dn Slope=0.005
Boundary for River Rch & Prof#=UNT 002 IN DRY C,Reach-1         , 5
Up Type= 0
Dn Type= 3
Dn Slope=0.005
Boundary for River Rch & Prof#=UNT 002 IN DRY C,Reach-1         , 6
Up Type= 0
Dn Type= 3
Dn Slope=0.005
Boundary for River Rch & Prof#=UNT 002 IN DRY C,Reach-1         , 7
Up Type= 0
Dn Type= 3
Dn Slope=0.005
DSS Import GetInterval= 0
DSS Import GetPeak= 0
DSS Import FillOption= 0

--- UNT 002 IN DRY CR WATERSHED.g01 (geometry) ---

Geom Title=Existing Conditions

River Reach=UNT 002 IN DRY C,Reach-1
Reach XY= 30
      2904216.83      6942507.29      2904420.43      6942622.95
      2904484.06      6942968.20      2904625.00      6943099.35
      2904598.83      6943248.83      2904775.00      6943225.00
      2904925.00      6943325.00      2905025.00      6943225.00
      2905325.00      6943475.00      2905327.11      6943959.85
      2905415.34      6944013.68      2905478.38      6943946.55
      2905543.14      6944055.28      2905297.36      6945325.17
      2905585.30      6945500.97      2905569.47      6945618.20
      2905735.81      6945849.68      2905434.48      6946627.18
      2905449.61      6946811.85      2905017.55      6946924.57
      2904928.77      6947092.52      2905088.58      6947752.88
      2904742.22      6948765.90      2904656.28      6949311.47
      2904940.14      6950427.36      2905140.66      6950672.15
      2905075.59      6951370.71      2904751.77      6952046.10
      2904754.37      6952884.64      2904954.89      6953148.96

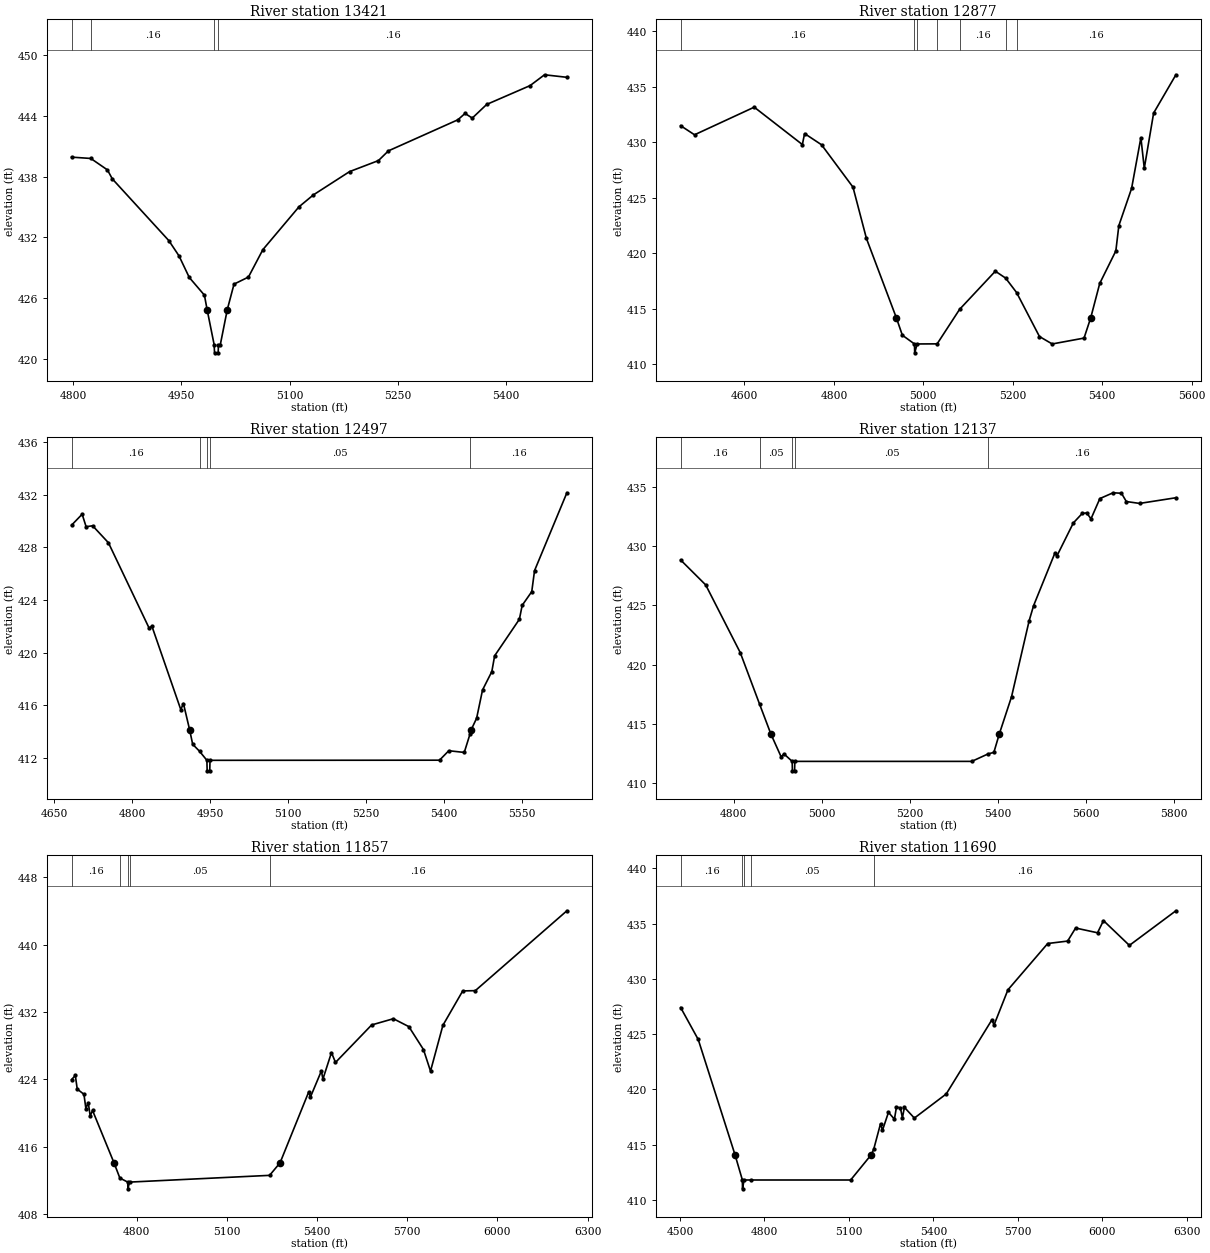
Type RM Length L Ch R = 1,13421,544,544,544
BEGIN DESCRIPTION:
UNT 002 IN DRY CR WATERSHED 27.0
END DESCRIPTION:
XS GIS Cut Line= 3
      2904125.00      6942675.00      2904273.47      6942537.88
      2904286.89      6942053.97
#Sta/Elev= 30
  4797.9  439.93  4824.5  439.80  4847.5  438.67  4854.3  437.78  4932.6  431.68
  4946.7  430.17  4960.9  428.04  4981.9  426.29  4985.6  424.87  4995.4  421.39
  4995.9  420.59  5000.9  420.59  5001.4  421.39  5003.9  421.39  5013.6  424.87
  5022.9  427.38  5042.9  428.08  5062.9  430.79  5112.9  435.02  5132.9  436.20
  5183.0  438.50  5223.0  439.59  5236.8  440.55  5333.0  443.62  5343.0  444.25
  5353.0  443.79  5373.0  445.14  5433.1  447.00  5453.1  448.07  5484.1  447.82
#Mann=4,-1,0
  4797.9     0.1       0  4824.5    0.16       0  4995.4    0.07       0
  5001.4    0.16       0
Bank Sta=4985.6,5013.6
Exp/Cntr=0.3,0.1

Type RM Length L Ch R = 1,12877,380,380,380
BEGIN DESCRIPTION:
UNT 002 IN DRY CR WATERSHED 26.0
END DESCRIPTION:
XS GIS Cut Line= 3
      2903950.94      6943022.75      2904525.00      6942975.00
      2904874.97      6942575.03
#Sta/Elev= 30
  4457.3  431.49  4488.4  430.67  4621.9  433.16  4729.5  429.79  4734.5  430.78
  4772.4  429.77  4842.7  425.95  4872.8  421.32  4939.6  414.18  4953.1  412.60
  4980.2  411.81  4980.7  411.01  4986.2  411.81  5030.9  411.82  5081.1  414.93
  5161.0  418.37  5184.0  417.75  5208.5  416.45  5259.7  412.48  5288.2  411.81
  5359.4  412.34  5374.4  414.18  5394.5  417.27  5430.5  420.20  5437.2  422.48
  5465.7  425.83  5486.5  430.41  5494.1  427.65  5515.0  432.63  5564.8  436.08
#Mann=7,-1,0
  4457.3    0.16       0  4980.2    0.07       0  4986.2    0.16       0
  5030.9    0.05       0  5081.1    0.16       0  5184.0    0.05       0
  5208.5    0.16       0
Bank Sta=4939.6,5374.4
Exp/Cntr=0.3,0.1

Type RM Length L Ch R = 1,12497,360,360,360
BEGIN DESCRIPTION:
UNT 002 IN DRY CR WATERSHED 25.0
END DESCRIPTION:
XS GIS Cut Line= 3
      2904575.00      6943574.98      2904625.00      6943275.00
      2904874.99      6942675.02
#Sta/Elev= 30
  4683.0  429.70  4703.3  430.53  4710.9  429.58  4723.5  429.65  4753.9  428.36
  4832.5  421.85  4837.6  422.02  4893.3  415.67  4898.4  416.13  4910.3  414.14
  4916.2  413.03  4929.4  412.50  4943.6  411.81  4944.1  411.01  4949.1  411.01
  4949.6  411.81  5391.7  411.82  5409.6  412.54  5439.4  412.41  5450.8  413.85
  5452.8  414.14  5463.2  415.01  5474.6  417.16  5492.5  418.56  5497.9  419.76
  5545.6  422.54  5551.0  423.60  5569.4  424.64  5574.8  426.24  5637.1  432.16
#Mann=5,-1,0
  4683.0    0.16       0  4929.4    0.05       0  4943.6   0.033       0
  4949.6    0.05       0  5450.8    0.16       0
Bank Sta=4910.3,5452.8
Exp/Cntr=0.3,0.1

Type RM Length L Ch R = 1,12137,280,280,280
BEGIN DESCRIPTION:
UNT 002 IN DRY CR WATERSHED 24.0
END DESCRIPTION:
XS GIS Cut Line= 3
      2904724.97      6943575.03      2904925.00      6943325.00
      2904977.86      6942522.74
#Sta/Elev= 30
  4679.8  428.84  4736.7  426.73  4815.1  421.01  4859.2  416.63  4884.7  414.12
  4908.0  412.19  4914.4  412.44  4933.0  411.81  4933.5  411.01  4938.5  411.01
  4939.0  411.81  5340.7  411.81  5377.6  412.44  5390.8  412.57  5403.1  414.12
  5430.9  417.27  5471.0  423.72  5481.0  424.98  5529.2  429.41  5534.2  429.20
  5571.2  431.97  5591.3  432.77  5601.3  432.82  5611.3  432.32  5631.4  434.03
  5661.4  434.52  5680.4  434.48  5691.5  433.78  5721.6  433.62  5804.0  434.10
#Mann=5,-1,0
  4679.8    0.16       0  4859.2    0.05       0  4933.0   0.033       0
  4939.0    0.05       0  5377.6    0.16       0
Bank Sta=4884.7,5403.1
Exp/Cntr=0.3,0.1

Type RM Length L Ch R = 1,11857,167,167,167
BEGIN DESCRIPTION:
Mapping XS 0676d0ef
END DESCRIPTION:
XS GIS Cut Line= 3
      2904791.24      6943538.36      2905125.43      6943264.93
      2905411.89      6942084.39
#Sta/Elev= 30
  4584.1  423.98  4596.4  424.47  4602.8  422.85  4625.1  422.23  4631.5  420.54
  4639.4  421.24  4645.9  419.65  4653.6  420.32  4725.0  414.10  4744.5  412.29
  4770.7  411.81  4771.2  411.01  4776.7  411.81  5242.3  412.61  5277.1  414.10
  5372.7  422.54  5377.8  421.88  5414.5  425.00  5419.6  424.04  5448.0  427.18
  5461.4  426.01  5581.6  430.46  5653.8  431.20  5705.3  430.26  5753.9  427.54
  5777.3  424.98  5818.5  430.42  5884.4  434.50  5926.2  434.53  6230.7  444.01
#Mann=5,-1,0
  4584.1    0.16       0  4744.5    0.05       0  4770.7   0.033       0
  4776.7    0.05       0  5242.3    0.16       0
Bank Sta=4725,5277.1
Exp/Cntr=0.3,0.1

Type RM Length L Ch R = 1,11690,138,138,138
BEGIN DESCRIPTION:
UNT 002 IN DRY CR WATERSHED 23.0
END DESCRIPTION:
XS GIS Cut Line= 3
      2904775.00      6943575.00      2905235.20      6943385.20
      2906122.73      6942489.00
#Sta/Elev= 30
  4502.2  427.41  4564.7  424.52  4695.4  414.09  4721.5  411.81  4722.0  411.01
  4727.5  411.81  4752.0  411.81  5106.1  411.81  5179.1  414.09  5188.0  414.59
  5212.1  416.89  5219.2  416.31  5240.4  417.93  5261.6  417.31  5268.7  418.40
  5282.8  418.34  5289.9  417.43  5297.0  418.38  5332.4  417.41  5445.5  419.59
  5608.1  426.31  5615.2  425.82  5664.7  429.01  5806.1  433.20  5876.8  433.42
  5905.1  434.60  5982.9  434.17  6004.1  435.27  6096.1  433.03  6261.3  436.16
#Mann=5,-1,0
  4502.2    0.16       0  4721.5   0.033       0  4727.5    0.16       0
  4752.0    0.05       0  5188.0    0.16       0
Bank Sta=4695.4,5179.1
Exp/Cntr=0.3,0.1

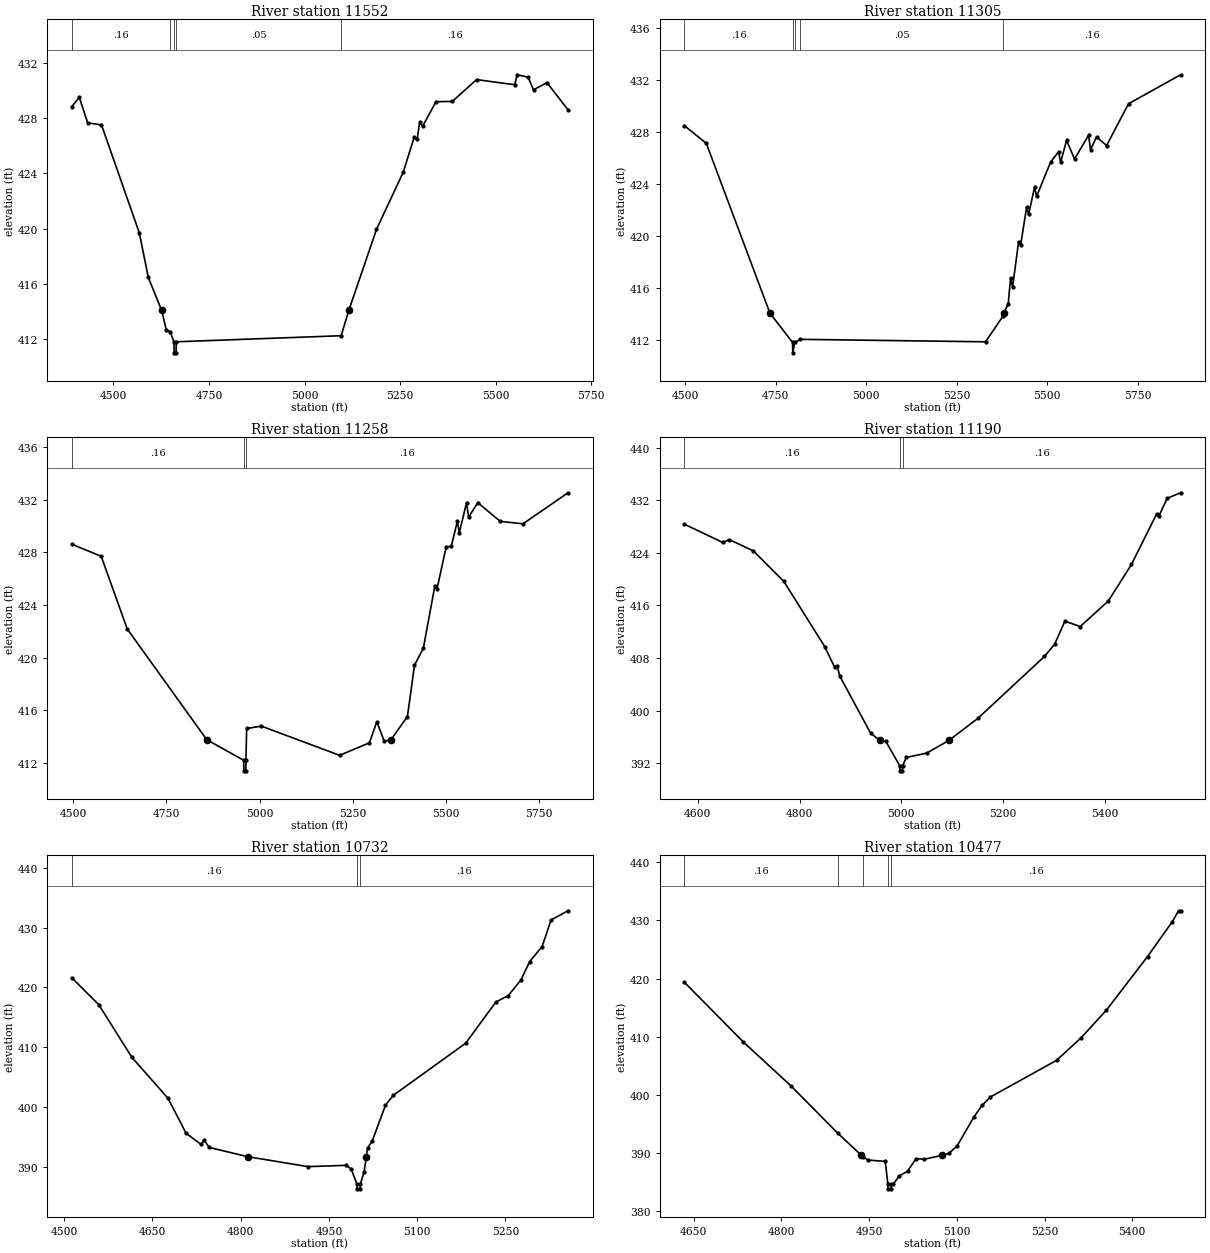
Type RM Length L Ch R = 1,11552,247,247,247
BEGIN DESCRIPTION:
Mapping XS c655613d
END DESCRIPTION:
XS GIS Cut Line= 3
      2904767.02      6943730.42      2905361.62      6943470.01
      2905847.72      6943040.33
#Sta/Elev= 30
  4391.2  428.84  4410.8  429.52  4432.7  427.67  4468.9  427.52  4567.9  419.69
  4591.3  416.47  4626.3  414.08  4638.1  412.69  4648.3  412.54  4658.4  411.81
  4658.9  411.01  4663.9  411.01  4664.4  411.81  5095.7  412.25  5115.7  414.08
  5188.1  419.95  5258.4  424.11  5286.8  426.64  5294.4  426.48  5301.1  427.71
  5308.6  427.41  5343.7  429.20  5386.4  429.22  5450.0  430.80  5549.5  430.43
  5556.2  431.15  5584.6  430.98  5598.9  430.06  5634.0  430.58  5689.1  428.61
#Mann=5,-1,0
  4391.2    0.16       0  4648.3    0.05       0  4658.4   0.033       0
  4664.4    0.05       0  5095.7    0.16       0
Bank Sta=4626.3,5115.7
Exp/Cntr=0.3,0.1

Type RM Length L Ch R = 1,11305,47,47,47
BEGIN DESCRIPTION:
Mapping XS b95eaa13
END DESCRIPTION:
XS GIS Cut Line= 4
      2904814.70      6943769.49      2905140.26      6943734.77
      2905704.50      6943726.09      2906129.84      6943504.74
#Sta/Elev= 30
  4497.2  428.51  4557.8  427.15  4733.6  414.07  4796.2  411.81  4796.7  411.01
  4802.2  411.81  4817.8  412.05  5329.4  411.86  5377.7  413.84  5380.2  414.07
  5392.0  414.79  5398.6  416.74  5404.2  416.10  5420.7  419.56  5426.3  419.30
  5442.8  422.21  5448.4  421.68  5464.9  423.77  5470.6  423.07  5509.1  425.70
  5531.2  426.50  5536.9  425.68  5553.3  427.38  5575.4  425.94  5614.0  427.77
  5619.6  426.67  5636.1  427.64  5663.9  426.98  5724.5  430.20  5868.4  432.43
#Mann=5,-1,0
  4497.2    0.16       0  4796.2   0.033       0  4802.2    0.16       0
  4817.8    0.05       0  5377.7    0.16       0
Bank Sta=4733.6,5380.2
Exp/Cntr=0.3,0.1

Type RM Length L Ch R = 1,11258,68,68,68
BEGIN DESCRIPTION:
Mapping XS 0fd683ec
END DESCRIPTION:
XS GIS Cut Line= 4
      2904806.02      6943786.85      2905174.98      6943782.51
      2905674.12      6943769.49      2906108.14      6943604.56
#Sta/Elev= 30
  4495.8  428.63  4574.8  427.71  4644.8  422.18  4858.2  413.77  4957.4  412.20
  4957.9  411.40  4962.9  411.40  4963.4  412.20  4965.4  414.62  5004.9  414.80
  5214.9  412.58  5295.0  413.53  5315.0  415.13  5335.0  413.64  5353.1  413.77
  5397.1  415.53  5416.1  419.43  5439.9  420.73  5471.0  425.49  5476.3  425.19
  5501.1  428.42  5514.8  428.47  5531.2  430.36  5536.6  429.52  5556.0  431.80
  5561.3  430.68  5586.1  431.79  5646.3  430.37  5707.4  430.18  5828.4  432.54
#Mann=3,-1,0
  4495.8    0.16       0  4957.4    0.07       0  4963.4    0.16       0
Bank Sta=4858.2,5353.1
Exp/Cntr=0.3,0.1

Type RM Length L Ch R = 1,11190,458,458,458
BEGIN DESCRIPTION:
Mapping XS a65706fc
END DESCRIPTION:
XS GIS Cut Line= 3
      2904879.80      6943825.91      2905339.91      6943847.61
      2905851.05      6943795.63
#Sta/Elev= 30
  4573.9  428.37  4649.2  425.60  4662.4  426.02  4709.3  424.31  4769.3  419.65
  4849.4  409.74  4868.7  406.63  4873.7  406.82  4879.4  405.19  4939.5  396.56
  4957.7  395.45  4969.5  395.30  4996.6  391.61  4997.1  390.81  5002.1  390.81
  5002.6  391.61  5009.6  392.85  5049.7  393.51  5093.5  395.45  5150.2  398.80
  5280.9  408.23  5301.0  410.10  5321.1  413.60  5351.2  412.79  5406.4  416.68
  5451.8  422.25  5501.1  429.91  5506.1  429.68  5522.1  432.33  5548.3  433.16
#Mann=3,-1,0
  4573.9    0.16       0  4996.6    0.07       0  5002.6    0.16       0
Bank Sta=4957.7,5093.5
Exp/Cntr=0.3,0.1

Type RM Length L Ch R = 1,10732,255,255,255
BEGIN DESCRIPTION:
UNT 002 IN DRY CR WATERSHED 21.0
END DESCRIPTION:
XS GIS Cut Line= 3
      2905075.02      6943925.01      2905455.37      6944062.02
      2905825.02      6943824.99
#Sta/Elev= 30
  4513.0  421.61  4559.0  417.09  4615.1  408.29  4676.5  401.44  4707.2  395.59
  4732.6  393.72  4737.9  394.42  4746.8  393.20  4812.2  391.66  4914.4  390.00
  4979.4  390.21  4988.1  389.56  4997.5  387.08  4998.0  386.28  5003.0  386.28
  5003.5  387.08  5009.8  389.10  5013.6  391.66  5015.7  393.11  5023.8  394.33
  5046.1  400.27  5059.4  401.93  5182.3  410.64  5233.8  417.55  5254.9  418.63
  5276.1  421.20  5291.3  424.33  5312.4  426.84  5327.6  431.29  5356.4  432.82
#Mann=3,-1,0
  4513.0    0.16       0  4997.5    0.07       0  5003.5    0.16       0
Bank Sta=4812.2,5013.6
Exp/Cntr=0.3,0.1

Type RM Length L Ch R = 1,10477,351,351,351
BEGIN DESCRIPTION:
UNT 002 IN DRY CR WATERSHED 20.0
END DESCRIPTION:
XS GIS Cut Line= 3
      2905124.99      6944275.00      2905475.00      6944225.00
      2905824.97      6943875.03
#Sta/Elev= 30
  4634.1  419.36  4735.1  409.05  4815.9  401.55  4896.2  393.37  4936.9  389.54
  4940.2  389.28  4947.3  388.74  4977.6  388.49  4982.1  384.57  4982.6  383.77
  4987.6  383.77  4988.1  384.57  4991.2  384.57  5001.8  386.01  5015.9  386.82
  5030.1  388.97  5044.2  388.86  5074.2  389.54  5086.7  389.88  5100.8  391.22
  5129.1  396.14  5143.2  398.15  5157.4  399.59  5270.5  405.91  5312.9  409.83
  5355.4  414.52  5426.1  423.79  5468.5  429.81  5479.1  431.67  5482.6  431.67
#Mann=5,-1,0
  4634.1    0.16       0  4896.2    0.12       0  4940.2    0.16       0
  4982.1    0.07       0  4988.1    0.16       0
Bank Sta=4936.9,5074.2
Exp/Cntr=0.3,0.1

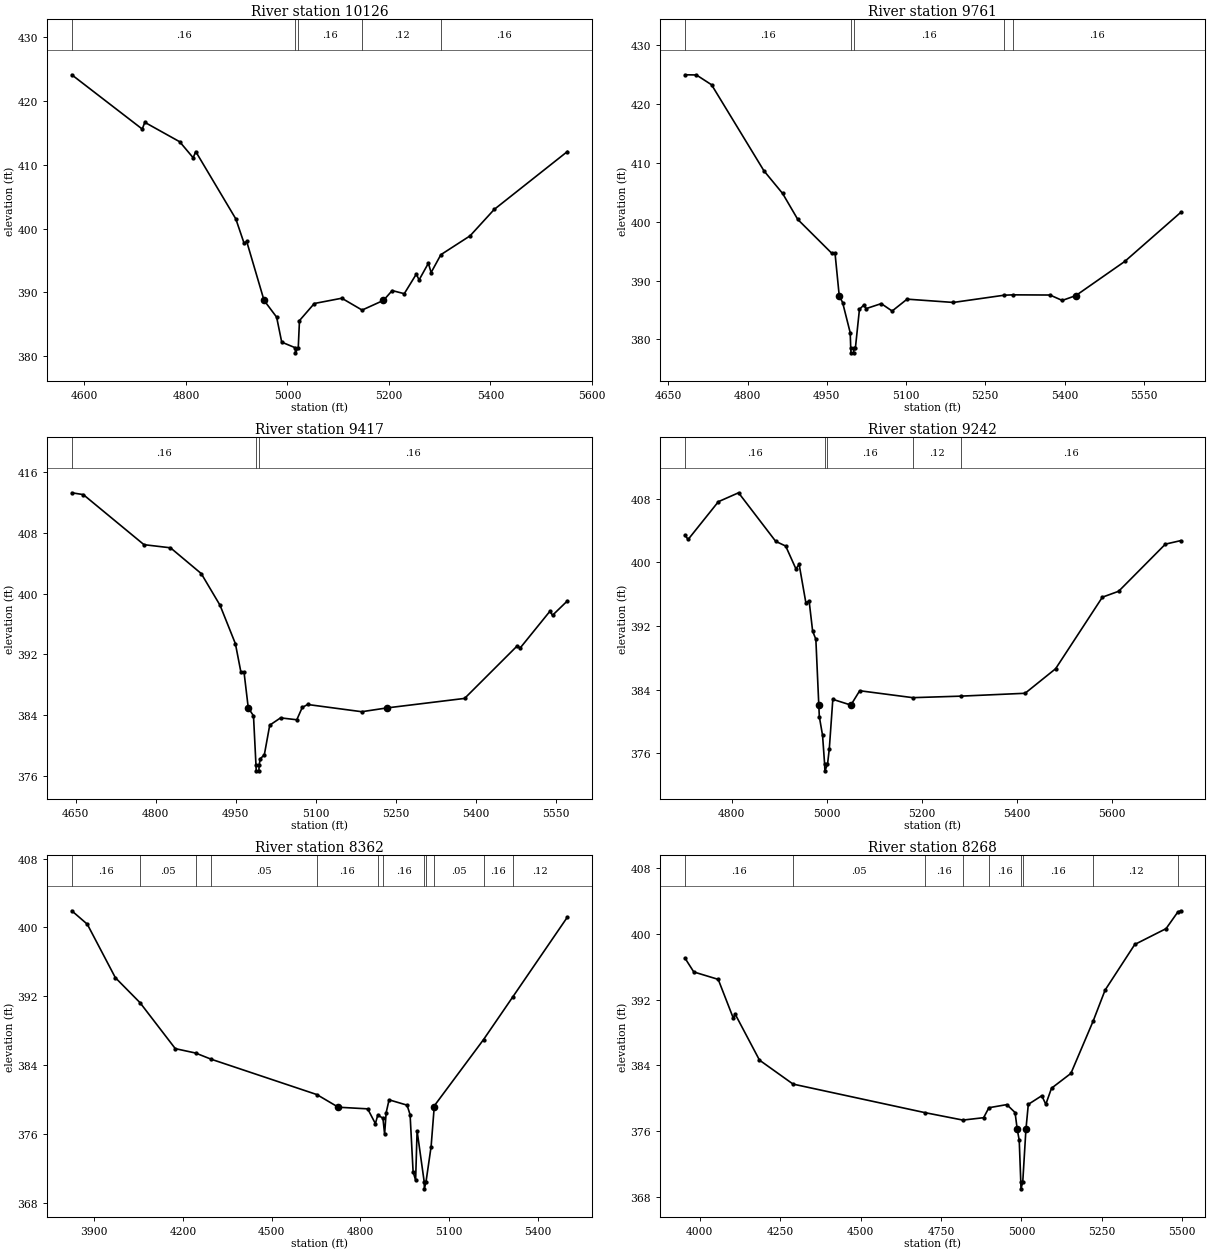
Type RM Length L Ch R = 1,10126,365,365,365
BEGIN DESCRIPTION:
UNT 002 IN DRY CR WATERSHED 19.0
END DESCRIPTION:
XS GIS Cut Line= 3
      2905043.34      6944446.00      2905466.22      6944488.39
      2905974.98      6944275.01
#Sta/Elev= 30
  4575.0  424.13  4713.9  415.61  4718.9  416.67  4787.7  413.62  4814.2  411.11
  4819.3  412.08  4898.3  401.51  4914.6  397.68  4919.7  397.98  4953.9  388.73
  4978.7  386.10  4988.7  382.18  5015.3  381.30  5015.8  380.50  5021.3  381.30
  5023.7  385.56  5052.9  388.24  5107.1  389.07  5147.1  387.21  5189.2  388.73
  5206.4  390.27  5230.2  389.78  5253.9  392.85  5259.4  391.94  5277.7  394.56
  5283.1  393.10  5302.3  395.90  5359.9  398.86  5407.4  403.00  5551.7  412.09
#Mann=5,-1,0
  4575.0    0.16       0  5015.3    0.07       0  5021.3    0.16       0
  5147.1    0.12       0  5302.3    0.16       0
Bank Sta=4953.9,5189.2
Exp/Cntr=0.3,0.1

Type RM Length L Ch R = 1,9761,344,344,344
BEGIN DESCRIPTION:
UNT 002 IN DRY CR WATERSHED 18.0
END DESCRIPTION:
XS GIS Cut Line= 3
      2905125.03      6944575.02      2905375.00      6944775.00
      2905975.01      6944925.00
#Sta/Elev= 30
  4681.3  424.95  4702.9  424.92  4731.7  423.25  4830.9  408.63  4866.2  404.79
  4895.0  400.37  4959.0  394.66  4965.4  394.69  4973.4  387.42  4979.8  386.27
  4994.2  381.14  4995.2  378.52  4995.7  377.72  5000.7  377.72  5001.2  378.52
  5004.0  378.52  5011.7  385.11  5019.5  385.80  5024.6  385.24  5053.0  386.08
  5073.6  384.82  5101.9  386.84  5189.5  386.28  5285.8  387.51  5302.7  387.57
  5372.5  387.54  5395.7  386.62  5421.4  387.44  5514.2  393.25  5619.9  401.56
#Mann=5,-1,0
  4681.3    0.16       0  4995.2    0.07       0  5001.2    0.16       0
  5285.8    0.12       0  5302.7    0.16       0
Bank Sta=4973.4,5421.4
Exp/Cntr=0.3,0.1

Type RM Length L Ch R = 1,9417,175,175,175
BEGIN DESCRIPTION:
UNT 002 IN DRY CR WATERSHED 17.0
END DESCRIPTION:
XS GIS Cut Line= 3
      2905075.01      6944875.01      2905325.00      6945075.00
      2905924.98      6944975.00
#Sta/Elev= 30
  4642.9  413.26  4664.5  413.02  4778.2  406.43  4827.8  406.02  4885.4  402.63
  4920.6  398.46  4949.4  393.40  4959.8  389.63  4965.6  389.63  4973.5  384.95
  4983.3  383.91  4987.9  377.47  4988.4  376.67  4993.4  376.67  4993.9  377.47
  4996.0  378.26  5003.6  378.78  5013.7  382.68  5034.0  383.64  5064.4  383.39
  5074.6  385.01  5084.7  385.40  5186.1  384.45  5233.2  384.95  5378.7  386.20
  5477.5  393.13  5482.6  392.82  5538.4  397.66  5543.4  397.14  5571.3  399.04
#Mann=3,-1,0
  4642.9    0.16       0  4987.9    0.07       0  4993.9    0.16       0
Bank Sta=4973.5,5233.2
Exp/Cntr=0.3,0.1

Type RM Length L Ch R = 1,9242,880,880,880
BEGIN DESCRIPTION:
UNT 002 IN DRY CR WATERSHED 16.0
END DESCRIPTION:
XS GIS Cut Line= 3
      2905093.81      6945016.57      2905385.49      6945287.42
      2905974.98      6945025.01
#Sta/Elev= 30
  4701.5  403.39  4708.2  402.87  4771.8  407.61  4814.3  408.73  4892.5  402.63
  4913.5  402.04  4935.0  399.18  4941.8  399.74  4956.0  394.91  4962.8  395.16
  4970.2  391.36  4977.0  390.33  4983.2  382.07  4984.3  380.61  4991.1  378.27
  4995.5  374.61  4996.0  373.81  5001.5  374.61  5005.3  376.57  5012.7  382.79
  5050.7  382.07  5069.3  383.87  5181.0  383.00  5281.8  383.19  5417.4  383.55
  5481.6  386.63  5580.1  395.62  5614.3  396.36  5712.7  402.28  5744.8  402.72
#Mann=5,-1,0
  4701.5    0.16       0  4995.5    0.07       0  5001.5    0.16       0
  5181.0    0.12       0  5281.8    0.16       0
Bank Sta=4983.2,5050.7
Exp/Cntr=0.3,0.1

Type RM Length L Ch R = 1,8362,94,94,94
BEGIN DESCRIPTION:
Mapping XS 5518916f
END DESCRIPTION:
XS GIS Cut Line= 5
      2904625.03      6945422.81      2904770.90      6945511.38
      2905619.86      6945803.04      2905828.19      6945839.50
      2906224.04      6945870.75
#Sta/Elev= 30
  3824.1  401.93  3876.6  400.37  3971.6  394.15  4054.9  391.25  4174.4  385.90
  4243.0  385.39  4295.8  384.67  4653.3  380.56  4725.9  379.09  4825.3  378.90
  4851.3  377.18  4859.4  378.18  4876.9  377.81  4882.5  375.95  4887.7  378.45
  4897.6  379.95  4958.5  379.33  4968.7  378.22  4978.9  371.58  4987.4  370.60
  4992.4  376.35  5016.5  370.40  5017.0  369.60  5022.5  370.40  5039.8  374.51
  5050.3  379.10  5050.8  379.26  5217.3  386.96  5316.4  391.93  5501.0  401.20
#Mann=12,-1,0
  3824.1    0.16       0  4054.9    0.05       0  4243.0    0.16       0
  4295.8    0.05       0  4653.3    0.16       0  4859.4    0.08       0
  4876.9    0.16       0  5016.5    0.07       0  5022.5    0.16       0
  5050.8    0.05       0  5217.3    0.16       0  5316.4    0.12       0
Bank Sta=4725.9,5050.3
Exp/Cntr=0.3,0.1

Type RM Length L Ch R = 1,8268,398,398,398
BEGIN DESCRIPTION:
Mapping XS 765805ec
END DESCRIPTION:
XS GIS Cut Line= 4
      2904744.87      6945579.09      2905057.36      6945714.50
      2905786.53      6945928.04      2906224.06      6945974.92
#Sta/Elev= 30
  3954.4  397.03  3981.8  395.35  4057.7  394.45  4104.6  389.74  4110.1  390.25
  4186.0  384.64  4290.4  381.73  4700.8  378.26  4818.1  377.36  4882.5  377.65
  4898.9  378.86  4954.6  379.24  4980.2  378.28  4987.1  376.22  4993.2  374.91
  4998.1  369.81  4998.6  369.01  5004.1  369.81  5014.0  376.22  5021.4  379.27
  5063.3  380.32  5075.8  379.28  5093.5  381.23  5153.8  383.03  5223.0  389.39
  5260.1  393.15  5352.3  398.69  5449.5  400.61  5485.7  402.61  5494.8  402.78
#Mann=9,-1,0
  3954.4    0.16       0  4290.4    0.05       0  4700.8    0.16       0
  4818.1    0.08       0  4898.9    0.16       0  4998.1    0.07       0
  5004.1    0.16       0  5223.0    0.12       0  5485.7    0.16       0
Bank Sta=4987.1,5014
Exp/Cntr=0.3,0.1

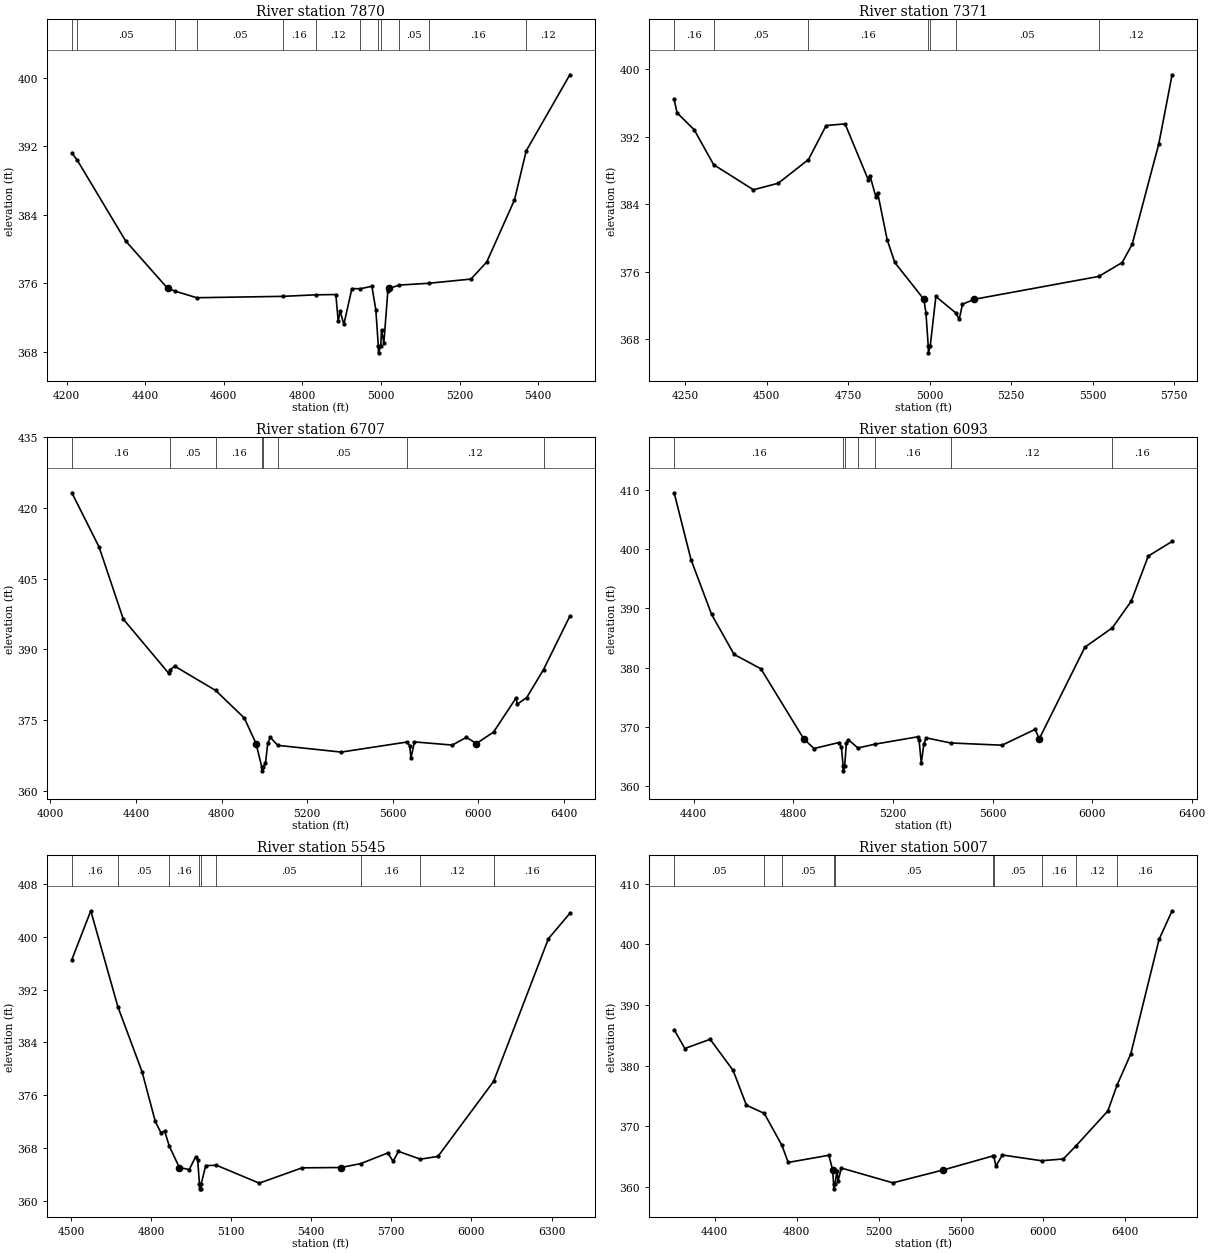
Type RM Length L Ch R = 1,7870,499,499,499
BEGIN DESCRIPTION:
UNT 002 IN DRY CR WATERSHED 14.0
END DESCRIPTION:
XS GIS Cut Line= 3
      2904825.01      6946425.00      2905625.00      6946275.00
      2906075.00      6946225.00
#Sta/Elev= 30
  4213.6  391.21  4227.5  390.37  4350.1  380.96  4457.1  375.41  4475.3  375.09
  4531.1  374.31  4749.9  374.47  4834.6  374.65  4885.1  374.68  4891.0  371.59
  4896.1  372.74  4905.4  371.19  4925.8  375.37  4947.6  375.36  4976.7  375.65
  4986.8  372.89  4993.1  368.67  4993.6  367.87  4999.2  368.67  5001.3  370.57
  5007.2  369.00  5017.4  375.12  5021.4  375.41  5046.7  375.79  5121.7  376.00
  5228.8  376.49  5269.0  378.49  5339.4  385.73  5369.4  391.48  5480.3  400.36
#Mann=12,-1,0
  4213.6    0.16       0  4227.5    0.05       0  4475.3    0.16       0
  4531.1    0.05       0  4749.9    0.16       0  4834.6    0.12       0
  4947.6    0.16       0  4993.1    0.07       0  4999.2    0.16       0
  5046.7    0.05       0  5121.7    0.16       0  5369.4    0.12       0
Bank Sta=4457.1,5021.4
Exp/Cntr=0.3,0.1

Type RM Length L Ch R = 1,7371,664,664,664
BEGIN DESCRIPTION:
UNT 002 IN DRY CR WATERSHED 13.0
END DESCRIPTION:
XS GIS Cut Line= 3
      2904725.02      6946425.01      2905425.00      6946725.00
      2906174.99      6946575.00
#Sta/Elev= 30
  4216.8  396.42  4225.8  394.83  4278.4  392.82  4337.9  388.68  4459.8  385.70
  4535.9  386.48  4628.6  389.29  4682.8  393.33  4740.8  393.52  4811.5  386.92
  4817.0  387.39  4835.1  384.87  4840.5  385.37  4869.6  379.80  4893.1  377.08
  4982.2  372.71  4988.6  371.11  4995.7  367.15  4996.2  366.35  5001.8  367.15
  5019.1  373.04  5080.6  371.07  5090.5  370.32  5100.7  372.12  5137.4  372.71
  5518.5  375.42  5590.2  377.07  5620.8  379.23  5702.4  391.15  5743.2  399.35
#Mann=7,-1,0
  4216.8    0.16       0  4337.9    0.05       0  4628.6    0.16       0
  4995.7    0.07       0  5001.8    0.16       0  5080.6    0.05       0
  5518.5    0.12       0
Bank Sta=4982.2,5137.4
Exp/Cntr=0.3,0.1

Type RM Length L Ch R = 1,6707,614,614,614
BEGIN DESCRIPTION:
double UNT 002 IN DRY CR WATERSHED 12.0
END DESCRIPTION:
XS GIS Cut Line= 3
      2904374.99      6946374.99      2905025.00      6947025.00
      2906274.96      6947674.98
#Sta/Elev= 30
  4100.3  423.24  4227.6  411.72  4340.7  396.43  4552.9  384.94  4560.9  385.71
  4581.1  386.44  4772.1  381.30  4906.4  375.45  4961.4  370.02  4988.2  365.03
  4988.7  364.23  4994.3  365.03  5005.4  365.82  5016.0  370.08  5027.8  371.35
  5062.9  369.64  5359.4  368.21  5667.8  370.35  5679.8  369.48  5685.4  366.93
  5701.9  370.37  5878.8  369.70  5945.1  371.34  5991.5  370.02  6072.1  372.47
  6177.0  379.70  6182.7  378.37  6226.9  379.79  6305.3  385.72  6428.4  397.05
#Mann=8,-1,0
  4100.3    0.16       0  4560.9    0.05       0  4772.1    0.16       0
  4988.2    0.07       0  4994.3    0.16       0  5062.9    0.05       0
  5667.8    0.12       0  6305.3    0.16       0
Bank Sta=4961.4,5991.5
Exp/Cntr=0.3,0.1

Type RM Length L Ch R = 1,6093,548,548,548
BEGIN DESCRIPTION:
double UNT 002 IN DRY CR WATERSHED 11.0
END DESCRIPTION:
XS GIS Cut Line= 3
      2904374.96      6947575.00      2905075.00      6947525.00
      2906325.00      6947875.00
#Sta/Elev= 30
  4321.3  409.53  4389.0  398.25  4471.7  388.99  4562.0  382.23  4669.7  379.80
  4841.5  367.99  4882.8  366.33  4983.0  367.34  4993.0  366.58  5000.0  363.36
  5000.5  362.56  5006.2  363.36  5013.1  367.33  5020.6  367.83  5059.4  366.42
  5128.4  367.07  5299.8  368.31  5305.0  367.71  5313.9  363.85  5324.3  367.13
  5333.9  368.13  5431.6  367.27  5638.0  366.89  5770.8  369.56  5787.9  367.99
  5971.1  383.45  6081.0  386.71  6157.3  391.23  6225.5  398.84  6321.2  401.31
#Mann=7,-1,0
  4321.3    0.16       0  5000.0    0.07       0  5006.2    0.16       0
  5059.4    0.12       0  5128.4    0.16       0  5431.6    0.12       0
  6081.0    0.16       0
Bank Sta=4841.5,5787.9
Exp/Cntr=0.3,0.1

Type RM Length L Ch R = 1,5545,538,538,538
BEGIN DESCRIPTION:
UNT 002 IN DRY CR WATERSHED 10.0
END DESCRIPTION:
XS GIS Cut Line= 3
      2904624.98      6947724.98      2904975.00      6948025.00
      2906375.03      6947925.00
#Sta/Elev= 30
  4503.7  396.55  4574.5  403.93  4676.1  389.38  4766.6  379.55  4816.0  372.03
  4836.8  370.35  4851.1  370.57  4868.6  368.28  4906.1  365.06  4943.3  364.75
  4967.2  366.70  4974.7  366.26  4981.3  362.63  4981.8  361.83  4987.7  361.83
  4988.2  362.63  5004.8  365.35  5045.1  365.40  5205.3  362.69  5365.7  365.01
  5511.6  365.06  5586.0  365.66  5686.5  367.26  5706.6  366.00  5726.6  367.50
  5808.6  366.32  5874.5  366.74  6083.1  378.12  6288.1  399.71  6368.3  403.54
#Mann=9,-1,0
  4503.7    0.16       0  4676.1    0.05       0  4868.6    0.16       0
  4981.3    0.07       0  4988.2    0.16       0  5045.1    0.05       0
  5586.0    0.16       0  5808.6    0.12       0  6083.1    0.16       0
Bank Sta=4906.1,5511.6
Exp/Cntr=0.3,0.1

Type RM Length L Ch R = 1,5007,374,374,374
BEGIN DESCRIPTION:
UNT 002 IN DRY CR WATERSHED 9.0
END DESCRIPTION:
XS GIS Cut Line= 3
      2904433.74      6947845.27      2904825.00      6948525.00
      2906375.01      6947974.99
#Sta/Elev= 30
  4202.7  385.94  4254.8  382.83  4378.4  384.35  4490.5  379.22  4555.2  373.49
  4642.3  372.15  4728.6  366.87  4759.2  364.07  4957.5  365.25  4975.9  362.83
  4980.7  360.52  4981.2  359.72  4987.6  360.52  4997.1  362.73  5002.4  361.06
  5018.8  363.14  5269.6  360.71  5515.5  362.83  5758.8  365.15  5761.6  365.15
  5772.2  363.46  5804.0  365.29  5994.8  364.35  6101.1  364.64  6163.0  366.80
  6318.2  372.54  6363.2  376.80  6430.1  381.93  6568.0  400.79  6631.7  405.51
#Mann=10,-1,0
  4202.7    0.05       0  4642.3    0.16       0  4728.6    0.05       0
  4980.7    0.03       0  4987.6    0.05       0  5758.8    0.16       0
  5761.6    0.05       0  5994.8    0.16       0  6163.0    0.12       0
  6363.2    0.16       0
Bank Sta=4975.9,5515.5
Exp/Cntr=0.3,0.1

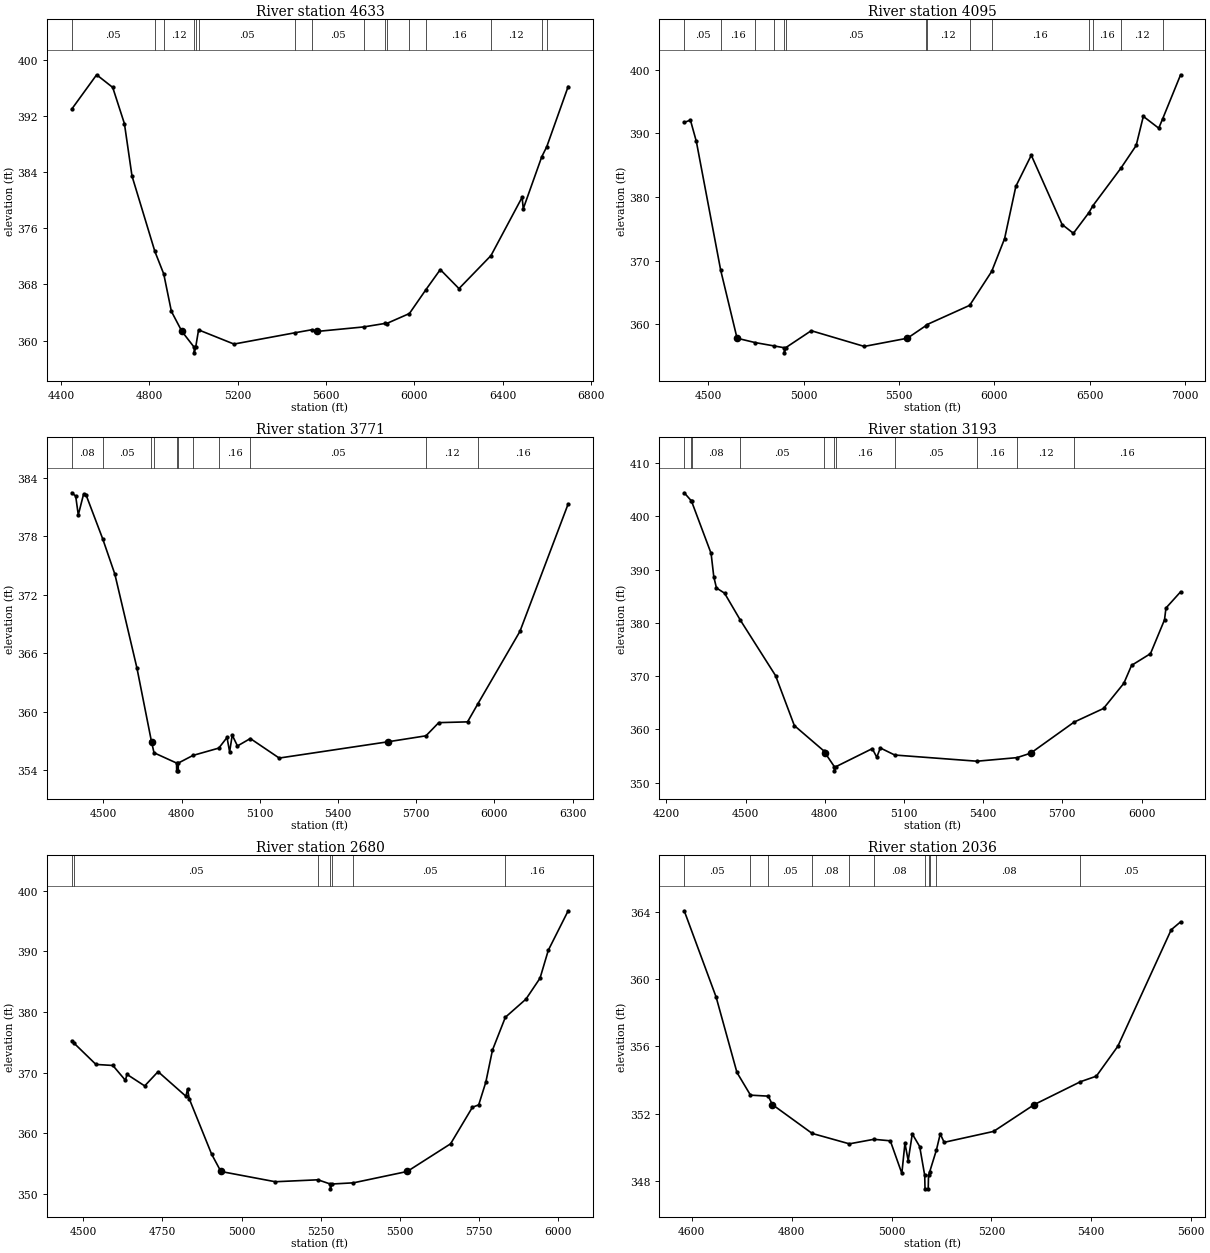
Type RM Length L Ch R = 1,4633,538,538,538
BEGIN DESCRIPTION:
Mapping XS 20ad2410
END DESCRIPTION:
XS GIS Cut Line= 3
      2904256.70      6948610.92      2904735.83      6948876.53
      2906370.61      6948413.17
#Sta/Elev= 30
  4449.0  392.99  4561.4  397.87  4634.2  396.07  4687.2  390.91  4721.5  383.45
  4825.1  372.70  4865.2  369.50  4899.8  364.17  4947.5  361.31  5002.9  359.06
  5003.4  358.26  5009.8  359.06  5022.9  361.53  5183.1  359.51  5459.3  361.12
  5535.5  361.55  5559.7  361.31  5770.1  361.95  5867.1  362.45  5873.7  362.43
  5977.3  363.86  6052.2  367.27  6117.1  370.12  6201.7  367.41  6346.7  372.12
  6487.5  380.42  6492.7  378.79  6576.4  386.19  6598.9  387.61  6696.0  396.20
#Mann=16,-1,0
  4449.0    0.05       0  4825.1    0.16       0  4865.2    0.12       0
  5002.9    0.07       0  5009.8    0.12       0  5022.9    0.05       0
  5459.3    0.16       0  5535.5    0.05       0  5770.1    0.16       0
  5867.1    0.05       0  5873.7    0.16       0  5977.3    0.12       0
  6052.2    0.16       0  6346.7    0.12       0  6576.4    0.16       0
  6598.9    0.12       0
Bank Sta=4947.5,5559.7
Exp/Cntr=0.3,0.1

Type RM Length L Ch R = 1,4095,324,324,324
BEGIN DESCRIPTION:
Mapping XS 09535918
END DESCRIPTION:
XS GIS Cut Line= 4
      2904284.46      6948980.44      2904549.20      6949423.11
      2905191.56      6949266.86      2906431.48      6948564.53
#Sta/Elev= 30
  4374.0  391.71  4406.4  392.09  4437.5  388.73  4565.2  368.47  4651.0  357.78
  4744.8  357.10  4842.2  356.58  4898.5  356.28  4899.0  355.48  4905.4  356.28
  5039.8  358.96  5317.7  356.49  5543.9  357.78  5641.1  359.76  5647.1  359.93
  5870.3  362.95  5985.6  368.28  6053.3  373.44  6112.4  381.67  6193.2  386.56
  6354.8  375.66  6414.0  374.28  6495.5  377.54  6516.5  378.63  6662.9  384.52
  6743.0  388.09  6780.5  392.67  6861.3  390.81  6881.8  392.28  6975.9  399.21
#Mann=14,-1,0
  4374.0    0.05       0  4565.2    0.16       0  4744.8    0.12       0
  4842.2    0.05       0  4898.5    0.03       0  4905.4    0.05       0
  5641.1    0.16       0  5647.1    0.12       0  5870.3     0.1       0
  5985.6    0.16       0  6495.5    0.12       0  6516.5    0.16       0
  6662.9    0.12       0  6881.8    0.16       0
Bank Sta=4651,5543.9
Exp/Cntr=0.3,0.1

Type RM Length L Ch R = 1,3771,578,578,578
BEGIN DESCRIPTION:
double UNT 002 IN DRY CR WATERSHED 7.0
END DESCRIPTION:
XS GIS Cut Line= 3
      2904100.07      6949691.69      2905037.57      6949722.94
      2905999.34      6949636.13
#Sta/Elev= 30
  4379.2  382.46  4394.1  382.12  4404.1  380.19  4424.2  382.30  4434.2  382.22
  4497.7  377.74  4544.2  374.13  4629.0  364.50  4684.5  357.00  4685.1  356.92
  4694.6  355.81  4780.9  354.76  4781.4  353.96  4787.3  353.96  4787.8  354.76
  4843.9  355.54  4942.9  356.29  4974.5  357.38  4984.5  355.90  4994.5  357.62
  5014.5  356.51  5063.9  357.27  5174.6  355.27  5590.0  356.93  5737.5  357.55
  5786.5  358.90  5897.0  358.98  5936.8  360.84  6097.8  368.25  6282.9  381.32
#Mann=11,-1,0
  4379.2    0.08       0  4497.7    0.05       0  4684.5    0.07       0
  4694.6    0.05       0  4780.9    0.07       0  4787.8    0.05       0
  4843.9    0.07       0  4942.9    0.16       0  5063.9    0.05       0
  5737.5    0.12       0  5936.8    0.16       0
Bank Sta=4685.1,5590
Exp/Cntr=0.3,0.1

Type RM Length L Ch R = 1,3193,513,513,513
BEGIN DESCRIPTION:
double UNT 002 IN DRY CR WATERSHED 6.0
END DESCRIPTION:
XS GIS Cut Line= 3
      2904224.95      6950375.01      2905182.53      6950195.16
      2906019.33      6949847.94
#Sta/Elev= 30
  4267.7  404.45  4294.9  402.92  4295.3  402.88  4369.5  393.06  4379.7  388.67
  4389.8  386.56  4420.4  385.59  4480.0  380.54  4613.7  370.09  4684.9  360.70
  4797.2  355.92  4801.9  355.52  4836.2  353.00  4836.7  352.20  4843.1  353.00
  4980.0  356.37  4997.2  354.76  5010.5  356.50  5065.2  355.17  5376.7  354.01
  5528.2  354.68  5580.0  355.52  5744.7  361.36  5856.0  363.92  5933.0  368.65
  5962.3  372.02  6033.9  374.22  6087.1  380.58  6092.5  382.79  6148.0  385.84
#Mann=11,-1,0
  4267.7    0.16       0  4294.9    0.05       0  4295.3    0.08       0
  4480.0    0.05       0  4797.2    0.16       0  4836.2    0.07       0
  4843.1    0.16       0  5065.2    0.05       0  5376.7    0.16       0
  5528.2    0.12       0  5744.7    0.16       0
Bank Sta=4801.9,5580
Exp/Cntr=0.3,0.1

Type RM Length L Ch R = 1,2680,644,644,644
BEGIN DESCRIPTION:
double UNT 002 IN DRY CR WATERSHED 5.0
END DESCRIPTION:
XS GIS Cut Line= 3
      2904606.12      6950611.82      2905265.87      6950681.27
      2906121.17      6950390.40
#Sta/Elev= 30
  4464.1  375.27  4470.4  374.92  4540.3  371.38  4593.7  371.21  4633.3  368.76
  4638.3  369.74  4694.2  367.84  4736.4  370.19  4824.4  366.13  4829.4  367.34
  4835.0  365.70  4905.4  356.60  4934.7  353.74  5106.5  352.05  5241.0  352.37
  5279.7  351.68  5280.2  350.88  5286.7  351.68  5353.0  351.87  5522.8  353.74
  5659.7  358.30  5728.6  364.32  5748.5  364.72  5770.9  368.45  5792.0  373.75
  5832.6  379.15  5897.6  382.14  5942.1  385.60  5968.2  390.20  6030.9  396.70
#Mann=7,-1,0
  4464.1    0.08       0  4470.4    0.05       0  5241.0    0.12       0
  5279.7    0.03       0  5286.7    0.12       0  5353.0    0.05       0
  5832.6    0.16       0
Bank Sta=4934.7,5522.8
Exp/Cntr=0.3,0.1

Type RM Length L Ch R = 1,2036,129,129,129
BEGIN DESCRIPTION:
double UNT 002 IN DRY CR WATERSHED 4.0
END DESCRIPTION:
XS GIS Cut Line= 3
      2904828.65      6950963.39      2905105.55      6951340.75
      2905440.71      6951746.08
#Sta/Elev= 30
  4584.9  364.08  4648.8  358.94  4690.5  354.45  4717.6  353.10  4753.3  353.04
  4761.3  352.54  4841.1  350.82  4915.6  350.20  4964.6  350.47  4997.6  350.38
  5020.7  348.44  5026.9  350.24  5033.4  349.20  5041.6  350.79  5056.4  350.04
  5066.5  348.32  5067.1  347.52  5073.5  347.52  5074.1  348.32  5076.1  348.50
  5089.8  349.82  5097.6  350.79  5105.4  350.29  5204.4  350.94  5286.0  352.54
  5378.4  353.90  5410.2  354.23  5453.2  356.01  5560.1  362.95  5578.9  363.42
#Mann=11,-1,0
  4584.9    0.05       0  4717.6    0.08       0  4753.3    0.05       0
  4841.1    0.08       0  4915.6    0.05       0  4964.6    0.08       0
  5066.5    0.07       0  5074.1    0.08       0  5076.1    0.16       0
  5089.8    0.08       0  5378.4    0.05       0
Bank Sta=4761.3,5286
Exp/Cntr=0.3,0.1