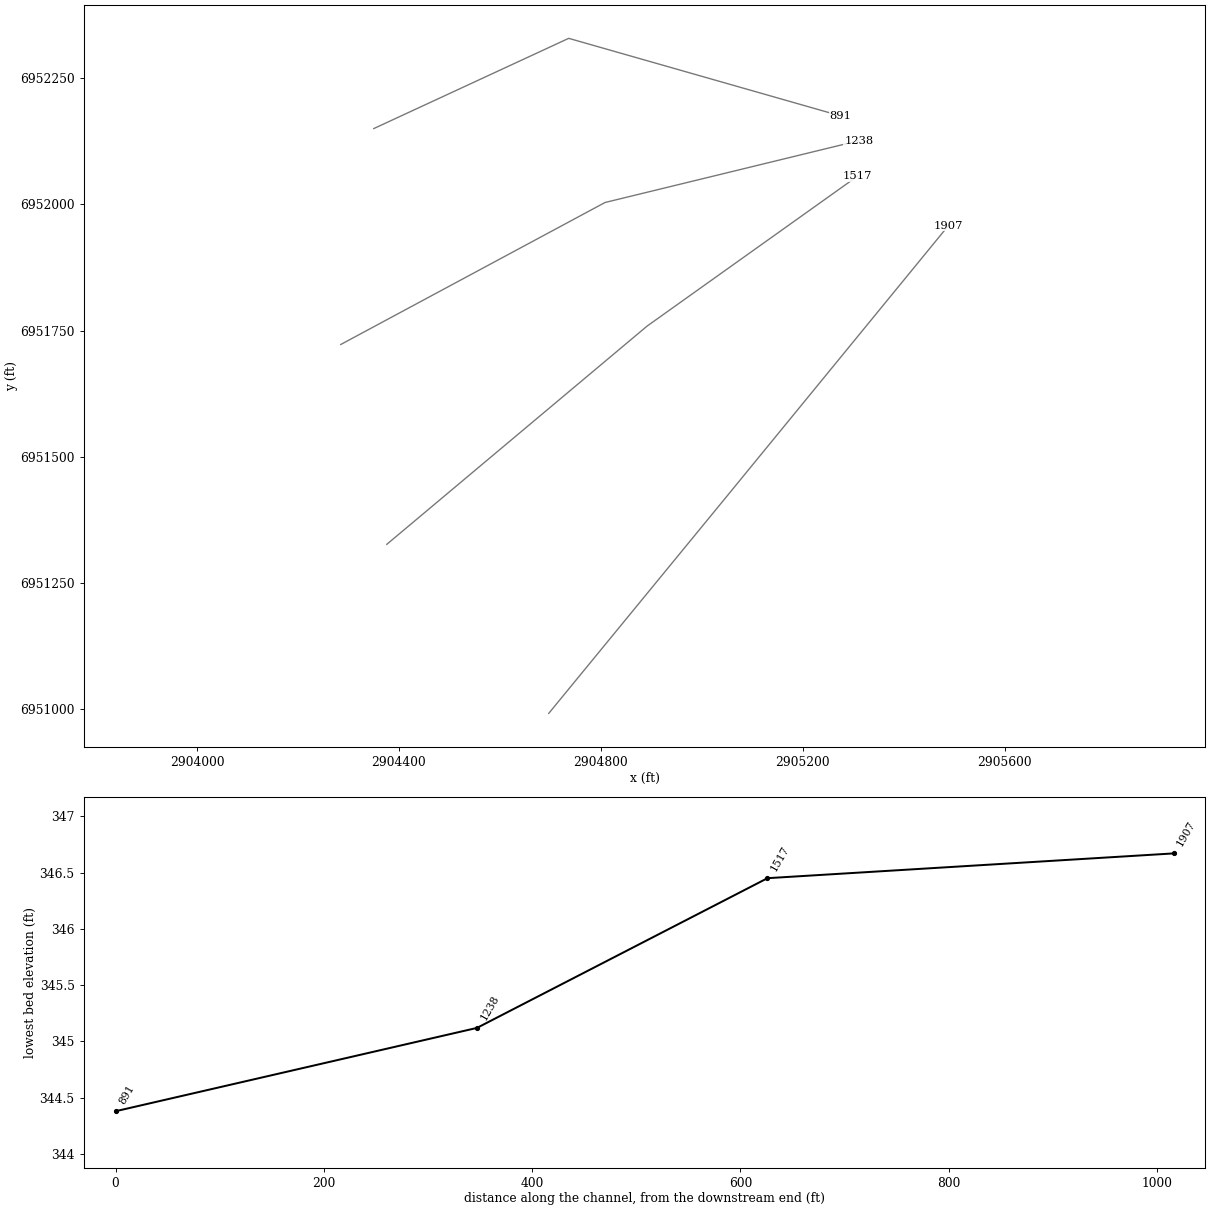
HEC-RAS study UNT 002 IN DRY CR WATERSHED.prj: UNT 002 IN DRY CR WATERSHED Base Level Engineering

--- UNT 002 IN DRY CR WATERSHED.g01 (geometry) --- (continued)

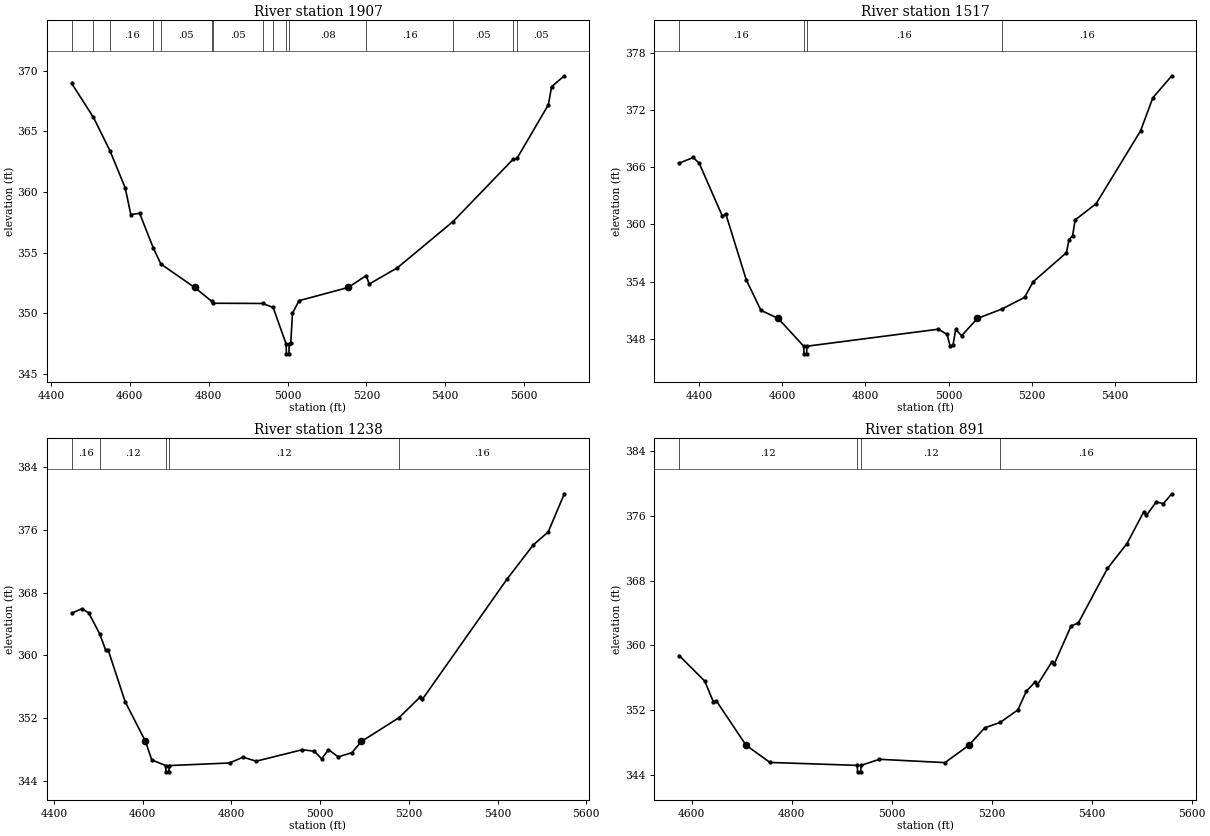
Type RM Length L Ch R = 1,1907,390,390,390
BEGIN DESCRIPTION:
Mapping XS 12e42922
END DESCRIPTION:
XS GIS Cut Line= 3
      2904696.60      6950991.69      2905053.37      6951426.58
      2905488.29      6951957.86
#Sta/Elev= 30
  4452.7  368.96  4508.1  366.15  4549.9  363.40  4588.5  360.35  4602.8  358.14
  4625.1  358.25  4659.9  355.38  4679.0  354.07  4764.6  352.14  4808.1  350.99
  4811.8  350.84  4937.1  350.82  4963.6  350.49  4996.6  347.47  4997.2  346.67
  5003.6  346.67  5004.2  347.47  5008.3  347.60  5012.6  350.01  5029.1  351.05
  5154.2  352.14  5199.6  353.12  5207.0  352.42  5278.2  353.75  5419.6  357.57
  5571.6  362.69  5581.9  362.78  5661.5  367.20  5669.4  368.68  5701.8  369.58
#Mann=15,-1,0
  4452.7    0.16       0  4508.1    0.08       0  4549.9    0.16       0
  4659.9    0.08       0  4679.0    0.05       0  4808.1    0.12       0
  4811.8    0.05       0  4937.1    0.12       0  4963.6    0.08       0
  4996.6    0.07       0  5004.2    0.08       0  5199.6    0.16       0
  5419.6    0.05       0  5571.6    0.08       0  5581.9    0.05       0
Bank Sta=4764.6,5154.2
Exp/Cntr=0.3,0.1

Type RM Length L Ch R = 1,1517,279,279,279
BEGIN DESCRIPTION:
Mapping XS dec00f40
END DESCRIPTION:
XS GIS Cut Line= 3
      2904375.83      6951326.52      2904891.47      6951758.83
      2905308.14      6952055.71
#Sta/Elev= 30
  4352.0  366.42  4386.0  367.02  4400.4  366.41  4456.3  360.85  4464.1  361.13
  4513.6  354.19  4548.7  351.01  4590.2  350.16  4651.6  347.25  4652.2  346.45
  4658.6  346.45  4659.2  347.25  4975.4  349.03  4996.2  348.49  5003.4  347.29
  5010.5  347.36  5017.1  349.03  5031.1  348.34  5069.2  350.16  5127.8  351.14
  5182.4  352.36  5203.2  354.00  5283.2  357.05  5289.3  358.41  5297.9  358.81
  5304.1  360.48  5354.5  362.18  5461.4  369.81  5490.9  373.28  5536.5  375.58
#Mann=4,-1,0
  4352.0    0.16       0  4651.6    0.07       0  4659.2    0.16       0
  5127.8    0.16       0
Bank Sta=4590.2,5069.2
Exp/Cntr=0.3,0.1

Type RM Length L Ch R = 1,1238,347,347,347
BEGIN DESCRIPTION:
Mapping XS 35b0ed24
END DESCRIPTION:
XS GIS Cut Line= 3
      2904284.66      6951722.35      2904808.14      6952003.62
      2905310.41      6952125.94
#Sta/Elev= 30
  4439.5  365.36  4462.6  365.94  4478.2  365.40  4503.2  362.69  4516.4  360.63
  4522.0  360.66  4560.2  354.08  4606.1  349.00  4620.3  346.64  4651.8  345.92
  4652.4  345.12  4658.8  345.12  4659.4  345.92  4795.6  346.25  4825.9  346.99
  4855.7  346.48  4959.6  347.94  4987.2  347.75  5003.4  346.77  5018.8  347.95
  5040.8  347.03  5071.7  347.57  5093.1  349.00  5178.0  352.04  5225.3  354.66
  5230.5  354.37  5421.6  369.73  5480.8  374.09  5514.3  375.74  5550.7  380.61
#Mann=5,-1,0
  4439.5    0.16       0  4503.2    0.12       0  4651.8    0.07       0
  4659.4    0.12       0  5178.0    0.16       0
Bank Sta=4606.1,5093.1
Exp/Cntr=0.3,0.1

Type RM Length L Ch R = 1,891,0,0,0
BEGIN DESCRIPTION:
UNT 002 IN DRY CR WATERSHED 2.0
END DESCRIPTION:
XS GIS Cut Line= 3
      2904350.03      6952150.01      2904736.16      6952328.76
      2905274.96      6952175.01
#Sta/Elev= 30
  4574.5  358.75  4625.8  355.59  4643.2  353.01  4648.7  353.18  4708.4  347.67
  4756.3  345.54  4931.0  345.18  4931.6  344.38  4938.0  344.38  4938.6  345.18
  4975.2  345.93  5106.4  345.52  5154.5  347.67  5186.0  349.82  5216.8  350.48
  5252.1  352.02  5269.2  354.33  5285.9  355.43  5291.1  355.10  5319.7  357.91
  5324.9  357.68  5358.7  362.39  5373.2  362.77  5431.6  369.51  5470.6  372.58
  5504.4  376.53  5509.6  376.07  5529.1  377.72  5543.4  377.51  5560.3  378.73
#Mann=4,-1,0
  4574.5    0.12       0  4931.0    0.07       0  4938.6    0.12       0
  5216.8    0.16       0
Bank Sta=4708.4,5154.5
Exp/Cntr=0.3,0.1

Chan Stop Cuts=-1