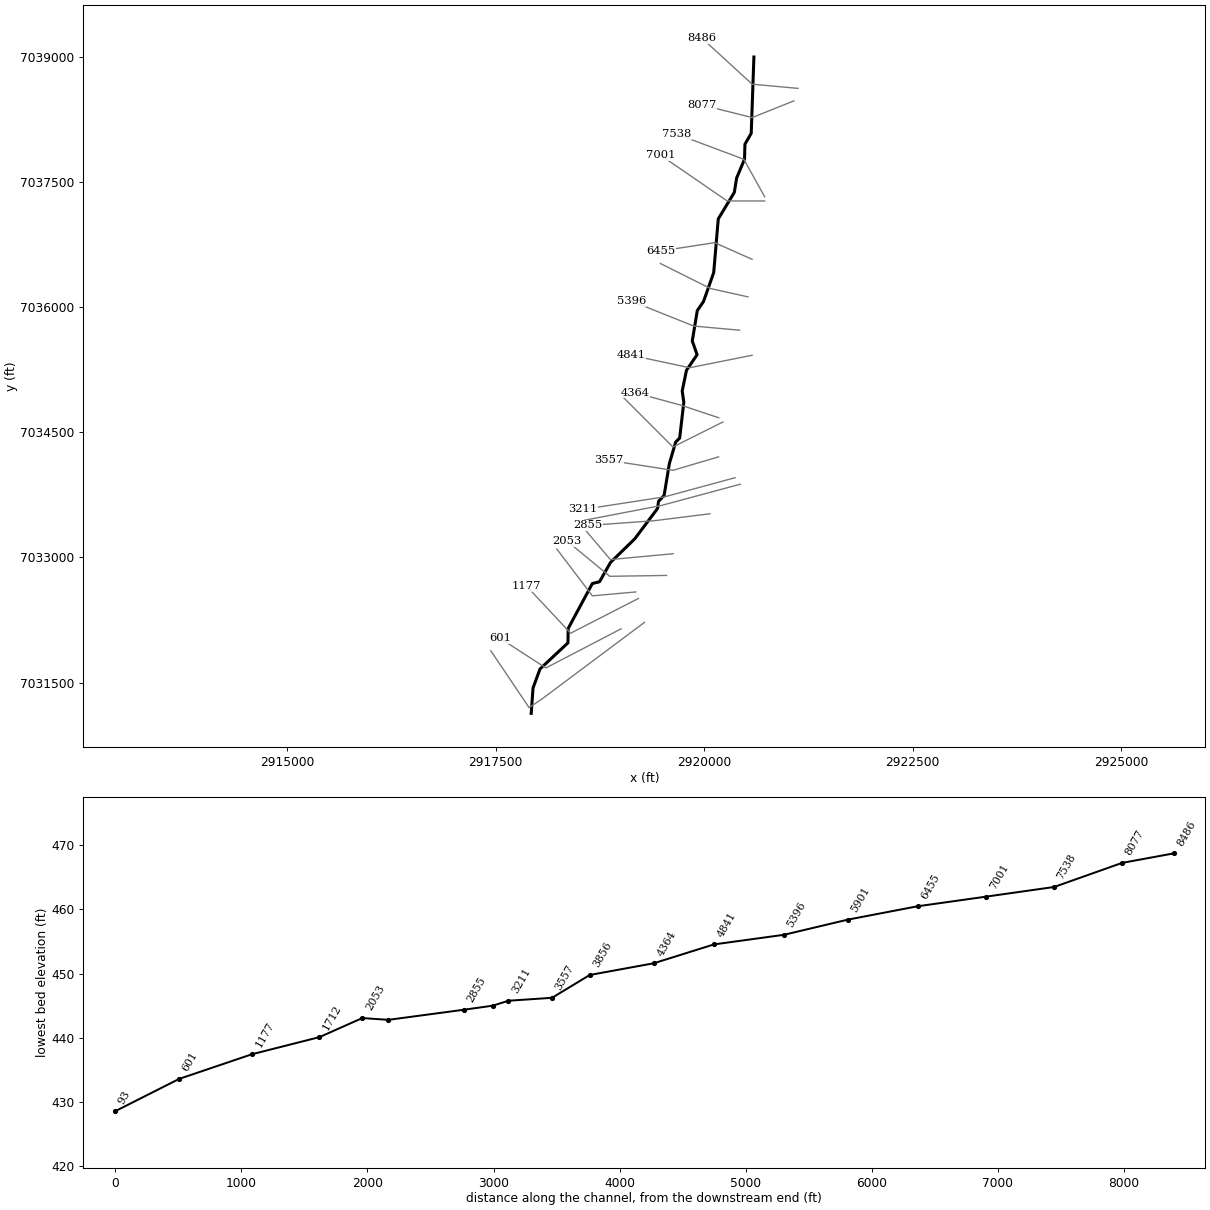
--- UNT 003 IN DRY CR WATERSHED.prj (project) ---

Proj Title=UNT 003 IN DRY CR WATERSHED Base Level Engineering
Current Plan=p01
Default Exp/Contr=0.3,0.1
English Units
Geom File=g01
Flow File=f01
Plan File=p01
BEGIN DESCRIPTION:
UNT 003 IN DRY CR WATERSHED
END DESCRIPTION:

--- UNT 003 IN DRY CR WATERSHED.p01 (plan) ---

Plan Title=Multiple Run
Short Identifier=Multiple
Geom File=g01
Flow File=f01
Subcritical Flow
K Sum by GR= 0
Std Step Tol= 0.01
Critical Tol= 0.01
Num of Std Step Trials= 20
Max Error Tol= 0.3
Flow Tol Ratio= 0.001
Split Flow NTrial= 30
Split Flow Tol= 0.02
Split Flow Ratio= 0.02
Log Output Level= 0
Friction Slope Method= 1
Unsteady Friction Slope Method= 2
Unsteady Bridges Friction Slope Method= 1
Parabolic Critical Depth
Global Vel Dist=  1 , 1 , 1
Global Log Level= 0
CheckData=True
Encroach Param= -1, 0, 0, 0
BEGIN DESCRIPTION:
Multiple Run
END DESCRIPTION:

--- UNT 003 IN DRY CR WATERSHED.f01 (steady flow) ---

Flow Title=Multiple
Number of Profiles=7
Profile Names=10-year,25-year,50-year,1pct_min,100-year,1pct_plu,500-year
River Rch & RM= UNT 003 IN DRY C,Reach-1,8486
     509     675     808     481     960    1915    1357
River Rch & RM= UNT 003 IN DRY C,Reach-1,7538
     731     988    1197     721    1438    2869    2078
Boundary for River Rch & Prof#=UNT 003 IN DRY C,Reach-1,1
Up Type=0
Dn Type=3
Dn Slope=0.005
Boundary for River Rch & Prof#=UNT 003 IN DRY C,Reach-1,2
Up Type=0
Dn Type=3
Dn Slope=0.005
Boundary for River Rch & Prof#=UNT 003 IN DRY C,Reach-1,3
Up Type=0
Dn Type=3
Dn Slope=0.005
Boundary for River Rch & Prof#=UNT 003 IN DRY C,Reach-1,4
Up Type=0
Dn Type=3
Dn Slope=0.005
Boundary for River Rch & Prof#=UNT 003 IN DRY C,Reach-1,5
Up Type=0
Dn Type=3
Dn Slope=0.005
Boundary for River Rch & Prof#=UNT 003 IN DRY C,Reach-1,6
Up Type=0
Dn Type=3
Dn Slope=0.005
Boundary for River Rch & Prof#=UNT 003 IN DRY C,Reach-1,7
Up Type=0
Dn Type=3
Dn Slope=0.005

--- UNT 003 IN DRY CR WATERSHED.g01 (geometry) ---

Geom Title=Existing Conditions

River Reach=UNT 003 IN DRY C,Reach-1
Reach XY= 30
      2920595.84      7039000.95      2920563.62      7038086.07
      2920488.16      7037955.51      2920483.51      7037776.57
      2920388.53      7037549.49      2920361.10      7037377.85
      2920168.49      7037059.49      2920113.92      7036416.28
      2919990.99      7036067.90      2919916.91      7035960.69
      2919856.76      7035595.65      2919914.74      7035431.34
      2919787.42      7035244.96      2919736.06      7034996.47
      2919755.34      7034860.97      2919705.58      7034431.74
      2919658.10      7034384.70      2919581.71      7034124.29
      2919519.29      7033744.51      2919452.17      7033673.61
      2919440.72      7033587.82      2919167.68      7033224.23
      2918876.49      7032940.33      2918744.58      7032708.88
      2918658.87      7032687.75      2918369.18      7032149.19
      2918366.04      7031976.14      2918031.02      7031663.17
      2917947.47      7031435.15      2917925.59      7031130.71

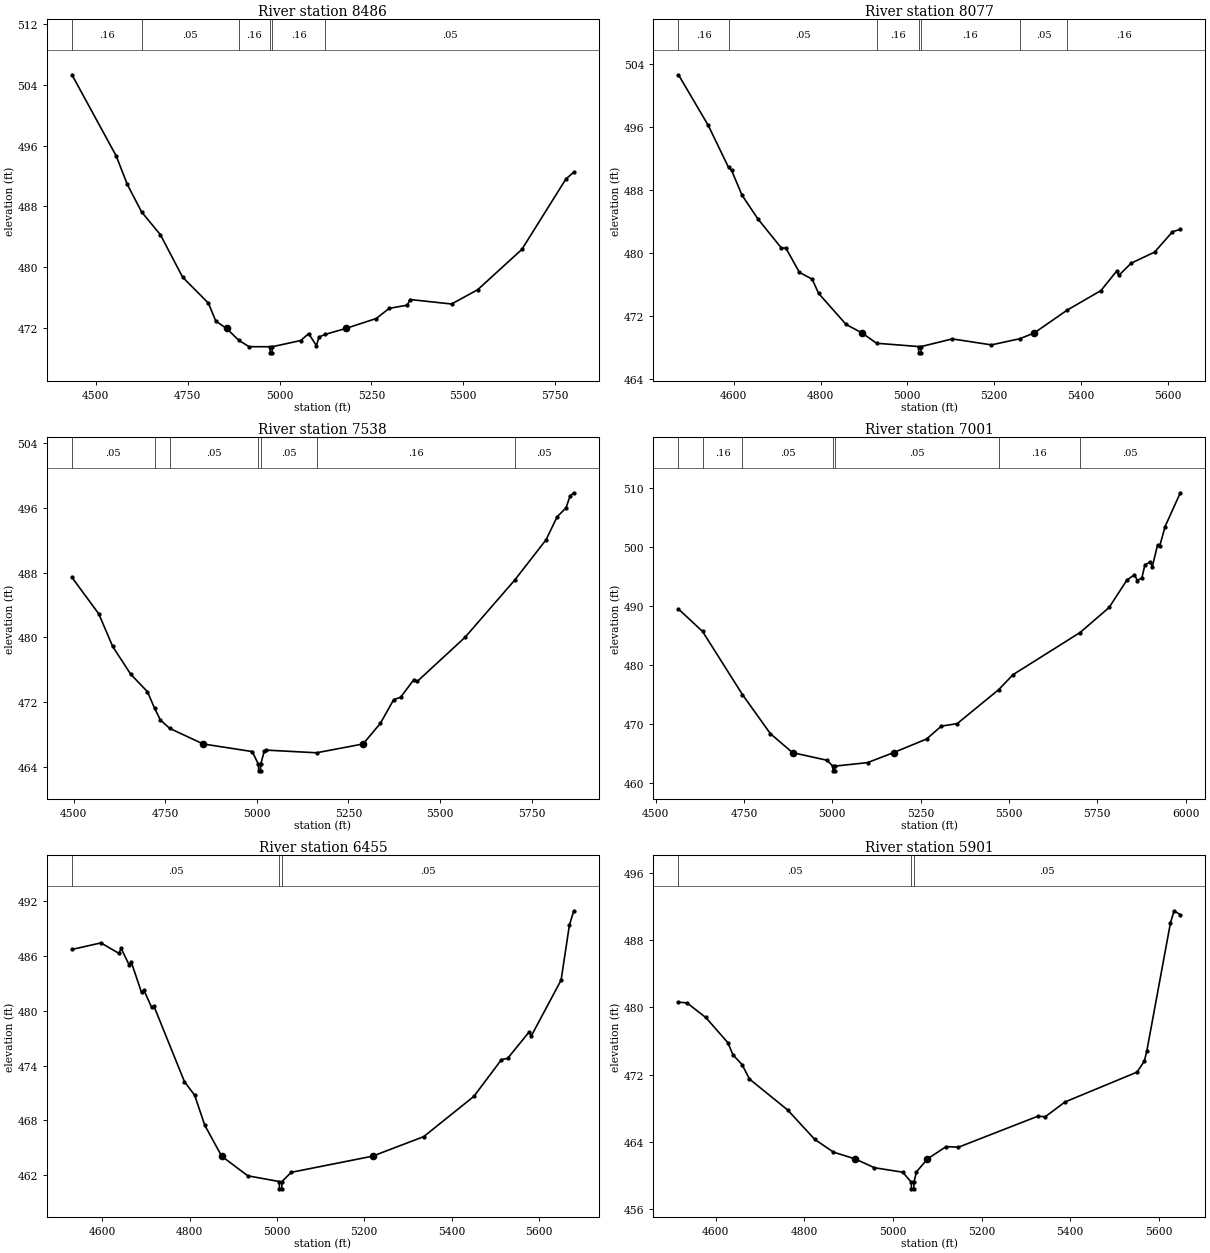
Type RM Length L Ch R = 1,8486,409,409,409
BEGIN DESCRIPTION:
UNT 003 IN DRY CR WATERSHED 14.0
END DESCRIPTION:
XS GIS Cut Line= 3
      2921124.97      7038625.00      2920575.00      7038675.00
      2919974.99      7039225.01
#Sta/Elev= 30
  4434.9  505.30  4555.4  494.63  4585.5  490.90  4624.4  487.28  4675.9  484.26
  4736.1  478.70  4806.4  475.28  4826.5  472.92  4855.9  471.95  4888.8  470.41
  4916.9  469.56  4974.1  469.55  4974.6  468.75  4979.6  468.75  4980.1  469.55
  5057.7  470.37  5079.3  471.27  5100.3  469.71  5107.7  470.83  5123.9  471.17
  5180.1  471.95  5263.1  473.26  5298.8  474.60  5348.2  475.02  5355.0  475.76
  5468.4  475.17  5539.3  477.04  5659.6  482.34  5779.8  491.61  5801.1  492.50
#Mann=6,-1,0
  4434.9    0.16       0  4624.4    0.05       0  4888.8    0.16       0
  4974.1    0.07       0  4980.1    0.16       0  5123.9    0.05       0
Bank Sta=4855.9,5180.1
Exp/Cntr=0.3,0.1

Type RM Length L Ch R = 1,8077,539,539,539
BEGIN DESCRIPTION:
UNT 003 IN DRY CR WATERSHED 13.0
END DESCRIPTION:
XS GIS Cut Line= 3
      2921074.98      7038474.99      2920575.00      7038275.00
      2919974.96      7038425.01
#Sta/Elev= 30
  4472.3  502.60  4540.9  496.17  4587.8  490.82  4594.8  490.44  4619.0  487.28
  4655.4  484.29  4709.2  480.61  4720.0  480.58  4751.0  477.50  4780.6  476.63
  4795.4  474.82  4858.7  470.88  4895.6  469.79  4928.9  468.49  5025.8  468.07
  5026.3  467.27  5031.3  467.27  5031.8  468.07  5103.6  469.04  5193.8  468.28
  5259.0  469.06  5292.4  469.79  5368.5  472.70  5446.3  475.18  5482.4  477.65
  5487.5  477.11  5515.9  478.66  5570.0  480.07  5611.2  482.65  5629.3  482.97
#Mann=7,-1,0
  4472.3    0.16       0  4587.8    0.05       0  4928.9    0.16       0
  5025.8    0.07       0  5031.8    0.16       0  5259.0    0.05       0
  5368.5    0.16       0
Bank Sta=4895.6,5292.4
Exp/Cntr=0.3,0.1

Type RM Length L Ch R = 1,7538,537,537,537
BEGIN DESCRIPTION:
UNT 003 IN DRY CR WATERSHED 12.0
END DESCRIPTION:
XS GIS Cut Line= 3
      2920725.02      7037324.96      2920475.00      7037775.00
      2919675.02      7038074.99
#Sta/Elev= 30
  4495.5  487.40  4568.8  482.89  4606.5  478.88  4655.7  475.45  4701.5  473.28
  4721.0  471.23  4736.9  469.79  4761.9  468.76  4853.4  466.83  4987.4  465.89
  5004.4  464.31  5004.9  463.51  5010.0  463.51  5010.5  464.31  5020.1  465.93
  5025.5  466.07  5162.8  465.74  5289.9  466.83  5337.0  469.38  5373.4  472.31
  5392.1  472.59  5427.7  474.74  5437.5  474.55  5568.4  480.02  5704.1  487.10
  5789.1  492.05  5819.3  494.89  5843.4  495.98  5854.9  497.49  5864.7  497.85
#Mann=7,-1,0
  4495.5    0.05       0  4721.0    0.16       0  4761.9    0.05       0
  5004.4    0.03       0  5010.5    0.05       0  5162.8    0.16       0
  5704.1    0.05       0
Bank Sta=4853.4,5289.9
Exp/Cntr=0.3,0.1

Type RM Length L Ch R = 1,7001,546,546,546
BEGIN DESCRIPTION:
UNT 003 IN DRY CR WATERSHED 11.0
END DESCRIPTION:
XS GIS Cut Line= 3
      2920724.98      7037275.00      2920275.00      7037275.00
      2919475.00      7037825.00
#Sta/Elev= 30
  4564.4  489.42  4632.6  485.62  4745.5  474.93  4824.4  468.32  4887.3  465.09
  4984.4  463.81  5001.3  462.81  5001.8  462.01  5006.9  462.01  5007.4  462.81
  5099.6  463.40  5173.2  465.09  5266.7  467.40  5308.7  469.59  5353.3  470.00
  5470.9  475.76  5511.6  478.30  5701.4  485.44  5783.6  489.68  5834.3  494.36
  5855.3  495.21  5863.8  494.25  5876.3  494.69  5885.1  496.93  5900.0  497.36
  5906.0  496.61  5920.9  500.31  5927.0  500.10  5941.9  503.37  5985.2  509.11
#Mann=7,-1,0
  4564.4    0.05       0  4632.6    0.16       0  4745.5    0.05       0
  5001.3    0.03       0  5007.4    0.05       0  5470.9    0.16       0
  5701.4    0.05       0
Bank Sta=4887.3,5173.2
Exp/Cntr=0.3,0.1

Type RM Length L Ch R = 1,6455,554,554,554
BEGIN DESCRIPTION:
UNT 003 IN DRY CR WATERSHED 10.0
END DESCRIPTION:
XS GIS Cut Line= 3
      2920575.02      7036574.99      2920125.00      7036775.00
      2919475.01      7036675.00
#Sta/Elev= 30
  4530.1  486.74  4596.5  487.46  4637.5  486.32  4643.0  486.85  4660.8  485.08
  4666.2  485.34  4689.5  482.03  4695.0  482.28  4712.7  480.39  4718.2  480.50
  4788.0  472.24  4811.2  470.77  4834.5  467.47  4873.2  464.08  4933.0  461.93
  5005.1  461.30  5005.6  460.50  5010.8  460.50  5011.3  461.30  5032.7  462.31
  5218.9  464.08  5336.2  466.22  5451.3  470.64  5514.5  474.67  5528.4  474.79
  5577.8  477.69  5582.8  477.26  5651.1  483.38  5670.1  489.40  5680.2  490.98
#Mann=3,-1,0
  4530.1    0.05       0  5005.1    0.03       0  5011.3    0.05       0
Bank Sta=4873.2,5218.9
Exp/Cntr=0.3,0.1

Type RM Length L Ch R = 1,5901,505,505,505
BEGIN DESCRIPTION:
UNT 003 IN DRY CR WATERSHED 9.0
END DESCRIPTION:
XS GIS Cut Line= 3
      2920525.02      7036124.99      2920075.00      7036225.00
      2919475.02      7036524.99
#Sta/Elev= 30
  4516.4  480.60  4535.6  480.51  4577.9  478.78  4627.8  475.78  4639.4  474.33
  4659.8  473.18  4676.5  471.46  4762.3  467.80  4823.7  464.29  4866.0  462.77
  4914.7  461.97  4958.2  460.92  5022.1  460.39  5041.3  459.21  5041.8  458.41
  5047.1  458.41  5047.6  459.21  5052.9  460.41  5078.0  461.97  5120.0  463.43
  5147.9  463.36  5326.8  467.04  5343.6  466.98  5388.3  468.74  5550.4  472.28
  5567.2  473.60  5572.8  474.85  5625.9  490.01  5634.2  491.46  5648.2  490.99
#Mann=3,-1,0
  4516.4    0.05       0  5041.3    0.03       0  5047.6    0.05       0
Bank Sta=4914.7,5078
Exp/Cntr=0.3,0.1

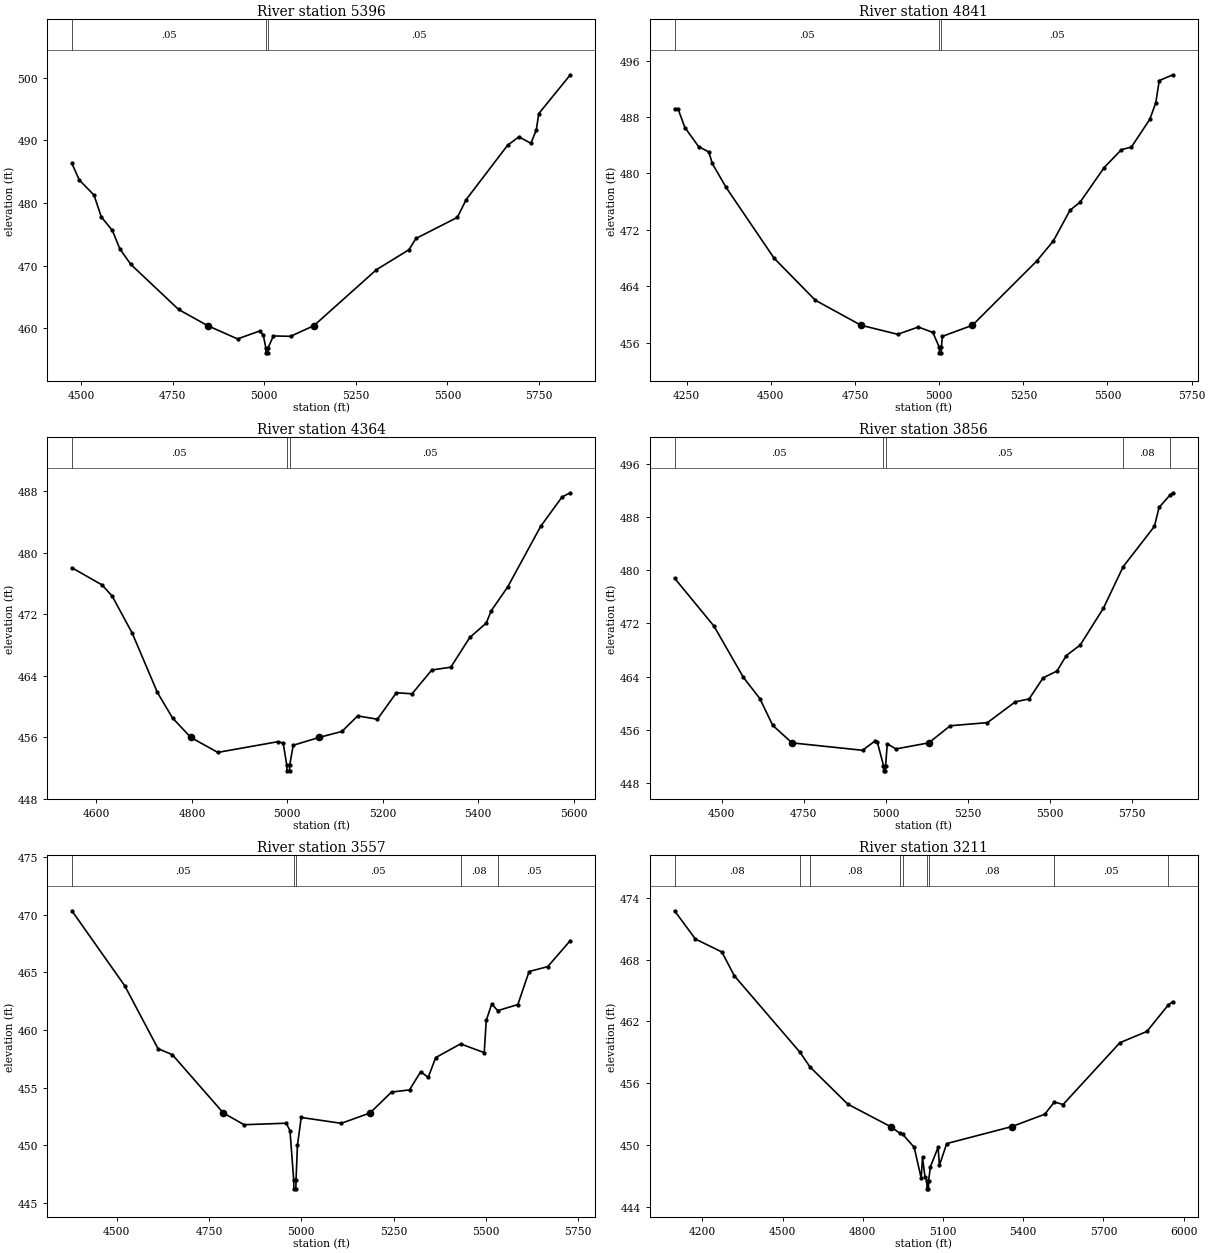
Type RM Length L Ch R = 1,5396,555,555,555
BEGIN DESCRIPTION:
UNT 003 IN DRY CR WATERSHED 8.0
END DESCRIPTION:
XS GIS Cut Line= 3
      2920425.01      7035725.00      2919875.00      7035775.00
      2919124.96      7036075.02
#Sta/Elev= 30
  4475.3  486.34  4495.4  483.68  4535.6  481.27  4555.6  477.77  4585.8  475.61
  4605.9  472.70  4636.0  470.19  4766.5  462.98  4845.9  460.39  4927.2  458.28
  4987.4  459.53  4997.5  458.91  5004.4  456.85  5004.9  456.05  5010.2  456.05
  5010.7  456.85  5025.1  458.75  5072.0  458.69  5135.5  460.39  5306.3  469.34
  5395.1  472.54  5414.0  474.33  5527.1  477.70  5551.3  480.56  5664.4  489.25
  5695.3  490.58  5727.7  489.54  5742.5  491.68  5749.2  494.29  5835.4  500.50
#Mann=3,-1,0
  4475.3    0.05       0  5004.4    0.03       0  5010.7    0.05       0
Bank Sta=4845.9,5135.5
Exp/Cntr=0.3,0.1

Type RM Length L Ch R = 1,4841,477,477,477
BEGIN DESCRIPTION:
UNT 003 IN DRY CR WATERSHED 7.0
END DESCRIPTION:
XS GIS Cut Line= 3
      2920574.97      7035424.99      2919825.00      7035275.00
      2919125.01      7035425.00
#Sta/Elev= 30
  4213.9  489.16  4224.1  489.16  4244.5  486.50  4285.3  483.80  4315.8  483.03
  4326.0  481.40  4366.8  478.02  4509.6  467.97  4632.0  462.01  4767.9  458.46
  4876.7  457.18  4937.9  458.21  4981.3  457.44  5000.2  455.35  5000.7  454.55
  5006.1  454.55  5006.6  455.35  5009.4  456.89  5098.8  458.46  5289.8  467.57
  5339.2  470.42  5388.7  474.77  5418.5  475.91  5490.1  480.82  5541.2  483.36
  5571.0  483.73  5625.6  487.66  5643.5  490.02  5653.7  493.16  5694.6  493.98
#Mann=3,-1,0
  4213.9    0.05       0  5000.2    0.03       0  5006.6    0.05       0
Bank Sta=4767.9,5098.8
Exp/Cntr=0.3,0.1

Type RM Length L Ch R = 1,4364,508,508,508
BEGIN DESCRIPTION:
UNT 003 IN DRY CR WATERSHED 6.0
END DESCRIPTION:
XS GIS Cut Line= 3
      2920175.03      7034674.99      2919725.00      7034825.00
      2919174.97      7034975.01
#Sta/Elev= 30
  4548.5  478.05  4611.8  475.81  4632.9  474.36  4675.0  469.52  4727.7  461.81
  4759.4  458.49  4797.7  455.96  4854.2  454.01  4980.7  455.41  4991.3  455.21
  4998.6  452.41  4999.1  451.61  5004.5  451.61  5005.0  452.41  5012.3  454.94
  5066.5  455.96  5114.4  456.74  5147.3  458.76  5188.7  458.33  5228.5  461.78
  5261.3  461.64  5302.7  464.74  5342.5  465.10  5382.2  468.97  5416.8  470.85
  5427.1  472.44  5461.7  475.55  5530.8  483.44  5575.7  487.27  5593.0  487.81
#Mann=3,-1,0
  4548.5    0.05       0  4998.6    0.03       0  5005.0    0.05       0
Bank Sta=4797.7,5066.5
Exp/Cntr=0.3,0.1

Type RM Length L Ch R = 1,3856,299,299,299
BEGIN DESCRIPTION:
UNT 003 IN DRY CR WATERSHED 5.0
END DESCRIPTION:
XS GIS Cut Line= 3
      2920225.00      7034625.00      2919625.00      7034325.00
      2919024.97      7034925.03
#Sta/Elev= 30
  4356.2  478.83  4476.4  471.60  4565.8  463.89  4616.1  460.68  4655.3  456.65
  4714.1  454.00  4929.2  452.88  4968.3  454.32  4973.9  454.18  4993.1  450.58
  4993.6  449.78  4999.0  449.78  4999.5  450.58  5004.7  453.87  5030.6  453.08
  5131.1  454.00  5196.7  456.58  5309.9  457.05  5394.7  460.18  5437.1  460.63
  5479.6  463.80  5522.0  464.83  5550.3  467.16  5592.7  468.75  5663.4  474.30
  5723.9  480.58  5819.0  486.65  5833.1  489.50  5867.3  491.42  5875.6  491.71
#Mann=5,-1,0
  4356.2    0.05       0  4993.1    0.03       0  4999.5    0.05       0
  5723.9    0.08       0  5867.3    0.05       0
Bank Sta=4714.1,5131.1
Exp/Cntr=0.3,0.1

Type RM Length L Ch R = 1,3557,346,346,346
BEGIN DESCRIPTION:
Mapping XS bd49a9a9
END DESCRIPTION:
XS GIS Cut Line= 3
      2920172.22      7034206.57      2919625.39      7034045.12
      2918854.51      7034164.92
#Sta/Elev= 30
  4378.6  470.33  4521.7  463.83  4612.0  458.37  4650.5  457.86  4788.8  452.80
  4844.9  451.78  4959.3  451.91  4969.4  451.26  4979.4  447.02  4979.9  446.22
  4985.3  446.22  4985.8  447.02  4989.6  449.99  4999.8  452.41  5108.4  451.90
  5186.2  452.80  5244.4  454.61  5293.2  454.80  5323.6  456.38  5343.8  455.88
  5364.1  457.60  5431.5  458.79  5495.6  458.03  5501.1  460.82  5515.9  462.25
  5532.1  461.67  5586.7  462.20  5617.1  465.06  5667.7  465.49  5728.9  467.75
#Mann=5,-1,0
  4378.6    0.05       0  4979.4    0.03       0  4985.8    0.05       0
  5431.5    0.08       0  5532.1    0.05       0
Bank Sta=4788.8,5186.2
Exp/Cntr=0.3,0.1

Type RM Length L Ch R = 1,3211,124,124,124
BEGIN DESCRIPTION:
Mapping XS 91657722
END DESCRIPTION:
XS GIS Cut Line= 3
      2920370.22      7033956.59      2919526.43      7033727.41
      2918548.65      7033576.58
#Sta/Elev= 30
  4096.3  472.73  4174.2  469.99  4273.4  468.73  4319.3  466.44  4564.8  459.02
  4602.8  457.58  4744.2  453.97  4903.8  451.80  4937.8  451.17  4949.6  451.04
  4992.3  449.79  5018.4  446.79  5023.5  448.81  5032.8  446.87  5039.7  446.56
  5040.2  445.76  5045.7  445.76  5046.2  446.56  5053.0  447.91  5081.6  449.78
  5086.7  448.04  5113.8  450.15  5357.6  451.80  5480.7  453.00  5516.2  454.18
  5549.0  453.94  5761.3  459.93  5862.5  461.03  5941.9  463.58  5960.0  463.93
#Mann=9,-1,0
  4096.3    0.08       0  4564.8    0.05       0  4602.8    0.08       0
  4937.8    0.05       0  4949.6    0.08       0  5039.7    0.07       0
  5046.2    0.08       0  5516.2    0.05       0  5941.9    0.08       0
Bank Sta=4903.8,5357.6
Exp/Cntr=0.3,0.1

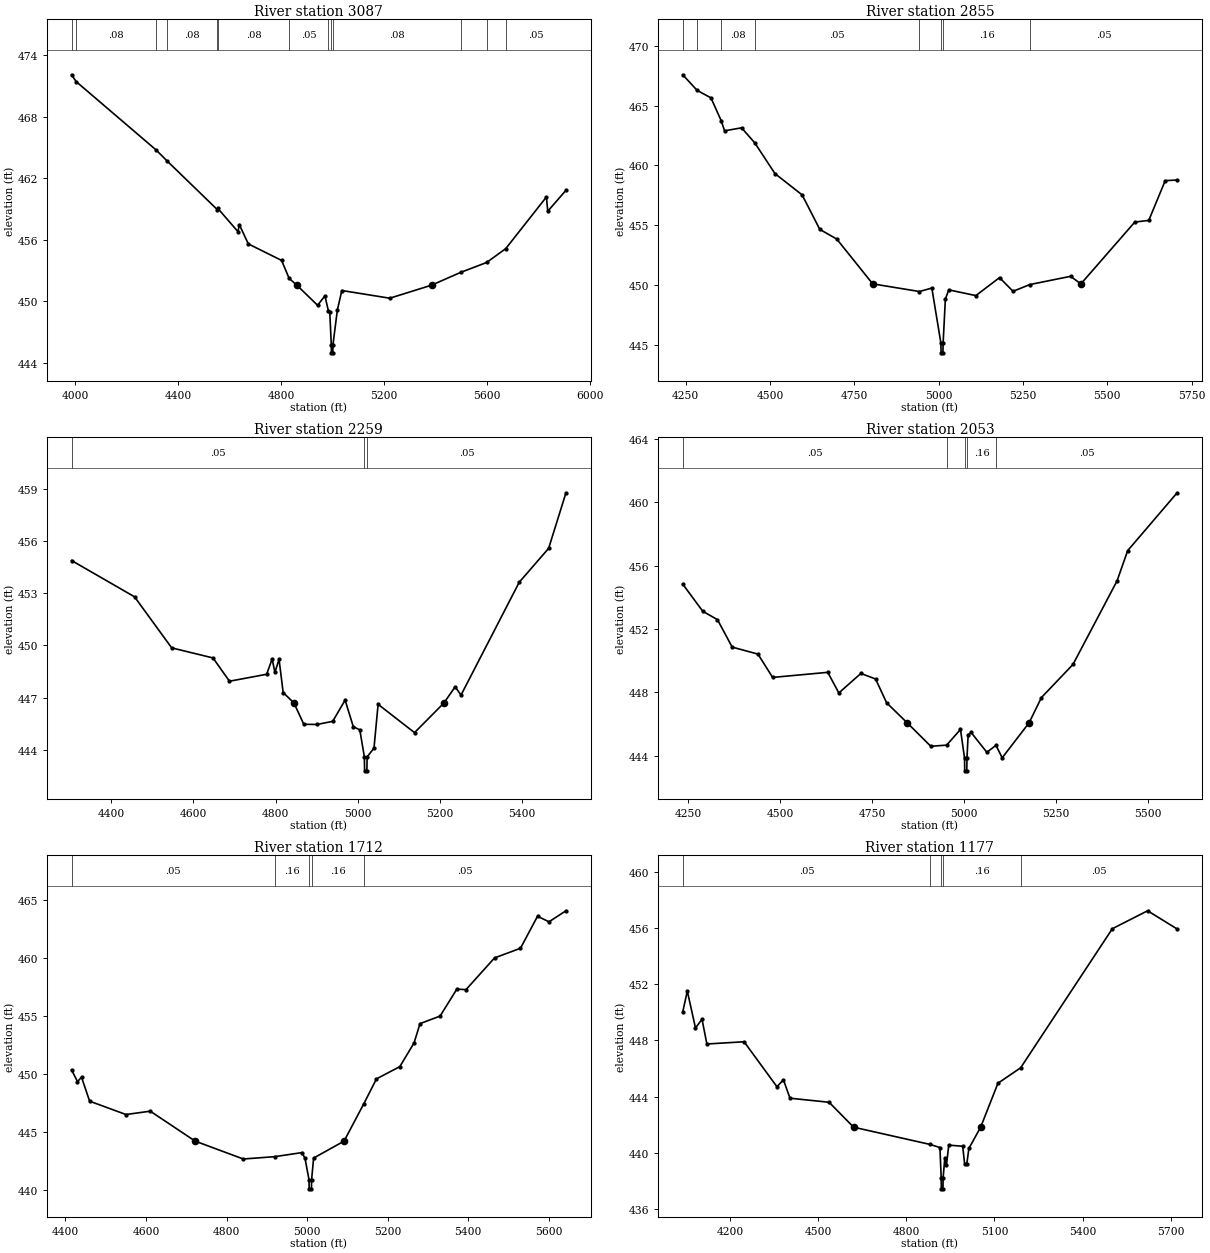
Type RM Length L Ch R = 1,3087,232,232,232
BEGIN DESCRIPTION:
Mapping XS e4d80672
END DESCRIPTION:
XS GIS Cut Line= 3
      2920432.72      7033878.46      2919484.76      7033623.24
      2918562.92      7033446.17
#Sta/Elev= 30
  3986.7  472.07  4004.8  471.40  4314.5  464.76  4358.5  463.66  4552.7  458.94
  4555.0  459.05  4633.1  456.79  4638.3  457.48  4673.1  455.60  4802.5  453.99
  4831.6  452.25  4861.6  451.58  4942.3  449.62  4970.8  450.54  4984.6  449.04
  4989.6  448.98  4995.5  445.79  4996.0  444.99  5001.5  444.99  5002.0  445.79
  5019.1  449.16  5036.5  451.06  5222.7  450.31  5384.9  451.58  5498.6  452.83
  5599.0  453.79  5673.2  455.14  5831.2  460.17  5836.3  458.78  5907.1  460.82
#Mann=13,-1,0
  3986.7    0.05       0  4004.8    0.08       0  4314.5     0.1       0
  4358.5    0.08       0  4552.7    0.05       0  4555.0    0.08       0
  4831.6    0.05       0  4984.6    0.08       0  4995.5    0.07       0
  5002.0    0.08       0  5498.6    0.05       0  5599.0    0.08       0
  5673.2    0.05       0
Bank Sta=4861.6,5384.9
Exp/Cntr=0.3,0.1

Type RM Length L Ch R = 1,2855,596,596,596
BEGIN DESCRIPTION:
Mapping XS ece55e45
END DESCRIPTION:
XS GIS Cut Line= 3
      2920068.08      7033524.28      2919401.43      7033440.95
      2918609.84      7033383.67
#Sta/Elev= 30
  4241.5  467.57  4284.1  466.27  4325.2  465.64  4355.6  463.73  4365.5  462.89
  4415.9  463.14  4455.2  461.88  4514.8  459.32  4595.4  457.54  4647.7  454.66
  4698.1  453.85  4804.6  450.11  4943.2  449.47  4979.9  449.76  5006.8  445.15
  5007.3  444.35  5012.8  444.35  5013.3  445.15  5020.0  448.84  5030.1  449.61
  5110.3  449.13  5180.5  450.63  5220.6  449.49  5270.2  450.05  5391.0  450.74
  5421.8  450.11  5581.5  455.27  5622.9  455.41  5671.7  458.73  5707.0  458.78
#Mann=8,-1,0
  4241.5    0.08       0  4284.1    0.05       0  4355.6    0.08       0
  4455.2    0.05       0  4943.2    0.16       0  5006.8    0.07       0
  5013.3    0.16       0  5270.2    0.05       0
Bank Sta=4804.6,5421.8
Exp/Cntr=0.3,0.1

Type RM Length L Ch R = 1,2259,206,206,206
BEGIN DESCRIPTION:
UNT 003 IN DRY CR WATERSHED 2.0
END DESCRIPTION:
XS GIS Cut Line= 3
      2919627.59      7033045.12      2918875.00      7032975.00
      2918585.87      7033315.97
#Sta/Elev= 30
  4303.5  454.89  4456.7  452.80  4547.1  449.86  4647.6  449.28  4687.7  447.94
  4778.1  448.34  4791.5  449.22  4798.2  448.45  4808.3  449.20  4818.3  447.29
  4844.7  446.68  4868.5  445.46  4900.7  445.45  4938.8  445.63  4969.0  446.85
  4989.0  445.32  5004.8  445.14  5015.9  443.58  5016.4  442.78  5022.0  442.78
  5022.5  443.58  5039.3  444.09  5049.3  446.61  5137.9  444.98  5209.2  446.68
  5236.8  447.62  5251.0  447.14  5392.7  453.64  5464.2  455.59  5506.4  458.79
#Mann=3,-1,0
  4303.5    0.05       0  5015.9    0.03       0  5022.5    0.05       0
Bank Sta=4844.7,5209.2
Exp/Cntr=0.3,0.1

Type RM Length L Ch R = 1,2053,341,341,341
BEGIN DESCRIPTION:
Mapping XS 7fd7e388
END DESCRIPTION:
XS GIS Cut Line= 3
      2919549.48      7032784.70      2918867.14      7032774.29
      2918356.74      7033196.15
#Sta/Elev= 30
  4234.8  454.83  4289.3  453.12  4329.3  452.59  4369.3  450.86  4439.3  450.42
  4479.3  448.95  4629.3  449.27  4659.3  447.97  4719.3  449.20  4759.3  448.85
  4789.3  447.35  4845.1  446.09  4909.4  444.61  4952.5  444.68  4990.2  445.67
  5001.2  443.86  5001.7  443.06  5007.3  443.06  5007.8  443.86  5011.0  445.31
  5018.8  445.49  5061.8  444.23  5086.8  444.67  5103.5  443.88  5176.8  446.09
  5210.3  447.68  5296.2  449.77  5416.1  455.04  5444.8  456.94  5579.4  460.59
#Mann=5,-1,0
  4234.8    0.05       0  4952.5    0.16       0  5001.2    0.07       0
  5007.8    0.16       0  5086.8    0.05       0
Bank Sta=4845.1,5176.8
Exp/Cntr=0.3,0.1

Type RM Length L Ch R = 1,1712,535,535,535
BEGIN DESCRIPTION:
Mapping XS b8aa75d2
END DESCRIPTION:
XS GIS Cut Line= 3
      2919179.65      7032586.79      2918658.81      7032539.91
      2918232.64      7033101.21
#Sta/Elev= 30
  4415.2  450.33  4429.9  449.31  4439.9  449.70  4460.0  447.63  4550.4  446.48
  4610.6  446.77  4722.1  444.19  4841.6  442.65  4919.2  442.85  4987.1  443.20
  4994.8  442.72  5004.7  440.88  5005.2  440.08  5010.8  440.08  5011.3  440.88
  5016.2  442.73  5091.9  444.19  5141.2  447.43  5172.3  449.55  5230.4  450.61
  5265.8  452.66  5280.4  454.31  5330.3  454.96  5371.9  457.28  5394.7  457.24
  5465.5  459.97  5529.9  460.80  5572.3  463.56  5600.7  463.08  5642.9  464.03
#Mann=5,-1,0
  4415.2    0.05       0  4919.2    0.16       0  5004.7    0.07       0
  5011.3    0.16       0  5141.2    0.05       0
Bank Sta=4722.1,5091.9
Exp/Cntr=0.3,0.1

Type RM Length L Ch R = 1,1177,576,576,576
BEGIN DESCRIPTION:
Mapping XS 3e0cc308
END DESCRIPTION:
XS GIS Cut Line= 3
      2919210.88      7032508.65      2918398.39      7032091.99
      2917872.38      7032654.46
#Sta/Elev= 30
  4038.8  450.04  4054.4  451.53  4082.2  448.89  4104.4  449.52  4121.0  447.75
  4247.7  447.91  4359.5  444.70  4381.7  445.19  4403.9  443.88  4537.1  443.59
  4620.6  441.81  4880.8  440.58  4914.4  440.36  4918.7  438.21  4919.2  437.41
  4924.8  437.41  4925.3  438.21  4931.0  439.60  4936.6  439.10  4944.5  440.53
  4991.9  440.45  4998.7  439.15  5006.0  439.20  5012.9  440.29  5053.0  441.81
  5112.0  444.95  5189.2  446.05  5501.4  455.98  5621.5  457.26  5722.0  455.96
#Mann=5,-1,0
  4038.8    0.05       0  4880.8    0.16       0  4918.7    0.07       0
  4925.3    0.16       0  5189.2    0.05       0
Bank Sta=4620.6,5053
Exp/Cntr=0.3,0.1

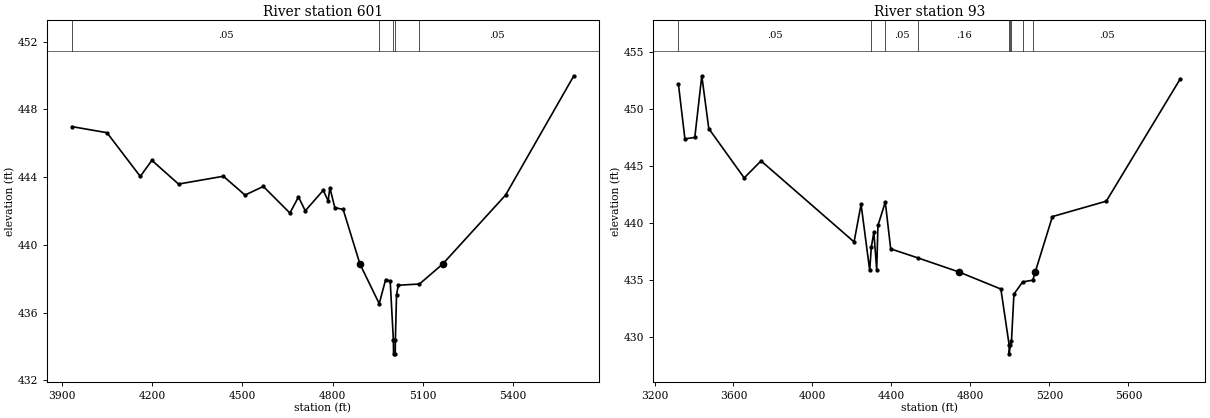
Type RM Length L Ch R = 1,601,508,508,508
BEGIN DESCRIPTION:
Mapping XS a01989bc
END DESCRIPTION:
XS GIS Cut Line= 3
      2919002.60      7032144.10      2918101.52      7031675.33
      2917554.61      7032029.51
#Sta/Elev= 30
  3934.4  446.98  4050.8  446.62  4161.4  444.04  4199.9  444.99  4288.4  443.59
  4437.5  444.05  4509.4  442.94  4570.1  443.45  4658.5  441.88  4686.9  442.83
  4709.5  442.01  4769.1  443.22  4785.5  442.60  4791.2  443.37  4807.6  442.20
  4835.4  442.09  4891.1  438.87  4955.2  436.53  4976.4  437.95  4991.6  437.86
  5002.2  434.37  5002.7  433.57  5008.3  433.57  5008.8  434.37  5012.7  437.07
  5018.7  437.62  5088.8  437.69  5165.9  438.87  5374.9  442.94  5601.7  449.98
#Mann=5,-1,0
  3934.4    0.05       0  4955.2    0.16       0  5002.2    0.07       0
  5008.8    0.16       0  5088.8    0.05       0
Bank Sta=4891.1,5165.9
Exp/Cntr=0.3,0.1

Type RM Length L Ch R = 1,93,0,0,0
BEGIN DESCRIPTION:
UNT 003 IN DRY CR WATERSHED 1.0
END DESCRIPTION:
XS GIS Cut Line= 4
      2919283.61      7032221.78      2918050.00      7031300.00
      2917900.00      7031200.00      2917441.00      7031881.50
#Sta/Elev= 30
  3321.1  452.16  3354.0  447.36  3404.1  447.49  3439.5  452.89  3474.9  448.26
  3654.2  443.94  3739.6  445.43  4210.7  438.33  4246.2  441.62  4289.9  435.83
  4297.9  437.85  4310.8  439.17  4325.4  435.89  4331.6  439.77  4368.8  441.82
  4396.2  437.72  4533.7  436.93  4739.6  435.71  4954.2  434.20  4995.9  429.32
  4996.4  428.52  5002.6  429.32  5007.9  429.65  5020.3  433.75  5064.3  434.82
  5116.0  434.98  5128.5  435.71  5215.2  440.55  5488.1  441.90  5863.0  452.63
#Mann=9,-1,0
  3321.1    0.05       0  4297.9    0.16       0  4368.8    0.05       0
  4533.7    0.16       0  4995.9    0.07       0  5002.6    0.16       0
  5007.9    0.12       0  5064.3    0.16       0  5116.0    0.05       0
Bank Sta=4739.6,5128.5
Exp/Cntr=0.3,0.1

Chan Stop Cuts=-1