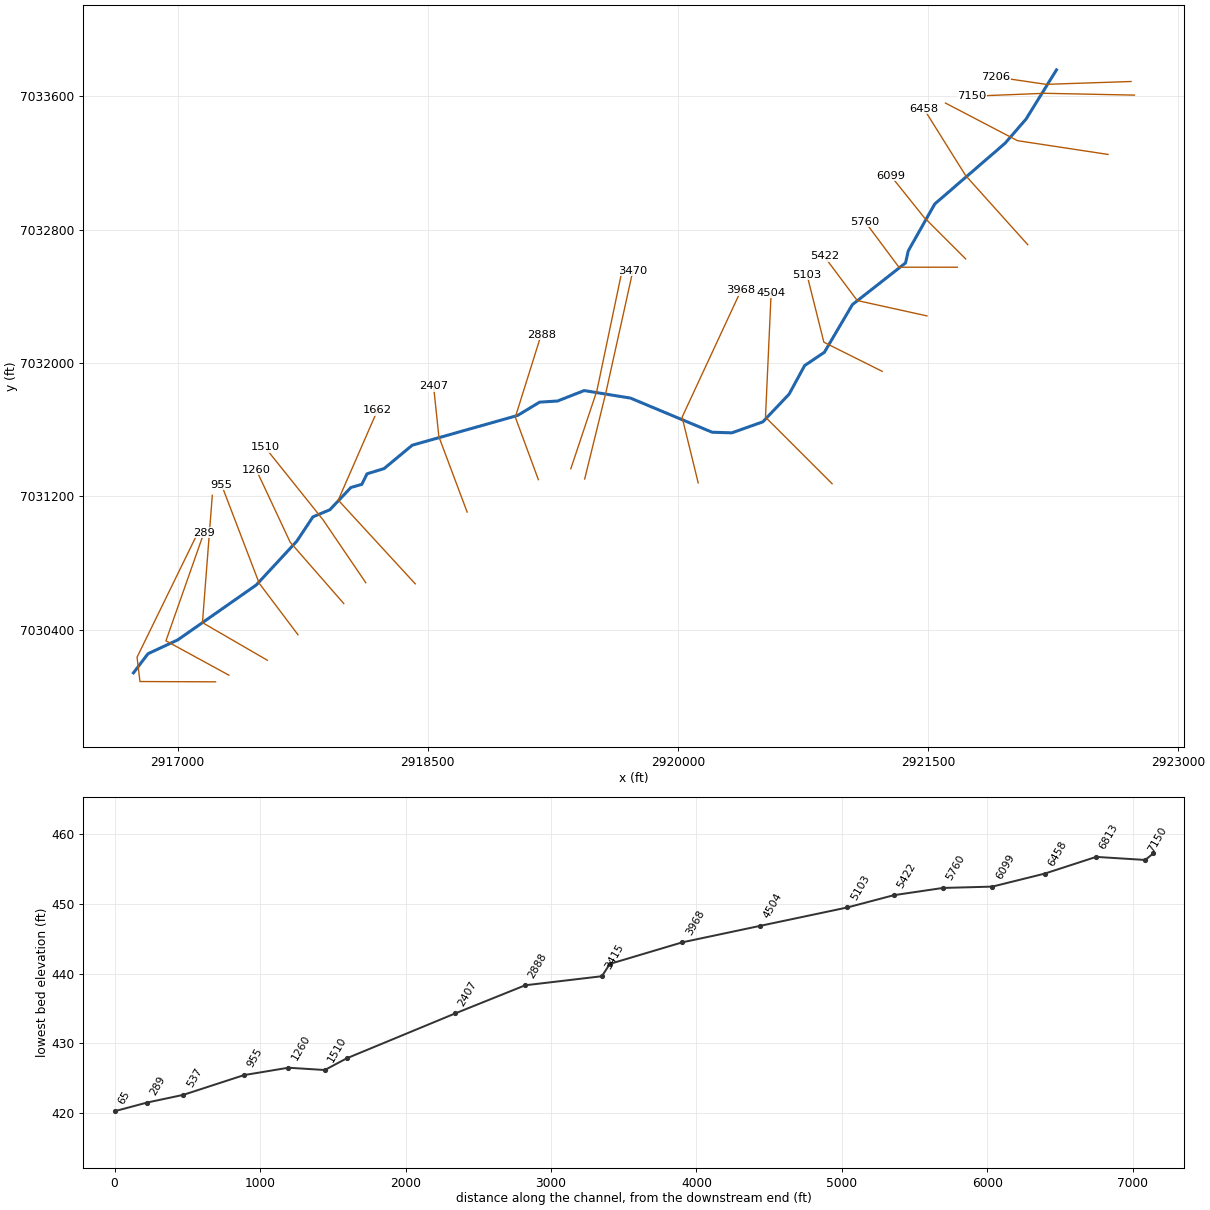
--- UNT 004 IN DRY CR WATERSHED.prj (project) ---

Proj Title=UNT 004 IN DRY CR WATERSHED Base Level Engineering
Current Plan=p01
Default Exp/Contr=0.3,0.1
English Units
Geom File=g01
Flow File=f01
Plan File=p01
BEGIN DESCRIPTION:
UNT 004 IN DRY CR WATERSHED
END DESCRIPTION:

--- UNT 004 IN DRY CR WATERSHED.p01 (plan) ---

Plan Title=Multiple Run
Short Identifier=Multiple
Geom File=g01
Flow File=f01
Subcritical Flow
K Sum by GR= 0
Std Step Tol= 0.01
Critical Tol= 0.01
Num of Std Step Trials= 20
Max Error Tol= 0.3
Flow Tol Ratio= 0.001
Split Flow NTrial= 30
Split Flow Tol= 0.02
Split Flow Ratio= 0.02
Log Output Level= 0
Friction Slope Method= 1
Unsteady Friction Slope Method= 2
Unsteady Bridges Friction Slope Method= 1
Parabolic Critical Depth
Global Vel Dist=  1 , 1 , 1
Global Log Level= 0
CheckData=True
Encroach Param= -1, 0, 0, 0
BEGIN DESCRIPTION:
Multiple Run
END DESCRIPTION:

--- UNT 004 IN DRY CR WATERSHED.f01 (steady flow) ---

Flow Title=Multiple
Program Version=5.07
Number of Profiles= 7
Profile Names=10-year,25-year,50-year,1pct_min,100-year,1pct_plu,500-year
River Rch & RM=UNT 004 IN DRY C,Reach-1         ,7206
     414     538     636     373     744    1485    1023
River Rch & RM=UNT 004 IN DRY C,Reach-1         ,4504
     640     856    1030     615    1228    2450    1749
River Rch & RM=UNT 004 IN DRY C,Reach-1         ,1510
    1220    1694    2092    1281    2555    5098    3821
River Rch & RM=UNT 004 IN DRY C,Reach-1         ,65
    1712    2406    2994    1845    3681    7345    5579
Boundary for River Rch & Prof#=UNT 004 IN DRY C,Reach-1         , 1
Up Type= 0
Dn Type= 3
Dn Slope=0.01088
Boundary for River Rch & Prof#=UNT 004 IN DRY C,Reach-1         , 2
Up Type= 0
Dn Type= 3
Dn Slope=0.01088
Boundary for River Rch & Prof#=UNT 004 IN DRY C,Reach-1         , 3
Up Type= 0
Dn Type= 3
Dn Slope=0.01088
Boundary for River Rch & Prof#=UNT 004 IN DRY C,Reach-1         , 4
Up Type= 0
Dn Type= 3
Dn Slope=0.01088
Boundary for River Rch & Prof#=UNT 004 IN DRY C,Reach-1         , 5
Up Type= 0
Dn Type= 3
Dn Slope=0.01088
Boundary for River Rch & Prof#=UNT 004 IN DRY C,Reach-1         , 6
Up Type= 0
Dn Type= 3
Dn Slope=0.01088
Boundary for River Rch & Prof#=UNT 004 IN DRY C,Reach-1         , 7
Up Type= 0
Dn Type= 3
Dn Slope=0.01088
DSS Import GetInterval= 0
DSS Import GetPeak= 0
DSS Import FillOption= 0

--- UNT 004 IN DRY CR WATERSHED.g01 (geometry) ---

Geom Title=Existing Conditions

River Reach=UNT 004 IN DRY C,Reach-1
Reach XY= 30
      2922269.62      7033759.06      2922087.59      7033464.19
      2921961.39      7033318.66      2921539.81      7032954.33
      2921381.12      7032673.13      2921364.58      7032600.46
      2921046.13      7032350.65      2920878.03      7032064.38
      2920759.65      7031984.59      2920666.50      7031813.17
      2920508.91      7031646.93      2920323.41      7031581.14
      2920205.35      7031584.62      2919715.77      7031789.48
      2919437.99      7031834.62      2919278.27      7031772.12
      2919170.63      7031765.17      2919038.68      7031685.31
      2918407.16      7031506.91      2918238.11      7031366.50
      2918135.86      7031335.03      2918104.74      7031271.90
      2918039.09      7031252.92      2917913.22      7031119.57
      2917811.59      7031076.82      2917714.75      7030930.51
      2917472.03      7030668.24      2917001.98      7030339.02
      2916822.78      7030255.64      2916735.59      7030140.71

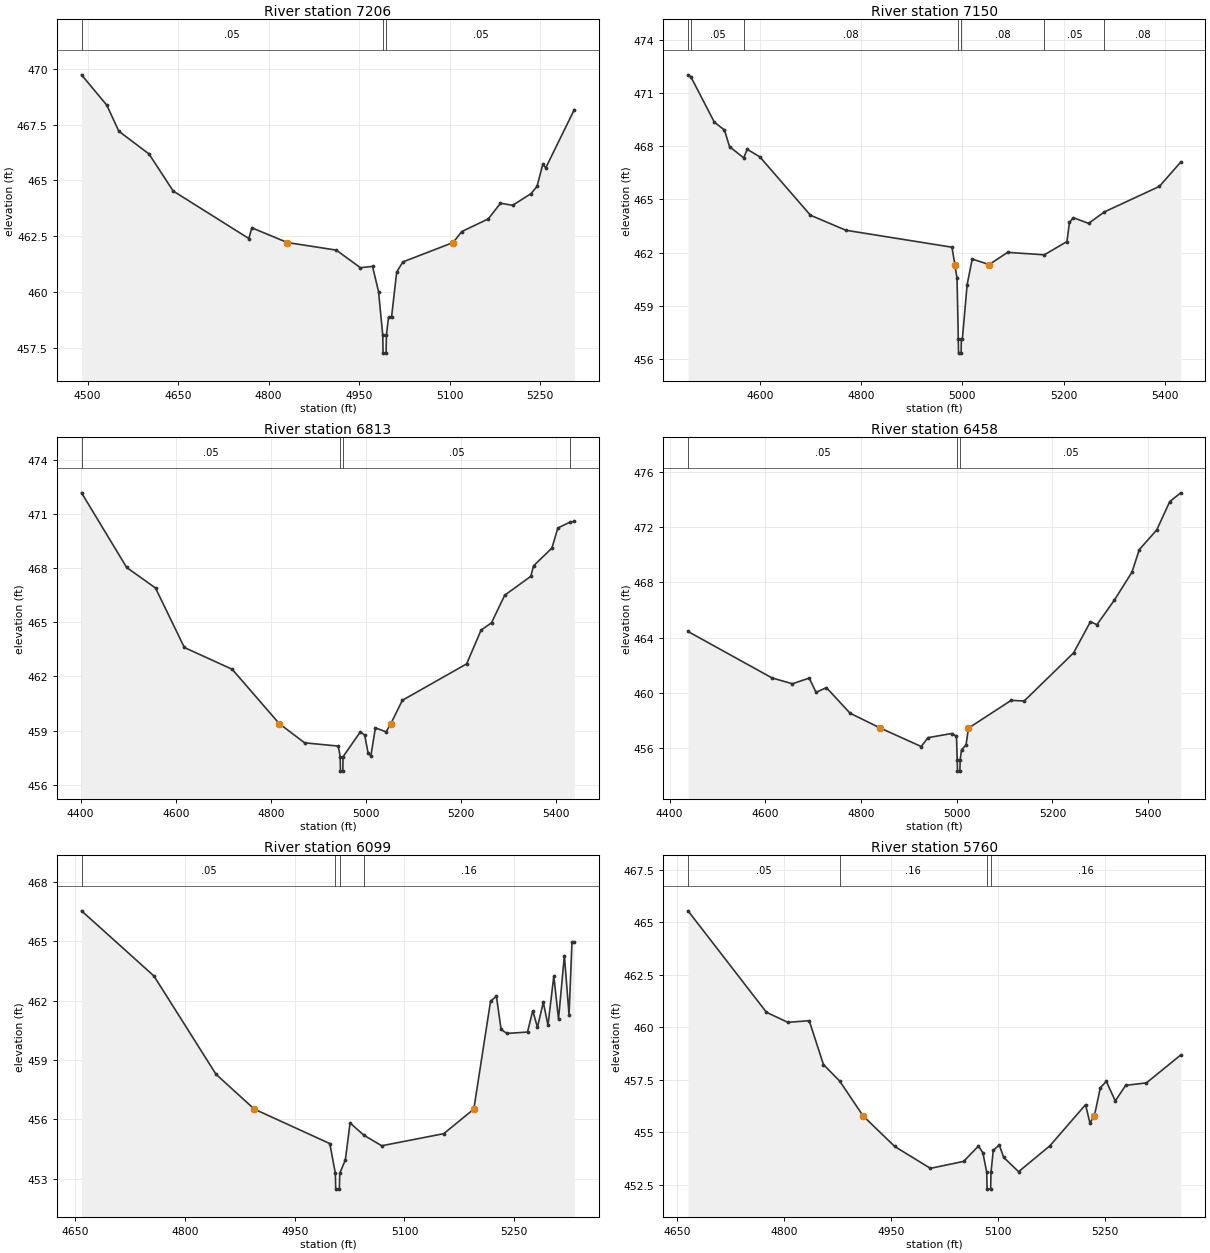
Type RM Length L Ch R = 1,7206,56,56,56
BEGIN DESCRIPTION:
UNT 004 IN DRY CR WATERSHED 14.0
END DESCRIPTION:
XS GIS Cut Line= 3
      2922716.73      7033689.24      2922207.12      7033672.25
      2921904.00      7033717.02
#Sta/Elev= 30
  4490.1  469.73  4531.9  468.37  4551.9  467.20  4601.9  466.18  4641.9  464.52
  4767.2  462.39  4772.2  462.87  4830.9  462.21  4912.1  461.87  4952.1  461.08
  4972.1  461.14  4982.1  460.01  4989.1  458.05  4989.6  457.25  4994.6  457.25
  4995.1  458.05  4998.6  458.86  5003.6  458.86  5012.2  460.89  5022.4  461.34
  5105.6  462.21  5119.9  462.70  5163.9  463.27  5184.1  463.97  5204.3  463.88
  5234.6  464.40  5244.7  464.73  5254.1  465.71  5259.1  465.56  5306.4  468.17
#Mann=3,-1,0
  4490.1    0.05       0  4989.1    0.04       0  4995.1    0.05       0
Bank Sta=4830.9,5105.6
Exp/Cntr=0.3,0.1

Type RM Length L Ch R = 1,7150,337,337,337
BEGIN DESCRIPTION:
Mapping XS 5c958751
END DESCRIPTION:
XS GIS Cut Line= 3
      2922737.11      7033607.64      2922198.96      7033618.49
      2921762.77      7033601.13
#Sta/Elev= 30
  4457.2  472.05  4462.8  471.94  4509.3  469.37  4529.3  468.93  4539.3  467.99
  4567.5  467.35  4574.2  467.84  4599.3  467.41  4699.4  464.11  4769.4  463.26
  4979.4  462.30  4985.0  461.32  4989.4  460.54  4991.9  457.11  4992.4  456.31
  4997.4  456.31  4997.9  457.11  4999.9  457.11  5009.4  460.19  5019.4  461.63
  5053.0  461.32  5089.5  462.01  5162.1  461.87  5206.8  462.62  5211.8  463.71
  5219.6  463.97  5249.6  463.65  5281.1  464.30  5389.7  465.74  5432.0  467.12
#Mann=7,-1,0
  4457.2    0.08       0  4462.8    0.05       0  4567.5    0.08       0
  4991.9    0.07       0  4997.9    0.08       0  5162.1    0.05       0
  5281.1    0.08       0
Bank Sta=4985,5053
Exp/Cntr=0.3,0.1

Type RM Length L Ch R = 1,6813,355,355,355
BEGIN DESCRIPTION:
Mapping XS ef92756c
END DESCRIPTION:
XS GIS Cut Line= 3
      2922578.70      7033251.74      2922036.20      7033334.20
      2921604.35      7033559.90
#Sta/Elev= 30
  4401.9  472.19  4496.7  468.05  4557.4  466.91  4618.0  463.61  4718.6  462.40
  4817.4  459.39  4870.9  458.32  4941.7  458.14  4945.7  457.55  4946.2  456.75
  4951.2  456.75  4951.7  457.55  4988.1  458.93  4997.1  458.75  5004.5  457.74
  5010.2  457.60  5019.7  459.15  5042.2  458.93  5052.3  459.39  5076.4  460.68
  5211.5  462.70  5241.8  464.57  5263.8  464.98  5291.6  466.51  5346.5  467.56
  5352.1  468.14  5390.7  469.12  5403.3  470.24  5429.3  470.57  5437.9  470.60
#Mann=4,-1,0
  4401.9    0.05       0  4945.7    0.03       0  4951.7    0.05       0
  5429.3    0.08       0
Bank Sta=4817.4,5052.3
Exp/Cntr=0.3,0.1

Type RM Length L Ch R = 1,6458,359,359,359
BEGIN DESCRIPTION:
UNT 004 IN DRY CR WATERSHED 13.0
END DESCRIPTION:
XS GIS Cut Line= 3
      2922097.68      7032709.75      2921725.00      7033125.00
      2921474.98      7033525.03
#Sta/Elev= 30
  4438.4  464.44  4614.0  461.08  4656.6  460.66  4691.7  461.07  4705.9  460.04
  4727.6  460.38  4777.0  458.53  4840.5  457.45  4925.7  456.12  4939.9  456.76
  4989.3  457.06  4999.3  456.87  5001.0  455.14  5001.5  454.34  5006.5  454.34
  5007.0  455.14  5009.9  455.88  5019.4  456.24  5024.4  457.45  5113.7  459.46
  5140.8  459.41  5244.0  462.89  5279.4  465.15  5292.9  464.93  5329.5  466.72
  5366.1  468.73  5381.4  470.36  5417.9  471.79  5445.1  473.84  5468.1  474.47
#Mann=3,-1,0
  4438.4    0.05       0  5001.0    0.03       0  5007.0    0.05       0
Bank Sta=4840.5,5024.4
Exp/Cntr=0.3,0.1

Type RM Length L Ch R = 1,6099,339,339,339
BEGIN DESCRIPTION:
UNT 004 IN DRY CR WATERSHED 12.0
END DESCRIPTION:
XS GIS Cut Line= 3
      2921724.98      7032625.02      2921475.00      7032875.00
      2921274.99      7033125.01
#Sta/Elev= 30
  4658.5  466.53  4757.5  463.24  4842.3  458.28  4894.7  456.52  4997.9  454.78
  5005.5  453.28  5006.0  452.48  5011.0  452.48  5011.5  453.28  5019.2  453.96
  5025.6  455.82  5044.6  455.20  5068.9  454.67  5153.7  455.28  5194.8  456.52
  5217.7  461.97  5225.7  462.22  5232.1  460.54  5240.1  460.34  5268.2  460.41
  5275.4  461.49  5281.8  460.65  5289.8  461.91  5296.2  460.76  5304.2  463.24
  5310.6  461.06  5318.6  464.27  5325.0  461.28  5329.0  464.95  5332.2  464.95
#Mann=4,-1,0
  4658.5    0.05       0  5005.5    0.03       0  5011.5    0.05       0
  5044.6    0.16       0
Bank Sta=4894.7,5194.8
Exp/Cntr=0.3,0.1

Type RM Length L Ch R = 1,5760,338,338,338
BEGIN DESCRIPTION:
UNT 004 IN DRY CR WATERSHED 11.0
END DESCRIPTION:
XS GIS Cut Line= 3
      2921675.03      7032575.00      2921325.00      7032575.00
      2921121.41      7032848.77
#Sta/Elev= 30
  4665.7  465.54  4775.7  460.71  4805.7  460.23  4835.7  460.31  4855.7  458.22
  4878.6  457.43  4911.2  455.78  4955.7  454.32  5005.7  453.28  5052.3  453.61
  5073.1  454.34  5079.3  454.02  5084.7  453.09  5085.2  452.29  5090.2  452.29
  5090.7  453.09  5093.9  454.14  5102.3  454.39  5108.5  453.80  5129.4  453.12
  5173.2  454.35  5223.3  456.31  5229.5  455.44  5235.7  455.78  5244.1  457.12
  5252.5  457.42  5265.0  456.49  5279.6  457.23  5308.8  457.35  5356.9  458.68
#Mann=4,-1,0
  4665.7    0.05       0  4878.6    0.16       0  5084.7    0.07       0
  5090.7    0.16       0
Bank Sta=4911.2,5235.7
Exp/Cntr=0.3,0.1

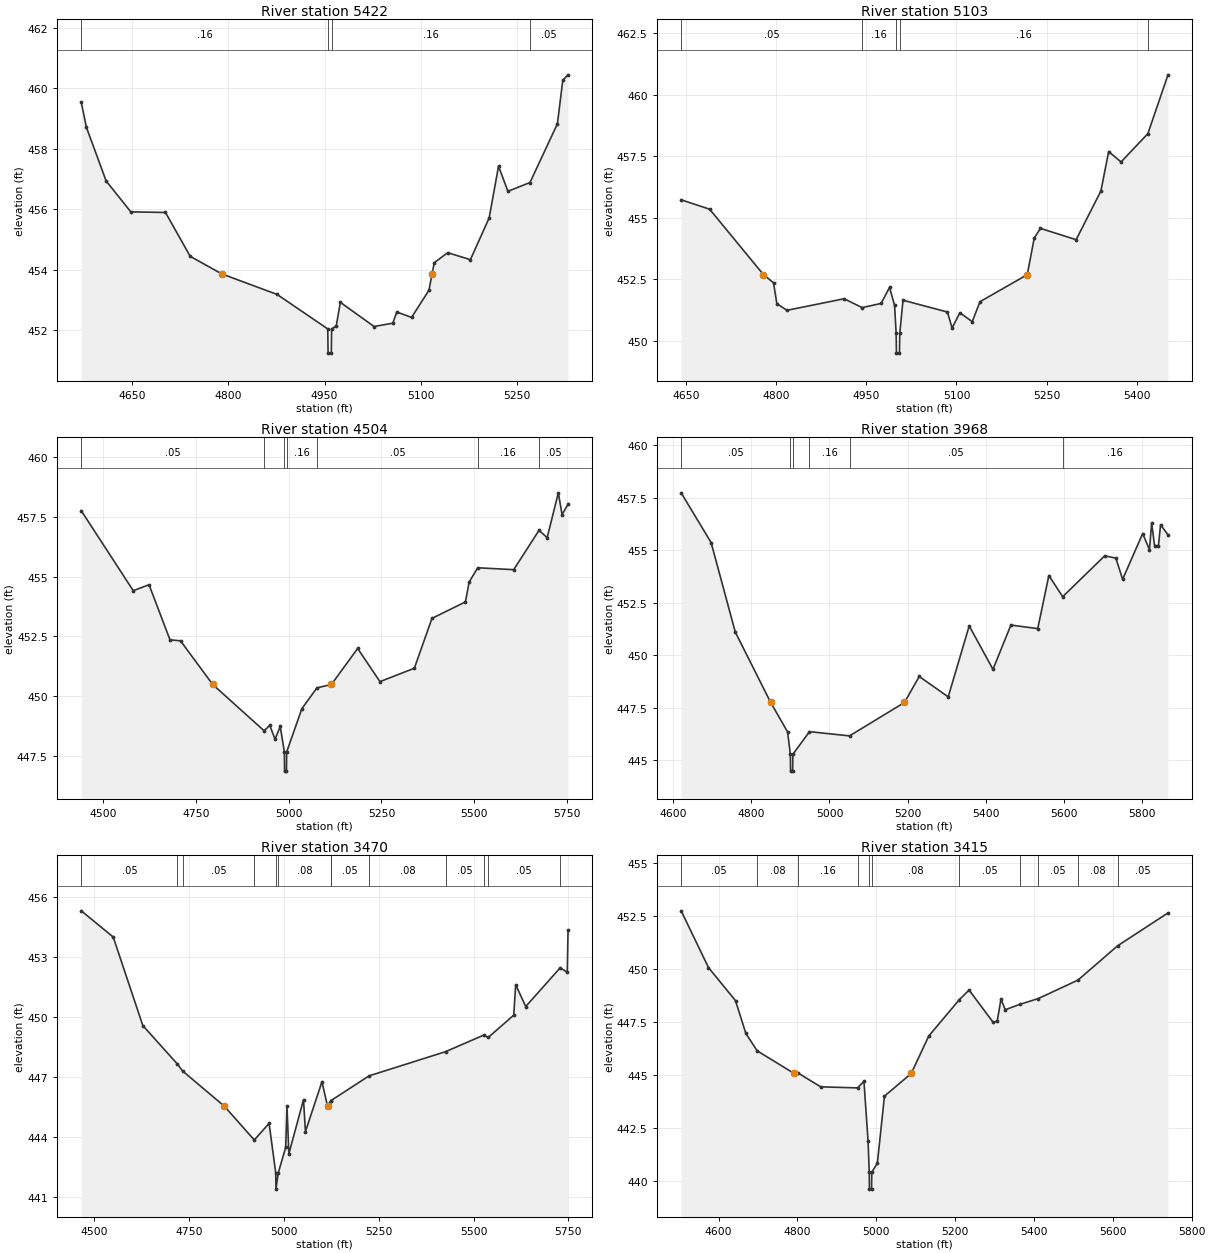
Type RM Length L Ch R = 1,5422,319,319,319
BEGIN DESCRIPTION:
UNT 004 IN DRY CR WATERSHED 10.0
END DESCRIPTION:
XS GIS Cut Line= 3
      2921492.92      7032282.82      2921075.00      7032375.00
      2920877.49      7032639.78
#Sta/Elev= 30
  4571.0  459.54  4579.1  458.71  4609.8  456.94  4648.2  455.92  4702.2  455.90
  4740.7  454.45  4789.8  453.87  4876.1  453.19  4955.0  452.05  4955.5  451.25
  4960.5  451.25  4961.0  452.05  4968.2  452.15  4974.6  452.93  5027.1  452.13
  5056.3  452.24  5062.5  452.61  5085.5  452.43  5112.6  453.33  5117.5  453.87
  5120.9  454.24  5141.8  454.57  5177.2  454.34  5206.4  455.72  5221.0  457.43
  5235.6  456.60  5270.0  456.89  5312.7  458.83  5321.1  460.27  5329.3  460.45
#Mann=4,-1,0
  4571.0    0.16       0  4955.0    0.07       0  4961.0    0.16       0
  5270.0    0.05       0
Bank Sta=4789.8,5117.5
Exp/Cntr=0.3,0.1

Type RM Length L Ch R = 1,5103,599,599,599
BEGIN DESCRIPTION:
UNT 004 IN DRY CR WATERSHED 9.0
END DESCRIPTION:
XS GIS Cut Line= 3
      2921224.84      7031950.08      2920875.00      7032125.00
      2920773.58      7032530.68
#Sta/Elev= 30
  4642.3  455.72  4689.6  455.34  4779.1  452.68  4795.8  452.35  4801.4  451.50
  4818.2  451.23  4913.2  451.70  4943.2  451.34  4974.7  451.51  4988.7  452.16
  4997.1  451.43  4999.7  450.29  5000.2  449.49  5005.2  449.49  5005.7  450.29
  5011.1  451.64  5085.0  451.16  5092.7  450.51  5105.6  451.13  5126.2  450.77
  5139.1  451.58  5217.7  452.68  5229.3  454.17  5239.6  454.56  5298.9  454.10
  5340.1  456.08  5353.0  457.68  5373.6  457.26  5418.2  458.41  5451.6  460.80
#Mann=5,-1,0
  4642.3    0.05       0  4943.2    0.16       0  4999.7    0.07       0
  5005.7    0.16       0  5418.2    0.05       0
Bank Sta=4779.1,5217.7
Exp/Cntr=0.3,0.1

Type RM Length L Ch R = 1,4504,536,536,536
BEGIN DESCRIPTION:
UNT 004 IN DRY CR WATERSHED 8.0
END DESCRIPTION:
XS GIS Cut Line= 3
      2920924.10      7031275.90      2920525.00      7031675.00
      2920558.92      7032421.22
#Sta/Elev= 30
  4441.3  457.76  4581.4  454.41  4623.9  454.66  4680.4  452.35  4708.7  452.31
  4795.4  450.48  4934.0  448.54  4949.1  448.77  4963.3  448.19  4977.4  448.72
  4988.5  447.65  4989.0  446.85  4994.1  446.85  4994.6  447.65  5035.7  449.47
  5076.3  450.34  5115.2  450.48  5185.9  451.99  5246.0  450.60  5338.6  451.16
  5386.1  453.25  5476.2  453.94  5486.2  454.77  5509.3  455.37  5606.3  455.29
  5674.5  456.94  5696.4  456.63  5726.5  458.51  5736.5  457.60  5752.7  458.03
#Mann=7,-1,0
  4441.3    0.05       0  4934.0    0.16       0  4988.5    0.07       0
  4994.6    0.16       0  5076.3    0.05       0  5509.3    0.16       0
  5674.5    0.05       0
Bank Sta=4795.4,5115.2
Exp/Cntr=0.3,0.1

Type RM Length L Ch R = 1,3968,498,498,498
BEGIN DESCRIPTION:
UNT 004 IN DRY CR WATERSHED 7.0
END DESCRIPTION:
XS GIS Cut Line= 3
      2920121.57      7031280.63      2920025.00      7031675.00
      2920378.39      7032436.14
#Sta/Elev= 30
  4620.6  457.74  4697.2  455.37  4758.9  451.11  4849.6  447.75  4892.8  446.35
  4899.9  445.28  4900.4  444.48  4905.7  444.48  4906.2  445.28  4948.8  446.36
  5051.3  446.16  5191.8  447.75  5229.5  448.99  5303.7  448.02  5357.4  451.40
  5418.2  449.33  5464.0  451.44  5532.7  451.27  5561.1  453.80  5596.5  452.79
  5704.0  454.74  5732.5  454.63  5749.8  453.62  5801.1  455.80  5818.5  455.03
  5824.0  456.31  5831.5  455.23  5841.4  455.22  5846.9  456.22  5865.8  455.74
#Mann=6,-1,0
  4620.6    0.05       0  4899.9    0.07       0  4906.2    0.05       0
  4948.8    0.16       0  5051.3    0.05       0  5596.5    0.16       0
Bank Sta=4849.6,5191.8
Exp/Cntr=0.3,0.1

Type RM Length L Ch R = 1,3470,55,55,55
BEGIN DESCRIPTION:
Mapping XS 13a8635c
END DESCRIPTION:
XS GIS Cut Line= 3
      2919441.01      7031304.02      2919568.62      7031824.87
      2919730.04      7032553.86
#Sta/Elev= 30
  4466.1  455.31  4550.3  454.00  4628.3  449.57  4719.5  447.64  4733.3  447.29
  4843.2  445.53  4922.1  443.84  4961.1  444.67  4978.7  442.18  4979.2  441.38
  4985.1  442.18  5005.0  443.48  5008.2  445.54  5013.3  443.15  5051.8  445.86
  5056.9  444.26  5100.5  446.76  5115.1  445.53  5123.8  445.80  5124.0  445.81
  5224.7  447.05  5426.1  448.26  5526.9  449.09  5538.6  448.97  5605.9  450.09
  5611.0  451.61  5637.5  450.52  5728.3  452.46  5746.9  452.23  5749.0  454.34
#Mann=13,-1,0
  4466.1    0.05       0  4719.5    0.08       0  4733.3    0.05       0
  4922.1    0.08       0  4978.7    0.07       0  4985.1    0.08       0
  5123.8    0.16       0  5124.0    0.05       0  5224.7    0.08       0
  5426.1    0.05       0  5526.9    0.08       0  5538.6    0.05       0
  5728.3    0.08       0
Bank Sta=4843.2,5115.1
Exp/Cntr=0.3,0.1

Type RM Length L Ch R = 1,3415,527,527,527
BEGIN DESCRIPTION:
UNT 004 IN DRY CR WATERSHED 6.0
END DESCRIPTION:
XS GIS Cut Line= 3
      2919357.70      7031365.28      2919514.38      7031834.62
      2919665.85      7032558.84
#Sta/Elev= 30
  4505.2  452.75  4574.5  450.07  4643.0  448.51  4669.3  446.96  4698.0  446.14
  4791.9  445.07  4802.0  445.09  4859.0  444.44  4952.6  444.39  4968.8  444.70
  4979.3  441.87  4982.2  440.41  4982.7  439.61  4988.1  439.61  4988.6  440.41
  5002.8  440.83  5020.8  444.00  5088.7  445.07  5133.2  446.84  5210.4  448.55
  5235.4  449.01  5296.7  447.48  5306.9  447.55  5316.3  448.58  5327.3  448.08
  5365.1  448.34  5411.3  448.61  5511.7  449.48  5612.2  451.10  5739.9  452.65
#Mann=11,-1,0
  4505.2    0.05       0  4698.0    0.08       0  4802.0    0.16       0
  4952.6    0.08       0  4982.2    0.07       0  4988.6    0.08       0
  5210.4    0.05       0  5365.1    0.08       0  5411.3    0.05       0
  5511.7    0.08       0  5612.2    0.05       0
Bank Sta=4791.9,5088.7
Exp/Cntr=0.3,0.1

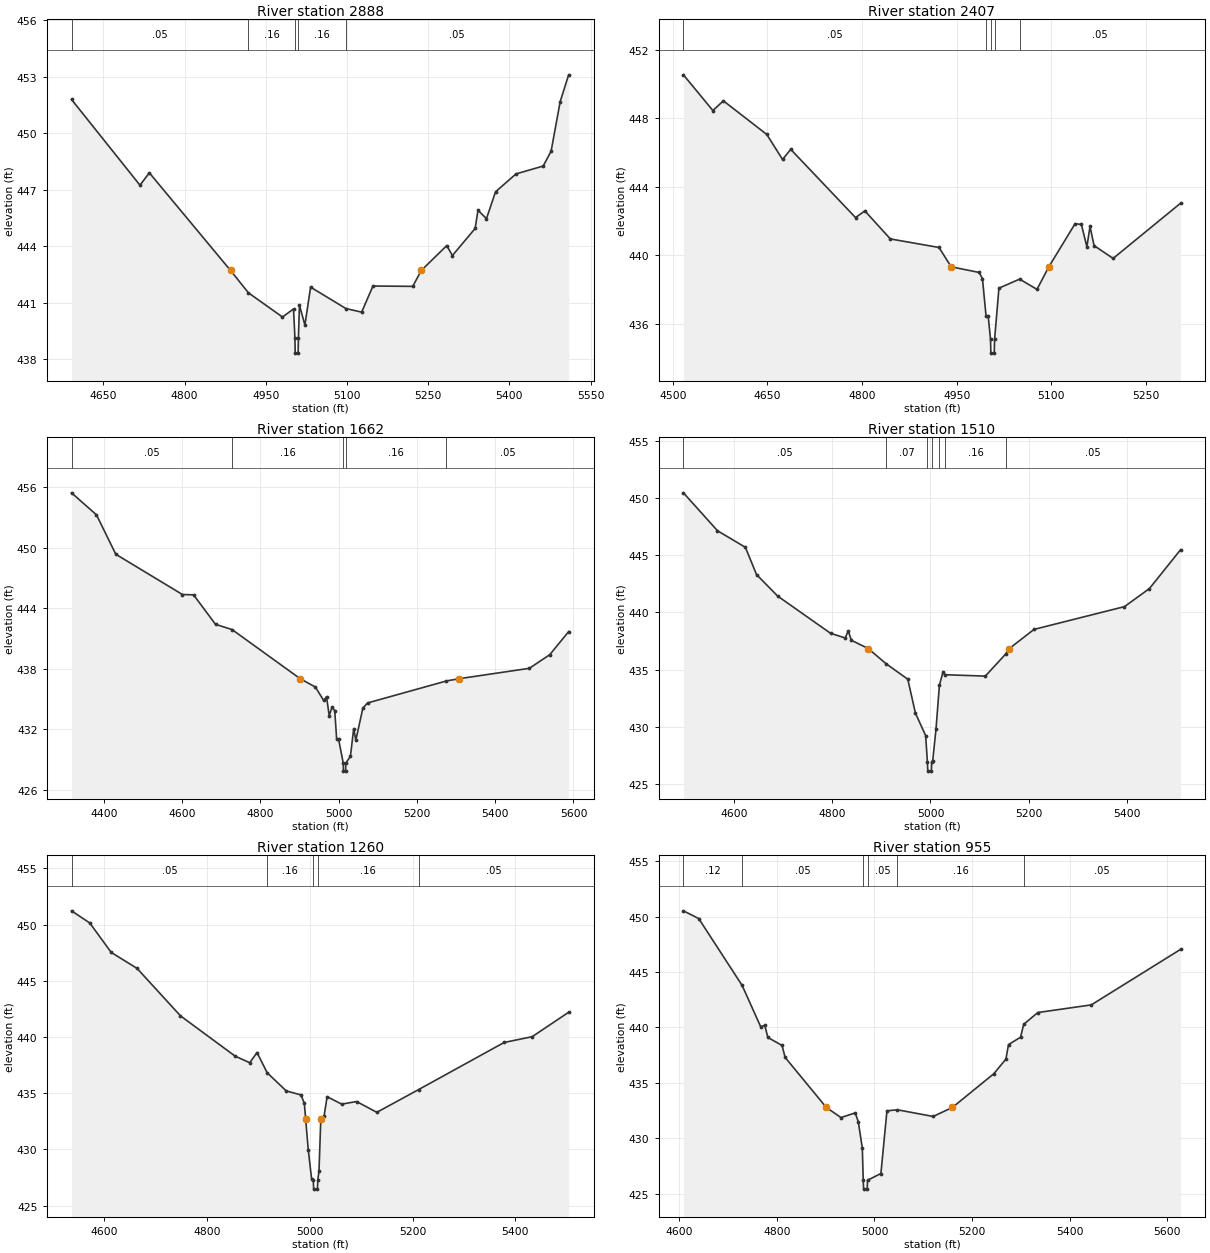
Type RM Length L Ch R = 1,2888,481,481,481
BEGIN DESCRIPTION:
UNT 004 IN DRY CR WATERSHED 5.0
END DESCRIPTION:
XS GIS Cut Line= 3
      2919163.24      7031300.14      2919025.00      7031675.00
      2919180.03      7032169.85
#Sta/Elev= 30
  4591.3  451.80  4717.7  447.24  4735.0  447.90  4884.9  442.71  4917.9  441.52
  4980.9  440.23  5001.3  440.66  5003.9  439.11  5004.4  438.31  5009.8  438.31
  5010.3  439.11  5012.3  440.86  5022.3  439.80  5032.8  441.82  5098.1  440.68
  5127.1  440.49  5148.0  441.88  5221.4  441.86  5237.4  442.71  5284.3  444.03
  5294.7  443.50  5336.7  444.94  5342.0  445.91  5357.6  445.46  5374.4  446.89
  5412.1  447.84  5462.4  448.26  5477.0  449.05  5493.8  451.69  5509.4  453.11
#Mann=5,-1,0
  4591.3    0.05       0  4917.9    0.16       0  5003.9    0.07       0
  5010.3    0.16       0  5098.1    0.05       0
Bank Sta=4884.9,5237.4
Exp/Cntr=0.3,0.1

Type RM Length L Ch R = 1,2407,745,745,745
BEGIN DESCRIPTION:
UNT 004 IN DRY CR WATERSHED 4.0
END DESCRIPTION:
XS GIS Cut Line= 3
      2918736.16      7031105.69      2918566.67      7031558.09
      2918534.91      7031861.33
#Sta/Elev= 30
  4516.9  450.55  4563.6  448.46  4580.2  449.03  4649.1  447.06  4674.0  445.60
  4687.0  446.19  4789.7  442.20  4804.5  442.59  4844.9  440.95  4922.0  440.45
  4941.3  439.32  4985.6  438.99  4990.9  438.63  4996.6  436.43  5000.0  436.43
  5003.7  435.07  5004.2  434.27  5009.6  434.27  5010.1  435.07  5017.0  438.07
  5049.8  438.60  5077.3  438.00  5096.1  439.32  5137.7  441.84  5147.7  441.80
  5156.4  440.49  5161.4  441.68  5167.8  440.56  5198.0  439.81  5304.9  443.04
#Mann=5,-1,0
  4516.9    0.05       0  4996.6    0.16       0  5003.7    0.07       0
  5010.1    0.16       0  5049.8    0.05       0
Bank Sta=4941.3,5096.1
Exp/Cntr=0.3,0.1

Type RM Length L Ch R = 1,1662,152,152,152
BEGIN DESCRIPTION:
UNT 004 IN DRY CR WATERSHED 3.0
END DESCRIPTION:
XS GIS Cut Line= 3
      2918425.01      7030674.99      2917963.40      7031177.30
      2918198.41      7031715.97
#Sta/Elev= 30
  4317.8  455.47  4381.6  453.28  4430.9  449.37  4601.1  445.37  4629.5  445.34
  4685.6  442.41  4727.9  441.89  4901.9  437.01  4940.8  436.18  4961.8  434.85
  4969.2  435.22  4976.0  433.35  4983.3  434.18  4990.2  433.84  4995.1  431.00
  5000.0  431.00  5011.9  428.63  5012.4  427.83  5017.9  427.83  5018.4  428.63
  5030.2  429.29  5038.6  432.05  5044.1  430.91  5062.0  434.08  5073.9  434.60
  5275.1  436.78  5307.9  437.01  5487.3  438.04  5539.6  439.40  5587.7  441.69
#Mann=5,-1,0
  4317.8    0.05       0  4727.9    0.16       0  5011.9    0.07       0
  5018.4    0.16       0  5275.1    0.05       0
Bank Sta=4901.9,5307.9
Exp/Cntr=0.3,0.1

Type RM Length L Ch R = 1,1510,250,250,250
BEGIN DESCRIPTION:
Mapping XS 8c5277e7
END DESCRIPTION:
XS GIS Cut Line= 3
      2918128.41      7030681.76      2917871.45      7031060.25
      2917524.23      7031494.28
#Sta/Elev= 30
  4496.4  450.45  4565.8  447.14  4622.7  445.69  4645.4  443.31  4688.5  441.43
  4796.3  438.18  4826.2  437.77  4832.3  438.40  4838.7  437.57  4873.0  436.85
  4909.5  435.52  4953.7  434.17  4969.3  431.20  4990.1  429.25  4993.7  426.94
  4994.5  426.14  5001.7  426.14  5002.5  426.94  5004.5  427.05  5011.2  429.80
  5018.2  433.65  5025.3  434.76  5030.0  434.56  5111.8  434.44  5153.0  436.36
  5160.7  436.85  5211.0  438.52  5395.4  440.51  5446.3  442.09  5509.7  445.48
#Mann=7,-1,0
  4496.4    0.05       0  4909.5    0.07       0  4993.7    0.07       0
  5002.5    0.07       0  5018.2    0.12       0  5030.0    0.16       0
  5153.0    0.05       0
Bank Sta=4873,5160.7
Exp/Cntr=0.3,0.1

Type RM Length L Ch R = 1,1260,305,305,305
BEGIN DESCRIPTION:
UNT 004 IN DRY CR WATERSHED 2.0
END DESCRIPTION:
XS GIS Cut Line= 3
      2917996.45      7030556.78      2917675.00      7030925.00
      2917472.16      7031358.83
#Sta/Elev= 30
  4536.1  451.22  4571.6  450.14  4613.4  447.52  4663.7  446.10  4748.2  441.88
  4854.5  438.30  4883.0  437.71  4897.2  438.62  4916.9  436.82  4954.2  435.20
  4982.7  434.85  4989.3  434.10  4991.8  432.73  4996.9  429.98  5003.5  427.35
  5006.7  427.27  5007.5  426.47  5014.7  426.47  5015.5  427.27  5017.8  428.07
  5021.4  432.73  5027.6  432.93  5033.6  434.69  5061.9  434.03  5091.1  434.26
  5130.4  433.30  5211.6  435.32  5378.1  439.51  5432.9  440.03  5503.8  442.20
#Mann=5,-1,0
  4536.1    0.05       0  4916.9    0.16       0  5006.7    0.07       0
  5015.5    0.16       0  5211.6    0.05       0
Bank Sta=4991.8,5021.4
Exp/Cntr=0.3,0.1

Type RM Length L Ch R = 1,955,418,418,418
BEGIN DESCRIPTION:
Mapping XS d56ef818
END DESCRIPTION:
XS GIS Cut Line= 3
      2917722.15      7030369.27      2917489.51      7030678.31
      2917263.80      7031268.61
#Sta/Elev= 30
  4608.5  450.53  4639.9  449.83  4728.9  443.79  4766.9  440.06  4775.2  440.20
  4781.5  439.10  4810.6  438.38  4816.9  437.30  4901.4  432.78  4931.4  431.87
  4960.6  432.29  4966.8  431.50  4975.1  429.12  4977.0  426.21  4977.8  425.41
  4985.0  425.41  4985.8  426.21  5013.2  426.82  5025.6  432.48  5047.1  432.57
  5120.2  431.97  5159.7  432.78  5244.7  435.83  5269.4  437.15  5274.7  438.46
  5299.4  439.12  5305.9  440.29  5334.8  441.35  5444.4  442.04  5627.3  447.05
#Mann=6,-1,0
  4608.5    0.12       0  4728.9    0.05       0  4977.0    0.03       0
  4985.8    0.05       0  5047.1    0.16       0  5305.9    0.05       0
Bank Sta=4901.4,5159.7
Exp/Cntr=0.3,0.1

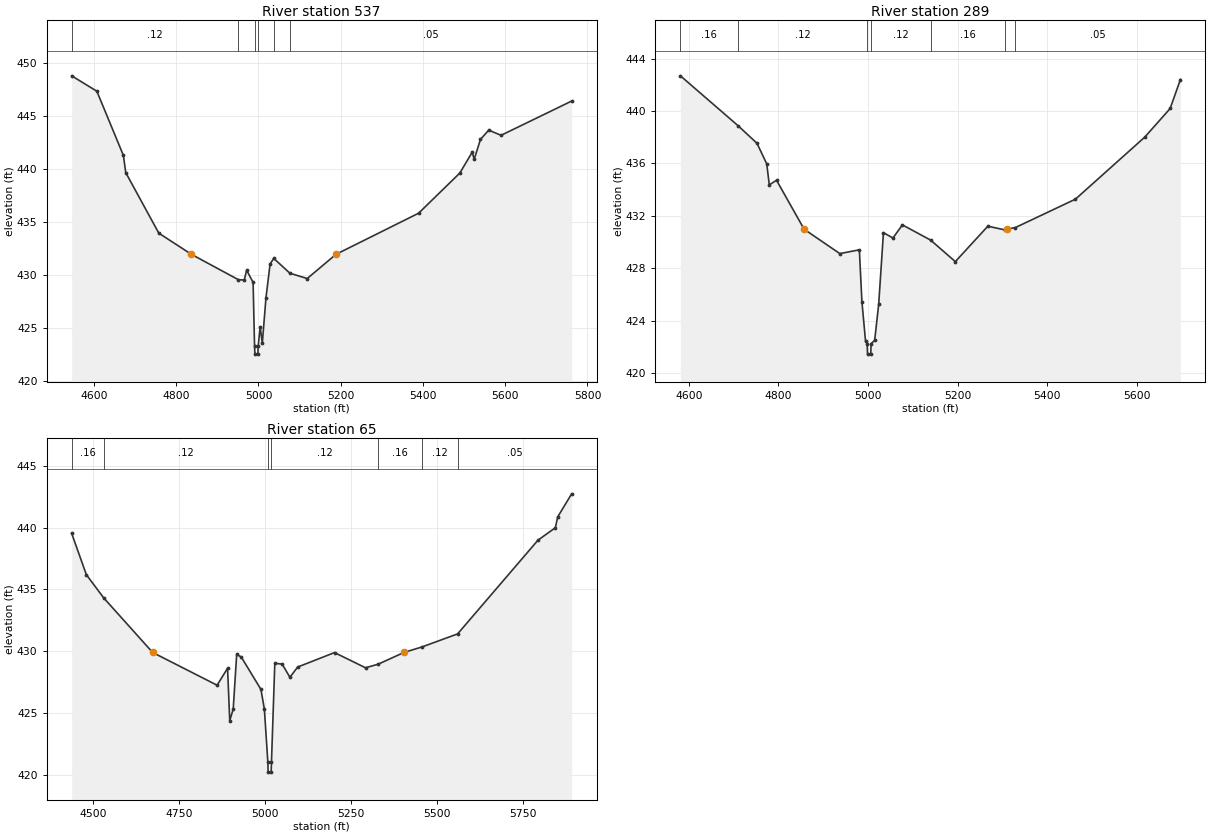
Type RM Length L Ch R = 1,537,248,248,248
BEGIN DESCRIPTION:
Mapping XS 01e5fa27
END DESCRIPTION:
XS GIS Cut Line= 3
      2917538.13      7030216.50      2917149.23      7030442.19
      2917208.26      7031206.08
#Sta/Elev= 30
  4545.7  448.82  4606.9  447.37  4671.5  441.31  4677.2  439.69  4757.6  433.98
  4837.0  431.98  4951.2  429.59  4965.4  429.56  4971.2  430.49  4986.9  429.33
  4990.4  423.37  4991.3  422.57  4998.5  422.57  4999.3  423.37  5004.2  425.13
  5009.3  423.60  5018.2  427.89  5028.2  431.07  5037.1  431.60  5076.4  430.20
  5118.5  429.70  5188.3  431.98  5389.3  435.86  5489.6  439.65  5519.6  441.61
  5524.6  440.96  5539.8  442.82  5559.8  443.70  5589.9  443.21  5761.5  446.44
#Mann=6,-1,0
  4545.7    0.12       0  4951.2    0.16       0  4990.4    0.07       0
  4999.3    0.16       0  5037.1    0.16       0  5076.4    0.05       0
Bank Sta=4837,5188.3
Exp/Cntr=0.3,0.1

Type RM Length L Ch R = 1,289,224,224,224
BEGIN DESCRIPTION:
Mapping XS f37303c5
END DESCRIPTION:
XS GIS Cut Line= 3
      2917307.91      7030126.86      2916930.31      7030333.02
      2917157.84      7030980.92
#Sta/Elev= 30
  4581.0  442.68  4709.7  438.88  4752.0  437.54  4773.8  435.97  4779.5  434.37
  4795.7  434.72  4857.3  430.99  4937.1  429.13  4980.7  429.42  4986.4  425.47
  4994.5  422.47  4998.1  422.27  4998.9  421.47  5006.1  421.47  5007.0  422.27
  5014.9  422.52  5023.9  425.27  5034.5  430.73  5055.7  430.32  5076.9  431.32
  5139.9  430.16  5195.1  428.52  5267.7  431.22  5306.9  430.93  5309.4  430.99
  5329.4  431.12  5463.4  433.28  5618.3  438.01  5675.0  440.19  5697.9  442.40
#Mann=7,-1,0
  4581.0    0.16       0  4709.7    0.12       0  4998.1    0.07       0
  5007.0    0.12       0  5139.9    0.16       0  5306.9    0.12       0
  5329.4    0.05       0
Bank Sta=4857.3,5309.4
Exp/Cntr=0.3,0.1

Type RM Length L Ch R = 1,65,0,0,0
BEGIN DESCRIPTION:
UNT 004 IN DRY CR WATERSHED 1.0
END DESCRIPTION:
XS GIS Cut Line= 4
      2917227.66      7030086.93      2916774.50      7030088.67
      2916757.14      7030234.50      2917131.21      7031001.52
#Sta/Elev= 30
  4437.7  439.53  4480.4  436.19  4530.6  434.32  4673.1  429.90  4860.4  427.25
  4890.9  428.62  4897.2  424.38  4907.3  425.32  4917.4  429.74  4930.7  429.53
  4987.9  426.91  4997.9  425.31  5008.0  421.02  5008.9  420.22  5017.6  420.22
  5018.5  421.02  5028.2  429.02  5049.6  428.96  5072.1  427.89  5094.7  428.72
  5201.8  429.89  5291.9  428.66  5328.7  428.95  5403.7  429.90  5455.5  430.34
  5559.6  431.40  5793.2  438.98  5843.8  439.99  5850.5  440.86  5891.1  442.73
#Mann=7,-1,0
  4437.7    0.16       0  4530.6    0.12       0  5008.0    0.07       0
  5018.5    0.12       0  5328.7    0.16       0  5455.5    0.12       0
  5559.6    0.05       0
Bank Sta=4673.1,5403.7
Exp/Cntr=0.3,0.1

Chan Stop Cuts=-1