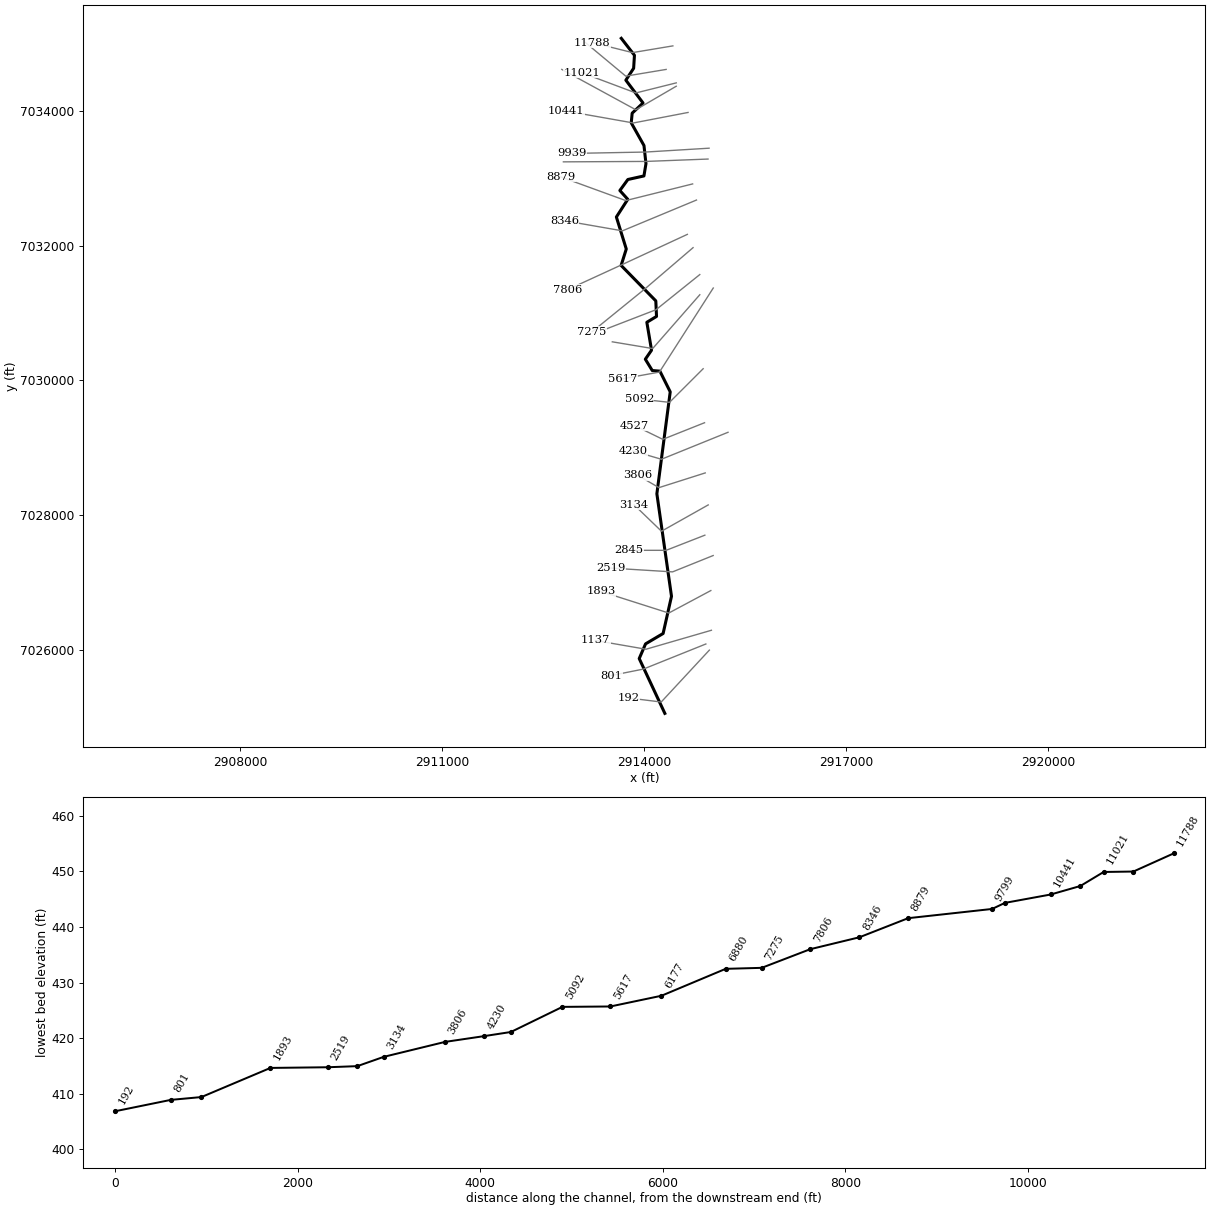
--- UNT 005 IN DRY CR WATERSHED.prj (project) ---

Proj Title=UNT 005 IN DRY CR WATERSHED Base Level Engineering
Current Plan=p01
Default Exp/Contr=0.3,0.1
English Units
Geom File=g01
Flow File=f01
Plan File=p01
BEGIN DESCRIPTION:
UNT 005 IN DRY CR WATERSHED
END DESCRIPTION:

--- UNT 005 IN DRY CR WATERSHED.p01 (plan) ---

Plan Title=Multiple Run
Short Identifier=Multiple
Geom File=g01
Flow File=f01
Subcritical Flow
K Sum by GR= 0
Std Step Tol= 0.01
Critical Tol= 0.01
Num of Std Step Trials= 20
Max Error Tol= 0.3
Flow Tol Ratio= 0.001
Split Flow NTrial= 30
Split Flow Tol= 0.02
Split Flow Ratio= 0.02
Log Output Level= 0
Friction Slope Method= 1
Unsteady Friction Slope Method= 2
Unsteady Bridges Friction Slope Method= 1
Parabolic Critical Depth
Global Vel Dist=  1 , 1 , 1
Global Log Level= 0
CheckData=True
Encroach Param= -1, 0, 0, 0
BEGIN DESCRIPTION:
Multiple Run
END DESCRIPTION:

--- UNT 005 IN DRY CR WATERSHED.f01 (steady flow) ---

Flow Title=Multiple
Number of Profiles=7
Profile Names=10-year,25-year,50-year,1pct_min,100-year,1pct_plu,500-year
River Rch & RM= UNT 005 IN DRY C,Reach-1,11788
     610     823     998     602    1201    2395    1741
River Rch & RM= UNT 005 IN DRY C,Reach-1,10441
     844    1155    1413     859    1713    3418    2523
River Rch & RM= UNT 005 IN DRY C,Reach-1,2845
     965    1329    1632     995    1985    3960    2943
Boundary for River Rch & Prof#=UNT 005 IN DRY C,Reach-1,1
Up Type=0
Dn Type=3
Dn Slope=0.005
Boundary for River Rch & Prof#=UNT 005 IN DRY C,Reach-1,2
Up Type=0
Dn Type=3
Dn Slope=0.005
Boundary for River Rch & Prof#=UNT 005 IN DRY C,Reach-1,3
Up Type=0
Dn Type=3
Dn Slope=0.005
Boundary for River Rch & Prof#=UNT 005 IN DRY C,Reach-1,4
Up Type=0
Dn Type=3
Dn Slope=0.005
Boundary for River Rch & Prof#=UNT 005 IN DRY C,Reach-1,5
Up Type=0
Dn Type=3
Dn Slope=0.005
Boundary for River Rch & Prof#=UNT 005 IN DRY C,Reach-1,6
Up Type=0
Dn Type=3
Dn Slope=0.005
Boundary for River Rch & Prof#=UNT 005 IN DRY C,Reach-1,7
Up Type=0
Dn Type=3
Dn Slope=0.005

--- UNT 005 IN DRY CR WATERSHED.g01 (geometry) ---

Geom Title=Existing Conditions

River Reach=UNT 005 IN DRY C,Reach-1
Reach XY= 30
      2913658.57      7035087.23      2913854.04      7034835.32
      2913842.03      7034642.07      2913726.20      7034465.28
      2913981.78      7034125.99      2913820.32      7033974.95
      2913806.44      7033830.85      2913995.67      7033493.18
      2914025.19      7033224.08      2913995.01      7033041.26
      2913756.28      7032988.41      2913637.23      7032824.64
      2913754.96      7032693.89      2913585.59      7032430.71
      2913732.65      7031954.87      2913656.21      7031710.75
      2914171.44      7031183.61      2914182.00      7030952.58
      2914038.24      7030865.36      2914108.06      7030450.58
      2914015.69      7030316.45      2914118.95      7030147.73
      2914232.16      7030139.10      2914385.53      7029831.31
      2914187.18      7028315.71      2914404.48      7026791.22
      2914279.97      7026238.29      2914019.25      7026084.14
      2913924.97      7025865.72      2914305.59      7025050.71

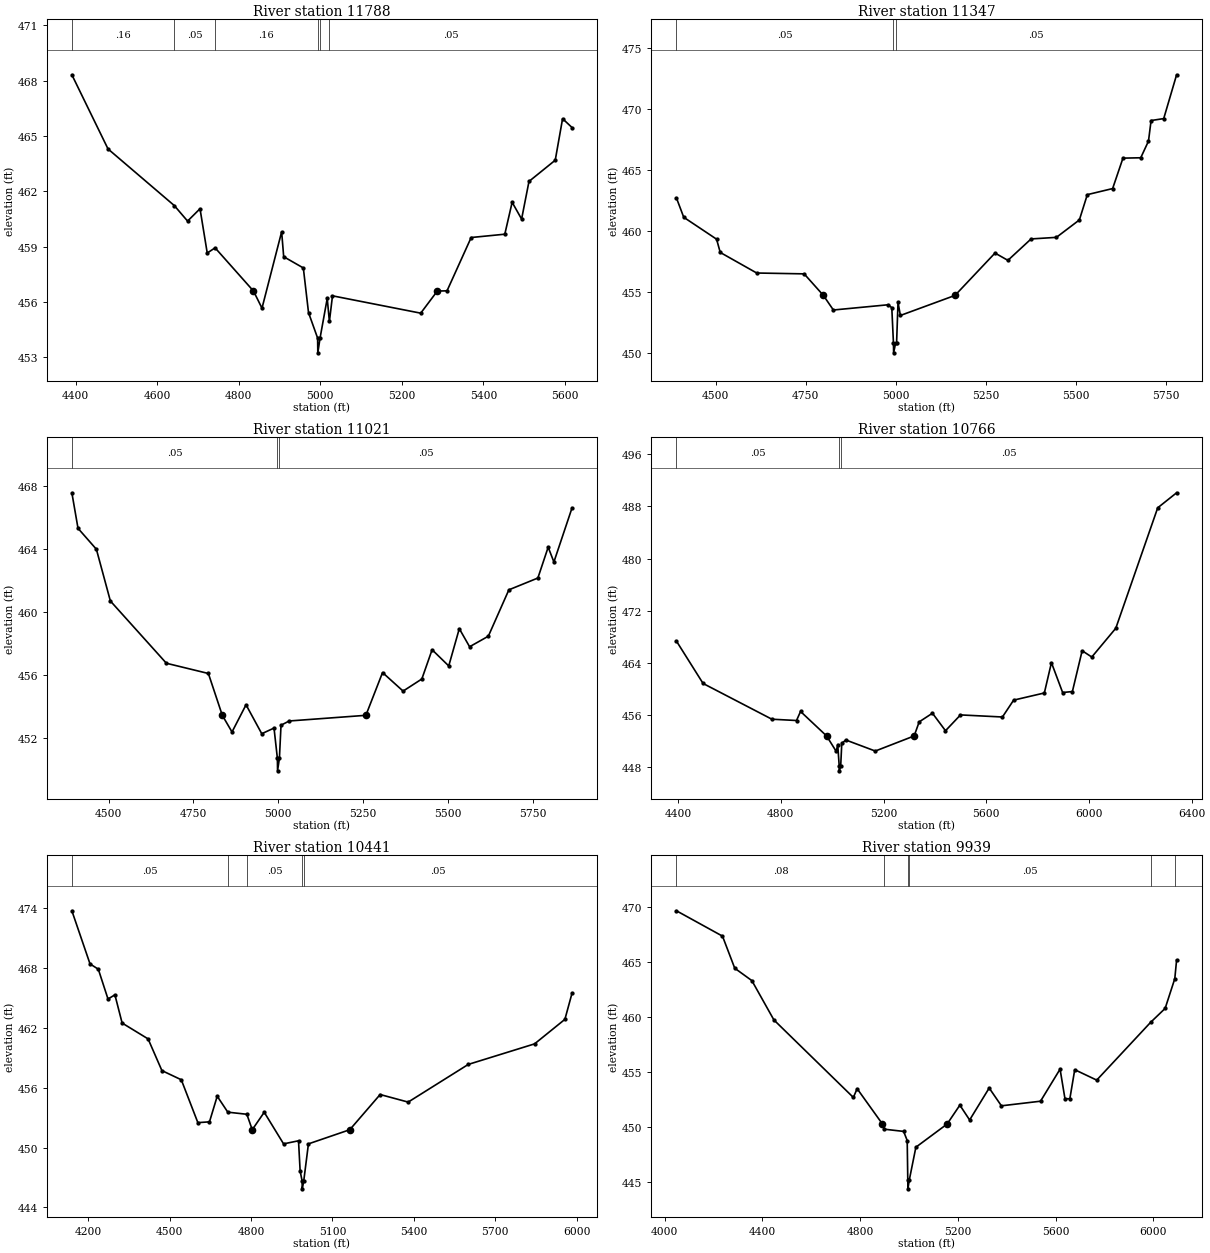
Type RM Length L Ch R = 1,11788,441,441,441
BEGIN DESCRIPTION:
UNT 005 IN DRY CR WATERSHED 18.0
END DESCRIPTION:
XS GIS Cut Line= 3
      2914424.98      7034975.00      2913825.00      7034875.00
      2913225.02      7035025.00
#Sta/Elev= 30
  4390.7  468.32  4479.4  464.30  4642.0  461.23  4674.5  460.39  4705.0  461.06
  4722.7  458.66  4742.0  458.94  4836.1  456.60  4857.0  455.67  4905.2  459.81
  4910.2  458.46  4958.4  457.85  4971.1  455.43  4993.4  454.05  4993.9  453.25
  4999.4  454.05  5017.0  456.20  5022.3  454.95  5029.9  456.34  5246.3  455.40
  5287.0  456.60  5310.8  456.61  5370.0  459.50  5452.5  459.68  5470.5  461.41
  5493.7  460.50  5511.8  462.54  5576.2  463.69  5594.2  465.94  5617.4  465.46
#Mann=6,-1,0
  4390.7    0.16       0  4642.0    0.05       0  4742.0    0.16       0
  4993.4    0.07       0  4999.4    0.16       0  5022.3    0.05       0
Bank Sta=4836.1,5287
Exp/Cntr=0.3,0.1

Type RM Length L Ch R = 1,11347,326,326,326
BEGIN DESCRIPTION:
UNT 005 IN DRY CR WATERSHED 17.0
END DESCRIPTION:
XS GIS Cut Line= 3
      2914325.01      7034625.00      2913725.00      7034525.00
      2913125.01      7035024.99
#Sta/Elev= 30
  4390.6  462.72  4410.9  461.13  4502.1  459.33  4512.3  458.24  4613.6  456.55
  4745.4  456.48  4798.8  454.71  4826.5  453.51  4978.6  453.94  4988.8  453.70
  4993.4  450.79  4993.9  449.99  4999.4  450.79  5002.1  450.79  5006.1  454.14
  5012.6  453.06  5164.4  454.71  5275.5  458.19  5311.3  457.59  5375.7  459.35
  5446.0  459.48  5509.8  460.91  5531.9  462.99  5602.2  463.49  5630.9  465.99
  5680.3  466.02  5701.8  467.39  5709.0  469.08  5744.1  469.24  5779.9  472.84
#Mann=3,-1,0
  4390.6    0.05       0  4993.4    0.03       0  4999.4    0.05       0
Bank Sta=4798.8,5164.4
Exp/Cntr=0.3,0.1

Type RM Length L Ch R = 1,11021,255,255,255
BEGIN DESCRIPTION:
UNT 005 IN DRY CR WATERSHED 16.0
END DESCRIPTION:
XS GIS Cut Line= 3
      2914475.04      7034425.01      2913875.00      7034275.00
      2913075.01      7034575.00
#Sta/Elev= 30
  4392.1  467.59  4410.2  465.33  4464.3  464.00  4505.5  460.71  4670.5  456.75
  4794.1  456.10  4835.1  453.44  4863.7  452.38  4905.0  454.11  4951.3  452.27
  4987.4  452.63  4997.3  450.71  4997.8  449.91  5003.3  450.71  5008.0  452.81
  5032.0  453.08  5257.9  453.44  5307.0  456.16  5367.5  454.98  5422.7  455.75
  5452.9  457.61  5501.9  456.58  5533.0  458.95  5563.3  457.80  5618.5  458.47
  5679.0  461.42  5764.4  462.17  5794.7  464.13  5811.6  463.19  5865.0  466.63
#Mann=3,-1,0
  4392.1    0.05       0  4997.3    0.03       0  5003.3    0.05       0
Bank Sta=4835.1,5257.9
Exp/Cntr=0.3,0.1

Type RM Length L Ch R = 1,10766,325,325,325
BEGIN DESCRIPTION:
UNT 005 IN DRY CR WATERSHED 15.0
END DESCRIPTION:
XS GIS Cut Line= 3
      2914474.99      7034375.00      2913875.00      7034025.00
      2912775.01      7034625.00
#Sta/Elev= 30
  4393.6  467.32  4497.4  460.81  4765.3  455.32  4861.2  455.12  4876.9  456.51
  4978.3  452.75  5015.9  450.37  5021.6  451.43  5027.3  448.19  5027.8  447.39
  5033.3  448.19  5037.4  451.60  5053.1  452.13  5167.9  450.43  5319.3  452.75
  5338.8  454.91  5390.5  456.24  5441.3  453.55  5499.7  455.98  5663.0  455.66
  5706.6  458.25  5826.2  459.35  5853.8  464.01  5897.4  459.42  5935.4  459.57
  5973.4  465.84  6010.9  464.87  6104.4  469.29  6267.6  487.79  6341.2  490.10
#Mann=3,-1,0
  4393.6    0.05       0  5027.3    0.03       0  5033.3    0.05       0
Bank Sta=4978.3,5319.3
Exp/Cntr=0.3,0.1

Type RM Length L Ch R = 1,10441,502,502,502
BEGIN DESCRIPTION:
Mapping XS a6d32bb6
END DESCRIPTION:
XS GIS Cut Line= 3
      2914650.65      7033985.15      2913838.13      7033828.90
      2912839.09      7034005.81
#Sta/Elev= 30
  4140.4  473.75  4207.3  468.42  4237.8  467.89  4273.5  464.90  4298.9  465.32
  4325.5  462.49  4421.1  460.90  4472.0  457.72  4543.4  456.80  4604.4  452.50
  4647.2  452.58  4675.7  455.15  4714.7  453.55  4784.8  453.34  4804.7  451.79
  4848.8  453.54  4920.1  450.37  4975.1  450.68  4981.1  447.64  4988.3  446.66
  4988.8  445.86  4994.4  446.66  5011.6  450.37  5163.9  451.79  5275.7  455.32
  5378.9  454.56  5600.3  458.34  5844.4  460.40  5956.1  462.86  5982.4  465.49
#Mann=5,-1,0
  4140.4    0.05       0  4714.7    0.08       0  4784.8    0.05       0
  4988.3    0.03       0  4994.4    0.05       0
Bank Sta=4804.7,5163.9
Exp/Cntr=0.3,0.1

Type RM Length L Ch R = 1,9939,140,140,140
BEGIN DESCRIPTION:
Mapping XS fef0fa7f
END DESCRIPTION:
XS GIS Cut Line= 3
      2914963.12      7033453.90      2914020.42      7033396.61
      2912918.15      7033375.81
#Sta/Elev= 30
  4048.2  469.67  4236.7  467.36  4286.8  464.44  4356.9  463.31  4447.1  459.73
  4772.3  452.67  4787.7  453.47  4891.4  450.25  4899.4  449.78  4978.0  449.58
  4992.6  448.75  4995.0  445.15  4995.5  444.35  5001.1  445.15  5028.1  448.14
  5155.9  450.25  5208.1  451.97  5248.1  450.62  5328.1  453.53  5378.1  451.91
  5538.2  452.33  5618.2  455.25  5638.2  452.56  5658.2  452.55  5678.2  455.20
  5768.2  454.25  5988.7  459.51  6048.2  460.78  6087.7  463.49  6095.1  465.19
#Mann=6,-1,0
  4048.2    0.08       0  4899.4    0.05       0  4995.0    0.03       0
  5001.1    0.05       0  5988.7    0.08       0  6087.7    0.05       0
Bank Sta=4891.4,5155.9
Exp/Cntr=0.3,0.1

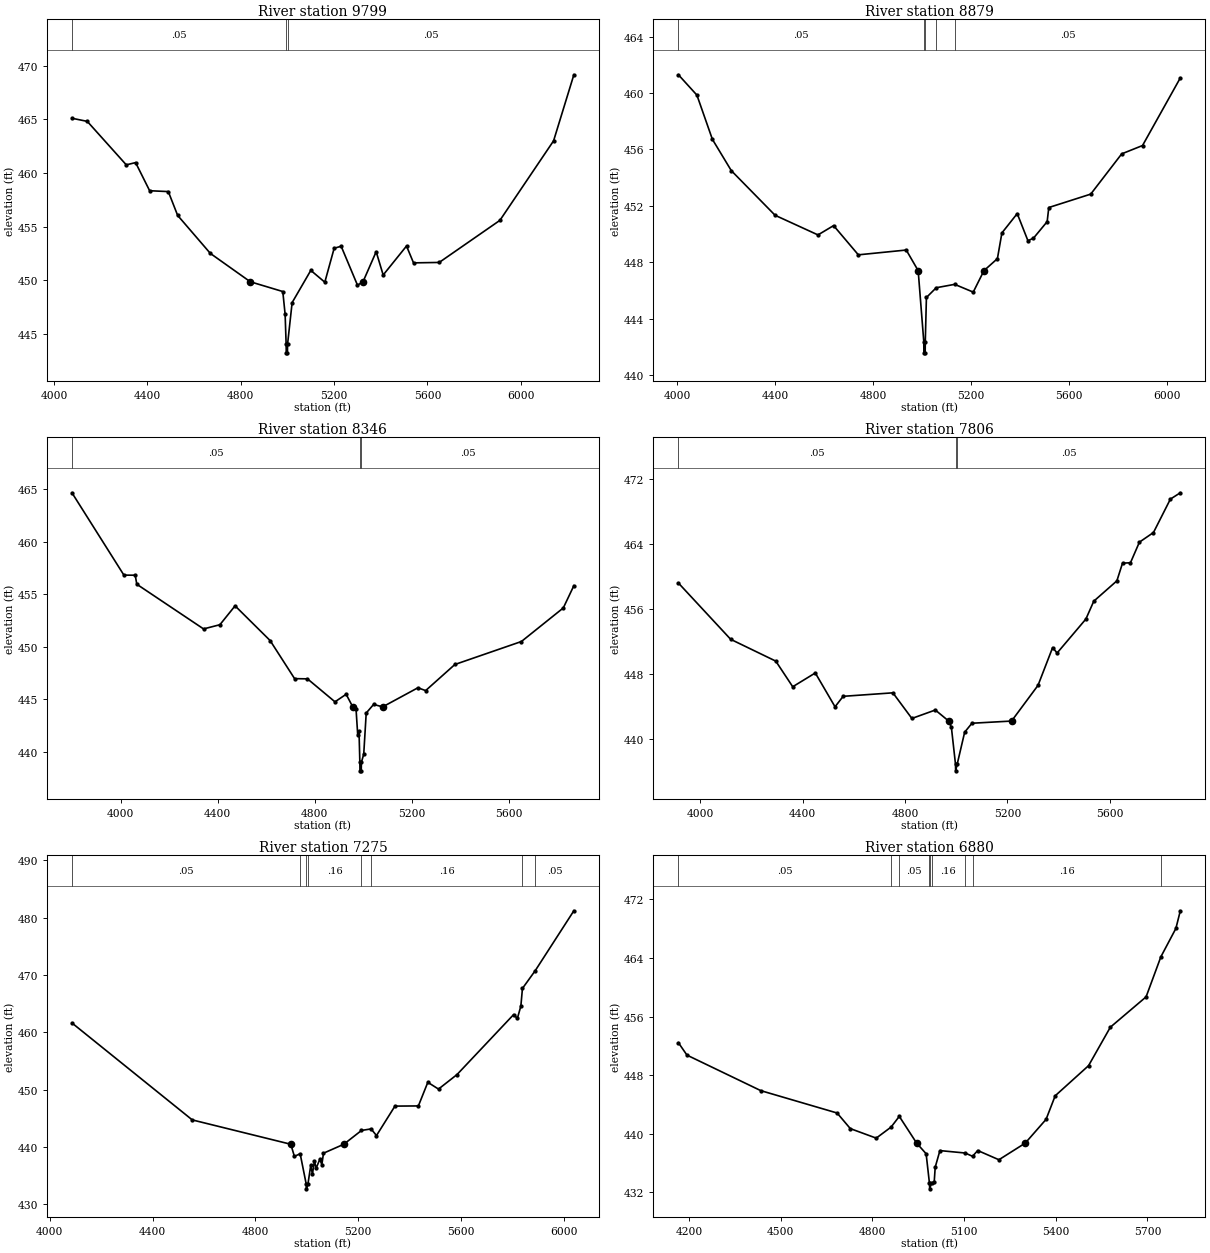
Type RM Length L Ch R = 1,9799,920,920,920
BEGIN DESCRIPTION:
UNT 005 IN DRY CR WATERSHED 13.0
END DESCRIPTION:
XS GIS Cut Line= 3
      2914947.51      7033292.44      2914025.19      7033257.07
      2912798.20      7033250.78
#Sta/Elev= 30
  4077.0  465.11  4142.6  464.82  4309.7  460.77  4349.7  460.98  4409.8  458.36
  4489.8  458.28  4529.8  456.06  4669.9  452.52  4841.0  449.88  4980.2  448.97
  4990.2  446.84  4994.5  444.06  4995.0  443.26  5000.1  443.26  5000.6  444.06
  5020.2  447.94  5100.2  450.94  5160.2  449.84  5200.2  453.00  5230.2  453.19
  5300.2  449.56  5323.8  449.88  5380.2  452.68  5410.2  450.51  5510.2  453.21
  5540.2  451.64  5650.2  451.68  5910.2  455.60  6140.2  463.01  6227.0  469.16
#Mann=3,-1,0
  4077.0    0.05       0  4994.5    0.03       0  5000.6    0.05       0
Bank Sta=4841,5323.8
Exp/Cntr=0.3,0.1

Type RM Length L Ch R = 1,8879,533,533,533
BEGIN DESCRIPTION:
UNT 005 IN DRY CR WATERSHED 12.0
END DESCRIPTION:
XS GIS Cut Line= 3
      2914718.34      7032922.65      2913725.00      7032675.00
      2912759.98      7033026.82
#Sta/Elev= 30
  4005.3  461.29  4080.9  459.85  4144.1  456.72  4221.5  454.50  4400.4  451.34
  4575.6  449.95  4639.4  450.61  4740.5  448.54  4936.3  448.88  4985.0  447.42
  5007.9  442.40  5008.4  441.60  5013.6  441.60  5014.1  442.40  5018.7  445.52
  5058.8  446.21  5134.1  446.45  5210.0  445.90  5253.8  447.42  5308.8  448.27
  5327.1  450.09  5389.8  451.46  5433.5  449.54  5456.2  449.72  5512.1  450.89
  5518.7  451.89  5690.1  452.84  5816.7  455.69  5901.8  456.28  6056.2  461.07
#Mann=5,-1,0
  4005.3    0.05       0  5007.9    0.03       0  5014.1    0.05       0
  5058.8    0.16       0  5134.1    0.05       0
Bank Sta=4985,5253.8
Exp/Cntr=0.3,0.1

Type RM Length L Ch R = 1,8346,540,540,540
BEGIN DESCRIPTION:
UNT 005 IN DRY CR WATERSHED 11.0
END DESCRIPTION:
XS GIS Cut Line= 3
      2914775.64      7032683.07      2913675.00      7032225.00
      2912812.13      7032375.77
#Sta/Elev= 30
  3799.8  464.68  4013.9  456.83  4060.5  456.82  4067.0  455.96  4342.1  451.70
  4409.4  452.10  4472.0  453.90  4616.4  450.59  4717.2  446.96  4770.3  446.94
  4883.6  444.75  4929.6  445.47  4956.9  444.27  4970.3  444.10  4977.3  441.60
  4982.7  441.94  4986.1  438.97  4986.6  438.17  4991.9  438.17  4992.4  438.97
  5002.1  439.76  5012.3  443.68  5042.7  444.50  5080.2  444.27  5225.4  446.09
  5257.2  445.82  5377.7  448.31  5651.8  450.50  5824.4  453.70  5867.9  455.82
#Mann=3,-1,0
  3799.8    0.05       0  4986.1    0.03       0  4992.4    0.05       0
Bank Sta=4956.9,5080.2
Exp/Cntr=0.3,0.1

Type RM Length L Ch R = 1,7806,531,531,531
BEGIN DESCRIPTION:
UNT 005 IN DRY CR WATERSHED 10.0
END DESCRIPTION:
XS GIS Cut Line= 3
      2914640.21      7032172.65      2913675.00      7031725.00
      2912859.73      7031350.09
#Sta/Elev= 30
  3914.7  459.18  4118.9  452.24  4295.2  449.55  4361.4  446.39  4449.6  448.09
  4526.7  443.92  4558.5  445.21  4752.8  445.64  4827.0  442.48  4918.6  443.52
  4970.9  442.16  4981.4  441.39  4997.5  436.82  4998.0  436.02  5003.9  436.82
  5033.3  440.79  5061.8  441.89  5216.5  442.16  5319.9  446.56  5377.0  451.22
  5394.5  450.55  5507.0  454.74  5537.8  456.94  5628.1  459.45  5650.1  461.63
  5681.2  461.68  5716.1  464.22  5771.1  465.41  5837.2  469.53  5876.0  470.31
#Mann=3,-1,0
  3914.7    0.05       0  4997.5    0.03       0  5003.9    0.05       0
Bank Sta=4970.9,5216.5
Exp/Cntr=0.3,0.1

Type RM Length L Ch R = 1,7275,395,395,395
BEGIN DESCRIPTION:
UNT 005 IN DRY CR WATERSHED 9.0
END DESCRIPTION:
XS GIS Cut Line= 3
      2914725.02      7031975.02      2914025.00      7031375.00
      2913224.97      7030724.98
#Sta/Elev= 30
  4086.0  461.62  4554.1  444.70  4937.5  440.45  4951.5  438.33  4973.9  438.80
  4997.6  433.47  4998.1  432.67  5004.1  433.47  5015.2  436.80  5021.6  435.23
  5029.5  437.54  5036.0  436.26  5050.4  437.83  5058.3  436.89  5064.7  438.89
  5143.7  440.45  5212.5  442.86  5249.8  443.13  5270.9  441.97  5342.7  447.11
  5433.9  447.14  5470.6  451.26  5512.2  450.08  5584.1  452.61  5804.6  463.09
  5819.0  462.41  5832.6  464.56  5838.8  467.65  5888.7  470.76  6038.8  481.20
#Mann=8,-1,0
  4086.0    0.05       0  4973.9    0.16       0  4997.6    0.07       0
  5004.1    0.16       0  5212.5    0.05       0  5249.8    0.16       0
  5838.8     0.1       0  5888.7    0.05       0
Bank Sta=4937.5,5143.7
Exp/Cntr=0.3,0.1

Type RM Length L Ch R = 1,6880,703,703,703
BEGIN DESCRIPTION:
UNT 005 IN DRY CR WATERSHED 8.0
END DESCRIPTION:
XS GIS Cut Line= 3
      2914824.96      7031574.97      2914174.75      7031052.37
      2913421.47      7030761.19
#Sta/Elev= 30
  4165.8  452.43  4193.8  450.74  4435.4  445.89  4684.9  442.84  4728.1  440.71
  4812.9  439.41  4861.5  440.92  4888.3  442.38  4945.1  438.73  4976.1  437.28
  4986.7  433.35  4987.2  433.29  4987.7  432.49  4993.8  433.29  5002.5  433.39
  5005.8  435.44  5021.2  437.71  5103.8  437.38  5127.9  436.93  5144.9  437.72
  5214.2  436.46  5300.3  438.73  5368.4  441.97  5398.3  445.19  5507.4  449.30
  5578.7  454.55  5695.6  458.69  5744.0  464.16  5793.1  468.03  5807.6  470.44
#Mann=9,-1,0
  4165.8    0.05       0  4861.5    0.16       0  4888.3    0.05       0
  4986.7    0.16       0  4987.2    0.07       0  4993.8    0.16       0
  5103.8    0.05       0  5127.9    0.16       0  5744.0     0.1       0
Bank Sta=4945.1,5300.3
Exp/Cntr=0.3,0.1

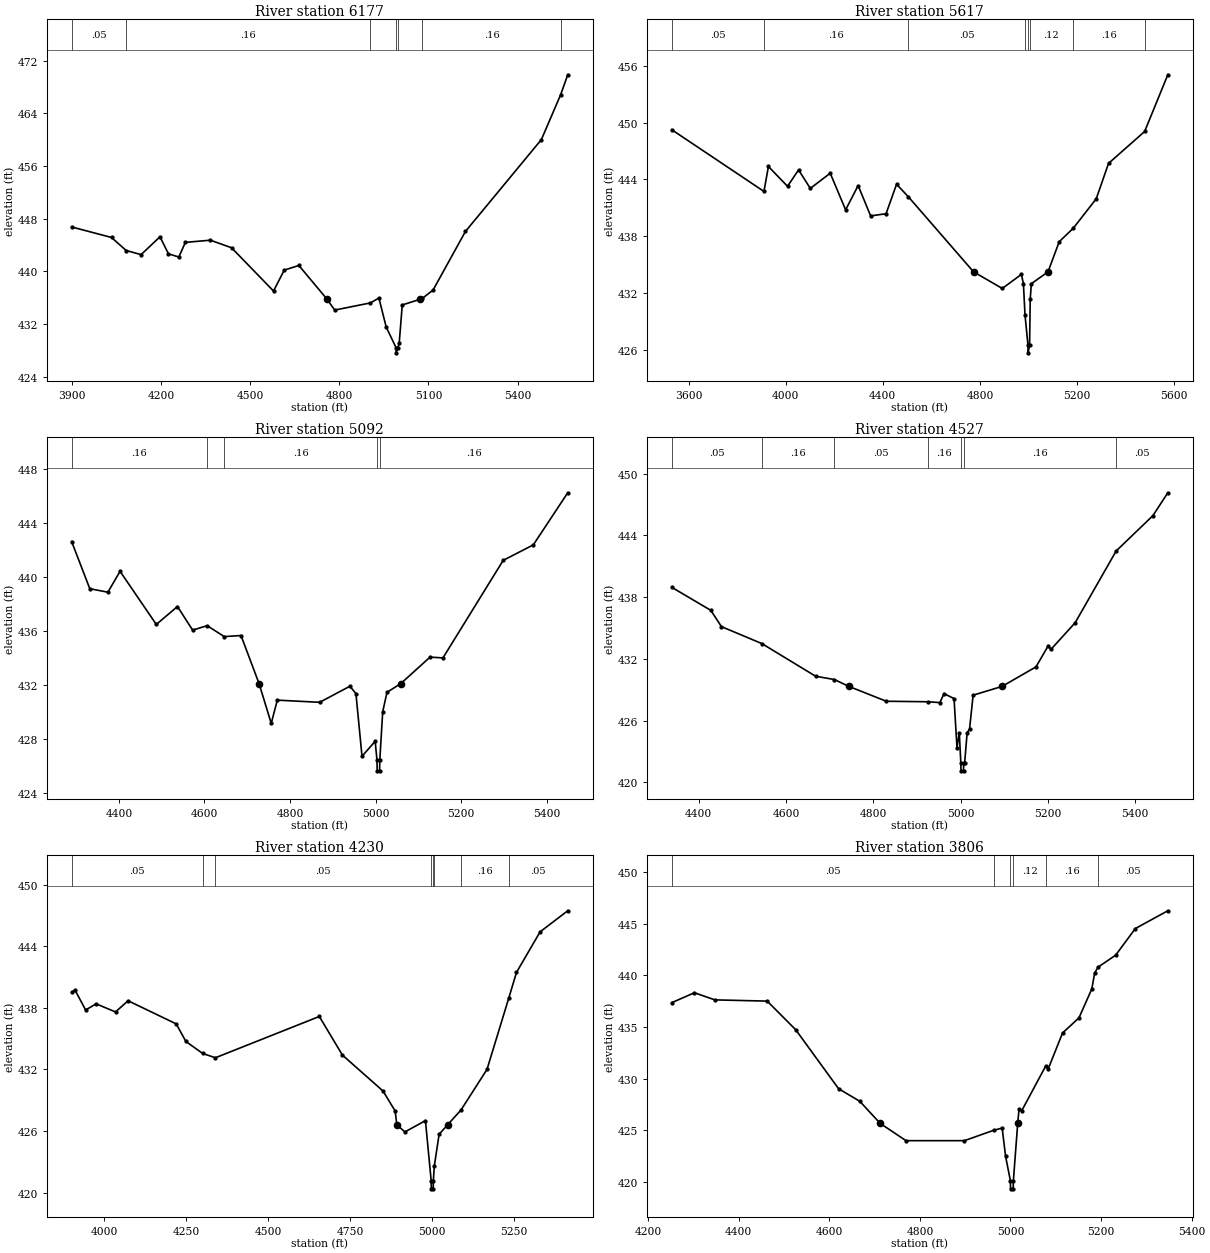
Type RM Length L Ch R = 1,6177,560,560,560
BEGIN DESCRIPTION:
UNT 005 IN DRY CR WATERSHED 7.0
END DESCRIPTION:
XS GIS Cut Line= 3
      2914825.03      7031275.04      2914125.00      7030475.00
      2913525.04      7030574.99
#Sta/Elev= 30
  3897.9  446.76  4032.2  445.16  4081.7  443.18  4131.9  442.56  4195.5  445.27
  4224.0  442.67  4259.1  442.20  4280.9  444.42  4365.4  444.75  4436.6  443.60
  4578.0  437.03  4614.1  440.21  4663.4  440.91  4758.9  435.76  4784.0  434.14
  4904.6  435.23  4933.0  435.97  4957.6  431.56  4990.6  428.45  4991.1  427.65
  4997.2  428.45  5001.5  429.18  5011.7  434.92  5070.3  435.76  5079.8  435.93
  5115.6  437.19  5224.6  446.08  5480.5  460.03  5545.5  466.86  5569.2  469.86
#Mann=7,-1,0
  3897.9    0.05       0  4081.7    0.16       0  4904.6    0.12       0
  4990.6    0.07       0  4997.2    0.12       0  5079.8    0.16       0
  5545.5    0.05       0
Bank Sta=4758.9,5070.3
Exp/Cntr=0.3,0.1

Type RM Length L Ch R = 1,5617,525,525,525
BEGIN DESCRIPTION:
UNT 005 IN DRY CR WATERSHED 6.0
END DESCRIPTION:
XS GIS Cut Line= 3
      2915024.99      7031374.98      2914225.00      7030125.00
      2913674.98      7030025.00
#Sta/Elev= 30
  3530.8  449.25  3910.6  442.74  3929.1  445.37  4007.7  443.28  4053.2  445.01
  4101.6  443.06  4183.6  444.66  4247.0  440.80  4298.6  443.36  4350.0  440.16
  4413.6  440.39  4456.8  443.50  4505.9  442.16  4773.9  434.26  4892.2  432.51
  4970.9  433.99  4979.2  433.03  4985.7  429.75  4998.0  426.52  4998.5  425.72
  5004.6  426.52  5007.3  431.39  5011.9  433.01  5080.5  434.26  5126.7  437.44
  5184.2  438.85  5279.1  441.96  5329.9  445.70  5478.5  449.06  5573.9  455.04
#Mann=8,-1,0
  3530.8    0.05       0  3910.6    0.16       0  4505.9    0.05       0
  4985.7    0.12       0  4998.0    0.07       0  5004.6    0.12       0
  5184.2    0.16       0  5478.5    0.05       0
Bank Sta=4773.9,5080.5
Exp/Cntr=0.3,0.1

Type RM Length L Ch R = 1,5092,565,565,565
BEGIN DESCRIPTION:
UNT 005 IN DRY CR WATERSHED 5.0
END DESCRIPTION:
XS GIS Cut Line= 3
      2914874.97      7030174.97      2914375.00      7029675.00
      2913925.03      7029725.00
#Sta/Elev= 30
  4289.6  442.64  4332.0  439.15  4374.4  438.89  4402.7  440.44  4487.5  436.50
  4537.0  437.83  4572.4  436.08  4606.4  436.41  4646.4  435.60  4685.5  435.68
  4727.7  432.12  4756.2  429.17  4770.4  430.89  4869.4  430.73  4940.1  431.92
  4954.2  431.38  4968.4  426.73  4999.2  427.84  5003.4  426.45  5003.9  425.65
  5009.5  425.65  5010.0  426.45  5016.8  430.03  5026.8  431.47  5059.2  432.12
  5127.5  434.08  5157.6  434.02  5298.5  441.25  5368.9  442.40  5449.4  446.26
#Mann=5,-1,0
  4289.6    0.16       0  4606.4    0.12       0  4646.4    0.16       0
  5003.4    0.07       0  5010.0    0.16       0
Bank Sta=4727.7,5059.2
Exp/Cntr=0.3,0.1

Type RM Length L Ch R = 1,4527,297,297,297
BEGIN DESCRIPTION:
UNT 005 IN DRY CR WATERSHED 4.0
END DESCRIPTION:
XS GIS Cut Line= 3
      2914895.60      7029372.11      2914275.00      7029125.00
      2913854.38      7029330.20
#Sta/Elev= 30
  4338.5  438.96  4428.0  436.72  4452.3  435.14  4545.0  433.49  4668.0  430.32
  4710.8  430.00  4744.4  429.33  4829.8  427.89  4924.7  427.84  4952.7  427.76
  4962.0  428.63  4985.0  428.15  4991.7  423.38  4997.0  424.83  5000.5  421.93
  5001.0  421.13  5006.7  421.13  5007.2  421.93  5009.3  421.93  5015.0  424.83
  5020.5  425.19  5028.7  428.48  5094.9  429.33  5172.7  431.23  5200.8  433.29
  5206.8  432.92  5262.4  435.52  5356.3  442.49  5440.4  445.92  5474.5  448.14
#Mann=7,-1,0
  4338.5    0.05       0  4545.0    0.16       0  4710.8    0.05       0
  4924.7    0.16       0  5000.5    0.07       0  5007.2    0.16       0
  5356.3    0.05       0
Bank Sta=4744.4,5094.9
Exp/Cntr=0.3,0.1

Type RM Length L Ch R = 1,4230,424,424,424
BEGIN DESCRIPTION:
Mapping XS 500e7933
END DESCRIPTION:
XS GIS Cut Line= 3
      2915244.36      7029229.93      2914254.79      7028828.90
      2913828.90      7028953.55
#Sta/Elev= 30
  3901.6  439.50  3911.7  439.74  3944.1  437.79  3976.2  438.39  4035.2  437.60
  4073.5  438.69  4220.1  436.44  4249.6  434.73  4300.7  433.56  4339.5  433.14
  4656.2  437.16  4726.6  433.40  4850.4  429.90  4887.4  427.95  4892.3  426.62
  4916.9  425.92  4979.5  427.02  4997.0  421.18  4997.5  420.38  5003.2  420.38
  5003.7  421.18  5006.5  422.59  5021.2  425.69  5047.3  426.62  5088.2  428.07
  5167.1  432.01  5233.8  438.99  5256.9  441.45  5328.9  445.40  5413.1  447.45
#Mann=8,-1,0
  3901.6    0.05       0  4300.7    0.16       0  4339.5    0.05       0
  4997.0    0.03       0  5003.7    0.05       0  5006.5    0.12       0
  5088.2    0.16       0  5233.8    0.05       0
Bank Sta=4892.3,5047.3
Exp/Cntr=0.3,0.1

Type RM Length L Ch R = 1,3806,672,672,672
BEGIN DESCRIPTION:
Mapping XS 18507e2f
END DESCRIPTION:
XS GIS Cut Line= 3
      2914905.85      7028625.78      2914218.34      7028407.02
      2913895.40      7028594.53
#Sta/Elev= 30
  4252.3  437.36  4302.4  438.32  4347.6  437.63  4463.1  437.51  4526.0  434.74
  4620.5  429.04  4667.4  427.82  4712.4  425.68  4769.4  424.01  4898.3  424.01
  4962.6  425.01  4981.6  425.23  4989.2  422.49  4999.7  420.15  5000.2  419.35
  5005.9  419.35  5006.4  420.15  5015.9  425.68  5018.8  427.04  5024.6  426.89
  5077.3  431.20  5083.4  430.97  5114.9  434.43  5151.1  435.89  5179.4  438.68
  5185.8  440.23  5193.3  440.80  5232.0  441.95  5275.5  444.53  5347.2  446.25
#Mann=6,-1,0
  4252.3    0.05       0  4962.6    0.12       0  4999.7    0.07       0
  5006.4    0.12       0  5077.3    0.16       0  5193.3    0.05       0
Bank Sta=4712.4,5015.9
Exp/Cntr=0.3,0.1

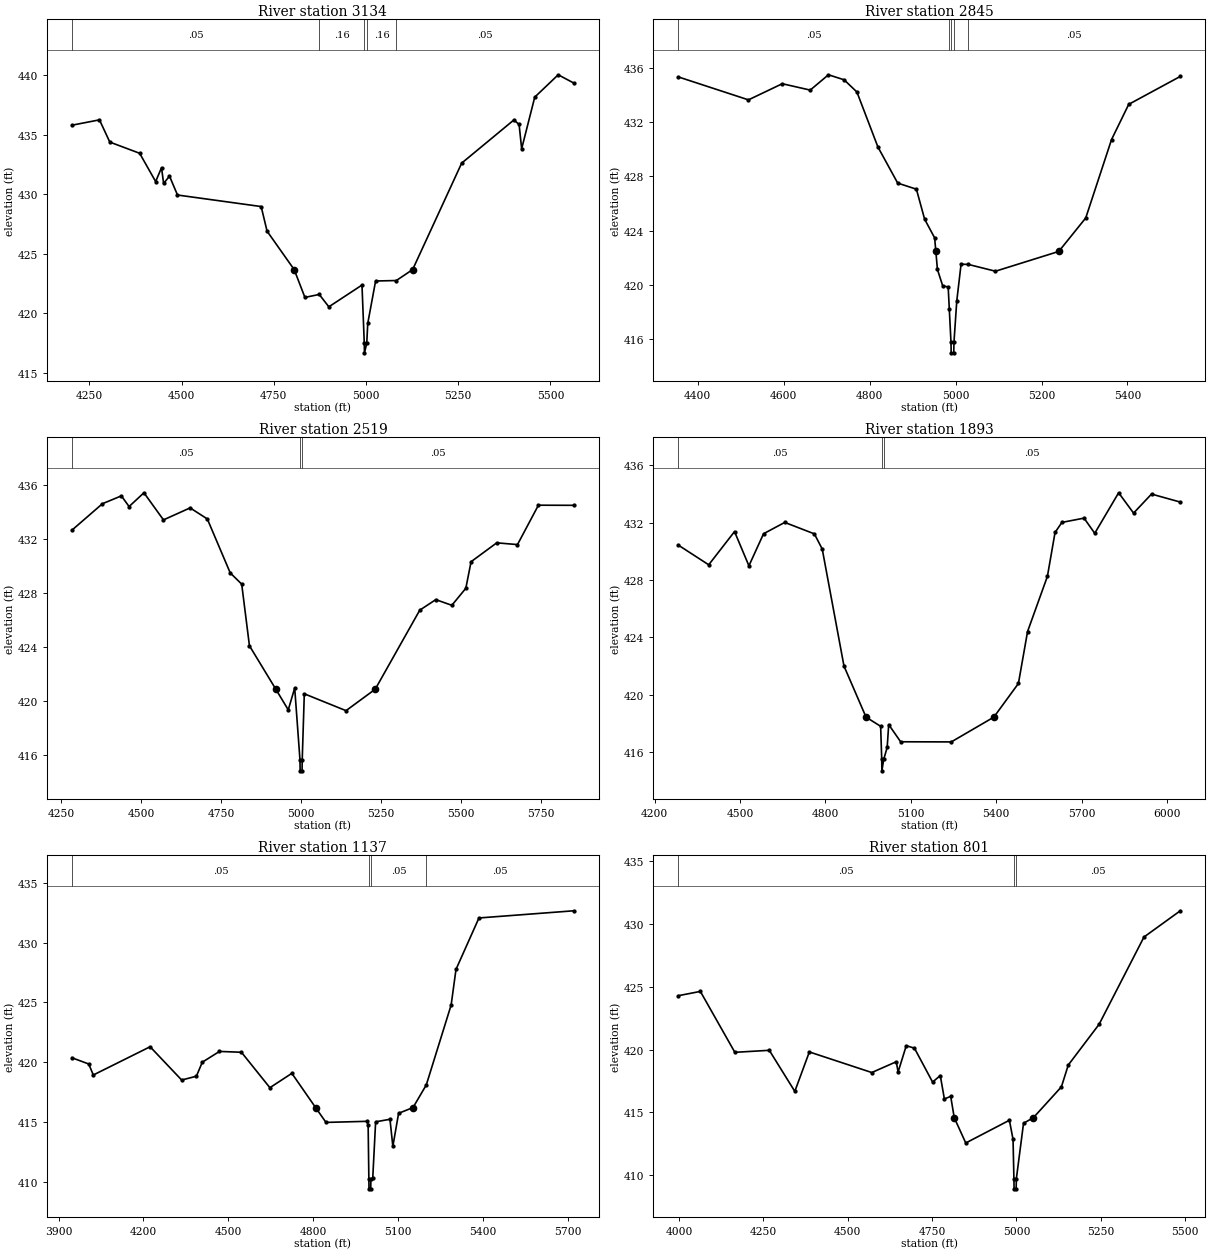
Type RM Length L Ch R = 1,3134,289,289,289
BEGIN DESCRIPTION:
UNT 005 IN DRY CR WATERSHED 3.0
END DESCRIPTION:
XS GIS Cut Line= 3
      2914950.02      7028150.01      2914255.63      7027758.82
      2913850.02      7028149.99
#Sta/Elev= 30
  4203.0  435.80  4277.6  436.25  4305.6  434.38  4386.5  433.44  4429.9  431.06
  4445.8  432.23  4451.5  430.90  4467.4  431.52  4489.1  429.93  4715.9  428.96
  4731.9  426.89  4805.4  423.66  4834.5  421.32  4873.3  421.57  4899.4  420.53
  4989.2  422.36  4995.4  417.46  4995.9  416.66  5002.1  417.46  5004.8  419.13
  5026.1  422.70  5082.3  422.74  5126.5  423.66  5259.4  432.61  5400.9  436.24
  5415.1  435.86  5422.0  433.82  5457.5  438.16  5521.1  440.04  5563.5  439.34
#Mann=5,-1,0
  4203.0    0.05       0  4873.3    0.16       0  4995.4    0.07       0
  5002.1    0.16       0  5082.3    0.05       0
Bank Sta=4805.4,5126.5
Exp/Cntr=0.3,0.1

Type RM Length L Ch R = 1,2845,326,326,326
BEGIN DESCRIPTION:
UNT 005 IN DRY CR WATERSHED 2.0
END DESCRIPTION:
XS GIS Cut Line= 3
      2914900.00      7027700.00      2914325.00      7027475.00
      2913774.96      7027475.00
#Sta/Elev= 30
  4355.4  435.34  4518.3  433.65  4597.0  434.84  4662.0  434.37  4704.4  435.50
  4740.8  435.13  4770.6  434.23  4819.5  430.17  4865.5  427.51  4909.0  427.06
  4928.1  424.85  4951.4  423.47  4954.2  422.47  4957.9  421.14  4970.2  419.93
  4982.9  419.85  4985.5  418.23  4989.4  415.79  4989.9  414.99  4995.9  414.99
  4996.4  415.79  5002.9  418.82  5012.9  421.53  5029.9  421.51  5092.9  421.01
  5240.2  422.47  5302.9  424.94  5362.9  430.72  5402.9  433.32  5522.9  435.38
#Mann=5,-1,0
  4355.4    0.05       0  4985.5    0.16       0  4989.4    0.07       0
  4996.4    0.16       0  5029.9    0.05       0
Bank Sta=4954.2,5240.2
Exp/Cntr=0.3,0.1

Type RM Length L Ch R = 1,2519,626,626,626
BEGIN DESCRIPTION:
Mapping XS f1802081
END DESCRIPTION:
XS GIS Cut Line= 3
      2915023.65      7027397.49      2914420.31      7027154.42
      2913504.51      7027210.84
#Sta/Elev= 30
  4284.3  432.63  4379.6  434.59  4438.7  435.17  4462.8  434.38  4509.2  435.40
  4570.2  433.39  4653.5  434.28  4707.2  433.46  4778.8  429.46  4814.6  428.63
  4838.8  424.06  4921.2  420.84  4960.1  419.31  4980.2  420.93  4996.7  415.59
  4997.2  414.79  5003.2  414.79  5003.7  415.59  5010.2  420.50  5140.5  419.25
  5231.8  420.84  5370.9  426.70  5421.0  427.48  5471.1  427.06  5514.8  428.32
  5531.2  430.29  5611.4  431.69  5676.2  431.56  5741.6  434.48  5852.3  434.47
#Mann=3,-1,0
  4284.3    0.05       0  4996.7    0.03       0  5003.7    0.05       0
Bank Sta=4921.2,5231.8
Exp/Cntr=0.3,0.1

Type RM Length L Ch R = 1,1893,756,756,756
BEGIN DESCRIPTION:
Mapping XS f496c2f2
END DESCRIPTION:
XS GIS Cut Line= 3
      2914988.91      7026876.66      2914363.88      7026542.44
      2913358.47      7026863.13
#Sta/Elev= 30
  4283.1  430.43  4389.6  429.06  4480.3  431.38  4530.9  428.99  4582.4  431.23
  4656.9  432.02  4761.0  431.22  4788.6  430.16  4865.0  421.99  4942.6  418.42
  4993.9  417.78  4997.7  415.47  4998.2  414.67  5004.7  415.47  5016.9  416.31
  5022.2  417.90  5064.2  416.70  5242.2  416.69  5391.7  418.42  5478.1  420.77
  5510.3  424.40  5580.0  428.25  5606.9  431.32  5631.0  432.02  5708.8  432.32
  5746.4  431.26  5830.4  434.09  5882.9  432.67  5945.9  434.00  6047.2  433.44
#Mann=3,-1,0
  4283.1    0.05       0  4997.7    0.03       0  5004.7    0.05       0
Bank Sta=4942.6,5391.7
Exp/Cntr=0.3,0.1

Type RM Length L Ch R = 1,1137,336,336,336
BEGIN DESCRIPTION:
Mapping XS a608e939
END DESCRIPTION:
XS GIS Cut Line= 3
      2914997.55      7026286.36      2914025.34      7026004.24
      2913274.46      7026134.45
#Sta/Elev= 30
  3947.2  420.38  4006.5  419.86  4022.7  418.94  4223.5  421.30  4335.1  418.52
  4387.2  418.84  4408.0  420.01  4468.8  420.91  4546.4  420.84  4647.0  417.88
  4724.6  419.08  4808.6  416.22  4845.3  414.98  4989.2  415.07  4994.3  414.80
  4996.9  410.23  4997.4  409.43  5003.5  409.43  5004.0  410.23  5010.6  410.32
  5020.8  415.03  5071.5  415.24  5081.7  412.98  5102.0  415.74  5153.0  416.22
  5199.9  418.11  5287.8  424.79  5304.9  427.76  5386.1  432.06  5721.6  432.66
#Mann=4,-1,0
  3947.2    0.05       0  4996.9    0.07       0  5004.0    0.05       0
  5199.9    0.05       0
Bank Sta=4808.6,5153
Exp/Cntr=0.3,0.1

Type RM Length L Ch R = 1,801,609,609,609
BEGIN DESCRIPTION:
Mapping XS 15a23d02
END DESCRIPTION:
XS GIS Cut Line= 3
      2914915.06      7026082.35      2913986.28      7025709.10
      2913509.40      7025613.73
#Sta/Elev= 30
  3998.4  424.30  4063.4  424.64  4165.6  419.79  4267.7  419.95  4343.3  416.68
  4386.4  419.82  4571.5  418.18  4644.0  419.04  4649.4  418.22  4673.6  420.32
  4697.8  420.12  4751.6  417.42  4774.4  417.94  4786.5  416.08  4805.3  416.28
  4815.7  414.59  4849.9  412.57  4979.2  414.38  4990.0  412.86  4992.6  409.72
  4993.1  408.92  4999.2  408.92  4999.8  409.72  5021.1  414.14  5050.4  414.59
  5133.3  417.04  5153.7  418.78  5245.0  422.02  5378.0  428.97  5485.7  431.06
#Mann=3,-1,0
  3998.4    0.05       0  4992.6    0.03       0  4999.8    0.05       0
Bank Sta=4815.7,5050.4
Exp/Cntr=0.3,0.1

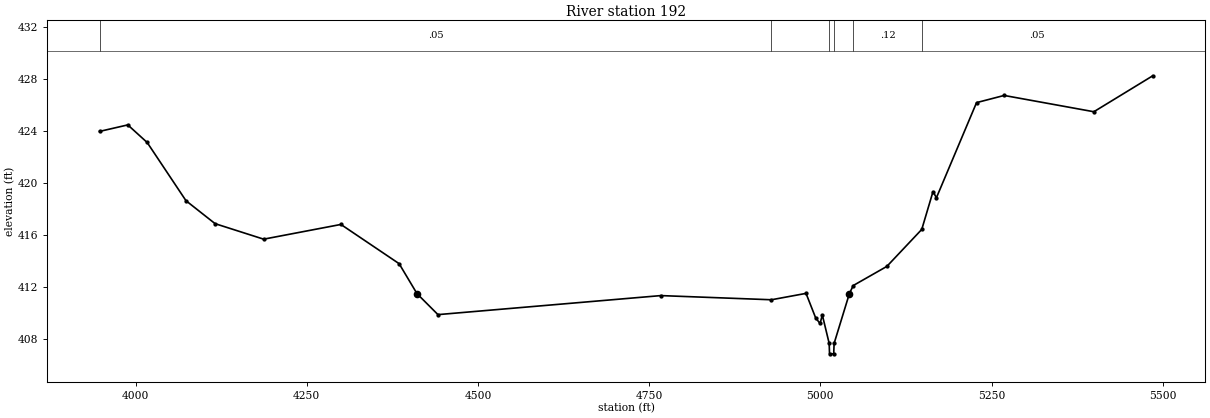
Type RM Length L Ch R = 1,192,0,0,0
BEGIN DESCRIPTION:
UNT 005 IN DRY CR WATERSHED 1.0
END DESCRIPTION:
XS GIS Cut Line= 3
      2914967.16      7025991.20      2914251.35      7025219.46
      2913769.66      7025279.37
#Sta/Elev= 30
  3947.4  423.95  3988.7  424.45  4017.0  423.10  4073.7  418.63  4116.2  416.87
  4187.1  415.68  4299.9  416.81  4384.9  413.80  4411.0  411.50  4441.6  409.89
  4767.1  411.35  4928.6  411.03  4979.1  411.52  4993.3  409.62  4999.6  409.21
  5002.9  409.86  5012.9  407.68  5013.4  406.88  5019.5  406.88  5020.1  407.68
  5042.4  411.50  5048.0  412.12  5097.1  413.59  5148.1  416.43  5164.5  419.33
  5169.5  418.86  5228.1  426.16  5268.4  426.71  5399.4  425.46  5485.4  428.22
#Mann=6,-1,0
  3947.4    0.05       0  4928.6    0.16       0  5012.9    0.07       0
  5020.1    0.16       0  5048.0    0.12       0  5148.1    0.05       0
Bank Sta=4411,5042.4
Exp/Cntr=0.3,0.1

Chan Stop Cuts=-1