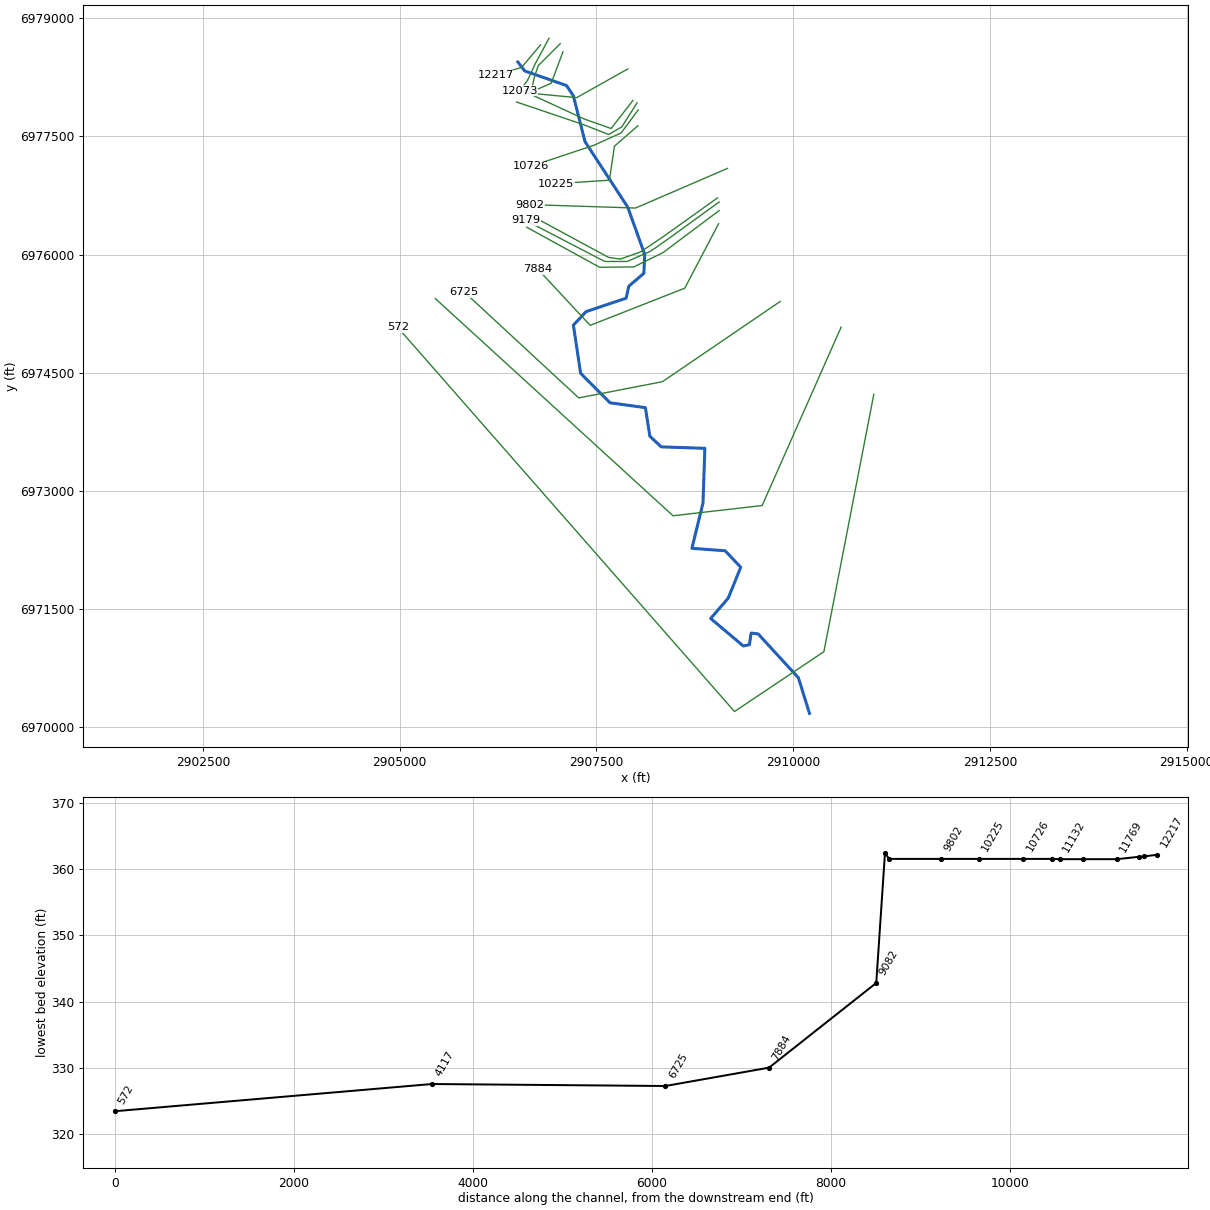
--- UNT 006 IN DRY CR WATERSHED.prj (project) ---

Proj Title=UNT 006 IN DRY CR WATERSHED Base Level Engineering
Current Plan=p01
Default Exp/Contr=0.3,0.1
English Units
Geom File=g01
Flow File=f01
Plan File=p01
BEGIN DESCRIPTION:
UNT 006 IN DRY CR WATERSHED
END DESCRIPTION:

--- UNT 006 IN DRY CR WATERSHED.p01 (plan) ---

Plan Title=Multiple Run
Short Identifier=Multiple
Geom File=g01
Flow File=f01
Subcritical Flow
K Sum by GR= 0
Std Step Tol= 0.01
Critical Tol= 0.01
Num of Std Step Trials= 20
Max Error Tol= 0.3
Flow Tol Ratio= 0.001
Split Flow NTrial= 30
Split Flow Tol= 0.02
Split Flow Ratio= 0.02
Log Output Level= 0
Friction Slope Method= 1
Unsteady Friction Slope Method= 2
Unsteady Bridges Friction Slope Method= 1
Parabolic Critical Depth
Global Vel Dist=  1 , 1 , 1
Global Log Level= 0
CheckData=True
Encroach Param= -1, 0, 0, 0
BEGIN DESCRIPTION:
Multiple Run
END DESCRIPTION:

--- UNT 006 IN DRY CR WATERSHED.f01 (steady flow) ---

Flow Title=Multiple
Number of Profiles=7
Profile Names=10-year,25-year,50-year,1pct_min,100-year,1pct_plu,500-year
River Rch & RM= UNT 006 IN DRY C,Reach-1,12217
     263     334     390     226     452     902     607
River Rch & RM= UNT 006 IN DRY C,Reach-1,9802
     650     870    1048     628    1252    2498    1788
Boundary for River Rch & Prof#=UNT 006 IN DRY C,Reach-1,1
Up Type=0
Dn Type=3
Dn Slope=0.005
Boundary for River Rch & Prof#=UNT 006 IN DRY C,Reach-1,2
Up Type=0
Dn Type=3
Dn Slope=0.005
Boundary for River Rch & Prof#=UNT 006 IN DRY C,Reach-1,3
Up Type=0
Dn Type=3
Dn Slope=0.005
Boundary for River Rch & Prof#=UNT 006 IN DRY C,Reach-1,4
Up Type=0
Dn Type=3
Dn Slope=0.005
Boundary for River Rch & Prof#=UNT 006 IN DRY C,Reach-1,5
Up Type=0
Dn Type=3
Dn Slope=0.005
Boundary for River Rch & Prof#=UNT 006 IN DRY C,Reach-1,6
Up Type=0
Dn Type=3
Dn Slope=0.005
Boundary for River Rch & Prof#=UNT 006 IN DRY C,Reach-1,7
Up Type=0
Dn Type=3
Dn Slope=0.005

--- UNT 006 IN DRY CR WATERSHED.g01 (geometry) ---

Geom Title=Existing Conditions

River Reach=UNT 006 IN DRY C,Reach-1
Reach XY= 30
      2906502.31      6978446.74      2906588.25      6978333.07
      2907120.53      6978146.91      2907207.33      6978016.70
      2907354.90      6977435.10      2907898.30      6976601.77
      2908113.58      6976001.08      2908103.17      6975761.49
      2907912.19      6975598.30      2907877.47      6975445.52
      2907370.53      6975275.38      2907207.71      6975103.71
      2907299.12      6974492.17      2907672.91      6974116.25
      2908122.59      6974054.38      2908179.08      6973692.08
      2908322.99      6973556.21      2908877.91      6973537.55
      2908854.33      6972842.84      2908713.71      6972267.32
      2909135.58      6972236.07      2909333.50      6972027.74
      2909176.05      6971635.95      2908952.09      6971375.54
      2909366.15      6971026.58      2909444.28      6971042.20
      2909465.68      6971190.49      2909554.58      6971180.02
      2910066.74      6970622.24      2910207.28      6970170.01

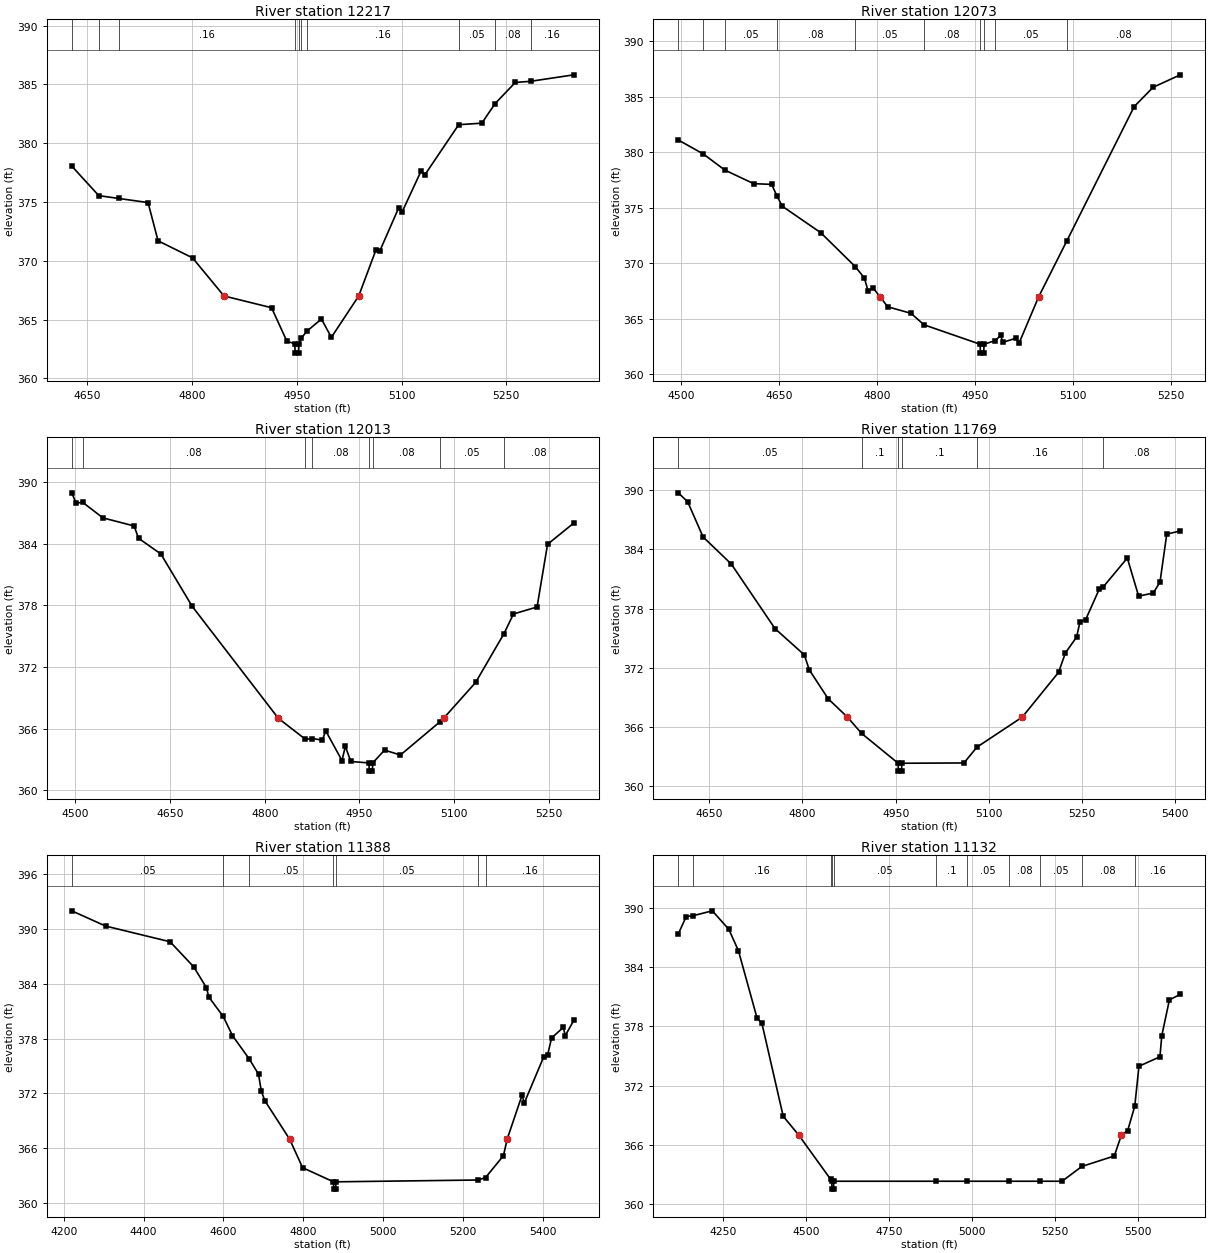
Type RM Length L Ch R = 1,12217,144,144,144
BEGIN DESCRIPTION:
UNT 006 IN DRY CR WATERSHED 10.0
END DESCRIPTION:
XS GIS Cut Line= 3
      2906790.52      6978663.57      2906550.06      6978379.08
      2906219.22      6978275.06
#Sta/Elev= 30
  4627.5  378.05  4666.2  375.54  4694.7  375.30  4736.8  374.95  4751.1  371.70
  4800.5  370.25  4845.6  367.01  4913.7  366.01  4935.7  363.16  4947.0  362.95
  4947.5  362.15  4952.5  362.15  4953.0  362.95  4956.1  363.42  4964.8  364.04
  4985.2  365.05  4999.4  363.49  5038.6  367.01  5063.3  370.93  5068.5  370.79
  5095.7  374.48  5100.9  374.17  5128.1  377.65  5133.3  377.30  5181.8  381.57
  5215.0  381.70  5233.9  383.36  5262.9  385.16  5284.9  385.26  5346.8  385.81
#Mann=10,-1,0
  4627.5    0.05       0  4666.2    0.08       0  4694.7    0.16       0
  4947.0    0.07       0  4953.0    0.16       0  4956.1    0.05       0
  4964.8    0.16       0  5181.8    0.05       0  5233.9    0.08       0
  5284.9    0.16       0
Bank Sta=4845.6,5038.6
Exp/Cntr=0.3,0.1

Type RM Length L Ch R = 1,12073,60,60,60
BEGIN DESCRIPTION:
Mapping XS 35c8f58c
END DESCRIPTION:
XS GIS Cut Line= 5
      2906897.30      6978746.91      2906722.83      6978424.01
      2906668.14      6978304.21      2906618.66      6978202.65
      2906523.23      6978078.85
#Sta/Elev= 30
  4496.2  381.10  4534.5  379.84  4567.5  378.39  4611.5  377.17  4639.1  377.10
  4647.2  376.06  4655.3  375.14  4714.3  372.75  4767.2  369.69  4780.9  368.68
  4786.6  367.52  4793.9  367.81  4804.8  367.00  4816.6  366.09  4852.3  365.50
  4872.1  364.47  4958.0  362.72  4958.5  361.92  4963.5  361.92  4964.0  362.72
  4981.1  363.05  4989.5  363.51  4992.7  362.89  5012.1  363.25  5017.7  362.84
  5047.6  367.00  5090.8  372.04  5193.6  384.10  5222.6  385.84  5264.2  386.96
#Mann=10,-1,0
  4496.2    0.16       0  4534.5    0.08       0  4567.5    0.05       0
  4647.2    0.08       0  4767.2    0.05       0  4872.1    0.08       0
  4958.0    0.04       0  4964.0    0.08       0  4981.1    0.05       0
  5090.8    0.08       0
Bank Sta=4804.8,5047.6
Exp/Cntr=0.3,0.1

Type RM Length L Ch R = 1,12013,244,244,244
BEGIN DESCRIPTION:
Mapping XS 3decffda
END DESCRIPTION:
XS GIS Cut Line= 5
      2907040.51      6978679.19      2906761.89      6978400.57
      2906720.22      6978280.78      2906681.16      6978124.53
      2906579.82      6978072.56
#Sta/Elev= 30
  4494.1  388.98  4501.0  387.97  4511.2  388.06  4543.4  386.54  4592.9  385.75
  4599.9  384.55  4635.3  383.02  4684.8  377.93  4821.5  367.00  4864.5  364.95
  4875.6  365.03  4891.3  364.87  4896.6  365.78  4922.4  362.88  4927.7  364.27
  4936.4  362.79  4965.1  362.65  4965.6  361.85  4970.6  361.85  4971.1  362.65
  4989.9  363.90  5015.0  363.42  5077.7  366.66  5083.5  367.00  5134.3  370.50
  5179.2  375.26  5194.2  377.17  5231.6  377.85  5248.2  383.96  5289.9  386.04
#Mann=8,-1,0
  4494.1    0.05       0  4511.2    0.08       0  4864.5    0.16       0
  4875.6    0.08       0  4965.1    0.07       0  4971.1    0.08       0
  5077.7    0.05       0  5179.2    0.08       0
Bank Sta=4821.5,5083.5
Exp/Cntr=0.3,0.1

Type RM Length L Ch R = 1,11769,381,381,381
BEGIN DESCRIPTION:
UNT 006 IN DRY CR WATERSHED 9.0
END DESCRIPTION:
XS GIS Cut Line= 3
      2907074.99      6978574.97      2906925.00      6978175.00
      2906574.96      6978024.98
#Sta/Elev= 30
  4600.1  389.75  4615.2  388.85  4640.1  385.27  4685.5  382.52  4755.8  375.97
  4803.0  373.30  4811.0  371.78  4841.3  368.85  4872.4  366.98  4895.2  365.33
  4954.0  362.30  4954.5  361.50  4959.5  361.50  4960.0  362.30  5059.9  362.33
  5080.9  363.94  5153.7  366.98  5212.2  371.53  5223.1  373.49  5241.2  375.11
  5246.7  376.67  5255.7  376.87  5277.5  379.95  5283.8  380.18  5322.8  383.13
  5341.0  379.27  5364.5  379.57  5375.4  380.69  5386.3  385.56  5408.1  385.88
#Mann=6,-1,0
  4600.1    0.05       0  4895.2     0.1       0  4954.0    0.07       0
  4960.0     0.1       0  5080.9    0.16       0  5283.8    0.08       0
Bank Sta=4872.4,5153.7
Exp/Cntr=0.3,0.1

Type RM Length L Ch R = 1,11388,256,256,256
BEGIN DESCRIPTION:
Mapping XS 8f8f4d3e
END DESCRIPTION:
XS GIS Cut Line= 3
      2907898.93      6978358.12      2907249.64      6977993.55
      2906739.58      6978042.12
#Sta/Elev= 30
  4220.2  392.00  4305.0  390.33  4466.4  388.61  4525.7  385.85  4557.3  383.58
  4563.3  382.55  4599.2  380.44  4622.6  378.32  4664.0  375.80  4687.7  374.10
  4694.9  372.21  4703.6  371.19  4765.7  366.97  4798.1  363.85  4875.4  362.30
  4875.9  361.50  4880.9  361.50  4881.4  362.30  5237.9  362.50  5256.2  362.77
  5301.0  365.17  5310.2  366.97  5347.8  371.83  5352.8  370.91  5401.4  375.96
  5411.5  376.20  5421.5  378.07  5450.7  379.22  5455.8  378.33  5477.2  380.00
#Mann=7,-1,0
  4220.2    0.05       0  4599.2    0.16       0  4664.0    0.05       0
  4875.4   0.033       0  4881.4    0.05       0  5237.9    0.08       0
  5256.2    0.16       0
Bank Sta=4765.7,5310.2
Exp/Cntr=0.3,0.1

Type RM Length L Ch R = 1,11132,88,88,88
BEGIN DESCRIPTION:
Mapping XS baa6693d
END DESCRIPTION:
XS GIS Cut Line= 4
      2907964.93      6977958.83      2907687.14      6977601.18
      2907343.39      6977722.71      2906711.41      6978014.40
#Sta/Elev= 30
  4115.5  387.37  4139.6  389.14  4160.6  389.23  4218.3  389.72  4268.1  387.84
  4297.1  385.66  4353.2  378.83  4367.7  378.31  4431.9  368.89  4479.0  366.97
  4575.2  362.48  4578.2  362.30  4578.7  361.50  4583.7  361.50  4584.2  362.30
  4892.9  362.30  4984.7  362.30  5111.8  362.30  5206.9  362.30  5272.6  362.30
  5332.2  363.80  5430.0  364.86  5451.3  366.97  5470.3  367.44  5491.7  369.91
  5504.3  373.96  5567.6  374.92  5573.1  377.05  5596.1  380.69  5629.0  381.25
#Mann=11,-1,0
  4115.5    0.05       0  4160.6    0.16       0  4575.2    0.05       0
  4578.2   0.033       0  4584.2    0.05       0  4892.9     0.1       0
  4984.7    0.05       0  5111.8    0.08       0  5206.9    0.05       0
  5332.2    0.08       0  5491.7    0.16       0
Bank Sta=4479,5451.3
Exp/Cntr=0.3,0.1

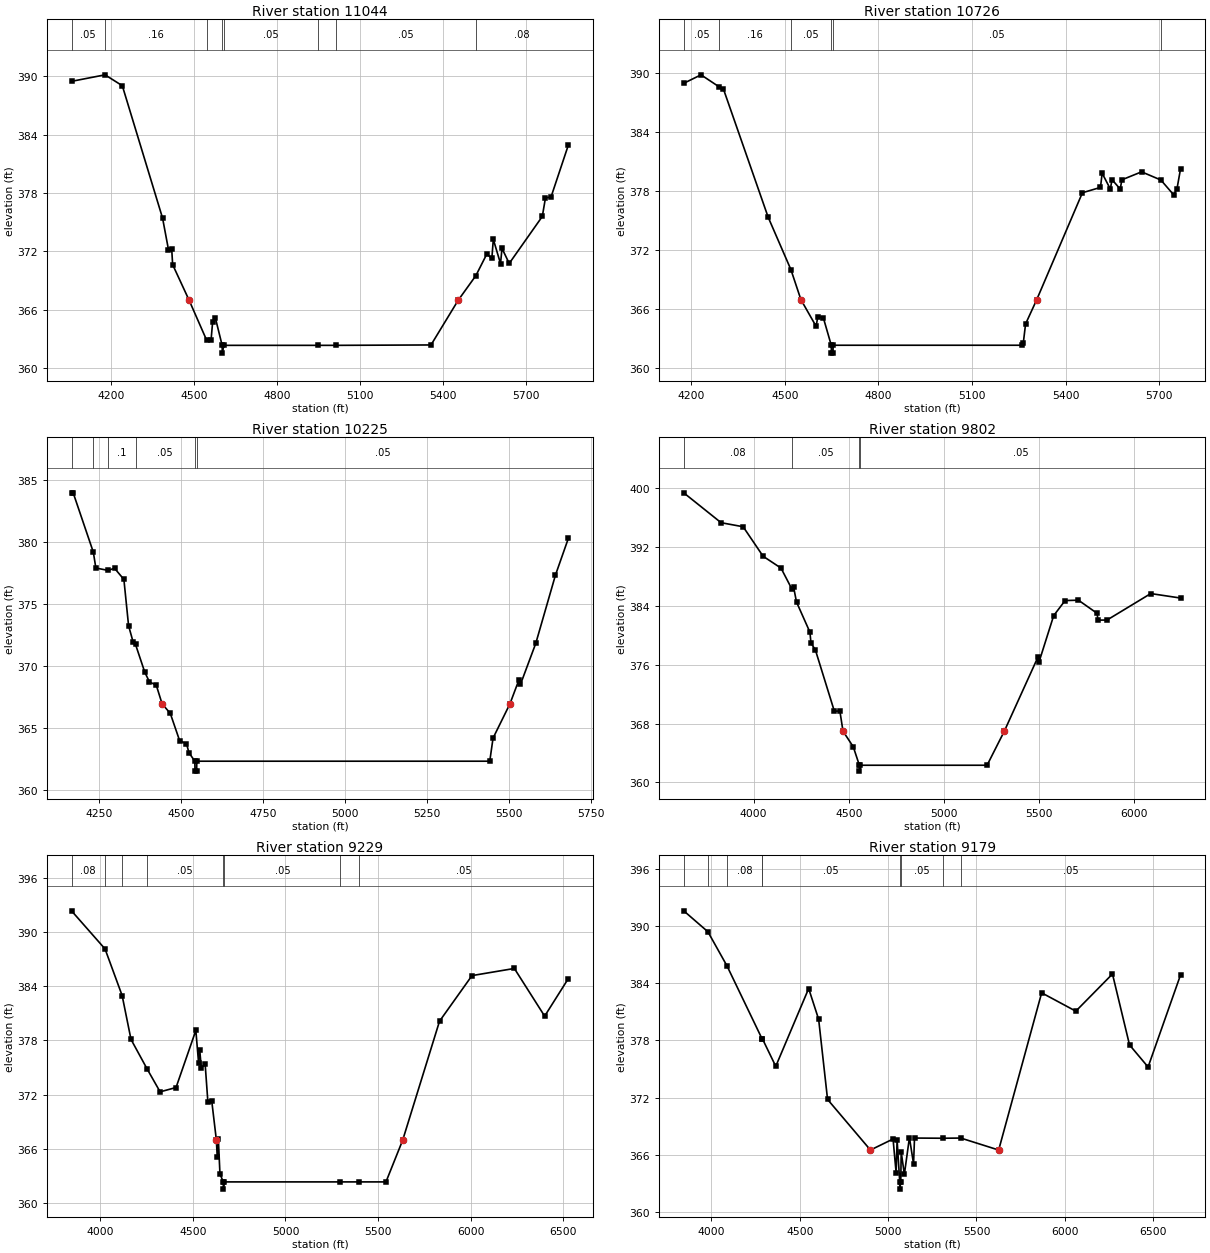
Type RM Length L Ch R = 1,11044,318,318,318
BEGIN DESCRIPTION:
Mapping XS a621f200
END DESCRIPTION:
XS GIS Cut Line= 5
      2908016.99      6977927.55      2907822.56      6977622.02
      2907655.89      6977524.80      2907346.87      6977646.32
      2906485.79      6977937.98
#Sta/Elev= 30
  4058.0  389.48  4179.2  390.15  4241.7  389.03  4387.3  375.41  4408.5  372.19
  4420.2  372.29  4423.6  370.64  4483.3  366.97  4546.4  362.88  4562.6  362.91
  4568.4  364.79  4578.3  365.14  4602.6  362.34  4603.1  361.54  4608.6  362.34
  4949.2  362.34  5012.5  362.34  5357.7  362.38  5455.9  366.97  5520.0  369.51
  5559.5  371.73  5577.7  371.27  5583.0  373.24  5609.1  370.74  5614.4  372.31
  5640.5  370.76  5760.1  375.59  5771.5  377.49  5791.8  377.60  5854.3  382.93
#Mann=8,-1,0
  4058.0    0.05       0  4179.2    0.16       0  4546.4    0.05       0
  4602.6    0.07       0  4608.6    0.05       0  4949.2     0.1       0
  5012.5    0.05       0  5520.0    0.08       0
Bank Sta=4483.3,5455.9
Exp/Cntr=0.3,0.1

Type RM Length L Ch R = 1,10726,501,501,501
BEGIN DESCRIPTION:
Mapping XS c52726eb
END DESCRIPTION:
XS GIS Cut Line= 4
      2908030.91      6977837.32      2907815.62      6977545.63
      2907471.87      6977389.38      2906663.94      6977119.65
#Sta/Elev= 30
  4176.4  388.91  4231.8  389.77  4289.4  388.56  4303.6  388.33  4446.9  375.33
  4519.8  370.01  4551.8  366.97  4600.5  364.26  4605.9  365.22  4623.5  365.15
  4649.1  362.34  4649.6  361.54  4654.6  361.54  4655.1  362.34  5258.9  362.34
  5264.2  362.52  5271.7  364.50  5307.5  366.97  5453.8  377.81  5511.7  378.35
  5517.0  379.79  5543.3  378.18  5548.6  379.14  5574.9  378.18  5580.2  379.12
  5643.4  379.93  5705.2  379.10  5746.1  377.60  5756.6  378.17  5768.3  380.25
#Mann=6,-1,0
  4176.4    0.05       0  4289.4    0.16       0  4519.8    0.05       0
  4649.1   0.033       0  4655.1    0.05       0  5705.2    0.08       0
Bank Sta=4551.8,5307.5
Exp/Cntr=0.3,0.1

Type RM Length L Ch R = 1,10225,423,423,423
BEGIN DESCRIPTION:
Mapping XS f7c562c8
END DESCRIPTION:
XS GIS Cut Line= 4
      2908028.26      6977636.75      2907728.81      6977376.36
      2907665.59      6976944.09      2906985.89      6976900.57
#Sta/Elev= 30
  4166.3  383.97  4171.4  383.97  4232.9  379.18  4240.5  377.91  4277.5  377.72
  4297.5  377.89  4326.0  376.99  4340.3  373.26  4354.5  371.91  4361.5  371.75
  4389.6  369.52  4403.9  368.73  4424.7  368.47  4442.4  366.97  4467.5  366.19
  4496.0  363.99  4516.8  363.75  4524.5  363.02  4542.3  362.34  4542.8  361.54
  4547.8  361.54  4548.3  362.34  5441.5  362.34  5451.5  364.20  5503.1  366.97
  5530.1  368.87  5535.1  368.53  5581.8  371.84  5641.9  377.35  5681.1  380.30
#Mann=6,-1,0
  4166.3    0.05       0  4232.9    0.16       0  4277.5     0.1       0
  4361.5    0.05       0  4542.3   0.033       0  4548.3    0.05       0
Bank Sta=4442.4,5503.1
Exp/Cntr=0.3,0.1

Type RM Length L Ch R = 1,9802,573,573,573
BEGIN DESCRIPTION:
Mapping XS d907712a
END DESCRIPTION:
XS GIS Cut Line= 3
      2909165.47      6977094.25      2907997.91      6976590.77
      2906658.41      6976634.12
#Sta/Elev= 30
  3632.6  399.36  3829.1  395.30  3944.9  394.75  4049.9  390.74  4144.0  389.13
  4202.2  386.23  4210.3  386.53  4225.4  384.52  4296.0  380.42  4301.4  378.95
  4324.9  377.99  4424.4  369.68  4453.4  369.71  4469.8  366.97  4523.9  364.84
  4555.8  362.34  4556.3  361.54  4561.8  362.34  5227.2  362.34  5317.8  366.97
  5495.5  377.09  5500.5  376.40  5577.4  382.68  5637.4  384.72  5707.4  384.77
  5805.2  382.99  5810.2  382.06  5857.5  382.07  6087.6  385.67  6244.3  385.06
#Mann=4,-1,0
  3632.6    0.08       0  4202.2    0.05       0  4555.8   0.033       0
  4561.8    0.05       0
Bank Sta=4469.8,5317.8
Exp/Cntr=0.3,0.1

Type RM Length L Ch R = 1,9229,50,50,50
BEGIN DESCRIPTION:
Mapping XS de2898aa
END DESCRIPTION:
XS GIS Cut Line= 6
      2909037.87      6976719.27      2908352.07      6976228.79
      2908061.27      6976033.48      2907805.20      6975942.33
      2907653.29      6975964.03      2906717.47      6976470.94
#Sta/Elev= 30
  3844.7  392.35  4025.8  388.13  4118.1  382.97  4165.9  378.12  4252.8  374.85
  4323.2  372.31  4409.2  372.79  4516.1  379.11  4530.8  375.55  4537.0  376.97
  4545.6  374.95  4566.4  375.38  4581.2  371.16  4602.1  371.28  4627.0  366.97
  4631.6  365.11  4637.7  367.08  4646.3  363.23  4664.2  362.34  4664.7  361.54
  4670.2  362.34  5296.3  362.34  5397.1  362.34  5542.8  362.34  5633.2  366.97
  5832.0  380.13  6007.4  385.18  6236.1  385.97  6399.7  380.69  6527.7  384.85
#Mann=8,-1,0
  3844.7    0.08       0  4025.8    0.05       0  4118.1    0.08       0
  4252.8    0.05       0  4664.2   0.033       0  4670.2    0.05       0
  5296.3     0.1       0  5397.1    0.05       0
Bank Sta=4627,5633.2
Exp/Cntr=0.3,0.1

Type RM Length L Ch R = 1,9179,97,97,97
BEGIN DESCRIPTION:
Mapping XS decc5867
END DESCRIPTION:
XS GIS Cut Line= 6
      2909059.55      6976667.16      2908430.20      6976211.43
      2908195.82      6976046.50      2907892.00      6975911.95
      2907605.55      6975911.95      2906602.92      6976432.79
#Sta/Elev= 30
  3843.2  391.63  3980.0  389.43  4087.8  385.85  4286.6  378.17  4288.7  378.17
  4364.1  375.28  4550.4  383.46  4606.9  380.22  4657.3  371.80  4900.1  366.48
  5028.0  367.64  5045.4  364.09  5050.9  367.55  5065.7  363.17  5066.2  362.37
  5071.7  363.17  5074.1  366.28  5092.0  363.92  5120.7  367.79  5144.0  365.02
  5149.5  367.74  5312.2  367.72  5411.2  367.74  5625.8  366.48  5869.1  383.01
  6062.5  381.08  6269.9  384.99  6366.5  377.53  6471.5  375.21  6655.4  384.90
#Mann=9,-1,0
  3843.2    0.08       0  3980.0    0.05       0  4087.8    0.08       0
  4286.6    0.16       0  4288.7    0.05       0  5065.7   0.033       0
  5071.7    0.05       0  5312.2     0.1       0  5411.2    0.05       0
Bank Sta=4900.1,5625.8
Exp/Cntr=0.3,0.1

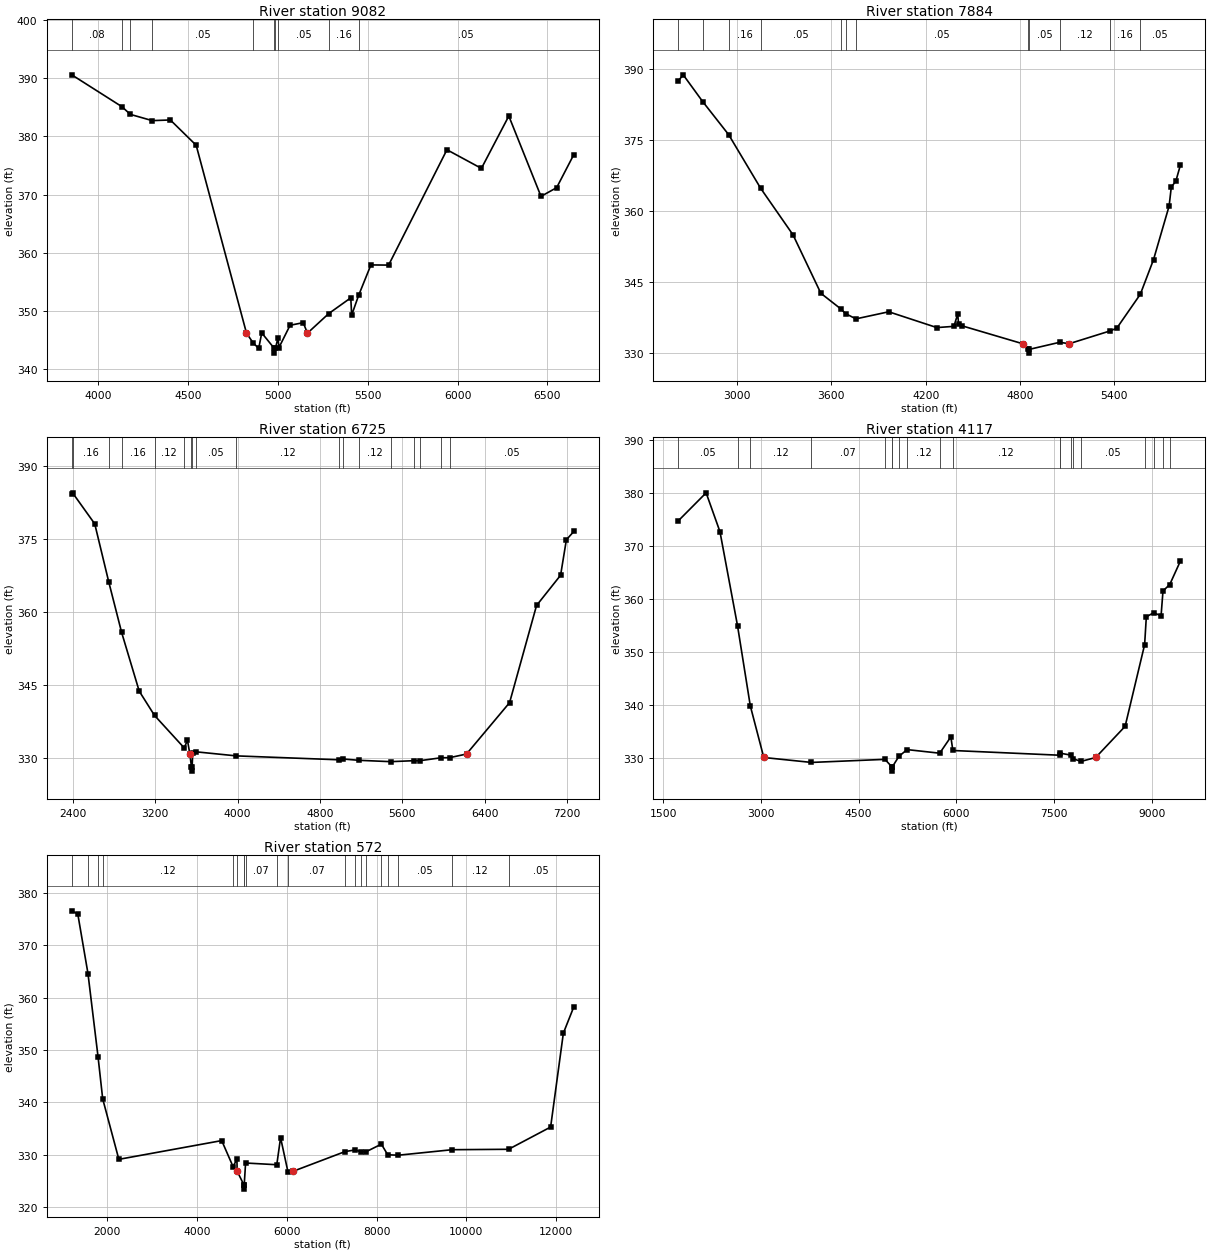
Type RM Length L Ch R = 1,9082,1198,1198,1198
BEGIN DESCRIPTION:
Mapping XS 83794845
END DESCRIPTION:
XS GIS Cut Line= 5
      2909059.51      6976558.63      2908347.73      6976024.80
      2907974.47      6975842.50      2907540.44      6975838.16
      2906616.00      6976345.96
#Sta/Elev= 30
  3852.8  390.58  4131.9  385.11  4178.8  383.79  4300.4  382.72  4401.4  382.83
  4545.1  378.49  4825.1  346.24  4860.9  344.62  4893.0  343.61  4909.9  346.28
  4980.1  343.61  4980.6  342.81  4986.1  343.61  5000.4  345.47  5005.6  343.76
  5067.6  347.59  5140.7  348.04  5164.3  346.24  5282.8  349.60  5405.4  352.30
  5410.4  349.34  5448.9  352.71  5517.4  357.95  5615.9  357.92  5940.5  377.72
  6132.3  374.52  6284.8  383.51  6463.9  369.72  6551.0  371.21  6646.7  376.90
#Mann=10,-1,0
  3852.8    0.08       0  4131.9    0.05       0  4178.8    0.16       0
  4300.4    0.05       0  4860.9    0.12       0  4980.1    0.07       0
  4986.1    0.12       0  5000.4    0.05       0  5282.8    0.16       0
  5448.9    0.05       0
Bank Sta=4825.1,5164.3
Exp/Cntr=0.3,0.1

Type RM Length L Ch R = 1,7884,1159,1159,1159
BEGIN DESCRIPTION:
Mapping XS 513971bf
END DESCRIPTION:
XS GIS Cut Line= 4
      2909052.88      6976391.68      2908622.33      6975572.25
      2907420.94      6975100.03      2906754.28      6975815.30
#Sta/Elev= 30
  2625.5  387.56  2657.2  388.85  2780.7  383.21  2946.3  376.20  3150.2  364.85
  3356.0  355.01  3532.9  342.67  3660.1  339.36  3689.7  338.38  3756.0  337.26
  3964.7  338.76  4270.8  335.42  4379.2  335.68  4403.6  338.26  4409.0  336.22
  4433.4  335.77  4816.6  332.01  4853.9  330.82  4854.4  330.02  4859.9  330.82
  5052.1  332.31  5112.7  332.01  5372.6  334.71  5415.8  335.30  5565.3  342.46
  5649.3  349.78  5748.5  361.11  5762.6  365.16  5791.0  366.33  5819.8  369.71
#Mann=12,-1,0
  2625.5    0.08       0  2780.7    0.05       0  2946.3    0.16       0
  3150.2    0.05       0  3660.1    0.07       0  3689.7    0.12       0
  3756.0    0.05       0  4853.9    0.03       0  4859.9    0.05       0
  5052.1    0.12       0  5372.6    0.16       0  5565.3    0.05       0
Bank Sta=4816.6,5112.7
Exp/Cntr=0.3,0.1

Type RM Length L Ch R = 1,6725,2608,2608,2608
BEGIN DESCRIPTION:
Mapping XS 4ffee51c
END DESCRIPTION:
XS GIS Cut Line= 4
      2909836.31      6975404.28      2908338.91      6974384.32
      2907275.54      6974178.15      2905821.52      6975523.66
#Sta/Elev= 30
  2388.8  384.41  2396.5  384.56  2611.9  378.17  2748.0  366.21  2872.5  355.85
  3043.8  343.72  3192.4  338.72  3480.3  332.04  3512.5  333.60  3535.6  330.77
  3551.5  328.05  3552.0  327.25  3557.5  328.05  3563.4  331.08  3598.3  331.22
  3986.5  330.39  4988.0  329.58  5027.6  329.74  5175.8  329.48  5485.9  329.20
  5712.2  329.40  5767.0  329.39  5977.0  330.01  6058.4  330.02  6222.3  330.77
  6640.6  341.35  6902.5  361.36  7136.1  367.59  7192.3  374.90  7264.8  376.61
#Mann=18,-1,0
  2388.8    0.05       0  2396.5    0.16       0  2748.0    0.12       0
  2872.5    0.16       0  3192.4    0.12       0  3480.3    0.16       0
  3551.5    0.03       0  3557.5    0.16       0  3598.3    0.05       0
  3986.5    0.12       0  4988.0    0.05       0  5027.6    0.07       0
  5175.8    0.12       0  5485.9    0.05       0  5712.2    0.12       0
  5767.0    0.05       0  5977.0    0.07       0  6058.4    0.05       0
Bank Sta=3535.6,6222.3
Exp/Cntr=0.3,0.1

Type RM Length L Ch R = 1,4117,3545,3545,3545
BEGIN DESCRIPTION:
Mapping XS e2bc957d
END DESCRIPTION:
XS GIS Cut Line= 4
      2910608.86      6975076.56      2909606.27      6972810.96
      2908473.46      6972680.76      2905453.29      6975440.56
#Sta/Elev= 30
  1731.0  374.74  2159.2  380.03  2371.6  372.70  2641.1  354.98  2837.3  339.87
  3044.5  330.12  3776.8  329.19  4904.6  329.77  5012.0  328.35  5012.5  327.55
  5018.1  328.35  5118.5  330.32  5244.5  331.61  5745.7  330.93  5916.7  334.01
  5947.8  331.44  7586.2  330.55  7598.5  330.93  7757.2  330.57  7795.6  329.86
  7917.8  329.39  8140.7  330.12  8592.6  336.00  8892.0  351.40  8918.2  356.65
  9030.3  357.41  9144.6  356.85  9174.1  361.53  9277.5  362.73  9440.0  367.13
#Mann=20,-1,0
  1731.0    0.05       0  2641.1    0.16       0  2837.3    0.12       0
  3776.8    0.07       0  4904.6    0.12       0  5012.0    0.07       0
  5018.1    0.12       0  5118.5    0.07       0  5244.5    0.12       0
  5745.7    0.07       0  5947.8    0.12       0  7586.2    0.07       0
  7598.5    0.12       0  7757.2    0.07       0  7795.6    0.12       0
  7917.8    0.05       0  8892.0     0.1       0  9030.3    0.15       0
  9174.1    0.08       0  9277.5    0.05       0
Bank Sta=3044.5,8140.7
Exp/Cntr=0.3,0.1

Type RM Length L Ch R = 1,572,0,0,0
BEGIN DESCRIPTION:
UNT 006 IN DRY CR WATERSHED 1.0
END DESCRIPTION:
XS GIS Cut Line= 4
      2911025.00      6974225.02      2910390.45      6970953.70
      2909254.71      6970193.78      2904975.02      6975074.98
#Sta/Elev= 30
  1205.6  376.60  1340.0  375.98  1566.7  364.62  1791.3  348.71  1894.8  340.69
  2254.8  329.13  4547.5  332.71  4799.4  327.76  4886.7  329.13  4891.5  326.87
  5042.7  324.24  5043.2  323.44  5049.1  324.24  5079.8  328.43  5774.9  328.10
  5859.6  333.27  6022.7  326.79  6146.1  326.87  7295.7  330.61  7514.7  330.92
  7642.2  330.61  7769.8  330.60  8105.8  332.03  8248.2  330.00  8485.2  329.92
  9682.8  330.97 10941.0  331.05 11878.5  335.30 12162.2  353.23 12396.1  358.28
#Mann=20,-1,0
  1205.6    0.16       0  1566.7    0.12       0  1791.3    0.16       0
  1894.8    0.12       0  4799.4    0.07       0  4886.7    0.12       0
  5042.7    0.07       0  5049.1    0.12       0  5079.8    0.07       0
  5774.9    0.12       0  6022.7    0.07       0  7295.7    0.12       0
  7514.7    0.05       0  7642.2    0.07       0  7769.8    0.12       0
  8105.8    0.05       0  8248.2    0.12       0  8485.2    0.05       0
  9682.8    0.12       0 10941.0    0.05       0
Bank Sta=4891.5,6146.1
Exp/Cntr=0.3,0.1

Chan Stop Cuts=-1