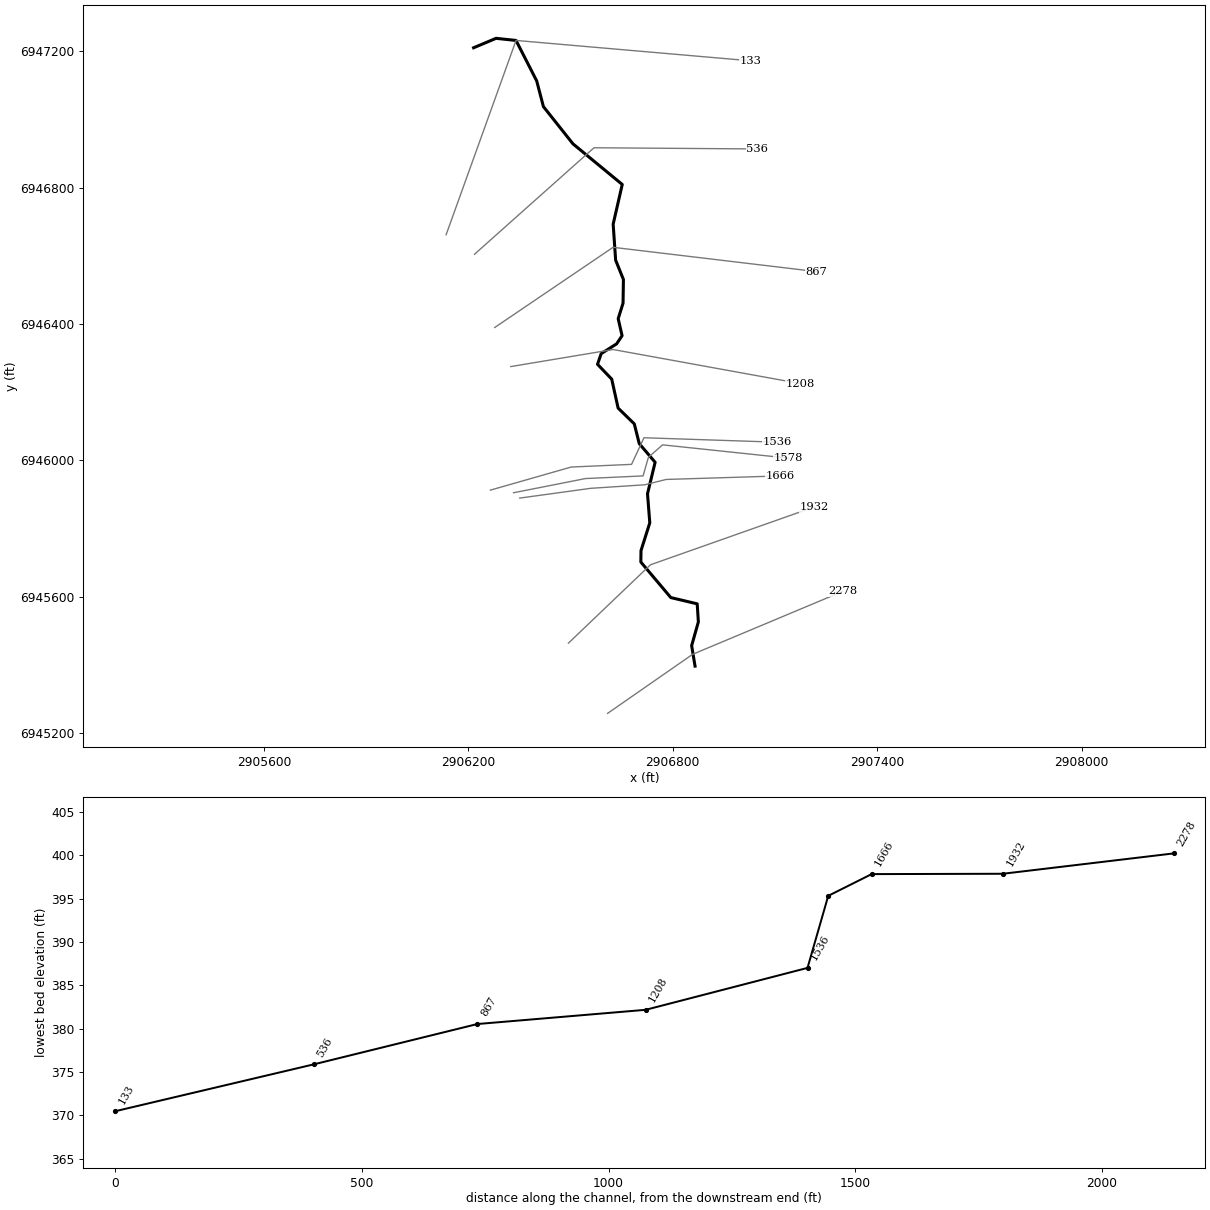
--- UNT 007 IN DRY CR WATERSHED.prj (project) ---

Proj Title=UNT 007 IN DRY CR WATERSHED Base Level Engineering
Current Plan=p01
Default Exp/Contr=0.3,0.1
English Units
Geom File=g01
Flow File=f01
Plan File=p01
BEGIN DESCRIPTION:
UNT 007 IN DRY CR WATERSHED
END DESCRIPTION:

--- UNT 007 IN DRY CR WATERSHED.p01 (plan) ---

Plan Title=Multiple Run
Short Identifier=Multiple
Geom File=g01
Flow File=f01
Subcritical Flow
K Sum by GR= 0
Std Step Tol= 0.01
Critical Tol= 0.01
Num of Std Step Trials= 20
Max Error Tol= 0.3
Flow Tol Ratio= 0.001
Split Flow NTrial= 30
Split Flow Tol= 0.02
Split Flow Ratio= 0.02
Log Output Level= 0
Friction Slope Method= 1
Unsteady Friction Slope Method= 2
Unsteady Bridges Friction Slope Method= 1
Parabolic Critical Depth
Global Vel Dist=  1 , 1 , 1
Global Log Level= 0
CheckData=True
Encroach Param= -1, 0, 0, 0
BEGIN DESCRIPTION:
Multiple Run
END DESCRIPTION:

--- UNT 007 IN DRY CR WATERSHED.f01 (steady flow) ---

Flow Title=Multiple
Number of Profiles=7
Profile Names=10-year,25-year,50-year,1pct_min,100-year,1pct_plu,500-year
River Rch & RM= UNT 007 IN DRY C,Reach-1,2278
     188     236     272     157     314     627     417
Boundary for River Rch & Prof#=UNT 007 IN DRY C,Reach-1,1
Up Type=0
Dn Type=3
Dn Slope=0.005
Boundary for River Rch & Prof#=UNT 007 IN DRY C,Reach-1,2
Up Type=0
Dn Type=3
Dn Slope=0.005
Boundary for River Rch & Prof#=UNT 007 IN DRY C,Reach-1,3
Up Type=0
Dn Type=3
Dn Slope=0.005
Boundary for River Rch & Prof#=UNT 007 IN DRY C,Reach-1,4
Up Type=0
Dn Type=3
Dn Slope=0.005
Boundary for River Rch & Prof#=UNT 007 IN DRY C,Reach-1,5
Up Type=0
Dn Type=3
Dn Slope=0.005
Boundary for River Rch & Prof#=UNT 007 IN DRY C,Reach-1,6
Up Type=0
Dn Type=3
Dn Slope=0.005
Boundary for River Rch & Prof#=UNT 007 IN DRY C,Reach-1,7
Up Type=0
Dn Type=3
Dn Slope=0.005

--- UNT 007 IN DRY CR WATERSHED.g01 (geometry) ---

Geom Title=Existing Conditions

River Reach=UNT 007 IN DRY C,Reach-1
Reach XY= 30
      2906865.59      6945395.71      2906855.59      6945455.80
      2906875.31      6945525.43      2906871.92      6945578.55
      2906794.48      6945596.90      2906706.46      6945701.22
      2906706.95      6945734.77      2906732.72      6945816.23
      2906726.04      6945901.65      2906748.42      6945994.08
      2906701.84      6946048.74      2906687.26      6946106.73
      2906639.78      6946153.08      2906620.99      6946238.11
      2906579.33      6946281.62      2906590.12      6946312.96
      2906635.41      6946341.66      2906651.40      6946365.66
      2906639.98      6946415.48      2906654.26      6946461.19
      2906655.33      6946530.59      2906632.54      6946587.14
      2906625.22      6946692.92      2906651.91      6946809.51
      2906507.15      6946928.80      2906420.48      6947038.02
      2906400.79      6947113.44      2906340.12      6947232.23
      2906281.42      6947238.40      2906215.59      6947210.71

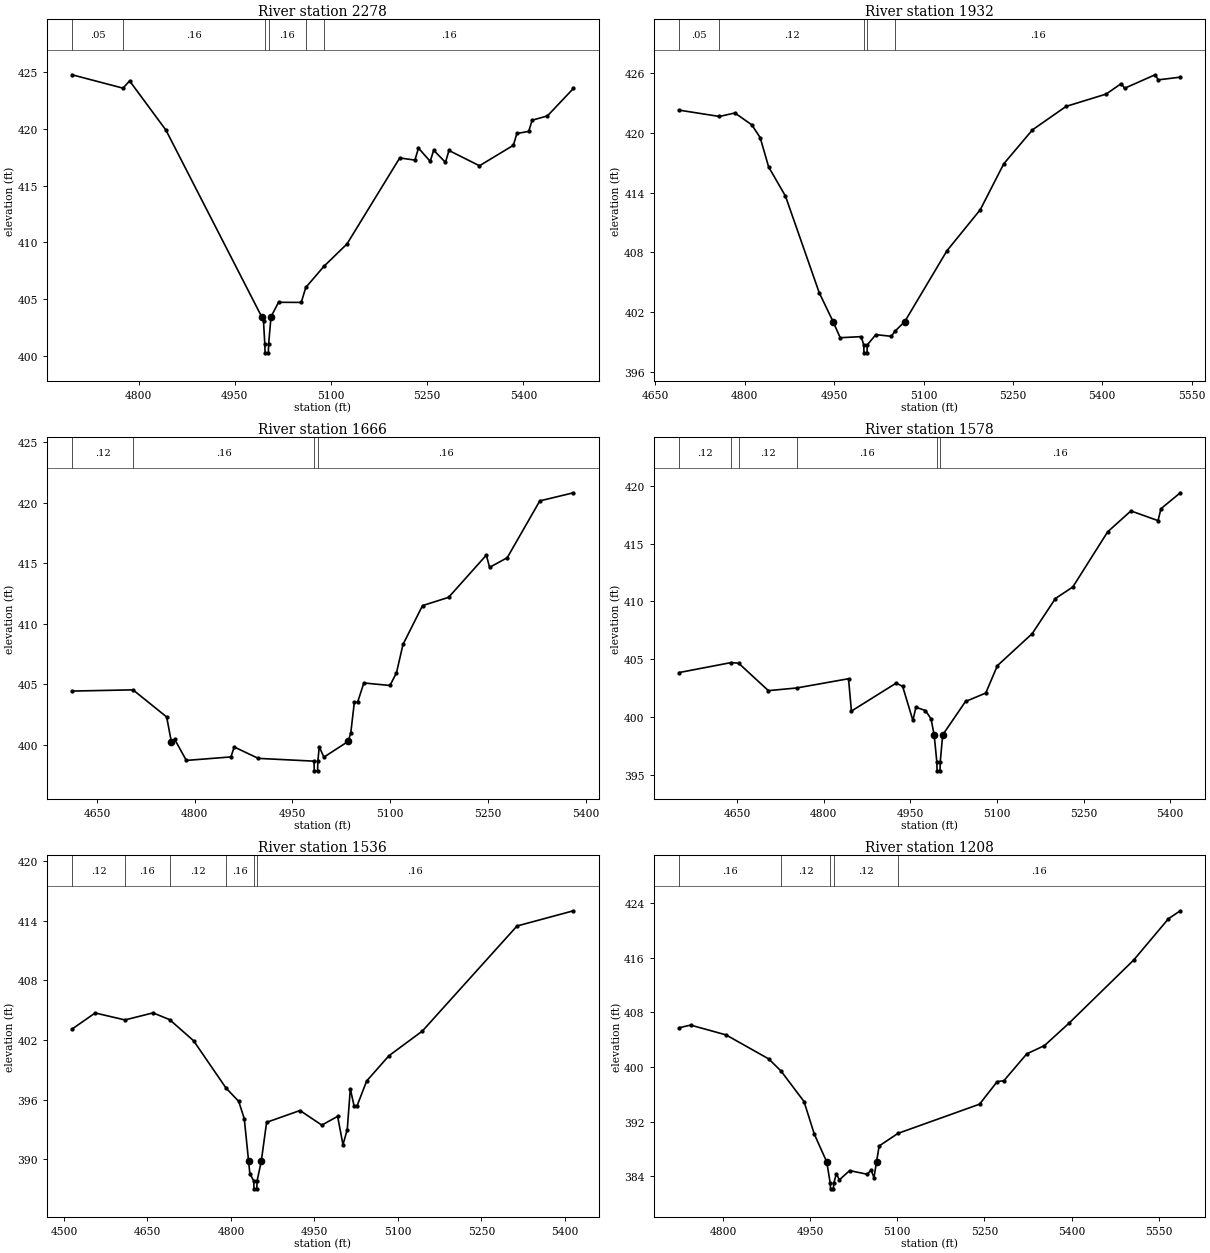
Type RM Length L Ch R = 1,2278,346,346,346
BEGIN DESCRIPTION:
UNT 007 IN DRY CR WATERSHED 5.0
END DESCRIPTION:
XS GIS Cut Line= 3
      2906608.91      6945257.03      2906858.24      6945430.26
      2907298.96      6945615.07
#Sta/Elev= 30
  4696.4  424.78  4775.8  423.60  4786.1  424.24  4842.8  419.89  4991.9  403.43
  4994.8  403.02  4996.8  401.04  4997.3  400.24  5002.3  400.24  5002.8  401.04
  5006.5  403.42  5018.2  404.70  5053.6  404.69  5060.7  406.01  5088.9  407.87
  5124.9  409.85  5207.1  417.44  5230.8  417.25  5236.3  418.31  5254.6  417.14
  5260.0  418.12  5278.4  417.05  5283.8  418.10  5331.4  416.75  5384.3  418.56
  5389.7  419.60  5408.1  419.78  5413.5  420.77  5437.3  421.15  5477.9  423.58
#Mann=6,-1,0
  4696.4    0.05       0  4775.8    0.16       0  4996.8    0.07       0
  5002.8    0.16       0  5060.7    0.12       0  5088.9    0.16       0
Bank Sta=4991.9,5006.5
Exp/Cntr=0.3,0.1

Type RM Length L Ch R = 1,1932,266,266,266
BEGIN DESCRIPTION:
Mapping XS 6d988215
END DESCRIPTION:
XS GIS Cut Line= 3
      2906493.88      6945463.19      2906734.75      6945693.21
      2907214.40      6945862.49
#Sta/Elev= 30
  4689.3  422.29  4757.4  421.65  4783.4  422.00  4811.7  420.81  4825.8  419.53
  4840.0  416.58  4868.3  413.64  4924.9  403.94  4948.2  401.03  4960.1  399.41
  4995.4  399.52  4999.6  398.69  5000.1  397.89  5005.1  397.89  5005.6  398.69
  5020.0  399.72  5046.0  399.55  5051.7  400.04  5068.5  401.03  5139.3  408.15
  5195.3  412.28  5234.7  416.89  5282.8  420.30  5339.3  422.66  5406.5  423.90
  5432.1  424.96  5437.4  424.48  5488.7  425.84  5494.0  425.33  5531.0  425.60
#Mann=5,-1,0
  4689.3    0.05       0  4757.4    0.12       0  4999.6    0.07       0
  5005.6    0.12       0  5051.7    0.16       0
Bank Sta=4948.2,5068.5
Exp/Cntr=0.3,0.1

Type RM Length L Ch R = 1,1666,88,88,88
BEGIN DESCRIPTION:
Mapping XS 95b70707
END DESCRIPTION:
XS GIS Cut Line= 5
      2906351.09      6945888.95      2906559.40      6945917.60
      2906718.26      6945928.01      2906780.76      6945943.64
      2907116.70      6945954.06
#Sta/Elev= 30
  4611.5  404.44  4705.1  404.54  4756.8  402.30  4763.9  400.27  4769.0  400.46
  4787.0  398.71  4855.5  399.00  4860.5  399.82  4897.5  398.88  4983.0  398.65
  4983.5  397.85  4988.5  397.85  4989.0  398.65  4991.1  399.84  4998.2  398.98
  5035.5  400.28  5039.5  400.97  5045.0  403.52  5050.0  403.52  5059.6  405.11
  5099.7  404.90  5109.7  405.95  5119.7  408.29  5149.7  411.50  5189.7  412.18
  5247.7  415.67  5252.7  414.66  5279.7  415.45  5329.8  420.15  5381.5  420.82
#Mann=4,-1,0
  4611.5    0.12       0  4705.1    0.16       0  4983.0    0.07       0
  4989.0    0.16       0
Bank Sta=4763.9,5035.5
Exp/Cntr=0.3,0.1

Type RM Length L Ch R = 1,1578,42,42,42
BEGIN DESCRIPTION:
Mapping XS c2d89216
END DESCRIPTION:
XS GIS Cut Line= 6
      2906332.83      6945904.58      2906543.78      6945946.24
      2906713.05      6945954.06      2906728.68      6946008.74
      2906770.34      6946045.20      2907140.07      6946006.15
#Sta/Elev= 30
  4549.1  403.84  4639.9  404.71  4652.7  404.65  4704.2  402.28  4753.2  402.51
  4843.0  403.31  4848.0  400.51  4925.5  402.93  4936.7  402.65  4954.5  399.70
  4959.7  400.84  4976.2  400.56  4985.9  399.84  4991.3  398.45  4995.9  396.14
  4996.4  395.34  5001.4  395.34  5001.9  396.14  5006.1  398.45  5045.6  401.34
  5080.7  402.07  5100.8  404.44  5161.1  407.21  5201.3  410.25  5231.5  411.25
  5291.8  416.02  5332.1  417.83  5379.1  416.99  5384.1  418.02  5417.6  419.40
#Mann=6,-1,0
  4549.1    0.12       0  4639.9    0.16       0  4652.7    0.12       0
  4753.2    0.16       0  4995.9    0.07       0  5001.9    0.16       0
Bank Sta=4991.3,5006.1
Exp/Cntr=0.3,0.1

Type RM Length L Ch R = 1,1536,328,328,328
BEGIN DESCRIPTION:
Mapping XS 67d23c72
END DESCRIPTION:
XS GIS Cut Line= 5
      2906265.13      6945912.39      2906502.11      6945980.10
      2906679.20      6945987.91      2906715.65      6946066.04
      2907106.30      6946053.01
#Sta/Elev= 30
  4514.5  403.09  4556.0  404.71  4609.6  404.01  4660.0  404.72  4689.8  404.04
  4732.8  401.92  4791.1  397.16  4813.9  395.82  4823.9  394.07  4831.7  389.78
  4833.9  388.55  4840.9  387.82  4841.4  387.02  4846.4  387.02  4846.9  387.82
  4854.4  389.78  4864.0  393.71  4924.0  394.90  4963.2  393.43  4991.6  394.31
  5001.2  391.46  5008.9  392.98  5014.4  397.08  5021.1  395.38  5026.6  395.38
  5043.8  397.87  5083.8  400.41  5143.8  402.89  5313.9  413.46  5415.3  414.99
#Mann=6,-1,0
  4514.5    0.12       0  4609.6    0.16       0  4689.8    0.12       0
  4791.1    0.16       0  4840.9    0.07       0  4846.9    0.16       0
Bank Sta=4831.7,4854.4
Exp/Cntr=0.3,0.1

Type RM Length L Ch R = 1,1208,341,341,341
BEGIN DESCRIPTION:
UNT 007 IN DRY CR WATERSHED 3.0
END DESCRIPTION:
XS GIS Cut Line= 3
      2906324.96      6946274.99      2906625.00      6946325.00
      2907175.01      6946225.00
#Sta/Elev= 30
  4723.9  405.73  4744.2  406.13  4805.0  404.70  4878.5  401.19  4899.6  399.43
  4939.4  394.95  4957.1  390.18  4978.6  386.10  4984.5  382.98  4985.0  382.18
  4990.0  382.18  4990.5  382.98  4995.1  384.40  5000.2  383.49  5017.9  384.85
  5048.4  384.31  5054.8  384.93  5059.8  383.82  5064.2  386.10  5068.7  388.45
  5101.1  390.29  5241.5  394.56  5272.0  397.87  5283.4  397.99  5322.8  401.92
  5353.3  403.13  5395.2  406.38  5507.1  415.66  5566.8  421.69  5587.1  422.85
#Mann=5,-1,0
  4723.9    0.16       0  4899.6    0.12       0  4984.5    0.07       0
  4990.5    0.12       0  5101.1    0.16       0
Bank Sta=4978.6,5064.2
Exp/Cntr=0.3,0.1

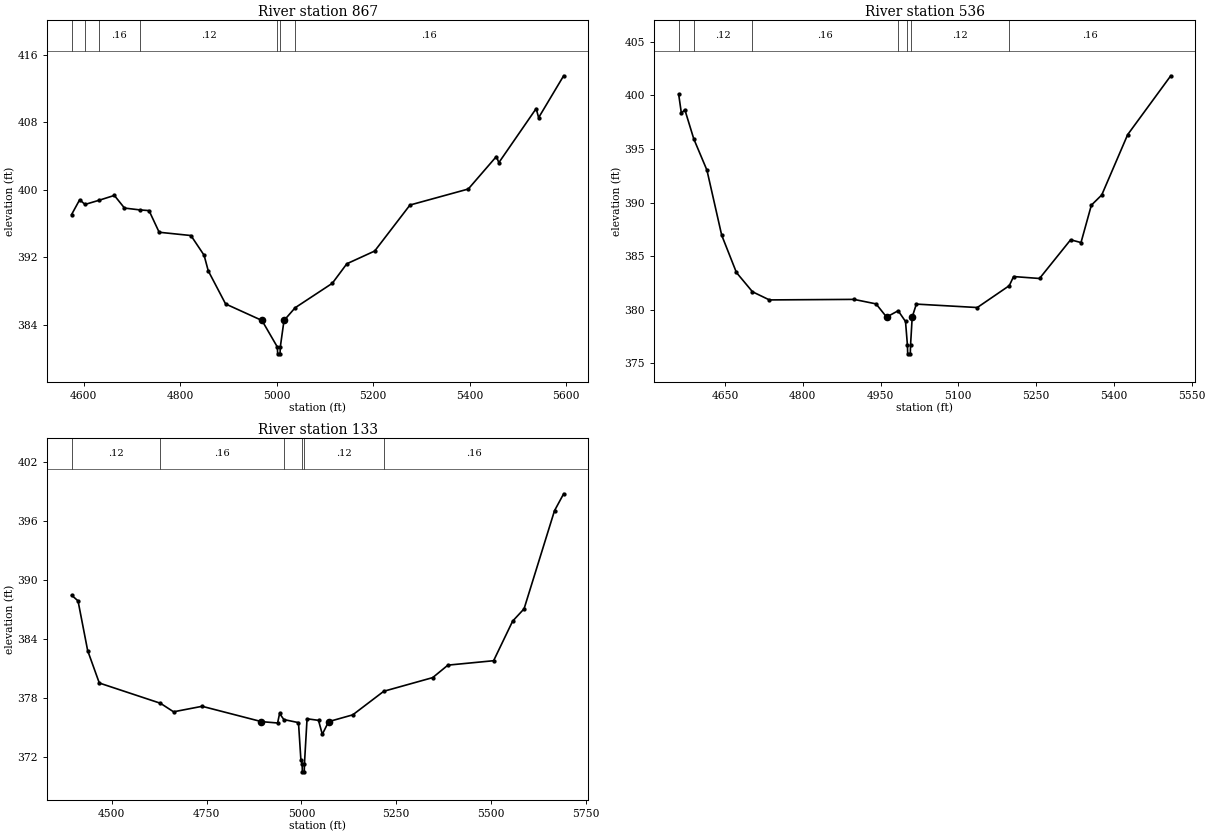
Type RM Length L Ch R = 1,867,331,331,331
BEGIN DESCRIPTION:
UNT 007 IN DRY CR WATERSHED 2.0
END DESCRIPTION:
XS GIS Cut Line= 3
      2906277.50      6946389.60      2906625.00      6946625.00
      2907221.44      6946553.83
#Sta/Elev= 30
  4574.7  397.07  4591.5  398.83  4602.5  398.27  4630.8  398.75  4663.4  399.34
  4684.4  397.84  4716.6  397.62  4735.3  397.54  4756.3  394.97  4822.2  394.58
  4849.5  392.24  4858.1  390.39  4894.1  386.46  4969.5  384.50  5001.5  381.34
  5002.0  380.54  5007.0  380.54  5007.5  381.34  5015.2  384.50  5038.3  386.01
  5115.3  388.91  5145.5  391.23  5203.2  392.74  5276.4  398.20  5397.3  400.10
  5455.6  403.96  5460.7  403.23  5538.1  409.65  5543.2  408.57  5595.1  413.54
#Mann=7,-1,0
  4574.7    0.16       0  4602.5    0.12       0  4630.8    0.16       0
  4716.6    0.12       0  5001.5    0.07       0  5007.5    0.12       0
  5038.3    0.16       0
Bank Sta=4969.5,5015.2
Exp/Cntr=0.3,0.1

Type RM Length L Ch R = 1,536,403,403,403
BEGIN DESCRIPTION:
Mapping XS f61579c5
END DESCRIPTION:
XS GIS Cut Line= 3
      2906218.27      6946604.68      2906569.00      6946917.21
      2907048.12      6946913.74
#Sta/Elev= 30
  4560.8  400.09  4566.0  398.33  4572.6  398.67  4589.9  395.94  4615.3  393.02
  4643.7  386.96  4672.1  383.48  4703.1  381.68  4735.7  380.92  4898.7  380.97
  4941.4  380.55  4961.7  379.32  4984.0  379.91  4998.2  378.91  5001.9  376.69
  5002.4  375.89  5007.4  375.89  5007.9  376.69  5011.1  379.32  5019.1  380.53
  5136.6  380.21  5198.3  382.25  5206.6  383.10  5256.6  382.92  5316.6  386.53
  5336.6  386.27  5356.6  389.76  5376.6  390.71  5426.6  396.34  5509.7  401.83
#Mann=7,-1,0
  4560.8    0.16       0  4589.9    0.12       0  4703.1    0.16       0
  4984.0    0.12       0  5001.9    0.07       0  5007.9    0.12       0
  5198.3    0.16       0
Bank Sta=4961.7,5011.1
Exp/Cntr=0.3,0.1

Type RM Length L Ch R = 1,133,0,0,0
BEGIN DESCRIPTION:
UNT 007 IN DRY CR WATERSHED 1.0
END DESCRIPTION:
XS GIS Cut Line= 3
      2906134.97      6946662.01      2906340.12      6947232.23
      2907029.02      6947172.42
#Sta/Elev= 30
  4394.0  388.45  4411.0  387.87  4436.4  382.81  4467.1  379.51  4628.2  377.45
  4662.9  376.58  4738.2  377.14  4894.7  375.58  4937.2  375.44  4942.5  376.41
  4953.7  375.79  4992.3  375.48  4998.6  371.72  5002.0  371.27  5002.5  370.47
  5007.5  370.47  5008.0  371.27  5014.9  375.87  5045.1  375.71  5055.1  374.29
  5071.8  375.58  5135.4  376.27  5217.2  378.67  5346.2  380.06  5386.3  381.33
  5506.8  381.78  5557.0  385.81  5587.1  387.06  5667.4  397.05  5691.5  398.77
#Mann=6,-1,0
  4394.0    0.12       0  4628.2    0.16       0  4953.7    0.12       0
  5002.0    0.07       0  5008.0    0.12       0  5217.2    0.16       0
Bank Sta=4894.7,5071.8
Exp/Cntr=0.3,0.1

Chan Stop Cuts=-1