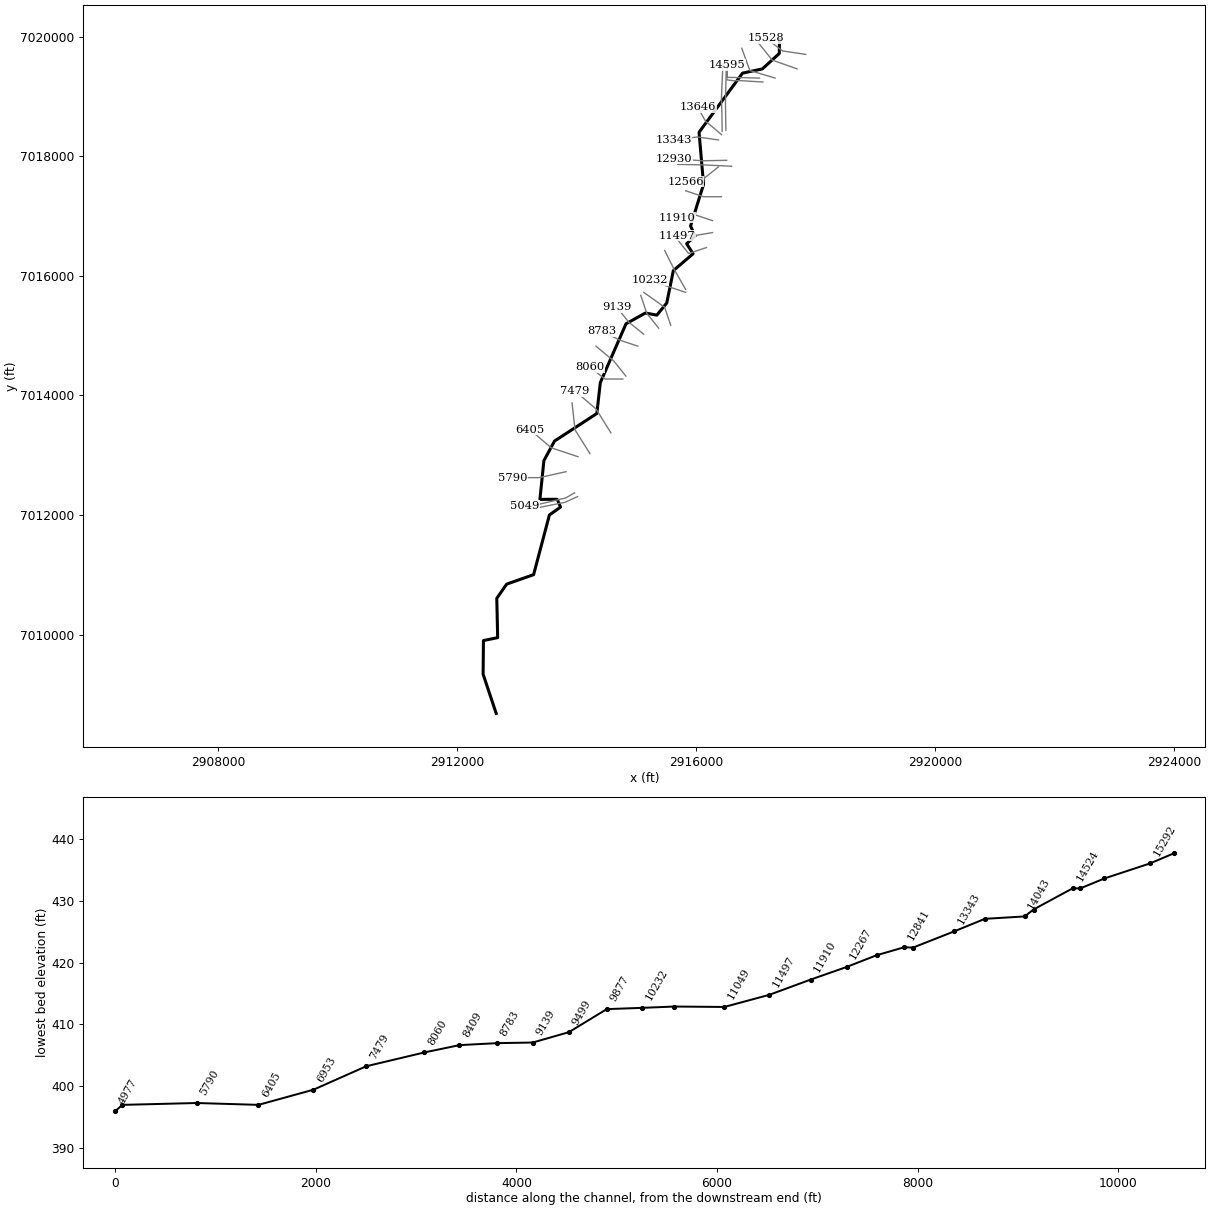
--- UNT 008 IN DRY CR WATERSHED.prj (project) ---

Proj Title=UNT 008 IN DRY CR WATERSHED Base Level Engineering
Current Plan=p01
Default Exp/Contr=0.3,0.1
English Units
Geom File=g01
Flow File=f01
Plan File=p01
BEGIN DESCRIPTION:
UNT 008 IN DRY CR WATERSHED
END DESCRIPTION:

--- UNT 008 IN DRY CR WATERSHED.p01 (plan) ---

Plan Title=Multiple Run
Short Identifier=Multiple
Geom File=g01
Flow File=f01
Subcritical Flow
K Sum by GR= 0
Std Step Tol= 0.01
Critical Tol= 0.01
Num of Std Step Trials= 20
Max Error Tol= 0.3
Flow Tol Ratio= 0.001
Split Flow NTrial= 30
Split Flow Tol= 0.02
Split Flow Ratio= 0.02
Log Output Level= 0
Friction Slope Method= 1
Unsteady Friction Slope Method= 2
Unsteady Bridges Friction Slope Method= 1
Parabolic Critical Depth
Global Vel Dist=  1 , 1 , 1
Global Log Level= 0
CheckData=True
Encroach Param= -1, 0, 0, 0
BEGIN DESCRIPTION:
Multiple Run
END DESCRIPTION:

--- UNT 008 IN DRY CR WATERSHED.f01 (steady flow) ---

Flow Title=Multiple
Number of Profiles=7
Profile Names=10-year,25-year,50-year,1pct_min,100-year,1pct_plu,500-year
River Rch & RM= UNT 008 IN DRY C,Reach-1,15528
     506     673     808     482     962    1919    1367
River Rch & RM= UNT 008 IN DRY C,Reach-1,7479
     742    1004    1219     734    1465    2924    2124
Boundary for River Rch & Prof#=UNT 008 IN DRY C,Reach-1,1
Up Type=0
Dn Type=3
Dn Slope=0.005
Boundary for River Rch & Prof#=UNT 008 IN DRY C,Reach-1,2
Up Type=0
Dn Type=3
Dn Slope=0.005
Boundary for River Rch & Prof#=UNT 008 IN DRY C,Reach-1,3
Up Type=0
Dn Type=3
Dn Slope=0.005
Boundary for River Rch & Prof#=UNT 008 IN DRY C,Reach-1,4
Up Type=0
Dn Type=3
Dn Slope=0.005
Boundary for River Rch & Prof#=UNT 008 IN DRY C,Reach-1,5
Up Type=0
Dn Type=3
Dn Slope=0.005
Boundary for River Rch & Prof#=UNT 008 IN DRY C,Reach-1,6
Up Type=0
Dn Type=3
Dn Slope=0.005
Boundary for River Rch & Prof#=UNT 008 IN DRY C,Reach-1,7
Up Type=0
Dn Type=3
Dn Slope=0.005

--- UNT 008 IN DRY CR WATERSHED.g01 (geometry) ---

Geom Title=Existing Conditions

River Reach=UNT 008 IN DRY C,Reach-1
Reach XY= 30
      2917395.28      7019962.29      2917392.57      7019721.95
      2917109.32      7019463.79      2916777.56      7019393.08
      2916049.92      7018403.63      2916125.28      7017530.89
      2915907.73      7016834.68      2915983.54      7016666.55
      2915842.16      7016538.40      2915950.60      7016371.09
      2915619.51      7016088.53      2915510.00      7015548.10
      2915344.08      7015344.00      2915151.58      7015379.01
      2914827.87      7015199.39      2914397.84      7014214.78
      2914339.96      7013698.10      2913632.05      7013237.24
      2913454.13      7012909.56      2913387.29      7012261.34
      2913676.35      7012262.64      2913732.38      7012132.24
      2913546.14      7012000.27      2913281.82      7011001.57
      2912830.98      7010842.96      2912665.66      7010605.72
      2912680.56      7009947.78      2912442.37      7009899.16
      2912437.00      7009335.88      2912655.59      7008680.71

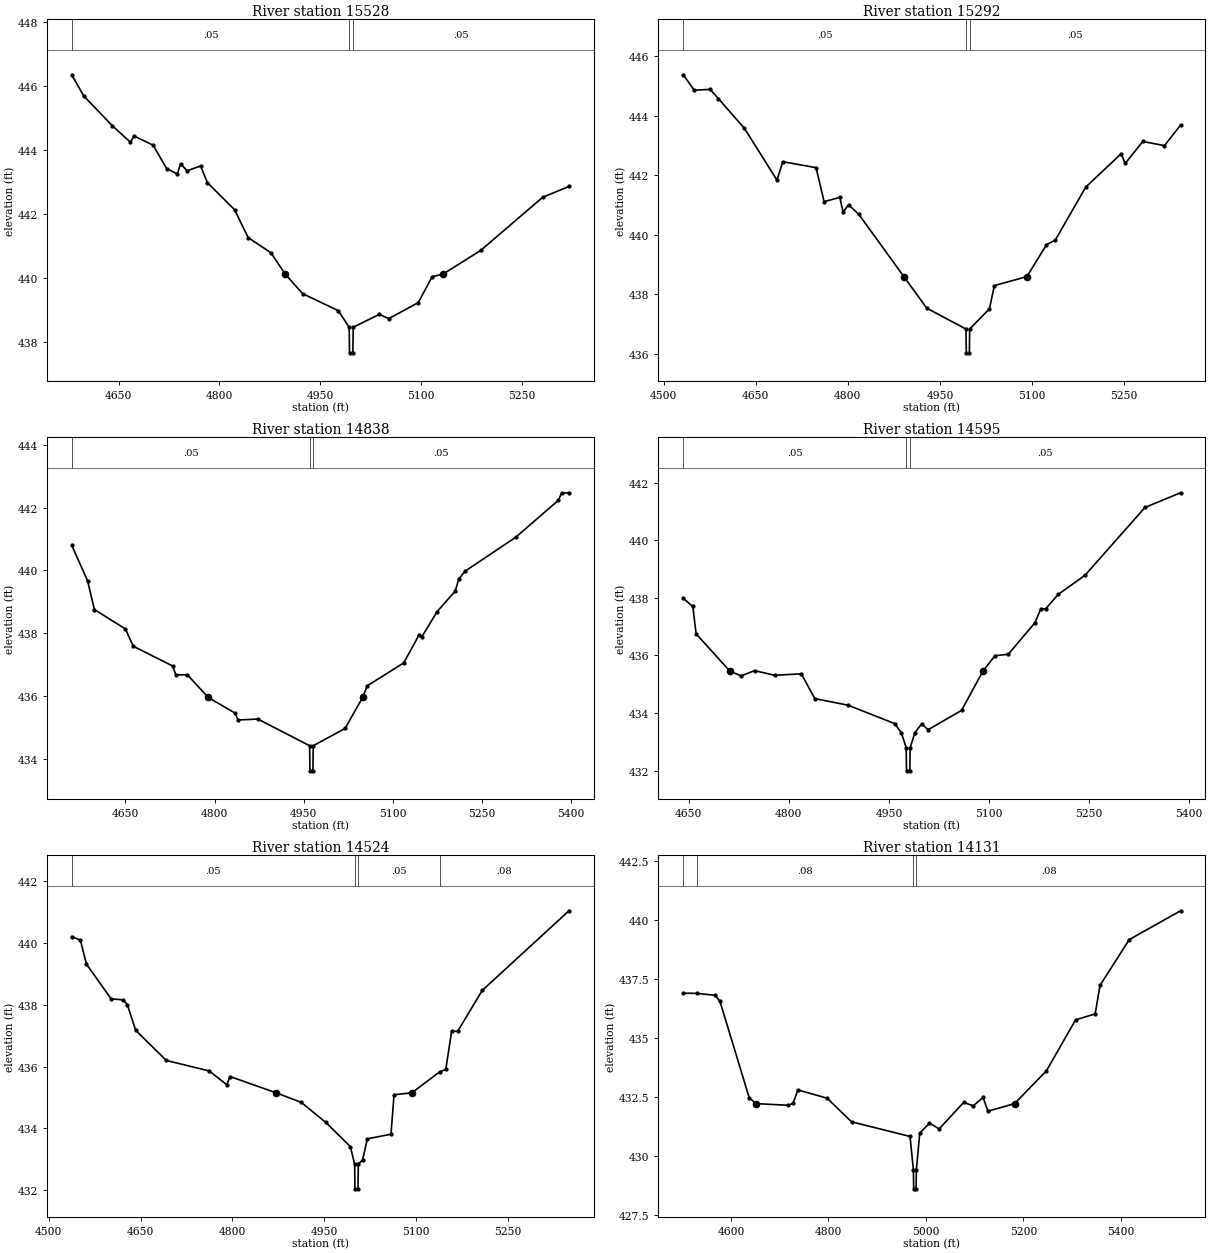
Type RM Length L Ch R = 1,15528,236,236,236
BEGIN DESCRIPTION:
UNT 008 IN DRY CR WATERSHED 32.0
END DESCRIPTION:
XS GIS Cut Line= 3
      2917834.68      7019706.98      2917446.69      7019764.27
      2917170.66      7019975.20
#Sta/Elev= 30
  4580.3  446.35  4598.1  445.69  4640.6  444.76  4667.7  444.24  4672.7  444.44
  4701.3  444.15  4721.5  443.42  4737.3  443.25  4742.3  443.57  4751.8  443.35
  4772.0  443.50  4782.1  442.98  4822.6  442.13  4842.8  441.26  4876.5  440.79
  4897.9  440.12  4923.7  439.51  4976.7  438.98  4993.0  438.46  4993.5  437.66
  4998.5  437.66  4999.0  438.46  5037.6  438.86  5052.1  438.73  5095.7  439.23
  5116.5  440.04  5132.5  440.12  5188.6  440.86  5280.7  442.52  5319.9  442.86
#Mann=3,-1,0
  4580.3    0.05       0  4993.0    0.03       0  4999.0    0.05       0
Bank Sta=4897.9,5132.5
Exp/Cntr=0.3,0.1

Type RM Length L Ch R = 1,15292,454,454,454
BEGIN DESCRIPTION:
Mapping XS 882c0a3f
END DESCRIPTION:
XS GIS Cut Line= 3
      2917688.84      7019464.80      2917274.82      7019610.62
      2917043.02      7019899.72
#Sta/Elev= 30
  4532.2  445.38  4550.0  444.86  4575.7  444.89  4589.3  444.58  4631.7  443.58
  4684.7  441.84  4694.2  442.46  4748.3  442.26  4761.4  441.12  4787.0  441.26
  4792.3  440.77  4801.3  441.01  4818.0  440.69  4891.3  438.60  4928.5  437.54
  4992.4  436.84  4992.9  436.04  4997.9  436.04  4998.4  436.84  5030.6  437.52
  5038.6  438.30  5091.6  438.60  5123.4  439.67  5137.8  439.83  5187.5  441.61
  5245.1  442.73  5251.5  442.40  5280.3  443.14  5315.5  443.00  5341.7  443.69
#Mann=3,-1,0
  4532.2    0.05       0  4992.4    0.03       0  4998.4    0.05       0
Bank Sta=4891.3,5091.6
Exp/Cntr=0.3,0.1

Type RM Length L Ch R = 1,14838,243,243,243
BEGIN DESCRIPTION:
UNT 008 IN DRY CR WATERSHED 31.0
END DESCRIPTION:
XS GIS Cut Line= 3
      2917321.66      7019311.16      2916899.43      7019436.70
      2916764.93      7019809.48
#Sta/Elev= 30
  4559.5  440.80  4586.3  439.66  4597.7  438.75  4649.9  438.13  4663.1  437.58
  4729.5  436.95  4734.7  436.67  4754.2  436.67  4789.1  435.95  4834.3  435.45
  4839.5  435.23  4872.7  435.26  4959.9  434.41  4960.4  433.61  4965.4  433.61
  4965.9  434.41  5019.5  434.96  5049.1  435.95  5056.9  436.32  5118.3  437.05
  5143.7  437.93  5149.0  437.89  5174.3  438.68  5205.0  439.34  5210.8  439.72
  5221.4  439.97  5306.5  441.05  5378.5  442.23  5383.8  442.46  5396.3  442.47
#Mann=3,-1,0
  4559.5    0.05       0  4959.9    0.03       0  4965.9    0.05       0
Bank Sta=4789.1,5049.1
Exp/Cntr=0.3,0.1

Type RM Length L Ch R = 1,14595,71,71,71
BEGIN DESCRIPTION:
Mapping XS 57aa1dd9
END DESCRIPTION:
XS GIS Cut Line= 4
      2917061.79      7019309.50      2916803.99      7019317.31
      2916522.74      7019322.52      2916520.13      7019528.28
#Sta/Elev= 30
  4641.9  437.98  4656.1  437.70  4661.1  436.75  4711.8  435.45  4728.7  435.29
  4748.7  435.47  4778.8  435.31  4818.8  435.36  4838.8  434.50  4888.8  434.27
  4958.8  433.63  4968.8  433.30  4975.8  432.79  4976.3  431.99  4981.3  431.99
  4981.8  432.79  4988.8  433.31  4998.8  433.62  5008.8  433.42  5058.8  434.09
  5090.7  435.45  5108.8  435.99  5128.8  436.04  5168.9  437.14  5177.5  437.62
  5184.9  437.62  5203.6  438.12  5243.6  438.78  5333.6  441.14  5386.9  441.65
#Mann=3,-1,0
  4641.9    0.05       0  4975.8    0.04       0  4981.8    0.05       0
Bank Sta=4711.8,5090.7
Exp/Cntr=0.3,0.1

Type RM Length L Ch R = 1,14524,393,393,393
BEGIN DESCRIPTION:
Mapping XS 5ed1b72f
END DESCRIPTION:
XS GIS Cut Line= 5
      2917119.07      7019244.39      2916733.67      7019267.83
      2916634.72      7019265.22      2916514.92      7019280.85
      2916514.92      7019486.54
#Sta/Elev= 30
  4537.7  440.21  4551.8  440.10  4561.8  439.32  4601.9  438.20  4621.9  438.16
  4628.5  438.01  4642.0  437.18  4692.1  436.20  4762.2  435.86  4791.0  435.41
  4796.0  435.68  4871.6  435.15  4912.5  434.84  4952.5  434.19  4992.5  433.41
  4999.5  432.84  5000.0  432.04  5005.0  432.04  5005.5  432.84  5012.5  432.98
  5020.2  433.66  5058.8  433.81  5063.8  435.09  5092.6  435.15  5138.3  435.83
  5148.2  435.91  5157.8  437.14  5167.8  437.15  5207.8  438.47  5349.3  441.05
#Mann=4,-1,0
  4537.7    0.05       0  4999.5    0.04       0  5005.5    0.05       0
  5138.3    0.08       0
Bank Sta=4871.6,5092.6
Exp/Cntr=0.3,0.1

Type RM Length L Ch R = 1,14131,88,88,88
BEGIN DESCRIPTION:
Mapping XS 193aa6c3
END DESCRIPTION:
XS GIS Cut Line= 3
      2916499.30      7018439.71      2916491.49      7018898.04
      2916504.50      7019460.30
#Sta/Elev= 30
  4502.0  436.88  4530.1  436.87  4567.3  436.79  4577.3  436.53  4637.3  432.45
  4651.1  432.20  4717.3  432.13  4727.3  432.21  4737.3  432.78  4797.3  432.43
  4847.3  431.43  4967.4  430.81  4974.4  429.39  4974.9  428.59  4979.9  428.59
  4980.4  429.39  4987.4  430.95  5007.4  431.37  5027.4  431.13  5077.4  432.25
  5097.4  432.11  5117.4  432.46  5127.4  431.88  5182.1  432.20  5247.4  433.59
  5307.4  435.75  5347.5  436.00  5357.5  437.21  5417.5  439.15  5522.8  440.37
#Mann=4,-1,0
  4502.0    0.05       0  4530.1    0.08       0  4974.4    0.07       0
  4980.4    0.08       0
Bank Sta=4651.1,5182.1
Exp/Cntr=0.3,0.1

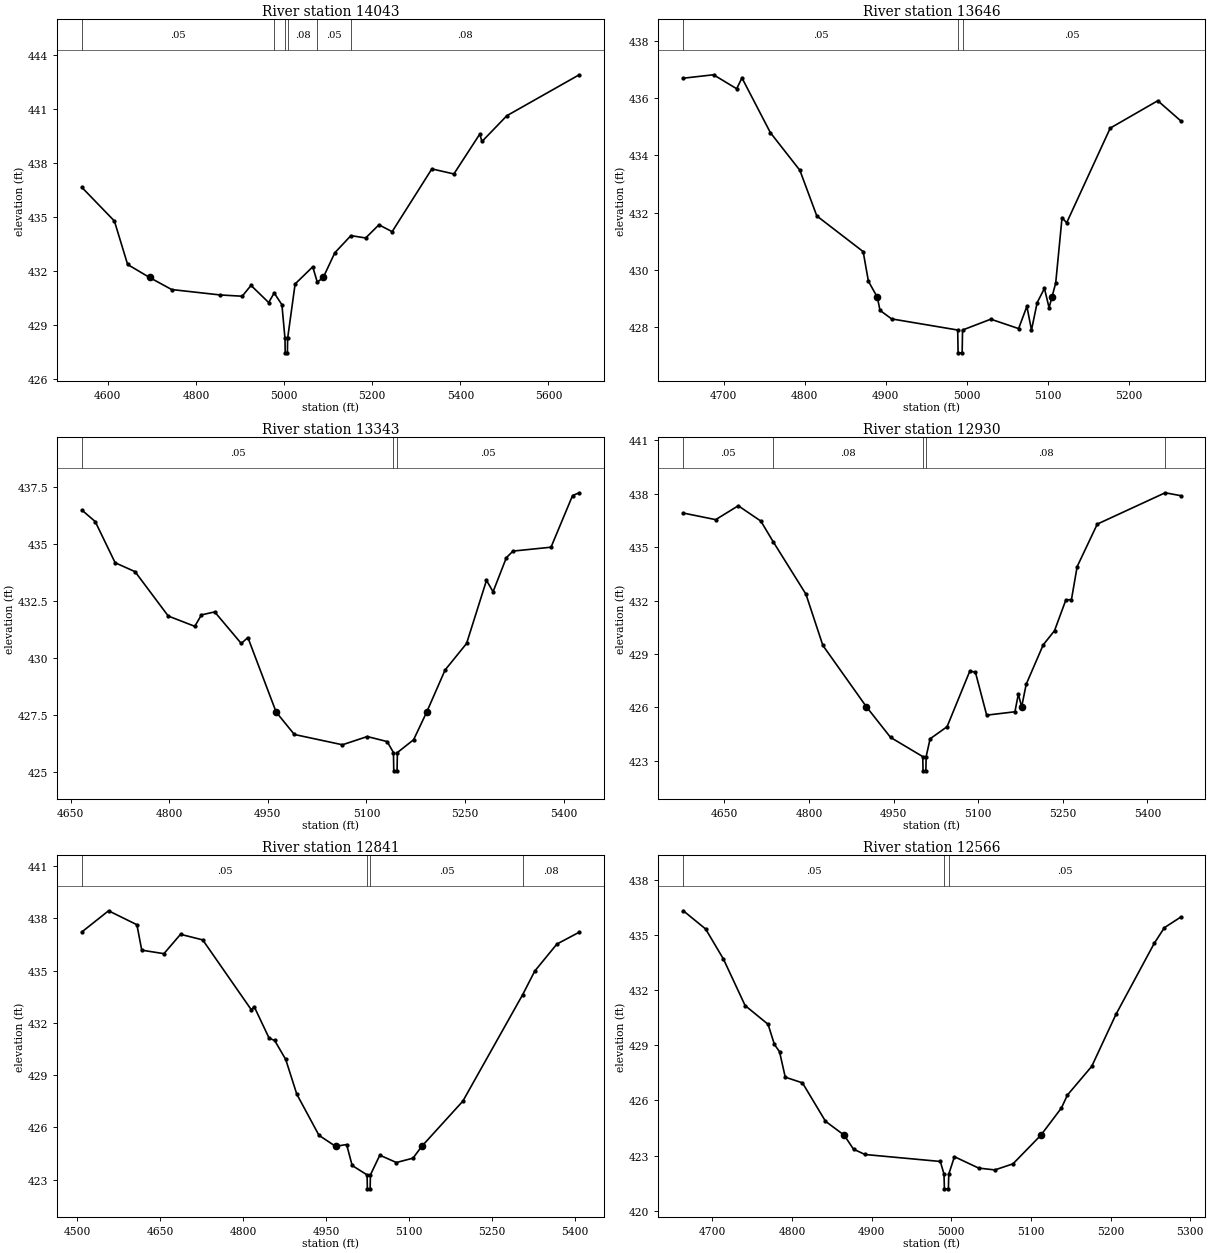
Type RM Length L Ch R = 1,14043,397,397,397
BEGIN DESCRIPTION:
Mapping XS 40217c1d
END DESCRIPTION:
XS GIS Cut Line= 4
      2916436.80      7018421.44      2916431.59      7018757.41
      2916423.78      7018960.54      2916449.82      7019549.08
#Sta/Elev= 30
  4541.4  436.64  4615.0  434.78  4645.0  432.37  4694.7  431.65  4745.0  430.98
  4855.0  430.68  4905.0  430.61  4925.0  431.21  4965.1  430.26  4977.6  430.79
  4995.1  430.14  5002.1  428.27  5002.6  427.47  5007.6  427.47  5008.1  428.27
  5025.1  431.29  5065.1  432.24  5075.4  431.39  5089.0  431.65  5115.2  433.02
  5151.7  433.97  5185.2  433.84  5215.3  434.57  5245.3  434.19  5335.4  437.67
  5385.4  437.39  5444.1  439.60  5449.1  439.19  5505.6  440.62  5669.8  442.89
#Mann=6,-1,0
  4541.4    0.05       0  4977.6    0.08       0  5002.1    0.07       0
  5008.1    0.08       0  5075.4    0.05       0  5151.7    0.08       0
Bank Sta=4694.7,5089
Exp/Cntr=0.3,0.1

Type RM Length L Ch R = 1,13646,303,303,303
BEGIN DESCRIPTION:
UNT 008 IN DRY CR WATERSHED 28.0
END DESCRIPTION:
XS GIS Cut Line= 3
      2916426.35      7018364.21      2916158.31      7018588.97
      2916029.80      7018819.58
#Sta/Elev= 30
  4650.2  436.71  4687.5  436.83  4716.1  436.34  4722.6  436.72  4757.7  434.80
  4794.1  433.48  4815.0  431.88  4872.2  430.63  4878.7  429.59  4889.7  429.03
  4893.0  428.57  4907.3  428.27  4988.9  427.88  4989.4  427.08  4994.4  427.08
  4994.9  427.88  5029.8  428.26  5064.1  427.93  5074.3  428.71  5080.0  427.88
  5087.0  428.84  5096.0  429.34  5101.7  428.66  5105.2  429.03  5109.9  429.53
  5117.7  431.82  5123.4  431.64  5177.2  434.96  5235.9  435.92  5264.0  435.22
#Mann=3,-1,0
  4650.2    0.05       0  4988.9    0.03       0  4994.9    0.05       0
Bank Sta=4889.7,5105.2
Exp/Cntr=0.3,0.1

Type RM Length L Ch R = 1,13343,413,413,413
BEGIN DESCRIPTION:
UNT 008 IN DRY CR WATERSHED 27.0
END DESCRIPTION:
XS GIS Cut Line= 3
      2916374.99      7018275.00      2916025.00      7018325.00
      2915624.95      7018274.99
#Sta/Elev= 30
  4667.1  436.47  4687.3  435.97  4717.6  434.17  4747.9  433.78  4798.4  431.84
  4838.8  431.39  4848.9  431.89  4869.1  432.02  4909.5  430.64  4919.6  430.90
  4962.6  427.64  4990.3  426.66  5063.5  426.21  5101.3  426.57  5131.5  426.35
  5141.1  425.87  5141.6  425.07  5146.6  425.07  5147.1  425.87  5171.8  426.43
  5191.7  427.64  5219.7  429.48  5252.4  430.64  5282.7  433.40  5292.7  432.90
  5312.9  434.39  5323.0  434.68  5380.9  434.85  5413.7  437.11  5423.8  437.23
#Mann=3,-1,0
  4667.1    0.05       0  5141.1    0.03       0  5147.1    0.05       0
Bank Sta=4962.6,5191.7
Exp/Cntr=0.3,0.1

Type RM Length L Ch R = 1,12930,89,89,89
BEGIN DESCRIPTION:
Mapping XS d78ff45b
END DESCRIPTION:
XS GIS Cut Line= 3
      2916512.36      7017934.50      2916103.47      7017926.68
      2915632.14      7017960.53
#Sta/Elev= 30
  4577.2  436.92  4634.6  436.55  4674.6  437.33  4714.6  436.47  4736.3  435.32
  4794.6  432.36  4824.6  429.48  4901.8  426.03  4944.6  424.31  5001.7  423.23
  5002.2  422.43  5007.2  422.43  5007.7  423.23  5014.7  424.23  5044.8  424.91
  5084.9  428.02  5094.9  427.99  5115.0  425.56  5165.1  425.75  5171.1  426.74
  5177.0  426.03  5185.1  427.30  5215.2  429.51  5235.3  430.31  5255.3  432.03
  5265.3  432.06  5275.4  433.91  5311.1  436.30  5431.4  438.06  5458.7  437.90
#Mann=5,-1,0
  4577.2    0.05       0  4736.3    0.08       0  5001.7    0.07       0
  5007.7    0.08       0  5431.4    0.05       0
Bank Sta=4901.8,5177
Exp/Cntr=0.3,0.1

Type RM Length L Ch R = 1,12841,275,275,275
BEGIN DESCRIPTION:
Mapping XS 6b9bea43
END DESCRIPTION:
XS GIS Cut Line= 3
      2916593.02      7017835.54      2916147.74      7017856.37
      2915694.63      7017866.79
#Sta/Elev= 30
  4508.2  437.22  4556.3  438.43  4607.5  437.63  4616.3  436.17  4656.4  435.97
  4686.4  437.08  4726.5  436.76  4814.6  432.74  4819.6  432.93  4846.6  431.12
  4856.6  430.99  4876.6  429.90  4896.6  427.91  4936.7  425.55  4966.6  424.92
  4986.7  425.02  4996.7  423.82  5023.7  423.28  5024.2  422.48  5029.2  422.48
  5029.7  423.28  5046.7  424.41  5076.7  423.99  5106.7  424.24  5122.6  424.92
  5196.8  427.51  5305.0  433.62  5326.8  434.97  5366.8  436.52  5407.2  437.20
#Mann=4,-1,0
  4508.2    0.05       0  5023.7    0.03       0  5029.7    0.05       0
  5305.0    0.08       0
Bank Sta=4966.6,5122.6
Exp/Cntr=0.3,0.1

Type RM Length L Ch R = 1,12566,299,299,299
BEGIN DESCRIPTION:
UNT 008 IN DRY CR WATERSHED 25.0
END DESCRIPTION:
XS GIS Cut Line= 3
      2916374.98      7017824.98      2916125.00      7017625.00
      2915824.97      7017575.00
#Sta/Elev= 30
  4663.6  436.33  4691.6  435.34  4714.0  433.70  4741.2  431.17  4770.0  430.15
  4778.0  429.05  4784.4  428.66  4791.6  427.27  4813.2  426.96  4842.1  424.87
  4865.6  424.11  4877.3  423.35  4891.7  423.06  4986.3  422.68  4990.9  421.99
  4991.4  421.19  4996.4  421.19  4996.9  421.99  5004.0  422.94  5034.4  422.32
  5054.7  422.22  5077.5  422.55  5112.5  424.11  5138.3  425.59  5145.9  426.30
  5176.4  427.86  5206.8  430.69  5254.9  434.56  5267.6  435.41  5287.9  435.98
#Mann=3,-1,0
  4663.6    0.05       0  4990.9    0.03       0  4996.9    0.05       0
Bank Sta=4865.6,5112.5
Exp/Cntr=0.3,0.1

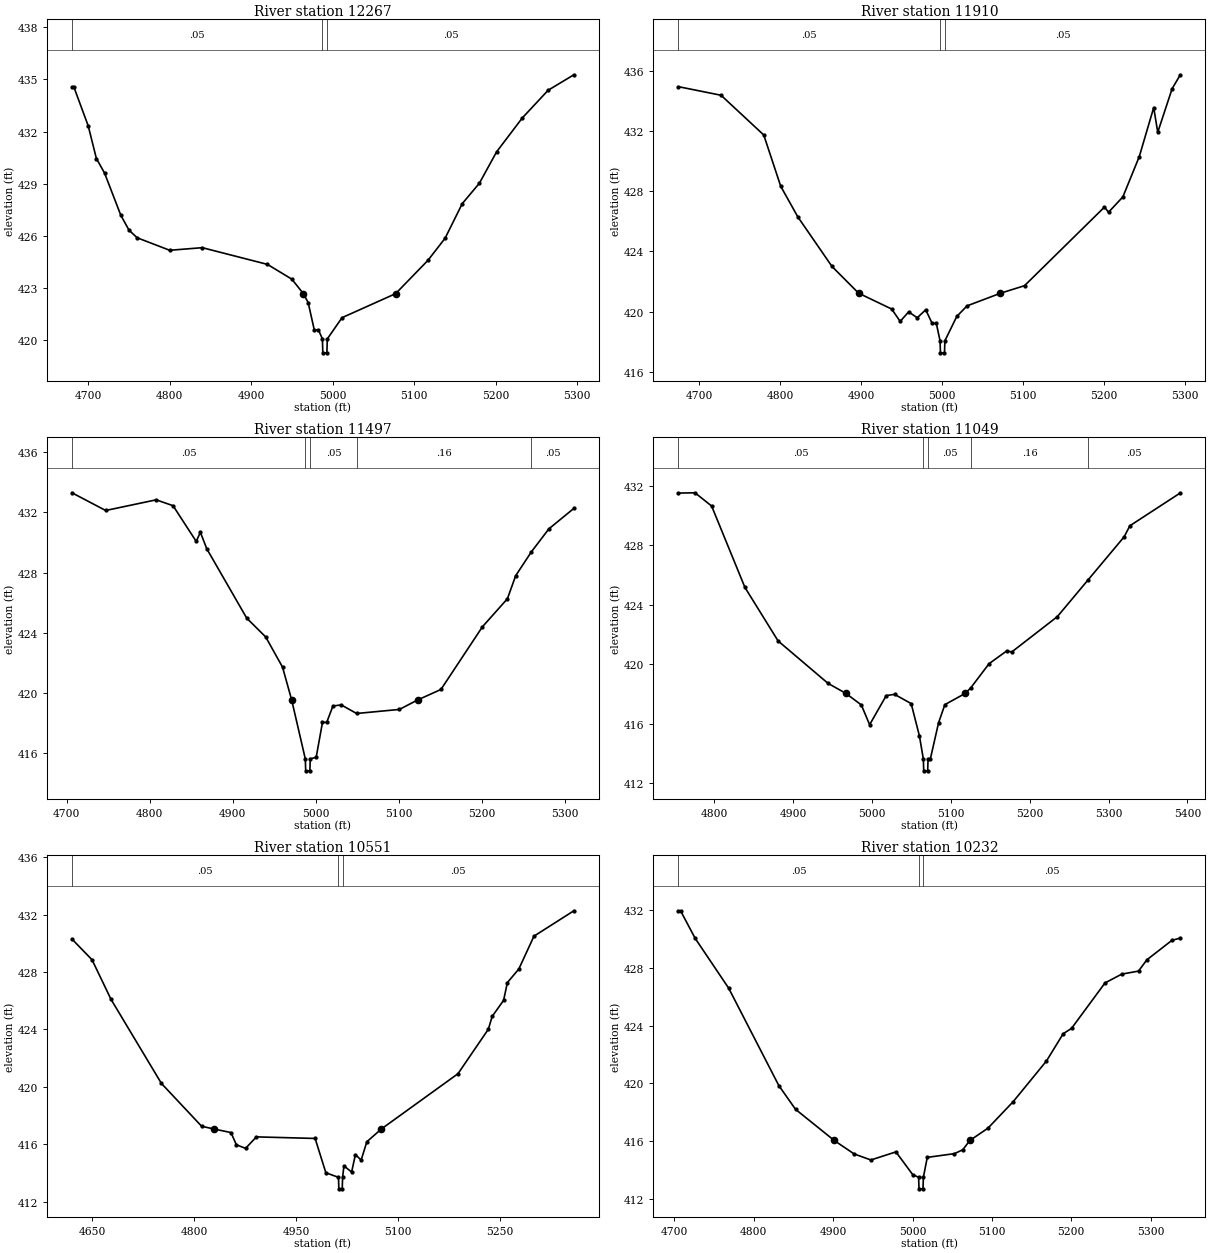
Type RM Length L Ch R = 1,12267,357,357,357
BEGIN DESCRIPTION:
UNT 008 IN DRY CR WATERSHED 24.0
END DESCRIPTION:
XS GIS Cut Line= 3
      2916424.96      7017325.00      2916125.00      7017325.00
      2915824.99      7017425.00
#Sta/Elev= 30
  4679.9  434.54  4682.4  434.54  4699.9  432.32  4709.9  430.45  4719.9  429.62
  4739.9  427.19  4749.9  426.34  4759.9  425.90  4799.9  425.18  4839.9  425.33
  4919.9  424.37  4949.9  423.52  4964.0  422.69  4969.9  422.18  4977.4  420.61
  4982.5  420.61  4987.4  420.09  4987.9  419.29  4992.9  419.29  4993.4  420.09
  5011.5  421.31  5077.3  422.69  5116.9  424.60  5138.0  425.87  5159.1  427.86
  5180.1  429.03  5201.2  430.83  5232.8  432.78  5264.5  434.37  5296.1  435.26
#Mann=3,-1,0
  4679.9    0.05       0  4987.4    0.03       0  4993.4    0.05       0
Bank Sta=4964,5077.3
Exp/Cntr=0.3,0.1

Type RM Length L Ch R = 1,11910,413,413,413
BEGIN DESCRIPTION:
UNT 008 IN DRY CR WATERSHED 23.0
END DESCRIPTION:
XS GIS Cut Line= 3
      2916275.04      7016924.99      2915975.00      7017025.00
      2915675.01      7016975.00
#Sta/Elev= 30
  4674.1  434.94  4726.8  434.37  4779.6  431.73  4800.6  428.32  4821.7  426.29
  4863.9  423.00  4896.9  421.22  4937.7  420.17  4948.2  419.35  4958.7  419.98
  4969.3  419.59  4979.8  420.12  4987.7  419.22  4992.9  419.22  4997.5  418.06
  4998.0  417.26  5003.0  417.26  5003.5  418.06  5018.2  419.68  5030.9  420.38
  5072.2  421.22  5101.9  421.72  5200.7  426.94  5205.8  426.60  5223.5  427.62
  5243.8  430.30  5261.6  433.55  5266.6  431.91  5284.4  434.81  5294.5  435.73
#Mann=3,-1,0
  4674.1    0.05       0  4997.5    0.03       0  5003.5    0.05       0
Bank Sta=4896.9,5072.2
Exp/Cntr=0.3,0.1

Type RM Length L Ch R = 1,11497,448,448,448
BEGIN DESCRIPTION:
UNT 008 IN DRY CR WATERSHED 22.0
END DESCRIPTION:
XS GIS Cut Line= 3
      2916275.04      7016725.01      2915975.00      7016675.00
      2915674.98      7016675.00
#Sta/Elev= 30
  4706.3  433.31  4746.9  432.13  4807.7  432.84  4828.0  432.45  4855.9  430.07
  4860.9  430.68  4868.6  429.58  4916.7  424.96  4939.5  423.71  4959.8  421.70
  4970.8  419.51  4987.2  415.59  4987.7  414.79  4992.7  414.79  4993.2  415.59
  5000.3  415.69  5007.9  418.02  5013.0  418.02  5020.5  419.11  5030.5  419.18
  5049.0  418.61  5100.5  418.88  5122.4  419.51  5150.5  420.21  5200.5  424.39
  5230.5  426.25  5240.5  427.79  5259.4  429.38  5280.5  430.91  5310.5  432.27
#Mann=5,-1,0
  4706.3    0.05       0  4987.2    0.03       0  4993.2    0.05       0
  5049.0    0.16       0  5259.4    0.05       0
Bank Sta=4970.8,5122.4
Exp/Cntr=0.3,0.1

Type RM Length L Ch R = 1,11049,498,498,498
BEGIN DESCRIPTION:
UNT 008 IN DRY CR WATERSHED 21.0
END DESCRIPTION:
XS GIS Cut Line= 3
      2916174.95      7016474.98      2915875.00      7016375.00
      2915675.02      7016624.97
#Sta/Elev= 30
  4754.6  431.50  4775.6  431.52  4796.7  430.63  4838.9  425.16  4881.0  421.56
  4944.3  418.71  4966.8  418.04  4986.5  417.26  4997.0  415.93  5018.1  417.89
  5028.6  417.97  5049.7  417.35  5060.2  415.16  5065.1  413.63  5065.6  412.83
  5070.6  412.83  5071.1  413.63  5074.0  413.63  5084.4  416.06  5092.4  417.28
  5118.4  418.04  5125.4  418.42  5148.4  420.03  5170.8  420.89  5177.2  420.82
  5234.9  423.19  5274.2  425.68  5319.7  428.56  5326.9  429.30  5390.9  431.51
#Mann=5,-1,0
  4754.6    0.05       0  5065.1    0.03       0  5071.1    0.05       0
  5125.4    0.16       0  5274.2    0.05       0
Bank Sta=4966.8,5118.4
Exp/Cntr=0.3,0.1

Type RM Length L Ch R = 1,10551,319,319,319
BEGIN DESCRIPTION:
UNT 008 IN DRY CR WATERSHED 20.0
END DESCRIPTION:
XS GIS Cut Line= 3
      2915825.00      7015775.00      2915625.00      7016125.00
      2915475.01      7016424.98
#Sta/Elev= 30
  4620.1  430.30  4649.6  428.86  4677.7  426.09  4751.8  420.24  4810.9  417.26
  4828.9  417.07  4854.1  416.82  4862.0  415.97  4875.6  415.72  4891.5  416.52
  4977.9  416.41  4993.7  414.02  5012.3  413.70  5012.8  412.90  5017.8  412.90
  5018.3  413.70  5020.3  414.50  5031.6  414.07  5037.2  415.29  5045.6  414.90
  5054.0  416.18  5075.4  417.07  5188.1  420.92  5232.8  424.02  5238.4  424.91
  5255.2  426.03  5260.8  427.27  5277.6  428.21  5299.9  430.50  5358.6  432.27
#Mann=3,-1,0
  4620.1    0.05       0  5012.3    0.03       0  5018.3    0.05       0
Bank Sta=4828.9,5075.4
Exp/Cntr=0.3,0.1

Type RM Length L Ch R = 1,10232,355,355,355
BEGIN DESCRIPTION:
UNT 008 IN DRY CR WATERSHED 19.0
END DESCRIPTION:
XS GIS Cut Line= 3
      2915825.01      7015725.00      2915525.00      7015825.00
      2915224.97      7015925.01
#Sta/Elev= 30
  4705.0  431.96  4707.7  431.96  4726.1  430.05  4768.3  426.60  4831.5  419.85
  4852.6  418.20  4901.4  416.04  4926.4  415.11  4947.5  414.69  4979.1  415.25
  5000.2  413.68  5007.7  413.49  5008.2  412.69  5013.2  412.69  5013.7  413.49
  5018.6  414.87  5052.9  415.13  5063.4  415.40  5072.2  416.04  5095.0  416.89
  5126.7  418.72  5168.8  421.55  5189.9  423.44  5200.4  423.81  5242.6  426.96
  5263.7  427.57  5284.8  427.78  5295.3  428.56  5326.9  429.91  5337.5  430.07
#Mann=3,-1,0
  4705.0    0.05       0  5007.7    0.03       0  5013.7    0.05       0
Bank Sta=4901.4,5072.2
Exp/Cntr=0.3,0.1

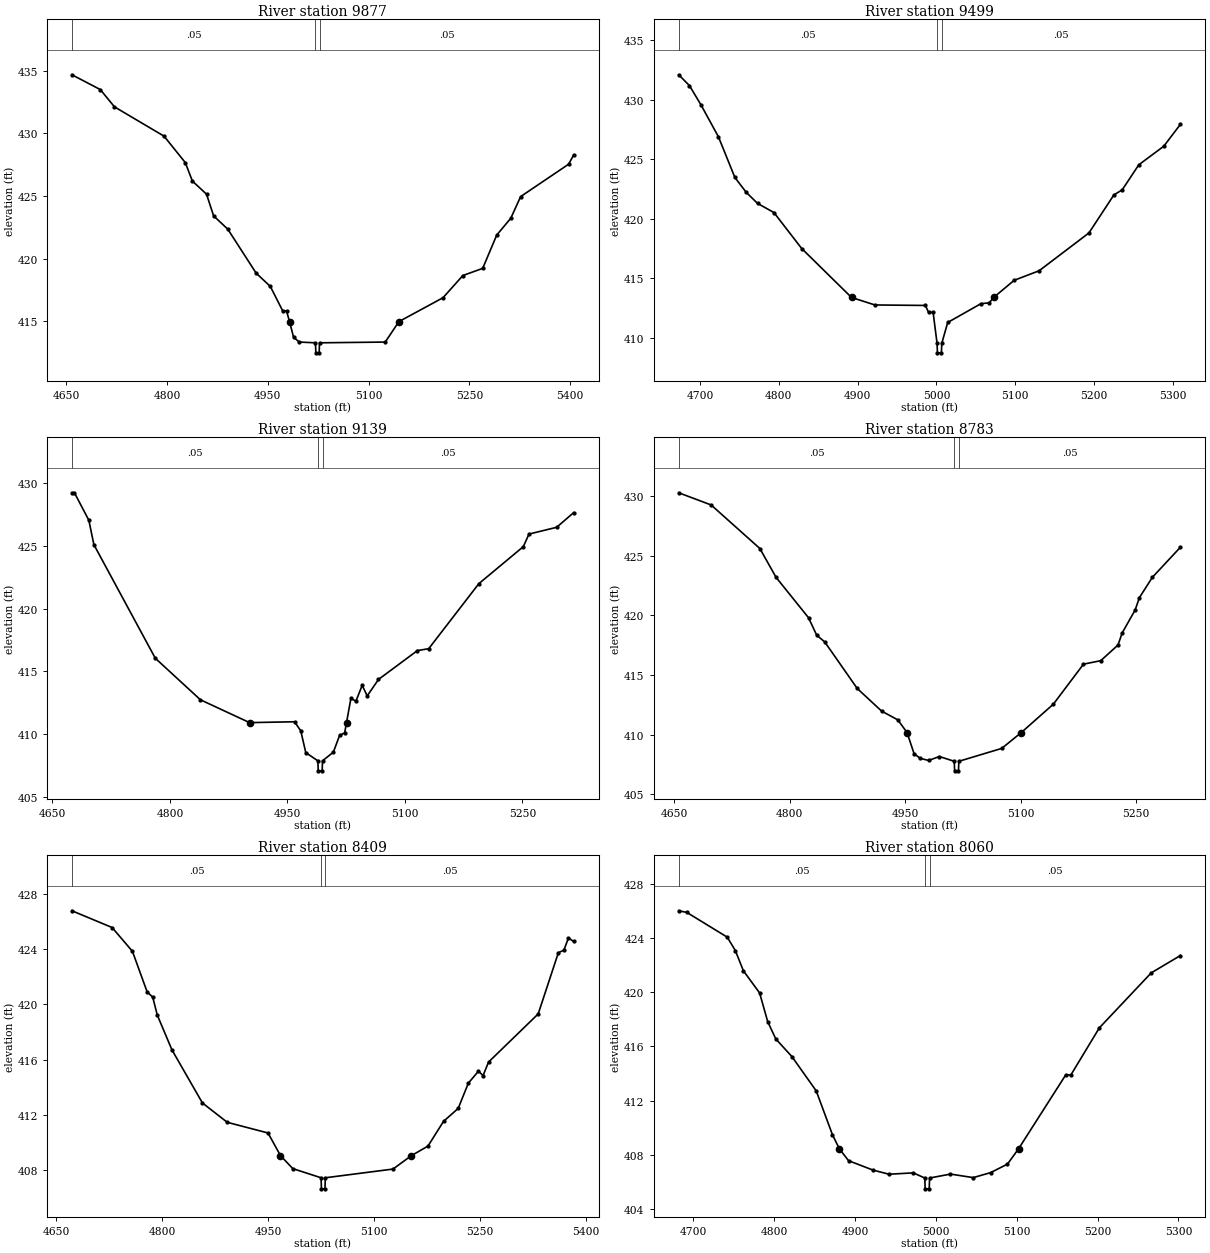
Type RM Length L Ch R = 1,9877,378,378,378
BEGIN DESCRIPTION:
UNT 008 IN DRY CR WATERSHED 18.0
END DESCRIPTION:
XS GIS Cut Line= 3
      2915575.01      7015174.97      2915475.00      7015475.00
      2915124.98      7015725.02
#Sta/Elev= 30
  4658.7  434.67  4700.9  433.49  4722.0  432.11  4795.8  429.77  4827.4  427.66
  4837.9  426.19  4859.0  425.14  4869.5  423.41  4890.6  422.35  4932.8  418.84
  4953.9  417.78  4972.3  415.83  4978.0  415.83  4982.5  414.97  4988.5  413.72
  4997.1  413.34  5021.1  413.28  5021.6  412.48  5026.6  412.48  5027.1  413.28
  5124.9  413.34  5145.2  414.97  5210.9  416.88  5240.4  418.65  5269.9  419.22
  5290.8  421.88  5311.7  423.22  5326.4  424.95  5397.7  427.53  5405.1  428.25
#Mann=3,-1,0
  4658.7    0.05       0  5021.1    0.03       0  5027.1    0.05       0
Bank Sta=4982.5,5145.2
Exp/Cntr=0.3,0.1

Type RM Length L Ch R = 1,9499,360,360,360
BEGIN DESCRIPTION:
UNT 008 IN DRY CR WATERSHED 17.0
END DESCRIPTION:
XS GIS Cut Line= 3
      2915374.97      7015125.04      2915175.00      7015375.00
      2915075.01      7015674.96
#Sta/Elev= 30
  4673.1  432.10  4686.7  431.19  4701.1  429.60  4723.5  426.89  4744.3  423.48
  4758.7  422.23  4773.1  421.30  4793.9  420.53  4829.1  417.51  4892.3  413.40
  4922.0  412.77  4986.0  412.73  4990.0  412.15  4995.8  412.15  5000.8  409.55
  5001.3  408.75  5006.3  408.75  5006.8  409.55  5014.3  411.30  5056.5  412.88
  5067.0  412.95  5072.6  413.40  5098.6  414.84  5130.2  415.64  5193.5  418.82
  5225.1  422.01  5235.7  422.44  5256.7  424.54  5288.4  426.10  5309.4  427.93
#Mann=3,-1,0
  4673.1    0.05       0  5000.8    0.03       0  5006.8    0.05       0
Bank Sta=4892.3,5072.6
Exp/Cntr=0.3,0.1

Type RM Length L Ch R = 1,9139,356,356,356
BEGIN DESCRIPTION:
UNT 008 IN DRY CR WATERSHED 16.0
END DESCRIPTION:
XS GIS Cut Line= 3
      2915124.96      7015025.03      2914875.00      7015225.00
      2914674.98      7015475.03
#Sta/Elev= 30
  4674.9  429.23  4678.1  429.23  4696.5  427.04  4702.9  425.10  4781.3  416.05
  4838.9  412.74  4901.7  410.92  4959.0  410.99  4967.0  410.27  4973.4  408.53
  4988.8  407.88  4989.3  407.08  4994.3  407.08  4994.8  407.88  5008.6  408.57
  5016.6  409.91  5023.0  410.10  5025.4  410.92  5031.0  412.85  5037.4  412.63
  5045.4  413.89  5051.8  413.05  5066.2  414.36  5115.9  416.66  5130.3  416.81
  5194.3  421.99  5251.1  424.94  5258.3  425.94  5293.6  426.48  5315.2  427.64
#Mann=3,-1,0
  4674.9    0.05       0  4988.8    0.03       0  4994.8    0.05       0
Bank Sta=4901.7,5025.4
Exp/Cntr=0.3,0.1

Type RM Length L Ch R = 1,8783,374,374,374
BEGIN DESCRIPTION:
UNT 008 IN DRY CR WATERSHED 15.0
END DESCRIPTION:
XS GIS Cut Line= 3
      2915024.98      7014825.01      2914725.00      7014925.00
      2914425.01      7015074.99
#Sta/Elev= 30
  4655.7  430.28  4697.8  429.26  4761.1  425.61  4782.2  423.19  4824.3  419.81
  4834.9  418.35  4845.4  417.78  4887.6  413.88  4919.2  411.99  4940.3  411.25
  4952.3  410.19  4961.4  408.42  4969.3  408.03  4980.3  407.85  4994.3  408.18
  5013.6  407.78  5014.1  406.98  5019.1  406.98  5019.6  407.78  5075.3  408.86
  5100.7  410.19  5142.4  412.57  5181.5  415.92  5203.9  416.21  5226.3  417.52
  5231.8  418.54  5248.6  420.46  5254.2  421.50  5271.0  423.20  5307.3  425.71
#Mann=3,-1,0
  4655.7    0.05       0  5013.6    0.03       0  5019.6    0.05       0
Bank Sta=4952.3,5100.7
Exp/Cntr=0.3,0.1

Type RM Length L Ch R = 1,8409,349,349,349
BEGIN DESCRIPTION:
UNT 008 IN DRY CR WATERSHED 14.0
END DESCRIPTION:
XS GIS Cut Line= 3
      2914825.02      7014324.98      2914625.00      7014575.00
      2914325.00      7014825.00
#Sta/Elev= 30
  4672.3  426.77  4729.2  425.56  4758.0  423.84  4778.8  420.91  4786.8  420.52
  4793.2  419.23  4814.0  416.71  4857.2  412.87  4892.4  411.47  4950.1  410.70
  4967.8  409.06  4985.3  408.12  5025.3  407.46  5025.8  406.66  5030.8  406.66
  5031.3  407.46  5127.2  408.09  5153.2  409.06  5176.7  409.75  5198.8  411.54
  5219.6  412.48  5233.9  414.30  5248.3  415.17  5254.8  414.85  5262.6  415.83
  5332.9  419.31  5361.5  423.74  5369.3  423.92  5375.8  424.81  5383.0  424.55
#Mann=3,-1,0
  4672.3    0.05       0  5025.3    0.03       0  5031.3    0.05       0
Bank Sta=4967.8,5153.2
Exp/Cntr=0.3,0.1

Type RM Length L Ch R = 1,8060,581,581,581
BEGIN DESCRIPTION:
UNT 008 IN DRY CR WATERSHED 13.0
END DESCRIPTION:
XS GIS Cut Line= 3
      2914775.03      7014275.00      2914475.00      7014275.00
      2914224.99      7014475.01
#Sta/Elev= 30
  4682.2  426.03  4692.2  425.91  4742.2  424.08  4752.2  423.09  4762.2  421.59
  4782.2  419.96  4792.2  417.84  4802.2  416.56  4822.2  415.25  4852.2  412.72
  4872.2  409.49  4880.8  408.44  4892.2  407.56  4922.2  406.87  4942.2  406.56
  4972.2  406.66  4986.4  406.28  4986.9  405.48  4991.9  405.48  4992.4  406.28
  5018.2  406.57  5046.3  406.31  5067.9  406.68  5088.7  407.31  5102.4  408.44
  5160.7  413.90  5167.1  413.90  5202.3  417.38  5266.4  421.44  5302.4  422.72
#Mann=3,-1,0
  4682.2    0.05       0  4986.4    0.03       0  4992.4    0.05       0
Bank Sta=4880.8,5102.4
Exp/Cntr=0.3,0.1

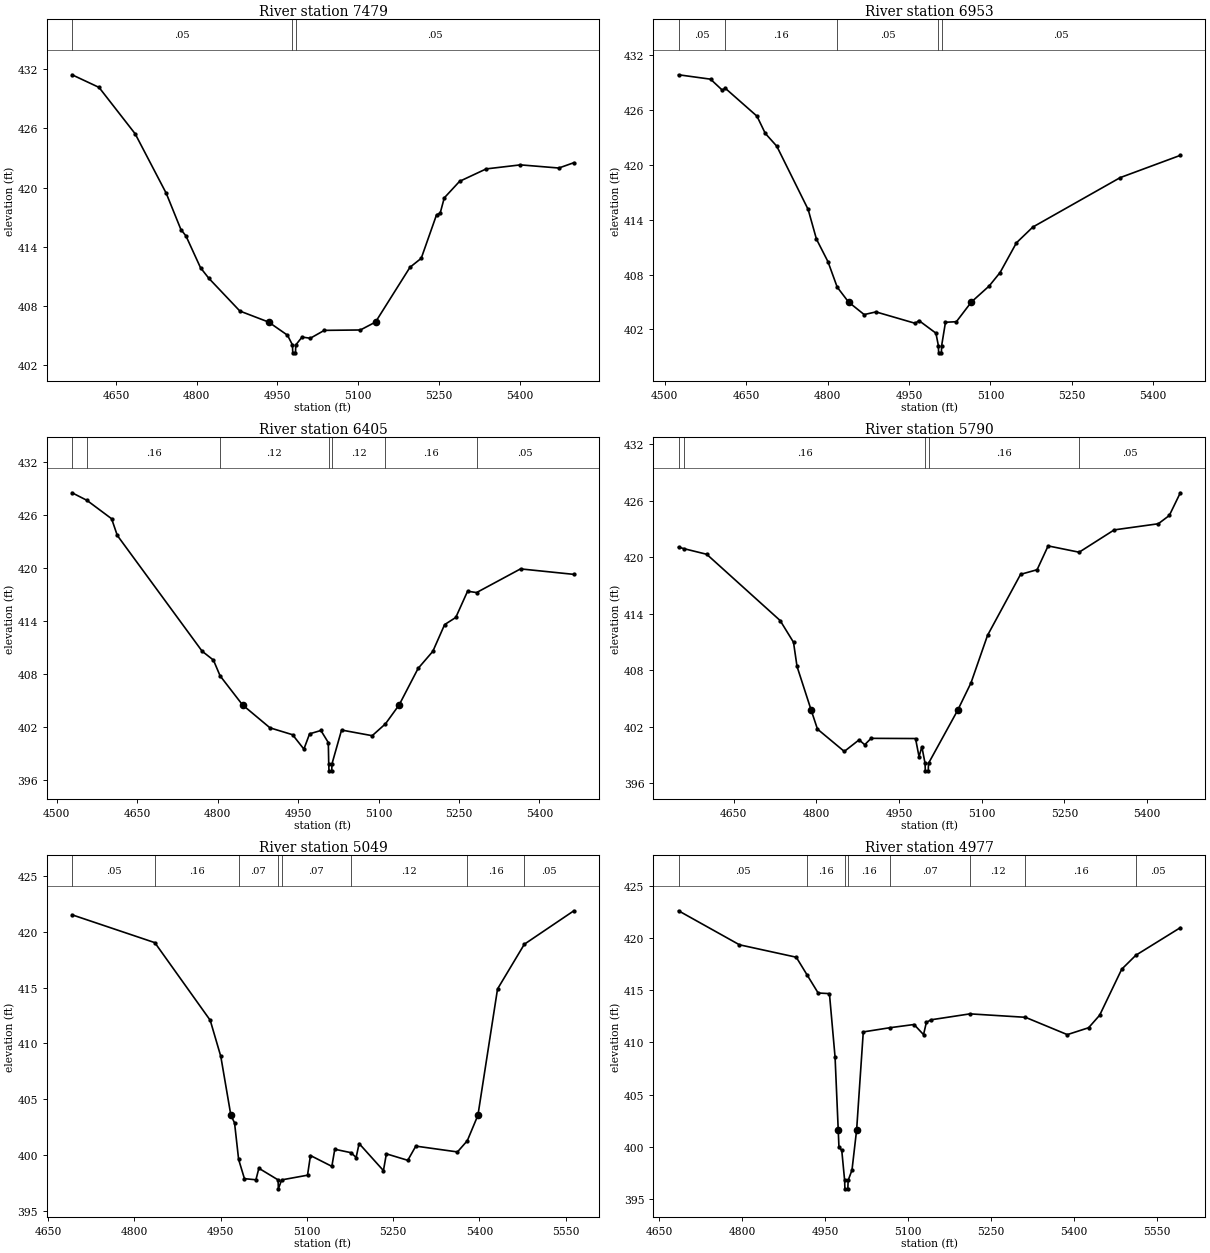
Type RM Length L Ch R = 1,7479,526,526,526
BEGIN DESCRIPTION:
UNT 008 IN DRY CR WATERSHED 12.0
END DESCRIPTION:
XS GIS Cut Line= 3
      2914575.01      7013374.99      2914325.00      7013775.00
      2913974.99      7014075.01
#Sta/Elev= 30
  4568.2  431.45  4618.3  430.17  4685.5  425.46  4743.3  419.42  4770.5  415.75
  4779.9  415.10  4807.0  411.87  4822.3  410.81  4880.1  407.48  4933.6  406.36
  4968.6  405.03  4977.9  404.04  4978.4  403.24  4983.5  403.24  4984.0  404.04
  4995.7  404.84  5011.0  404.72  5037.0  405.52  5104.1  405.56  5132.2  406.36
  5196.3  411.92  5217.2  412.83  5245.7  417.25  5252.3  417.39  5260.0  418.96
  5288.5  420.64  5337.9  421.90  5401.6  422.31  5472.9  421.99  5500.9  422.53
#Mann=3,-1,0
  4568.2    0.05       0  4977.9    0.03       0  4984.0    0.05       0
Bank Sta=4933.6,5132.2
Exp/Cntr=0.3,0.1

Type RM Length L Ch R = 1,6953,548,548,548
BEGIN DESCRIPTION:
UNT 008 IN DRY CR WATERSHED 11.0
END DESCRIPTION:
XS GIS Cut Line= 3
      2914225.00      7013025.00      2913975.00      7013425.00
      2913925.00      7013875.04
#Sta/Elev= 30
  4525.4  429.82  4584.4  429.34  4606.2  428.13  4611.3  428.36  4669.9  425.30
  4685.2  423.42  4706.4  422.02  4764.2  415.11  4779.5  411.87  4800.7  409.41
  4817.7  406.63  4838.6  405.00  4867.4  403.63  4889.2  403.92  4961.7  402.67
  4968.2  402.98  4999.6  401.60  5004.1  400.25  5004.6  399.45  5009.7  399.45
  5010.2  400.25  5017.2  402.79  5037.3  402.85  5064.9  405.00  5097.7  406.75
  5117.8  408.22  5148.0  411.47  5178.2  413.19  5339.2  418.59  5449.9  421.02
#Mann=5,-1,0
  4525.4    0.05       0  4611.3    0.16       0  4817.7    0.05       0
  5004.1    0.03       0  5010.2    0.05       0
Bank Sta=4838.6,5064.9
Exp/Cntr=0.3,0.1

Type RM Length L Ch R = 1,6405,615,615,615
BEGIN DESCRIPTION:
UNT 008 IN DRY CR WATERSHED 10.0
END DESCRIPTION:
XS GIS Cut Line= 3
      2914024.95      7012975.02      2913575.00      7013125.00
      2913224.98      7013425.02
#Sta/Elev= 30
  4528.8  428.49  4556.3  427.64  4602.5  425.55  4613.1  423.66  4771.2  410.55
  4792.3  409.54  4804.7  407.76  4846.5  404.47  4897.7  401.87  4939.8  401.09
  4960.9  399.46  4971.5  401.19  4992.6  401.57  5006.4  400.20  5007.2  397.80
  5007.7  397.00  5012.8  397.00  5013.3  397.80  5031.1  401.62  5088.2  400.98
  5112.9  402.32  5138.5  404.47  5173.8  408.60  5201.2  410.53  5223.2  413.56
  5244.0  414.37  5266.0  417.34  5282.8  417.19  5364.7  419.87  5464.1  419.25
#Mann=7,-1,0
  4528.8    0.05       0  4556.3    0.16       0  4804.7    0.12       0
  5007.2    0.07       0  5013.3    0.12       0  5112.9    0.16       0
  5282.8    0.05       0
Bank Sta=4846.5,5138.5
Exp/Cntr=0.3,0.1

Type RM Length L Ch R = 1,5790,741,741,741
BEGIN DESCRIPTION:
UNT 008 IN DRY CR WATERSHED 9.0
END DESCRIPTION:
XS GIS Cut Line= 3
      2913824.96      7012724.99      2913375.00      7012625.00
      2912925.04      7012625.00
#Sta/Elev= 30
  4549.6  421.05  4559.2  420.89  4600.8  420.29  4734.0  413.26  4758.3  410.95
  4764.7  408.38  4790.4  403.74  4801.8  401.73  4850.5  399.36  4877.4  400.59
  4887.6  400.07  4899.1  400.75  4979.8  400.73  4986.2  398.80  4991.3  399.86
  4997.1  398.10  4997.6  397.30  5002.9  397.30  5003.4  398.10  5056.4  403.74
  5080.5  406.64  5110.5  411.68  5170.5  418.16  5200.5  418.65  5220.5  421.18
  5276.8  420.51  5340.5  422.88  5420.5  423.53  5440.5  424.41  5460.5  426.82
#Mann=5,-1,0
  4549.6    0.05       0  4559.2    0.16       0  4997.1    0.07       0
  5003.4    0.16       0  5276.8    0.05       0
Bank Sta=4790.4,5056.4
Exp/Cntr=0.3,0.1

Type RM Length L Ch R = 1,5049,72,72,72
BEGIN DESCRIPTION:
Mapping XS 06d1f734
END DESCRIPTION:
XS GIS Cut Line= 4
      2913968.29      7012371.14      2913816.36      7012284.32
      2913338.93      7012171.47      2913132.73      7012154.11
#Sta/Elev= 30
  4691.7  421.50  4835.6  419.01  4931.9  412.07  4950.3  408.84  4967.8  403.58
  4974.2  402.90  4981.3  399.63  4991.4  397.91  5011.4  397.81  5016.5  398.84
  5049.9  397.80  5050.4  397.00  5056.2  397.80  5101.1  398.22  5106.2  399.98
  5143.4  399.01  5148.5  400.54  5176.9  400.23  5185.6  399.80  5190.8  401.05
  5233.1  398.63  5238.2  400.13  5275.4  399.55  5289.4  400.82  5361.8  400.30
  5378.9  401.30  5397.4  403.58  5431.5  414.87  5478.1  418.87  5564.2  421.86
#Mann=8,-1,0
  4691.7    0.05       0  4835.6    0.16       0  4981.3    0.07       0
  5049.9    0.07       0  5056.2    0.07       0  5176.9    0.12       0
  5378.9    0.16       0  5478.1    0.05       0
Bank Sta=4967.8,5397.4
Exp/Cntr=0.3,0.1

Type RM Length L Ch R = 1,4977,37,37,37
BEGIN DESCRIPTION:
Mapping XS 1ab5a8fa
END DESCRIPTION:
XS GIS Cut Line= 4
      2914016.01      7012308.19      2913809.85      7012212.71
      2913332.42      7012117.22      2913139.60      7012102.06
#Sta/Elev= 30
  4684.8  422.62  4795.0  419.36  4897.7  418.17  4917.9  416.42  4937.3  414.74
  4957.7  414.68  4967.9  408.59  4973.6  401.63  4974.9  399.99  4980.0  399.66
  4985.2  396.77  4985.7  395.97  4991.0  395.97  4991.5  396.77  4998.5  397.77
  5006.9  401.63  5018.9  411.01  5066.8  411.41  5110.7  411.72  5127.9  410.75
  5133.0  411.92  5141.3  412.17  5211.9  412.74  5312.2  412.41  5387.9  410.75
  5426.4  411.41  5446.4  412.61  5486.3  417.02  5511.9  418.36  5592.3  421.00
#Mann=8,-1,0
  4684.8    0.05       0  4917.9    0.16       0  4985.2    0.07       0
  4991.5    0.16       0  5066.8    0.07       0  5211.9    0.12       0
  5312.2    0.16       0  5511.9    0.05       0
Bank Sta=4973.6,5006.9
Exp/Cntr=0.3,0.1