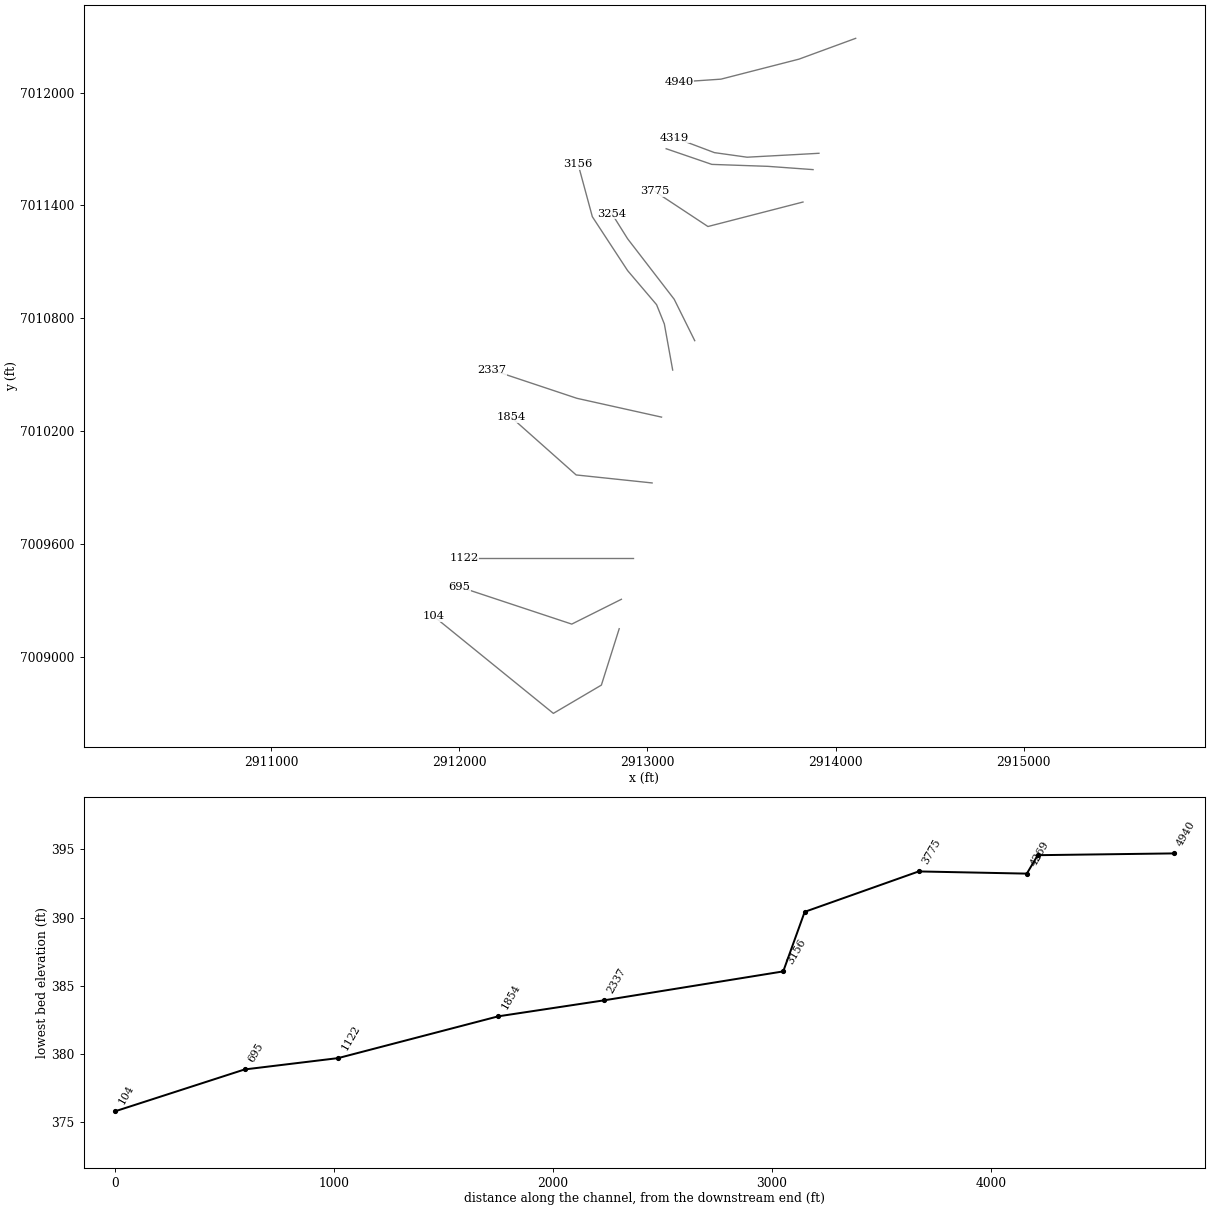
HEC-RAS study UNT 008 IN DRY CR WATERSHED.prj: UNT 008 IN DRY CR WATERSHED Base Level Engineering

--- UNT 008 IN DRY CR WATERSHED.g01 (geometry) --- (continued)

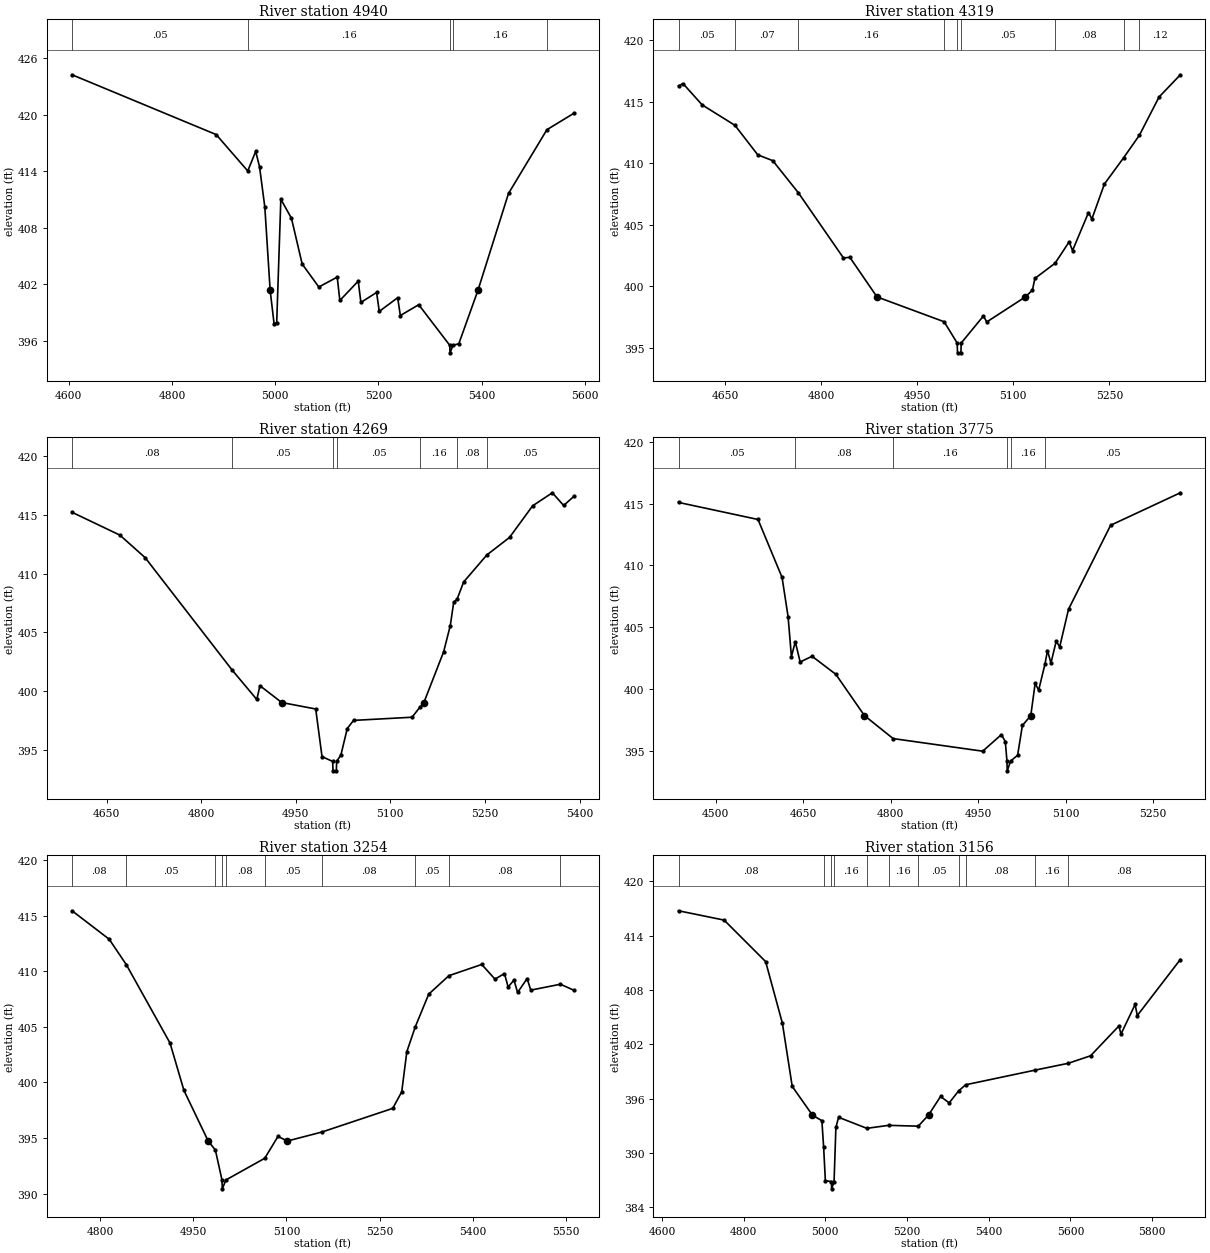
Type RM Length L Ch R = 1,4940,621,621,621
BEGIN DESCRIPTION:
Mapping XS c22e88d9
END DESCRIPTION:
XS GIS Cut Line= 4
      2914107.11      7012288.65      2913805.51      7012177.98
      2913391.01      7012071.65      2913168.71      7012056.54
#Sta/Elev= 30
  4606.5  424.22  4885.7  417.87  4946.8  414.01  4962.2  416.08  4969.6  414.47
  4979.9  410.16  4990.2  401.33  4997.8  397.79  5002.9  397.91  5010.9  411.01
  5031.5  408.98  5052.2  404.13  5084.5  401.69  5120.1  402.74  5125.2  400.26
  5160.8  402.31  5166.0  400.05  5196.4  401.11  5201.6  399.10  5237.2  400.55
  5242.4  398.66  5278.0  399.81  5338.1  395.50  5338.6  394.70  5344.4  395.50
  5355.7  395.67  5392.8  401.35  5451.9  411.62  5526.3  418.39  5578.5  420.13
#Mann=5,-1,0
  4606.5    0.05       0  4946.8    0.16       0  5338.1    0.07       0
  5344.4    0.16       0  5526.3    0.05       0
Bank Sta=4990.2,5392.8
Exp/Cntr=0.3,0.1

Type RM Length L Ch R = 1,4319,50,50,50
BEGIN DESCRIPTION:
Mapping XS 2123e310
END DESCRIPTION:
XS GIS Cut Line= 5
      2913911.87      7011677.55      2913786.84      7011670.61
      2913529.90      7011656.72      2913356.29      7011681.02
      2913145.61      7011760.46
#Sta/Elev= 30
  4577.6  416.27  4584.5  416.48  4614.5  414.74  4665.6  413.08  4701.2  410.68
  4724.7  410.20  4764.6  407.59  4834.9  402.29  4844.9  402.34  4887.3  399.12
  4992.0  397.10  5012.4  395.37  5012.9  394.57  5018.2  394.57  5018.7  395.37
  5053.4  397.57  5058.5  397.08  5118.8  399.12  5129.9  399.68  5133.6  400.62
  5165.2  401.86  5187.1  403.60  5192.4  402.89  5217.3  405.98  5222.6  405.46
  5242.1  408.30  5272.0  410.43  5296.7  412.27  5327.4  415.38  5360.6  417.19
#Mann=9,-1,0
  4577.6    0.05       0  4665.6    0.07       0  4764.6    0.16       0
  4992.0    0.05       0  5012.4    0.04       0  5018.7    0.05       0
  5165.2    0.08       0  5272.0    0.05       0  5296.7    0.12       0
Bank Sta=4887.3,5118.8
Exp/Cntr=0.3,0.1

Type RM Length L Ch R = 1,4269,494,494,494
BEGIN DESCRIPTION:
Mapping XS 6eb1c3d0
END DESCRIPTION:
XS GIS Cut Line= 4
      2913880.59      7011590.75      2913641.01      7011608.11
      2913342.40      7011618.52      2913099.67      7011701.75
#Sta/Elev= 30
  4595.4  415.21  4671.2  413.27  4711.3  411.35  4849.2  401.79  4888.3  399.29
  4893.3  400.46  4927.9  399.03  4981.7  398.48  4991.7  394.43  5008.6  394.02
  5009.1  393.22  5014.4  393.22  5014.9  394.02  5021.7  394.58  5031.7  396.82
  5041.7  397.51  5134.4  397.78  5147.5  398.67  5153.2  399.03  5184.5  403.34
  5195.1  405.58  5200.5  407.56  5205.8  407.81  5216.2  409.28  5253.0  411.58
  5289.0  413.07  5325.6  415.76  5356.9  416.87  5374.8  415.79  5391.0  416.56
#Mann=7,-1,0
  4595.4    0.08       0  4849.2    0.05       0  5008.6    0.04       0
  5014.9    0.05       0  5147.5    0.16       0  5205.8    0.08       0
  5253.0    0.05       0
Bank Sta=4927.9,5153.2
Exp/Cntr=0.3,0.1

Type RM Length L Ch R = 1,3775,521,521,521
BEGIN DESCRIPTION:
Mapping XS 3abf016e
END DESCRIPTION:
XS GIS Cut Line= 3
      2913827.00      7011418.44      2913321.78      7011288.23
      2913038.95      7011475.05
#Sta/Elev= 30
  4436.1  415.10  4572.4  413.72  4613.7  409.03  4624.0  405.86  4629.7  402.63
  4636.4  403.82  4644.7  402.19  4665.2  402.65  4705.9  401.19  4755.0  397.85
  4804.2  395.99  4957.8  394.97  4989.9  396.31  4996.6  395.75  4999.4  394.18
  4999.9  393.38  5005.8  394.18  5017.7  394.64  5025.9  397.05  5040.3  397.85
  5047.8  400.46  5053.8  399.91  5064.8  402.05  5068.9  403.11  5074.9  402.11
  5083.9  403.87  5089.9  403.41  5105.0  406.45  5177.2  413.25  5296.8  415.88
#Mann=6,-1,0
  4436.1    0.05       0  4636.4    0.08       0  4804.2    0.16       0
  4999.4    0.07       0  5005.8    0.16       0  5064.8    0.05       0
Bank Sta=4755,5040.3
Exp/Cntr=0.3,0.1

Type RM Length L Ch R = 1,3254,98,98,98
BEGIN DESCRIPTION:
UNT 008 IN DRY CR WATERSHED 7.0
END DESCRIPTION:
XS GIS Cut Line= 4
      2913251.48      7010681.44      2913142.50      7010901.31
      2912894.70      7011223.12      2912811.34      7011355.98
#Sta/Elev= 30
  4754.6  415.44  4814.4  412.88  4841.9  410.60  4912.4  403.54  4934.8  399.28
  4973.9  394.72  4985.5  393.91  4996.1  391.22  4996.6  390.42  5002.5  391.22
  5065.0  393.17  5086.4  395.14  5101.2  394.72  5157.0  395.53  5271.2  397.66
  5285.7  399.15  5293.9  402.76  5307.6  405.01  5329.2  407.94  5361.7  409.60
  5414.6  410.61  5435.9  409.29  5451.2  409.79  5457.1  408.58  5466.5  409.20
  5472.4  408.09  5487.7  409.34  5493.6  408.30  5541.3  408.83  5563.0  408.29
#Mann=10,-1,0
  4754.6    0.08       0  4841.9    0.05       0  4985.5    0.08       0
  4996.1    0.07       0  5002.5    0.08       0  5065.0    0.05       0
  5157.0    0.08       0  5307.6    0.05       0  5361.7    0.08       0
  5541.3    0.05       0
Bank Sta=4973.9,5101.2
Exp/Cntr=0.3,0.1

Type RM Length L Ch R = 1,3156,819,819,819
BEGIN DESCRIPTION:
UNT 008 IN DRY CR WATERSHED 6.0
END DESCRIPTION:
XS GIS Cut Line= 6
      2913134.28      7010525.22      2913090.01      7010770.00
      2913048.75      7010872.67      2912894.70      7011053.85
      2912707.20      7011340.31      2912631.67      7011618.97
#Sta/Elev= 30
  4640.6  416.76  4752.2  415.73  4853.8  411.15  4894.8  404.35  4918.9  397.37
  4968.2  394.21  4991.5  393.58  4995.8  390.65  5000.0  386.96  5014.9  386.86
  5015.4  386.06  5021.3  386.86  5025.8  392.84  5032.4  393.96  5101.5  392.74
  5154.8  393.07  5227.4  392.98  5252.6  394.21  5282.0  396.26  5303.1  395.55
  5326.3  396.88  5343.5  397.55  5513.8  399.17  5594.5  399.92  5649.2  400.75
  5718.5  404.04  5723.7  403.15  5758.3  406.42  5763.5  405.19  5868.9  411.38
#Mann=11,-1,0
  4640.6    0.08       0  4995.8    0.16       0  5014.9    0.07       0
  5021.3    0.16       0  5101.5    0.08       0  5154.8    0.16       0
  5227.4    0.05       0  5326.3    0.16       0  5343.5    0.08       0
  5513.8    0.16       0  5594.5    0.08       0
Bank Sta=4968.2,5252.6
Exp/Cntr=0.3,0.1

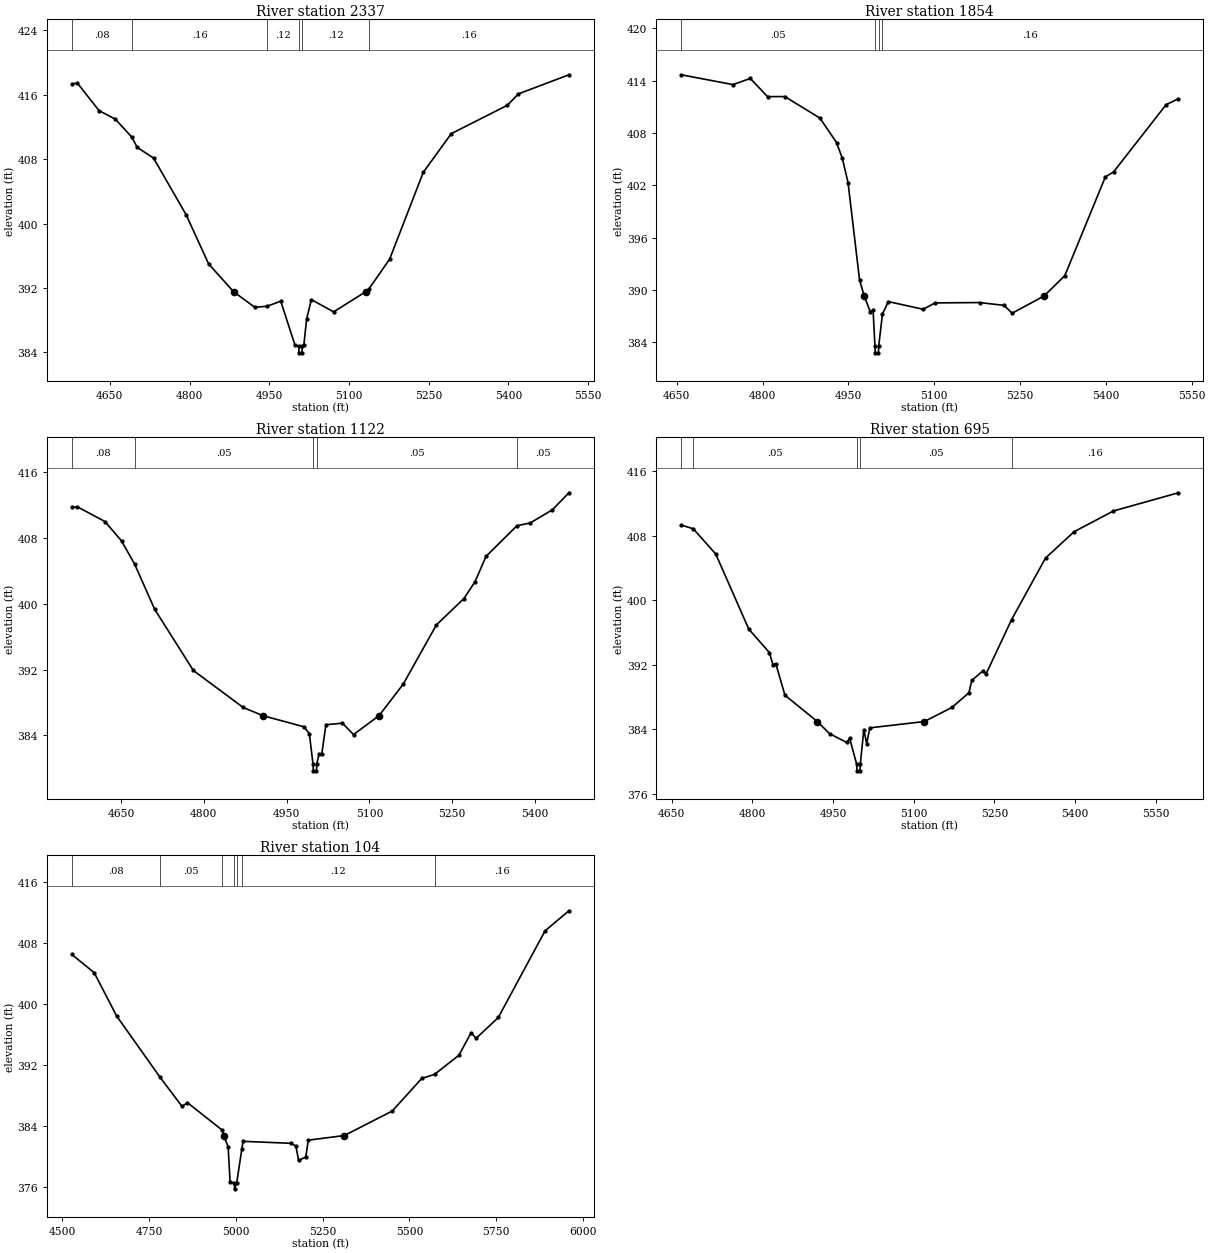
Type RM Length L Ch R = 1,2337,483,483,483
BEGIN DESCRIPTION:
UNT 008 IN DRY CR WATERSHED 4.0
END DESCRIPTION:
XS GIS Cut Line= 3
      2913075.00      7010275.00      2912625.00      7010375.00
      2912175.02      7010524.99
#Sta/Elev= 30
  4578.5  417.29  4588.7  417.46  4629.7  414.02  4660.4  412.96  4691.7  410.70
  4701.4  409.46  4732.2  408.13  4793.6  401.08  4835.9  394.98  4882.9  391.53
  4922.9  389.59  4945.9  389.73  4971.6  390.35  4998.5  384.87  5005.4  384.74
  5005.9  383.94  5011.5  383.94  5012.0  384.74  5015.1  384.94  5020.3  388.14
  5029.2  390.55  5071.1  389.03  5131.5  391.53  5137.3  391.86  5176.5  395.58
  5239.8  406.36  5292.5  411.16  5397.9  414.68  5418.9  416.10  5513.8  418.47
#Mann=6,-1,0
  4578.5    0.08       0  4691.7    0.16       0  4945.9    0.12       0
  5005.4    0.07       0  5012.0    0.12       0  5137.3    0.16       0
Bank Sta=4882.9,5131.5
Exp/Cntr=0.3,0.1

Type RM Length L Ch R = 1,1854,732,732,732
BEGIN DESCRIPTION:
UNT 008 IN DRY CR WATERSHED 3.0
END DESCRIPTION:
XS GIS Cut Line= 3
      2913024.99      7009925.00      2912621.05      7009967.57
      2912274.97      7010275.02
#Sta/Elev= 30
  4657.7  414.68  4748.2  413.55  4778.4  414.26  4808.5  412.17  4838.7  412.18
  4900.1  409.71  4929.2  406.90  4939.2  405.11  4949.3  402.30  4969.4  391.13
  4977.6  389.29  4988.1  387.49  4993.1  387.64  4996.3  383.57  4996.8  382.77
  5002.4  382.77  5002.9  383.57  5009.5  387.24  5019.7  388.65  5080.6  387.77
  5101.5  388.50  5179.3  388.54  5221.9  388.22  5236.2  387.32  5291.9  389.29
  5328.2  391.62  5399.2  402.96  5413.5  403.53  5505.4  411.25  5526.8  411.92
#Mann=4,-1,0
  4657.7    0.05       0  4996.3    0.03       0  5002.9    0.05       0
  5009.5    0.16       0
Bank Sta=4977.6,5291.9
Exp/Cntr=0.3,0.1

Type RM Length L Ch R = 1,1122,427,427,427
BEGIN DESCRIPTION:
UNT 008 IN DRY CR WATERSHED 2.0
END DESCRIPTION:
XS GIS Cut Line= 3
      2912925.00      7009525.00      2912475.00      7009525.00
      2912025.00      7009525.00
#Sta/Elev= 30
  4561.2  411.67  4571.2  411.75  4621.2  409.96  4651.2  407.61  4675.1  404.76
  4711.2  399.31  4781.2  391.89  4871.2  387.41  4906.8  386.41  4981.2  385.06
  4991.2  384.24  4997.9  380.51  4998.4  379.71  5004.0  379.71  5004.5  380.51
  5008.7  381.72  5013.7  381.72  5021.2  385.31  5051.2  385.49  5071.2  384.11
  5117.5  386.41  5161.2  390.23  5221.2  397.41  5271.2  400.62  5291.2  402.66
  5311.2  405.74  5367.1  409.45  5391.2  409.79  5431.2  411.38  5461.2  413.45
#Mann=5,-1,0
  4561.2    0.08       0  4675.1    0.05       0  4997.9    0.07       0
  5004.5    0.05       0  5367.1    0.05       0
Bank Sta=4906.8,5117.5
Exp/Cntr=0.3,0.1

Type RM Length L Ch R = 1,695,591,591,591
BEGIN DESCRIPTION:
Mapping XS e5a6d252
END DESCRIPTION:
XS GIS Cut Line= 3
      2912861.62      7009306.54      2912597.74      7009174.60
      2912000.51      7009372.52
#Sta/Elev= 30
  4667.9  409.29  4690.1  408.84  4732.0  405.71  4793.5  396.41  4831.8  393.51
  4838.2  392.03  4843.8  392.11  4860.6  388.24  4920.9  384.98  4943.6  383.48
  4975.6  382.39  4980.9  382.91  4994.1  379.68  4994.6  378.88  5000.2  378.88
  5000.7  379.68  5007.3  383.97  5012.6  382.25  5018.5  384.20  5119.7  384.98
  5171.0  386.72  5202.7  388.54  5208.1  390.07  5229.2  391.28  5234.4  390.84
  5282.0  397.59  5345.1  405.21  5398.2  408.47  5471.5  411.04  5592.1  413.29
#Mann=5,-1,0
  4667.9    0.08       0  4690.1    0.05       0  4994.1    0.04       0
  5000.7    0.05       0  5282.0    0.16       0
Bank Sta=4920.9,5119.7
Exp/Cntr=0.3,0.1

Type RM Length L Ch R = 1,104,0,0,0
BEGIN DESCRIPTION:
UNT 008 IN DRY CR WATERSHED 1.0
END DESCRIPTION:
XS GIS Cut Line= 4
      2912849.99      7009149.98      2912755.22      7008850.29
      2912500.00      7008700.00      2911861.63      7009218.00
#Sta/Elev= 30
  4527.2  406.55  4591.8  404.15  4656.4  398.48  4781.8  390.43  4844.8  386.63
  4860.5  387.12  4960.8  383.51  4964.7  382.81  4977.6  381.35  4983.4  376.66
  4995.7  376.62  4996.2  375.82  5002.4  376.62  5017.1  381.01  5020.6  382.05
  5158.5  381.79  5172.9  381.43  5180.8  379.55  5201.6  380.00  5208.5  382.20
  5312.5  382.81  5450.9  386.03  5535.7  390.30  5572.6  390.83  5642.8  393.34
  5677.9  396.29  5692.3  395.55  5756.3  398.29  5891.1  409.65  5959.8  412.28
#Mann=7,-1,0
  4527.2    0.08       0  4781.8    0.05       0  4960.8    0.16       0
  4995.7    0.07       0  5002.4    0.16       0  5017.1    0.12       0
  5572.6    0.16       0
Bank Sta=4964.7,5312.5
Exp/Cntr=0.3,0.1

Chan Stop Cuts=-1