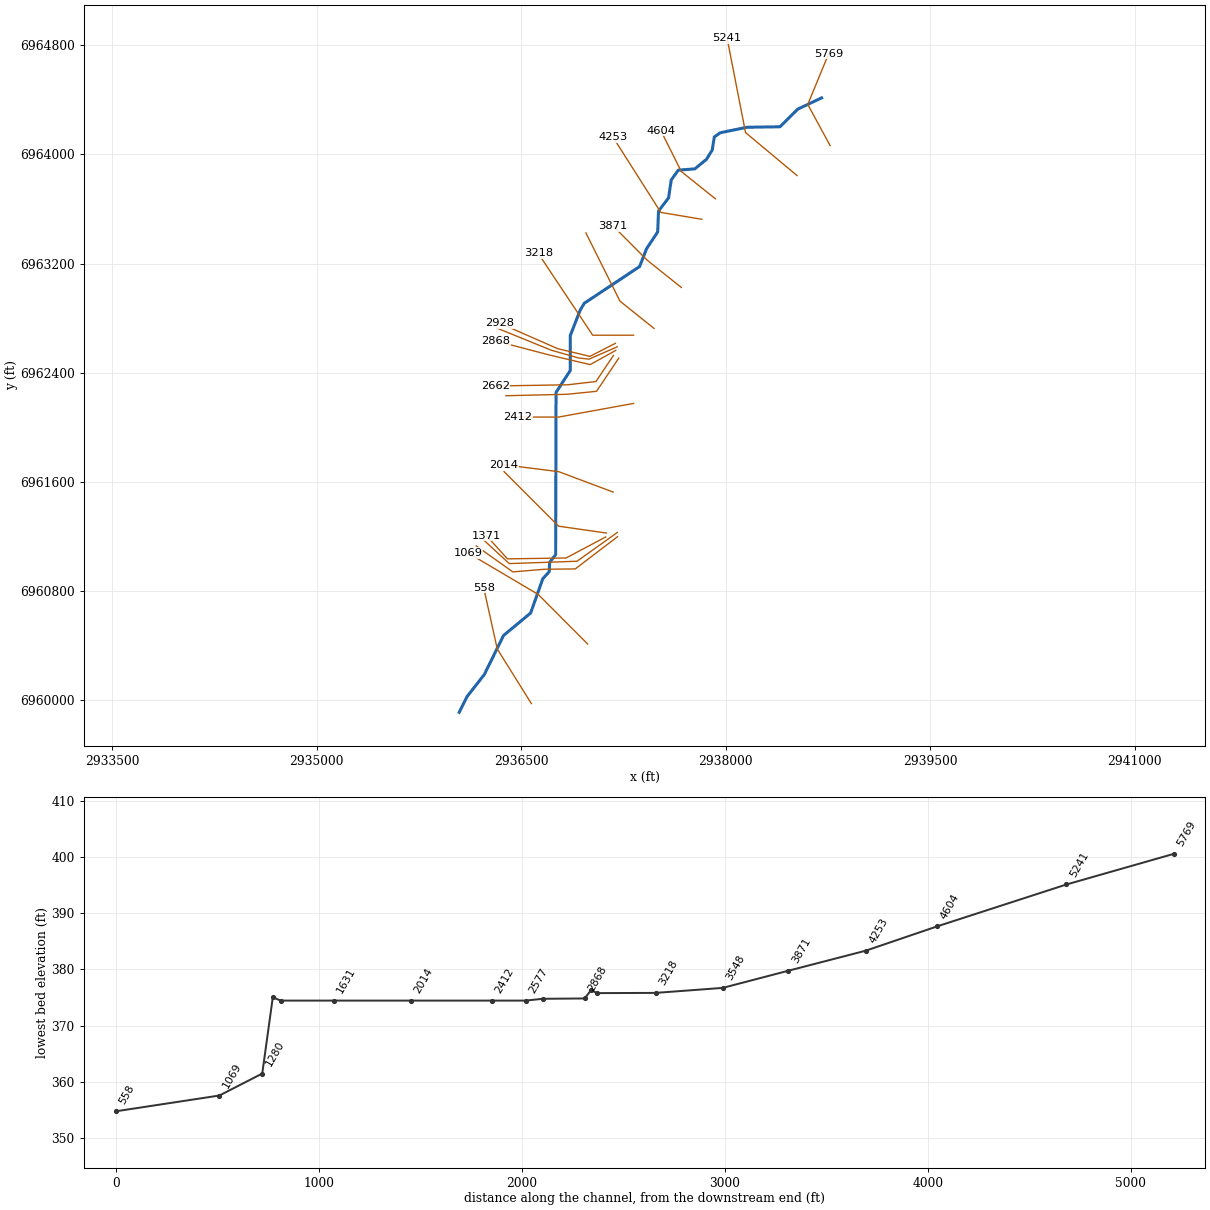
--- UNT 009 IN DRY CR WATERSHED.prj (project) ---

Proj Title=UNT 009 IN DRY CR WATERSHED Base Level Engineering
Current Plan=p01
Default Exp/Contr=0.3,0.1
English Units
Geom File=g01
Flow File=f01
Plan File=p01
BEGIN DESCRIPTION:
UNT 009 IN DRY CR WATERSHED
END DESCRIPTION:

--- UNT 009 IN DRY CR WATERSHED.p01 (plan) ---

Plan Title=Multiple Run
Short Identifier=Multiple
Geom File=g01
Flow File=f01
Subcritical Flow
K Sum by GR= 0
Std Step Tol= 0.01
Critical Tol= 0.01
Num of Std Step Trials= 20
Max Error Tol= 0.3
Flow Tol Ratio= 0.001
Split Flow NTrial= 30
Split Flow Tol= 0.02
Split Flow Ratio= 0.02
Log Output Level= 0
Friction Slope Method= 1
Unsteady Friction Slope Method= 2
Unsteady Bridges Friction Slope Method= 1
Parabolic Critical Depth
Global Vel Dist=  1 , 1 , 1
Global Log Level= 0
CheckData=True
Encroach Param= -1, 0, 0, 0
BEGIN DESCRIPTION:
Multiple Run
END DESCRIPTION:

--- UNT 009 IN DRY CR WATERSHED.f01 (steady flow) ---

Flow Title=Multiple
Number of Profiles=7
Profile Names=10-year,25-year,50-year,1pct_min,100-year,1pct_plu,500-year
River Rch & RM= UNT 009 IN DRY C,Reach-1,5769
     537     722     874     527    1052    2100    1525
River Rch & RM= UNT 009 IN DRY C,Reach-1,1069
     800    1103    1358     831    1658    3309    2477
Boundary for River Rch & Prof#=UNT 009 IN DRY C,Reach-1,1
Up Type=0
Dn Type=3
Dn Slope=0.005
Boundary for River Rch & Prof#=UNT 009 IN DRY C,Reach-1,2
Up Type=0
Dn Type=3
Dn Slope=0.005
Boundary for River Rch & Prof#=UNT 009 IN DRY C,Reach-1,3
Up Type=0
Dn Type=3
Dn Slope=0.005
Boundary for River Rch & Prof#=UNT 009 IN DRY C,Reach-1,4
Up Type=0
Dn Type=3
Dn Slope=0.005
Boundary for River Rch & Prof#=UNT 009 IN DRY C,Reach-1,5
Up Type=0
Dn Type=3
Dn Slope=0.005
Boundary for River Rch & Prof#=UNT 009 IN DRY C,Reach-1,6
Up Type=0
Dn Type=3
Dn Slope=0.005
Boundary for River Rch & Prof#=UNT 009 IN DRY C,Reach-1,7
Up Type=0
Dn Type=3
Dn Slope=0.005

--- UNT 009 IN DRY CR WATERSHED.g01 (geometry) ---

Geom Title=Existing Conditions

River Reach=UNT 009 IN DRY C,Reach-1
Reach XY= 30
      2938704.15      6964414.70      2938529.14      6964332.18
      2938399.29      6964203.02      2938156.00      6964199.26
      2937960.98      6964159.08      2937916.87      6964128.37
      2937901.99      6964032.21      2937859.21      6963963.90
      2937774.08      6963894.35      2937653.33      6963885.14
      2937601.00      6963813.25      2937581.90      6963682.24
      2937507.80      6963584.94      2937501.76      6963432.29
      2937419.79      6963308.36      2937369.45      6963178.65
      2936963.11      6962909.01      2936934.25      6962861.18
      2936860.32      6962671.87      2936860.46      6962416.30
      2936755.97      6962255.55      2936753.40      6961066.62
      2936709.21      6961009.21      2936705.59      6960940.71
      2936658.71      6960889.42      2936569.76      6960638.61
      2936370.66      6960473.72      2936230.32      6960188.18
      2936103.82      6960026.73      2936045.59      6959910.71

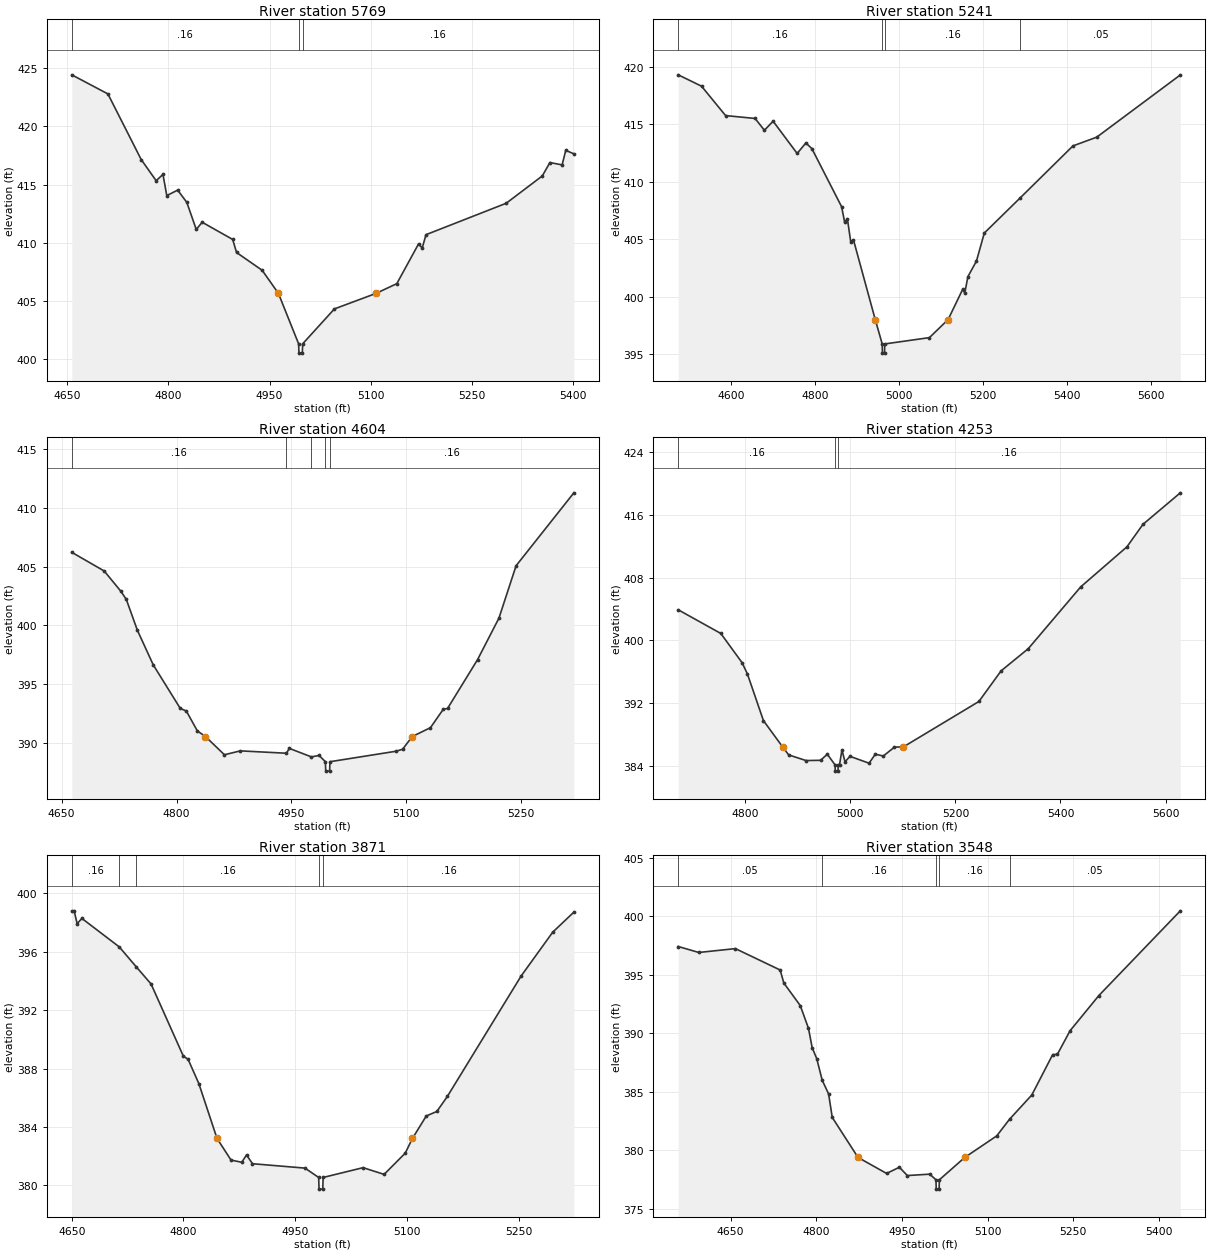
Type RM Length L Ch R = 1,5769,528,528,528
BEGIN DESCRIPTION:
UNT 009 IN DRY CR WATERSHED 12.0
END DESCRIPTION:
XS GIS Cut Line= 3
      2938766.81      6964065.07      2938602.56      6964366.64
      2938755.98      6964737.78
#Sta/Elev= 30
  4656.6  424.44  4710.2  422.80  4759.6  417.16  4781.8  415.34  4791.9  415.88
  4797.6  414.06  4813.7  414.53  4827.3  413.48  4841.3  411.15  4850.1  411.77
  4895.4  410.29  4901.1  409.17  4939.1  407.64  4963.2  405.66  4993.2  401.32
  4993.7  400.52  4998.7  400.52  4999.2  401.32  5046.3  404.32  5108.3  405.66
  5138.9  406.49  5171.2  409.91  5176.6  409.55  5182.2  410.70  5301.2  413.40
  5354.8  415.75  5366.1  416.90  5384.2  416.70  5389.6  417.95  5401.6  417.65
#Mann=3,-1,0
  4656.6    0.16       0  4993.2    0.07       0  4999.2    0.16       0
Bank Sta=4963.2,5108.3
Exp/Cntr=0.3,0.1

Type RM Length L Ch R = 1,5241,637,637,637
BEGIN DESCRIPTION:
Mapping XS 0373a5b7
END DESCRIPTION:
XS GIS Cut Line= 3
      2938523.80      6963845.39      2938146.17      6964160.52
      2938011.07      6964851.59
#Sta/Elev= 30
  4474.7  419.32  4530.2  418.33  4587.5  415.77  4657.8  415.52  4679.9  414.49
  4700.7  415.28  4758.0  412.47  4778.8  413.39  4793.1  412.89  4863.9  407.83
  4871.2  406.47  4877.7  406.77  4885.5  404.80  4892.1  404.95  4944.0  398.00
  4960.6  395.88  4961.1  395.08  4966.1  395.08  4966.6  395.88  5073.0  396.43
  5117.5  398.00  5152.2  400.63  5157.3  400.32  5164.7  401.74  5185.1  403.10
  5203.8  405.54  5289.8  408.62  5415.0  413.13  5471.6  413.89  5670.7  419.31
#Mann=4,-1,0
  4474.7    0.16       0  4960.6    0.07       0  4966.6    0.16       0
  5289.8    0.05       0
Bank Sta=4944,5117.5
Exp/Cntr=0.3,0.1

Type RM Length L Ch R = 1,4604,351,351,351
BEGIN DESCRIPTION:
UNT 009 IN DRY CR WATERSHED 11.0
END DESCRIPTION:
XS GIS Cut Line= 3
      2937924.97      6963675.02      2937675.00      6963875.00
      2937525.01      6964174.97
#Sta/Elev= 30
  4663.2  406.21  4705.6  404.62  4727.2  402.91  4734.4  402.21  4748.8  399.60
  4769.6  396.65  4804.8  392.96  4812.8  392.73  4827.2  391.04  4837.7  390.57
  4862.5  389.02  4883.3  389.35  4943.4  389.15  4947.3  389.56  4976.0  388.84
  4986.1  388.96  4994.3  388.43  4994.8  387.63  4999.8  387.63  5000.3  388.43
  5086.7  389.32  5095.1  389.49  5107.8  390.57  5131.5  391.32  5148.2  392.88
  5153.8  392.95  5193.0  397.10  5220.9  400.62  5243.3  405.07  5318.7  411.26
#Mann=5,-1,0
  4663.2    0.16       0  4943.4    0.05       0  4976.0    0.16       0
  4994.3    0.07       0  5000.3    0.16       0
Bank Sta=4837.7,5107.8
Exp/Cntr=0.3,0.1

Type RM Length L Ch R = 1,4253,382,382,382
BEGIN DESCRIPTION:
UNT 009 IN DRY CR WATERSHED 10.0
END DESCRIPTION:
XS GIS Cut Line= 3
      2937824.96      6963525.01      2937525.00      6963575.00
      2937175.01      6964124.99
#Sta/Elev= 30
  4672.2  403.90  4753.3  400.88  4793.8  397.15  4804.0  395.70  4834.4  389.76
  4870.9  386.41  4882.5  385.38  4915.5  384.66  4943.3  384.69  4956.0  385.47
  4970.8  384.11  4971.3  383.31  4976.3  383.31  4976.8  384.11  4979.3  384.11
  4983.9  386.01  4989.8  384.50  4999.2  385.20  5035.6  384.32  5047.4  385.47
  5062.7  385.24  5083.8  386.37  5101.1  386.41  5244.7  392.20  5287.0  396.11
  5338.7  398.94  5438.6  406.83  5526.6  411.94  5557.1  414.81  5628.2  418.83
#Mann=3,-1,0
  4672.2    0.16       0  4970.8    0.07       0  4976.8    0.16       0
Bank Sta=4870.9,5101.1
Exp/Cntr=0.3,0.1

Type RM Length L Ch R = 1,3871,323,323,323
BEGIN DESCRIPTION:
UNT 009 IN DRY CR WATERSHED 9.0
END DESCRIPTION:
XS GIS Cut Line= 3
      2937674.99      6963025.01      2937425.00      6963225.00
      2937175.00      6963475.00
#Sta/Elev= 30
  4650.1  398.80  4653.3  398.80  4657.3  397.92  4663.7  398.28  4713.8  396.33
  4736.7  394.96  4756.5  393.79  4799.8  388.85  4806.2  388.63  4820.6  386.97
  4845.0  383.21  4863.8  381.73  4878.2  381.58  4884.6  382.08  4892.6  381.48
  4963.0  381.18  4981.4  380.54  4981.9  379.74  4986.9  379.74  4987.4  380.54
  5041.0  381.21  5069.2  380.75  5097.5  382.20  5107.2  383.21  5125.8  384.75
  5140.0  385.06  5154.1  386.09  5253.1  394.34  5295.5  397.34  5323.8  398.71
#Mann=5,-1,0
  4650.1    0.16       0  4713.8    0.12       0  4736.7    0.16       0
  4981.4    0.07       0  4987.4    0.16       0
Bank Sta=4845,5107.2
Exp/Cntr=0.3,0.1

Type RM Length L Ch R = 1,3548,330,330,330
BEGIN DESCRIPTION:
UNT 009 IN DRY CR WATERSHED 8.0
END DESCRIPTION:
XS GIS Cut Line= 3
      2937475.01      6962725.00      2937225.00      6962925.00
      2936974.99      6963425.02
#Sta/Elev= 30
  4558.3  397.43  4594.3  396.92  4658.4  397.25  4736.8  395.42  4743.2  394.31
  4772.0  392.38  4786.4  390.43  4792.8  388.79  4800.8  387.85  4810.4  386.00
  4821.6  384.83  4828.0  382.82  4873.1  379.40  4923.2  378.03  4945.5  378.56
  4959.5  377.85  4998.7  377.97  5009.6  377.49  5010.1  376.69  5015.1  376.69
  5015.6  377.49  5060.1  379.40  5116.0  381.24  5138.4  382.66  5177.5  384.74
  5213.9  388.18  5222.3  388.22  5244.6  390.24  5294.9  393.24  5437.5  400.48
#Mann=5,-1,0
  4558.3    0.05       0  4810.4    0.16       0  5009.6    0.07       0
  5015.6    0.16       0  5138.4    0.05       0
Bank Sta=4873.1,5060.1
Exp/Cntr=0.3,0.1

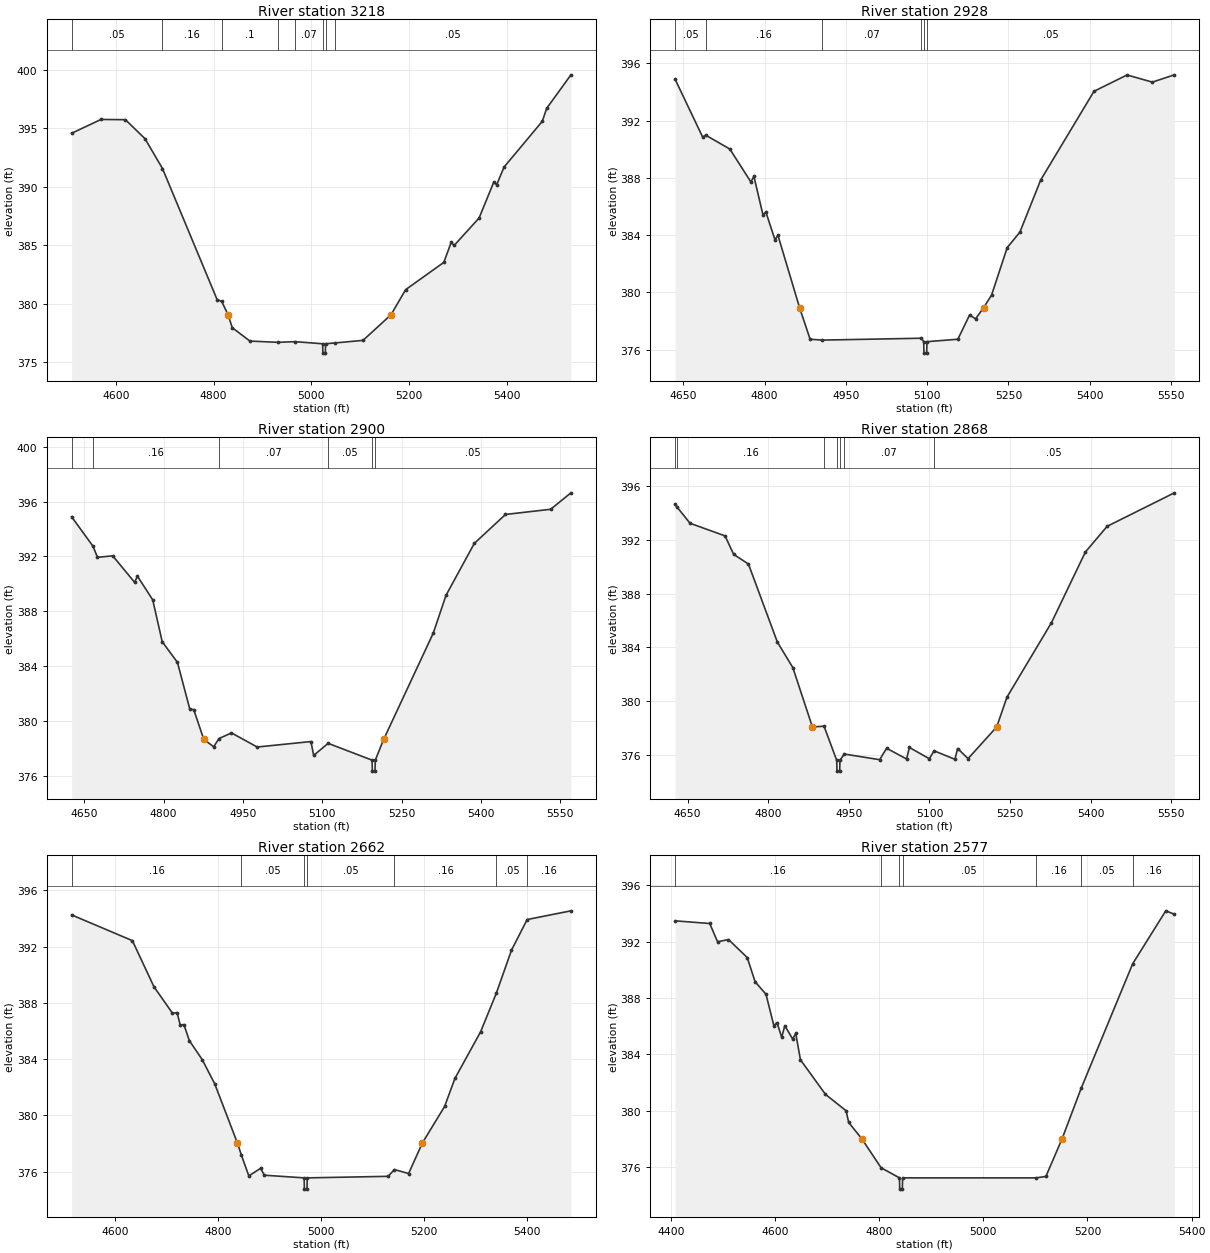
Type RM Length L Ch R = 1,3218,290,290,290
BEGIN DESCRIPTION:
UNT 009 IN DRY CR WATERSHED 7.0
END DESCRIPTION:
XS GIS Cut Line= 3
      2937324.97      6962675.00      2937025.00      6962675.00
      2936624.99      6963275.02
#Sta/Elev= 30
  4509.6  394.57  4569.6  395.75  4619.6  395.73  4659.6  394.11  4695.4  391.56
  4807.1  380.37  4816.5  380.21  4829.6  379.07  4838.1  377.97  4874.2  376.83
  4932.4  376.72  4966.3  376.78  5022.9  376.60  5023.4  375.80  5028.4  375.80
  5028.9  376.60  5048.2  376.67  5105.5  376.89  5162.6  379.07  5192.7  381.22
  5270.8  383.55  5285.8  385.26  5291.8  384.99  5342.9  387.34  5372.9  390.40
  5378.9  390.18  5394.0  391.69  5472.1  395.59  5481.1  396.70  5530.7  399.56
#Mann=8,-1,0
  4509.6    0.05       0  4695.4    0.16       0  4816.5     0.1       0
  4932.4    0.05       0  4966.3    0.07       0  5022.9    0.07       0
  5028.9    0.07       0  5048.2    0.05       0
Bank Sta=4829.6,5162.6
Exp/Cntr=0.3,0.1

Type RM Length L Ch R = 1,2928,28,28,28
BEGIN DESCRIPTION:
Mapping XS a28a9aa2
END DESCRIPTION:
XS GIS Cut Line= 4
      2937191.29      6962615.38      2937004.67      6962519.90
      2936768.13      6962576.32      2936339.22      6962764.78
#Sta/Elev= 30
  4634.8  394.89  4685.9  390.83  4691.2  390.98  4735.9  390.01  4774.7  387.71
  4780.3  388.10  4796.9  385.43  4802.5  385.60  4819.1  383.68  4824.7  383.98
  4864.6  378.93  4884.0  376.73  4906.5  376.67  5089.3  376.80  5093.6  376.56
  5094.1  375.76  5099.1  375.76  5099.6  376.56  5156.6  376.73  5178.4  378.43
  5189.3  378.15  5204.0  378.93  5218.8  379.81  5247.7  383.13  5271.0  384.20
  5309.5  387.85  5407.8  394.04  5468.8  395.18  5515.5  394.68  5556.1  395.19
#Mann=6,-1,0
  4634.8    0.05       0  4691.2    0.16       0  4906.5    0.07       0
  5089.3    0.05       0  5093.6    0.07       0  5099.6    0.05       0
Bank Sta=4864.6,5204
Exp/Cntr=0.3,0.1

Type RM Length L Ch R = 1,2900,32,32,32
BEGIN DESCRIPTION:
Mapping XS 372b0fe3
END DESCRIPTION:
XS GIS Cut Line= 5
      2937204.50      6962589.65      2936997.93      6962499.38
      2936921.54      6962508.06      2936720.15      6962565.35
      2936319.55      6962728.37
#Sta/Elev= 30
  4626.2  394.89  4666.8  392.73  4675.0  391.93  4703.9  392.04  4745.2  390.11
  4750.7  390.55  4779.5  388.83  4797.5  385.77  4826.3  384.26  4849.7  380.84
  4857.1  380.81  4876.1  378.64  4894.8  378.10  4904.9  378.70  4928.5  379.11
  4977.1  378.08  5078.7  378.48  5083.9  377.47  5111.3  378.35  5194.4  377.12
  5194.9  376.32  5199.9  376.32  5200.4  377.12  5216.3  378.64  5310.1  386.40
  5334.2  389.16  5387.7  392.95  5446.6  395.06  5532.1  395.44  5570.4  396.64
#Mann=6,-1,0
  4626.2    0.05       0  4666.8    0.16       0  4904.9    0.07       0
  5111.3    0.05       0  5194.4    0.07       0  5200.4    0.05       0
Bank Sta=4876.1,5216.3
Exp/Cntr=0.3,0.1

Type RM Length L Ch R = 1,2868,206,206,206
BEGIN DESCRIPTION:
Mapping XS 7cdc3e73
END DESCRIPTION:
XS GIS Cut Line= 4
      2937194.12      6962563.62      2937006.61      6962459.45
      2936697.58      6962532.37      2936313.89      6962633.06
#Sta/Elev= 30
  4626.8  394.65  4630.0  394.46  4654.6  393.23  4719.8  392.29  4735.8  390.92
  4763.3  390.20  4817.1  384.40  4845.9  382.50  4882.3  378.09  4903.9  378.15
  4927.5  375.61  4928.0  374.81  4933.0  374.81  4933.5  375.61  4941.5  376.08
  5007.4  375.66  5020.3  376.51  5057.5  375.71  5062.6  376.57  5099.8  375.73
  5108.5  376.32  5147.3  375.69  5152.4  376.49  5171.8  375.74  5225.0  378.09
  5244.2  380.31  5326.9  385.84  5390.0  391.09  5430.4  393.00  5555.5  395.49
#Mann=7,-1,0
  4626.8    0.05       0  4630.0    0.16       0  4903.9    0.05       0
  4927.5    0.07       0  4933.5    0.05       0  4941.5    0.07       0
  5108.5    0.05       0
Bank Sta=4882.3,5225
Exp/Cntr=0.3,0.1

Type RM Length L Ch R = 1,2662,85,85,85
BEGIN DESCRIPTION:
Mapping XS 86271bdb
END DESCRIPTION:
XS GIS Cut Line= 4
      2937176.90      6962526.34      2937048.89      6962335.41
      2936840.55      6962311.53      2936309.40      6962302.86
#Sta/Elev= 30
  4515.0  394.25  4633.1  392.42  4675.1  389.14  4711.1  387.26  4720.1  387.30
  4726.1  386.42  4733.3  386.45  4743.9  385.31  4768.9  383.96  4793.2  382.24
  4837.3  378.03  4845.2  377.16  4859.5  375.69  4882.4  376.23  4889.7  375.74
  4967.1  375.55  4967.6  374.75  4972.6  374.75  4973.1  375.55  5130.2  375.66
  5142.7  376.14  5170.2  375.86  5196.9  378.03  5240.2  380.63  5260.2  382.62
  5310.2  385.94  5340.7  388.68  5370.2  391.74  5400.6  393.92  5485.8  394.54
#Mann=7,-1,0
  4515.0    0.16       0  4845.2    0.05       0  4967.1   0.033       0
  4973.1    0.05       0  5142.7    0.16       0  5340.7    0.05       0
  5400.6    0.16       0
Bank Sta=4837.3,5196.9
Exp/Cntr=0.3,0.1

Type RM Length L Ch R = 1,2577,165,165,165
BEGIN DESCRIPTION:
Mapping XS a61366bd
END DESCRIPTION:
XS GIS Cut Line= 4
      2937216.00      6962506.87      2937053.23      6962263.79
      2936836.21      6962242.09      2936388.49      6962231.27
#Sta/Elev= 30
  4408.3  393.49  4474.9  393.30  4489.9  392.00  4510.9  392.16  4546.9  390.88
  4561.9  389.17  4582.9  388.27  4598.0  386.04  4604.0  386.26  4613.0  385.22
  4619.0  386.04  4634.0  385.10  4640.0  385.49  4649.0  383.62  4697.1  381.16
  4736.6  380.00  4741.6  379.17  4766.5  378.02  4803.8  375.95  4839.1  375.23
  4839.6  374.43  4844.6  374.43  4845.1  375.23  5101.1  375.23  5120.2  375.33
  5151.4  378.02  5188.2  381.62  5286.8  390.44  5350.3  394.20  5366.8  393.96
#Mann=7,-1,0
  4408.3    0.16       0  4803.8    0.05       0  4839.1   0.033       0
  4845.1    0.05       0  5101.1    0.16       0  5188.2    0.05       0
  5286.8    0.16       0
Bank Sta=4766.5,5151.4
Exp/Cntr=0.3,0.1

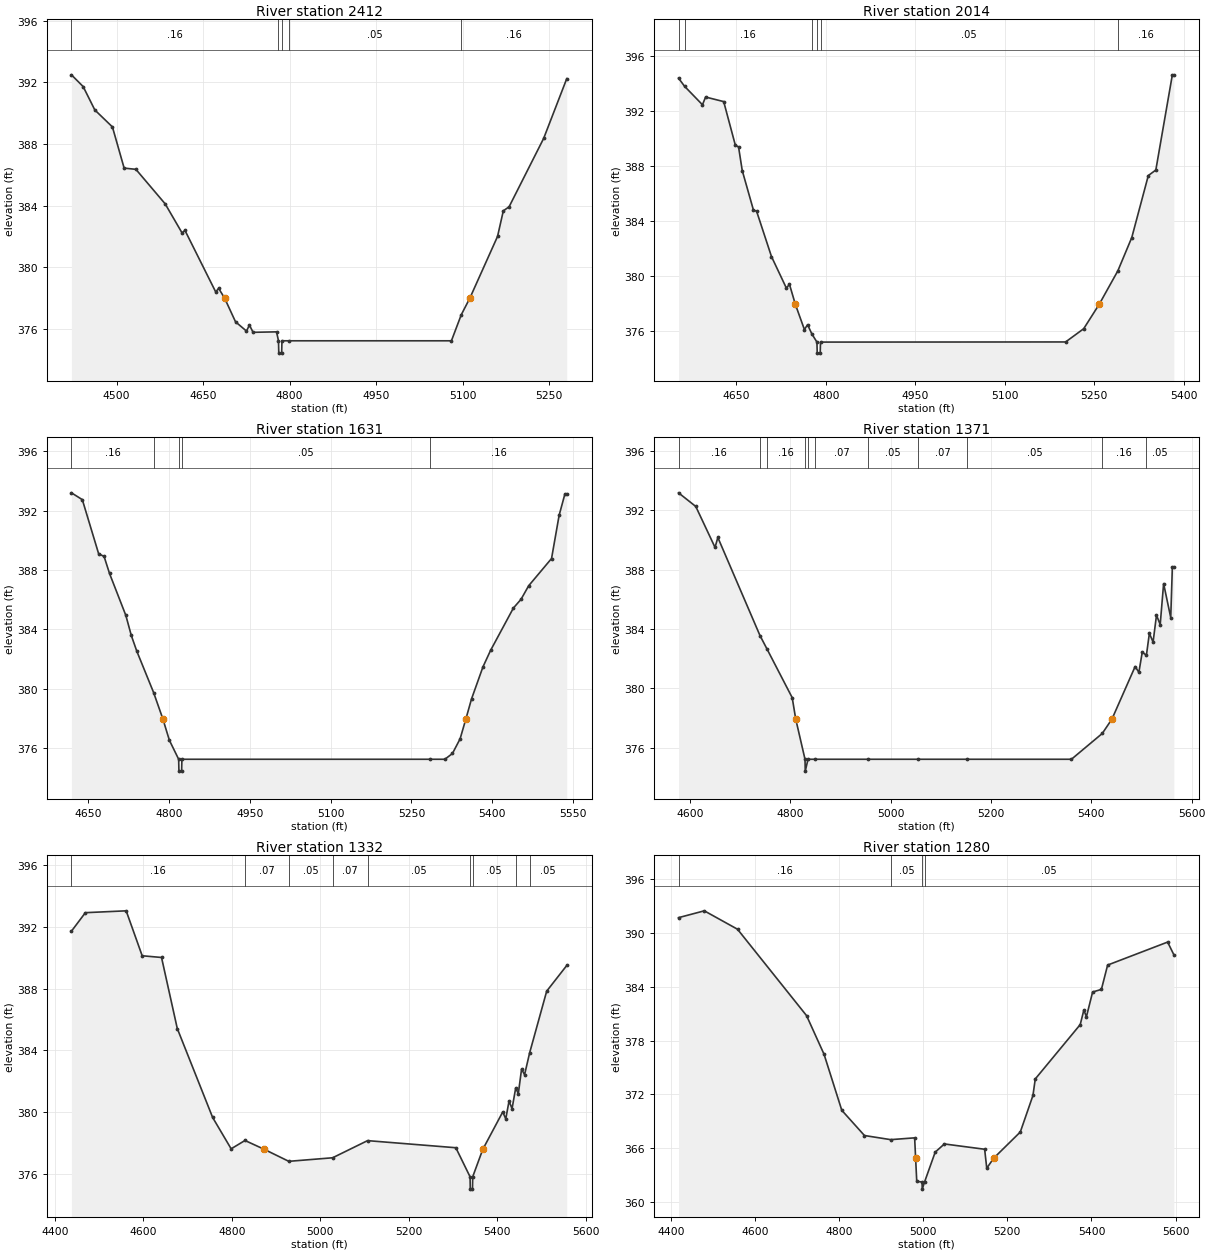
Type RM Length L Ch R = 1,2412,398,398,398
BEGIN DESCRIPTION:
UNT 009 IN DRY CR WATERSHED 5.0
END DESCRIPTION:
XS GIS Cut Line= 3
      2937324.96      6962174.99      2936775.00      6962075.00
      2936474.98      6962075.00
#Sta/Elev= 30
  4421.6  392.48  4441.9  391.72  4462.2  390.20  4492.7  389.10  4513.0  386.43
  4533.4  386.35  4584.2  384.11  4613.4  382.23  4618.5  382.39  4671.8  378.40
  4676.9  378.63  4687.2  378.00  4706.2  376.46  4725.2  375.86  4730.3  376.25
  4736.6  375.78  4777.3  375.81  4780.7  375.23  4781.2  374.43  4786.2  374.43
  4786.7  375.23  4798.5  375.23  5080.6  375.23  5097.7  376.92  5112.6  378.00
  5160.6  382.00  5170.6  383.66  5180.6  383.92  5240.6  388.36  5280.6  392.23
#Mann=5,-1,0
  4421.6    0.16       0  4780.7   0.033       0  4786.7    0.16       0
  4798.5    0.05       0  5097.7    0.16       0
Bank Sta=4687.2,5112.6
Exp/Cntr=0.3,0.1

Type RM Length L Ch R = 1,2014,383,383,383
BEGIN DESCRIPTION:
UNT 009 IN DRY CR WATERSHED 4.0
END DESCRIPTION:
XS GIS Cut Line= 3
      2937175.03      6961524.99      2936775.00      6961675.00
      2936375.05      6961724.99
#Sta/Elev= 30
  4553.2  394.36  4563.3  393.77  4593.3  392.43  4598.6  392.99  4628.9  392.66
  4648.5  389.49  4653.8  389.38  4660.0  387.66  4678.7  384.81  4684.1  384.71
  4709.0  381.43  4733.9  379.15  4739.2  379.41  4749.0  377.97  4764.2  376.14
  4769.5  376.49  4776.7  375.82  4785.2  375.23  4785.7  374.43  4790.7  374.43
  4791.2  375.23  5202.1  375.24  5232.4  376.20  5258.4  377.97  5289.7  380.40
  5313.0  382.81  5340.7  387.30  5353.3  387.70  5381.0  394.60  5383.5  394.60
#Mann=6,-1,0
  4553.2    0.05       0  4563.3    0.16       0  4776.7    0.05       0
  4785.2   0.033       0  4791.2    0.05       0  5289.7    0.16       0
Bank Sta=4749,5258.4
Exp/Cntr=0.3,0.1

Type RM Length L Ch R = 1,1631,260,260,260
BEGIN DESCRIPTION:
UNT 009 IN DRY CR WATERSHED 3.0
END DESCRIPTION:
XS GIS Cut Line= 3
      2937125.01      6961225.00      2936775.00      6961275.00
      2936375.03      6961674.97
#Sta/Elev= 30
  4619.0  393.20  4639.2  392.74  4669.5  389.09  4679.6  388.91  4689.7  387.76
  4720.0  384.93  4730.1  383.58  4740.2  382.53  4771.5  379.73  4788.6  377.96
  4800.8  376.51  4818.0  375.23  4818.5  374.43  4823.5  374.43  4824.0  375.23
  5284.5  375.23  5312.0  375.23  5326.1  375.62  5340.3  376.61  5351.1  377.96
  5361.5  379.30  5382.7  381.46  5396.8  382.57  5439.2  385.43  5453.4  386.02
  5467.5  386.93  5510.0  388.77  5524.1  391.69  5534.7  393.11  5538.2  393.11
#Mann=5,-1,0
  4619.0    0.16       0  4771.5    0.05       0  4818.0   0.033       0
  4824.0    0.05       0  5284.5    0.16       0
Bank Sta=4788.6,5351.1
Exp/Cntr=0.3,0.1

Type RM Length L Ch R = 1,1371,39,39,39
BEGIN DESCRIPTION:
Mapping XS 9b1776c8
END DESCRIPTION:
XS GIS Cut Line= 4
      2937120.49      6961196.08      2936829.70      6961042.00
      2936400.01      6961035.49      2936245.95      6961204.75
#Sta/Elev= 30
  4576.8  393.19  4611.2  392.27  4649.6  389.51  4655.2  390.18  4739.2  383.57
  4752.8  382.69  4803.5  379.38  4810.5  377.94  4829.0  375.23  4829.5  374.43
  4835.0  375.23  4849.9  375.23  4954.9  375.23  5053.9  375.23  5152.9  375.23
  5360.3  375.23  5421.8  376.97  5441.1  377.94  5487.3  381.48  5494.8  381.09
  5501.5  382.45  5509.8  382.24  5515.7  383.72  5523.1  383.13  5529.9  384.94
  5537.3  384.31  5544.1  387.07  5558.3  384.78  5561.5  388.16  5564.5  388.16
#Mann=11,-1,0
  4576.8    0.16       0  4739.2    0.05       0  4752.8    0.16       0
  4829.0   0.033       0  4835.0    0.16       0  4849.9    0.07       0
  4954.9    0.05       0  5053.9    0.07       0  5152.9    0.05       0
  5421.8    0.16       0  5509.8    0.05       0
Bank Sta=4810.5,5441.1
Exp/Cntr=0.3,0.1

Type RM Length L Ch R = 1,1332,52,52,52
BEGIN DESCRIPTION:
Mapping XS ca79d857
END DESCRIPTION:
XS GIS Cut Line= 4
      2937205.14      6961228.64      2936910.00      6961018.13
      2936413.04      6961000.77      2936222.10      6961176.52
#Sta/Elev= 30
  4437.6  391.72  4469.1  392.92  4561.3  393.04  4597.5  390.13  4641.2  390.02
  4676.8  385.42  4756.7  379.66  4798.5  377.63  4829.8  378.17  4873.8  377.59
  4928.8  376.82  5027.8  377.05  5106.8  378.16  5306.3  377.70  5338.4  375.82
  5338.9  375.02  5343.9  375.02  5344.4  375.82  5367.1  377.59  5412.3  380.02
  5419.1  379.57  5426.5  380.72  5433.3  380.23  5441.5  381.56  5447.5  381.21
  5454.8  382.79  5461.6  382.43  5473.0  383.84  5511.6  387.84  5556.9  389.50
#Mann=9,-1,0
  4437.6    0.16       0  4829.8    0.07       0  4928.8    0.05       0
  5027.8    0.07       0  5106.8    0.05       0  5338.4   0.033       0
  5344.4    0.05       0  5441.5    0.16       0  5473.0    0.05       0
Bank Sta=4873.8,5367.1
Exp/Cntr=0.3,0.1

Type RM Length L Ch R = 1,1280,211,211,211
BEGIN DESCRIPTION:
Mapping XS 2feaf205
END DESCRIPTION:
XS GIS Cut Line= 5
      2937207.33      6961198.27      2936896.98      6960961.71
      2936673.45      6960959.54      2936439.08      6960940.01
      2936170.66      6961130.50
#Sta/Elev= 30
  4417.9  391.69  4479.2  392.45  4558.2  390.40  4722.4  380.78  4764.0  376.48
  4806.2  370.24  4860.1  367.43  4922.5  366.97  4979.5  367.17  4981.8  364.92
  4984.5  362.32  4997.1  362.26  4997.6  361.46  5003.1  362.26  5028.4  365.58
  5050.2  366.49  5146.0  365.90  5151.0  363.79  5167.8  364.92  5230.8  367.82
  5260.9  371.89  5266.4  373.73  5373.3  379.78  5381.9  381.39  5388.1  380.66
  5402.8  383.41  5423.7  383.70  5438.5  386.41  5581.2  388.97  5596.0  387.56
#Mann=4,-1,0
  4417.9    0.16       0  4922.5    0.05       0  4997.1    0.03       0
  5003.1    0.05       0
Bank Sta=4981.8,5167.8
Exp/Cntr=0.3,0.1

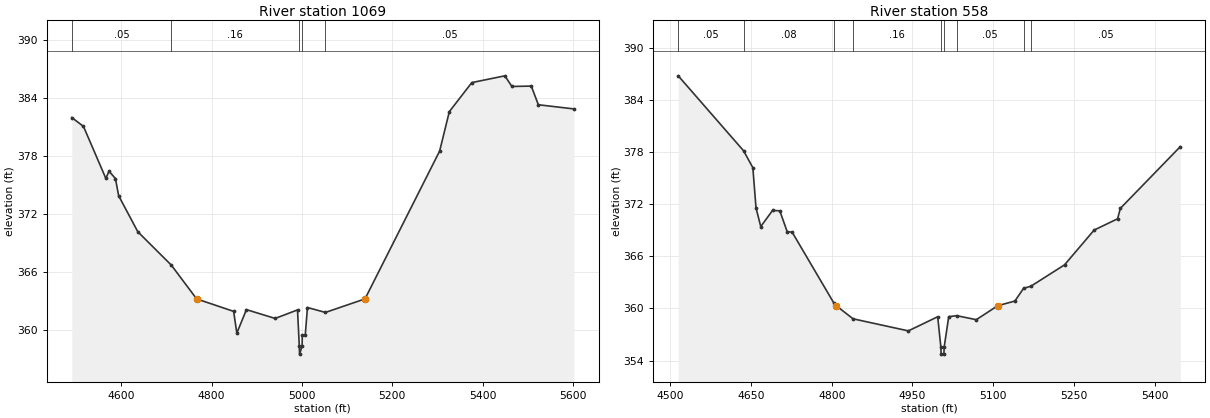
Type RM Length L Ch R = 1,1069,511,511,511
BEGIN DESCRIPTION:
UNT 009 IN DRY CR WATERSHED 2.0
END DESCRIPTION:
XS GIS Cut Line= 3
      2936988.09      6960411.39      2936625.00      6960775.00
      2936110.50      6961078.90
#Sta/Elev= 30
  4490.5  382.01  4516.4  381.09  4565.9  375.72  4573.0  376.46  4587.2  375.70
  4594.2  373.93  4636.7  370.20  4710.9  366.75  4766.9  363.26  4848.8  361.97
  4855.9  359.72  4877.1  362.15  4940.7  361.24  4990.2  362.12  4994.2  358.35
  4994.7  357.55  5000.3  358.35  5000.8  359.49  5007.3  359.49  5012.2  362.37
  5052.0  361.86  5139.6  363.26  5304.8  378.54  5326.3  382.62  5376.0  385.62
  5449.1  386.32  5464.8  385.22  5507.7  385.26  5523.3  383.33  5601.9  382.90
#Mann=5,-1,0
  4490.5    0.05       0  4710.9    0.16       0  4994.2    0.07       0
  5000.3    0.16       0  5052.0    0.05       0
Bank Sta=4766.9,5139.6
Exp/Cntr=0.3,0.1

Type RM Length L Ch R = 1,558,0,0,0
BEGIN DESCRIPTION:
UNT 009 IN DRY CR WATERSHED 1.0
END DESCRIPTION:
XS GIS Cut Line= 3
      2936575.02      6959974.97      2936325.00      6960375.00
      2936225.00      6960824.99
#Sta/Elev= 30
  4514.9  386.82  4636.3  378.18  4653.5  376.23  4659.4  371.59  4668.2  369.45
  4690.1  371.30  4703.6  371.26  4717.2  368.87  4726.6  368.79  4804.2  360.61
  4808.4  360.32  4839.7  358.81  4942.4  357.42  4996.9  359.05  5002.8  355.54
  5003.3  354.74  5008.4  354.74  5008.9  355.54  5017.4  359.06  5032.4  359.17
  5068.6  358.71  5108.4  360.32  5140.3  360.86  5156.4  362.32  5170.1  362.57
  5232.5  365.03  5287.5  369.04  5331.1  370.34  5336.2  371.54  5447.6  378.66
#Mann=9,-1,0
  4514.9    0.05       0  4636.3    0.08       0  4804.2    0.05       0
  4839.7    0.16       0  5002.8    0.07       0  5008.9    0.16       0
  5032.4    0.05       0  5156.4    0.16       0  5170.1    0.05       0
Bank Sta=4808.4,5108.4
Exp/Cntr=0.3,0.1

Chan Stop Cuts=-1