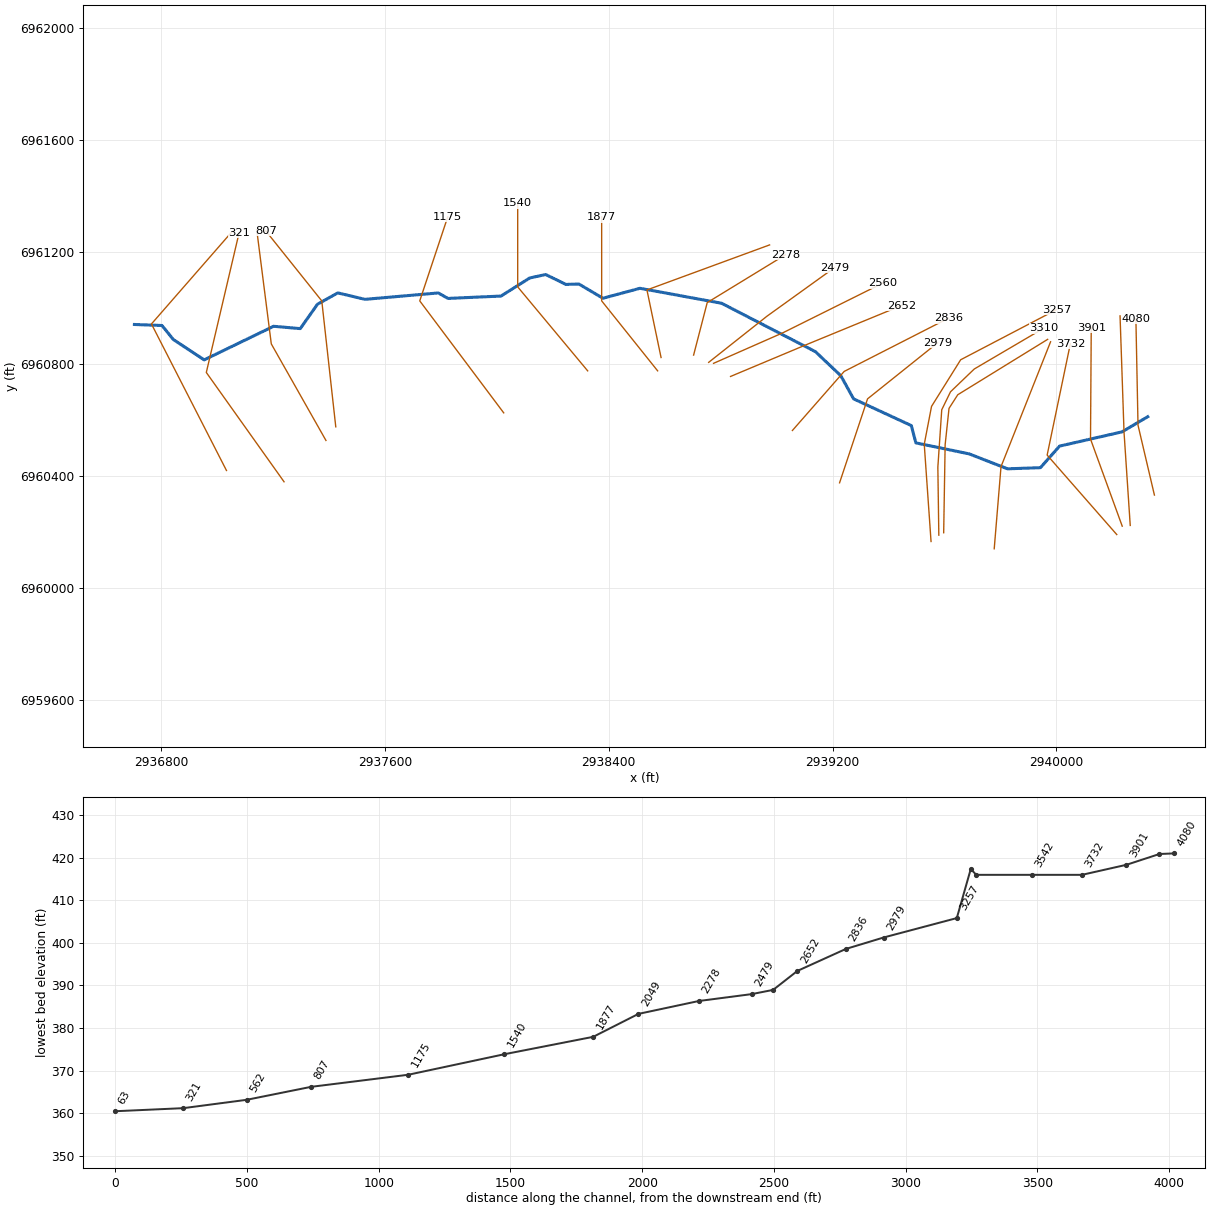
--- UNT 010 IN DRY CR WATERSHED.prj (project) ---

Proj Title=UNT 010 IN DRY CR WATERSHED Base Level Engineering
Current Plan=p01
Default Exp/Contr=0.3,0.1
English Units
Geom File=g01
Flow File=f01
Plan File=p01
BEGIN DESCRIPTION:
UNT 010 IN DRY CR WATERSHED
END DESCRIPTION:

--- UNT 010 IN DRY CR WATERSHED.p01 (plan) ---

Plan Title=Multiple Run
Short Identifier=Multiple
Geom File=g01
Flow File=f01
Subcritical Flow
K Sum by GR= 0
Std Step Tol= 0.01
Critical Tol= 0.01
Num of Std Step Trials= 20
Max Error Tol= 0.3
Flow Tol Ratio= 0.001
Split Flow NTrial= 30
Split Flow Tol= 0.02
Split Flow Ratio= 0.02
Log Output Level= 0
Friction Slope Method= 1
Unsteady Friction Slope Method= 2
Unsteady Bridges Friction Slope Method= 1
Parabolic Critical Depth
Global Vel Dist=  1 , 1 , 1
Global Log Level= 0
CheckData=True
Encroach Param= -1, 0, 0, 0
BEGIN DESCRIPTION:
Multiple Run
END DESCRIPTION:

--- UNT 010 IN DRY CR WATERSHED.f01 (steady flow) ---

Flow Title=Multiple
Number of Profiles=7
Profile Names=10-year,25-year,50-year,1pct_min,100-year,1pct_plu,500-year
River Rch & RM= UNT 010 IN DRY C,Reach-1,4080
     155     191     219     125     250     499     326
River Rch & RM= UNT 010 IN DRY C,Reach-1,1877
     395     522     625     374     746    1488    1059
Boundary for River Rch & Prof#=UNT 010 IN DRY C,Reach-1,1
Up Type=0
Dn Type=3
Dn Slope=0.005
Boundary for River Rch & Prof#=UNT 010 IN DRY C,Reach-1,2
Up Type=0
Dn Type=3
Dn Slope=0.005
Boundary for River Rch & Prof#=UNT 010 IN DRY C,Reach-1,3
Up Type=0
Dn Type=3
Dn Slope=0.005
Boundary for River Rch & Prof#=UNT 010 IN DRY C,Reach-1,4
Up Type=0
Dn Type=3
Dn Slope=0.005
Boundary for River Rch & Prof#=UNT 010 IN DRY C,Reach-1,5
Up Type=0
Dn Type=3
Dn Slope=0.005
Boundary for River Rch & Prof#=UNT 010 IN DRY C,Reach-1,6
Up Type=0
Dn Type=3
Dn Slope=0.005
Boundary for River Rch & Prof#=UNT 010 IN DRY C,Reach-1,7
Up Type=0
Dn Type=3
Dn Slope=0.005

--- UNT 010 IN DRY CR WATERSHED.g01 (geometry) ---

Geom Title=Existing Conditions

River Reach=UNT 010 IN DRY C,Reach-1
Reach XY= 30
      2940325.99      6960611.18      2940233.76      6960556.93
      2940011.04      6960506.16      2939942.63      6960429.13
      2939825.00      6960425.00      2939688.12      6960478.38
      2939497.58      6960517.66      2939481.31      6960579.51
      2939275.00      6960675.00      2939229.57      6960757.46
      2939138.73      6960843.61      2938803.27      6961016.58
      2938511.81      6961069.97      2938379.54      6961034.53
      2938293.77      6961085.14      2938246.92      6961083.93
      2938175.04      6961119.19      2938117.95      6961106.86
      2938015.33      6961042.26      2937825.81      6961033.81
      2937791.21      6961053.41      2937529.43      6961030.54
      2937432.25      6961053.56      2937359.59      6961013.08
      2937298.17      6960925.95      2937202.79      6960934.29
      2936954.80      6960814.29      2936844.47      6960887.10
      2936804.10      6960937.06      2936705.59      6960940.71

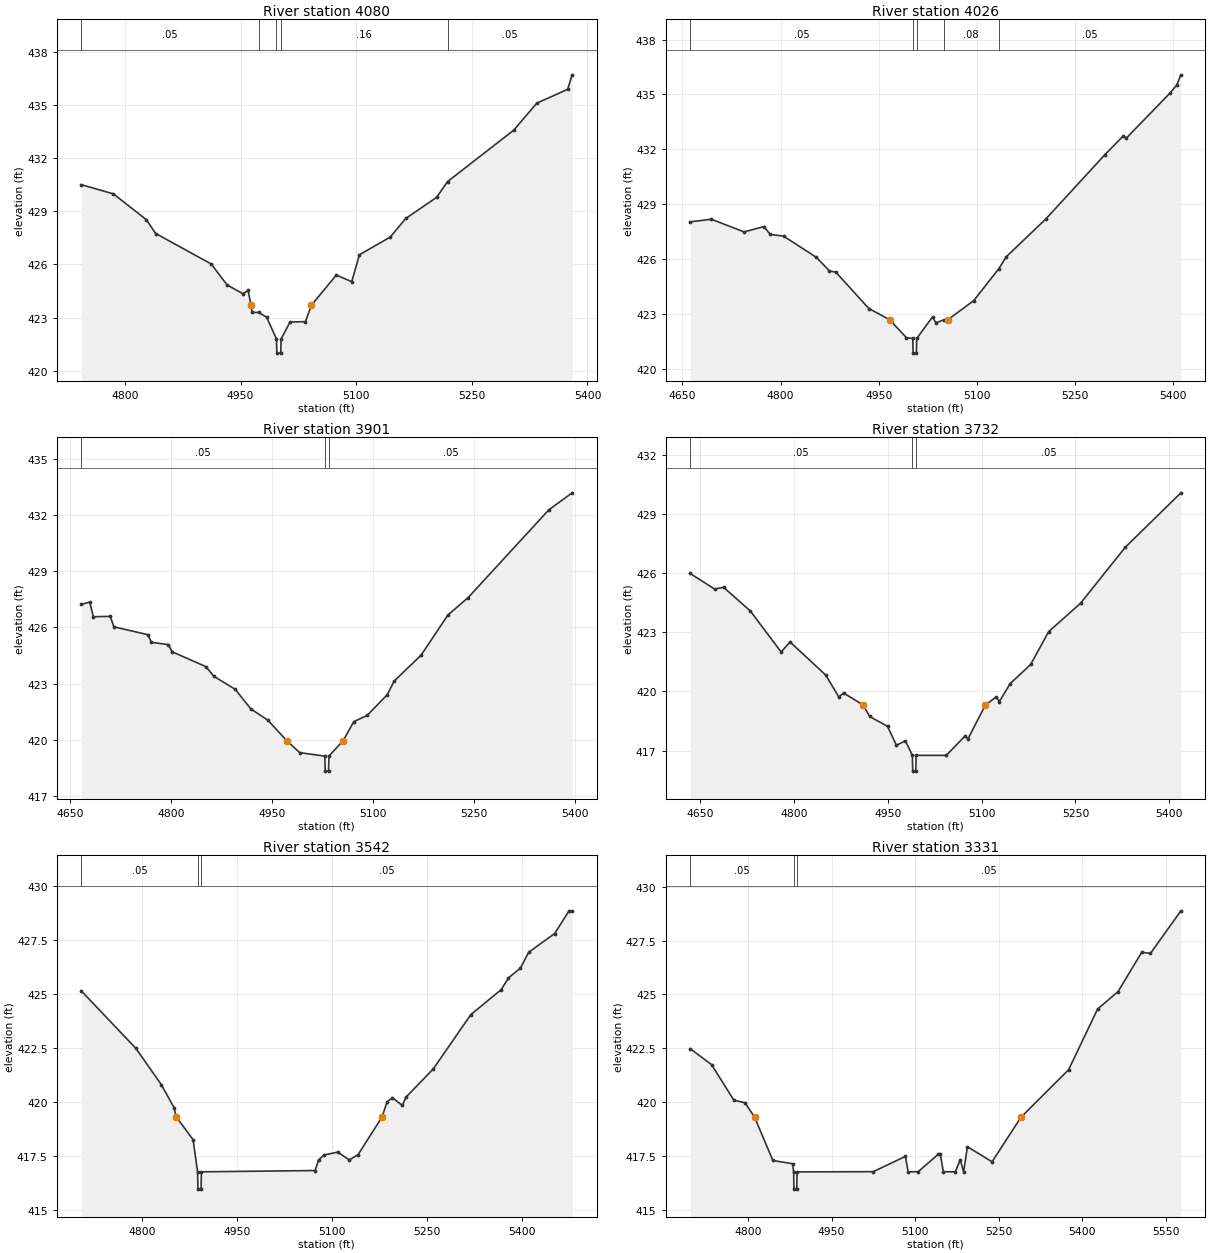
Type RM Length L Ch R = 1,4080,54,54,54
BEGIN DESCRIPTION:
UNT 010 IN DRY CR WATERSHED 10.0
END DESCRIPTION:
XS GIS Cut Line= 3
      2940349.87      6960331.19      2940291.27      6960580.80
      2940283.69      6960960.82
#Sta/Elev= 30
  4743.6  430.51  4785.1  429.99  4827.6  428.54  4840.0  427.75  4911.9  426.03
  4932.4  424.85  4953.0  424.35  4959.9  424.53  4963.4  423.70  4965.1  423.29
  4973.5  423.29  4983.8  423.02  4996.6  421.79  4997.1  420.99  5002.1  420.99
  5002.6  421.79  5014.2  422.75  5034.2  422.77  5041.9  423.70  5074.2  425.40
  5094.2  425.03  5104.2  426.55  5144.2  427.55  5164.2  428.60  5204.2  429.79
  5218.6  430.69  5304.3  433.59  5334.3  435.12  5374.3  435.90  5380.1  436.72
#Mann=5,-1,0
  4743.6    0.05       0  4973.5    0.16       0  4996.6    0.07       0
  5002.6    0.16       0  5218.6    0.05       0
Bank Sta=4963.4,5041.9
Exp/Cntr=0.3,0.1

Type RM Length L Ch R = 1,4026,125,125,125
BEGIN DESCRIPTION:
Mapping XS 7595edd4
END DESCRIPTION:
XS GIS Cut Line= 3
      2940263.49      6960222.75      2940241.36      6960554.76
      2940227.08      6960971.36
#Sta/Elev= 30
  4662.0  428.03  4694.3  428.17  4744.4  427.48  4774.5  427.77  4784.5  427.34
  4804.6  427.25  4854.7  426.09  4874.7  425.35  4884.7  425.27  4934.9  423.29
  4966.6  422.68  4992.4  421.69  5002.0  421.65  5002.5  420.85  5007.5  420.85
  5008.0  421.65  5032.2  422.83  5037.2  422.51  5049.1  422.66  5055.7  422.68
  5095.1  423.72  5133.5  425.47  5145.1  426.13  5205.1  428.18  5295.2  431.69
  5323.3  432.72  5328.3  432.61  5395.2  435.08  5405.2  435.51  5411.6  436.07
#Mann=5,-1,0
  4662.0    0.05       0  5002.0    0.03       0  5008.0    0.05       0
  5049.1    0.08       0  5133.5    0.05       0
Bank Sta=4966.6,5055.7
Exp/Cntr=0.3,0.1

Type RM Length L Ch R = 1,3901,169,169,169
BEGIN DESCRIPTION:
Mapping XS 76d414f1
END DESCRIPTION:
XS GIS Cut Line= 3
      2940234.85      6960220.12      2940121.56      6960531.32
      2940124.17      6960929.73
#Sta/Elev= 30
  4666.6  427.23  4678.9  427.35  4684.3  426.57  4709.5  426.59  4714.8  426.03
  4765.4  425.61  4770.7  425.20  4795.9  425.08  4801.3  424.70  4851.8  423.90
  4863.4  423.39  4895.3  422.69  4918.3  421.65  4943.5  421.05  4971.9  419.95
  4991.1  419.31  5028.5  419.12  5029.0  418.32  5034.0  418.32  5034.5  419.12
  5055.8  419.95  5071.5  420.96  5091.5  421.30  5121.5  422.41  5131.5  423.13
  5171.5  424.51  5211.5  426.66  5241.5  427.59  5361.5  432.28  5396.2  433.19
#Mann=3,-1,0
  4666.6    0.05       0  5028.5    0.03       0  5034.5    0.05       0
Bank Sta=4971.9,5055.8
Exp/Cntr=0.3,0.1

Type RM Length L Ch R = 1,3732,190,190,190
BEGIN DESCRIPTION:
Mapping XS 58be664a
END DESCRIPTION:
XS GIS Cut Line= 3
      2940215.30      6960190.19      2939966.62      6960474.03
      2940049.56      6960871.90
#Sta/Elev= 30
  4634.6  425.98  4673.6  425.19  4687.9  425.28  4730.6  424.08  4779.9  422.00
  4794.1  422.51  4851.1  420.83  4872.0  419.72  4879.6  419.92  4911.0  419.31
  4921.3  418.73  4949.8  418.23  4964.0  417.27  4978.3  417.50  4989.5  416.76
  4990.0  415.96  4995.0  415.96  4995.5  416.76  5043.6  416.76  5073.3  417.73
  5078.5  417.61  5106.1  419.31  5123.4  419.72  5128.5  419.49  5145.8  420.40
  5178.5  421.37  5207.1  423.03  5258.1  424.47  5329.6  427.31  5418.4  430.07
#Mann=3,-1,0
  4634.6    0.05       0  4989.5    0.03       0  4995.5    0.05       0
Bank Sta=4911,5106.1
Exp/Cntr=0.3,0.1

Type RM Length L Ch R = 1,3542,211,211,211
BEGIN DESCRIPTION:
Mapping XS 9b21174b
END DESCRIPTION:
XS GIS Cut Line= 3
      2939777.51      6960139.36      2939801.81      6960432.76
      2939978.88      6960878.90
#Sta/Elev= 30
  4704.4  425.12  4790.3  422.47  4830.5  420.79  4850.5  419.73  4854.0  419.30
  4880.6  418.25  4887.7  416.76  4888.2  415.96  4893.2  415.96  4893.7  416.76
  5073.2  416.82  5078.6  417.31  5087.3  417.54  5108.8  417.67  5127.2  417.31
  5141.1  417.56  5178.9  419.30  5186.6  419.99  5194.9  420.19  5210.9  419.83
  5216.4  420.21  5259.4  421.51  5318.9  424.03  5367.0  425.19  5378.3  425.73
  5397.2  426.18  5410.1  426.91  5451.2  427.78  5474.0  428.83  5478.8  428.83
#Mann=3,-1,0
  4704.4    0.05       0  4887.7   0.033       0  4893.7    0.05       0
Bank Sta=4854,5178.9
Exp/Cntr=0.3,0.1

Type RM Length L Ch R = 1,3331,21,21,21
BEGIN DESCRIPTION:
Mapping XS fc0c7cb3
END DESCRIPTION:
XS GIS Cut Line= 5
      2939596.95      6960196.68      2939602.16      6960510.88
      2939616.05      6960641.09      2939647.30      6960689.70
      2939968.44      6960887.60
#Sta/Elev= 30
  4696.4  422.48  4734.7  421.74  4774.7  420.09  4794.7  419.97  4811.9  419.30
  4844.7  417.29  4880.0  417.14  4882.0  416.76  4882.5  415.96  4887.5  415.96
  4888.0  416.76  5024.8  416.77  5082.4  417.48  5087.4  416.76  5105.3  416.77
  5141.0  417.57  5145.2  417.57  5150.5  416.77  5171.7  416.76  5180.9  417.32
  5186.9  416.76  5193.6  417.93  5237.9  417.23  5289.8  419.30  5375.1  421.50
  5427.2  424.32  5463.9  425.13  5506.4  426.96  5521.9  426.90  5576.6  428.88
#Mann=3,-1,0
  4696.4    0.05       0  4882.0    0.03       0  4888.0    0.05       0
Bank Sta=4811.9,5289.8
Exp/Cntr=0.3,0.1

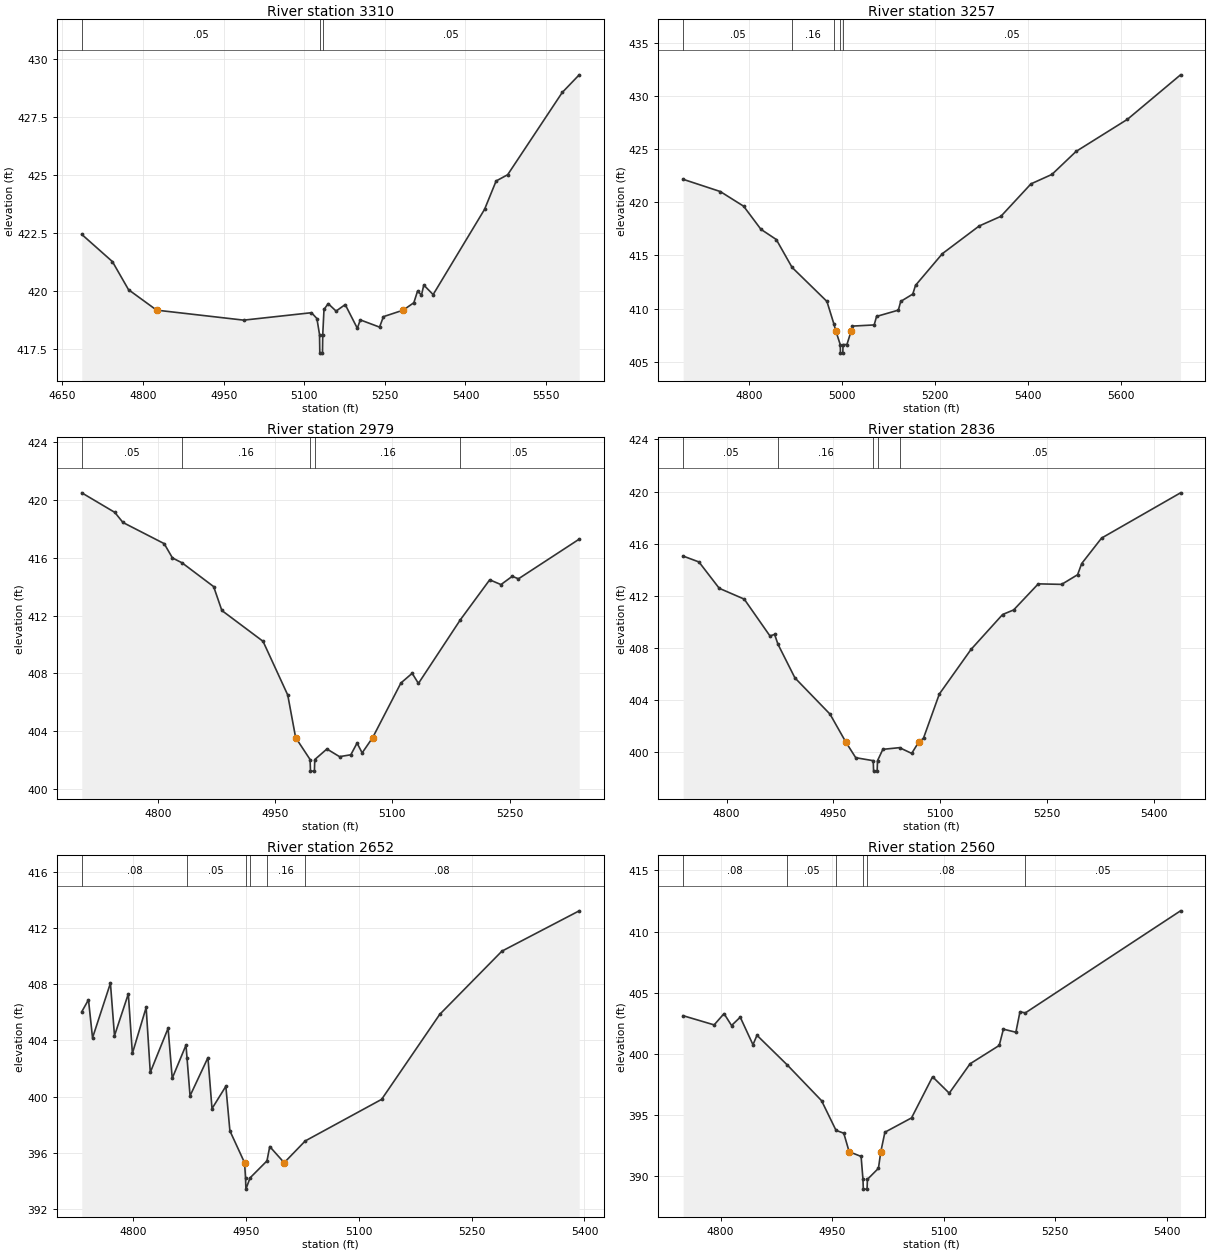
Type RM Length L Ch R = 1,3310,53,53,53
BEGIN DESCRIPTION:
Mapping XS 935bfcff
END DESCRIPTION:
XS GIS Cut Line= 6
      2939579.59      6960188.02      2939576.12      6960431.02
      2939590.01      6960635.88      2939621.26      6960700.12
      2939706.33      6960781.72      2939954.59      6960927.55
#Sta/Elev= 30
  4686.0  422.43  4743.0  421.26  4773.0  420.05  4825.3  419.17  4987.3  418.74
  5113.4  419.06  5123.5  418.81  5128.4  418.12  5128.9  417.32  5133.9  417.32
  5134.4  418.12  5136.7  419.20  5144.5  419.45  5159.2  419.13  5176.2  419.41
  5198.7  418.39  5204.3  418.75  5240.1  418.44  5247.3  418.89  5284.0  419.17
  5303.9  419.49  5310.8  419.99  5318.1  419.82  5322.4  420.25  5339.8  419.84
  5435.5  423.51  5457.0  424.73  5478.5  425.00  5580.0  428.54  5611.6  429.30
#Mann=3,-1,0
  4686.0    0.05       0  5128.4    0.03       0  5134.4    0.05       0
Bank Sta=4825.3,5284
Exp/Cntr=0.3,0.1

Type RM Length L Ch R = 1,3257,278,278,278
BEGIN DESCRIPTION:
Mapping XS f7a938c5
END DESCRIPTION:
XS GIS Cut Line= 5
      2939551.82      6960165.35      2939527.51      6960512.62
      2939553.55      6960648.04      2939657.72      6960814.70
      2939999.73      6960993.52
#Sta/Elev= 30
  4658.8  422.15  4738.6  421.00  4788.8  419.62  4825.9  417.45  4858.9  416.49
  4892.8  413.87  4967.7  410.67  4982.4  408.59  4986.8  407.90  4996.3  406.61
  4996.8  405.81  5001.8  405.81  5002.3  406.61  5010.7  406.62  5019.8  407.90
  5022.4  408.35  5069.2  408.46  5074.3  409.26  5121.1  409.85  5126.2  410.67
  5152.1  411.36  5158.0  412.18  5215.7  415.16  5294.7  417.76  5341.4  418.67
  5406.0  421.72  5451.1  422.61  5502.9  424.77  5613.3  427.79  5727.3  431.97
#Mann=5,-1,0
  4658.8    0.05       0  4892.8    0.16       0  4982.4    0.05       0
  4996.3    0.03       0  5002.3    0.05       0
Bank Sta=4986.8,5019.8
Exp/Cntr=0.3,0.1

Type RM Length L Ch R = 1,2979,143,143,143
BEGIN DESCRIPTION:
UNT 010 IN DRY CR WATERSHED 8.0
END DESCRIPTION:
XS GIS Cut Line= 3
      2939225.00      6960375.00      2939325.00      6960675.00
      2939575.01      6960875.01
#Sta/Elev= 30
  4702.7  420.48  4744.9  419.13  4755.4  418.43  4808.1  416.97  4818.7  415.98
  4831.1  415.64  4871.4  414.00  4881.9  412.35  4934.6  410.22  4966.2  406.51
  4976.3  403.57  4994.8  402.05  4995.3  401.25  5000.3  401.25  5000.8  402.05
  5016.3  402.78  5032.5  402.25  5046.9  402.38  5054.9  403.19  5061.4  402.51
  5074.9  403.57  5111.0  407.34  5125.4  408.01  5133.4  407.31  5187.2  411.72
  5224.6  414.47  5239.0  414.14  5253.4  414.71  5261.4  414.54  5339.1  417.28
#Mann=5,-1,0
  4702.7    0.05       0  4831.1    0.16       0  4994.8    0.07       0
  5000.8    0.16       0  5187.2    0.05       0
Bank Sta=4976.3,5074.9
Exp/Cntr=0.3,0.1

Type RM Length L Ch R = 1,2836,184,184,184
BEGIN DESCRIPTION:
Mapping XS 5e8586e7
END DESCRIPTION:
XS GIS Cut Line= 3
      2939056.47      6960561.99      2939241.34      6960772.89
      2939613.76      6960963.01
#Sta/Elev= 30
  4739.0  415.06  4761.2  414.61  4789.7  412.59  4824.8  411.76  4860.9  408.94
  4867.5  409.05  4872.2  408.30  4896.0  405.72  4945.3  402.94  4967.7  400.78
  4981.4  399.60  5006.0  399.37  5006.5  398.57  5011.5  398.57  5012.0  399.37
  5019.5  400.24  5042.9  400.37  5060.0  399.93  5069.7  400.78  5076.6  401.10
  5098.8  404.48  5143.3  407.90  5187.7  410.58  5203.2  410.93  5237.8  412.93
  5270.6  412.89  5293.0  413.63  5298.8  414.49  5326.7  416.44  5437.6  419.91
#Mann=5,-1,0
  4739.0    0.05       0  4872.2    0.16       0  5006.0    0.07       0
  5012.0    0.16       0  5042.9    0.05       0
Bank Sta=4967.7,5069.7
Exp/Cntr=0.3,0.1

Type RM Length L Ch R = 1,2652,92,92,92
BEGIN DESCRIPTION:
Mapping XS 1541166f
END DESCRIPTION:
XS GIS Cut Line= 3
      2938835.45      6960755.02      2939104.53      6960867.86
      2939446.56      6961008.49
#Sta/Elev= 30
  4731.4  406.04  4740.3  406.89  4745.7  404.18  4769.5  408.07  4774.9  404.33
  4793.3  407.31  4798.7  403.07  4817.0  406.34  4822.5  401.72  4846.2  404.86
  4851.7  401.30  4870.0  403.66  4871.4  402.72  4875.4  400.05  4899.2  402.77
  4904.6  399.14  4923.0  400.73  4928.4  397.56  4947.9  395.29  4949.2  394.21
  4949.7  393.41  4955.2  394.21  4977.7  395.42  4981.4  396.44  5000.6  395.29
  5028.6  396.84  5130.2  399.80  5207.5  405.85  5290.2  410.35  5393.0  413.22
#Mann=6,-1,0
  4731.4    0.08       0  4871.4    0.05       0  4949.2    0.07       0
  4955.2    0.05       0  4977.7    0.16       0  5028.6    0.08       0
Bank Sta=4947.9,5000.6
Exp/Cntr=0.3,0.1

Type RM Length L Ch R = 1,2560,81,81,81
BEGIN DESCRIPTION:
Mapping XS 7761a633
END DESCRIPTION:
XS GIS Cut Line= 3
      2938774.69      6960801.89      2939022.94      6960911.26
      2939378.85      6961088.35
#Sta/Elev= 30
  4749.6  403.13  4791.3  402.38  4804.6  403.30  4814.7  402.33  4826.4  403.01
  4843.5  400.76  4848.9  401.53  4889.4  399.12  4935.7  396.19  4955.2  393.76
  4965.6  393.53  4972.8  392.02  4988.9  391.63  4991.4  389.76  4991.9  388.96
  4996.9  388.96  4997.4  389.76  5012.2  390.66  5015.4  392.02  5020.9  393.61
  5056.7  394.78  5085.0  398.14  5107.4  396.80  5135.4  399.20  5174.6  400.70
  5180.2  402.03  5197.0  401.78  5202.5  403.45  5209.7  403.36  5418.4  411.70
#Mann=6,-1,0
  4749.6    0.08       0  4889.4    0.05       0  4955.2    0.08       0
  4991.4    0.07       0  4997.4    0.08       0  5209.7    0.05       0
Bank Sta=4972.8,5015.4
Exp/Cntr=0.3,0.1

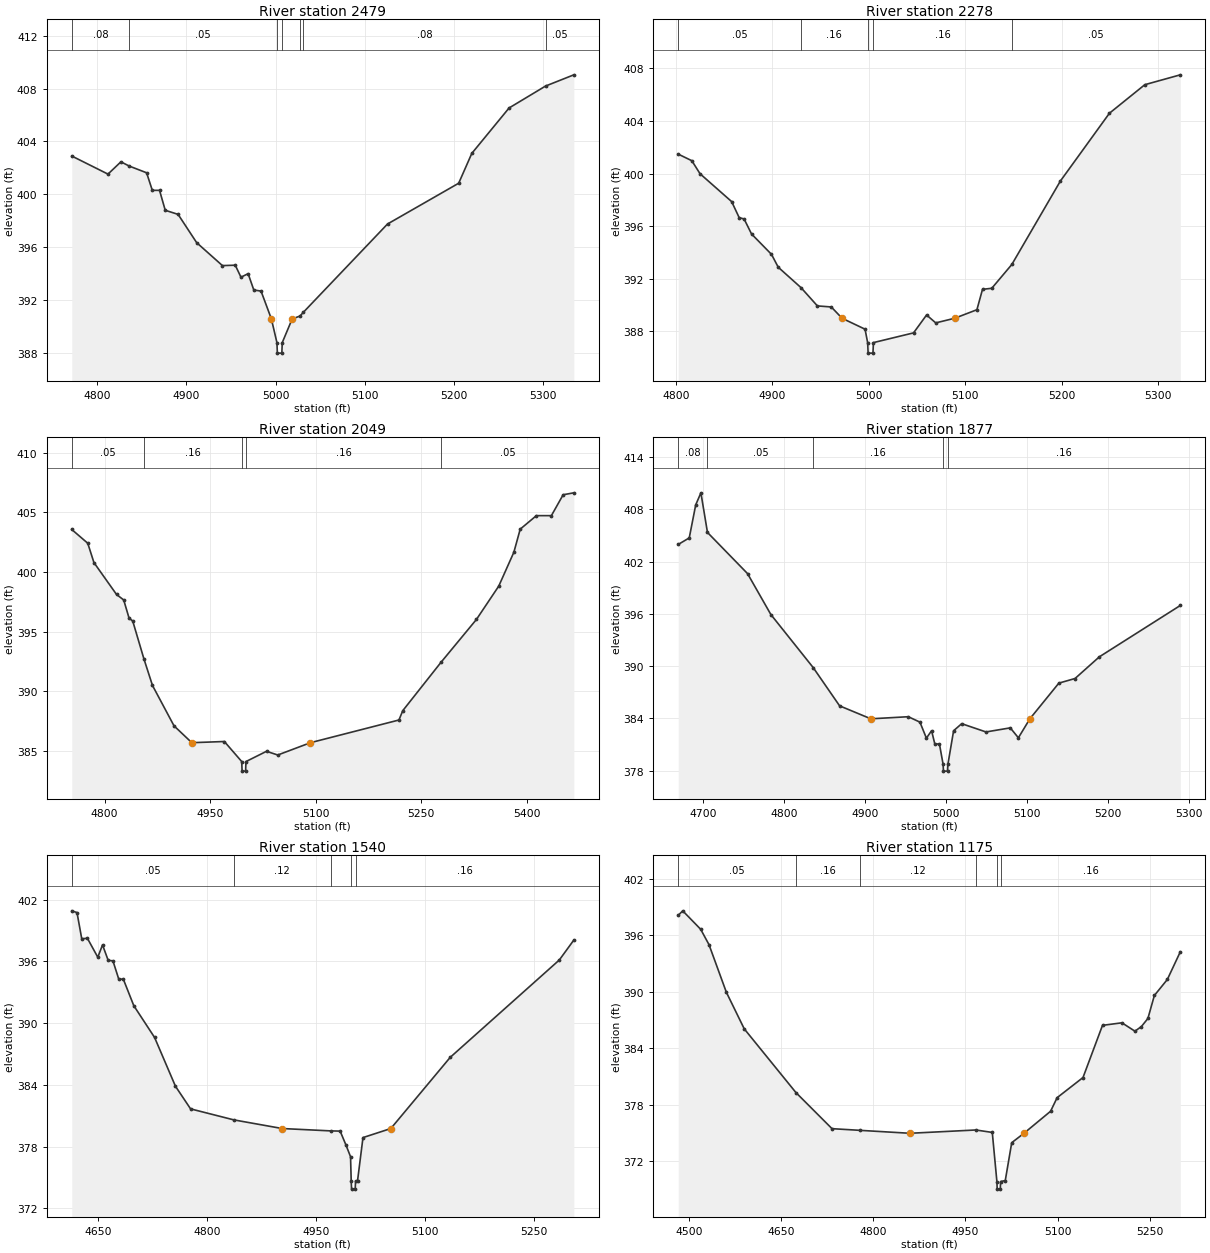
Type RM Length L Ch R = 1,2479,201,201,201
BEGIN DESCRIPTION:
Mapping XS 4f755f8d
END DESCRIPTION:
XS GIS Cut Line= 3
      2938757.35      6960805.39      2938965.64      6960970.29
      2939206.92      6961143.87
#Sta/Elev= 30
  4771.5  402.90  4812.1  401.53  4826.6  402.46  4835.9  402.14  4855.4  401.63
  4861.8  400.30  4869.9  400.30  4876.3  398.79  4890.7  398.48  4911.5  396.34
  4940.4  394.60  4954.8  394.63  4961.2  393.72  4969.2  393.99  4975.6  392.75
  4983.7  392.67  4995.3  390.56  5001.5  388.77  5002.0  387.97  5007.0  387.97
  5007.5  388.77  5018.6  390.56  5027.4  390.78  5031.1  391.06  5125.5  397.75
  5205.3  400.84  5220.0  403.10  5261.8  406.54  5302.7  408.20  5334.4  409.05
#Mann=7,-1,0
  4771.5    0.08       0  4835.9    0.05       0  5001.5    0.03       0
  5007.5    0.05       0  5027.4    0.16       0  5031.1    0.08       0
  5302.7    0.05       0
Bank Sta=4995.3,5018.6
Exp/Cntr=0.3,0.1

Type RM Length L Ch R = 1,2278,229,229,229
BEGIN DESCRIPTION:
Mapping XS e9ce91ab
END DESCRIPTION:
XS GIS Cut Line= 3
      2938703.49      6960831.40      2938752.10      6961018.90
      2939031.04      6961189.36
#Sta/Elev= 30
  4802.5  401.48  4816.6  400.98  4825.1  399.99  4857.9  397.87  4865.7  396.65
  4870.8  396.55  4878.5  395.41  4899.2  393.86  4906.2  392.88  4929.8  391.33
  4946.8  389.94  4961.2  389.86  4972.4  389.00  4996.2  388.17  4998.9  387.15
  4999.4  386.35  5004.4  386.35  5004.9  387.15  5046.5  387.89  5060.0  389.25
  5069.5  388.65  5089.1  389.00  5112.2  389.65  5118.0  391.20  5127.6  391.28
  5148.4  393.09  5198.8  399.44  5249.6  404.59  5286.3  406.76  5323.1  407.51
#Mann=5,-1,0
  4802.5    0.05       0  4929.8    0.16       0  4998.9    0.07       0
  5004.9    0.16       0  5148.4    0.05       0
Bank Sta=4972.4,5089.1
Exp/Cntr=0.3,0.1

Type RM Length L Ch R = 1,2049,172,172,172
BEGIN DESCRIPTION:
UNT 010 IN DRY CR WATERSHED 6.0
END DESCRIPTION:
XS GIS Cut Line= 3
      2938587.17      6960822.74      2938536.75      6961064.13
      2938974.96      6961224.98
#Sta/Elev= 30
  4753.4  403.56  4776.1  402.41  4784.9  400.79  4817.0  398.12  4827.2  397.66
  4834.8  396.14  4840.0  395.90  4855.9  392.73  4868.1  390.50  4898.7  387.12
  4924.0  385.71  4970.2  385.81  4994.9  384.13  4995.4  383.33  5000.4  383.33
  5000.9  384.13  5030.1  384.99  5046.1  384.68  5092.5  385.71  5218.3  387.61
  5223.7  388.39  5277.9  392.43  5328.4  396.03  5360.1  398.82  5381.6  401.66
  5390.6  403.59  5413.6  404.72  5434.9  404.72  5451.6  406.47  5466.8  406.63
#Mann=5,-1,0
  4753.4    0.05       0  4855.9    0.16       0  4994.9    0.07       0
  5000.9    0.16       0  5277.9    0.05       0
Bank Sta=4924,5092.5
Exp/Cntr=0.3,0.1

Type RM Length L Ch R = 1,1877,337,337,337
BEGIN DESCRIPTION:
UNT 010 IN DRY CR WATERSHED 5.0
END DESCRIPTION:
XS GIS Cut Line= 3
      2938574.98      6960775.02      2938375.00      6961025.00
      2938375.00      6961324.97
#Sta/Elev= 30
  4669.4  403.98  4683.0  404.73  4691.0  408.53  4697.4  409.91  4705.5  405.36
  4755.0  400.63  4783.8  395.93  4836.2  389.82  4868.7  385.44  4907.3  383.95
  4953.5  384.19  4967.9  383.57  4975.9  381.73  4982.3  382.58  4986.3  381.06
  4992.0  381.06  4996.5  378.74  4997.0  377.94  5002.0  377.94  5002.5  378.74
  5009.5  382.58  5019.5  383.39  5049.5  382.44  5079.5  382.91  5089.5  381.77
  5103.7  383.95  5139.5  388.05  5159.5  388.58  5189.5  391.07  5289.5  396.97
#Mann=5,-1,0
  4669.4    0.08       0  4705.5    0.05       0  4836.2    0.16       0
  4996.5    0.07       0  5002.5    0.16       0
Bank Sta=4907.3,5103.7
Exp/Cntr=0.3,0.1

Type RM Length L Ch R = 1,1540,365,365,365
BEGIN DESCRIPTION:
UNT 010 IN DRY CR WATERSHED 4.0
END DESCRIPTION:
XS GIS Cut Line= 3
      2938325.02      6960774.98      2938075.00      6961075.00
      2938075.00      6961374.96
#Sta/Elev= 30
  4614.0  400.91  4621.2  400.74  4627.7  398.20  4635.5  398.24  4649.8  396.40
  4656.3  397.60  4664.1  396.09  4670.6  396.05  4678.5  394.30  4685.0  394.25
  4699.3  391.69  4727.9  388.60  4756.6  383.86  4777.4  381.66  4836.9  380.59
  4903.4  379.75  4970.1  379.52  4983.1  379.50  4990.9  378.18  4997.4  377.01
  4998.3  374.66  4998.8  373.86  5003.8  373.86  5004.3  374.66  5007.0  374.66
  5014.5  378.87  5052.8  379.75  5134.5  386.67  5284.5  396.13  5304.5  398.07
#Mann=5,-1,0
  4614.0    0.05       0  4836.9    0.12       0  4970.1    0.16       0
  4998.3    0.07       0  5004.3    0.16       0
Bank Sta=4903.4,5052.8
Exp/Cntr=0.3,0.1

Type RM Length L Ch R = 1,1175,368,368,368
BEGIN DESCRIPTION:
UNT 010 IN DRY CR WATERSHED 3.0
END DESCRIPTION:
XS GIS Cut Line= 3
      2938025.02      6960624.97      2937725.00      6961025.00
      2937825.01      6961325.04
#Sta/Elev= 30
  4483.0  398.11  4490.3  398.59  4519.5  396.63  4533.0  395.00  4561.2  389.95
  4590.3  386.06  4674.4  379.29  4733.0  375.46  4778.9  375.28  4859.7  374.97
  4966.9  375.32  4993.6  375.06  5001.1  369.84  5001.6  369.04  5006.6  369.04
  5007.1  369.84  5014.7  369.95  5025.2  373.97  5045.1  374.97  5088.4  377.31
  5099.0  378.75  5141.1  380.89  5172.8  386.43  5204.4  386.70  5225.5  385.81
  5236.0  386.30  5246.6  387.16  5257.1  389.60  5278.2  391.30  5299.3  394.24
#Mann=6,-1,0
  4483.0    0.05       0  4674.4    0.16       0  4778.9    0.12       0
  4966.9    0.16       0  5001.1    0.07       0  5007.1    0.16       0
Bank Sta=4859.7,5045.1
Exp/Cntr=0.3,0.1

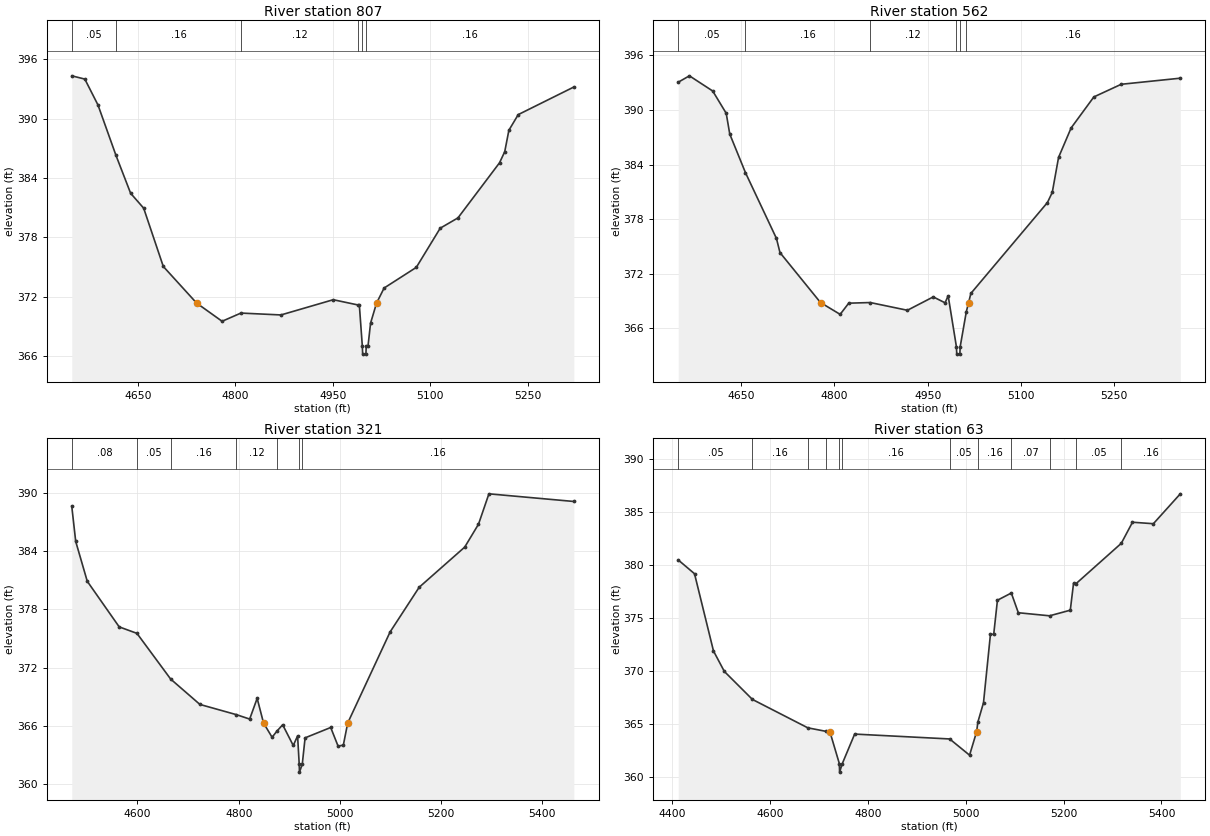
Type RM Length L Ch R = 1,807,245,245,245
BEGIN DESCRIPTION:
UNT 010 IN DRY CR WATERSHED 2.0
END DESCRIPTION:
XS GIS Cut Line= 3
      2937425.00      6960574.99      2937375.00      6961025.00
      2937175.02      6961274.97
#Sta/Elev= 30
  4548.2  394.34  4568.3  394.01  4588.5  391.40  4616.3  386.29  4638.8  382.47
  4658.9  380.96  4689.1  375.07  4740.4  371.37  4779.6  369.53  4808.6  370.36
  4870.2  370.17  4950.7  371.71  4989.5  371.17  4990.9  371.16  4995.5  367.01
  4996.0  366.21  5001.0  366.21  5001.5  367.01  5004.2  367.01  5008.2  369.35
  5017.4  371.37  5029.0  372.89  5078.6  374.98  5115.4  378.94  5142.7  379.98
  5206.7  385.55  5214.7  386.67  5221.1  388.84  5235.5  390.42  5321.1  393.21
#Mann=6,-1,0
  4548.2    0.05       0  4616.3    0.16       0  4808.6    0.12       0
  4989.5    0.16       0  4995.5    0.07       0  5001.5    0.16       0
Bank Sta=4740.4,5017.4
Exp/Cntr=0.3,0.1

Type RM Length L Ch R = 1,562,241,241,241
BEGIN DESCRIPTION:
Mapping XS 496530a8
END DESCRIPTION:
XS GIS Cut Line= 3
      2937389.95      6960526.26      2937194.65      6960871.29
      2937142.56      6961279.31
#Sta/Elev= 30
  4548.6  393.05  4566.6  393.75  4604.1  392.08  4625.8  389.63  4631.5  387.35
  4656.8  383.10  4706.6  375.88  4712.3  374.32  4777.5  368.83  4809.1  367.53
  4822.9  368.76  4857.5  368.83  4917.3  367.98  4958.9  369.45  4977.9  368.80
  4982.9  369.57  4996.2  363.96  4996.7  363.16  5001.7  363.16  5002.2  363.96
  5012.1  367.82  5015.8  368.83  5019.4  369.83  5142.6  379.82  5150.4  380.94
  5160.5  384.78  5180.7  388.02  5217.3  391.43  5261.3  392.82  5356.4  393.49
#Mann=6,-1,0
  4548.6    0.05       0  4656.8    0.16       0  4857.5    0.12       0
  4996.2    0.07       0  5002.2    0.12       0  5012.1    0.16       0
Bank Sta=4777.5,5015.8
Exp/Cntr=0.3,0.1

Type RM Length L Ch R = 1,321,258,258,258
BEGIN DESCRIPTION:
Mapping XS d5c3046a
END DESCRIPTION:
XS GIS Cut Line= 3
      2937240.23      6960378.65      2936962.45      6960769.29
      2937079.62      6961268.38
#Sta/Elev= 30
  4470.2  388.65  4478.0  385.02  4500.8  380.91  4563.9  376.20  4599.0  375.53
  4665.6  370.81  4723.4  368.19  4795.1  367.14  4821.7  366.68  4836.5  368.82
  4849.1  366.27  4866.0  364.80  4875.8  365.45  4886.9  366.09  4907.8  363.95
  4916.4  364.94  4919.6  362.00  4920.1  361.20  4925.6  362.00  4931.2  364.74
  4981.8  365.81  4996.5  363.87  5006.8  364.00  5015.4  366.27  5099.2  375.68
  5156.6  380.29  5246.6  384.44  5273.8  386.80  5294.4  389.94  5462.2  389.15
#Mann=7,-1,0
  4470.2    0.08       0  4599.0    0.05       0  4665.6    0.16       0
  4795.1    0.12       0  4875.8    0.16       0  4919.6    0.07       0
  4925.6    0.16       0
Bank Sta=4849.1,5015.4
Exp/Cntr=0.3,0.1

Type RM Length L Ch R = 1,63,0,0,0
BEGIN DESCRIPTION:
UNT 010 IN DRY CR WATERSHED 1.0
END DESCRIPTION:
XS GIS Cut Line= 3
      2937034.50      6960419.01      2936766.46      6960942.59
      2937054.88      6961273.03
#Sta/Elev= 30
  4411.8  380.50  4445.1  379.20  4483.9  371.91  4506.1  369.98  4563.5  367.34
  4676.8  364.66  4713.7  364.33  4721.9  364.30  4741.3  361.28  4741.8  360.48
  4747.3  361.28  4772.6  364.07  4966.9  363.61  5007.6  362.08  5022.1  364.30
  5024.5  365.19  5036.1  367.03  5050.3  373.48  5057.0  373.49  5064.6  376.70
  5093.0  377.38  5107.3  375.52  5171.2  375.23  5213.6  375.76  5220.2  378.28
  5225.5  378.27  5317.9  382.07  5340.8  384.06  5383.5  383.92  5438.6  386.74
#Mann=12,-1,0
  4411.8    0.05       0  4563.5    0.16       0  4676.8    0.12       0
  4713.7    0.16       0  4741.3    0.03       0  4747.3    0.16       0
  4966.9    0.05       0  5024.5    0.16       0  5093.0    0.07       0
  5171.2    0.16       0  5225.5    0.05       0  5317.9    0.16       0
Bank Sta=4721.9,5022.1
Exp/Cntr=0.3,0.1

Chan Stop Cuts=-1