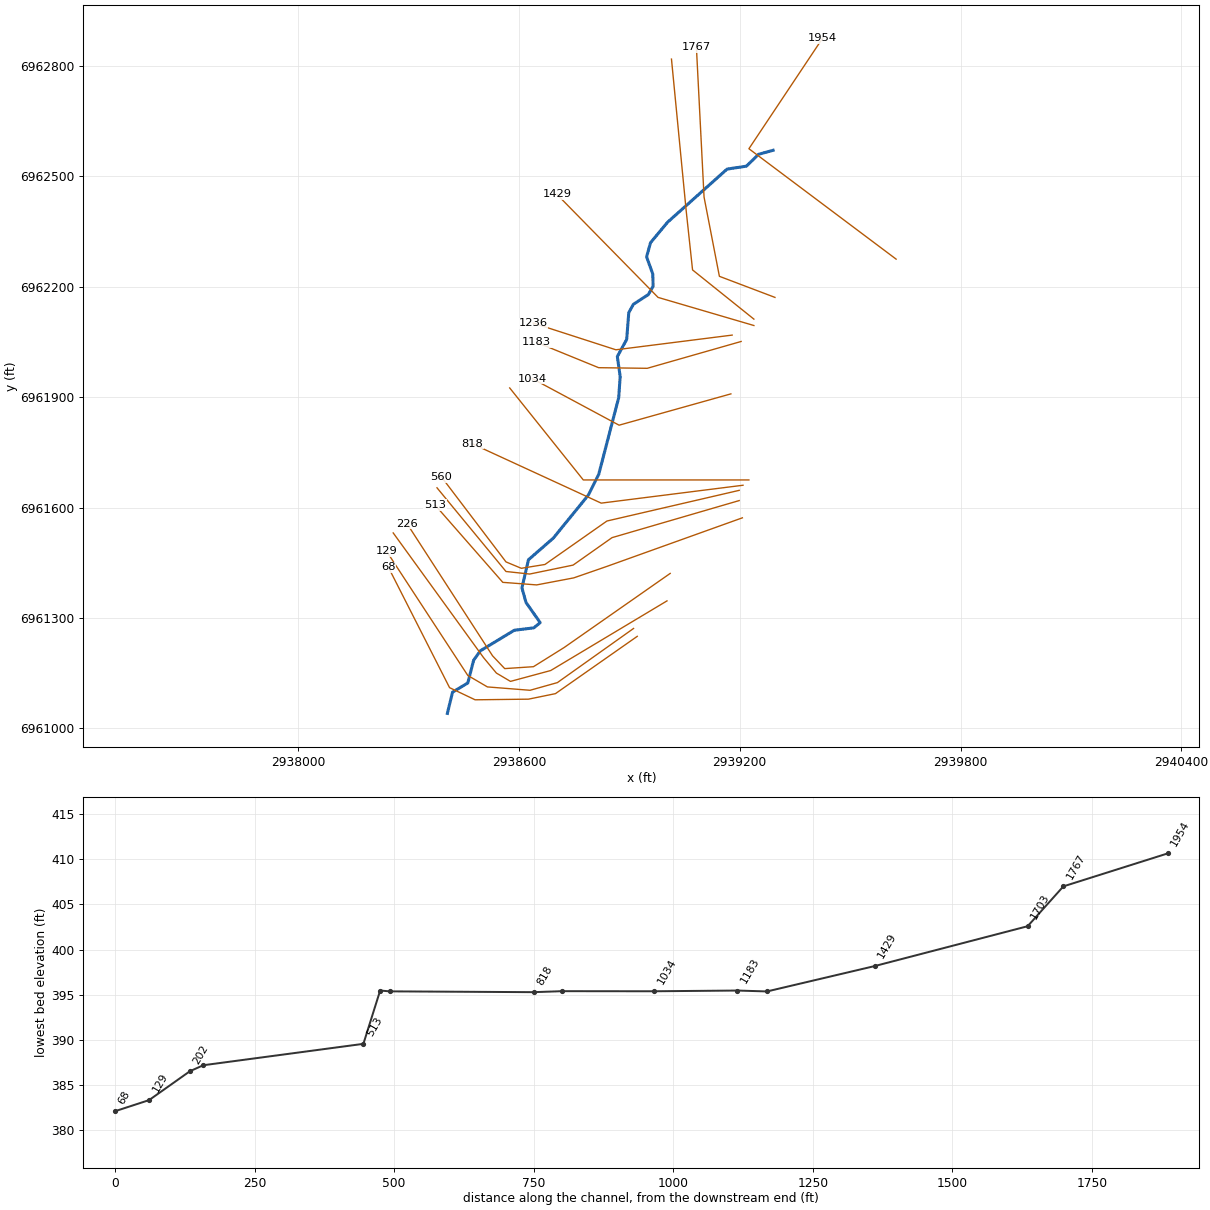
--- UNT 011 IN DRY CR WATERSHED.prj (project) ---

Proj Title=UNT 011 IN DRY CR WATERSHED Base Level Engineering
Current Plan=p01
Default Exp/Contr=0.3,0.1
English Units
Geom File=g01
Flow File=f01
Plan File=p01
BEGIN DESCRIPTION:
UNT 011 IN DRY CR WATERSHED
END DESCRIPTION:

--- UNT 011 IN DRY CR WATERSHED.p01 (plan) ---

Plan Title=Multiple Run
Short Identifier=Multiple
Geom File=g01
Flow File=f01
Subcritical Flow
K Sum by GR= 0
Std Step Tol= 0.01
Critical Tol= 0.01
Num of Std Step Trials= 20
Max Error Tol= 0.3
Flow Tol Ratio= 0.001
Split Flow NTrial= 30
Split Flow Tol= 0.02
Split Flow Ratio= 0.02
Log Output Level= 0
Friction Slope Method= 1
Unsteady Friction Slope Method= 2
Unsteady Bridges Friction Slope Method= 1
Parabolic Critical Depth
Global Vel Dist=  1 , 1 , 1
Global Log Level= 0
CheckData=True
Encroach Param= -1, 0, 0, 0
BEGIN DESCRIPTION:
Multiple Run
END DESCRIPTION:

--- UNT 011 IN DRY CR WATERSHED.f01 (steady flow) ---

Flow Title=Multiple
Program Version=5.07
Number of Profiles= 7
Profile Names=10-year,25-year,50-year,1pct_min,100-year,1pct_plu,500-year
River Rch & RM=UNT 011 IN DRY C,Reach-1         ,1954
     259     333     391     230     458     915     629
Boundary for River Rch & Prof#=UNT 011 IN DRY C,Reach-1         , 1
Up Type= 0
Dn Type= 3
Dn Slope=0.03166
Boundary for River Rch & Prof#=UNT 011 IN DRY C,Reach-1         , 2
Up Type= 0
Dn Type= 3
Dn Slope=0.03166
Boundary for River Rch & Prof#=UNT 011 IN DRY C,Reach-1         , 3
Up Type= 0
Dn Type= 3
Dn Slope=0.03166
Boundary for River Rch & Prof#=UNT 011 IN DRY C,Reach-1         , 4
Up Type= 0
Dn Type= 3
Dn Slope=0.03166
Boundary for River Rch & Prof#=UNT 011 IN DRY C,Reach-1         , 5
Up Type= 0
Dn Type= 3
Dn Slope=0.03166
Boundary for River Rch & Prof#=UNT 011 IN DRY C,Reach-1         , 6
Up Type= 0
Dn Type= 3
Dn Slope=0.03166
Boundary for River Rch & Prof#=UNT 011 IN DRY C,Reach-1         , 7
Up Type= 0
Dn Type= 3
Dn Slope=0.03166
DSS Import GetInterval= 0
DSS Import GetPeak= 0
DSS Import FillOption= 0

--- UNT 011 IN DRY CR WATERSHED.g01 (geometry) ---

Geom Title=Existing Conditions

River Reach=UNT 011 IN DRY C,Reach-1
Reach XY= 30
      2939290.59      6962570.71      2939251.67      6962560.01
      2939217.97      6962527.56      2939165.64      6962519.69
      2939003.93      6962375.31      2938957.68      6962319.71
      2938946.94      6962281.21      2938963.80      6962234.62
      2938964.67      6962201.15      2938951.63      6962178.72
      2938911.01      6962152.24      2938898.55      6962129.59
      2938892.81      6962056.81      2938867.48      6962010.29
      2938875.17      6961955.71      2938871.19      6961898.65
      2938816.94      6961690.32      2938788.72      6961633.89
      2938693.24      6961516.71      2938625.96      6961458.11
      2938608.21      6961381.78      2938619.29      6961342.20
      2938657.85      6961287.21      2938640.48      6961273.10
      2938587.54      6961266.59      2938495.37      6961210.84
      2938477.03      6961185.21      2938461.14      6961123.28
      2938419.69      6961098.33      2938405.59      6961040.71

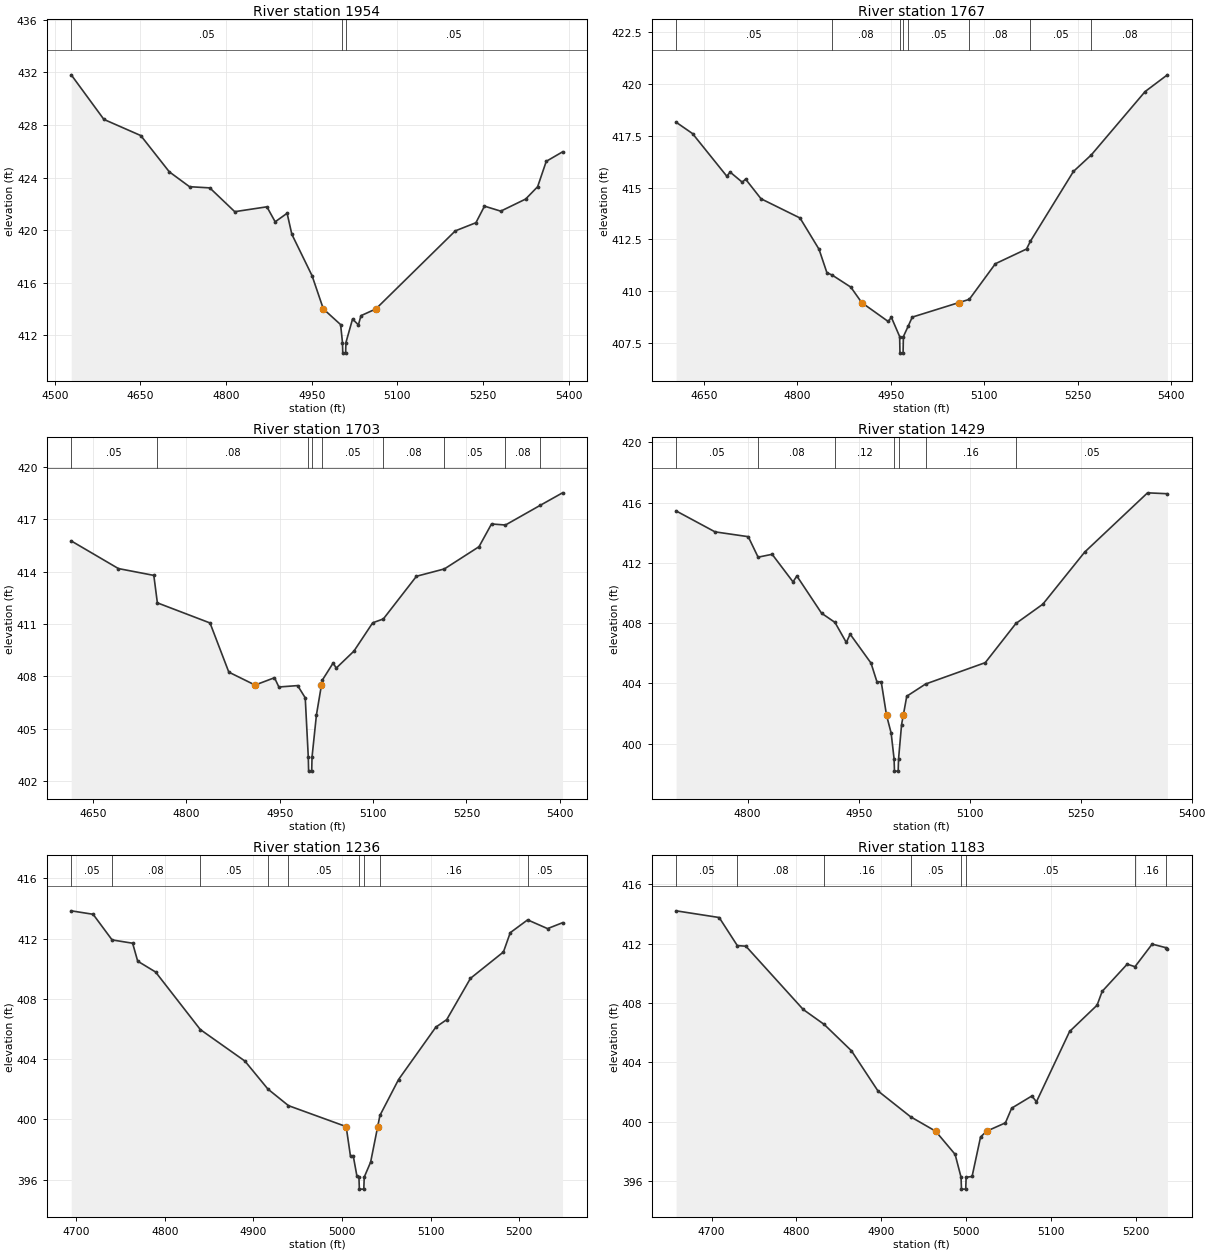
Type RM Length L Ch R = 1,1954,187,187,187
BEGIN DESCRIPTION:
UNT 011 IN DRY CR WATERSHED 5.0
END DESCRIPTION:
XS GIS Cut Line= 3
      2939624.96      6962275.03      2939225.00      6962575.00
      2939425.00      6962874.99
#Sta/Elev= 30
  4528.8  431.82  4586.0  428.43  4650.6  427.20  4700.6  424.44  4736.0  423.31
  4771.5  423.22  4815.2  421.41  4871.5  421.78  4886.0  420.64  4906.9  421.29
  4915.2  419.69  4950.6  416.54  4970.4  414.01  5000.6  412.82  5003.9  411.45
  5004.4  410.65  5009.4  410.65  5009.9  411.45  5021.5  413.24  5031.8  412.80
  5036.3  413.50  5062.3  414.01  5201.5  419.95  5237.6  420.57  5252.6  421.83
  5281.1  421.45  5324.7  422.37  5345.7  423.31  5360.8  425.24  5389.3  425.96
#Mann=3,-1,0
  4528.8    0.05       0  5003.9    0.03       0  5009.9    0.05       0
Bank Sta=4970.4,5062.3
Exp/Cntr=0.3,0.1

Type RM Length L Ch R = 1,1767,64,64,64
BEGIN DESCRIPTION:
Mapping XS 91b6efbc
END DESCRIPTION:
XS GIS Cut Line= 4
      2939295.80      6962171.04      2939144.77      6962228.33
      2939103.11      6962443.61      2939082.31      6962850.78
#Sta/Elev= 30
  4605.3  418.16  4631.7  417.61  4686.7  415.55  4692.0  415.75  4711.5  415.26
  4716.8  415.41  4741.6  414.46  4804.2  413.53  4834.7  412.02  4847.3  410.89
  4855.9  410.77  4885.7  410.19  4903.3  409.44  4945.7  408.53  4950.8  408.73
  4964.1  407.80  4964.6  407.00  4969.6  407.00  4970.1  407.80  4977.9  408.31
  4984.3  408.74  5058.9  409.44  5075.9  409.60  5117.7  411.32  5167.7  412.03
  5173.8  412.40  5243.0  415.78  5271.7  416.58  5358.0  419.64  5393.8  420.45
#Mann=8,-1,0
  4605.3    0.05       0  4855.9    0.08       0  4964.1    0.04       0
  4970.1    0.08       0  4977.9    0.05       0  5075.9    0.08       0
  5173.8    0.05       0  5271.7    0.08       0
Bank Sta=4903.3,5058.9
Exp/Cntr=0.3,0.1

Type RM Length L Ch R = 1,1703,274,274,274
BEGIN DESCRIPTION:
Mapping XS 2d7f03f4
END DESCRIPTION:
XS GIS Cut Line= 4
      2939238.51      6962112.02      2939071.86      6962245.69
      2939054.49      6962407.15      2939014.57      6962818.59
#Sta/Elev= 30
  4615.0  415.75  4690.8  414.17  4747.7  413.78  4753.4  412.21  4838.0  411.06
  4868.2  408.25  4910.4  407.51  4941.6  407.93  4948.6  407.40  4978.8  407.48
  4991.0  406.78  4995.9  403.39  4996.4  402.59  5001.4  402.59  5001.9  403.39
  5009.0  405.81  5017.1  407.52  5018.4  407.79  5035.8  408.77  5040.8  408.48
  5069.2  409.45  5099.4  411.07  5116.5  411.29  5169.7  413.73  5214.6  414.15
  5270.2  415.42  5290.3  416.72  5312.7  416.66  5368.3  417.78  5404.4  418.50
#Mann=9,-1,0
  4615.0    0.05       0  4753.4    0.08       0  4995.9    0.07       0
  5001.9    0.08       0  5018.4    0.05       0  5116.5    0.08       0
  5214.6    0.05       0  5312.7    0.08       0  5368.3    0.05       0
Bank Sta=4910.4,5017.1
Exp/Cntr=0.3,0.1

Type RM Length L Ch R = 1,1429,193,193,193
BEGIN DESCRIPTION:
Mapping XS 6d69b540
END DESCRIPTION:
XS GIS Cut Line= 3
      2939238.52      6962094.65      2938978.11      6962171.04
      2938703.16      6962451.17
#Sta/Elev= 30
  4703.3  415.45  4755.9  414.06  4800.8  413.74  4814.1  412.38  4833.1  412.57
  4861.3  410.74  4866.5  411.13  4899.9  408.66  4918.0  408.05  4933.3  406.72
  4938.5  407.27  4966.7  405.35  4974.7  404.11  4980.5  404.11  4987.7  401.88
  4993.9  400.71  4997.9  398.98  4998.4  398.18  5003.4  398.18  5003.9  398.98
  5008.0  401.27  5010.3  401.88  5015.0  403.15  5040.4  403.96  5121.1  405.38
  5162.5  407.98  5198.9  409.26  5255.5  412.72  5340.4  416.65  5367.2  416.59
#Mann=7,-1,0
  4703.3    0.05       0  4814.1    0.08       0  4918.0    0.12       0
  4997.9    0.07       0  5003.9    0.12       0  5040.4    0.16       0
  5162.5    0.05       0
Bank Sta=4987.7,5010.3
Exp/Cntr=0.3,0.1

Type RM Length L Ch R = 1,1236,53,53,53
BEGIN DESCRIPTION:
Mapping XS 747b2712
END DESCRIPTION:
XS GIS Cut Line= 3
      2939179.46      6962068.60      2938863.52      6962028.67
      2938638.90      6962101.24
#Sta/Elev= 30
  4694.4  413.84  4719.1  413.61  4740.5  411.91  4763.7  411.69  4769.4  410.50
  4789.6  409.78  4840.1  405.96  4890.4  403.87  4916.4  402.01  4939.6  400.91
  5004.7  399.52  5009.6  397.54  5012.8  397.54  5016.9  396.22  5019.1  396.17
  5019.6  395.37  5024.6  395.37  5025.1  396.17  5032.3  397.16  5040.3  399.52
  5042.8  400.26  5063.8  402.64  5105.9  406.12  5118.2  406.62  5145.0  409.36
  5182.2  411.11  5189.9  412.39  5209.5  413.24  5232.0  412.66  5248.9  413.05
#Mann=9,-1,0
  4694.4    0.05       0  4740.5    0.08       0  4840.1    0.05       0
  4916.4    0.16       0  4939.6    0.05       0  5019.1    0.04       0
  5025.1    0.05       0  5042.8    0.16       0  5209.5    0.05       0
Bank Sta=5004.7,5040.3
Exp/Cntr=0.3,0.1

Type RM Length L Ch R = 1,1183,149,149,149
BEGIN DESCRIPTION:
Mapping XS cc3d39ca
END DESCRIPTION:
XS GIS Cut Line= 4
      2939203.82      6962051.25      2938948.59      6961978.33
      2938816.65      6961980.06      2938648.23      6962048.81
#Sta/Elev= 30
  4658.2  414.20  4709.0  413.75  4730.4  411.86  4740.5  411.82  4808.1  407.56
  4832.7  406.56  4865.0  404.78  4896.2  402.08  4934.7  400.34  4964.2  399.37
  4987.2  397.81  4994.2  396.27  4994.7  395.47  4999.7  395.47  5000.2  396.27
  5007.2  396.32  5017.2  398.98  5024.4  399.37  5046.5  399.93  5053.9  400.92
  5077.7  401.74  5083.1  401.35  5122.2  406.08  5154.6  407.85  5160.6  408.78
  5190.1  410.61  5199.3  410.44  5219.5  411.96  5236.4  411.71  5237.5  411.63
#Mann=8,-1,0
  4658.2    0.05       0  4730.4    0.08       0  4832.7    0.16       0
  4934.7    0.05       0  4994.2    0.04       0  5000.2    0.05       0
  5199.3    0.16       0  5236.4    0.05       0
Bank Sta=4964.2,5024.4
Exp/Cntr=0.3,0.1

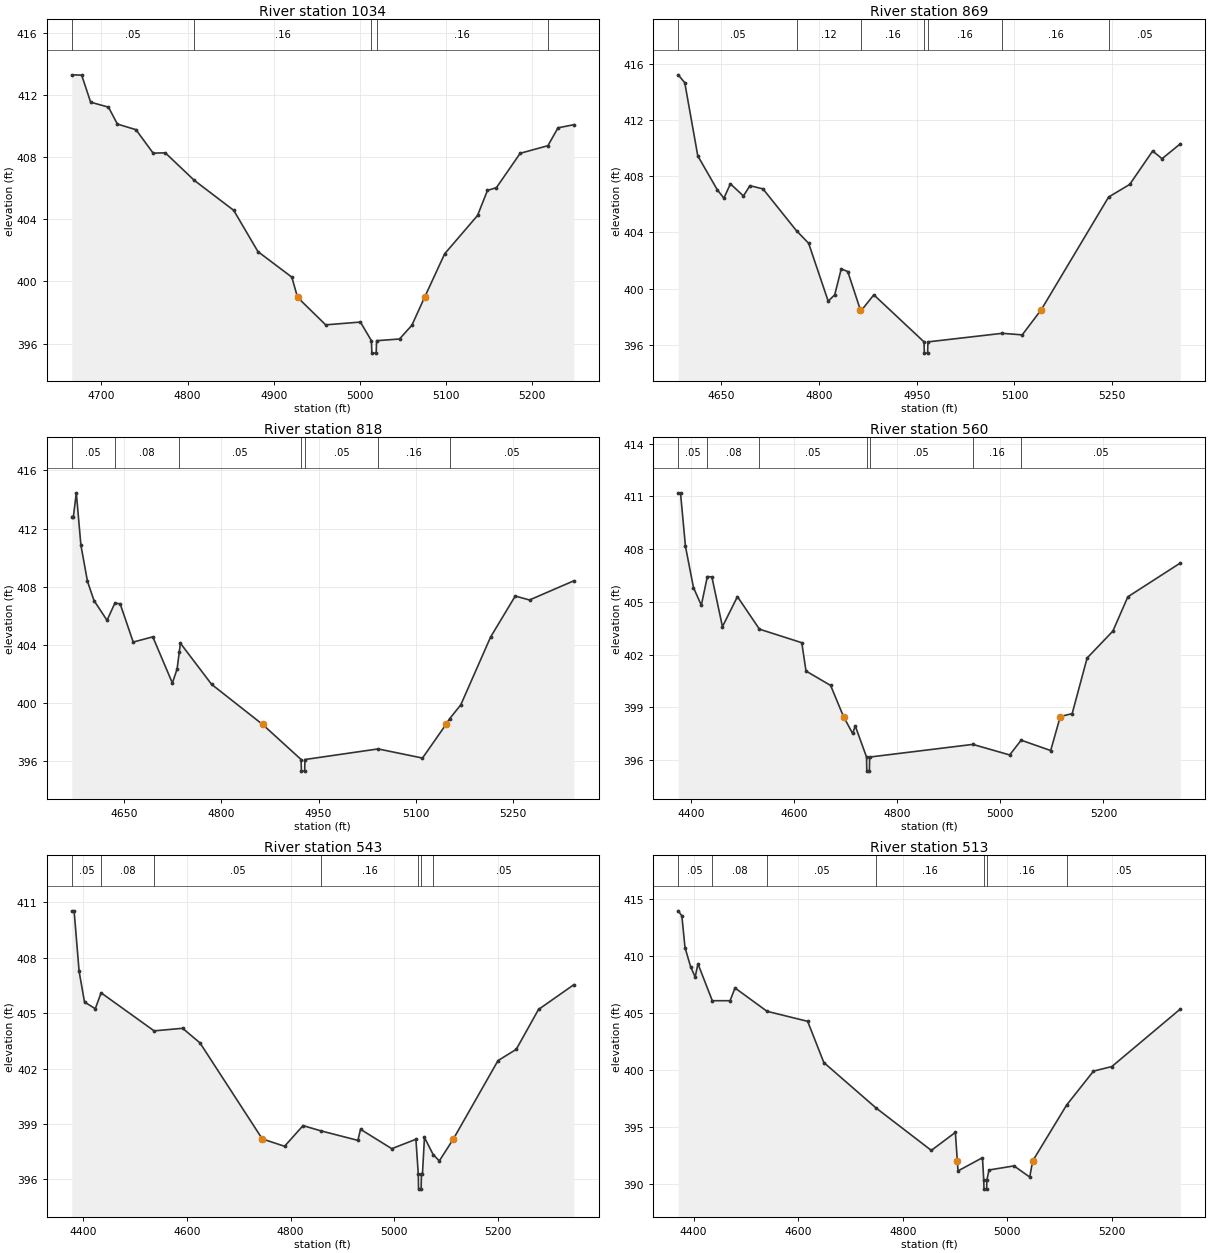
Type RM Length L Ch R = 1,1034,165,165,165
BEGIN DESCRIPTION:
Mapping XS d87a0678
END DESCRIPTION:
XS GIS Cut Line= 3
      2939176.05      6961908.89      2938872.20      6961823.81
      2938636.63      6961950.26
#Sta/Elev= 30
  4665.6  413.30  4677.1  413.28  4687.5  411.54  4708.2  411.22  4718.6  410.13
  4740.1  409.77  4760.1  408.26  4774.2  408.28  4807.8  406.51  4853.6  404.58
  4881.8  401.92  4921.1  400.28  4927.7  398.98  4960.4  397.21  5000.7  397.39
  5013.5  396.19  5014.0  395.39  5019.0  395.39  5019.5  396.19  5046.1  396.30
  5060.4  397.18  5075.2  398.98  5098.5  401.78  5136.7  404.25  5148.2  405.86
  5158.6  406.04  5186.2  408.25  5218.4  408.74  5230.1  409.89  5248.5  410.09
#Mann=5,-1,0
  4665.6    0.05       0  4807.8    0.16       0  5013.5    0.07       0
  5019.5    0.16       0  5218.4    0.05       0
Bank Sta=4927.7,5075.2
Exp/Cntr=0.3,0.1

Type RM Length L Ch R = 1,869,51,51,51
BEGIN DESCRIPTION:
UNT 011 IN DRY CR WATERSHED 2.0
END DESCRIPTION:
XS GIS Cut Line= 3
      2939224.98      6961675.00      2938775.00      6961675.00
      2938575.02      6961924.97
#Sta/Elev= 30
  4584.3  415.21  4594.3  414.65  4614.3  409.44  4644.3  407.02  4654.3  406.43
  4664.3  407.45  4684.3  406.59  4694.3  407.32  4714.3  407.09  4765.7  404.11
  4784.3  403.22  4814.3  399.10  4824.3  399.55  4834.3  401.39  4844.3  401.21
  4863.6  398.49  4864.7  398.41  4884.3  399.55  4961.3  396.20  4961.8  395.40
  4966.8  395.40  4967.3  396.20  5081.2  396.81  5111.9  396.70  5141.1  398.49
  5244.4  406.51  5276.8  407.41  5312.0  409.79  5326.4  409.24  5354.4  410.30
#Mann=7,-1,0
  4584.3    0.05       0  4765.7    0.12       0  4864.7    0.16       0
  4961.3   0.033       0  4967.3    0.16       0  5081.2    0.16       0
  5244.4    0.05       0
Bank Sta=4863.6,5141.1
Exp/Cntr=0.3,0.1

Type RM Length L Ch R = 1,818,258,258,258
BEGIN DESCRIPTION:
Mapping XS 1fcc2bf2
END DESCRIPTION:
XS GIS Cut Line= 3
      2939209.02      6961660.62      2938823.59      6961612.01
      2938472.86      6961773.48
#Sta/Elev= 30
  4569.3  412.82  4571.8  412.82  4576.3  414.46  4583.4  410.85  4593.5  408.37
  4603.6  407.04  4623.7  405.68  4635.7  406.85  4643.9  406.82  4664.1  404.18
  4694.3  404.54  4724.5  401.36  4731.8  402.32  4735.2  403.51  4736.9  404.10
  4785.0  401.27  4863.6  398.51  4923.1  396.09  4923.6  395.29  4928.6  395.29
  4929.1  396.09  5041.9  396.82  5110.4  396.19  5146.7  398.51  5152.1  398.89
  5169.5  399.86  5215.5  404.53  5253.5  407.35  5275.5  407.08  5343.9  408.40
#Mann=7,-1,0
  4569.3    0.05       0  4635.7    0.08       0  4735.2    0.05       0
  4923.1   0.033       0  4929.1    0.05       0  5041.9    0.16       0
  5152.1    0.05       0
Bank Sta=4863.6,5146.7
Exp/Cntr=0.3,0.1

Type RM Length L Ch R = 1,560,17,17,17
BEGIN DESCRIPTION:
Mapping XS 32c0c647
END DESCRIPTION:
XS GIS Cut Line= 6
      2939198.61      6961646.73      2938839.22      6961563.40
      2938670.81      6961445.34      2938606.58      6961434.92
      2938564.91      6961452.29      2938389.77      6961682.91
#Sta/Elev= 30
  4374.7  411.20  4379.1  411.20  4388.7  408.16  4404.3  405.81  4419.5  404.81
  4431.2  406.44  4440.0  406.42  4460.5  403.59  4489.6  405.30  4532.3  403.45
  4614.5  402.68  4622.7  401.07  4670.5  400.25  4695.5  398.48  4713.2  397.52
  4718.3  397.95  4740.2  396.18  4740.7  395.38  4745.7  395.38  4746.2  396.18
  4946.5  396.90  5018.0  396.30  5040.3  397.14  5097.6  396.55  5116.2  398.48
  5139.3  398.65  5168.3  401.81  5218.3  403.34  5247.4  405.29  5349.2  407.21
#Mann=7,-1,0
  4374.7    0.05       0  4431.2    0.08       0  4532.3    0.05       0
  4740.2    0.07       0  4746.2    0.05       0  4946.5    0.16       0
  5040.3    0.05       0
Bank Sta=4695.5,5116.2
Exp/Cntr=0.3,0.1

Type RM Length L Ch R = 1,543,30,30,30
BEGIN DESCRIPTION:
Mapping XS 8f85faf9
END DESCRIPTION:
XS GIS Cut Line= 6
      2939198.61      6961618.96      2938853.11      6961518.26
      2938747.20      6961443.61      2938629.15      6961419.30
      2938564.91      6961426.24      2938377.44      6961653.64
#Sta/Elev= 30
  4377.6  410.54  4382.1  410.54  4391.8  407.26  4402.2  405.60  4423.0  405.24
  4434.2  406.10  4536.6  404.04  4591.6  404.18  4625.1  403.39  4745.4  398.19
  4788.4  397.79  4824.1  398.91  4858.0  398.63  4930.0  398.11  4935.1  398.71
  4995.4  397.66  5042.0  398.17  5046.6  396.27  5047.1  395.47  5052.1  395.47
  5052.6  396.27  5054.6  396.27  5058.5  398.27  5075.3  397.34  5087.2  397.00
  5114.4  398.19  5200.5  402.43  5235.7  403.04  5278.7  405.20  5346.9  406.54
#Mann=7,-1,0
  4377.6    0.05       0  4434.2    0.08       0  4536.6    0.05       0
  4858.0    0.16       0  5046.6    0.07       0  5052.6    0.16       0
  5075.3    0.05       0
Bank Sta=4745.4,5114.4
Exp/Cntr=0.3,0.1

Type RM Length L Ch R = 1,513,287,287,287
BEGIN DESCRIPTION:
Mapping XS 6f160063
END DESCRIPTION:
XS GIS Cut Line= 6
      2939207.26      6961572.07      2938839.22      6961440.13
      2938748.94      6961408.88      2938648.24      6961389.79
      2938556.23      6961396.73      2938372.18      6961606.83
#Sta/Elev= 30
  4370.5  414.00  4377.4  413.56  4383.5  410.77  4394.2  409.09  4402.9  408.19
  4408.2  409.35  4435.7  406.11  4469.7  406.11  4479.1  407.23  4540.4  405.18
  4618.1  404.30  4649.1  400.68  4749.1  396.69  4854.7  392.97  4900.7  394.55
  4904.5  392.04  4905.8  391.17  4952.6  392.33  4955.0  390.37  4955.5  389.57
  4960.5  389.57  4961.0  390.37  4965.1  391.25  5012.9  391.61  5043.0  390.63
  5048.6  392.04  5113.7  396.96  5165.0  399.93  5200.1  400.33  5331.1  405.38
#Mann=7,-1,0
  4370.5    0.05       0  4435.7    0.08       0  4540.4    0.05       0
  4749.1    0.16       0  4955.0    0.07       0  4961.0    0.16       0
  5113.7    0.05       0
Bank Sta=4904.5,5048.6
Exp/Cntr=0.3,0.1

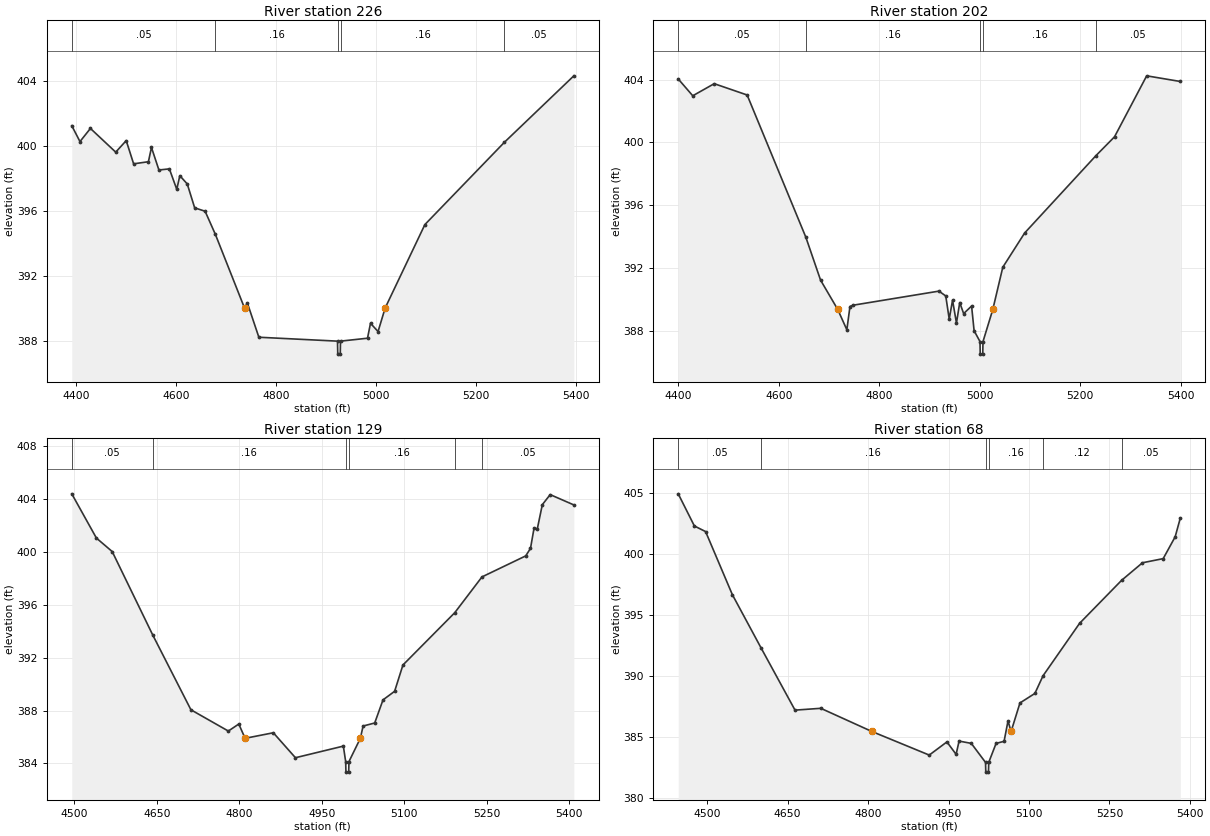
Type RM Length L Ch R = 1,226,24,24,24
BEGIN DESCRIPTION:
Mapping XS b89cc777
END DESCRIPTION:
XS GIS Cut Line= 6
      2939011.10      6961421.04      2938722.90      6961219.65
      2938639.56      6961167.56      2938561.44      6961162.36
      2938528.45      6961197.08      2938295.79      6961556.49
#Sta/Elev= 30
  4392.1  401.27  4408.5  400.29  4429.4  401.10  4480.0  399.64  4501.0  400.35
  4515.8  398.92  4545.4  399.05  4551.5  399.93  4566.4  398.54  4587.3  398.61
  4602.1  397.35  4608.2  398.19  4623.1  397.68  4637.9  396.21  4658.8  396.00
  4679.4  394.57  4737.6  390.04  4743.4  390.34  4766.3  388.24  4923.6  388.00
  4924.1  387.20  4929.1  387.20  4929.6  388.00  4983.6  388.18  4989.6  389.10
  5004.7  388.59  5018.9  390.04  5098.4  395.18  5257.5  400.25  5396.3  404.34
#Mann=5,-1,0
  4392.1    0.05       0  4679.4    0.16       0  4923.6    0.07       0
  4929.6    0.16       0  5257.5    0.05       0
Bank Sta=4737.6,5018.9
Exp/Cntr=0.3,0.1

Type RM Length L Ch R = 1,202,73,73,73
BEGIN DESCRIPTION:
Mapping XS fc5d488d
END DESCRIPTION:
XS GIS Cut Line= 6
      2939002.38      6961346.37      2938686.44      6961157.15
      2938577.06      6961127.63      2938538.87      6961150.20
      2938504.15      6961191.87      2938258.43      6961531.03
#Sta/Elev= 30
  4400.0  404.04  4428.9  402.97  4471.6  403.74  4537.1  403.02  4653.9  393.97
  4683.2  391.24  4717.4  389.37  4735.5  388.08  4741.7  389.56  4747.4  389.64
  4918.8  390.54  4932.3  390.23  4939.2  388.76  4945.8  389.96  4953.6  388.51
  4960.1  389.81  4967.9  389.11  4983.7  389.59  4988.7  388.02  5000.4  387.33
  5000.9  386.53  5005.9  386.53  5006.4  387.33  5025.9  389.37  5045.8  392.06
  5089.3  394.24  5231.1  399.16  5268.1  400.36  5332.1  404.24  5399.0  403.88
#Mann=5,-1,0
  4400.0    0.05       0  4653.9    0.16       0  5000.4    0.07       0
  5006.4    0.16       0  5231.1    0.05       0
Bank Sta=4717.4,5025.9
Exp/Cntr=0.3,0.1

Type RM Length L Ch R = 1,129,61,61,61
BEGIN DESCRIPTION:
Mapping XS f6322613
END DESCRIPTION:
XS GIS Cut Line= 6
      2938911.54      6961271.43      2938704.53      6961124.31
      2938630.31      6961103.47      2938514.42      6961112.59
      2938461.04      6961143.84      2938240.61      6961480.97
#Sta/Elev= 30
  4495.4  404.41  4540.2  401.06  4568.9  400.04  4642.5  393.73  4712.0  388.06
  4780.0  386.45  4799.0  386.98  4810.5  385.90  4861.8  386.32  4902.0  384.43
  4989.1  385.31  4993.3  384.14  4993.8  383.34  4998.8  383.34  4999.3  384.14
  5020.0  385.90  5025.0  386.83  5046.1  387.06  5061.2  388.81  5082.3  389.46
  5097.4  391.45  5191.6  395.41  5241.1  398.12  5320.6  399.71  5329.3  400.28
  5335.7  401.80  5341.7  401.76  5350.8  403.59  5365.1  404.35  5408.1  403.57
#Mann=6,-1,0
  4495.4    0.05       0  4642.5    0.16       0  4993.3    0.07       0
  4999.3    0.16       0  5191.6    0.12       0  5241.1    0.05       0
Bank Sta=4810.5,5020
Exp/Cntr=0.3,0.1

Type RM Length L Ch R = 1,68,0,0,0
BEGIN DESCRIPTION:
UNT 011 IN DRY CR WATERSHED 1.0
END DESCRIPTION:
XS GIS Cut Line= 6
      2938921.58      6961250.03      2938699.32      6961094.36
      2938625.99      6961079.33      2938481.02      6961077.60
      2938411.58      6961110.58      2938245.26      6961437.85
#Sta/Elev= 30
  4446.1  404.96  4476.2  402.32  4497.1  401.86  4547.0  396.68  4600.6  392.30
  4663.8  387.20  4711.8  387.35  4806.9  385.45  4914.0  383.51  4946.9  384.59
  4964.1  383.57  4969.6  384.66  4992.4  384.47  5018.9  382.91  5019.4  382.11
  5024.4  382.11  5024.9  382.91  5038.6  384.47  5053.5  384.64  5060.8  386.31
  5066.6  385.45  5083.1  387.79  5110.9  388.57  5126.1  390.02  5194.3  394.33
  5272.6  397.86  5311.5  399.30  5350.1  399.64  5372.4  401.43  5382.0  402.97
#Mann=6,-1,0
  4446.1    0.05       0  4600.6    0.16       0  5018.9    0.07       0
  5024.9    0.16       0  5126.1    0.12       0  5272.6    0.05       0
Bank Sta=4806.9,5066.6
Exp/Cntr=0.3,0.1

Chan Stop Cuts=-1