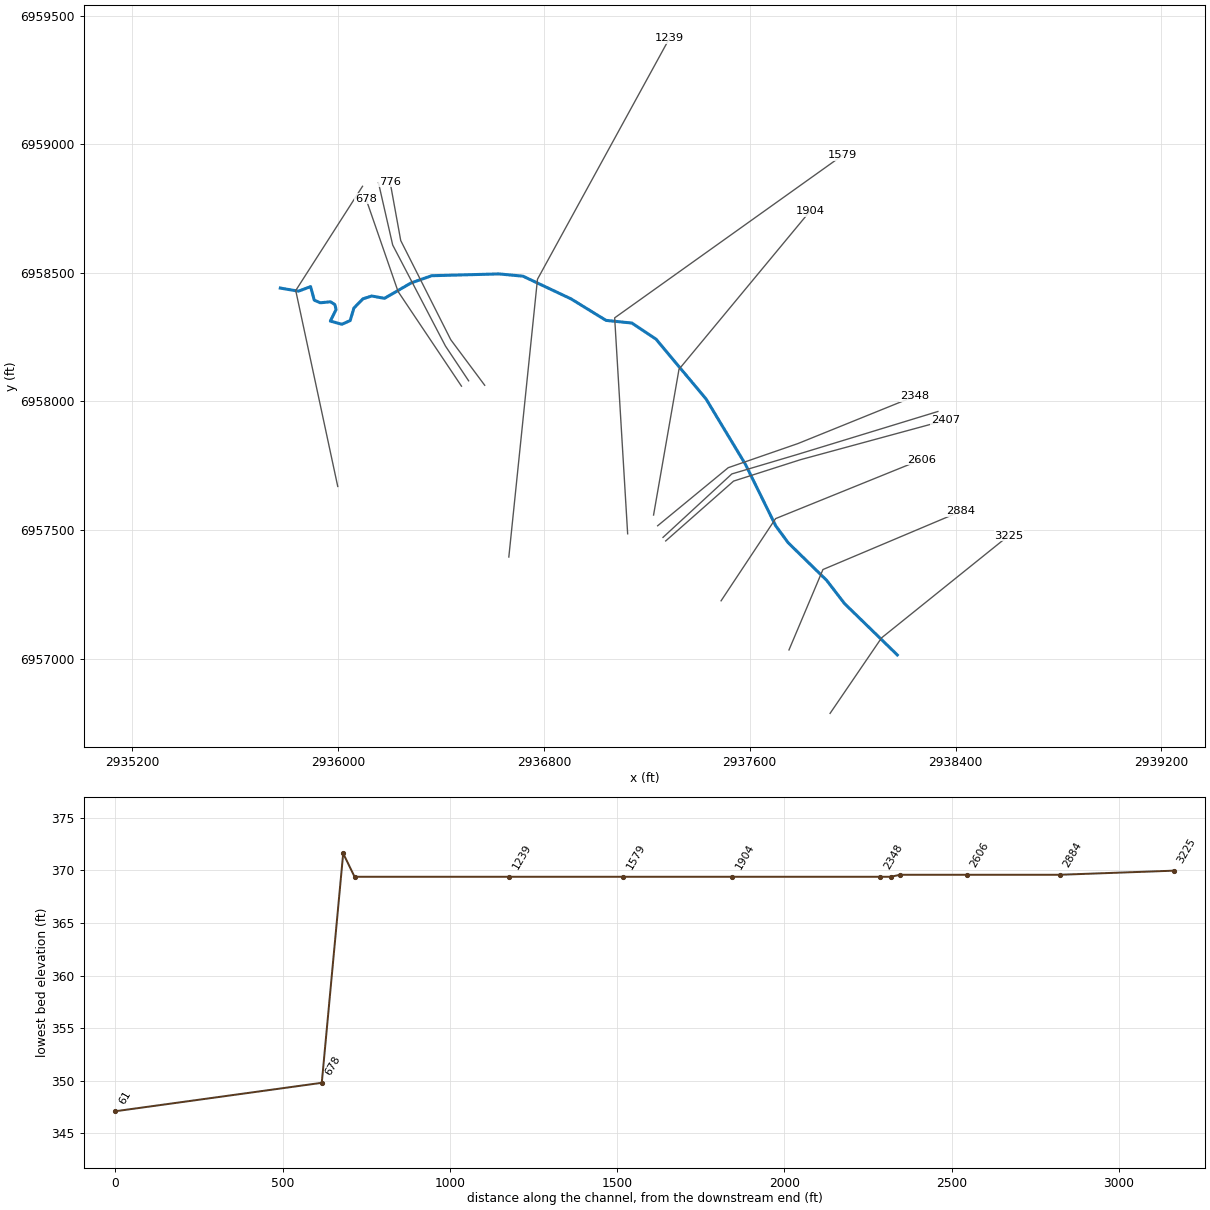
--- UNT 012 IN DRY CR WATERSHED.prj (project) ---

Proj Title=UNT 012 IN DRY CR WATERSHED Base Level Engineering
Current Plan=p01
Default Exp/Contr=0.3,0.1
English Units
Geom File=g01
Flow File=f01
Plan File=p01
BEGIN DESCRIPTION:
UNT 012 IN DRY CR WATERSHED
END DESCRIPTION:

--- UNT 012 IN DRY CR WATERSHED.p01 (plan) ---

Plan Title=Multiple Run
Short Identifier=Multiple
Geom File=g01
Flow File=f01
Subcritical Flow
K Sum by GR= 0
Std Step Tol= 0.01
Critical Tol= 0.01
Num of Std Step Trials= 20
Max Error Tol= 0.3
Flow Tol Ratio= 0.001
Split Flow NTrial= 30
Split Flow Tol= 0.02
Split Flow Ratio= 0.02
Log Output Level= 0
Friction Slope Method= 1
Unsteady Friction Slope Method= 2
Unsteady Bridges Friction Slope Method= 1
Parabolic Critical Depth
Global Vel Dist=  1 , 1 , 1
Global Log Level= 0
CheckData=True
Encroach Param= -1, 0, 0, 0
BEGIN DESCRIPTION:
Multiple Run
END DESCRIPTION:

--- UNT 012 IN DRY CR WATERSHED.f01 (steady flow) ---

Flow Title=Multiple
Number of Profiles=7
Profile Names=10-year,25-year,50-year,1pct_min,100-year,1pct_plu,500-year
River Rch & RM= UNT 012 IN DRY C,Reach-1,3225
     588     790     954     574    1145    2284    1649
River Rch & RM= UNT 012 IN DRY C,Reach-1,742
     638     864    1049     635    1266    2526    1845
Boundary for River Rch & Prof#=UNT 012 IN DRY C,Reach-1,1
Up Type=0
Dn Type=3
Dn Slope=0.005
Boundary for River Rch & Prof#=UNT 012 IN DRY C,Reach-1,2
Up Type=0
Dn Type=3
Dn Slope=0.005
Boundary for River Rch & Prof#=UNT 012 IN DRY C,Reach-1,3
Up Type=0
Dn Type=3
Dn Slope=0.005
Boundary for River Rch & Prof#=UNT 012 IN DRY C,Reach-1,4
Up Type=0
Dn Type=3
Dn Slope=0.005
Boundary for River Rch & Prof#=UNT 012 IN DRY C,Reach-1,5
Up Type=0
Dn Type=3
Dn Slope=0.005
Boundary for River Rch & Prof#=UNT 012 IN DRY C,Reach-1,6
Up Type=0
Dn Type=3
Dn Slope=0.005
Boundary for River Rch & Prof#=UNT 012 IN DRY C,Reach-1,7
Up Type=0
Dn Type=3
Dn Slope=0.005

--- UNT 012 IN DRY CR WATERSHED.g01 (geometry) ---

Geom Title=Existing Conditions

River Reach=UNT 012 IN DRY C,Reach-1
Reach XY= 30
      2938173.53      6957014.86      2937968.41      6957214.48
      2937898.97      6957304.76      2937749.66      6957450.59
      2937701.05      6957516.56      2937582.99      6957756.14
      2937430.22      6958009.62      2937235.77      6958242.26
      2937142.02      6958304.76      2937041.33      6958315.17
      2936905.91      6958398.51      2936718.41      6958487.05
      2936624.66      6958495.73      2936364.24      6958488.78
      2936284.38      6958461.01      2936180.44      6958400.81
      2936130.58      6958409.92      2936096.35      6958398.77
      2936061.50      6958363.05      2936047.08      6958314.58
      2936015.15      6958300.00      2935969.99      6958312.42
      2935992.21      6958357.23      2935987.63      6958376.49
      2935970.53      6958387.42      2935930.92      6958383.60
      2935907.57      6958393.67      2935893.08      6958446.38
      2935845.86      6958428.69      2935775.59      6958440.71

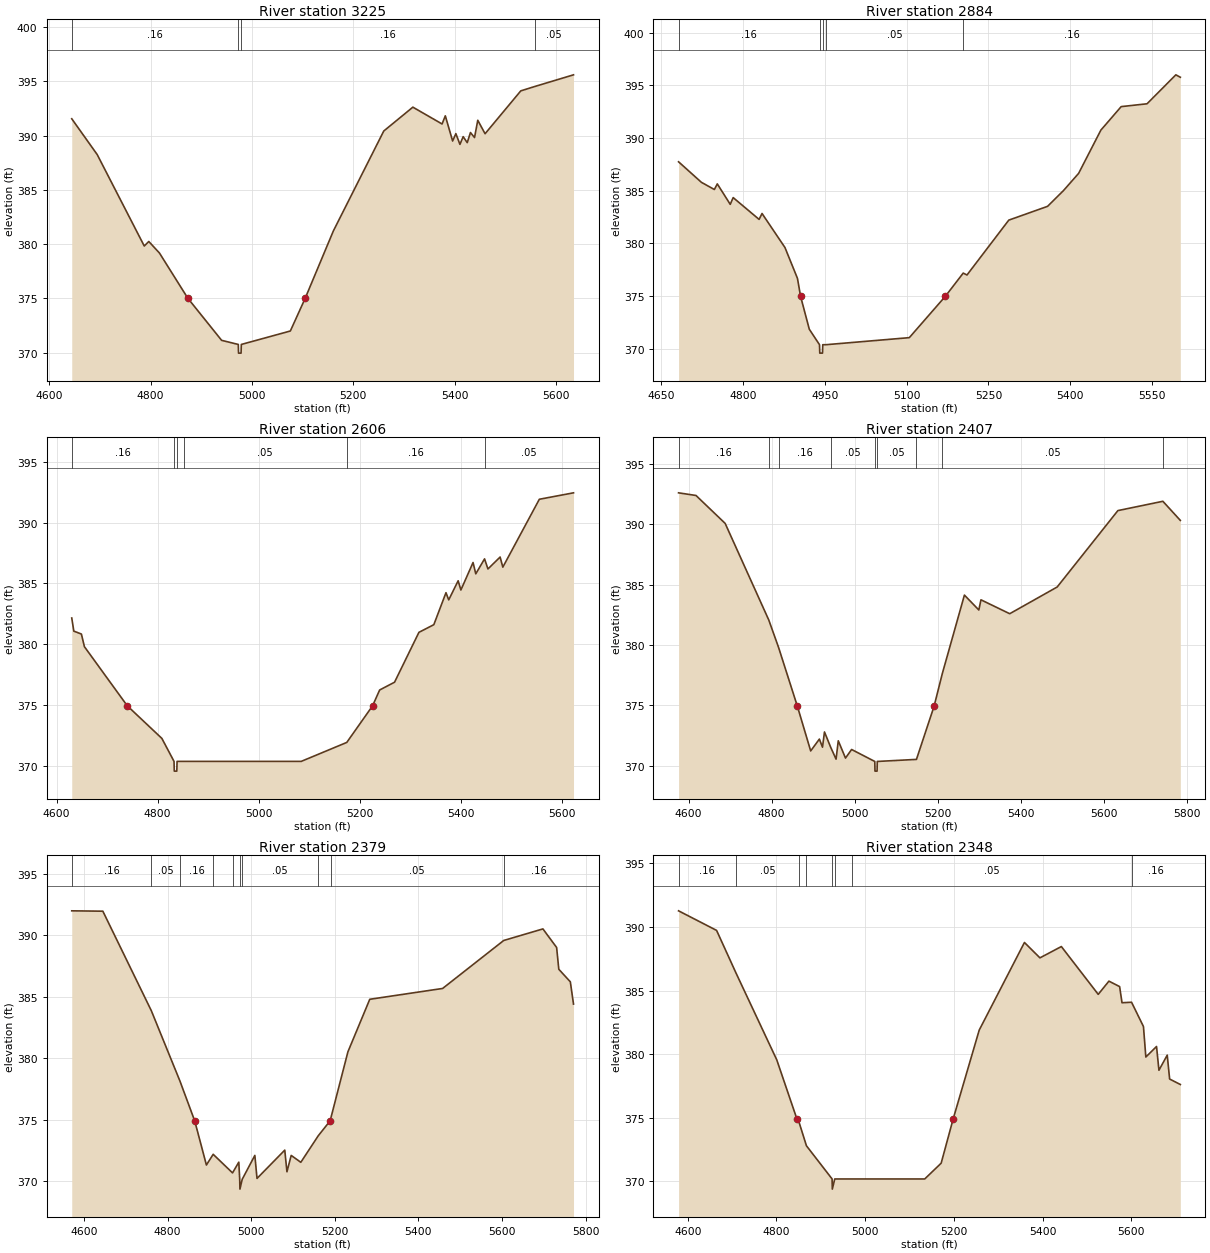
Type RM Length L Ch R = 1,3225,341,341,341
BEGIN DESCRIPTION:
UNT 012 IN DRY CR WATERSHED 8.0
END DESCRIPTION:
XS GIS Cut Line= 3
      2937912.22      6956787.77      2938112.40      6957081.31
      2938606.64      6957478.72
#Sta/Elev= 30
  4644.7  391.56  4694.9  388.26  4787.7  379.83  4796.6  380.25  4817.6  379.19
  4873.6  375.02  4940.2  371.14  4973.1  370.76  4973.6  369.96  4978.6  369.96
  4979.1  370.76  5075.8  372.00  5105.1  375.02  5160.6  381.22  5260.0  390.43
  5317.4  392.63  5375.0  391.08  5381.4  391.83  5395.8  389.51  5402.2  390.19
  5410.2  389.20  5416.6  389.91  5424.6  389.36  5431.0  390.29  5439.0  389.83
  5445.4  391.42  5459.8  390.18  5530.2  394.13  5557.5  394.53  5634.2  395.61
#Mann=4,-1,0
  4644.7    0.16       0  4973.1    0.07       0  4979.1    0.16       0
  5557.5    0.05       0
Bank Sta=4873.6,5105.1
Exp/Cntr=0.3,0.1

Type RM Length L Ch R = 1,2884,278,278,278
BEGIN DESCRIPTION:
Mapping XS 5765d38e
END DESCRIPTION:
XS GIS Cut Line= 3
      2937752.50      6957034.30      2937884.44      6957346.80
      2938419.16      6957572.49
#Sta/Elev= 30
  4682.2  387.74  4724.1  385.79  4747.8  385.11  4753.2  385.64  4776.9  383.70
  4782.3  384.34  4829.8  382.27  4835.2  382.83  4877.2  379.60  4900.1  376.67
  4905.9  374.95  4921.8  371.84  4940.5  370.37  4941.0  369.57  4946.0  369.57
  4946.5  370.37  4952.4  370.37  5105.1  371.04  5170.9  374.95  5203.9  377.17
  5210.8  376.99  5287.4  382.20  5358.5  383.51  5387.7  385.01  5415.4  386.64
  5456.2  390.75  5493.4  392.98  5540.8  393.25  5593.6  396.00  5601.8  395.77
#Mann=5,-1,0
  4682.2    0.16       0  4940.5   0.033       0  4946.5    0.16       0
  4952.4    0.05       0  5203.9    0.16       0
Bank Sta=4905.9,5170.9
Exp/Cntr=0.3,0.1

Type RM Length L Ch R = 1,2606,199,199,199
BEGIN DESCRIPTION:
Mapping XS 349606ed
END DESCRIPTION:
XS GIS Cut Line= 3
      2937488.63      6957225.30      2937700.42      6957544.71
      2938266.43      6957773.90
#Sta/Elev= 30
  4629.9  382.16  4634.0  381.08  4649.0  380.84  4655.0  379.80  4739.9  374.94
  4808.4  372.26  4832.5  370.37  4833.0  369.57  4838.0  369.57  4838.5  370.37
  4851.4  370.37  5084.4  370.37  5174.7  371.93  5225.8  374.94  5239.8  376.24
  5269.3  376.88  5317.6  380.98  5347.1  381.61  5371.2  384.24  5376.6  383.65
  5395.3  385.22  5400.7  384.46  5424.8  386.72  5430.2  385.79  5447.6  387.02
  5454.3  386.19  5478.4  387.17  5483.8  386.34  5556.1  391.92  5623.8  392.45
#Mann=6,-1,0
  4629.9    0.16       0  4832.5   0.033       0  4838.5    0.16       0
  4851.4    0.05       0  5174.7    0.16       0  5447.6    0.05       0
Bank Sta=4739.9,5225.8
Exp/Cntr=0.3,0.1

Type RM Length L Ch R = 1,2407,28,28,28
BEGIN DESCRIPTION:
Mapping XS a5b7add8
END DESCRIPTION:
XS GIS Cut Line= 4
      2937273.36      6957457.94      2937537.22      6957690.55
      2937797.64      6957773.88      2938360.09      6957926.64
#Sta/Elev= 30
  4575.9  392.59  4617.9  392.37  4688.1  390.06  4793.1  382.07  4816.5  379.82
  4862.0  374.93  4894.0  371.24  4914.9  372.22  4922.4  371.55  4927.2  372.81
  4942.2  371.54  4955.1  370.56  4960.4  372.08  4977.8  370.65  4992.5  371.36
  5048.3  370.37  5048.8  369.57  5053.8  369.57  5054.3  370.37  5148.6  370.54
  5191.0  374.93  5210.9  377.64  5264.1  384.13  5298.8  382.90  5303.9  383.74
  5373.2  382.59  5487.4  384.80  5633.6  391.12  5741.9  391.89  5783.9  390.31
#Mann=9,-1,0
  4575.9    0.16       0  4793.1    0.05       0  4816.5    0.16       0
  4942.2    0.05       0  5048.3   0.033       0  5054.3    0.05       0
  5148.6    0.16       0  5210.9    0.05       0  5741.9    0.16       0
Bank Sta=4862,5191
Exp/Cntr=0.3,0.1

Type RM Length L Ch R = 1,2379,31,31,31
BEGIN DESCRIPTION:
Mapping XS 1bd32502
END DESCRIPTION:
XS GIS Cut Line= 4
      2937262.89      6957471.78      2937530.28      6957718.33
      2937787.22      6957794.71      2938331.20      6957961.03
#Sta/Elev= 30
  4570.7  392.00  4645.1  391.97  4761.0  383.89  4829.5  378.17  4865.0  374.92
  4892.9  371.34  4909.1  372.21  4955.4  370.70  4970.4  371.57  4972.6  370.18
  4973.1  369.38  4978.6  370.18  5008.8  372.12  5014.0  370.25  5080.4  372.55
  5085.6  370.79  5095.8  372.12  5118.8  371.56  5160.6  373.72  5188.7  374.92
  5190.0  375.07  5231.5  380.54  5283.8  384.81  5458.1  385.69  5604.3  389.59
  5698.1  390.53  5730.9  389.02  5736.1  387.25  5763.7  386.23  5771.3  384.42
#Mann=10,-1,0
  4570.7    0.16       0  4761.0    0.05       0  4829.5    0.16       0
  4909.1     0.1       0  4955.4    0.05       0  4972.6   0.033       0
  4978.6    0.05       0  5160.6    0.16       0  5190.0    0.05       0
  5604.3    0.16       0
Bank Sta=4865,5188.7
Exp/Cntr=0.3,0.1

Type RM Length L Ch R = 1,2348,444,444,444
BEGIN DESCRIPTION:
Mapping XS 9f4209d0
END DESCRIPTION:
XS GIS Cut Line= 4
      2937242.10      6957516.95      2937516.39      6957742.63
      2937787.22      6957836.38      2938240.53      6958019.78
#Sta/Elev= 30
  4579.4  391.27  4665.1  389.73  4709.1  386.36  4800.7  379.55  4845.8  374.93
  4851.4  374.59  4867.6  372.79  4925.4  370.18  4925.9  369.38  4931.4  370.18
  4969.8  370.18  5134.2  370.18  5171.2  371.42  5198.5  374.93  5257.0  381.89
  5358.9  388.78  5393.8  387.57  5442.1  388.46  5525.2  384.70  5549.3  385.74
  5573.4  385.31  5578.8  384.04  5600.3  384.08  5627.1  382.17  5632.5  379.77
  5656.6  380.60  5662.0  378.73  5680.7  379.92  5686.1  378.04  5710.2  377.61
#Mann=8,-1,0
  4579.4    0.16       0  4709.1    0.05       0  4851.4    0.16       0
  4867.6     0.1       0  4925.4   0.033       0  4931.4     0.1       0
  4969.8    0.05       0  5600.3    0.16       0
Bank Sta=4845.8,5198.5
Exp/Cntr=0.3,0.1

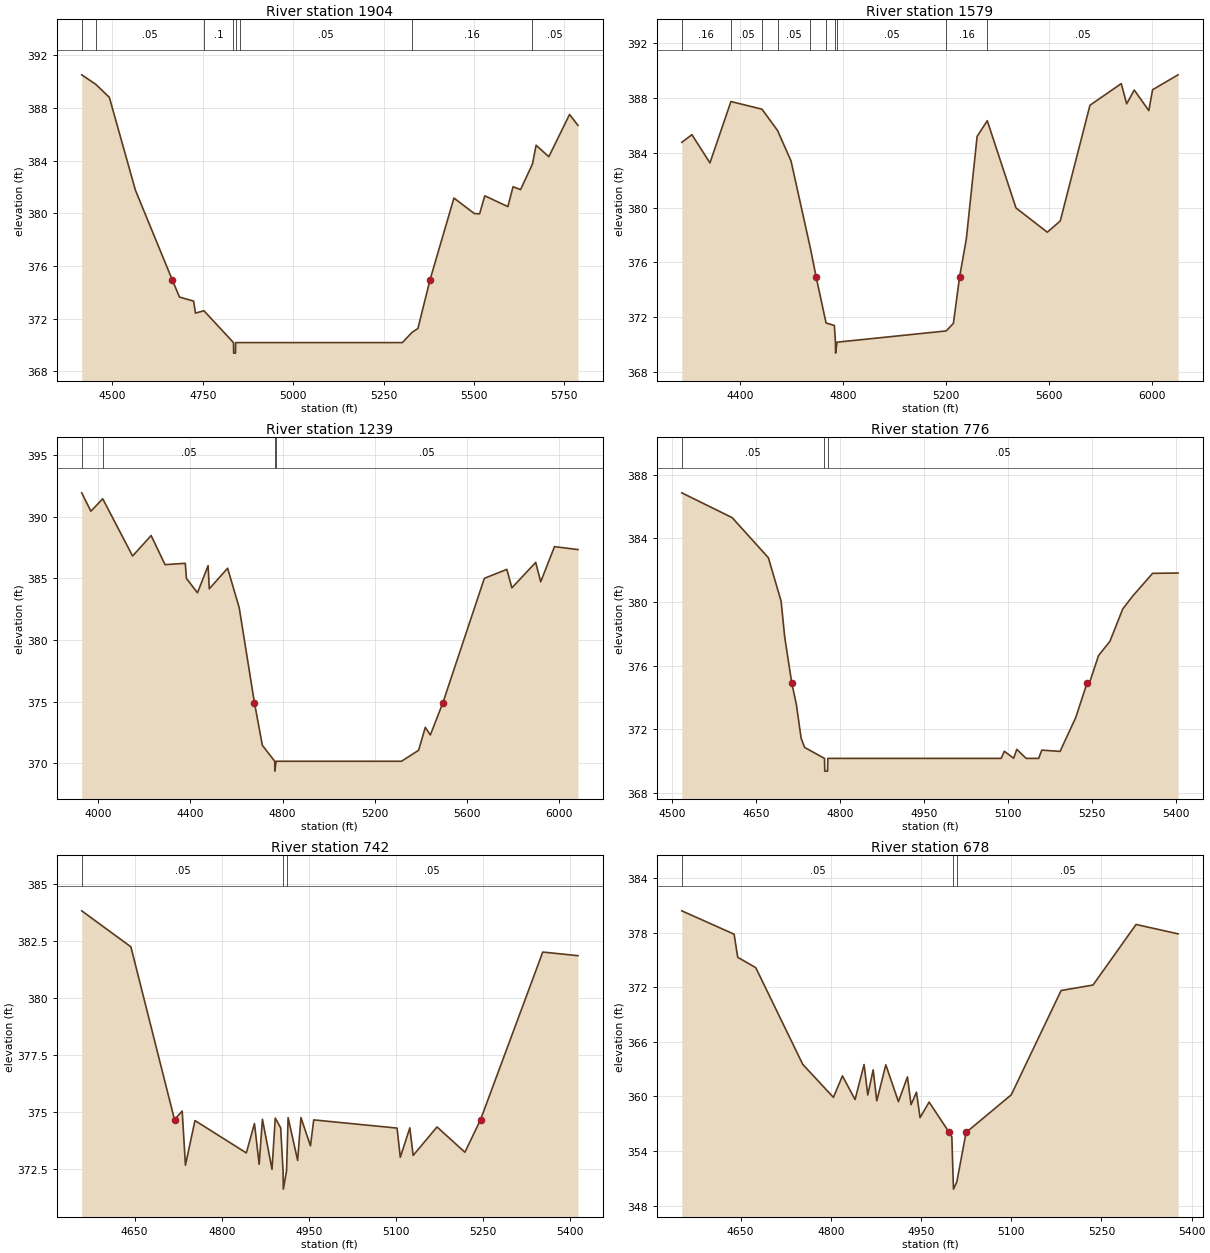
Type RM Length L Ch R = 1,1904,325,325,325
BEGIN DESCRIPTION:
UNT 012 IN DRY CR WATERSHED 5.0
END DESCRIPTION:
XS GIS Cut Line= 3
      2937226.17      6957558.63      2937325.00      6958125.00
      2937833.82      6958739.18
#Sta/Elev= 30
  4415.1  390.52  4453.9  389.80  4491.5  388.81  4563.7  381.75  4665.9  374.92
  4685.5  373.64  4724.6  373.33  4729.7  372.42  4753.1  372.60  4834.8  370.18
  4835.3  369.38  4840.3  369.38  4840.8  370.18  4852.9  370.18  5301.9  370.18
  5328.8  370.96  5344.9  371.25  5378.1  374.92  5444.5  381.16  5501.2  379.98
  5515.5  379.96  5529.9  381.33  5593.7  380.51  5608.0  382.02  5628.8  381.80
  5661.6  383.74  5671.8  385.17  5707.0  384.30  5764.3  387.51  5787.6  386.68
#Mann=8,-1,0
  4415.1    0.16       0  4453.9    0.05       0  4753.1     0.1       0
  4834.8   0.033       0  4840.8     0.1       0  4852.9    0.05       0
  5328.8    0.16       0  5661.6    0.05       0
Bank Sta=4665.9,5378.1
Exp/Cntr=0.3,0.1

Type RM Length L Ch R = 1,1579,340,340,340
BEGIN DESCRIPTION:
UNT 012 IN DRY CR WATERSHED 4.0
END DESCRIPTION:
XS GIS Cut Line= 3
      2937125.47      6957485.70      2937075.00      6958325.00
      2937961.14      6958957.10
#Sta/Elev= 30
  4172.6  384.77  4212.0  385.33  4282.1  383.27  4363.6  387.75  4484.4  387.19
  4545.1  385.63  4597.3  383.41  4672.9  377.01  4695.2  374.92  4733.5  371.58
  4765.8  371.40  4770.0  370.18  4770.5  369.38  4776.0  370.18  5200.5  371.00
  5228.5  371.55  5252.4  374.92  5278.9  377.73  5320.7  385.20  5360.2  386.35
  5471.9  379.98  5593.6  378.21  5644.0  379.03  5759.5  387.48  5881.2  389.06
  5902.1  387.58  5931.6  388.59  5988.2  387.09  6002.9  388.61  6101.9  389.70
#Mann=10,-1,0
  4172.6    0.16       0  4363.6    0.05       0  4484.4    0.16       0
  4545.1    0.05       0  4672.9     0.1       0  4733.5    0.05       0
  4770.0   0.033       0  4776.0    0.05       0  5200.5    0.16       0
  5360.2    0.05       0
Bank Sta=4695.2,5252.4
Exp/Cntr=0.3,0.1

Type RM Length L Ch R = 1,1239,463,463,463
BEGIN DESCRIPTION:
UNT 012 IN DRY CR WATERSHED 3.0
END DESCRIPTION:
XS GIS Cut Line= 3
      2936663.67      6957395.46      2936775.00      6958475.00
      2937287.90      6959411.36
#Sta/Elev= 30
  3928.8  391.93  3968.6  390.44  4019.8  391.45  4149.5  386.81  4229.9  388.47
  4290.3  386.11  4378.1  386.22  4383.1  384.99  4431.0  383.83  4477.1  386.03
  4482.1  384.15  4561.7  385.82  4611.9  382.63  4678.1  374.92  4712.5  371.47
  4766.1  370.18  4766.6  369.38  4772.1  370.18  5316.1  370.18  5390.3  371.07
  5419.4  372.93  5441.2  372.31  5495.6  374.92  5675.4  385.00  5773.1  385.73
  5794.9  384.23  5898.2  386.29  5920.0  384.72  5979.8  387.57  6081.7  387.33
#Mann=4,-1,0
  3928.8    0.16       0  4019.8    0.05       0  4766.1   0.033       0
  4772.1    0.05       0
Bank Sta=4678.1,5495.6
Exp/Cntr=0.3,0.1

Type RM Length L Ch R = 1,776,34,34,34
BEGIN DESCRIPTION:
Mapping XS ad502857
END DESCRIPTION:
XS GIS Cut Line= 4
      2936569.92      6958062.94      2936437.97      6958240.03
      2936243.53      6958625.44      2936201.87      6958854.56
#Sta/Elev= 30
  4517.7  386.87  4607.6  385.31  4672.2  382.79  4694.9  380.06  4701.4  377.78
  4714.0  374.91  4722.2  373.55  4730.6  371.45  4736.8  370.87  4772.3  370.18
  4772.8  369.38  4777.8  369.38  4778.3  370.18  5087.5  370.18  5093.1  370.63
  5109.8  370.19  5115.4  370.75  5132.1  370.18  5154.4  370.18  5160.0  370.70
  5192.6  370.62  5220.6  372.75  5240.7  374.91  5245.9  375.01  5261.2  376.64
  5281.6  377.54  5304.4  379.57  5322.2  380.38  5357.7  381.81  5403.1  381.83
#Mann=3,-1,0
  4517.7    0.05       0  4772.3    0.03       0  4778.3    0.05       0
Bank Sta=4714,5240.7
Exp/Cntr=0.3,0.1

Type RM Length L Ch R = 1,742,64,64,64
BEGIN DESCRIPTION:
Mapping XS 46d16f92
END DESCRIPTION:
XS GIS Cut Line= 4
      2936507.41      6958080.32      2936417.14      6958215.72
      2936212.28      6958608.08      2936156.85      6958850.57
#Sta/Elev= 30
  4559.0  383.82  4643.6  382.24  4718.7  374.65  4731.9  375.03  4737.5  372.65
  4753.9  374.61  4842.3  373.19  4856.3  374.48  4864.4  372.69  4870.0  374.67
  4886.5  372.47  4892.1  374.72  4901.4  374.29  4905.5  372.40  4906.0  371.60
  4911.5  372.40  4914.2  374.74  4930.6  372.86  4936.3  374.74  4952.7  373.50
  4958.3  374.64  5101.7  374.28  5107.3  373.00  5123.7  374.29  5129.4  373.08
  5170.5  374.33  5218.5  373.22  5245.4  374.65  5352.5  382.01  5413.1  381.85
#Mann=3,-1,0
  4559.0    0.05       0  4905.5    0.03       0  4911.5    0.05       0
Bank Sta=4718.7,5245.4
Exp/Cntr=0.3,0.1

Type RM Length L Ch R = 1,678,617,617,617
BEGIN DESCRIPTION:
Mapping XS bec5bc17
END DESCRIPTION:
XS GIS Cut Line= 3
      2936479.62      6958059.50      2936233.11      6958427.53
      2936108.11      6958788.65
#Sta/Elev= 30
  4552.3  380.41  4639.3  377.84  4645.3  375.30  4675.3  374.16  4753.4  363.53
  4804.4  359.90  4819.4  362.26  4840.4  359.66  4855.4  363.51  4861.5  360.16
  4870.5  362.92  4876.5  359.51  4891.5  363.48  4912.5  359.43  4927.5  362.15
  4933.5  359.09  4942.5  360.47  4948.5  357.67  4963.5  359.38  4997.0  356.04
  5001.3  355.56  5003.6  350.61  5004.1  349.81  5009.6  350.61  5025.0  356.04
  5100.1  360.18  5183.0  371.65  5236.0  372.25  5307.6  378.91  5377.4  377.88
#Mann=3,-1,0
  4552.3    0.05       0  5003.6    0.03       0  5009.6    0.05       0
Bank Sta=4997,5025
Exp/Cntr=0.3,0.1

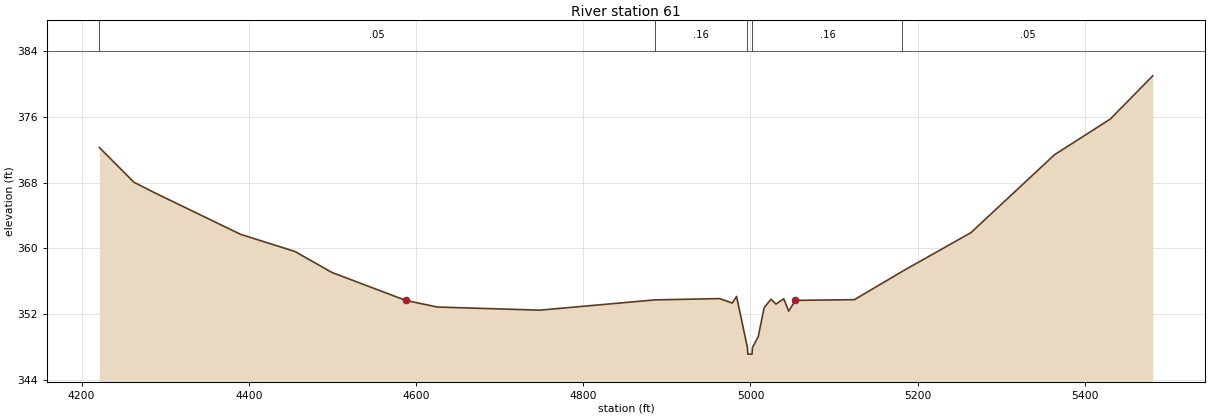
Type RM Length L Ch R = 1,61,0,0,0
BEGIN DESCRIPTION:
UNT 012 IN DRY CR WATERSHED 1.0
END DESCRIPTION:
XS GIS Cut Line= 3
      2935998.73      6957669.73      2935835.45      6958431.22
      2936095.09      6958836.37
#Sta/Elev= 30
  4221.2  372.30  4262.6  368.06  4287.9  366.75  4390.2  361.71  4455.2  359.62
  4499.5  357.06  4587.7  353.66  4625.5  352.85  4748.2  352.47  4885.7  353.72
  4963.0  353.88  4978.3  353.34  4983.4  354.14  4996.4  347.91  4996.9  347.11
  5001.9  347.11  5002.4  347.91  5009.4  349.26  5016.4  352.78  5024.6  353.80
  5030.6  353.21  5039.8  353.86  5045.8  352.36  5053.7  353.66  5124.4  353.75
  5181.7  357.20  5263.9  361.93  5363.7  371.41  5430.4  375.76  5481.2  381.03
#Mann=5,-1,0
  4221.2    0.05       0  4885.7    0.16       0  4996.4    0.07       0
  5002.4    0.16       0  5181.7    0.05       0
Bank Sta=4587.7,5053.7
Exp/Cntr=0.3,0.1

Chan Stop Cuts=-1