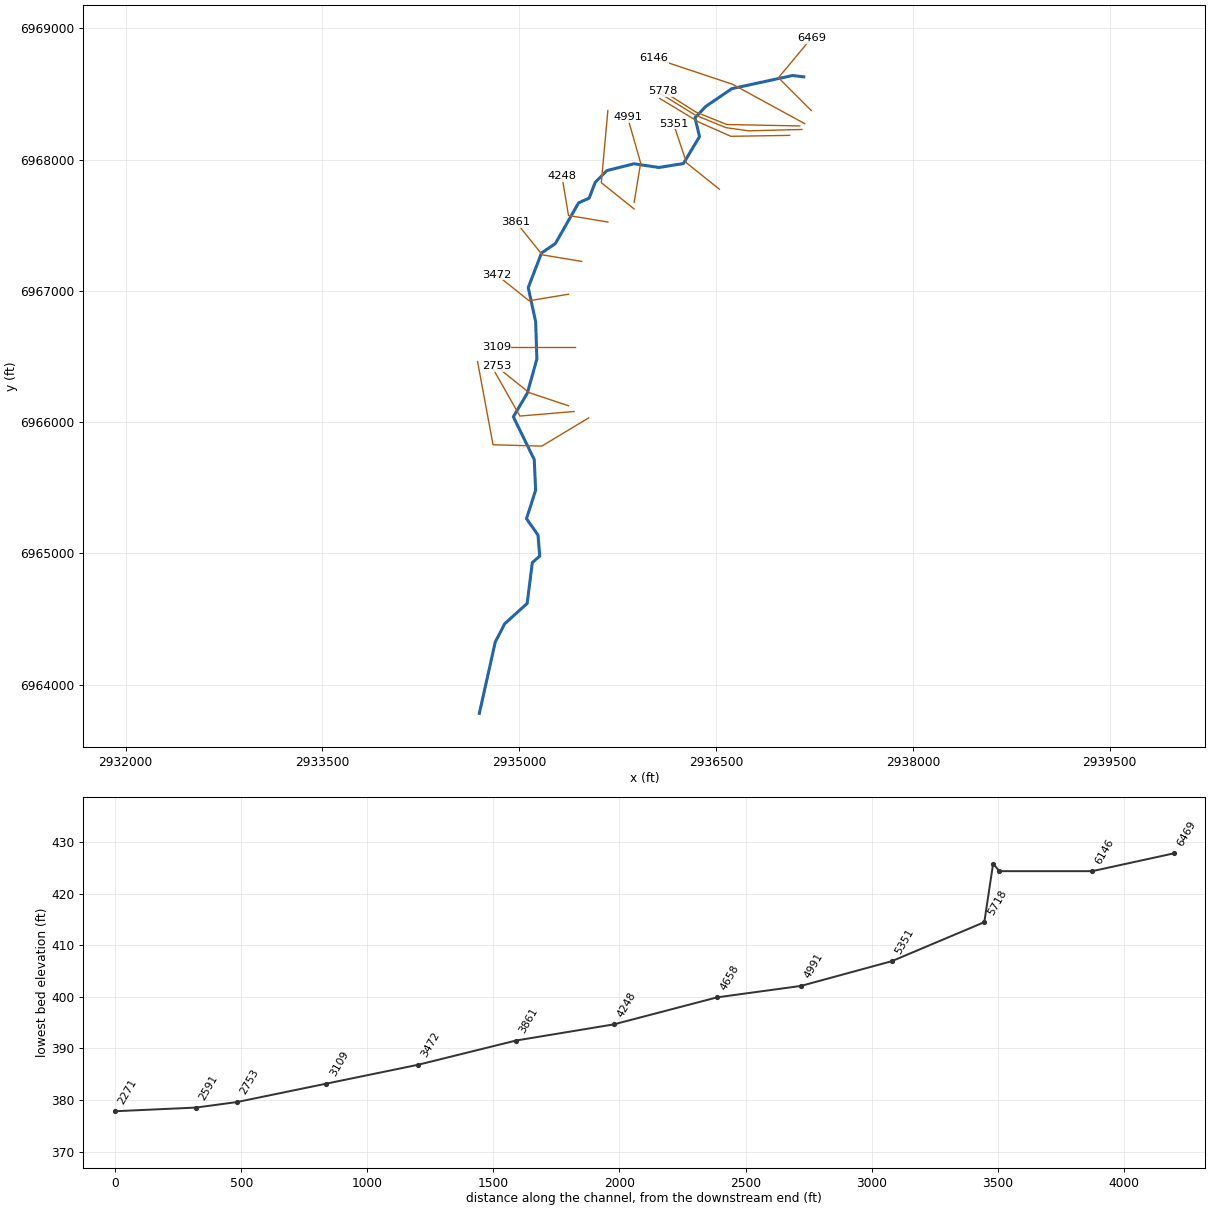
--- UNT 013 IN DRY CR WATERSHED.prj (project) ---

Proj Title=UNT 013 IN DRY CR WATERSHED Base Level Engineering
Current Plan=p01
Default Exp/Contr=0.3,0.1
English Units
Geom File=g01
Flow File=f01
Plan File=p01
BEGIN DESCRIPTION:
UNT 013 IN DRY CR WATERSHED
END DESCRIPTION:

--- UNT 013 IN DRY CR WATERSHED.p01 (plan) ---

Plan Title=Multiple Run
Short Identifier=Multiple
Geom File=g01
Flow File=f01
Subcritical Flow
K Sum by GR= 0
Std Step Tol= 0.01
Critical Tol= 0.01
Num of Std Step Trials= 20
Max Error Tol= 0.3
Flow Tol Ratio= 0.001
Split Flow NTrial= 30
Split Flow Tol= 0.02
Split Flow Ratio= 0.02
Log Output Level= 0
Friction Slope Method= 1
Unsteady Friction Slope Method= 2
Unsteady Bridges Friction Slope Method= 1
Parabolic Critical Depth
Global Vel Dist=  1 , 1 , 1
Global Log Level= 0
CheckData=True
Encroach Param= -1, 0, 0, 0
BEGIN DESCRIPTION:
Multiple Run
END DESCRIPTION:

--- UNT 013 IN DRY CR WATERSHED.f01 (steady flow) ---

Flow Title=Multiple
Number of Profiles=7
Profile Names=10-year,25-year,50-year,1pct_min,100-year,1pct_plu,500-year
River Rch & RM= UNT 013 IN DRY C,Reach-1,6469
     296     382     450     265     529    1055     728
Boundary for River Rch & Prof#=UNT 013 IN DRY C,Reach-1,1
Up Type=0
Dn Type=3
Dn Slope=0.005
Boundary for River Rch & Prof#=UNT 013 IN DRY C,Reach-1,2
Up Type=0
Dn Type=3
Dn Slope=0.005
Boundary for River Rch & Prof#=UNT 013 IN DRY C,Reach-1,3
Up Type=0
Dn Type=3
Dn Slope=0.005
Boundary for River Rch & Prof#=UNT 013 IN DRY C,Reach-1,4
Up Type=0
Dn Type=3
Dn Slope=0.005
Boundary for River Rch & Prof#=UNT 013 IN DRY C,Reach-1,5
Up Type=0
Dn Type=3
Dn Slope=0.005
Boundary for River Rch & Prof#=UNT 013 IN DRY C,Reach-1,6
Up Type=0
Dn Type=3
Dn Slope=0.005
Boundary for River Rch & Prof#=UNT 013 IN DRY C,Reach-1,7
Up Type=0
Dn Type=3
Dn Slope=0.005

--- UNT 013 IN DRY CR WATERSHED.g01 (geometry) ---

Geom Title=Existing Conditions

River Reach=UNT 013 IN DRY C,Reach-1
Reach XY= 30
      2937167.97      6968631.29      2937082.04      6968641.70
      2936619.80      6968541.44      2936420.35      6968405.52
      2936338.83      6968319.12      2936373.58      6968176.40
      2936250.83      6967970.72      2936063.39      6967940.83
      2935874.67      6967969.00      2935667.65      6967917.19
      2935579.20      6967828.65      2935532.17      6967707.03
      2935451.82      6967670.98      2935274.39      6967360.21
      2935169.43      6967289.23      2935068.24      6967025.33
      2935124.64      6966766.20      2935134.08      6966481.33
      2935061.75      6966222.30      2934954.77      6966040.72
      2935113.94      6965715.00      2935124.59      6965481.28
      2935055.04      6965264.28      2935142.72      6965139.52
      2935155.82      6964979.52      2935099.33      6964929.64
      2935059.89      6964618.13      2934889.17      6964464.03
      2934817.01      6964325.01      2934695.59      6963780.71

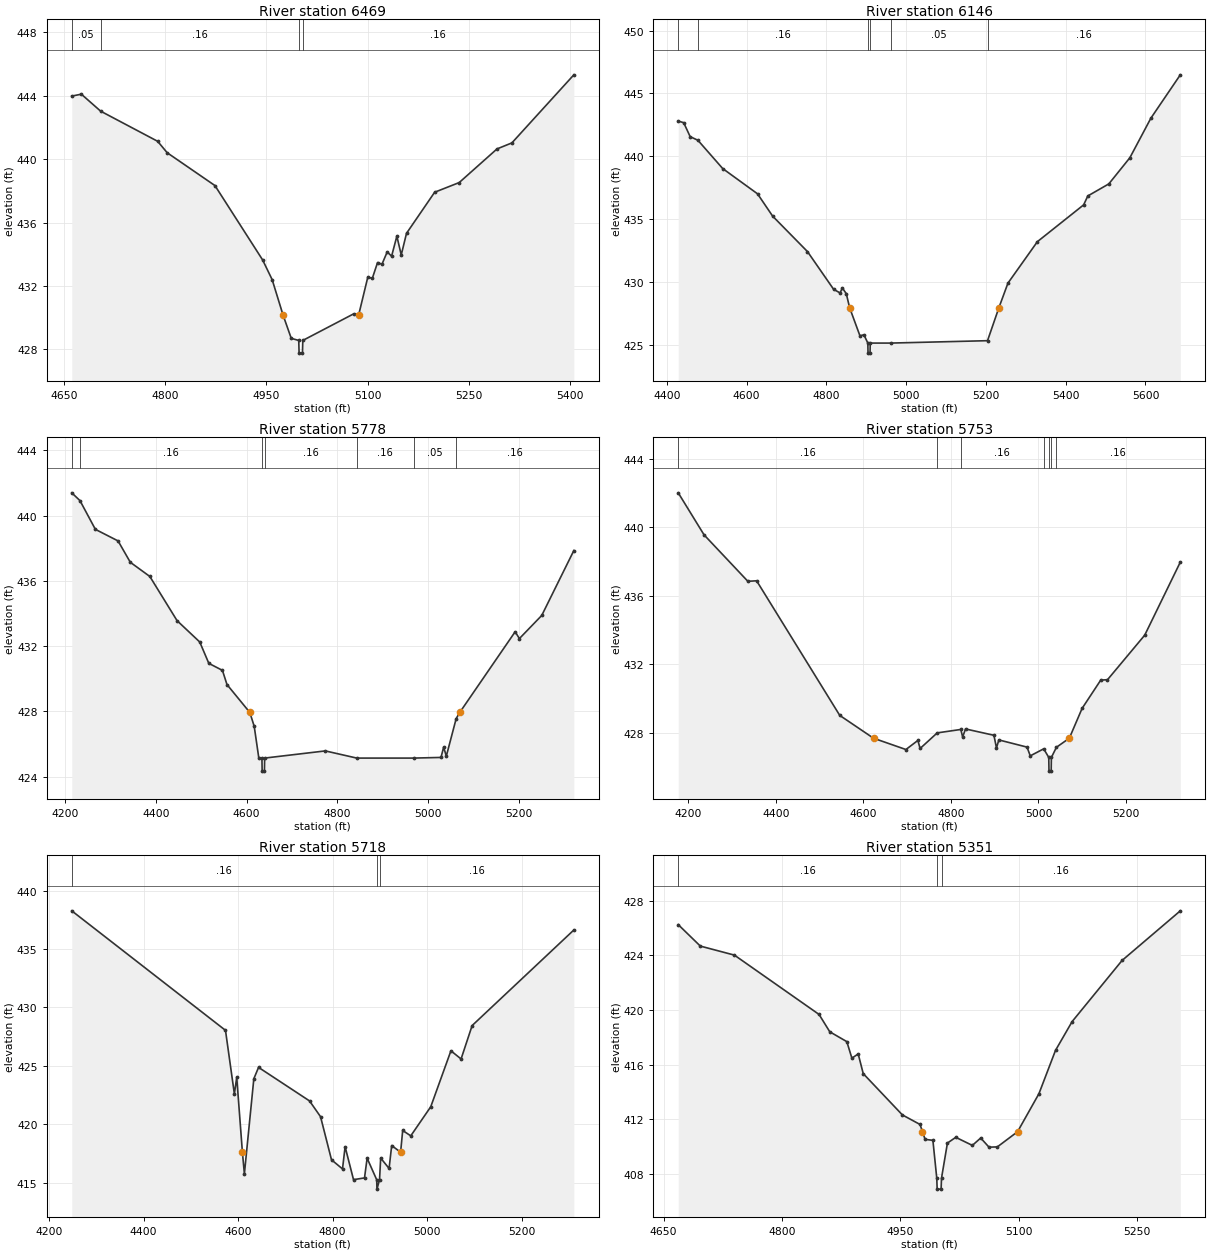
Type RM Length L Ch R = 1,6469,323,323,323
BEGIN DESCRIPTION:
UNT 013 IN DRY CR WATERSHED 12.0
END DESCRIPTION:
XS GIS Cut Line= 3
      2937225.02      6968374.98      2936975.00      6968625.00
      2937225.00      6968925.01
#Sta/Elev= 30
  4661.6  443.97  4675.8  444.09  4704.4  443.02  4788.9  441.12  4803.0  440.40
  4873.8  438.33  4944.5  433.64  4958.6  432.40  4974.8  430.16  4986.9  428.70
  4998.0  428.57  4998.5  427.77  5003.5  427.77  5004.0  428.57  5079.6  430.25
  5086.7  430.16  5100.4  432.57  5107.0  432.48  5114.8  433.48  5121.3  433.37
  5129.1  434.15  5135.6  433.88  5143.4  435.14  5149.9  433.96  5157.7  435.32
  5199.4  437.91  5235.8  438.52  5291.8  440.64  5313.9  441.02  5405.7  445.31
#Mann=4,-1,0
  4661.6    0.05       0  4704.4    0.16       0  4998.0    0.07       0
  5004.0    0.16       0
Bank Sta=4974.8,5086.7
Exp/Cntr=0.3,0.1

Type RM Length L Ch R = 1,6146,368,368,368
BEGIN DESCRIPTION:
UNT 013 IN DRY CR WATERSHED 11.0
END DESCRIPTION:
XS GIS Cut Line= 3
      2937174.97      6968275.02      2936625.00      6968575.00
      2936025.02      6968774.99
#Sta/Elev= 30
  4428.5  442.80  4442.2  442.67  4458.4  441.56  4477.9  441.27  4540.0  439.02
  4627.3  437.01  4665.3  435.23  4752.6  432.41  4818.1  429.41  4834.3  429.12
  4840.0  429.52  4849.9  429.06  4858.2  427.95  4884.1  425.71  4894.1  425.79
  4903.9  425.13  4904.4  424.33  4909.4  424.33  4909.9  425.13  4961.6  425.13
  5204.0  425.32  5232.6  427.95  5255.2  429.90  5329.0  433.20  5445.0  436.13
  5455.5  436.84  5508.2  437.80  5560.9  439.88  5613.6  443.03  5687.4  446.48
#Mann=6,-1,0
  4428.5    0.05       0  4477.9    0.16       0  4903.9   0.033       0
  4909.9    0.16       0  4961.6    0.05       0  5204.0    0.16       0
Bank Sta=4858.2,5232.6
Exp/Cntr=0.3,0.1

Type RM Length L Ch R = 1,5778,25,25,25
BEGIN DESCRIPTION:
Mapping XS f38139f4
END DESCRIPTION:
XS GIS Cut Line= 4
      2937136.95      6968257.44      2936581.44      6968268.29
      2936344.89      6968363.78      2936095.33      6968522.19
#Sta/Elev= 30
  4214.7  441.40  4232.8  440.92  4266.7  439.16  4316.7  438.45  4343.7  437.14
  4386.7  436.27  4446.7  433.56  4496.7  432.25  4516.7  430.94  4546.7  430.51
  4556.7  429.64  4607.0  427.93  4616.7  427.08  4626.7  425.16  4633.7  425.13
  4634.2  424.33  4639.2  424.33  4639.7  425.13  4773.4  425.57  4842.7  425.13
  4967.9  425.13  5028.3  425.17  5034.1  425.80  5040.0  425.25  5061.7  427.55
  5069.6  427.93  5191.7  432.88  5201.0  432.46  5250.3  433.88  5321.0  437.86
#Mann=7,-1,0
  4214.7    0.05       0  4232.8    0.16       0  4633.7   0.033       0
  4639.7    0.16       0  4842.7    0.16       0  4967.9    0.05       0
  5061.7    0.16       0
Bank Sta=4607,5069.6
Exp/Cntr=0.3,0.1

Type RM Length L Ch R = 1,5753,35,35,35
BEGIN DESCRIPTION:
Mapping XS 934edd97
END DESCRIPTION:
XS GIS Cut Line= 5
      2937154.02      6968230.53      2936747.82      6968220.11
      2936574.20      6968244.42      2936338.09      6968341.64
      2936074.17      6968504.86
#Sta/Elev= 30
  4176.8  442.01  4235.8  439.56  4335.9  436.85  4355.9  436.88  4545.9  429.03
  4623.0  427.70  4697.1  427.04  4724.4  427.57  4729.5  427.10  4768.6  428.01
  4822.5  428.21  4826.7  427.77  4833.3  428.24  4898.2  427.87  4904.0  427.13
  4909.4  427.60  4973.9  427.18  4981.2  426.67  5011.9  427.08  5023.5  426.58
  5024.0  425.78  5029.0  425.78  5029.5  426.58  5041.0  427.17  5070.5  427.70
  5099.7  429.44  5142.3  431.09  5157.7  431.11  5242.8  433.71  5324.1  437.97
#Mann=7,-1,0
  4176.8    0.16       0  4768.6    0.05       0  4822.5    0.16       0
  5011.9    0.05       0  5023.5    0.07       0  5029.5    0.05       0
  5041.0    0.16       0
Bank Sta=4623,5070.5
Exp/Cntr=0.3,0.1

Type RM Length L Ch R = 1,5718,367,367,367
BEGIN DESCRIPTION:
Mapping XS 17b57349
END DESCRIPTION:
XS GIS Cut Line= 4
      2937060.36      6968185.39      2936612.40      6968178.45
      2936369.34      6968286.09      2936070.72      6968466.65
#Sta/Elev= 30
  4247.9  438.27  4573.3  428.04  4592.1  422.60  4597.1  424.02  4609.1  417.61
  4613.3  415.76  4633.3  423.90  4643.3  424.87  4751.2  422.00  4774.5  420.65
  4797.7  416.96  4821.0  416.18  4826.5  418.08  4844.3  415.26  4867.6  415.41
  4873.1  417.10  4893.4  415.25  4893.9  414.45  4899.4  415.25  4901.8  417.11
  4919.6  416.22  4925.1  418.18  4944.0  417.61  4948.4  419.47  4965.5  419.01
  5007.8  421.50  5050.5  426.29  5072.0  425.59  5095.4  428.45  5310.7  436.63
#Mann=3,-1,0
  4247.9    0.16       0  4893.4    0.07       0  4899.4    0.16       0
Bank Sta=4609.1,4944
Exp/Cntr=0.3,0.1

Type RM Length L Ch R = 1,5351,360,360,360
BEGIN DESCRIPTION:
UNT 013 IN DRY CR WATERSHED 9.0
END DESCRIPTION:
XS GIS Cut Line= 3
      2936524.98      6967775.01      2936275.00      6967975.00
      2936174.99      6968275.04
#Sta/Elev= 30
  4668.5  426.24  4696.5  424.67  4739.7  424.01  4847.0  419.67  4860.6  418.40
  4882.2  417.68  4888.6  416.47  4896.6  416.78  4903.0  415.34  4952.6  412.32
  4975.0  411.62  4978.1  411.09  4981.4  410.53  4991.3  410.46  4996.2  407.69
  4996.7  406.89  5001.7  406.89  5002.2  407.69  5009.7  410.26  5020.3  410.68
  5041.3  410.09  5051.9  410.63  5062.4  409.96  5073.0  409.98  5098.6  411.09
  5125.7  413.87  5146.7  417.04  5167.8  419.15  5231.1  423.62  5304.9  427.25
#Mann=3,-1,0
  4668.5    0.16       0  4996.2    0.07       0  5002.2    0.16       0
Bank Sta=4978.1,5098.6
Exp/Cntr=0.3,0.1

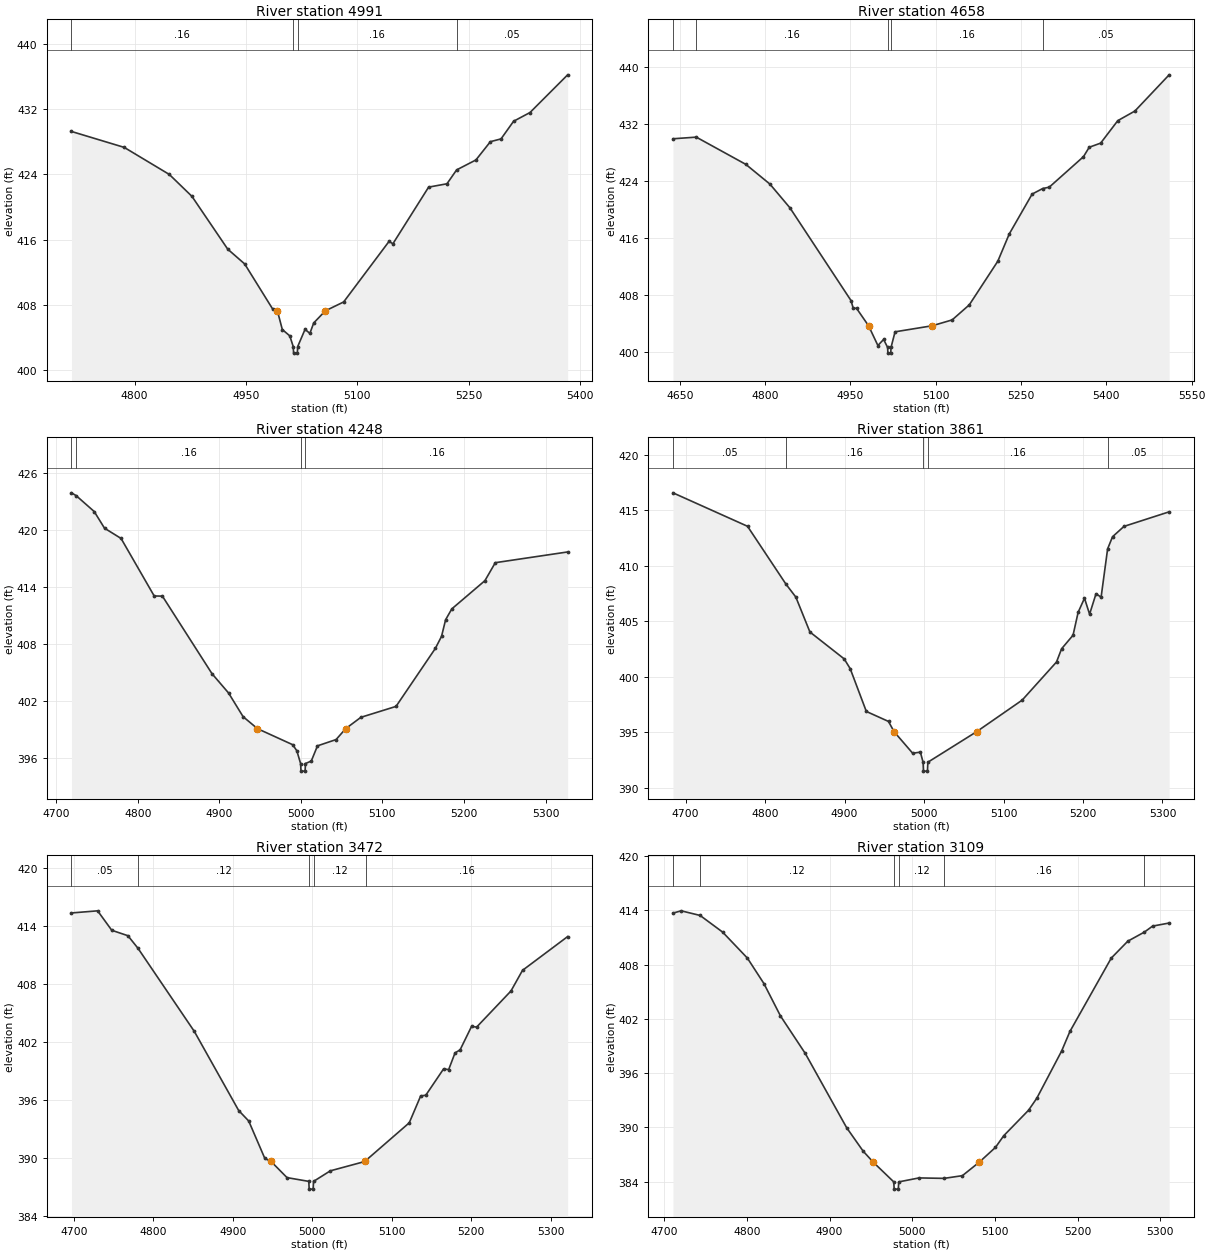
Type RM Length L Ch R = 1,4991,333,333,333
BEGIN DESCRIPTION:
UNT 013 IN DRY CR WATERSHED 8.0
END DESCRIPTION:
XS GIS Cut Line= 3
      2935875.00      6967675.00      2935925.00      6967975.00
      2935825.01      6968324.95
#Sta/Elev= 30
  4715.0  429.26  4786.0  427.31  4846.8  423.99  4877.2  421.31  4925.4  414.84
  4948.2  413.03  4986.2  407.46  4992.3  407.28  4998.9  404.99  5009.0  404.21
  5013.6  402.90  5014.1  402.10  5019.1  402.10  5019.6  402.90  5029.5  405.01
  5036.0  404.52  5041.2  405.80  5056.8  407.28  5081.5  408.37  5142.6  415.79
  5147.8  415.50  5195.9  422.44  5220.6  422.85  5233.6  424.55  5259.6  425.77
  5279.1  428.01  5293.4  428.35  5310.3  430.51  5332.4  431.58  5383.1  436.20
#Mann=4,-1,0
  4715.0    0.16       0  5013.6    0.07       0  5019.6    0.16       0
  5233.6    0.05       0
Bank Sta=4992.3,5056.8
Exp/Cntr=0.3,0.1

Type RM Length L Ch R = 1,4658,410,410,410
BEGIN DESCRIPTION:
UNT 013 IN DRY CR WATERSHED 7.0
END DESCRIPTION:
XS GIS Cut Line= 3
      2935875.02      6967624.99      2935625.00      6967825.00
      2935675.00      6968374.96
#Sta/Elev= 30
  4638.0  429.95  4679.0  430.18  4766.1  426.36  4808.5  423.59  4843.7  420.26
  4951.0  407.26  4955.0  406.17  4960.7  406.17  4981.9  403.72  4998.3  400.95
  5008.4  401.80  5015.4  400.68  5015.9  399.88  5020.9  399.88  5021.4  400.68
  5028.5  402.87  5093.9  403.72  5128.9  404.54  5159.0  406.65  5209.2  412.78
  5229.3  416.60  5269.5  422.19  5288.1  422.97  5299.6  423.16  5359.8  427.44
  5369.9  428.76  5390.0  429.34  5420.1  432.49  5450.2  433.84  5510.4  438.92
#Mann=5,-1,0
  4638.0    0.05       0  4679.0    0.16       0  5015.4    0.07       0
  5021.4    0.16       0  5288.1    0.05       0
Bank Sta=4981.9,5093.9
Exp/Cntr=0.3,0.1

Type RM Length L Ch R = 1,4248,387,387,387
BEGIN DESCRIPTION:
UNT 013 IN DRY CR WATERSHED 6.0
END DESCRIPTION:
XS GIS Cut Line= 3
      2935674.99      6967525.00      2935375.00      6967575.00
      2935324.99      6967875.03
#Sta/Elev= 30
  4718.8  423.92  4724.6  423.62  4746.7  421.95  4759.3  420.20  4779.6  419.12
  4820.2  413.07  4830.3  413.05  4891.1  404.89  4911.4  402.86  4929.2  400.37
  4946.8  399.11  4990.0  397.42  4995.1  396.78  4999.7  395.44  5000.2  394.64
  5005.2  394.64  5005.7  395.44  5012.8  395.70  5020.4  397.30  5043.2  397.96
  5055.0  399.11  5073.6  400.30  5116.7  401.45  5164.9  407.55  5172.5  408.82
  5177.5  410.57  5185.1  411.71  5225.7  414.68  5238.4  416.57  5327.1  417.70
#Mann=4,-1,0
  4718.8    0.05       0  4724.6    0.16       0  4999.7    0.07       0
  5005.7    0.16       0
Bank Sta=4946.8,5055
Exp/Cntr=0.3,0.1

Type RM Length L Ch R = 1,3861,389,389,389
BEGIN DESCRIPTION:
UNT 013 IN DRY CR WATERSHED 5.0
END DESCRIPTION:
XS GIS Cut Line= 3
      2935475.00      6967225.00      2935175.00      6967275.00
      2934975.00      6967525.00
#Sta/Elev= 30
  4684.1  416.56  4777.9  413.55  4826.3  408.34  4838.7  407.18  4856.4  404.04
  4899.5  401.62  4907.1  400.74  4927.4  396.89  4955.3  395.99  4962.3  395.07
  4985.7  393.13  4995.4  393.23  4998.8  392.32  4999.3  391.52  5004.3  391.52
  5004.8  392.32  5066.2  395.07  5123.5  397.91  5166.7  401.34  5173.1  402.53
  5187.5  403.75  5193.9  405.81  5201.9  407.08  5208.3  405.64  5216.4  407.48
  5222.8  407.17  5231.0  411.52  5237.2  412.61  5251.6  413.54  5308.4  414.85
#Mann=5,-1,0
  4684.1    0.05       0  4826.3    0.16       0  4998.8    0.07       0
  5004.8    0.16       0  5231.0    0.05       0
Bank Sta=4962.3,5066.2
Exp/Cntr=0.3,0.1

Type RM Length L Ch R = 1,3472,363,363,363
BEGIN DESCRIPTION:
UNT 013 IN DRY CR WATERSHED 4.0
END DESCRIPTION:
XS GIS Cut Line= 3
      2935374.99      6966975.00      2935075.00      6966925.00
      2934824.99      6967125.01
#Sta/Elev= 30
  4697.1  415.35  4730.0  415.57  4747.8  413.56  4768.1  413.00  4780.8  411.70
  4851.7  403.11  4907.5  394.94  4920.1  393.86  4940.4  389.99  4948.2  389.68
  4968.3  388.01  4995.7  387.62  4996.2  386.82  5001.2  386.82  5001.7  387.62
  5022.8  388.71  5066.5  389.68  5068.2  389.83  5122.1  393.67  5136.5  396.45
  5142.9  396.52  5165.3  399.24  5171.7  399.17  5179.7  400.89  5186.1  401.21
  5200.5  403.63  5206.9  403.56  5250.1  407.29  5264.6  409.42  5321.4  412.91
#Mann=5,-1,0
  4697.1    0.05       0  4780.8    0.12       0  4995.7    0.07       0
  5001.7    0.12       0  5068.2    0.16       0
Bank Sta=4948.2,5066.5
Exp/Cntr=0.3,0.1

Type RM Length L Ch R = 1,3109,356,356,356
BEGIN DESCRIPTION:
UNT 013 IN DRY CR WATERSHED 3.0
END DESCRIPTION:
XS GIS Cut Line= 3
      2935424.97      6966575.00      2935125.00      6966575.00
      2934824.97      6966575.00
#Sta/Elev= 30
  4710.7  413.71  4720.7  413.96  4743.5  413.45  4770.7  411.61  4800.7  408.73
  4820.7  405.91  4840.7  402.33  4870.7  398.18  4920.7  389.97  4940.7  387.37
  4952.8  386.16  4977.7  383.97  4978.2  383.17  4983.2  383.17  4983.7  383.97
  5008.2  384.41  5038.5  384.36  5060.7  384.66  5081.2  386.16  5100.7  387.79
  5110.7  389.08  5140.7  391.90  5150.7  393.23  5180.7  398.45  5190.7  400.61
  5240.7  408.73  5260.7  410.60  5280.8  411.61  5290.7  412.27  5310.7  412.61
#Mann=6,-1,0
  4710.7    0.05       0  4743.5    0.12       0  4977.7    0.07       0
  4983.7    0.12       0  5038.5    0.16       0  5280.8    0.12       0
Bank Sta=4952.8,5081.2
Exp/Cntr=0.3,0.1

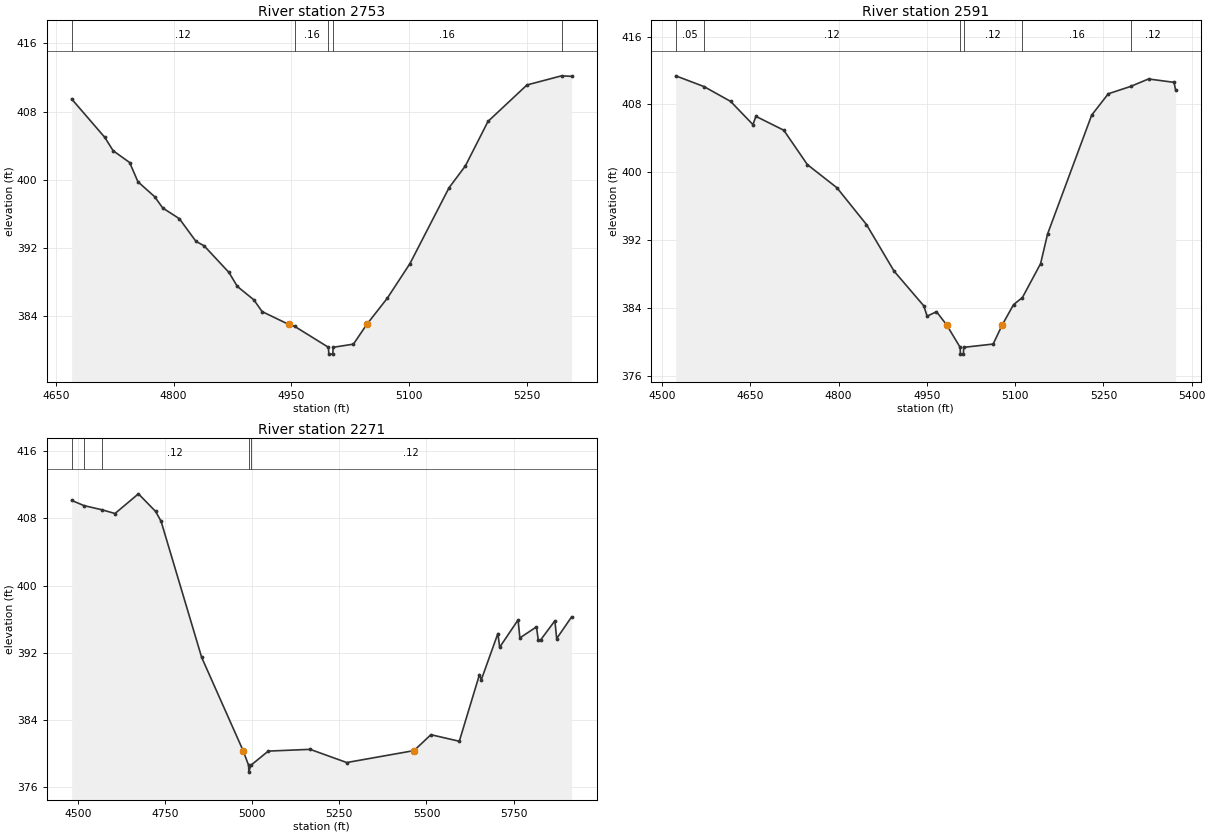
Type RM Length L Ch R = 1,2753,162,162,162
BEGIN DESCRIPTION:
UNT 013 IN DRY CR WATERSHED 2.0
END DESCRIPTION:
XS GIS Cut Line= 3
      2935375.05      6966124.98      2935075.00      6966225.00
      2934825.03      6966424.98
#Sta/Elev= 30
  4670.3  409.47  4712.5  404.97  4723.1  403.41  4744.1  402.03  4754.7  399.77
  4775.8  398.04  4786.3  396.70  4807.4  395.45  4828.5  392.80  4839.0  392.27
  4870.6  389.15  4881.2  387.52  4902.2  385.95  4912.8  384.57  4946.6  383.07
  4954.4  382.83  4997.2  380.39  4997.7  379.59  5002.7  379.59  5003.2  380.39
  5029.0  380.76  5046.0  383.07  5072.2  386.15  5101.0  390.20  5150.7  399.07
  5171.5  401.63  5200.3  406.84  5249.9  411.11  5293.9  412.18  5306.7  412.12
#Mann=5,-1,0
  4670.3    0.12       0  4954.4    0.16       0  4997.2    0.07       0
  5003.2    0.16       0  5293.9    0.12       0
Bank Sta=4946.6,5046
Exp/Cntr=0.3,0.1

Type RM Length L Ch R = 1,2591,320,320,320
BEGIN DESCRIPTION:
Mapping XS 27c5f747
END DESCRIPTION:
XS GIS Cut Line= 3
      2935417.93      6966081.22      2935004.76      6966046.50
      2934789.75      6966424.51
#Sta/Elev= 30
  4523.3  411.38  4571.4  410.11  4616.6  408.36  4654.5  405.62  4659.5  406.60
  4706.9  404.96  4747.0  400.90  4797.2  398.17  4847.4  393.83  4894.4  388.32
  4944.8  384.23  4950.5  383.01  4966.4  383.54  4983.7  381.98  5006.6  379.33
  5007.1  378.53  5012.1  378.53  5012.6  379.33  5062.7  379.72  5078.1  381.98
  5097.3  384.37  5112.4  385.21  5143.3  389.21  5155.2  392.72  5230.1  406.74
  5258.3  409.26  5296.3  410.13  5326.7  411.01  5370.0  410.61  5372.8  409.70
#Mann=6,-1,0
  4523.3    0.05       0  4571.4    0.12       0  5006.6    0.07       0
  5012.6    0.12       0  5112.4    0.16       0  5296.3    0.12       0
Bank Sta=4983.7,5078.1
Exp/Cntr=0.3,0.1

Type RM Length L Ch R = 1,2271,0,0,0
BEGIN DESCRIPTION:
UNT 013 IN DRY CR WATERSHED 1.0
END DESCRIPTION:
XS GIS Cut Line= 4
      2935529.04      6966032.60      2935171.43      6965817.34
      2934799.90      6965827.75      2934682.13      6966461.62
#Sta/Elev= 30
  4482.3  410.13  4517.6  409.51  4568.5  409.02  4606.6  408.57  4673.8  410.91
  4723.2  408.81  4738.7  407.65  4855.2  391.46  4974.0  380.38  4989.9  378.62
  4990.4  377.82  4995.9  378.62  5046.2  380.32  5166.2  380.53  5271.3  378.96
  5464.2  380.38  5512.7  382.27  5594.1  381.49  5652.0  389.42  5657.1  388.79
  5704.8  394.30  5709.9  392.67  5762.7  395.92  5767.8  393.78  5815.5  395.09
  5820.6  393.53  5828.0  393.57  5868.3  395.82  5873.4  393.70  5916.1  396.27
#Mann=5,-1,0
  4482.3    0.16       0  4517.6    0.05       0  4568.5    0.12       0
  4989.9    0.07       0  4995.9    0.12       0
Bank Sta=4974,5464.2
Exp/Cntr=0.3,0.1

Chan Stop Cuts=-1