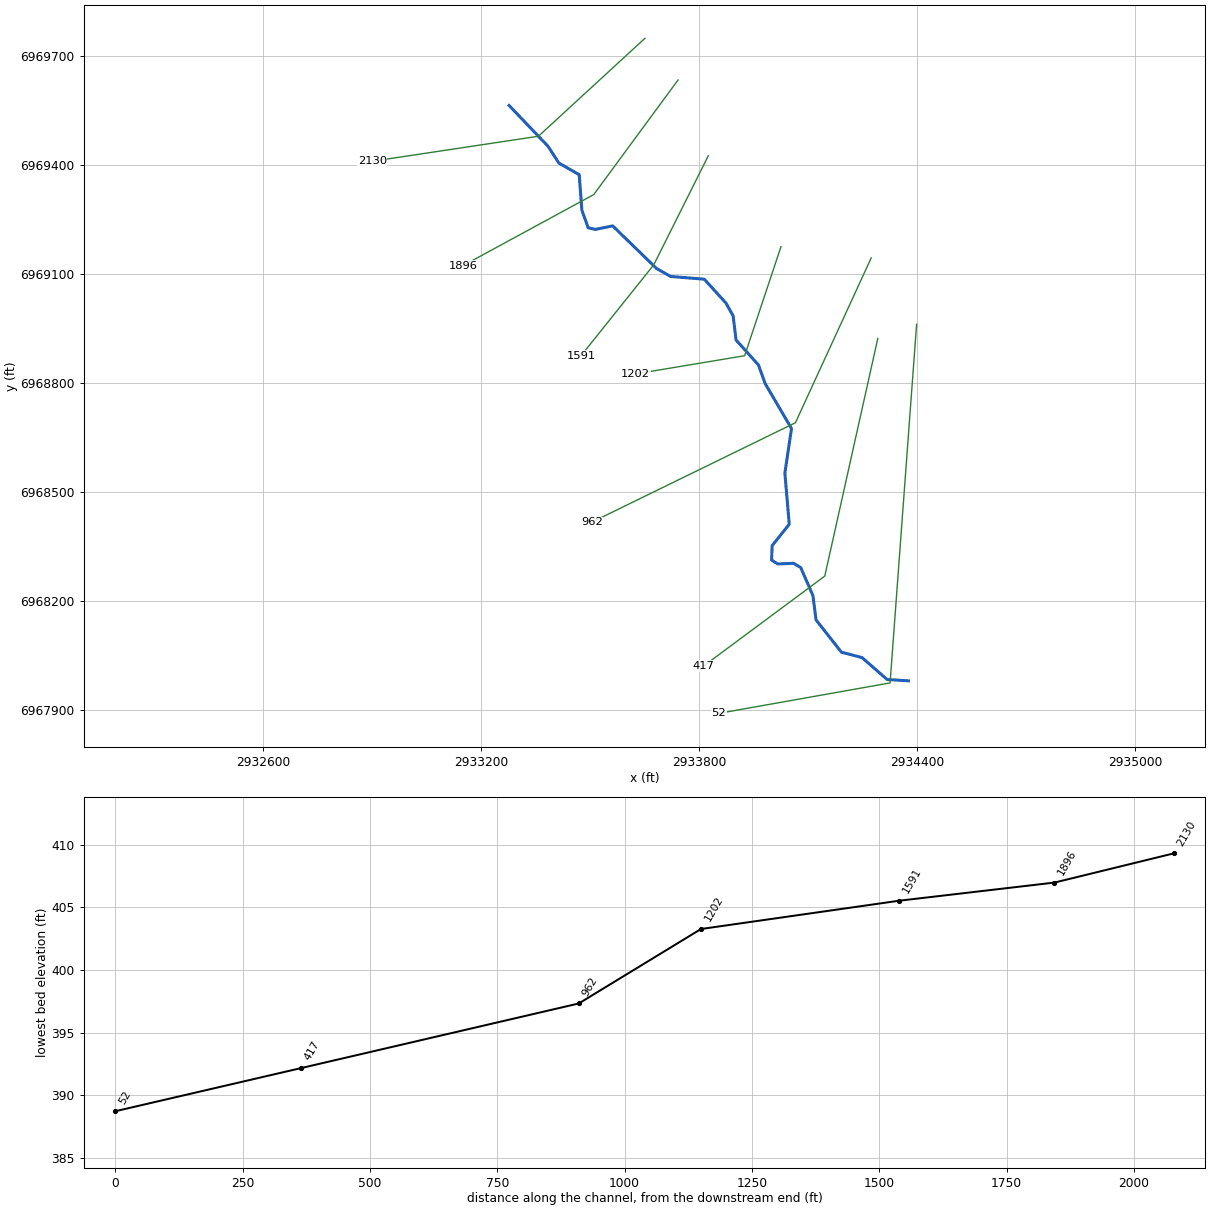
--- UNT 014 IN DRY CR WATERSHED.prj (project) ---

Proj Title=UNT 014 IN DRY CR WATERSHED Base Level Engineering
Current Plan=p01
Default Exp/Contr=0.3,0.1
English Units
Geom File=g01
Flow File=f01
Plan File=p01
BEGIN DESCRIPTION:
UNT 014 IN DRY CR WATERSHED
END DESCRIPTION:

--- UNT 014 IN DRY CR WATERSHED.p01 (plan) ---

Plan Title=Multiple Run
Short Identifier=Multiple
Geom File=g01
Flow File=f01
Subcritical Flow
K Sum by GR= 0
Std Step Tol= 0.01
Critical Tol= 0.01
Num of Std Step Trials= 20
Max Error Tol= 0.3
Flow Tol Ratio= 0.001
Split Flow NTrial= 30
Split Flow Tol= 0.02
Split Flow Ratio= 0.02
Log Output Level= 0
Friction Slope Method= 1
Unsteady Friction Slope Method= 2
Unsteady Bridges Friction Slope Method= 1
Parabolic Critical Depth
Global Vel Dist=  1 , 1 , 1
Global Log Level= 0
CheckData=True
Encroach Param= -1, 0, 0, 0
BEGIN DESCRIPTION:
Multiple Run
END DESCRIPTION:

--- UNT 014 IN DRY CR WATERSHED.f01 (steady flow) ---

Flow Title=Multiple
Number of Profiles=7
Profile Names=10-year,25-year,50-year,1pct_min,100-year,1pct_plu,500-year
River Rch & RM= UNT 014 IN DRY C,Reach-1,2130
     373     493     589     352     701    1400     994
Boundary for River Rch & Prof#=UNT 014 IN DRY C,Reach-1,1
Up Type=0
Dn Type=3
Dn Slope=0.005
Boundary for River Rch & Prof#=UNT 014 IN DRY C,Reach-1,2
Up Type=0
Dn Type=3
Dn Slope=0.005
Boundary for River Rch & Prof#=UNT 014 IN DRY C,Reach-1,3
Up Type=0
Dn Type=3
Dn Slope=0.005
Boundary for River Rch & Prof#=UNT 014 IN DRY C,Reach-1,4
Up Type=0
Dn Type=3
Dn Slope=0.005
Boundary for River Rch & Prof#=UNT 014 IN DRY C,Reach-1,5
Up Type=0
Dn Type=3
Dn Slope=0.005
Boundary for River Rch & Prof#=UNT 014 IN DRY C,Reach-1,6
Up Type=0
Dn Type=3
Dn Slope=0.005
Boundary for River Rch & Prof#=UNT 014 IN DRY C,Reach-1,7
Up Type=0
Dn Type=3
Dn Slope=0.005

--- UNT 014 IN DRY CR WATERSHED.g01 (geometry) ---

Geom Title=Existing Conditions

River Reach=UNT 014 IN DRY C,Reach-1
Reach XY= 30
      2933277.03      6969563.36      2933384.54      6969450.65
      2933413.80      6969405.09      2933469.94      6969372.94
      2933477.23      6969275.84      2933494.55      6969226.74
      2933514.75      6969222.52      2933562.08      6969232.05
      2933682.59      6969115.02      2933721.21      6969093.03
      2933813.95      6969085.50      2933873.50      6969019.95
      2933893.24      6968984.75      2933901.41      6968918.17
      2933962.96      6968849.62      2933981.40      6968798.39
      2934053.84      6968674.73      2934035.63      6968552.04
      2934047.67      6968411.42      2934000.69      6968352.67
      2933999.09      6968312.95      2934015.76      6968302.27
      2934059.26      6968304.00      2934079.35      6968292.21
      2934112.85      6968214.96      2934121.34      6968148.36
      2934191.13      6968059.52      2934247.96      6968044.63
      2934316.90      6967984.40      2934375.59      6967980.71

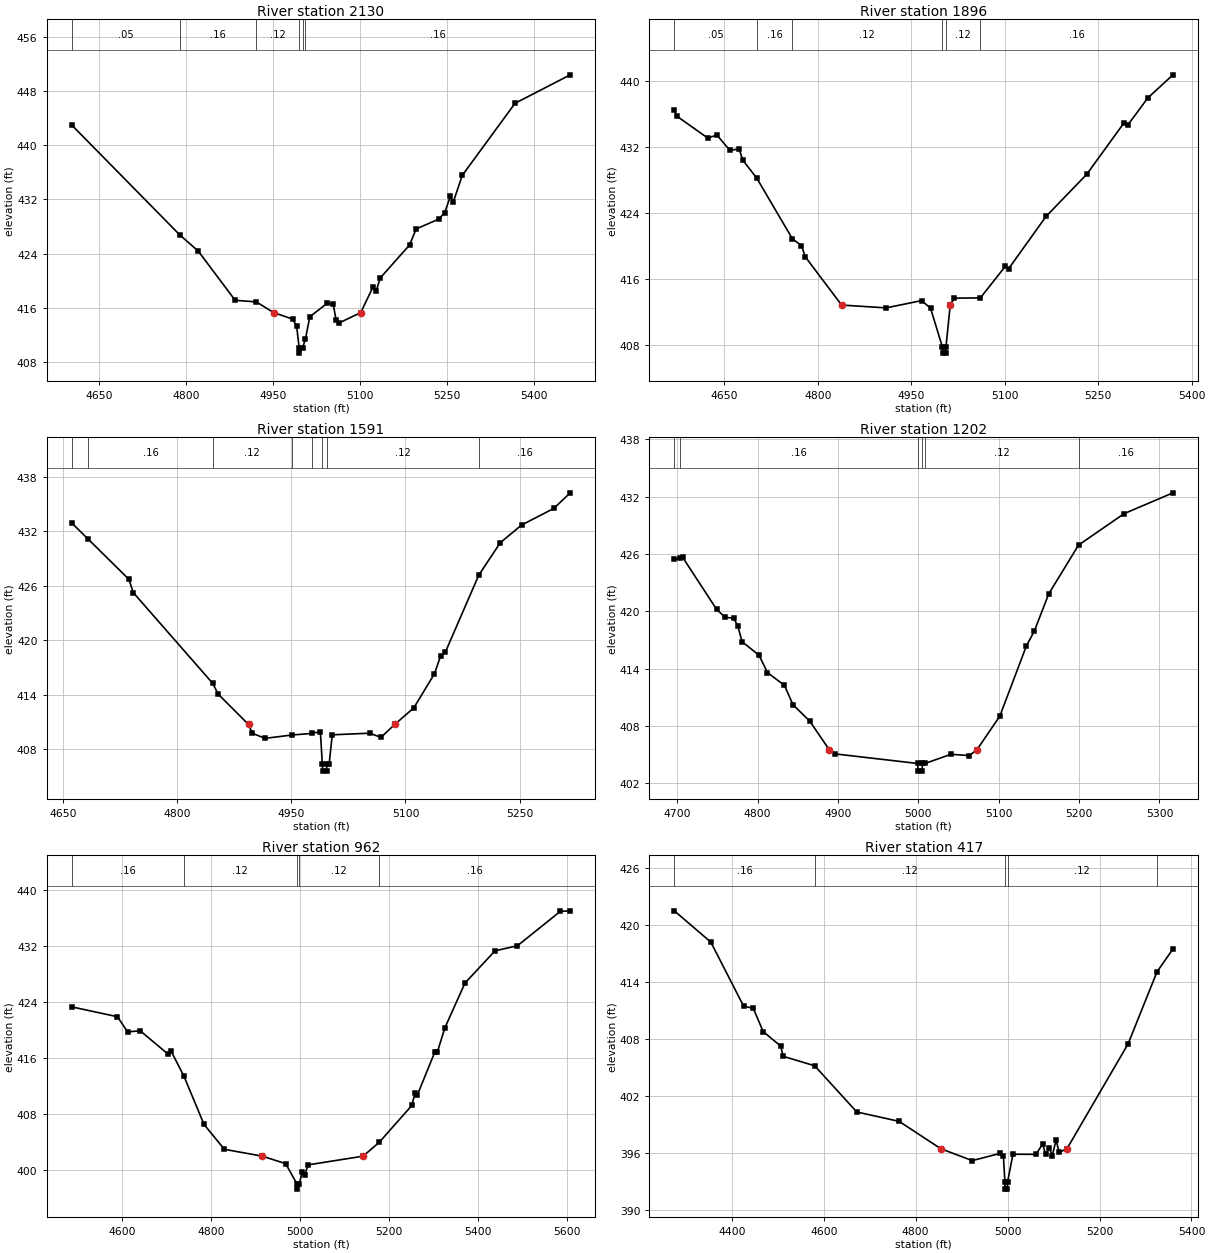
Type RM Length L Ch R = 1,2130,234,234,234
BEGIN DESCRIPTION:
UNT 014 IN DRY CR WATERSHED 4.0
END DESCRIPTION:
XS GIS Cut Line= 3
      2933650.64      6969748.00      2933357.75      6969478.67
      2932900.91      6969409.87
#Sta/Elev= 30
  4602.1  443.01  4789.0  426.74  4820.5  424.38  4884.1  417.12  4920.8  416.88
  4950.4  415.30  4983.3  414.35  4990.2  413.26  4994.5  410.12  4995.0  409.32
  5000.5  410.12  5005.4  411.43  5012.9  414.70  5043.2  416.69  5053.3  416.52
  5058.3  414.17  5063.5  413.78  5100.6  415.30  5122.2  419.13  5127.3  418.47
  5134.3  420.41  5184.8  425.27  5196.3  427.65  5235.4  429.11  5245.5  430.04
  5255.1  432.46  5260.2  431.61  5275.8  435.56  5366.8  446.20  5462.0  450.40
#Mann=6,-1,0
  4602.1    0.05       0  4789.0    0.16       0  4920.8    0.12       0
  4994.5    0.07       0  5000.5    0.12       0  5005.4    0.16       0
Bank Sta=4950.4,5100.6
Exp/Cntr=0.3,0.1

Type RM Length L Ch R = 1,1896,305,305,305
BEGIN DESCRIPTION:
Mapping XS 8b7eff2c
END DESCRIPTION:
XS GIS Cut Line= 3
      2933741.74      6969633.37      2933509.99      6969318.29
      2933150.58      6969122.96
#Sta/Elev= 30
  4569.8  436.49  4573.4  435.76  4623.5  433.08  4638.2  433.44  4659.0  431.59
  4673.7  431.76  4679.9  430.38  4702.2  428.21  4759.3  420.86  4773.9  420.02
  4780.1  418.66  4838.3  412.82  4909.7  412.48  4966.6  413.36  4981.0  412.44
  4999.8  407.79  5000.3  406.99  5005.3  406.99  5005.8  407.79  5012.6  412.82
  5019.0  413.66  5061.0  413.69  5100.7  417.50  5106.4  417.24  5166.3  423.57
  5231.8  428.70  5291.7  434.95  5297.4  434.65  5329.7  437.95  5370.0  440.75
#Mann=6,-1,0
  4569.8    0.05       0  4702.2    0.16       0  4759.3    0.12       0
  4999.8    0.07       0  5005.8    0.12       0  5061.0    0.16       0
Bank Sta=4838.3,5012.6
Exp/Cntr=0.3,0.1

Type RM Length L Ch R = 1,1591,389,389,389
BEGIN DESCRIPTION:
UNT 014 IN DRY CR WATERSHED 3.0
END DESCRIPTION:
XS GIS Cut Line= 3
      2933824.98      6969424.96      2933675.00      6969125.00
      2933475.02      6968875.02
#Sta/Elev= 30
  4661.1  432.96  4683.2  431.13  4736.5  426.71  4742.1  425.26  4846.5  415.24
  4853.9  414.03  4893.7  410.69  4898.6  409.72  4915.4  409.16  4950.9  409.53
  4976.6  409.70  4988.1  409.90  4990.7  406.34  4991.2  405.54  4996.2  405.54
  4996.7  406.34  4999.7  406.34  5003.7  409.55  5053.3  409.73  5067.7  409.26
  5085.8  410.69  5110.9  412.52  5138.1  416.29  5146.1  418.24  5152.5  418.70
  5196.3  427.17  5224.6  430.76  5252.6  432.71  5295.0  434.55  5316.6  436.27
#Mann=8,-1,0
  4661.1    0.05       0  4683.2    0.16       0  4846.5    0.12       0
  4950.9    0.16       0  4976.6    0.12       0  4990.7    0.07       0
  4996.7    0.12       0  5196.3    0.16       0
Bank Sta=4893.7,5085.8
Exp/Cntr=0.3,0.1

Type RM Length L Ch R = 1,1202,240,240,240
BEGIN DESCRIPTION:
UNT 014 IN DRY CR WATERSHED 2.0
END DESCRIPTION:
XS GIS Cut Line= 3
      2934024.99      6969174.98      2933925.00      6968875.00
      2933625.05      6968825.01
#Sta/Elev= 30
  4696.5  425.42  4704.1  425.55  4707.0  425.63  4749.2  420.19  4759.7  419.37
  4770.3  419.28  4775.5  418.46  4780.8  416.82  4801.9  415.40  4812.4  413.59
  4833.5  412.25  4844.1  410.23  4865.1  408.50  4889.3  405.51  4896.8  405.08
  4999.2  404.08  4999.7  403.28  5004.7  403.28  5005.2  404.08  5008.7  404.09
  5040.6  405.04  5063.4  404.91  5072.9  405.51  5101.4  409.03  5134.4  416.36
  5144.5  417.96  5162.2  421.81  5199.3  426.92  5256.0  430.21  5316.8  432.39
#Mann=6,-1,0
  4696.5    0.05       0  4704.1    0.16       0  4999.2    0.07       0
  5005.2    0.16       0  5008.7    0.12       0  5199.3    0.16       0
Bank Sta=4889.3,5072.9
Exp/Cntr=0.3,0.1

Type RM Length L Ch R = 1,962,545,545,545
BEGIN DESCRIPTION:
Mapping XS 318ed5f7
END DESCRIPTION:
XS GIS Cut Line= 3
      2934272.99      6969143.77      2934064.67      6968690.68
      2933504.76      6968417.24
#Sta/Elev= 30
  4485.7  423.34  4588.8  421.93  4611.7  419.77  4640.2  419.92  4703.6  416.54
  4709.1  417.08  4738.6  413.42  4783.6  406.56  4829.5  403.01  4914.9  402.03
  4967.4  400.96  4992.1  398.13  4992.6  397.33  4998.1  398.13  5004.7  399.83
  5010.3  399.30  5017.4  400.79  5141.4  402.03  5177.6  404.00  5251.1  409.27
  5258.0  410.98  5263.6  410.78  5303.1  416.93  5308.6  416.92  5325.6  420.37
  5370.6  426.73  5438.2  431.33  5488.8  432.06  5585.0  436.96  5607.5  437.04
#Mann=5,-1,0
  4485.7    0.16       0  4738.6    0.12       0  4992.1    0.07       0
  4998.1    0.12       0  5177.6    0.16       0
Bank Sta=4914.9,5141.4
Exp/Cntr=0.3,0.1

Type RM Length L Ch R = 1,417,365,365,365
BEGIN DESCRIPTION:
Mapping XS c05c3e1b
END DESCRIPTION:
XS GIS Cut Line= 3
      2934291.25      6968922.49      2934145.40      6968268.81
      2933812.04      6968021.39
#Sta/Elev= 30
  4274.9  421.46  4354.3  418.17  4426.0  411.40  4446.5  411.23  4468.2  408.75
  4506.5  407.22  4511.7  406.15  4580.3  405.15  4671.9  400.29  4764.1  399.30
  4854.8  396.42  4923.2  395.17  4982.5  395.92  4990.9  395.67  4994.1  392.97
  4994.6  392.17  4999.6  392.17  5000.1  392.97  5011.7  395.84  5061.8  395.83
  5076.4  396.93  5082.6  395.82  5091.0  396.48  5097.2  395.68  5105.6  397.36
  5111.9  396.03  5129.2  396.42  5262.1  407.45  5325.1  415.04  5359.8  417.45
#Mann=5,-1,0
  4274.9    0.16       0  4580.3    0.12       0  4994.1    0.07       0
  5000.1    0.12       0  5325.1    0.16       0
Bank Sta=4854.8,5129.2
Exp/Cntr=0.3,0.1

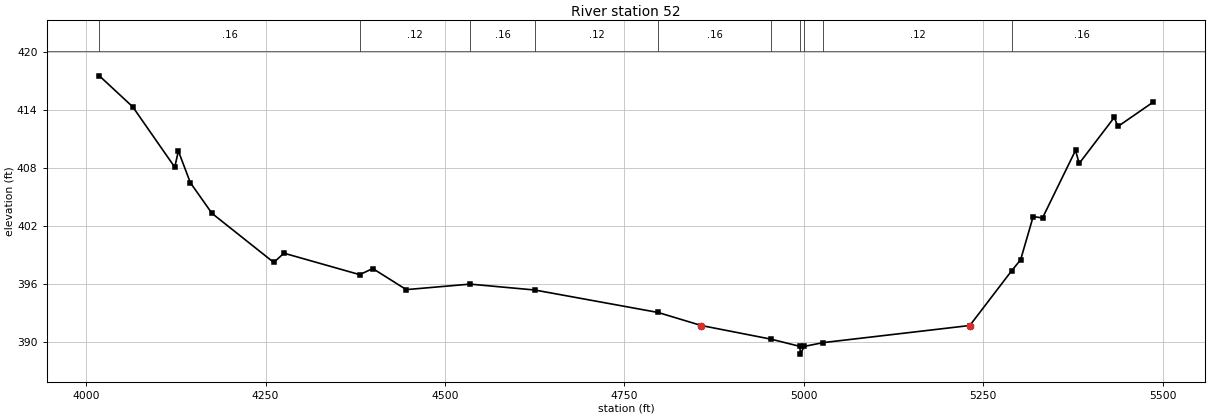
Type RM Length L Ch R = 1,52,0,0,0
BEGIN DESCRIPTION:
UNT 014 IN DRY CR WATERSHED 1.0
END DESCRIPTION:
XS GIS Cut Line= 3
      2934398.01      6968961.50      2934325.00      6967975.00
      2933853.78      6967891.21
#Sta/Elev= 30
  4018.3  417.50  4064.9  414.29  4123.4  408.05  4128.4  409.73  4145.1  406.45
  4175.2  403.28  4261.4  398.20  4275.5  399.16  4381.1  396.94  4399.3  397.57
  4446.0  395.39  4534.8  395.96  4625.1  395.35  4796.7  393.03  4857.0  391.68
  4954.1  390.27  4994.5  389.52  4995.0  388.72  5000.5  389.52  5026.8  389.91
  5231.2  391.68  5289.6  397.35  5302.0  398.48  5319.5  402.95  5332.5  402.80
  5378.5  409.79  5383.6  408.44  5432.5  413.20  5437.5  412.26  5486.1  414.75
#Mann=10,-1,0
  4018.3    0.16       0  4381.1    0.12       0  4534.8    0.16       0
  4625.1    0.12       0  4796.7    0.16       0  4954.1    0.12       0
  4994.5    0.07       0  5000.5    0.12       0  5026.8    0.12       0
  5289.6    0.16       0
Bank Sta=4857,5231.2
Exp/Cntr=0.3,0.1

Chan Stop Cuts=-1