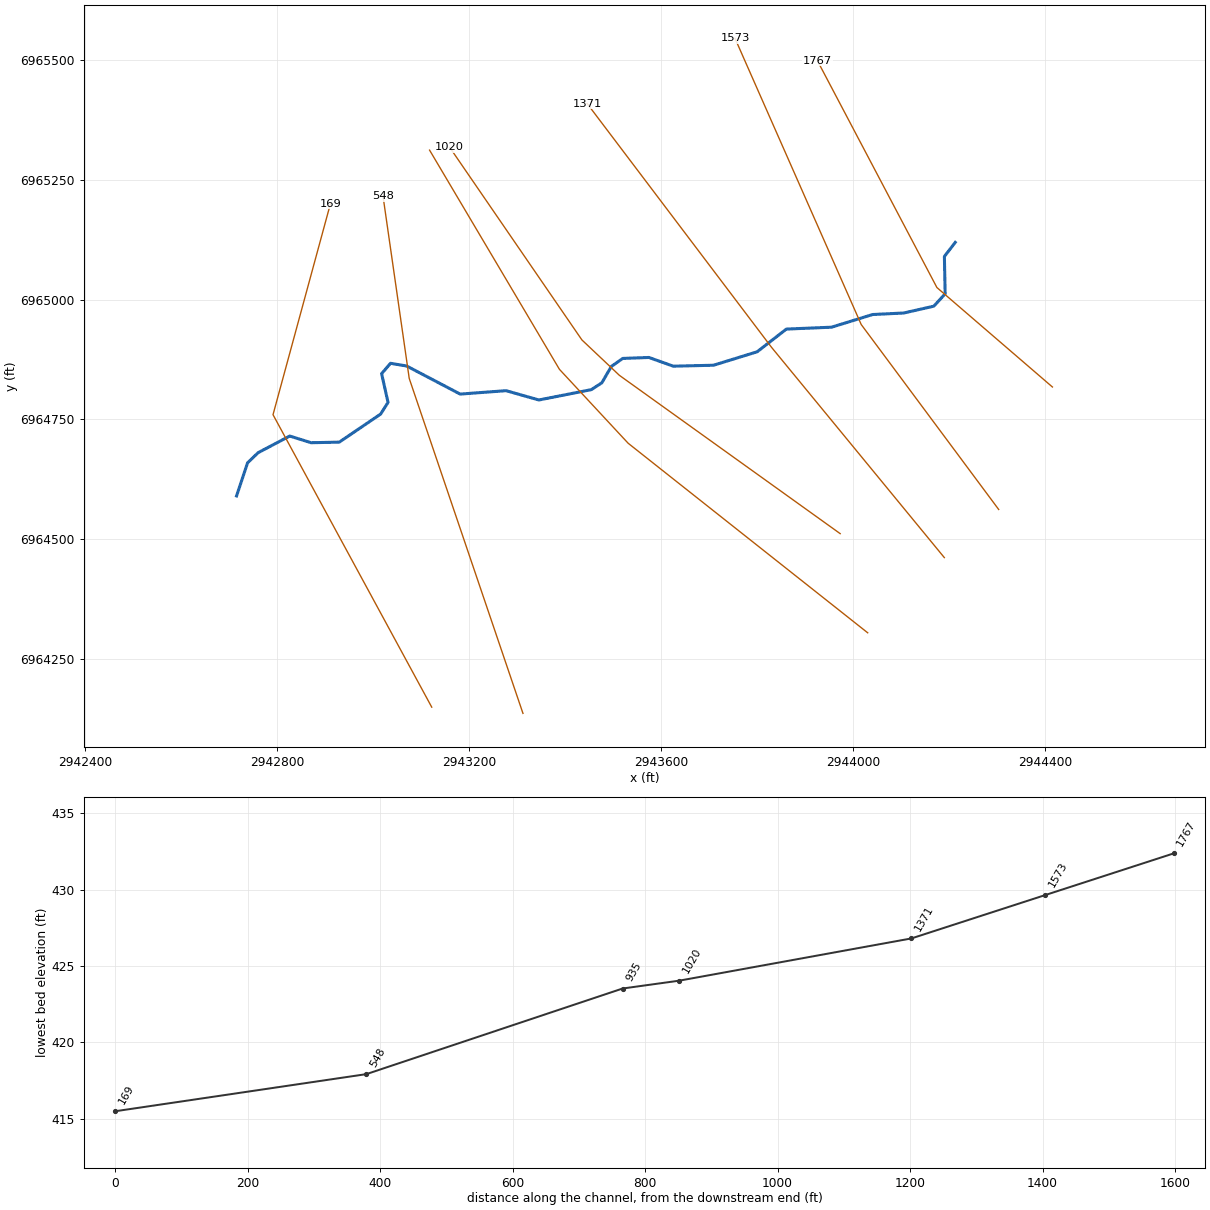
--- UNT 015 IN DRY CR WATERSHED.prj (project) ---

Proj Title=UNT 015 IN DRY CR WATERSHED Base Level Engineering
Current Plan=p01
Default Exp/Contr=0.3,0.1
English Units
Geom File=g01
Flow File=f01
Plan File=p01
BEGIN DESCRIPTION:
UNT 015 IN DRY CR WATERSHED
END DESCRIPTION:

--- UNT 015 IN DRY CR WATERSHED.p01 (plan) ---

Plan Title=Multiple Run
Short Identifier=Multiple
Geom File=g01
Flow File=f01
Subcritical Flow
K Sum by GR= 0
Std Step Tol= 0.01
Critical Tol= 0.01
Num of Std Step Trials= 20
Max Error Tol= 0.3
Flow Tol Ratio= 0.001
Split Flow NTrial= 30
Split Flow Tol= 0.02
Split Flow Ratio= 0.02
Log Output Level= 0
Friction Slope Method= 1
Unsteady Friction Slope Method= 2
Unsteady Bridges Friction Slope Method= 1
Parabolic Critical Depth
Global Vel Dist=  1 , 1 , 1
Global Log Level= 0
CheckData=True
Encroach Param= -1, 0, 0, 0
BEGIN DESCRIPTION:
Multiple Run
END DESCRIPTION:

--- UNT 015 IN DRY CR WATERSHED.f01 (steady flow) ---

Flow Title=Multiple
Number of Profiles=7
Profile Names=10-year,25-year,50-year,1pct_min,100-year,1pct_plu,500-year
River Rch & RM= UNT 015 IN DRY C,Reach-1,1767
     336     437     518     306     611    1219     850
Boundary for River Rch & Prof#=UNT 015 IN DRY C,Reach-1,1
Up Type=0
Dn Type=3
Dn Slope=0.005
Boundary for River Rch & Prof#=UNT 015 IN DRY C,Reach-1,2
Up Type=0
Dn Type=3
Dn Slope=0.005
Boundary for River Rch & Prof#=UNT 015 IN DRY C,Reach-1,3
Up Type=0
Dn Type=3
Dn Slope=0.005
Boundary for River Rch & Prof#=UNT 015 IN DRY C,Reach-1,4
Up Type=0
Dn Type=3
Dn Slope=0.005
Boundary for River Rch & Prof#=UNT 015 IN DRY C,Reach-1,5
Up Type=0
Dn Type=3
Dn Slope=0.005
Boundary for River Rch & Prof#=UNT 015 IN DRY C,Reach-1,6
Up Type=0
Dn Type=3
Dn Slope=0.005
Boundary for River Rch & Prof#=UNT 015 IN DRY C,Reach-1,7
Up Type=0
Dn Type=3
Dn Slope=0.005

--- UNT 015 IN DRY CR WATERSHED.g01 (geometry) ---

Geom Title=Existing Conditions

River Reach=UNT 015 IN DRY C,Reach-1
Reach XY= 30
      2944213.22      6965119.08      2944190.59      6965089.70
      2944192.20      6965011.86      2944168.50      6964986.12
      2944105.74      6964971.88      2944041.12      6964968.73
      2943955.35      6964942.32      2943861.32      6964938.41
      2943800.43      6964891.10      2943709.57      6964863.07
      2943625.75      6964861.08      2943574.78      6964879.25
      2943520.30      6964877.24      2943496.59      6964860.43
      2943476.67      6964826.32      2943454.97      6964812.27
      2943345.65      6964790.64      2943277.18      6964810.05
      2943181.62      6964802.94      2943070.13      6964861.47
      2943036.46      6964867.08      2943017.86      6964845.52
      2943031.25      6964785.69      2943015.86      6964761.30
      2942929.63      6964702.79      2942870.93      6964701.62
      2942826.42      6964715.55      2942760.42      6964680.74
      2942738.57      6964659.69      2942715.59      6964590.71

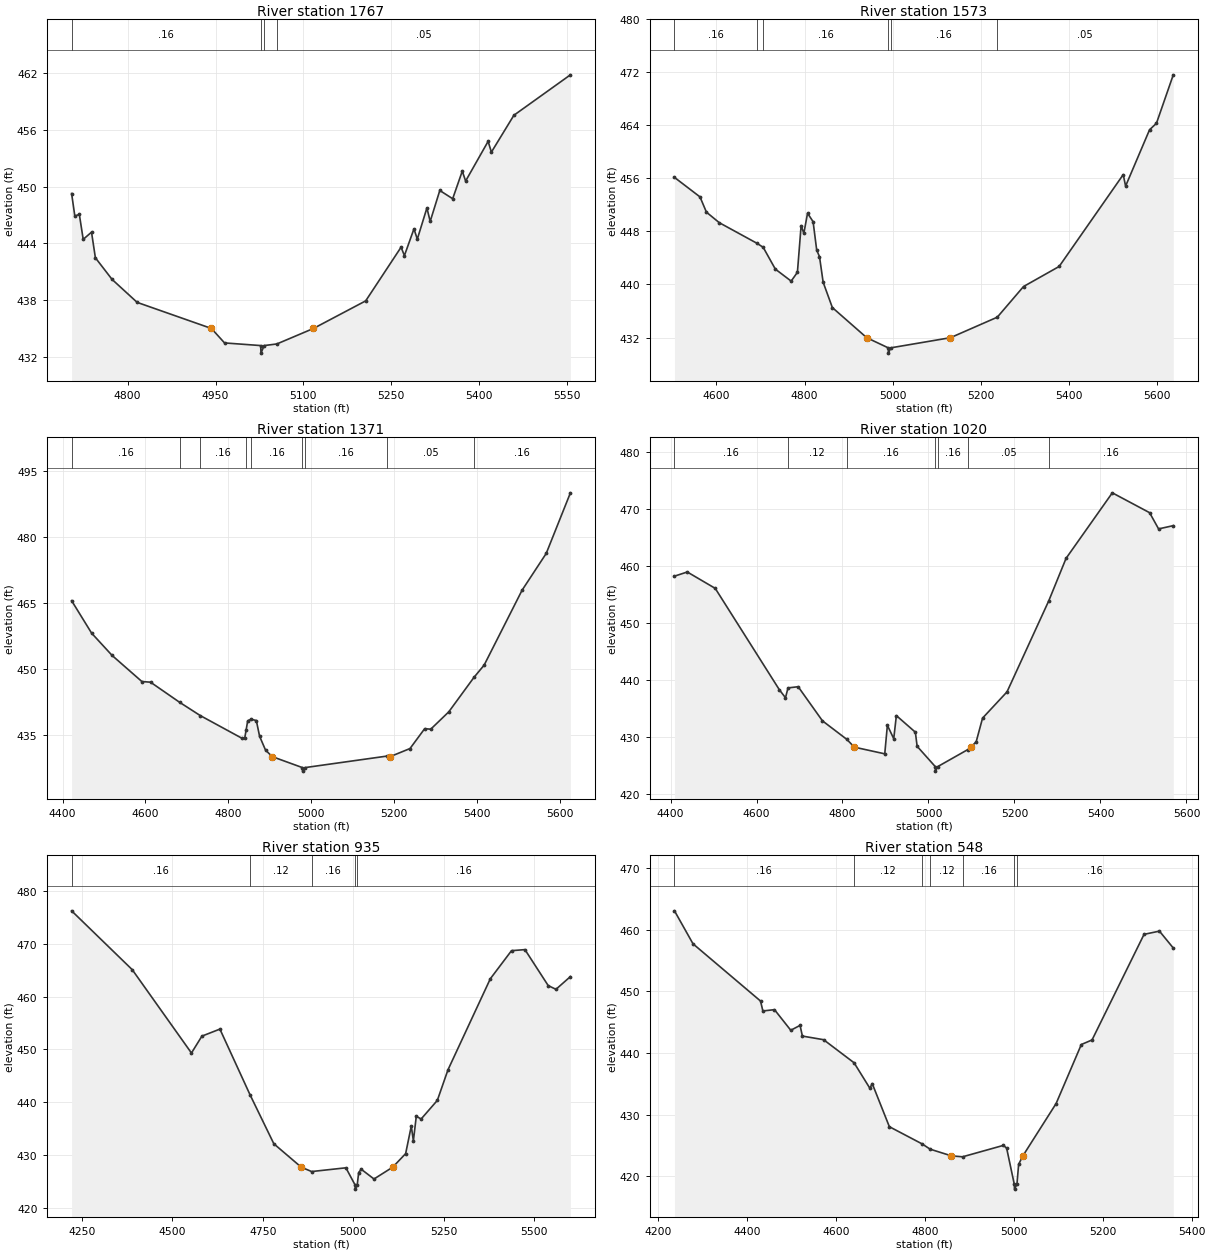
Type RM Length L Ch R = 1,1767,194,194,194
BEGIN DESCRIPTION:
UNT 015 IN DRY CR WATERSHED 4.0
END DESCRIPTION:
XS GIS Cut Line= 3
      2944415.70      6964817.73      2944175.00      6965025.00
      2943926.13      6965497.41
#Sta/Elev= 30
  4704.3  449.27  4709.8  446.89  4717.5  447.06  4724.1  444.42  4738.3  445.18
  4744.9  442.47  4773.4  440.18  4816.2  437.75  4943.0  434.99  4965.4  433.46
  5027.1  433.18  5027.6  432.38  5033.1  433.18  5054.7  433.35  5117.2  434.99
  5206.4  437.91  5266.8  443.59  5272.5  442.70  5288.8  445.53  5294.5  444.44
  5310.9  447.74  5316.5  446.32  5332.9  449.59  5354.9  448.72  5371.3  451.64
  5377.0  450.59  5415.4  454.79  5421.0  453.65  5459.4  457.55  5555.9  461.83
#Mann=4,-1,0
  4704.3    0.16       0  5027.1    0.07       0  5033.1    0.16       0
  5054.7    0.05       0
Bank Sta=4943,5117.2
Exp/Cntr=0.3,0.1

Type RM Length L Ch R = 1,1573,202,202,202
BEGIN DESCRIPTION:
Mapping XS 05479ff5
END DESCRIPTION:
XS GIS Cut Line= 3
      2944303.75      6964562.48      2944017.28      6964947.91
      2943754.27      6965544.26
#Sta/Elev= 30
  4504.9  456.15  4562.8  453.21  4577.4  450.91  4606.6  449.32  4691.7  446.23
  4706.2  445.61  4733.8  442.32  4769.7  440.51  4783.9  441.84  4792.3  448.88
  4798.5  447.72  4806.9  450.75  4819.5  449.47  4827.7  445.17  4834.0  444.21
  4842.3  440.34  4863.2  436.52  4941.1  431.98  4989.9  430.45  4990.4  429.65
  4995.9  430.45  5131.3  431.98  5237.5  435.07  5297.0  439.69  5377.9  442.72
  5523.3  456.57  5528.7  454.84  5583.1  463.34  5598.7  464.31  5636.9  471.62
#Mann=6,-1,0
  4504.9    0.16       0  4691.7    0.12       0  4706.2    0.16       0
  4989.9    0.07       0  4995.9    0.16       0  5237.5    0.05       0
Bank Sta=4941.1,5131.3
Exp/Cntr=0.3,0.1

Type RM Length L Ch R = 1,1371,351,351,351
BEGIN DESCRIPTION:
Mapping XS bc7d071d
END DESCRIPTION:
XS GIS Cut Line= 3
      2944190.46      6964462.23      2943830.22      6964900.60
      2943446.12      6965408.39
#Sta/Elev= 30
  4421.8  465.59  4470.2  458.19  4519.7  453.12  4591.5  447.19  4612.3  447.05
  4682.7  442.46  4732.2  439.46  4832.6  434.31  4839.6  434.26  4843.2  436.23
  4846.9  438.26  4855.0  438.62  4867.7  438.32  4875.6  434.74  4890.0  431.58
  4906.3  430.10  4979.0  427.61  4979.5  426.81  4985.0  427.61  5182.9  430.23
  5190.5  430.10  5238.7  431.95  5274.1  436.47  5288.7  436.35  5332.3  440.30
  5393.0  448.13  5417.7  450.94  5509.2  467.97  5567.5  476.34  5625.9  490.13
#Mann=9,-1,0
  4421.8    0.16       0  4682.7    0.12       0  4732.2    0.16       0
  4843.2    0.12       0  4855.0    0.16       0  4979.0    0.07       0
  4985.0    0.16       0  5182.9    0.05       0  5393.0    0.16       0
Bank Sta=4906.3,5190.5
Exp/Cntr=0.3,0.1

Type RM Length L Ch R = 1,1020,85,85,85
BEGIN DESCRIPTION:
Mapping XS f369d8b8
END DESCRIPTION:
XS GIS Cut Line= 4
      2943973.46      6964512.14      2943513.38      6964842.01
      2943435.25      6964915.80      2943159.84      6965316.98
#Sta/Elev= 30
  4409.2  458.20  4439.0  458.93  4504.0  456.06  4653.4  438.27  4667.4  436.90
  4673.3  438.62  4696.9  438.83  4753.4  432.85  4809.8  429.62  4827.6  428.24
  4898.3  427.07  4904.4  432.07  4919.2  429.72  4925.3  433.77  4969.5  430.86
  4973.6  428.39  5015.7  424.84  5016.2  424.04  5021.7  424.84  5091.6  427.82
  5098.2  428.24  5110.9  429.17  5125.8  433.33  5182.7  437.93  5279.9  453.90
  5320.0  461.32  5427.6  472.80  5514.3  469.32  5535.2  466.48  5569.4  467.05
#Mann=7,-1,0
  4409.2    0.16       0  4673.3    0.12       0  4809.8    0.16       0
  5015.7    0.07       0  5021.7    0.16       0  5091.6    0.05       0
  5279.9    0.16       0
Bank Sta=4827.6,5098.2
Exp/Cntr=0.3,0.1

Type RM Length L Ch R = 1,935,387,387,387
BEGIN DESCRIPTION:
Mapping XS e8b1ed82
END DESCRIPTION:
XS GIS Cut Line= 4
      2944030.78      6964305.52      2943531.61      6964700.52
      2943388.38      6964854.60      2943117.84      6965311.26
#Sta/Elev= 30
  4221.7  476.26  4389.3  465.10  4552.7  449.32  4581.6  452.52  4631.3  453.85
  4714.5  441.41  4780.3  432.12  4855.8  427.70  4884.6  426.86  4979.3  427.57
  5004.6  424.33  5005.1  423.53  5010.6  424.33  5014.6  426.68  5021.8  427.29
  5056.9  425.45  5108.8  427.70  5144.3  430.26  5159.9  435.47  5165.7  432.69
  5173.7  437.33  5187.1  436.82  5231.8  440.34  5261.2  446.13  5378.2  463.39
  5436.7  468.71  5473.8  468.91  5538.1  462.09  5559.5  461.39  5599.4  463.80
#Mann=5,-1,0
  4221.7    0.16       0  4714.5    0.12       0  4884.6    0.16       0
  5004.6    0.07       0  5010.6    0.16       0
Bank Sta=4855.8,5108.8
Exp/Cntr=0.3,0.1

Type RM Length L Ch R = 1,548,379,379,379
BEGIN DESCRIPTION:
Mapping XS ea1e1025
END DESCRIPTION:
XS GIS Cut Line= 3
      2943312.41      6964137.61      2943075.44      6964835.50
      2943020.75      6965215.76
#Sta/Elev= 30
  4237.5  463.03  4279.2  457.68  4430.9  448.41  4436.2  446.80  4462.3  447.01
  4498.9  443.67  4519.8  444.46  4525.0  442.73  4572.7  442.14  4641.2  438.40
  4676.7  434.27  4682.0  435.03  4720.5  428.04  4793.6  425.27  4812.4  424.39
  4860.1  423.31  4885.1  423.16  4976.8  425.01  4984.1  424.57  5001.3  418.72
  5001.8  417.92  5007.3  418.72  5011.1  421.94  5020.6  423.31  5095.3  431.79
  5152.0  441.36  5176.1  442.10  5293.0  459.22  5327.6  459.74  5358.7  457.00
#Mann=7,-1,0
  4237.5    0.16       0  4641.2    0.12       0  4793.6    0.16       0
  4812.4    0.12       0  4885.1    0.16       0  5001.3    0.07       0
  5007.3    0.16       0
Bank Sta=4860.1,5020.6
Exp/Cntr=0.3,0.1

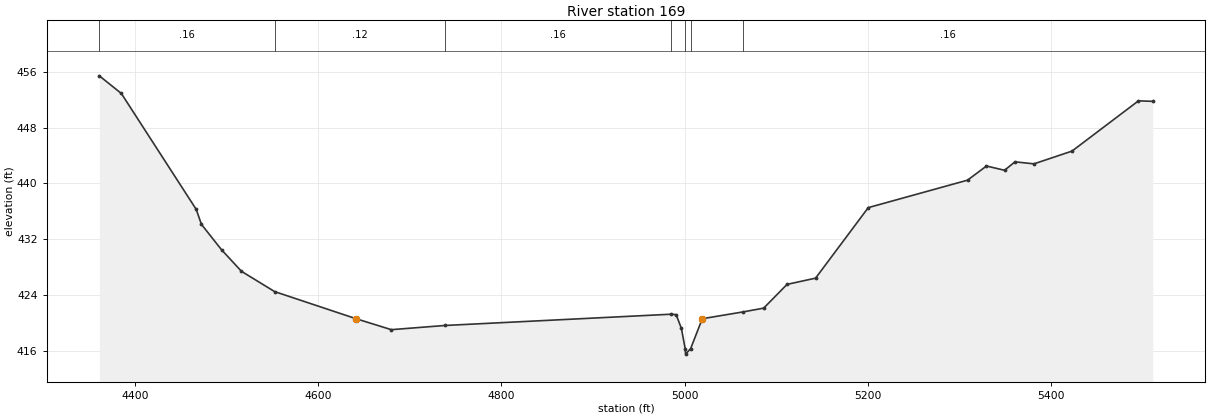
Type RM Length L Ch R = 1,169,0,0,0
BEGIN DESCRIPTION:
UNT 015 IN DRY CR WATERSHED 1.0
END DESCRIPTION:
XS GIS Cut Line= 3
      2943122.32      6964150.60      2942791.59      6964759.98
      2942911.36      6965200.02
#Sta/Elev= 30
  4361.3  455.42  4385.3  452.89  4467.0  436.26  4472.7  434.11  4494.6  430.47
  4516.4  427.37  4552.6  424.46  4641.4  420.57  4679.9  419.00  4738.3  419.60
  4985.6  421.22  4990.7  421.15  4996.4  419.18  5000.5  416.29  5001.0  415.49
  5006.5  416.29  5019.2  420.57  5063.8  421.55  5086.2  422.09  5111.7  425.50
  5142.8  426.39  5200.3  436.51  5308.6  440.45  5329.3  442.48  5349.0  441.87
  5360.4  443.08  5381.1  442.79  5422.6  444.62  5495.1  451.83  5510.7  451.76
#Mann=7,-1,0
  4361.3    0.16       0  4552.6    0.12       0  4738.3    0.16       0
  4985.6    0.12       0  5000.5    0.07       0  5006.5    0.12       0
  5063.8    0.16       0
Bank Sta=4641.4,5019.2
Exp/Cntr=0.3,0.1

Chan Stop Cuts=-1