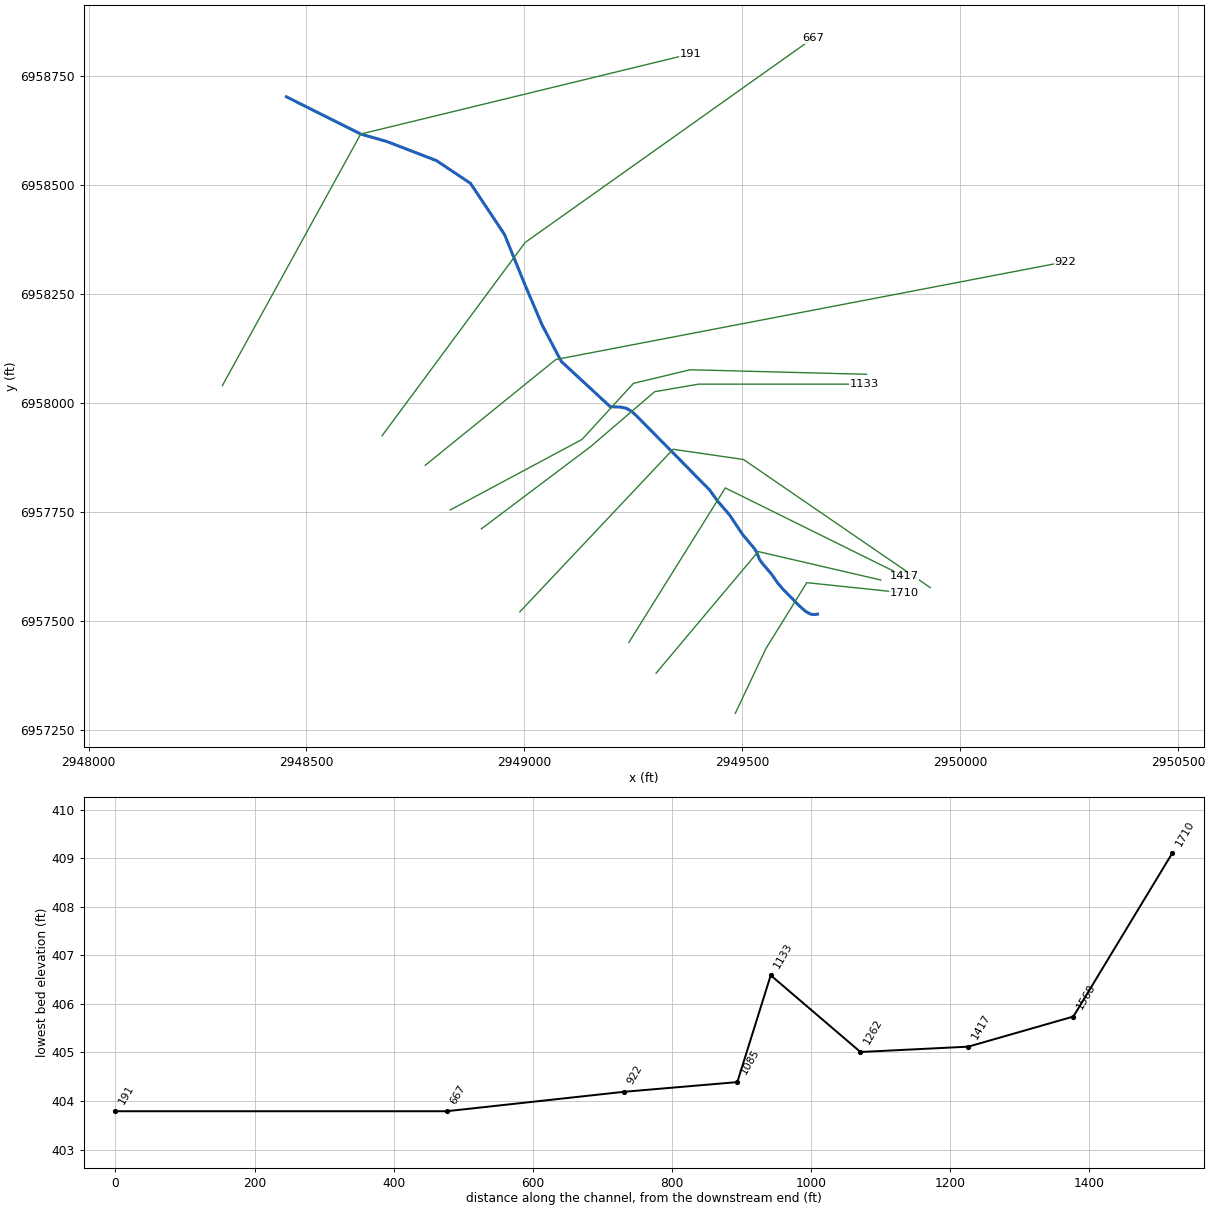
--- UNT 016 IN DRY CR WATERSHED.prj (project) ---

Proj Title=UNT 016 IN DRY CR WATERSHED Base Level Engineering
Current Plan=p01
Default Exp/Contr=0.3,0.1
English Units
Geom File=g01
Flow File=f01
Plan File=p01
BEGIN DESCRIPTION:
UNT 016 IN DRY CR WATERSHED
END DESCRIPTION:

--- UNT 016 IN DRY CR WATERSHED.p01 (plan) ---

Plan Title=Multiple Run
Short Identifier=Multiple
Geom File=g01
Flow File=f01
Subcritical Flow
K Sum by GR= 0
Std Step Tol= 0.01
Critical Tol= 0.01
Num of Std Step Trials= 20
Max Error Tol= 0.3
Flow Tol Ratio= 0.001
Split Flow NTrial= 30
Split Flow Tol= 0.02
Split Flow Ratio= 0.02
Log Output Level= 0
Friction Slope Method= 1
Unsteady Friction Slope Method= 2
Unsteady Bridges Friction Slope Method= 1
Parabolic Critical Depth
Global Vel Dist=  1 , 1 , 1
Global Log Level= 0
CheckData=True
Encroach Param= -1, 0, 0, 0
BEGIN DESCRIPTION:
Multiple Run
END DESCRIPTION:

--- UNT 016 IN DRY CR WATERSHED.f01 (steady flow) ---

Flow Title=Multiple
Number of Profiles=7
Profile Names=10-year,25-year,50-year,1pct_min,100-year,1pct_plu,500-year
River Rch & RM= UNT 016 IN DRY C,Reach-1,1710
     353     464     554     331     660    1316     933
River Rch & RM= UNT 016 IN DRY C,Reach-1,1133
     769    1066    1316     809    1614    3221    2431
Boundary for River Rch & Prof#=UNT 016 IN DRY C,Reach-1,1
Up Type=0
Dn Type=3
Dn Slope=0.005
Boundary for River Rch & Prof#=UNT 016 IN DRY C,Reach-1,2
Up Type=0
Dn Type=3
Dn Slope=0.005
Boundary for River Rch & Prof#=UNT 016 IN DRY C,Reach-1,3
Up Type=0
Dn Type=3
Dn Slope=0.005
Boundary for River Rch & Prof#=UNT 016 IN DRY C,Reach-1,4
Up Type=0
Dn Type=3
Dn Slope=0.005
Boundary for River Rch & Prof#=UNT 016 IN DRY C,Reach-1,5
Up Type=0
Dn Type=3
Dn Slope=0.005
Boundary for River Rch & Prof#=UNT 016 IN DRY C,Reach-1,6
Up Type=0
Dn Type=3
Dn Slope=0.005
Boundary for River Rch & Prof#=UNT 016 IN DRY C,Reach-1,7
Up Type=0
Dn Type=3
Dn Slope=0.005

--- UNT 016 IN DRY CR WATERSHED.g01 (geometry) ---

Geom Title=Existing Conditions

River Reach=UNT 016 IN DRY C,Reach-1
Reach XY= 30
      2949672.47      6957515.94      2949664.79      6957514.92
      2949656.62      6957515.86      2949645.33      6957522.06
      2949631.10      6957534.61      2949593.09      6957573.23
      2949580.61      6957587.81      2949567.57      6957606.80
      2949543.85      6957634.70      2949539.18      6957642.20
      2949531.94      6957659.20      2949527.26      6957666.69
      2949500.74      6957698.13      2949470.55      6957743.34
      2949443.55      6957774.58      2949424.50      6957800.92
      2949256.62      6957970.84      2949245.57      6957980.65
      2949234.22      6957987.41      2949220.90      6957990.28
      2949197.03      6957991.07      2949084.49      6958095.04
      2949041.09      6958177.50      2949002.02      6958268.65
      2948954.28      6958385.84      2948876.16      6958503.02
      2948798.03      6958555.11      2948685.18      6958598.51
      2948624.42      6958615.87      2948453.99      6958701.19

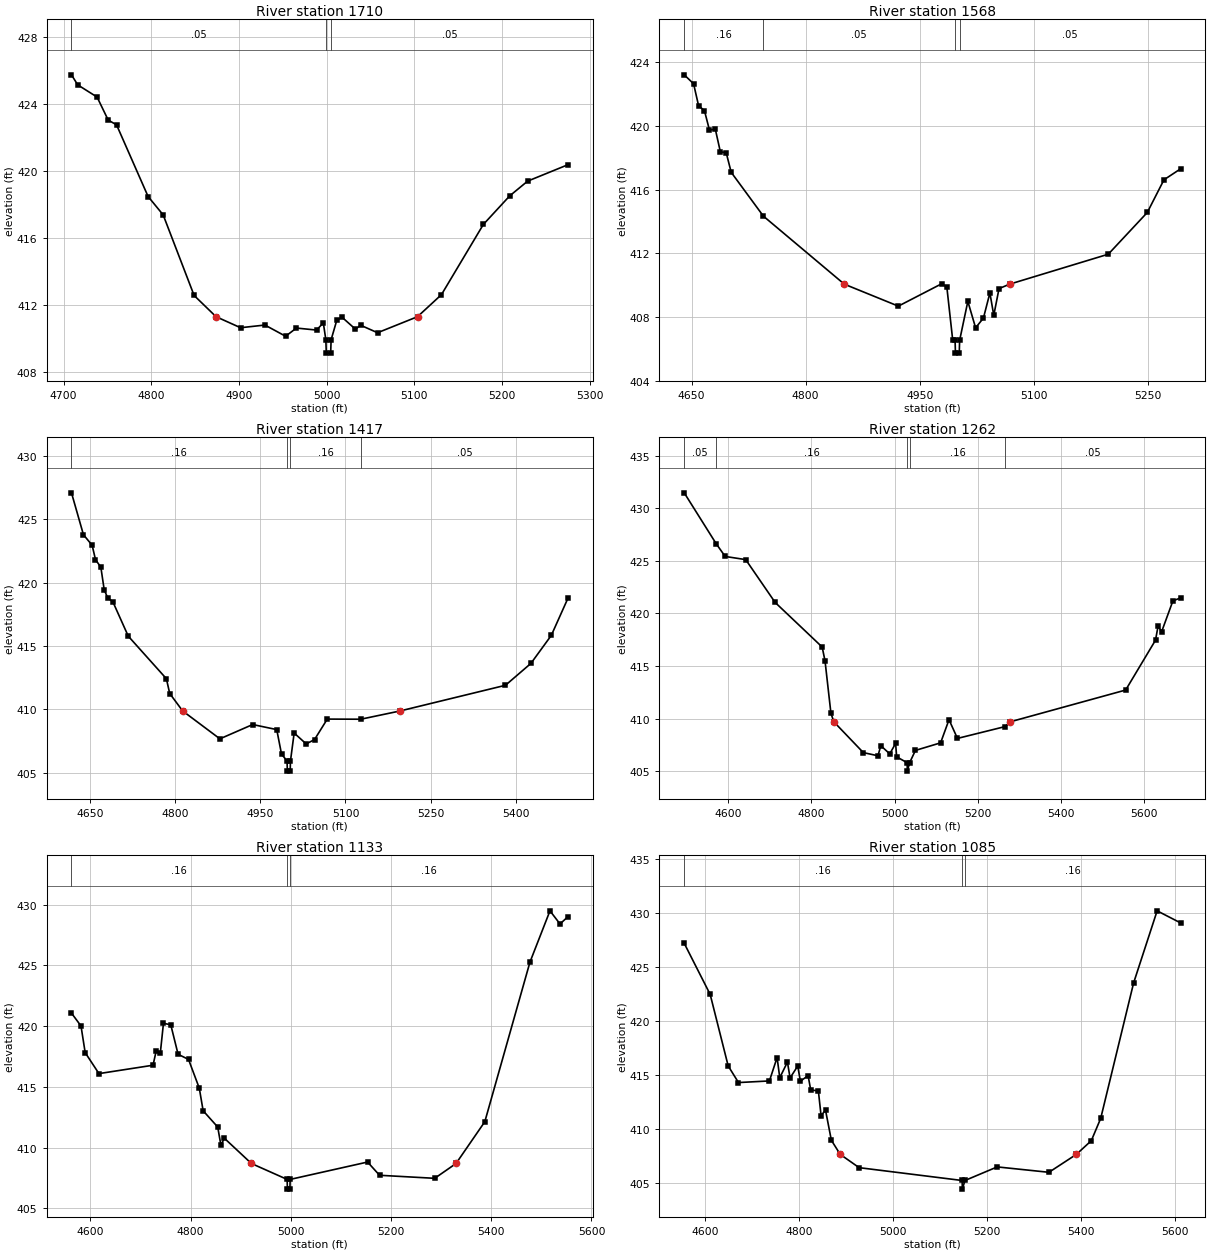
Type RM Length L Ch R = 1,1710,142,142,142
BEGIN DESCRIPTION:
UNT 016 IN DRY CR WATERSHED 2.0
END DESCRIPTION:
XS GIS Cut Line= 4
      2949483.78      6957288.57      2949554.10      6957437.02
      2949647.85      6957588.06      2949870.90      6957564.72
#Sta/Elev= 30
  4709.0  425.75  4716.1  425.15  4738.2  424.42  4750.9  423.04  4760.4  422.76
  4796.4  418.47  4813.6  417.37  4848.9  412.55  4873.9  411.28  4901.9  410.62
  4929.7  410.78  4953.3  410.11  4965.6  410.60  4988.6  410.48  4996.3  410.91
  4999.2  409.90  4999.7  409.10  5004.7  409.10  5005.2  409.90  5011.7  411.07
  5017.6  411.25  5033.0  410.53  5038.8  410.77  5058.2  410.32  5103.8  411.28
  5131.1  412.60  5178.9  416.80  5209.0  418.51  5229.4  419.39  5275.3  420.37
#Mann=3,-1,0
  4709.0    0.05       0  4999.2    0.03       0  5005.2    0.05       0
Bank Sta=4873.9,5103.8
Exp/Cntr=0.3,0.1

Type RM Length L Ch R = 1,1568,151,151,151
BEGIN DESCRIPTION:
Mapping XS 8b696e80
END DESCRIPTION:
XS GIS Cut Line= 3
      2949302.01      6957380.63      2949536.39      6957659.29
      2949817.64      6957594.18
#Sta/Elev= 30
  4640.4  423.21  4652.7  422.65  4659.3  421.27  4667.0  420.96  4673.6  419.74
  4681.3  419.80  4687.9  418.38  4695.6  418.32  4702.2  417.09  4744.5  414.34
  4850.9  410.07  4922.0  408.69  4979.2  410.10  4985.8  409.88  4993.5  406.56
  4996.6  406.54  4997.1  405.74  5002.1  405.74  5002.6  406.54  5013.4  408.99
  5023.6  407.33  5033.9  407.94  5042.4  409.52  5047.5  408.11  5054.4  409.79
  5068.4  410.07  5198.1  411.95  5249.4  414.57  5271.3  416.62  5293.2  417.31
#Mann=4,-1,0
  4640.4    0.16       0  4744.5    0.05       0  4996.6    0.03       0
  5002.6    0.05       0
Bank Sta=4850.9,5068.4
Exp/Cntr=0.3,0.1

Type RM Length L Ch R = 1,1417,155,155,155
BEGIN DESCRIPTION:
Mapping XS 770e2bed
END DESCRIPTION:
XS GIS Cut Line= 3
      2949239.53      6957450.97      2949460.87      6957805.12
      2949871.17      6957602.57
#Sta/Elev= 30
  4616.9  427.10  4638.0  423.79  4653.3  422.96  4659.2  421.83  4668.7  421.22
  4674.6  419.44  4680.6  418.82  4689.9  418.49  4717.0  415.78  4784.2  412.42
  4790.1  411.25  4813.0  409.87  4878.6  407.67  4936.4  408.80  4978.8  408.40
  4987.2  406.47  4997.0  405.92  4997.5  405.12  5002.5  405.12  5003.0  405.92
  5009.5  408.13  5030.7  407.27  5045.4  407.61  5067.9  409.23  5127.0  409.22
  5196.1  409.87  5382.1  411.90  5427.0  413.63  5462.9  415.84  5492.1  418.76
#Mann=4,-1,0
  4616.9    0.16       0  4997.0    0.07       0  5003.0    0.16       0
  5127.0    0.05       0
Bank Sta=4813,5196.1
Exp/Cntr=0.3,0.1

Type RM Length L Ch R = 1,1262,129,129,129
BEGIN DESCRIPTION:
Mapping XS 6fbc3f61
END DESCRIPTION:
XS GIS Cut Line= 4
      2948989.52      6957521.27      2949341.08      6957893.66
      2949502.54      6957870.22      2949931.09      6957576.73
#Sta/Elev= 30
  4493.8  431.47  4570.9  426.62  4592.4  425.42  4641.8  425.12  4712.6  421.05
  4825.8  416.81  4832.7  415.49  4846.9  410.51  4853.9  409.70  4924.9  406.77
  4960.1  406.47  4967.0  407.43  4988.5  406.65  5002.6  407.65  5005.1  406.37
  5030.3  405.81  5030.8  405.01  5036.3  405.81  5050.3  406.98  5110.9  407.70
  5131.1  409.90  5151.4  408.12  5266.6  409.25  5278.5  409.70  5556.3  412.72
  5628.1  417.46  5634.2  418.78  5643.0  418.28  5670.0  421.20  5688.5  421.48
#Mann=5,-1,0
  4493.8    0.05       0  4570.9    0.16       0  5030.3    0.07       0
  5036.3    0.16       0  5266.6    0.05       0
Bank Sta=4853.9,5278.5
Exp/Cntr=0.3,0.1

Type RM Length L Ch R = 1,1133,48,48,48
BEGIN DESCRIPTION:
Mapping XS 6b15849c
END DESCRIPTION:
XS GIS Cut Line= 5
      2948901.21      6957711.29      2949152.92      6957900.51
      2949298.75      6958025.51      2949399.45      6958042.87
      2949780.69      6958042.87
#Sta/Elev= 30
  4562.5  421.08  4581.5  420.02  4589.8  417.83  4617.3  416.10  4725.2  416.79
  4731.5  417.96  4739.8  417.82  4746.0  420.24  4760.6  420.12  4775.2  417.69
  4796.0  417.27  4817.5  414.90  4825.2  413.04  4854.3  411.70  4860.6  410.21
  4867.5  410.78  4921.5  408.70  4992.8  407.39  4993.3  406.59  4998.3  406.59
  4998.8  407.39  5153.3  408.82  5177.2  407.73  5287.2  407.48  5329.8  408.70
  5387.2  412.14  5477.2  425.27  5517.2  429.50  5537.2  428.42  5552.9  429.01
#Mann=3,-1,0
  4562.5    0.16       0  4992.8    0.07       0  4998.8    0.16       0
Bank Sta=4921.5,5329.8
Exp/Cntr=0.3,0.1

Type RM Length L Ch R = 1,1085,163,163,163
BEGIN DESCRIPTION:
Mapping XS 4cd5b481
END DESCRIPTION:
XS GIS Cut Line= 5
      2948829.97      6957754.66      2949132.09      6957916.13
      2949250.14      6958044.61      2949380.35      6958075.86
      2949784.88      6958065.44
#Sta/Elev= 30
  4555.7  427.18  4610.9  422.44  4649.2  415.81  4671.1  414.27  4736.9  414.42
  4753.2  416.59  4758.9  414.72  4775.2  416.17  4780.8  414.70  4797.1  415.80
  4802.8  414.39  4819.1  414.92  4824.7  413.59  4841.0  413.49  4846.7  411.21
  4856.2  411.71  4868.6  408.92  4887.5  407.61  4927.7  406.38  5146.7  405.19
  5147.2  404.39  5152.7  405.19  5221.3  406.45  5331.3  405.95  5389.6  407.61
  5421.4  408.88  5441.4  410.95  5511.4  423.51  5561.4  430.19  5611.3  429.07
#Mann=3,-1,0
  4555.7    0.16       0  5146.7    0.07       0  5152.7    0.16       0
Bank Sta=4887.5,5389.6
Exp/Cntr=0.3,0.1

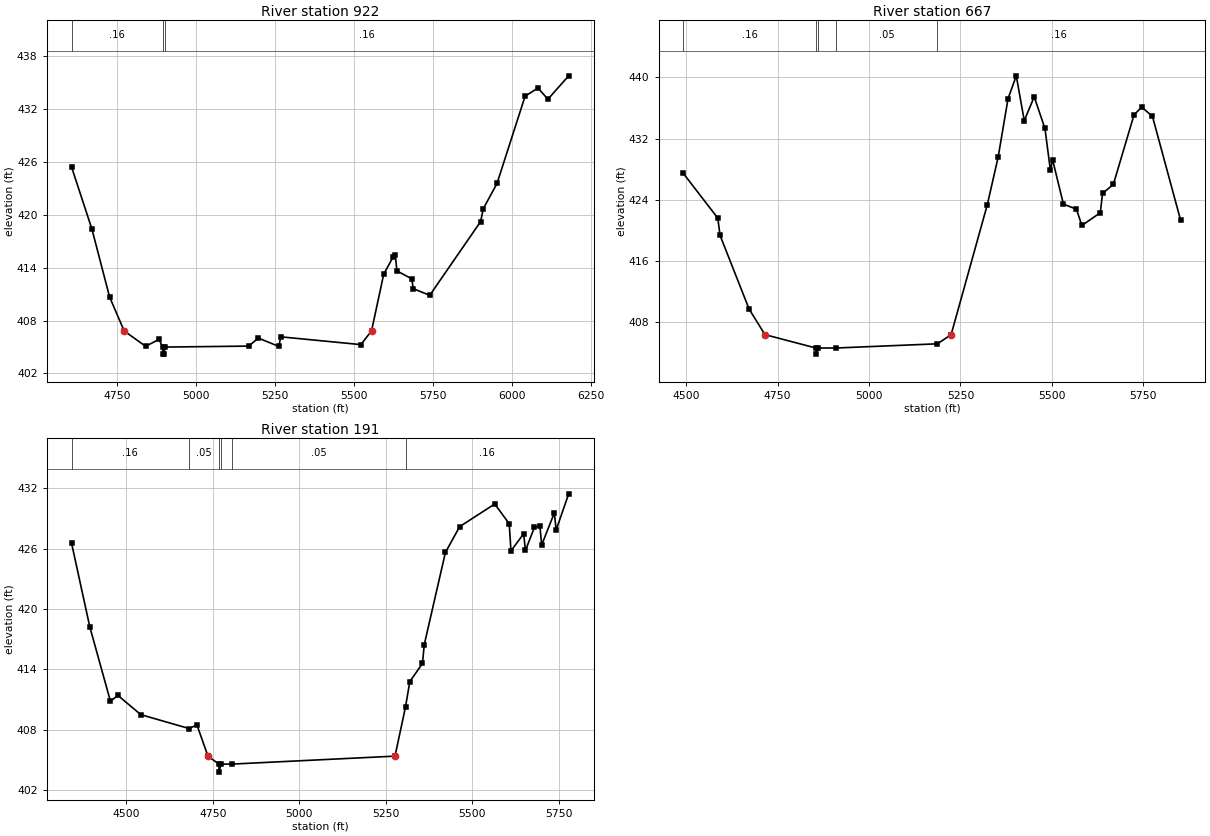
Type RM Length L Ch R = 1,922,255,255,255
BEGIN DESCRIPTION:
Mapping XS 50af0cd9
END DESCRIPTION:
XS GIS Cut Line= 3
      2948772.55      6957857.12      2949072.02      6958099.29
      2950240.64      6958323.13
#Sta/Elev= 30
  4605.4  425.42  4670.0  418.37  4726.0  410.67  4772.2  406.82  4840.0  405.08
  4882.7  405.86  4894.1  404.99  4894.6  404.19  4899.6  404.19  4900.1  404.99
  5166.7  405.10  5197.2  406.01  5261.7  405.07  5268.5  406.15  5521.9  405.27
  5555.8  406.82  5594.3  413.24  5624.8  415.26  5631.1  415.43  5636.2  413.63
  5683.1  412.73  5688.2  411.61  5740.2  410.86  5901.4  419.22  5909.9  420.69
  5953.4  423.55  6042.3  433.44  6083.0  434.37  6114.6  433.10  6180.4  435.75
#Mann=3,-1,0
  4605.4    0.16       0  4894.1    0.07       0  4900.1    0.16       0
Bank Sta=4772.2,5555.8
Exp/Cntr=0.3,0.1

Type RM Length L Ch R = 1,667,476,476,476
BEGIN DESCRIPTION:
Mapping XS 42762563
END DESCRIPTION:
XS GIS Cut Line= 3
      2948673.61      6957924.85      2949001.71      6958367.52
      2949661.60      6958835.16
#Sta/Elev= 30
  4492.3  427.43  4586.4  421.59  4592.6  419.33  4672.0  409.69  4715.4  406.34
  4854.7  404.59  4855.2  403.79  4860.7  404.59  4909.0  404.59  5187.1  405.14
  5224.6  406.34  5323.7  423.37  5353.3  429.60  5380.3  437.23  5402.8  440.21
  5424.6  434.35  5451.8  437.46  5481.2  433.32  5496.0  427.89  5502.1  429.23
  5531.7  423.42  5567.3  422.76  5582.1  420.63  5632.6  422.29  5638.7  424.82
  5668.3  426.00  5724.8  435.10  5746.0  436.12  5775.3  434.89  5852.1  421.34
#Mann=5,-1,0
  4492.3    0.16       0  4854.7   0.035       0  4860.7    0.16       0
  4909.0    0.05       0  5187.1    0.16       0
Bank Sta=4715.4,5224.6
Exp/Cntr=0.3,0.1

Type RM Length L Ch R = 1,191,0,0,0
BEGIN DESCRIPTION:
UNT 016 IN DRY CR WATERSHED 1.0
END DESCRIPTION:
XS GIS Cut Line= 3
      2948306.93      6958039.42      2948624.42      6958615.87
      2949381.25      6958799.53
#Sta/Elev= 30
  4341.9  426.56  4394.7  418.23  4454.3  410.84  4476.1  411.41  4542.3  409.50
  4681.9  408.12  4704.3  408.49  4736.2  405.38  4767.7  404.59  4768.2  403.79
  4773.7  404.59  4806.4  404.59  5276.8  405.38  5307.3  410.29  5319.6  412.79
  5356.2  414.59  5361.3  416.45  5422.5  425.62  5463.7  428.19  5565.1  430.44
  5606.9  428.48  5612.0  425.78  5648.7  427.48  5653.8  425.82  5679.8  428.12
  5695.6  428.24  5700.7  426.37  5737.4  429.56  5742.5  427.85  5778.8  431.45
#Mann=6,-1,0
  4341.9    0.16       0  4681.9    0.05       0  4767.7   0.033       0
  4773.7    0.05       0  4806.4    0.05       0  5307.3    0.16       0
Bank Sta=4736.2,5276.8
Exp/Cntr=0.3,0.1

Chan Stop Cuts=-1