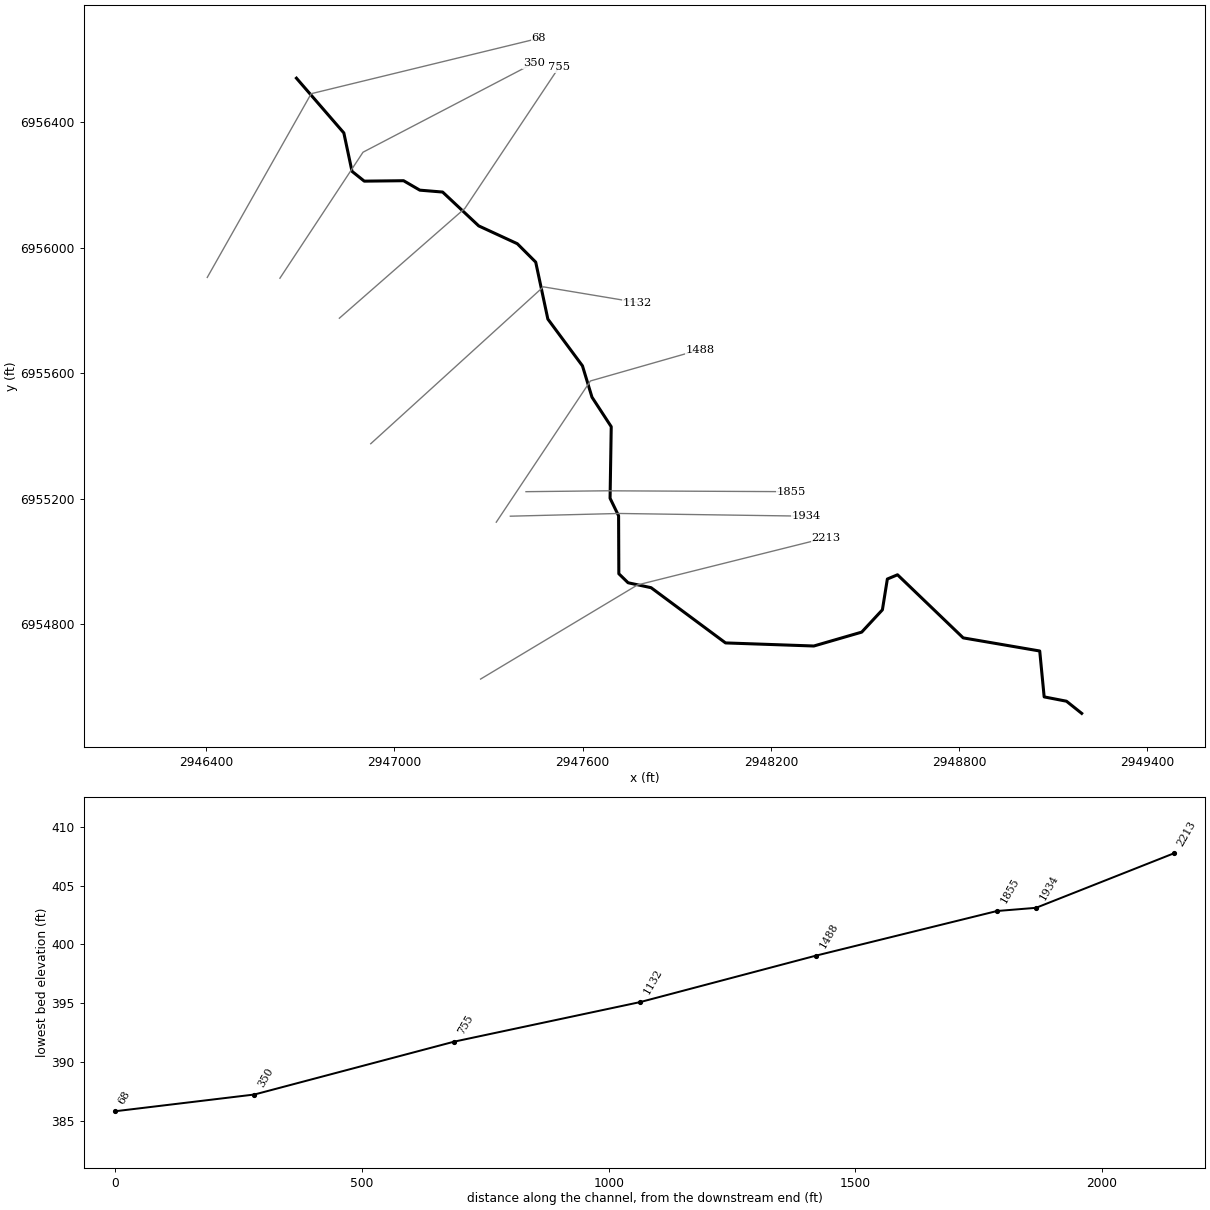
--- UNT 017 IN DRY CR WATERSHED.prj (project) ---

Proj Title=UNT 017 IN DRY CR WATERSHED Base Level Engineering
Current Plan=p01
Default Exp/Contr=0.3,0.1
English Units
Geom File=g01
Flow File=f01
Plan File=p01
BEGIN DESCRIPTION:
UNT 017 IN DRY CR WATERSHED
END DESCRIPTION:

--- UNT 017 IN DRY CR WATERSHED.p01 (plan) ---

Plan Title=Multiple Run
Short Identifier=Multiple
Geom File=g01
Flow File=f01
Subcritical Flow
K Sum by GR= 0
Std Step Tol= 0.01
Critical Tol= 0.01
Num of Std Step Trials= 20
Max Error Tol= 0.3
Flow Tol Ratio= 0.001
Split Flow NTrial= 30
Split Flow Tol= 0.02
Split Flow Ratio= 0.02
Log Output Level= 0
Friction Slope Method= 1
Unsteady Friction Slope Method= 2
Unsteady Bridges Friction Slope Method= 1
Parabolic Critical Depth
Global Vel Dist=  1 , 1 , 1
Global Log Level= 0
CheckData=True
Encroach Param= -1, 0, 0, 0
BEGIN DESCRIPTION:
Multiple Run
END DESCRIPTION:

--- UNT 017 IN DRY CR WATERSHED.f01 (steady flow) ---

Flow Title=Multiple
Number of Profiles=7
Profile Names=10-year,25-year,50-year,1pct_min,100-year,1pct_plu,500-year
River Rch & RM= UNT 017 IN DRY C,Reach-1,2213
     496     667     808     488     974    1944    1416
Boundary for River Rch & Prof#=UNT 017 IN DRY C,Reach-1,1
Up Type=0
Dn Type=3
Dn Slope=0.005
Boundary for River Rch & Prof#=UNT 017 IN DRY C,Reach-1,2
Up Type=0
Dn Type=3
Dn Slope=0.005
Boundary for River Rch & Prof#=UNT 017 IN DRY C,Reach-1,3
Up Type=0
Dn Type=3
Dn Slope=0.005
Boundary for River Rch & Prof#=UNT 017 IN DRY C,Reach-1,4
Up Type=0
Dn Type=3
Dn Slope=0.005
Boundary for River Rch & Prof#=UNT 017 IN DRY C,Reach-1,5
Up Type=0
Dn Type=3
Dn Slope=0.005
Boundary for River Rch & Prof#=UNT 017 IN DRY C,Reach-1,6
Up Type=0
Dn Type=3
Dn Slope=0.005
Boundary for River Rch & Prof#=UNT 017 IN DRY C,Reach-1,7
Up Type=0
Dn Type=3
Dn Slope=0.005

--- UNT 017 IN DRY CR WATERSHED.g01 (geometry) ---

Geom Title=Existing Conditions

River Reach=UNT 017 IN DRY C,Reach-1
Reach XY= 30
      2949190.59      6954515.71      2949142.14      6954554.45
      2949070.99      6954568.24      2949056.85      6954714.49
      2948812.96      6954756.30      2948603.67      6954957.40
      2948571.27      6954943.84      2948555.50      6954845.75
      2948489.55      6954774.64      2948337.02      6954730.41
      2948055.60      6954740.24      2947818.34      6954916.25
      2947745.02      6954931.97      2947715.59      6954960.71
      2947714.80      6955145.43      2947687.66      6955201.20
      2947691.36      6955429.29      2947630.01      6955523.33
      2947599.67      6955623.19      2947489.37      6955772.27
      2947450.71      6955953.71      2947392.10      6956012.36
      2947269.10      6956069.13      2947154.06      6956177.03
      2947081.44      6956183.05      2947029.65      6956213.16
      2946904.37      6956211.79      2946865.30      6956243.04
      2946839.26      6956365.44      2946688.22      6956539.92

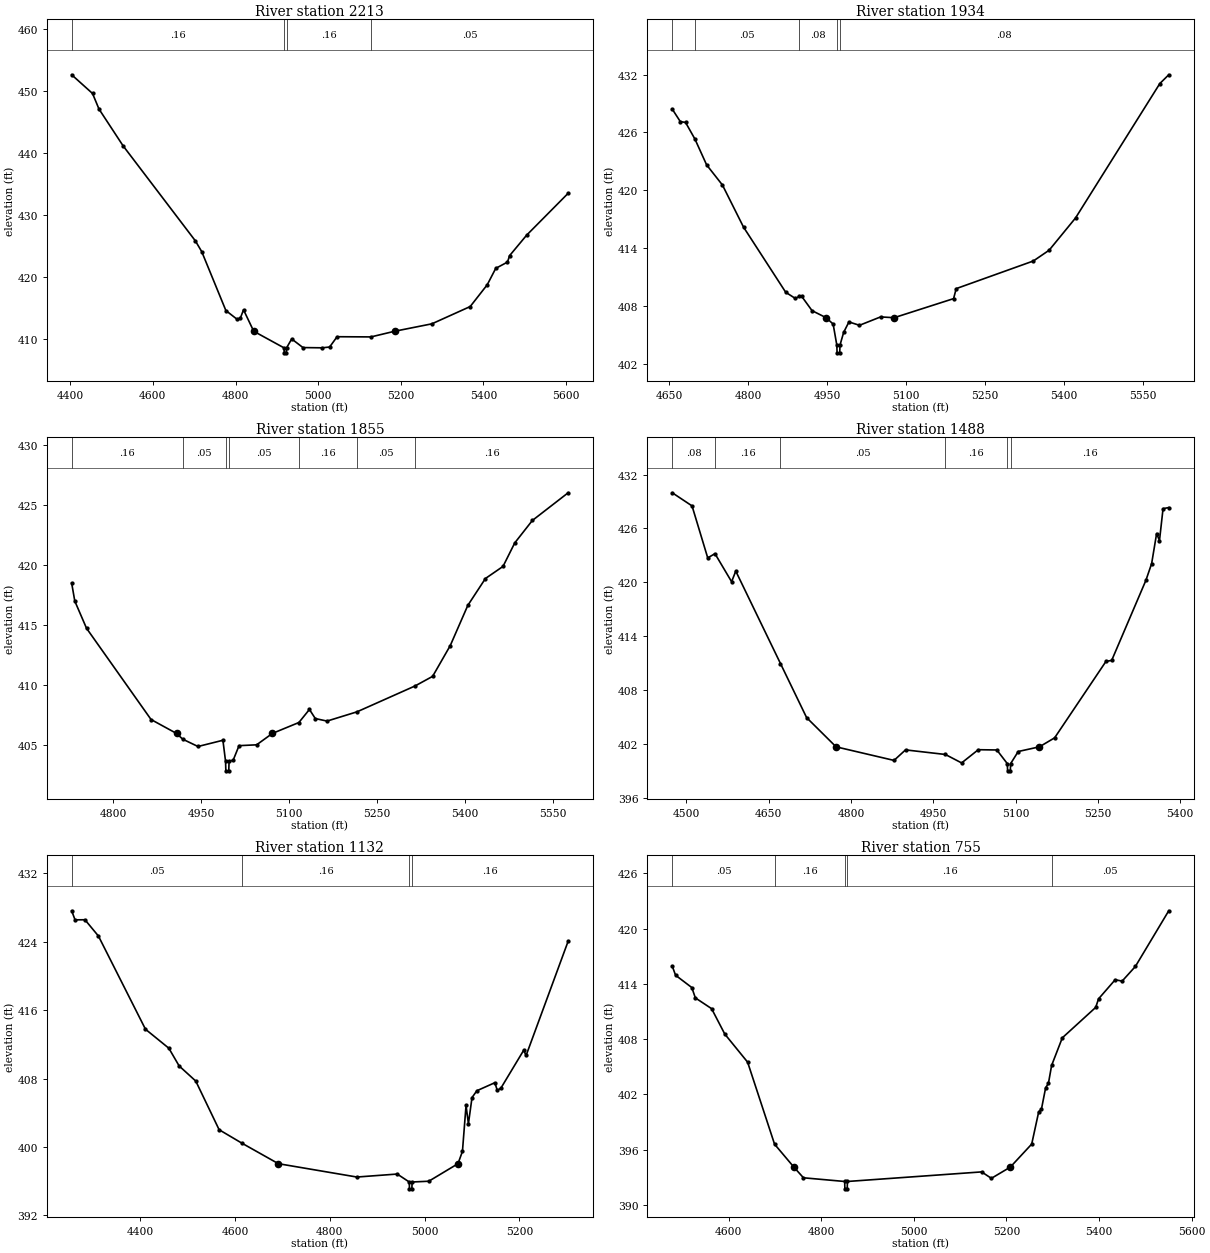
Type RM Length L Ch R = 1,2213,279,279,279
BEGIN DESCRIPTION:
UNT 017 IN DRY CR WATERSHED 6.0
END DESCRIPTION:
XS GIS Cut Line= 3
      2947275.02      6954625.01      2947775.00      6954925.00
      2948374.96      6955074.99
#Sta/Elev= 30
  4403.5  452.59  4454.0  449.57  4469.6  447.06  4527.9  441.13  4702.8  425.80
  4718.3  424.05  4776.7  414.55  4803.9  413.14  4811.6  413.31  4819.4  414.67
  4844.1  411.21  4917.5  408.53  4918.0  407.73  4923.0  407.73  4923.5  408.53
  4936.0  409.97  4963.2  408.58  5009.8  408.54  5027.8  408.67  5045.8  410.33
  5127.9  410.30  5184.9  411.21  5275.2  412.41  5368.0  415.20  5409.2  418.71
  5429.8  421.36  5458.2  422.37  5463.3  423.41  5504.5  426.71  5605.0  433.47
#Mann=4,-1,0
  4403.5    0.16       0  4917.5    0.07       0  4923.5    0.16       0
  5127.9    0.05       0
Bank Sta=4844.1,5184.9
Exp/Cntr=0.3,0.1

Type RM Length L Ch R = 1,1934,79,79,79
BEGIN DESCRIPTION:
Mapping XS 530e8841
END DESCRIPTION:
XS GIS Cut Line= 3
      2947369.80      6955144.09      2947716.99      6955152.76
      2948311.93      6955144.11
#Sta/Elev= 30
  4656.2  428.42  4671.4  427.13  4681.4  427.04  4699.2  425.31  4721.4  422.63
  4751.4  420.54  4791.4  416.17  4871.5  409.40  4889.7  408.76  4897.2  408.97
  4901.5  409.00  4921.5  407.49  4948.2  406.76  4961.5  406.10  4968.5  403.91
  4969.0  403.11  4974.0  403.11  4974.5  403.91  4981.5  405.24  4991.5  406.32
  5011.5  405.97  5051.5  406.84  5077.3  406.76  5190.1  408.74  5195.1  409.78
  5341.5  412.65  5371.5  413.77  5421.6  417.12  5581.6  431.08  5598.5  431.99
#Mann=5,-1,0
  4656.2    0.08       0  4699.2    0.05       0  4897.2    0.08       0
  4968.5    0.07       0  4974.5    0.08       0
Bank Sta=4948.2,5077.3
Exp/Cntr=0.3,0.1

Type RM Length L Ch R = 1,1855,367,367,367
BEGIN DESCRIPTION:
UNT 017 IN DRY CR WATERSHED 5.0
END DESCRIPTION:
XS GIS Cut Line= 3
      2947419.73      6955222.21      2947675.00      6955225.00
      2948266.01      6955222.21
#Sta/Elev= 30
  4729.7  418.49  4735.0  417.00  4755.0  414.73  4865.0  407.12  4908.4  405.96
  4919.0  405.48  4945.0  404.87  4987.5  405.39  4992.0  403.64  4992.5  402.84
  4997.5  402.84  4998.0  403.64  5005.0  403.73  5015.0  404.94  5045.0  405.01
  5071.8  405.96  5117.0  406.87  5135.0  407.96  5145.0  407.20  5165.0  406.99
  5216.0  407.76  5315.1  409.92  5345.0  410.72  5375.0  413.28  5405.0  416.64
  5435.0  418.88  5465.0  419.89  5485.0  421.85  5515.0  423.72  5576.0  426.03
#Mann=7,-1,0
  4729.7    0.16       0  4919.0    0.05       0  4992.0    0.03       0
  4998.0    0.05       0  5117.0    0.16       0  5216.0    0.05       0
  5315.1    0.16       0
Bank Sta=4908.4,5071.8
Exp/Cntr=0.3,0.1

Type RM Length L Ch R = 1,1488,356,356,356
BEGIN DESCRIPTION:
UNT 017 IN DRY CR WATERSHED 4.0
END DESCRIPTION:
XS GIS Cut Line= 3
      2947325.02      6955125.02      2947625.00      6955575.00
      2947974.99      6955675.00
#Sta/Elev= 30
  4474.2  429.97  4510.2  428.51  4538.8  422.73  4552.0  423.20  4582.3  420.08
  4589.9  421.26  4671.4  410.98  4719.0  404.97  4772.7  401.72  4878.3  400.21
  4899.3  401.38  4971.9  400.87  5001.5  399.93  5031.9  401.40  5065.7  401.37
  5084.8  399.85  5085.3  399.05  5090.3  399.05  5090.8  399.85  5104.7  401.20
  5143.3  401.72  5171.0  402.72  5264.6  411.22  5275.0  411.33  5337.4  420.24
  5347.8  422.09  5356.9  425.44  5362.1  424.65  5368.6  428.20  5379.0  428.33
#Mann=6,-1,0
  4474.2    0.08       0  4552.0    0.16       0  4671.4    0.05       0
  4971.9    0.16       0  5084.8    0.07       0  5090.8    0.16       0
Bank Sta=4772.7,5143.3
Exp/Cntr=0.3,0.1

Type RM Length L Ch R = 1,1132,377,377,377
BEGIN DESCRIPTION:
UNT 017 IN DRY CR WATERSHED 3.0
END DESCRIPTION:
XS GIS Cut Line= 3
      2946925.03      6955375.03      2947475.00      6955875.00
      2947775.00      6955825.00
#Sta/Elev= 30
  4255.5  427.62  4262.6  426.56  4283.5  426.57  4311.9  424.67  4411.2  413.77
  4460.5  411.55  4482.2  409.48  4517.3  407.71  4566.6  402.02  4614.6  400.45
  4691.6  398.05  4857.2  396.49  4942.3  396.84  4967.7  395.91  4968.2  395.11
  4973.2  395.11  4973.7  395.91  5008.9  396.00  5070.5  398.05  5079.9  399.49
  5087.5  404.86  5092.5  402.72  5100.1  405.78  5110.3  406.58  5148.3  407.52
  5153.4  406.62  5161.0  406.88  5209.1  411.31  5214.2  410.70  5302.9  424.06
#Mann=4,-1,0
  4255.5    0.05       0  4614.6    0.16       0  4967.7    0.07       0
  4973.7    0.16       0
Bank Sta=4691.6,5070.5
Exp/Cntr=0.3,0.1

Type RM Length L Ch R = 1,755,405,405,405
BEGIN DESCRIPTION:
UNT 017 IN DRY CR WATERSHED 2.0
END DESCRIPTION:
XS GIS Cut Line= 3
      2946825.03      6955775.03      2947225.00      6956125.00
      2947525.00      6956575.00
#Sta/Elev= 30
  4478.2  415.93  4485.3  414.95  4520.4  413.61  4528.0  412.49  4563.1  411.32
  4591.6  408.56  4640.9  405.51  4699.1  396.60  4740.8  394.11  4761.5  392.95
  4850.5  392.55  4851.0  391.75  4856.0  391.75  4856.5  392.55  5146.4  393.59
  5167.4  392.89  5208.3  394.11  5254.5  396.61  5269.6  400.11  5275.6  400.42
  5284.6  402.73  5290.6  403.20  5297.5  405.15  5320.6  408.15  5392.8  411.46
  5398.8  412.38  5434.8  414.46  5449.8  414.31  5478.4  415.90  5550.5  421.95
#Mann=5,-1,0
  4478.2    0.05       0  4699.1    0.16       0  4850.5    0.07       0
  4856.5    0.16       0  5297.5    0.05       0
Bank Sta=4740.8,5208.3
Exp/Cntr=0.3,0.1

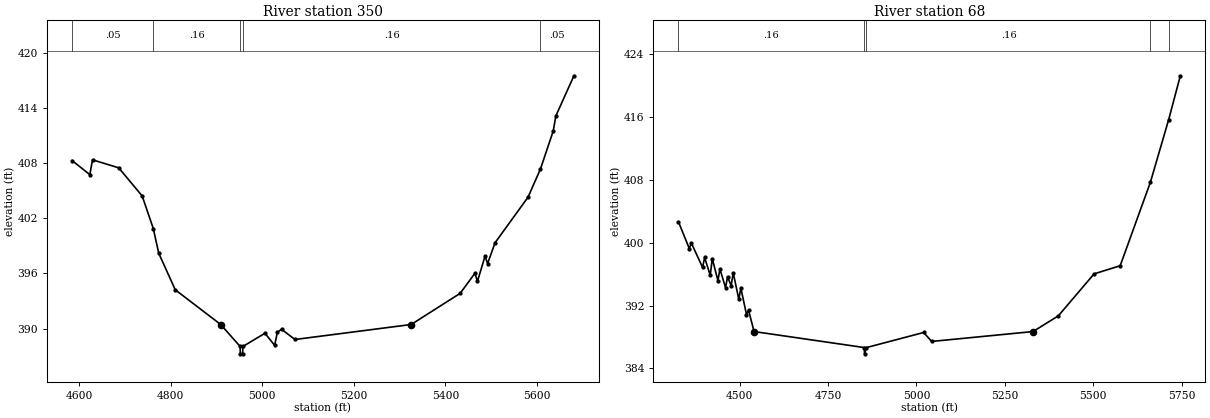
Type RM Length L Ch R = 1,350,282,282,282
BEGIN DESCRIPTION:
Mapping XS 31e65a6e
END DESCRIPTION:
XS GIS Cut Line= 3
      2946635.58      6955902.48      2946900.34      6956303.95
      2947445.01      6956588.22
#Sta/Elev= 30
  4585.0  408.28  4623.7  406.75  4629.6  408.36  4686.8  407.49  4738.0  404.43
  4762.3  400.88  4774.2  398.19  4810.3  394.22  4909.4  390.45  4951.8  388.06
  4952.3  387.26  4957.3  387.26  4957.8  388.06  5006.0  389.50  5027.1  388.18
  5033.1  389.61  5042.2  389.93  5071.4  388.82  5325.0  390.45  5432.1  393.84
  5464.2  396.02  5469.8  395.15  5486.3  397.88  5491.9  397.08  5508.3  399.35
  5580.2  404.30  5607.3  407.37  5635.2  411.50  5640.9  413.14  5680.3  417.50
#Mann=5,-1,0
  4585.0    0.05       0  4762.3    0.16       0  4951.8    0.07       0
  4957.8    0.16       0  5607.3    0.05       0
Bank Sta=4909.4,5325
Exp/Cntr=0.3,0.1

Type RM Length L Ch R = 1,68,0,0,0
BEGIN DESCRIPTION:
UNT 017 IN DRY CR WATERSHED 1.0
END DESCRIPTION:
XS GIS Cut Line= 3
      2946404.02      6955904.96      2946735.10      6956490.44
      2947460.13      6956666.88
#Sta/Elev= 30
  4327.4  402.66  4358.0  399.26  4363.8  399.96  4395.6  396.85  4401.3  398.12
  4417.2  395.84  4422.9  397.97  4438.9  395.18  4444.6  396.64  4460.5  394.27
  4466.2  395.65  4476.4  394.52  4482.1  396.18  4498.0  392.79  4503.8  394.22
  4519.7  390.84  4525.4  391.41  4541.1  388.68  4852.9  386.64  4853.4  385.84
  4858.9  386.64  5020.5  388.56  5043.3  387.42  5329.7  388.68  5401.3  390.68
  5502.3  396.03  5576.2  397.07  5661.8  407.74  5713.3  415.70  5746.2  421.28
#Mann=5,-1,0
  4327.4    0.16       0  4852.9    0.07       0  4858.9    0.16       0
  5661.8    0.05       0  5713.3    0.16       0
Bank Sta=4541.1,5329.7
Exp/Cntr=0.3,0.1

Chan Stop Cuts=-1