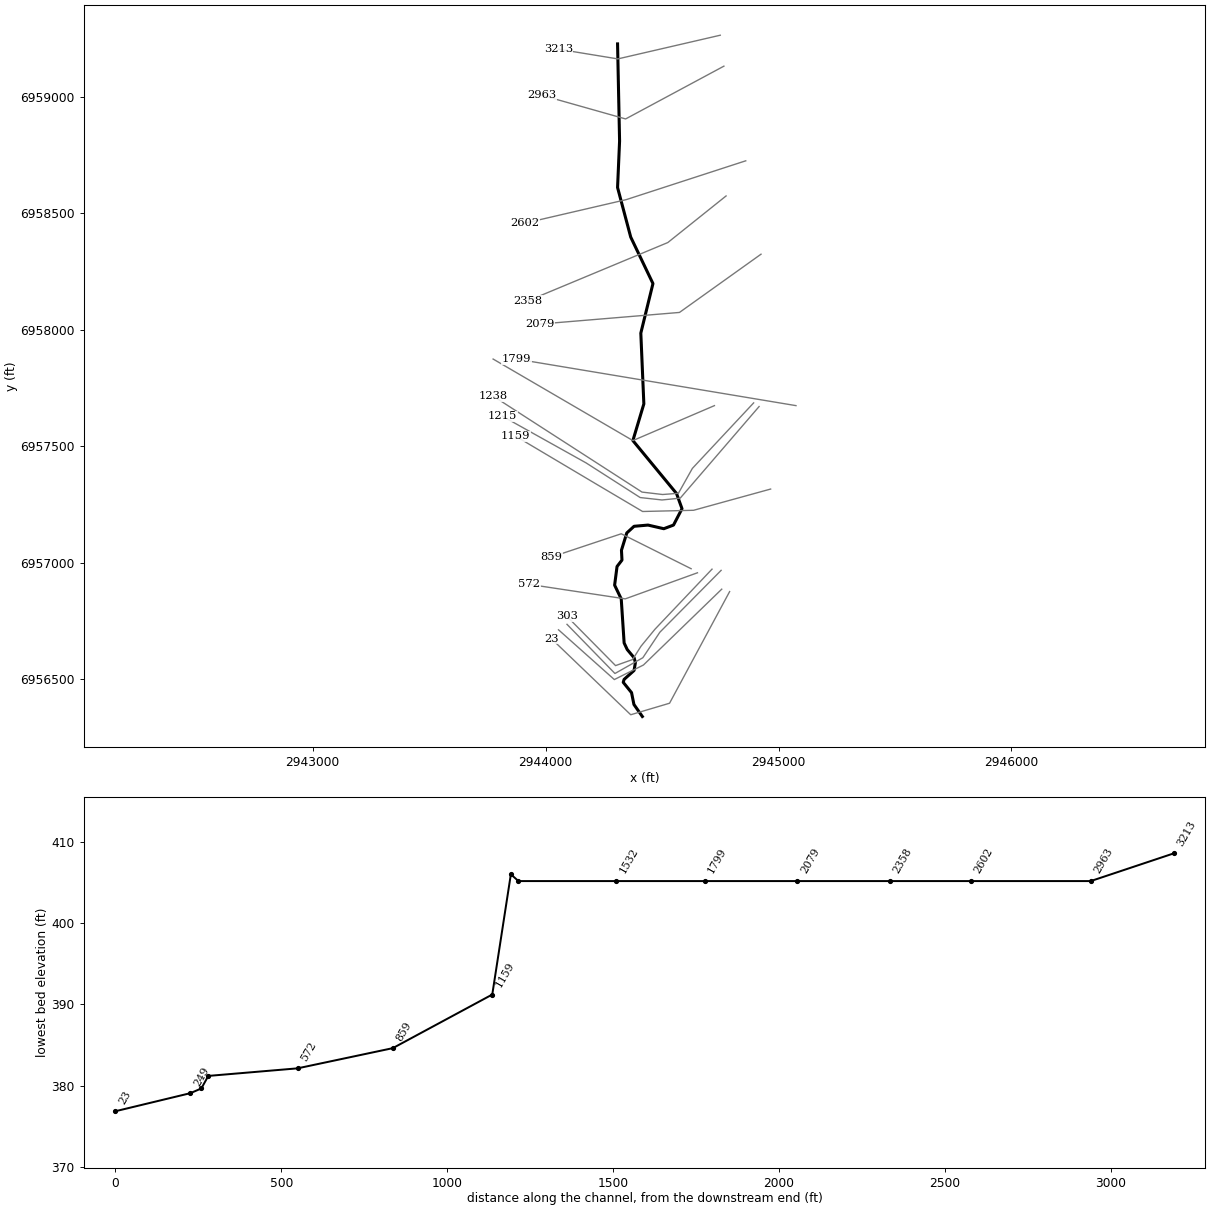
--- UNT 018 IN DRY CR WATERSHED.prj (project) ---

Proj Title=UNT 018 IN DRY CR WATERSHED Base Level Engineering
Current Plan=p01
Default Exp/Contr=0.3,0.1
English Units
Geom File=g01
Flow File=f01
Plan File=p01
BEGIN DESCRIPTION:
UNT 018 IN DRY CR WATERSHED
END DESCRIPTION:

--- UNT 018 IN DRY CR WATERSHED.p01 (plan) ---

Plan Title=Multiple Run
Short Identifier=Multiple
Geom File=g01
Flow File=f01
Subcritical Flow
K Sum by GR= 0
Std Step Tol= 0.01
Critical Tol= 0.01
Num of Std Step Trials= 20
Max Error Tol= 0.3
Flow Tol Ratio= 0.001
Split Flow NTrial= 30
Split Flow Tol= 0.02
Split Flow Ratio= 0.02
Log Output Level= 0
Friction Slope Method= 1
Unsteady Friction Slope Method= 2
Unsteady Bridges Friction Slope Method= 1
Parabolic Critical Depth
Global Vel Dist=  1 , 1 , 1
Global Log Level= 0
CheckData=True
Encroach Param= -1, 0, 0, 0
BEGIN DESCRIPTION:
Multiple Run
END DESCRIPTION:

--- UNT 018 IN DRY CR WATERSHED.f01 (steady flow) ---

Flow Title=Multiple
Number of Profiles=7
Profile Names=10-year,25-year,50-year,1pct_min,100-year,1pct_plu,500-year
River Rch & RM= UNT 018 IN DRY C,Reach-1,3213
     158     195     224     128     256     511     334
River Rch & RM= UNT 018 IN DRY C,Reach-1,1159
     218     277     323     188     375     749     506
Boundary for River Rch & Prof#=UNT 018 IN DRY C,Reach-1,1
Up Type=0
Dn Type=3
Dn Slope=0.005
Boundary for River Rch & Prof#=UNT 018 IN DRY C,Reach-1,2
Up Type=0
Dn Type=3
Dn Slope=0.005
Boundary for River Rch & Prof#=UNT 018 IN DRY C,Reach-1,3
Up Type=0
Dn Type=3
Dn Slope=0.005
Boundary for River Rch & Prof#=UNT 018 IN DRY C,Reach-1,4
Up Type=0
Dn Type=3
Dn Slope=0.005
Boundary for River Rch & Prof#=UNT 018 IN DRY C,Reach-1,5
Up Type=0
Dn Type=3
Dn Slope=0.005
Boundary for River Rch & Prof#=UNT 018 IN DRY C,Reach-1,6
Up Type=0
Dn Type=3
Dn Slope=0.005
Boundary for River Rch & Prof#=UNT 018 IN DRY C,Reach-1,7
Up Type=0
Dn Type=3
Dn Slope=0.005

--- UNT 018 IN DRY CR WATERSHED.g01 (geometry) ---

Geom Title=Existing Conditions

River Reach=UNT 018 IN DRY C,Reach-1
Reach XY= 30
      2944309.22      6959227.53      2944317.90      6958810.86
      2944309.22      6958611.21      2944365.65      6958398.54
      2944461.13      6958198.88      2944409.05      6957986.21
      2944422.07      6957682.39      2944375.00      6957525.00
      2944562.35      6957297.73      2944585.79      6957232.63
      2944549.33      6957162.31      2944507.67      6957146.69
      2944439.96      6957162.31      2944380.06      6957157.10
      2944348.81      6957128.46      2944325.94      6957054.36
      2944328.15      6957012.05      2944306.97      6956984.47
      2944296.60      6956904.42      2944325.00      6956845.43
      2944337.43      6956656.26      2944350.73      6956628.06
      2944380.21      6956592.84      2944385.75      6956572.17
      2944380.11      6956538.37      2944337.29      6956499.92
      2944333.56      6956487.41      2944369.26      6956443.10
      2944379.44      6956392.34      2944415.59      6956340.71

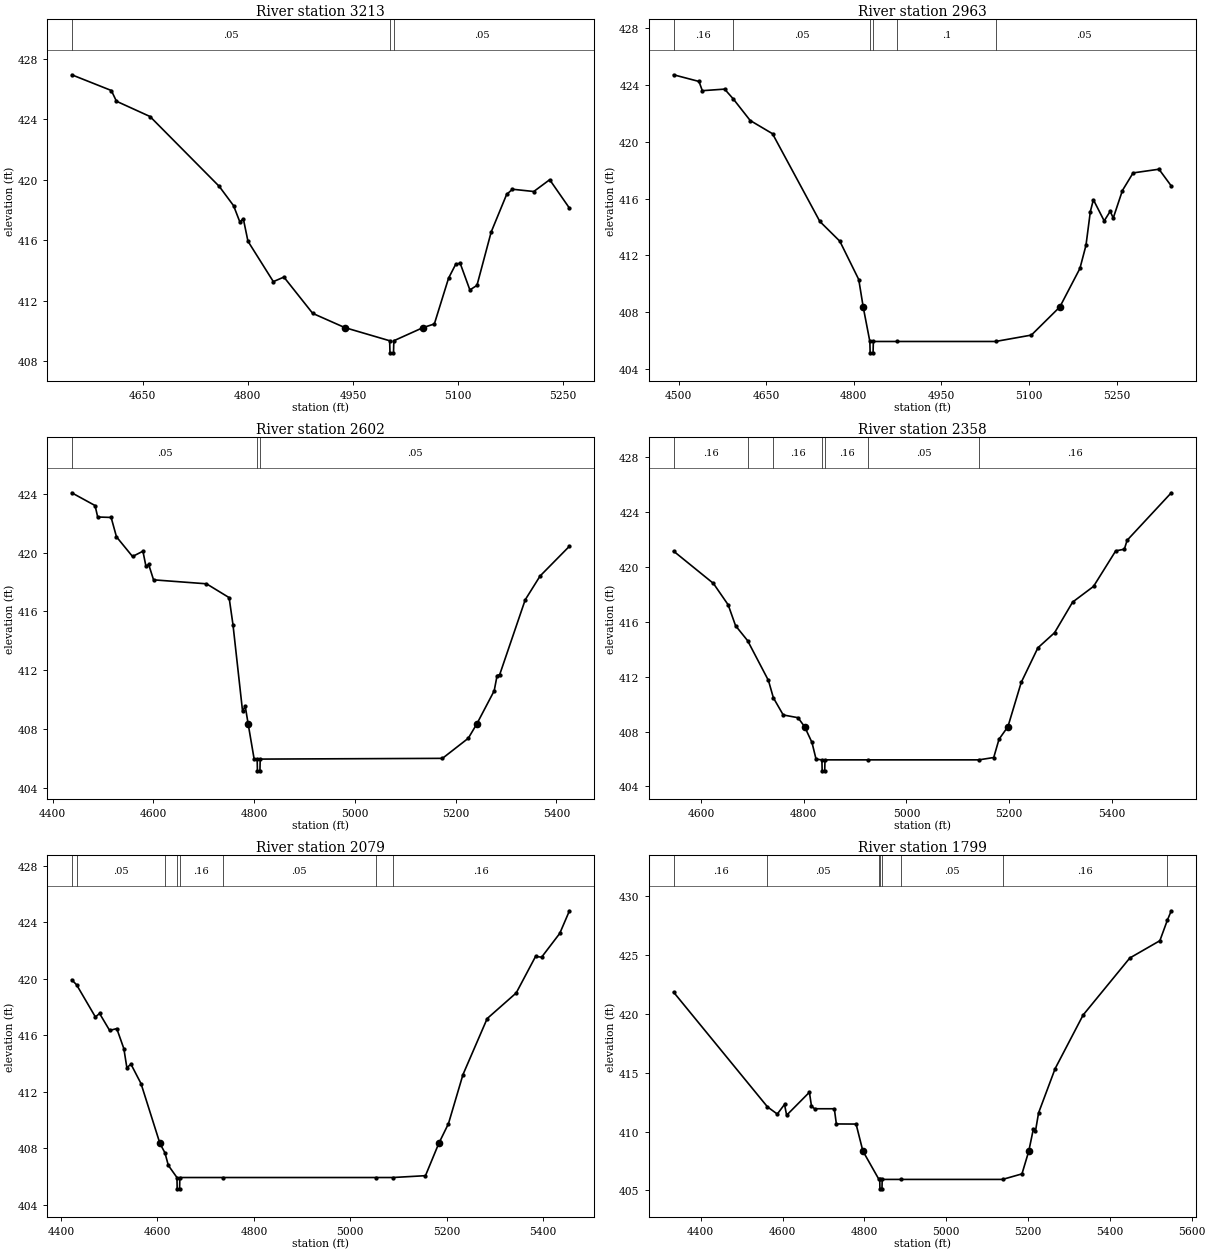
Type RM Length L Ch R = 1,3213,250,250,250
BEGIN DESCRIPTION:
UNT 018 IN DRY CR WATERSHED 8.0
END DESCRIPTION:
XS GIS Cut Line= 3
      2944750.05      6959264.87      2944310.35      6959163.17
      2944054.75      6959204.97
#Sta/Elev= 30
  4548.7  426.93  4605.2  425.89  4612.5  425.18  4660.4  424.17  4759.2  419.55
  4779.7  418.27  4788.5  417.21  4793.6  417.40  4800.2  415.92  4836.4  413.25
  4851.5  413.55  4892.6  411.15  4938.4  410.21  5002.4  409.34  5002.9  408.54
  5007.9  408.54  5008.4  409.34  5050.1  410.21  5066.2  410.45  5086.5  413.48
  5096.6  414.39  5103.0  414.47  5116.9  412.70  5127.0  413.00  5147.3  416.53
  5169.4  419.02  5177.7  419.36  5208.1  419.21  5230.8  419.99  5259.0  418.11
#Mann=3,-1,0
  4548.7    0.05       0  5002.4    0.03       0  5008.4    0.05       0
Bank Sta=4938.4,5050.1
Exp/Cntr=0.3,0.1

Type RM Length L Ch R = 1,2963,361,361,361
BEGIN DESCRIPTION:
Mapping XS 899d6e01
END DESCRIPTION:
XS GIS Cut Line= 3
      2944765.67      6959132.05      2944343.80      6958905.49
      2943984.43      6959007.05
#Sta/Elev= 30
  4491.5  424.72  4535.0  424.25  4540.7  423.60  4578.9  423.71  4593.7  423.02
  4622.7  421.50  4660.9  420.57  4742.0  414.39  4776.2  413.00  4808.6  410.30
  4816.2  408.37  4827.6  405.94  4828.1  405.14  4833.1  405.14  4833.6  405.94
  4874.7  405.94  5042.8  405.94  5104.2  406.39  5152.9  408.37  5187.3  411.08
  5197.7  412.71  5205.2  415.09  5210.4  415.92  5228.9  414.43  5239.2  415.11
  5244.4  414.63  5260.1  416.57  5278.4  417.81  5322.7  418.07  5343.8  416.89
#Mann=6,-1,0
  4491.5    0.16       0  4593.7    0.05       0  4827.6    0.07       0
  4833.6    0.05       0  4874.7     0.1       0  5042.8    0.05       0
Bank Sta=4816.2,5152.9
Exp/Cntr=0.3,0.1

Type RM Length L Ch R = 1,2602,244,244,244
BEGIN DESCRIPTION:
Mapping XS ea6da996
END DESCRIPTION:
XS GIS Cut Line= 3
      2944859.41      6958725.80      2944346.40      6958559.14
      2943909.43      6958457.70
#Sta/Elev= 30
  4438.0  424.08  4484.3  423.21  4489.5  422.43  4516.2  422.40  4526.8  421.08
  4558.7  419.74  4579.3  420.10  4585.4  419.06  4590.7  419.20  4600.4  418.15
  4705.5  417.88  4750.4  416.94  4758.1  415.09  4777.1  409.20  4782.4  409.54
  4788.1  408.36  4800.1  405.94  4806.1  405.94  4806.6  405.14  4811.6  405.14
  4812.1  405.94  5173.9  405.99  5225.2  407.36  5242.5  408.36  5276.6  410.59
  5282.4  411.63  5287.6  411.70  5338.2  416.79  5367.7  418.41  5426.0  420.44
#Mann=3,-1,0
  4438.0    0.05       0  4806.1   0.033       0  4812.1    0.05       0
Bank Sta=4788.1,5242.5
Exp/Cntr=0.3,0.1

Type RM Length L Ch R = 1,2358,279,279,279
BEGIN DESCRIPTION:
UNT 018 IN DRY CR WATERSHED 7.0
END DESCRIPTION:
XS GIS Cut Line= 3
      2944774.97      6958574.98      2944525.00      6958375.00
      2943925.02      6958125.01
#Sta/Elev= 30
  4546.1  421.14  4623.7  418.79  4652.5  417.23  4666.9  415.71  4690.4  414.62
  4731.0  411.72  4740.6  410.46  4759.8  409.21  4788.6  409.01  4801.4  408.36
  4815.8  407.21  4823.8  405.99  4835.2  405.94  4835.7  405.14  4840.7  405.14
  4841.2  405.94  4925.9  405.94  5141.2  405.94  5170.1  406.11  5180.4  407.44
  5197.8  408.36  5223.7  411.58  5256.2  414.10  5288.7  415.20  5323.9  417.43
  5364.6  418.57  5407.9  421.16  5424.7  421.28  5430.1  421.93  5516.2  425.39
#Mann=7,-1,0
  4546.1    0.16       0  4690.4    0.05       0  4740.6    0.16       0
  4835.2   0.033       0  4841.2    0.16       0  4925.9    0.05       0
  5141.2    0.16       0
Bank Sta=4801.4,5197.8
Exp/Cntr=0.3,0.1

Type RM Length L Ch R = 1,2079,280,280,280
BEGIN DESCRIPTION:
UNT 018 IN DRY CR WATERSHED 6.0
END DESCRIPTION:
XS GIS Cut Line= 3
      2944924.97      6958324.98      2944575.00      6958075.00
      2943974.96      6958025.00
#Sta/Elev= 30
  4422.2  419.92  4432.2  419.57  4471.3  417.29  4479.9  417.54  4500.8  416.34
  4515.6  416.47  4530.3  415.05  4536.5  413.71  4545.1  413.95  4565.9  412.58
  4605.1  408.35  4615.6  407.68  4622.5  406.80  4640.4  405.94  4640.9  405.14
  4645.9  405.14  4646.4  405.94  4735.3  405.94  5052.9  405.94  5088.0  405.94
  5155.8  406.07  5183.4  408.35  5203.5  409.75  5233.6  413.22  5283.8  417.18
  5344.0  418.99  5384.1  421.57  5396.7  421.52  5434.3  423.20  5454.4  424.80
#Mann=8,-1,0
  4422.2    0.16       0  4432.2    0.05       0  4615.6    0.16       0
  4640.4   0.033       0  4646.4    0.16       0  4735.3    0.05       0
  5052.9    0.07       0  5088.0    0.16       0
Bank Sta=4605.1,5183.4
Exp/Cntr=0.3,0.1

Type RM Length L Ch R = 1,1799,267,267,267
BEGIN DESCRIPTION:
UNT 018 IN DRY CR WATERSHED 5.0
END DESCRIPTION:
XS GIS Cut Line= 3
      2945075.02      6957675.00      2944475.00      6957775.00
      2943874.98      6957875.00
#Sta/Elev= 30
  4333.6  421.84  4563.1  412.10  4587.1  411.49  4604.8  412.31  4609.9  411.39
  4665.6  413.34  4670.7  412.16  4678.3  411.94  4726.5  411.94  4731.5  410.65
  4779.7  410.64  4796.3  408.35  4835.4  405.95  4837.5  405.94  4838.0  405.14
  4843.0  405.14  4843.5  405.94  4888.3  405.94  5137.7  405.94  5185.2  406.41
  5201.9  408.35  5213.1  410.23  5218.2  410.04  5225.8  411.59  5266.3  415.35
  5334.7  419.90  5448.8  424.74  5522.3  426.21  5540.8  427.97  5550.2  428.75
#Mann=8,-1,0
  4333.6    0.16       0  4563.1    0.05       0  4835.4    0.16       0
  4837.5   0.033       0  4843.5    0.16       0  4888.3    0.05       0
  5137.7    0.16       0  5540.8    0.05       0
Bank Sta=4796.3,5201.9
Exp/Cntr=0.3,0.1

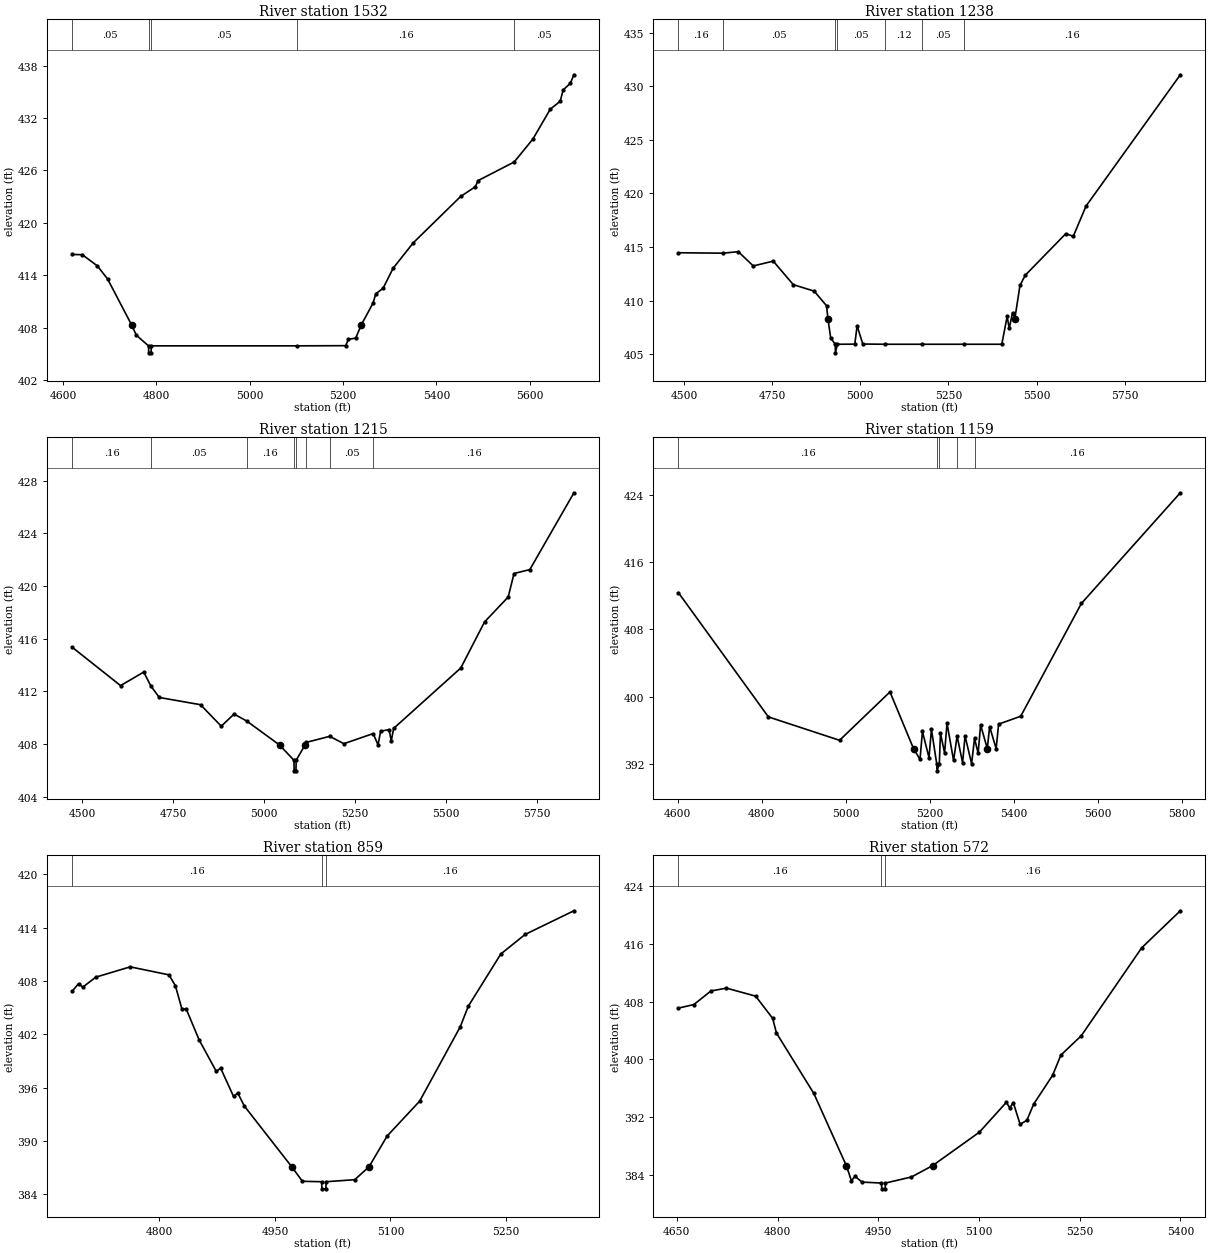
Type RM Length L Ch R = 1,1532,294,294,294
BEGIN DESCRIPTION:
UNT 018 IN DRY CR WATERSHED 4.0
END DESCRIPTION:
XS GIS Cut Line= 3
      2944725.01      6957675.00      2944375.00      6957525.00
      2943775.02      6957874.99
#Sta/Elev= 30
  4619.2  416.39  4641.0  416.37  4673.6  415.08  4695.4  413.58  4746.6  408.35
  4757.0  407.15  4783.0  405.94  4783.5  405.14  4788.5  405.14  4789.0  405.94
  5101.7  405.94  5205.5  405.96  5211.3  406.68  5227.0  406.83  5239.1  408.35
  5264.2  410.84  5270.0  411.89  5285.7  412.53  5307.2  414.82  5350.2  417.72
  5451.9  423.03  5483.3  424.14  5489.1  424.84  5566.5  426.97  5606.6  429.59
  5643.8  433.00  5665.3  433.93  5671.5  435.22  5686.8  435.96  5694.6  436.95
#Mann=5,-1,0
  4619.2    0.05       0  4783.0   0.033       0  4789.0    0.05       0
  5101.7    0.16       0  5566.5    0.05       0
Bank Sta=4746.6,5239.1
Exp/Cntr=0.3,0.1

Type RM Length L Ch R = 1,1238,23,23,23
BEGIN DESCRIPTION:
Mapping XS 78536069
END DESCRIPTION:
XS GIS Cut Line= 6
      2944893.29      6957686.76      2944630.26      6957405.49
      2944570.36      6957298.72      2944502.65      6957293.51
      2944414.11      6957303.93      2943776.06      6957715.40
#Sta/Elev= 30
  4484.1  414.47  4610.4  414.43  4653.8  414.57  4696.3  413.24  4753.0  413.69
  4809.6  411.50  4869.2  410.89  4904.2  409.53  4908.0  408.34  4916.0  406.52
  4928.9  405.94  4929.4  405.14  4934.9  405.94  4984.4  405.95  4990.9  407.66
  5007.0  405.96  5070.6  405.94  5174.9  405.94  5294.7  405.94  5401.4  405.94
  5416.6  408.53  5422.5  407.42  5431.8  408.88  5438.5  408.34  5452.9  411.42
  5468.1  412.38  5583.0  416.25  5604.1  416.00  5640.4  418.82  5907.9  431.06
#Mann=7,-1,0
  4484.1    0.16       0  4610.4    0.05       0  4928.9    0.03       0
  4934.9    0.05       0  5070.6    0.12       0  5174.9    0.05       0
  5294.7    0.16       0
Bank Sta=4908,5438.5
Exp/Cntr=0.3,0.1

Type RM Length L Ch R = 1,1215,56,56,56
BEGIN DESCRIPTION:
Mapping XS ba16b614
END DESCRIPTION:
XS GIS Cut Line= 6
      2944916.71      6957671.11      2944578.17      6957277.89
      2944500.05      6957270.08      2944406.30      6957280.49
      2944174.53      6957428.93      2943815.14      6957629.46
#Sta/Elev= 30
  4472.7  415.36  4605.9  412.44  4669.6  413.47  4689.3  412.40  4712.4  411.54
  4825.5  410.99  4882.5  409.36  4917.7  410.28  4952.5  409.75  5042.7  407.93
  5082.2  406.77  5082.7  405.97  5087.7  405.97  5088.2  406.77  5112.6  407.93
  5116.1  408.13  5180.5  408.59  5219.3  408.03  5299.8  408.80  5313.1  407.94
  5320.3  408.98  5343.5  409.10  5349.5  408.24  5356.0  409.19  5540.5  413.78
  5605.6  417.27  5670.7  419.17  5686.7  420.95  5730.1  421.25  5851.2  427.08
#Mann=8,-1,0
  4472.7    0.16       0  4689.3    0.05       0  4952.5    0.16       0
  5082.2    0.07       0  5088.2    0.16       0  5116.1    0.12       0
  5180.5    0.05       0  5299.8    0.16       0
Bank Sta=5042.7,5112.6
Exp/Cntr=0.3,0.1

Type RM Length L Ch R = 1,1159,300,300,300
BEGIN DESCRIPTION:
Mapping XS 1e341a85
END DESCRIPTION:
XS GIS Cut Line= 5
      2944966.17      6957316.94      2944635.47      6957225.80
      2944416.72      6957220.60      2944231.82      6957329.97
      2943872.44      6957543.51
#Sta/Elev= 30
  4602.2  412.37  4816.3  397.61  4985.7  394.83  5105.7  400.58  5161.8  393.84
  5177.2  392.56  5183.0  395.88  5198.6  392.77  5204.4  396.12  5217.1  392.00
  5217.6  391.20  5223.1  392.00  5225.9  395.66  5235.7  393.33  5241.5  396.86
  5257.1  392.43  5265.5  395.34  5278.6  392.16  5284.4  395.35  5300.0  392.05
  5307.0  395.05  5315.6  393.29  5321.4  396.66  5337.4  393.84  5342.9  396.45
  5358.5  393.84  5364.3  396.75  5417.0  397.69  5561.3  411.09  5796.9  424.25
#Mann=5,-1,0
  4602.2    0.16       0  5217.1    0.07       0  5223.1    0.16       0
  5265.5    0.05       0  5307.0    0.16       0
Bank Sta=5161.8,5337.4
Exp/Cntr=0.3,0.1

Type RM Length L Ch R = 1,859,287,287,287
BEGIN DESCRIPTION:
UNT 018 IN DRY CR WATERSHED 2.0
END DESCRIPTION:
XS GIS Cut Line= 3
      2944625.02      6956974.99      2944325.00      6957125.00
      2944024.96      6957024.99
#Sta/Elev= 30
  4686.6  406.83  4695.0  407.70  4700.6  407.31  4717.4  408.43  4762.1  409.59
  4812.4  408.69  4820.8  407.46  4829.2  404.85  4834.8  404.85  4851.5  401.39
  4873.9  397.82  4879.5  398.19  4896.3  395.01  4901.8  395.39  4910.2  393.94
  4971.9  387.09  4985.7  385.46  5010.6  385.41  5011.1  384.61  5016.1  384.61
  5016.6  385.41  5053.7  385.64  5072.2  387.09  5095.8  390.56  5138.0  394.48
  5190.7  402.85  5201.2  405.17  5243.4  411.04  5275.0  413.24  5338.3  415.90
#Mann=3,-1,0
  4686.6    0.16       0  5010.6    0.07       0  5016.6    0.16       0
Bank Sta=4971.9,5072.2
Exp/Cntr=0.3,0.1

Type RM Length L Ch R = 1,572,269,269,269
BEGIN DESCRIPTION:
Mapping XS d28521ec
END DESCRIPTION:
XS GIS Cut Line= 3
      2944652.17      6956957.57      2944342.28      6956845.60
      2943929.07      6956907.97
#Sta/Elev= 30
  4652.5  407.09  4675.4  407.58  4700.8  409.45  4723.9  409.85  4767.4  408.74
  4792.8  405.67  4798.4  403.65  4854.1  395.30  4902.5  385.33  4910.1  383.24
  4915.4  383.86  4925.9  383.06  4954.8  382.93  4955.3  382.13  4960.3  382.13
  4960.8  382.93  4999.5  383.77  5030.9  385.33  5100.6  389.95  5140.8  394.08
  5145.8  393.32  5151.2  394.02  5161.3  391.04  5171.4  391.60  5181.5  393.83
  5209.7  397.81  5222.0  400.60  5252.3  403.26  5342.4  415.42  5399.9  420.53
#Mann=3,-1,0
  4652.5    0.16       0  4954.8    0.07       0  4960.8    0.16       0
Bank Sta=4902.5,5030.9
Exp/Cntr=0.3,0.1

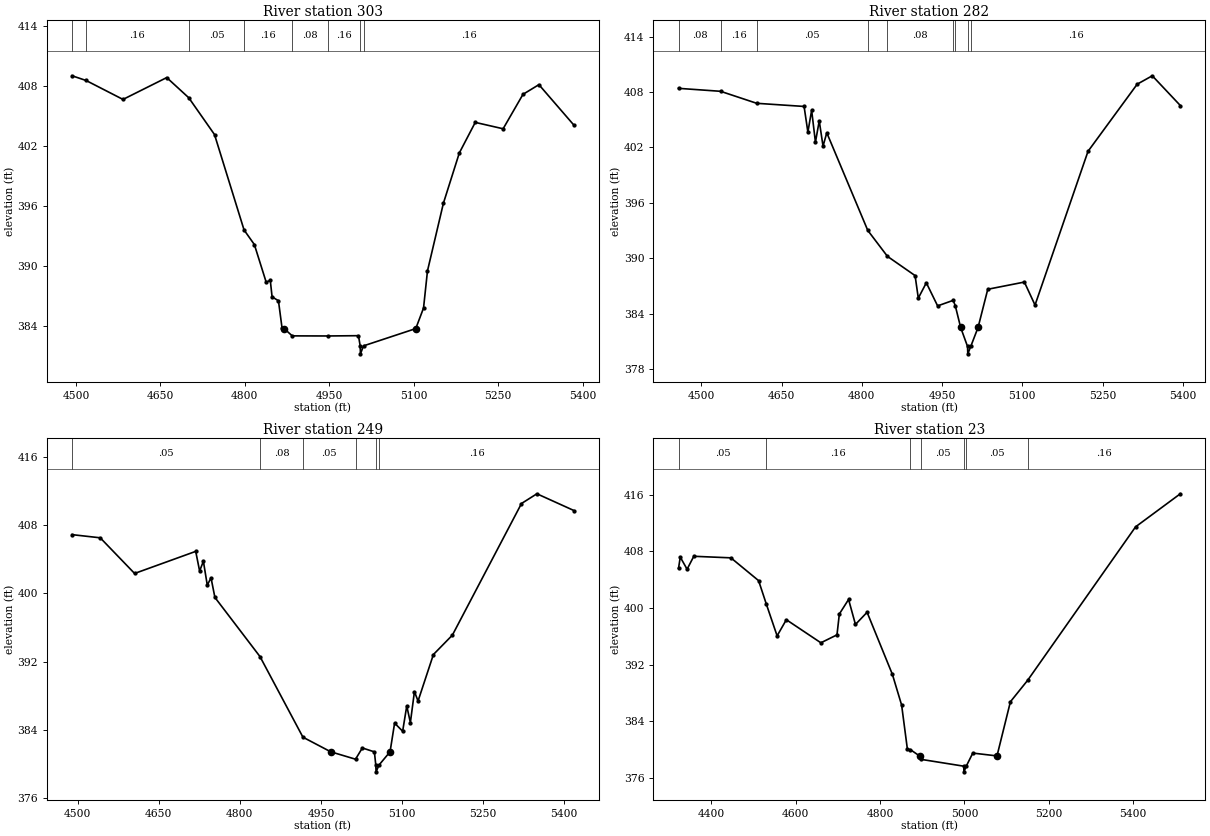
Type RM Length L Ch R = 1,303,21,21,21
BEGIN DESCRIPTION:
Mapping XS 2bd54a5c
END DESCRIPTION:
XS GIS Cut Line= 6
      2944714.65      6956973.17      2944469.88      6956715.39
      2944409.99      6956642.47      2944373.53      6956585.18
      2944300.61      6956559.14      2944092.31      6956770.04
#Sta/Elev= 30
  4493.0  409.06  4517.8  408.59  4583.5  406.69  4661.2  408.88  4700.3  406.86
  4746.1  403.17  4798.6  393.61  4816.9  392.15  4837.9  388.38  4845.2  388.56
  4848.4  386.91  4859.7  386.52  4866.2  383.74  4869.8  383.73  4884.2  383.00
  4947.0  382.99  5001.9  383.02  5004.9  382.00  5005.4  381.20  5010.9  382.00
  5103.7  383.73  5117.5  385.79  5124.5  389.51  5152.8  396.29  5181.1  401.33
  5209.4  404.39  5258.9  403.75  5294.2  407.20  5322.5  408.17  5384.6  404.12
#Mann=8,-1,0
  4493.0    0.08       0  4517.8    0.16       0  4700.3    0.05       0
  4798.6    0.16       0  4884.2    0.08       0  4947.0    0.16       0
  5004.9    0.07       0  5010.9    0.16       0
Bank Sta=4869.8,5103.7
Exp/Cntr=0.3,0.1

Type RM Length L Ch R = 1,282,33,33,33
BEGIN DESCRIPTION:
Mapping XS 6fcf284d
END DESCRIPTION:
XS GIS Cut Line= 5
      2944753.76      6956968.01      2944490.72      6956702.37
      2944417.80      6956592.99      2944298.01      6956525.28
      2944092.25      6956736.26
#Sta/Elev= 30
  4457.6  408.40  4536.1  408.08  4603.7  406.78  4692.2  406.44  4699.3  403.66
  4706.3  406.02  4713.4  402.57  4720.5  404.88  4727.6  402.14  4734.6  403.59
  4811.2  393.02  4848.0  390.21  4899.6  388.13  4905.6  385.69  4920.6  387.35
  4941.7  384.85  4970.8  385.45  4974.7  384.87  4984.7  382.52  4997.6  380.46
  4998.1  379.66  5003.6  380.46  5017.3  382.52  5035.4  386.65  5103.8  387.43
  5123.7  384.94  5222.7  401.58  5314.6  408.85  5342.8  409.76  5395.2  406.54
#Mann=9,-1,0
  4457.6    0.08       0  4536.1    0.16       0  4603.7    0.05       0
  4811.2    0.16       0  4848.0    0.08       0  4970.8    0.05       0
  4974.7    0.16       0  4997.6    0.07       0  5003.6    0.16       0
Bank Sta=4984.7,5017.3
Exp/Cntr=0.3,0.1

Type RM Length L Ch R = 1,249,226,226,226
BEGIN DESCRIPTION:
Mapping XS b9a7d01a
END DESCRIPTION:
XS GIS Cut Line= 4
      2944756.36      6956887.28      2944420.40      6956561.74
      2944295.40      6956499.24      2944055.82      6956712.79
#Sta/Elev= 30
  4489.6  406.88  4541.7  406.51  4605.3  402.33  4718.4  404.92  4725.6  402.62
  4732.6  403.76  4739.8  400.96  4746.7  401.82  4753.9  399.52  4837.3  392.59
  4916.8  383.14  4968.2  381.43  5014.1  380.56  5026.7  381.88  5049.0  381.42
  5051.6  379.88  5052.1  379.08  5057.6  379.88  5078.0  381.43  5086.4  384.79
  5101.3  383.84  5108.9  386.80  5115.6  384.85  5123.1  388.48  5129.8  387.38
  5158.2  392.83  5193.3  395.10  5321.2  410.53  5349.7  411.67  5418.1  409.71
#Mann=6,-1,0
  4489.6    0.05       0  4837.3    0.08       0  4916.8    0.05       0
  5014.1    0.16       0  5051.6    0.04       0  5057.6    0.16       0
Bank Sta=4968.2,5078
Exp/Cntr=0.3,0.1

Type RM Length L Ch R = 1,23,0,0,0
BEGIN DESCRIPTION:
UNT 018 IN DRY CR WATERSHED 1.0
END DESCRIPTION:
XS GIS Cut Line= 4
      2944790.21      6956876.87      2944532.38      6956397.68
      2944365.72      6956348.20      2944025.01      6956674.99
#Sta/Elev= 30
  4321.9  405.62  4326.0  407.19  4342.2  405.48  4358.1  407.31  4446.1  407.09
  4511.8  403.87  4530.2  400.54  4555.7  396.07  4577.6  398.35  4659.5  395.09
  4697.7  396.21  4703.3  399.16  4725.2  401.21  4741.5  397.68  4769.1  399.40
  4829.1  390.63  4851.0  386.29  4864.7  380.05  4871.7  380.00  4893.4  379.11
  4897.3  378.62  4998.3  377.66  4998.8  376.86  5004.3  377.66  5019.8  379.51
  5077.2  379.11  5109.0  386.76  5149.9  389.79  5405.9  411.47  5512.0  416.14
#Mann=7,-1,0
  4321.9    0.05       0  4530.2    0.16       0  4871.7    0.12       0
  4897.3    0.05       0  4998.3    0.04       0  5004.3    0.05       0
  5149.9    0.16       0
Bank Sta=4893.4,5077.2
Exp/Cntr=0.3,0.1

Chan Stop Cuts=-1