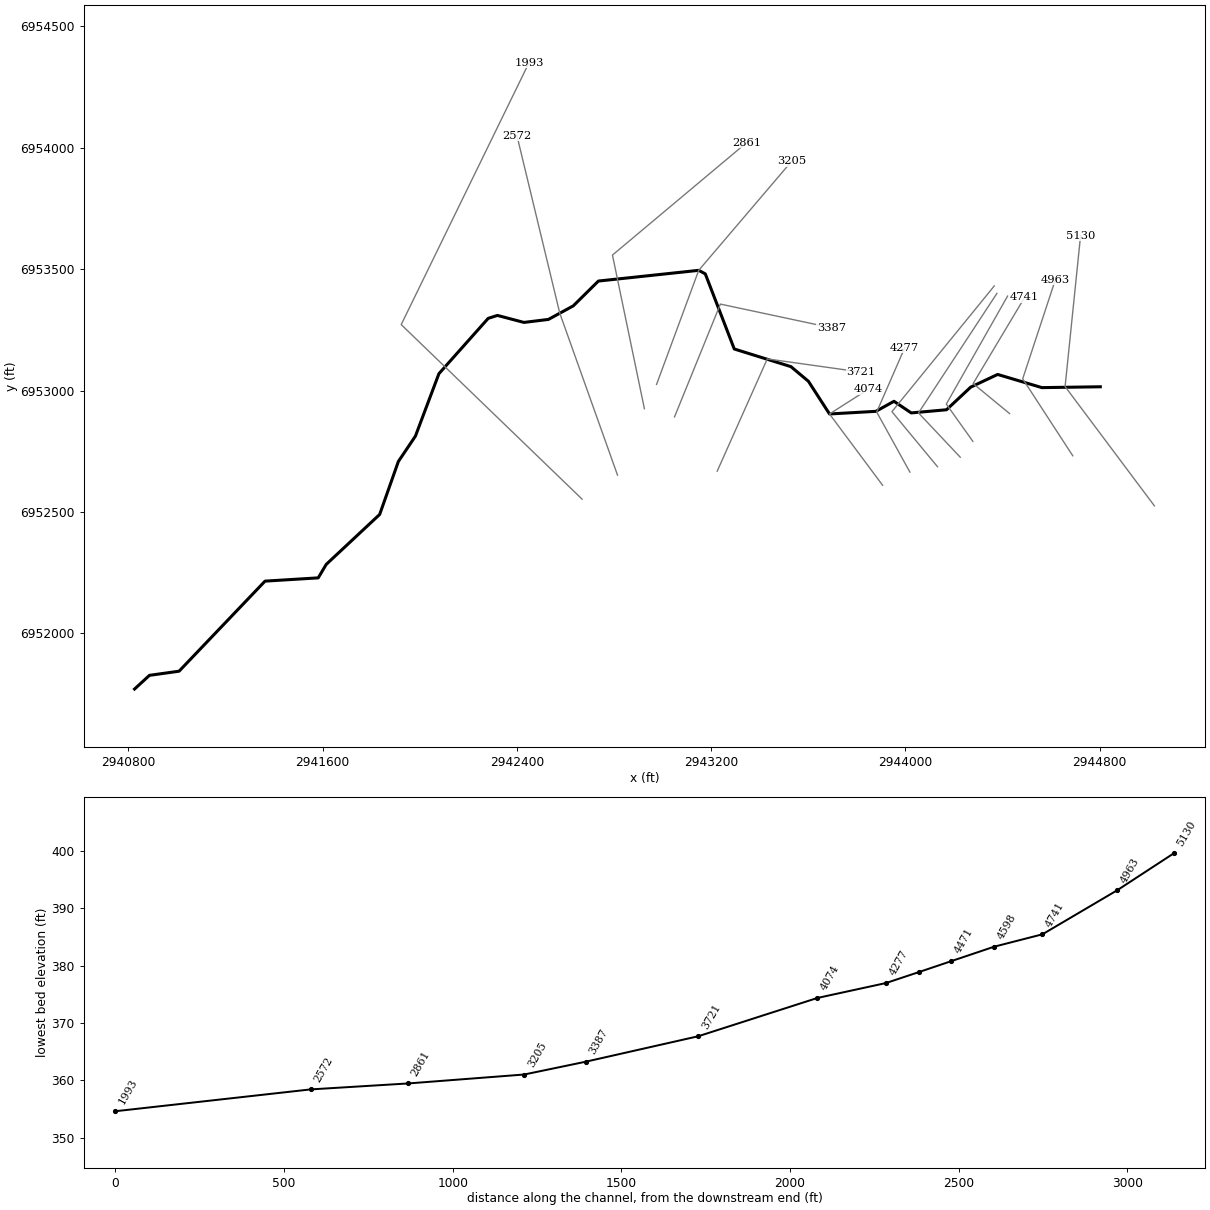
--- UNT 019 IN DRY CR WATERSHED.prj (project) ---

Proj Title=UNT 019 IN DRY CR WATERSHED Base Level Engineering
Current Plan=p01
Default Exp/Contr=0.3,0.1
English Units
Geom File=g01
Flow File=f01
Plan File=p01
BEGIN DESCRIPTION:
UNT 019 IN DRY CR WATERSHED
END DESCRIPTION:

--- UNT 019 IN DRY CR WATERSHED.p01 (plan) ---

Plan Title=Multiple Run
Short Identifier=Multiple
Geom File=g01
Flow File=f01
Subcritical Flow
K Sum by GR= 0
Std Step Tol= 0.01
Critical Tol= 0.01
Num of Std Step Trials= 20
Max Error Tol= 0.3
Flow Tol Ratio= 0.001
Split Flow NTrial= 30
Split Flow Tol= 0.02
Split Flow Ratio= 0.02
Log Output Level= 0
Friction Slope Method= 1
Unsteady Friction Slope Method= 2
Unsteady Bridges Friction Slope Method= 1
Parabolic Critical Depth
Global Vel Dist=  1 , 1 , 1
Global Log Level= 0
CheckData=True
Encroach Param= -1, 0, 0, 0
BEGIN DESCRIPTION:
Multiple Run
END DESCRIPTION:

--- UNT 019 IN DRY CR WATERSHED.f01 (steady flow) ---

Flow Title=Multiple
Number of Profiles=7
Profile Names=10-year,25-year,50-year,1pct_min,100-year,1pct_plu,500-year
River Rch & RM= UNT 019 IN DRY C,Reach-1,5130
     389     514     614     367     732    1460    1038
Boundary for River Rch & Prof#=UNT 019 IN DRY C,Reach-1,1
Up Type=0
Dn Type=3
Dn Slope=0.005
Boundary for River Rch & Prof#=UNT 019 IN DRY C,Reach-1,2
Up Type=0
Dn Type=3
Dn Slope=0.005
Boundary for River Rch & Prof#=UNT 019 IN DRY C,Reach-1,3
Up Type=0
Dn Type=3
Dn Slope=0.005
Boundary for River Rch & Prof#=UNT 019 IN DRY C,Reach-1,4
Up Type=0
Dn Type=3
Dn Slope=0.005
Boundary for River Rch & Prof#=UNT 019 IN DRY C,Reach-1,5
Up Type=0
Dn Type=3
Dn Slope=0.005
Boundary for River Rch & Prof#=UNT 019 IN DRY C,Reach-1,6
Up Type=0
Dn Type=3
Dn Slope=0.005
Boundary for River Rch & Prof#=UNT 019 IN DRY C,Reach-1,7
Up Type=0
Dn Type=3
Dn Slope=0.005

--- UNT 019 IN DRY CR WATERSHED.g01 (geometry) ---

Geom Title=Existing Conditions

River Reach=UNT 019 IN DRY C,Reach-1
Reach XY= 30
      2944802.20      6953015.38      2944561.75      6953011.91
      2944379.46      6953066.17      2944268.78      6953014.08
      2944168.96      6952920.77      2944023.56      6952907.75
      2943952.69      6952955.64      2943878.16      6952914.26
      2943687.19      6952903.40      2943600.38      6953037.95
      2943528.33      6953098.28      2943295.04      6953170.98
      2943175.72      6953480.25      2943148.64      6953494.83
      2942735.59      6953450.71      2942632.08      6953348.51
      2942529.75      6953292.71      2942428.91      6953280.38
      2942319.71      6953309.19      2942281.80      6953297.09
      2942078.91      6953069.33      2941982.12      6952812.15
      2941911.82      6952707.56      2941834.92      6952489.64
      2941614.97      6952284.12      2941581.90      6952228.56
      2941362.94      6952215.14      2941008.95      6951844.24
      2940887.09      6951827.21      2940825.59      6951770.71

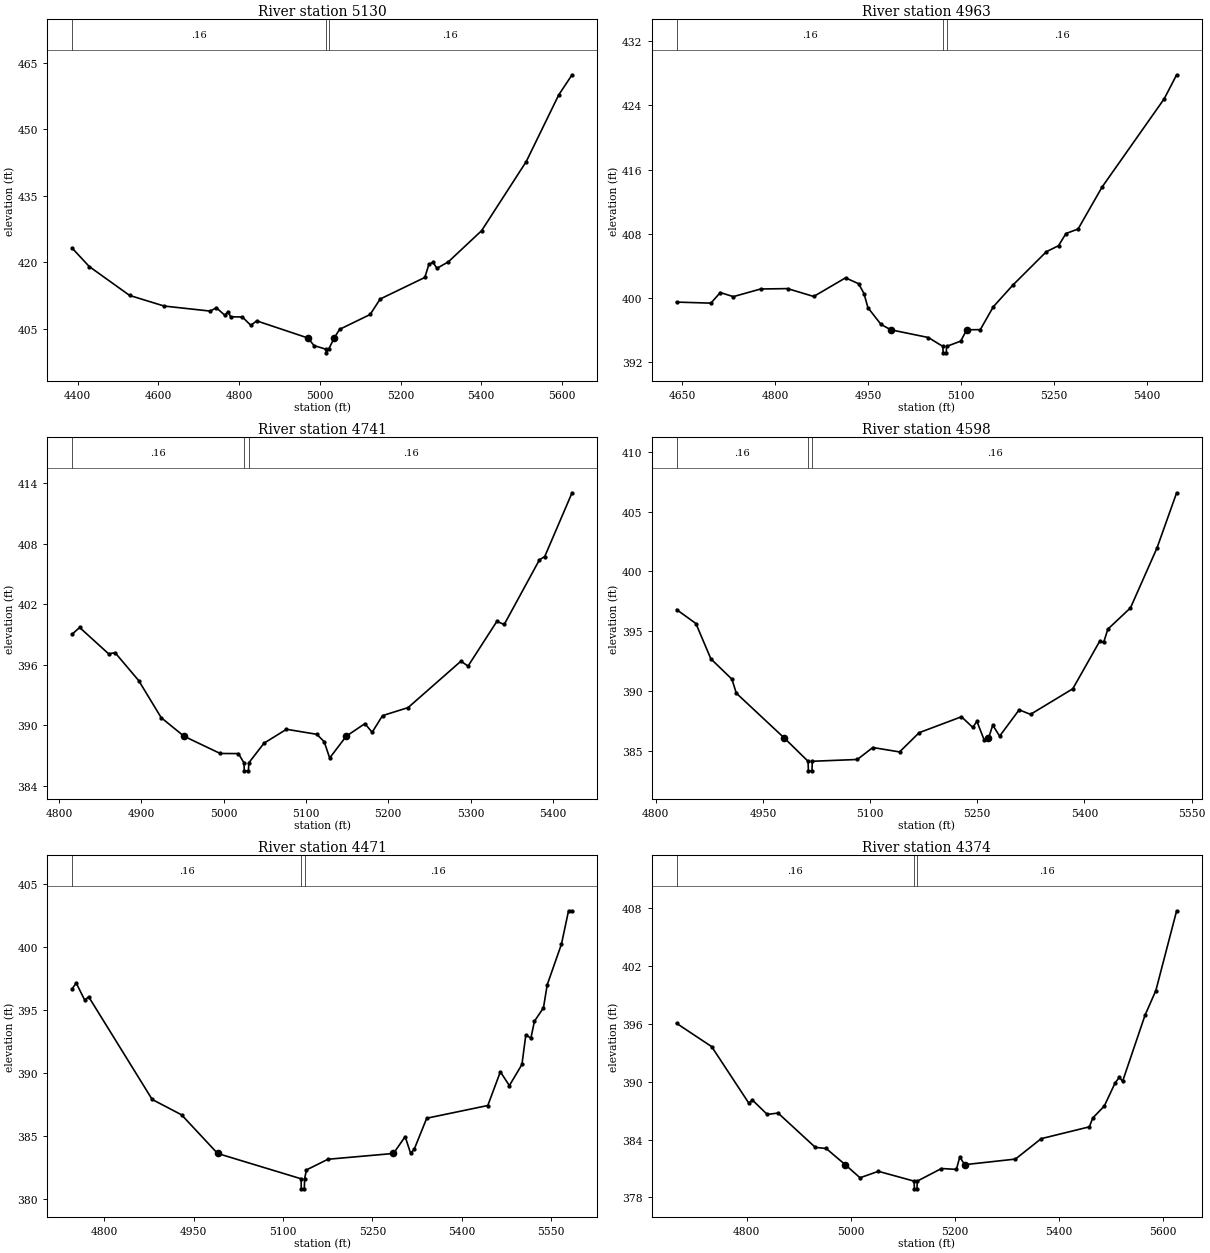
Type RM Length L Ch R = 1,5130,167,167,167
BEGIN DESCRIPTION:
UNT 019 IN DRY CR WATERSHED 8.0
END DESCRIPTION:
XS GIS Cut Line= 3
      2945025.02      6952524.97      2944657.24      6953016.25
      2944720.95      6953637.80
#Sta/Elev= 30
  4386.3  423.24  4429.1  419.05  4529.1  412.54  4614.5  410.15  4729.1  409.01
  4743.7  409.79  4764.6  408.09  4772.9  408.91  4779.1  407.74  4808.3  407.68
  4829.2  405.80  4843.8  406.81  4970.4  402.96  4985.9  401.24  5015.8  400.41
  5016.3  399.61  5021.8  400.41  5035.8  402.96  5049.0  404.90  5124.8  408.25
  5149.5  411.73  5260.1  416.59  5270.2  419.53  5280.2  420.00  5290.3  418.66
  5318.3  420.10  5400.8  427.13  5511.4  442.71  5591.8  457.72  5624.8  462.25
#Mann=3,-1,0
  4386.3    0.16       0  5015.8    0.07       0  5021.8    0.16       0
Bank Sta=4970.4,5035.8
Exp/Cntr=0.3,0.1

Type RM Length L Ch R = 1,4963,222,222,222
BEGIN DESCRIPTION:
Mapping XS 4d1af96e
END DESCRIPTION:
XS GIS Cut Line= 3
      2944688.79      6952731.27      2944482.61      6953048.14
      2944617.17      6953456.17
#Sta/Elev= 30
  4640.7  399.51  4696.2  399.38  4711.3  400.70  4732.4  400.19  4776.4  401.14
  4820.0  401.19  4862.2  400.21  4913.6  402.53  4934.7  401.80  4943.4  400.58
  4949.8  398.81  4970.9  396.73  4986.7  396.06  5047.3  395.10  5070.8  393.99
  5071.3  393.19  5076.3  393.19  5076.8  393.99  5099.7  394.65  5109.3  396.06
  5131.3  396.08  5152.3  398.93  5183.9  401.63  5237.9  405.78  5257.6  406.53
  5269.6  408.05  5289.2  408.61  5327.9  413.83  5428.4  424.84  5448.4  427.82
#Mann=3,-1,0
  4640.7    0.16       0  5070.8    0.07       0  5076.8    0.16       0
Bank Sta=4986.7,5109.3
Exp/Cntr=0.3,0.1

Type RM Length L Ch R = 1,4741,143,143,143
BEGIN DESCRIPTION:
Mapping XS 1732f79c
END DESCRIPTION:
XS GIS Cut Line= 3
      2944428.53      6952905.14      2944278.61      6953028.61
      2944490.66      6953383.47
#Sta/Elev= 30
  4815.7  399.02  4825.0  399.70  4860.2  397.09  4868.1  397.20  4896.8  394.43
  4924.1  390.76  4951.8  388.92  4995.8  387.21  5017.9  387.20  5024.6  386.29
  5025.1  385.49  5030.1  385.49  5030.6  386.29  5049.0  388.23  5076.3  389.61
  5113.2  389.11  5122.2  388.37  5128.8  386.76  5148.9  388.92  5171.6  390.17
  5180.4  389.31  5193.0  390.96  5224.1  391.76  5288.3  396.36  5296.9  395.87
  5331.9  400.30  5340.9  400.00  5383.7  406.41  5390.1  406.73  5423.3  413.05
#Mann=3,-1,0
  4815.7    0.16       0  5024.6    0.07       0  5030.6    0.16       0
Bank Sta=4951.8,5148.9
Exp/Cntr=0.3,0.1

Type RM Length L Ch R = 1,4598,127,127,127
BEGIN DESCRIPTION:
Mapping XS 00e0cca9
END DESCRIPTION:
XS GIS Cut Line= 3
      2944277.53      6952790.52      2944168.14      6952944.18
      2944420.36      6953388.81
#Sta/Elev= 30
  4829.2  396.81  4856.3  395.64  4877.2  392.69  4906.7  390.99  4912.8  389.82
  4980.2  386.06  5013.2  384.13  5013.7  383.33  5018.7  383.33  5019.2  384.13
  5082.2  384.28  5103.8  385.28  5141.3  384.91  5168.7  386.52  5227.9  387.85
  5243.7  386.96  5249.5  387.47  5259.6  385.92  5265.7  386.06  5271.7  387.15
  5281.3  386.23  5308.6  388.43  5324.5  388.05  5383.7  390.19  5421.2  394.15
  5426.9  394.07  5432.7  395.17  5464.4  396.95  5501.6  401.97  5529.0  406.57
#Mann=3,-1,0
  4829.2    0.16       0  5013.2    0.07       0  5019.2    0.16       0
Bank Sta=4980.2,5265.7
Exp/Cntr=0.3,0.1

Type RM Length L Ch R = 1,4471,97,97,97
BEGIN DESCRIPTION:
Mapping XS f369b46c
END DESCRIPTION:
XS GIS Cut Line= 3
      2944225.44      6952725.42      2944053.56      6952907.72
      2944376.46      6953399.89
#Sta/Elev= 30
  4746.0  396.69  4753.1  397.16  4767.3  395.81  4774.1  396.06  4880.6  387.91
  4929.9  386.69  4990.4  383.62  5130.4  381.61  5130.9  380.81  5135.9  380.81
  5136.4  381.61  5139.4  382.31  5175.5  383.16  5285.5  383.62  5305.1  384.96
  5314.2  383.64  5320.2  383.94  5341.3  386.42  5443.8  387.43  5464.9  390.11
  5480.0  389.01  5501.1  390.69  5507.6  393.04  5516.1  392.78  5522.1  394.13
  5537.2  395.19  5543.5  397.02  5567.4  400.25  5579.3  402.90  5585.2  402.90
#Mann=3,-1,0
  4746.0    0.16       0  5130.4    0.07       0  5136.4    0.16       0
Bank Sta=4990.4,5285.5
Exp/Cntr=0.3,0.1

Type RM Length L Ch R = 1,4374,97,97,97
BEGIN DESCRIPTION:
Mapping XS 8fb62bd1
END DESCRIPTION:
XS GIS Cut Line= 3
      2944131.70      6952686.35      2943944.18      6952912.93
      2944365.58      6953430.58
#Sta/Elev= 30
  4664.9  396.07  4732.4  393.65  4804.1  387.76  4810.6  388.11  4839.2  386.61
  4860.1  386.75  4931.7  383.19  4952.6  383.07  4989.2  381.39  5017.7  380.03
  5052.9  380.70  5121.7  379.68  5122.2  378.88  5127.2  378.88  5127.7  379.68
  5174.3  380.99  5203.0  380.90  5209.5  382.19  5218.9  381.39  5316.5  381.97
  5366.0  384.09  5458.7  385.32  5465.1  386.23  5487.4  387.48  5508.2  389.88
  5516.2  390.46  5522.6  390.05  5565.7  396.91  5586.5  399.47  5626.5  407.76
#Mann=3,-1,0
  4664.9    0.16       0  5121.7    0.07       0  5127.7    0.16       0
Bank Sta=4989.2,5218.9
Exp/Cntr=0.3,0.1

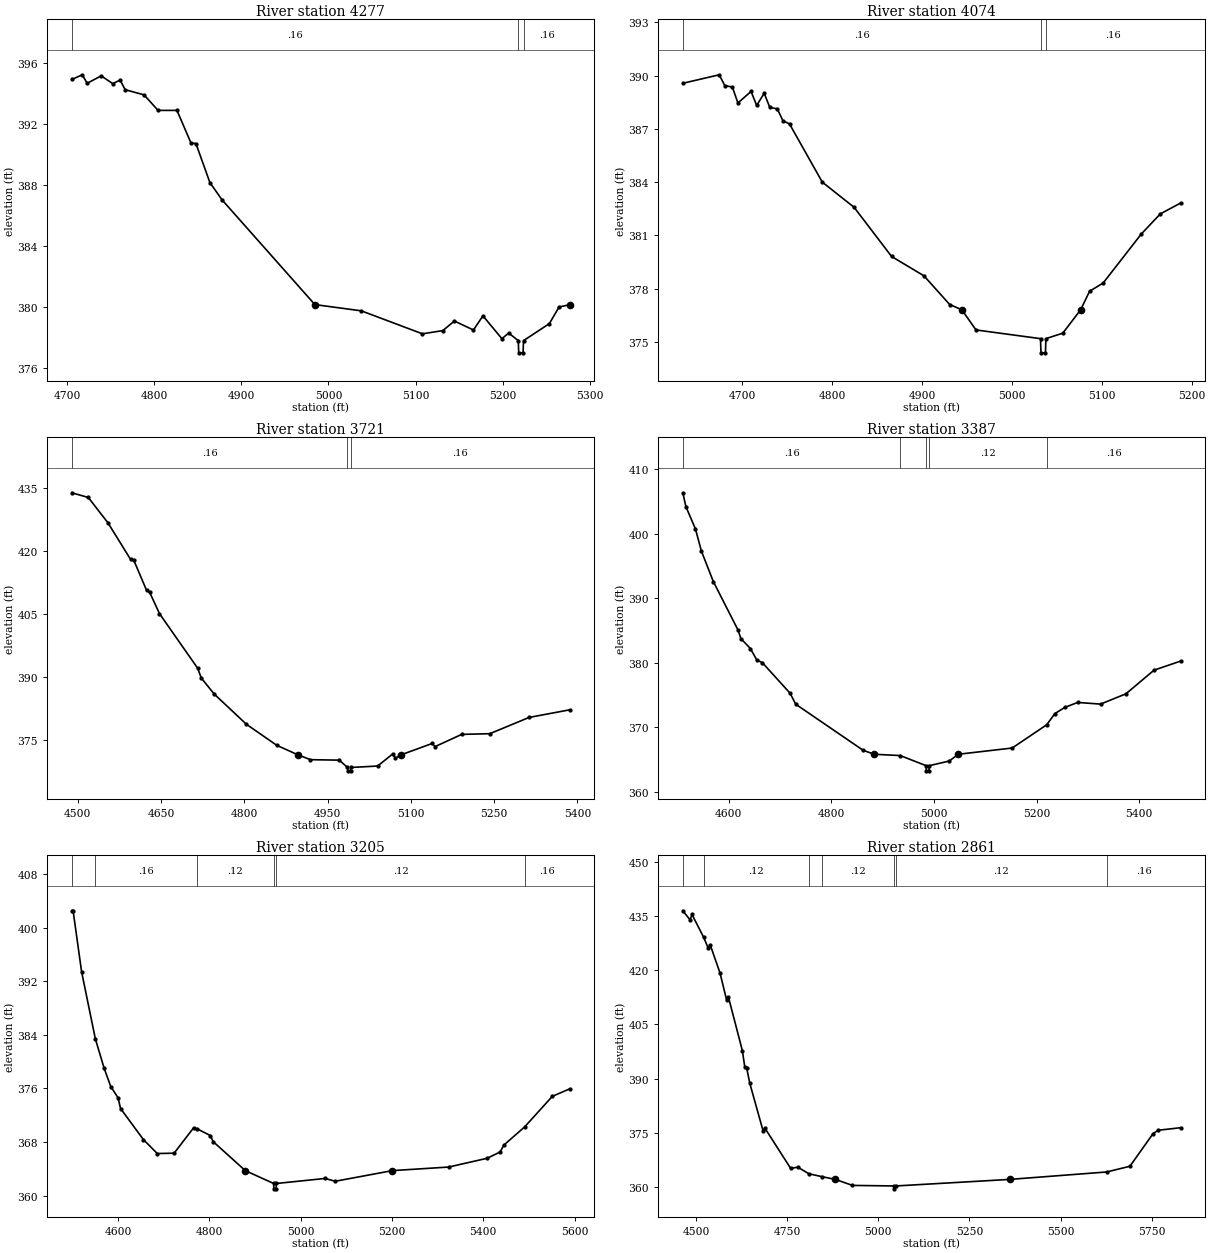
Type RM Length L Ch R = 1,4277,203,203,203
BEGIN DESCRIPTION:
Mapping XS 0632dc4f
END DESCRIPTION:
XS GIS Cut Line= 3
      2944018.21      6952663.99      2943881.48      6952911.42
      2943996.98      6953176.23
#Sta/Elev= 30
  4705.3  394.94  4717.2  395.25  4722.9  394.69  4739.0  395.18  4752.2  394.67
  4760.7  394.90  4766.5  394.27  4788.2  393.93  4804.3  392.91  4826.0  392.91
  4842.1  390.77  4847.8  390.73  4863.8  388.17  4877.8  387.03  4984.4  380.15
  5037.7  379.74  5107.9  378.23  5131.3  378.44  5144.6  379.07  5166.5  378.48
  5177.4  379.41  5199.2  377.91  5207.0  378.28  5218.0  377.78  5218.5  376.98
  5223.5  376.98  5224.0  377.78  5253.7  378.90  5264.8  379.99  5276.9  380.14
#Mann=3,-1,0
  4705.3    0.16       0  5218.0    0.07       0  5224.0    0.16       0
Bank Sta=4984.4,5276.9
Exp/Cntr=0.3,0.1

Type RM Length L Ch R = 1,4074,353,353,353
BEGIN DESCRIPTION:
Mapping XS d67fce25
END DESCRIPTION:
XS GIS Cut Line= 3
      2943905.87      6952609.80      2943687.19      6952903.40
      2943845.46      6953004.31
#Sta/Elev= 30
  4633.9  389.57  4674.4  390.05  4680.6  389.44  4689.0  389.36  4695.2  388.46
  4709.8  389.11  4716.1  388.32  4724.4  389.01  4730.7  388.21  4739.0  388.13
  4745.3  387.46  4752.6  387.28  4789.1  384.00  4824.5  382.58  4866.2  379.81
  4902.2  378.72  4930.9  377.10  4944.3  376.81  4960.1  375.67  5031.9  375.18
  5032.4  374.38  5037.4  374.38  5037.9  375.18  5056.7  375.49  5076.6  376.81
  5086.5  377.85  5101.7  378.32  5144.1  381.08  5165.2  382.21  5187.7  382.82
#Mann=3,-1,0
  4633.9    0.16       0  5031.9    0.07       0  5037.9    0.16       0
Bank Sta=4944.3,5076.6
Exp/Cntr=0.3,0.1

Type RM Length L Ch R = 1,3721,334,334,334
BEGIN DESCRIPTION:
Mapping XS 0613c37c
END DESCRIPTION:
XS GIS Cut Line= 3
      2943224.81      6952667.97      2943430.96      6953130.17
      2943817.28      6953075.91
#Sta/Elev= 30
  4489.6  433.75  4519.2  432.63  4554.5  426.63  4595.4  417.91  4600.9  417.78
  4624.1  410.59  4629.6  410.13  4647.4  405.04  4716.3  392.04  4722.5  389.78
  4745.7  385.97  4803.9  378.76  4858.6  373.76  4896.9  371.49  4919.3  370.35
  4971.2  370.24  4985.9  368.50  4986.4  367.70  4991.4  367.70  4991.9  368.50
  5040.2  368.84  5067.1  371.69  5072.2  370.71  5082.1  371.49  5138.4  374.20
  5143.5  373.45  5191.6  376.36  5242.1  376.52  5312.8  380.38  5385.8  382.19
#Mann=3,-1,0
  4489.6    0.16       0  4985.9    0.07       0  4991.9    0.16       0
Bank Sta=4896.9,5082.1
Exp/Cntr=0.3,0.1

Type RM Length L Ch R = 1,3387,182,182,182
BEGIN DESCRIPTION:
Mapping XS 4e3c7f6a
END DESCRIPTION:
XS GIS Cut Line= 3
      2943049.03      6952891.49      2943237.81      6953355.87
      2943695.74      6953258.20
#Sta/Elev= 30
  4510.8  406.38  4516.7  404.24  4535.4  400.77  4547.0  397.33  4570.2  392.61
  4618.4  385.08  4623.8  383.77  4642.4  382.22  4654.9  380.44  4665.7  380.03
  4719.7  375.29  4730.8  373.58  4862.0  366.44  4883.5  365.82  4934.3  365.62
  4984.7  364.05  4985.2  363.25  4990.2  363.25  4990.7  364.05  5029.7  364.77
  5047.4  365.82  5152.4  366.79  5219.5  370.39  5235.6  372.13  5254.6  373.08
  5280.0  373.86  5324.5  373.60  5374.0  375.20  5428.6  378.86  5480.3  380.27
#Mann=5,-1,0
  4510.8    0.16       0  4934.3    0.12       0  4984.7    0.07       0
  4990.7    0.12       0  5219.5    0.16       0
Bank Sta=4883.5,5047.4
Exp/Cntr=0.3,0.1

Type RM Length L Ch R = 1,3205,344,344,344
BEGIN DESCRIPTION:
UNT 019 IN DRY CR WATERSHED 4.0
END DESCRIPTION:
XS GIS Cut Line= 3
      2942975.00      6953024.99      2943148.64      6953494.83
      2943530.63      6953943.16
#Sta/Elev= 30
  4499.1  402.52  4501.8  402.52  4520.4  393.43  4550.4  383.44  4569.8  379.01
  4584.4  376.27  4600.2  374.62  4605.7  373.01  4655.7  368.38  4686.1  366.29
  4723.0  366.34  4765.6  370.12  4773.5  369.97  4802.5  368.97  4808.3  368.08
  4878.9  363.74  4940.9  361.82  4941.4  361.02  4946.4  361.02  4946.9  361.82
  5053.9  362.57  5075.8  362.15  5200.9  363.74  5324.0  364.27  5408.5  365.58
  5437.1  366.53  5444.8  367.53  5490.7  370.27  5551.3  374.83  5589.0  375.93
#Mann=6,-1,0
  4499.1    0.12       0  4550.4    0.16       0  4773.5    0.12       0
  4940.9    0.07       0  4946.9    0.12       0  5490.7    0.16       0
Bank Sta=4878.9,5200.9
Exp/Cntr=0.3,0.1

Type RM Length L Ch R = 1,2861,289,289,289
BEGIN DESCRIPTION:
UNT 019 IN DRY CR WATERSHED 3.0
END DESCRIPTION:
XS GIS Cut Line= 3
      2942925.00      6952925.00      2942793.48      6953557.69
      2943345.40      6954020.18
#Sta/Elev= 30
  4463.2  436.48  4483.1  433.96  4488.3  435.46  4520.4  429.13  4533.2  426.07
  4538.4  427.02  4565.3  419.25  4583.3  411.79  4588.5  412.53  4626.6  397.75
  4633.4  393.16  4638.6  392.90  4647.1  388.66  4683.6  375.49  4688.7  376.24
  4759.4  365.10  4778.6  365.47  4809.3  363.63  4845.8  362.82  4882.0  362.07
  4928.9  360.41  5042.4  360.26  5042.9  359.46  5048.4  360.26  5360.1  362.07
  5626.5  364.13  5690.5  365.71  5754.3  374.78  5768.6  375.69  5829.5  376.39
#Mann=7,-1,0
  4463.2    0.16       0  4520.4    0.12       0  4809.3    0.16       0
  4845.8    0.12       0  5042.4    0.07       0  5048.4    0.12       0
  5626.5    0.16       0
Bank Sta=4882,5360.1
Exp/Cntr=0.3,0.1

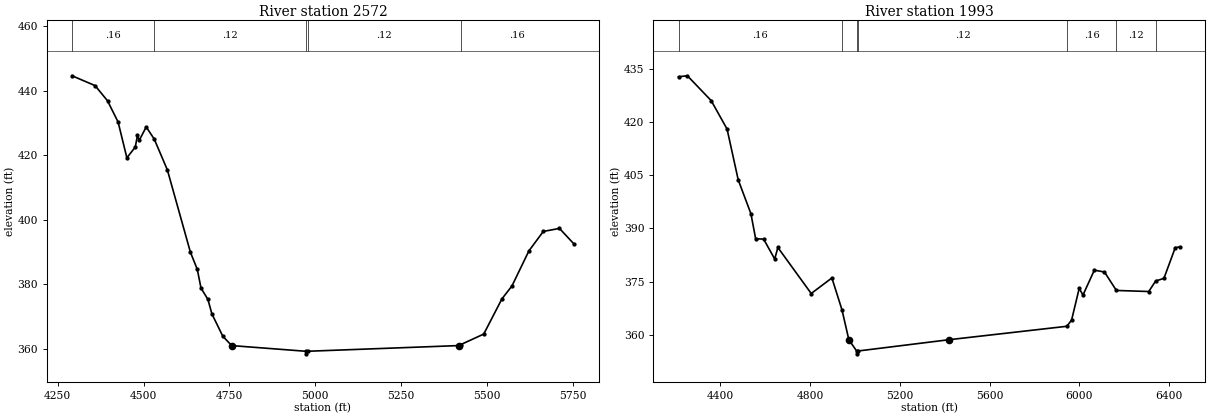
Type RM Length L Ch R = 1,2572,579,579,579
BEGIN DESCRIPTION:
UNT 019 IN DRY CR WATERSHED 2.0
END DESCRIPTION:
XS GIS Cut Line= 3
      2942814.24      6952651.69      2942576.51      6953318.48
      2942400.00      6954049.99
#Sta/Elev= 30
  4292.1  444.63  4359.1  441.58  4395.3  436.87  4426.1  430.28  4451.6  419.19
  4476.1  422.54  4482.4  426.14  4487.7  424.64  4507.9  428.77  4531.3  424.99
  4569.5  415.43  4636.5  389.93  4656.6  384.60  4667.3  378.82  4687.5  375.29
  4699.0  370.82  4730.9  363.86  4756.6  360.98  4972.1  359.22  4972.6  358.42
  4978.1  359.22  5417.3  360.98  5422.8  361.26  5490.2  364.55  5543.1  375.45
  5572.5  379.50  5621.7  390.35  5663.6  396.37  5710.6  397.31  5752.5  392.52
#Mann=5,-1,0
  4292.1    0.16       0  4531.3    0.12       0  4972.1    0.07       0
  4978.1    0.12       0  5422.8    0.16       0
Bank Sta=4756.6,5417.3
Exp/Cntr=0.3,0.1

Type RM Length L Ch R = 1,1993,0,0,0
BEGIN DESCRIPTION:
UNT 019 IN DRY CR WATERSHED 1.0
END DESCRIPTION:
XS GIS Cut Line= 3
      2942668.44      6952552.68      2941923.63      6953271.44
      2942450.00      6954349.99
#Sta/Elev= 30
  4214.1  432.73  4253.5  433.00  4359.5  426.00  4430.3  417.98  4479.9  403.67
  4536.5  394.11  4557.6  387.06  4593.1  386.95  4642.5  381.35  4656.6  384.59
  4805.1  371.62  4897.2  376.00  4942.1  367.03  4972.7  358.60  5007.4  355.41
  5007.9  354.61  5013.4  355.41  5420.0  358.60  5944.2  362.38  5965.1  364.16
  5998.8  373.06  6015.7  371.19  6066.3  378.20  6111.4  377.68  6164.5  372.48
  6308.6  372.18  6339.6  375.16  6376.2  375.88  6426.8  384.56  6449.3  384.77
#Mann=7,-1,0
  4214.1    0.16       0  4942.1    0.12       0  5007.4    0.07       0
  5013.4    0.12       0  5944.2    0.16       0  6164.5    0.12       0
  6339.6    0.16       0
Bank Sta=4972.7,5420
Exp/Cntr=0.3,0.1

Chan Stop Cuts=-1