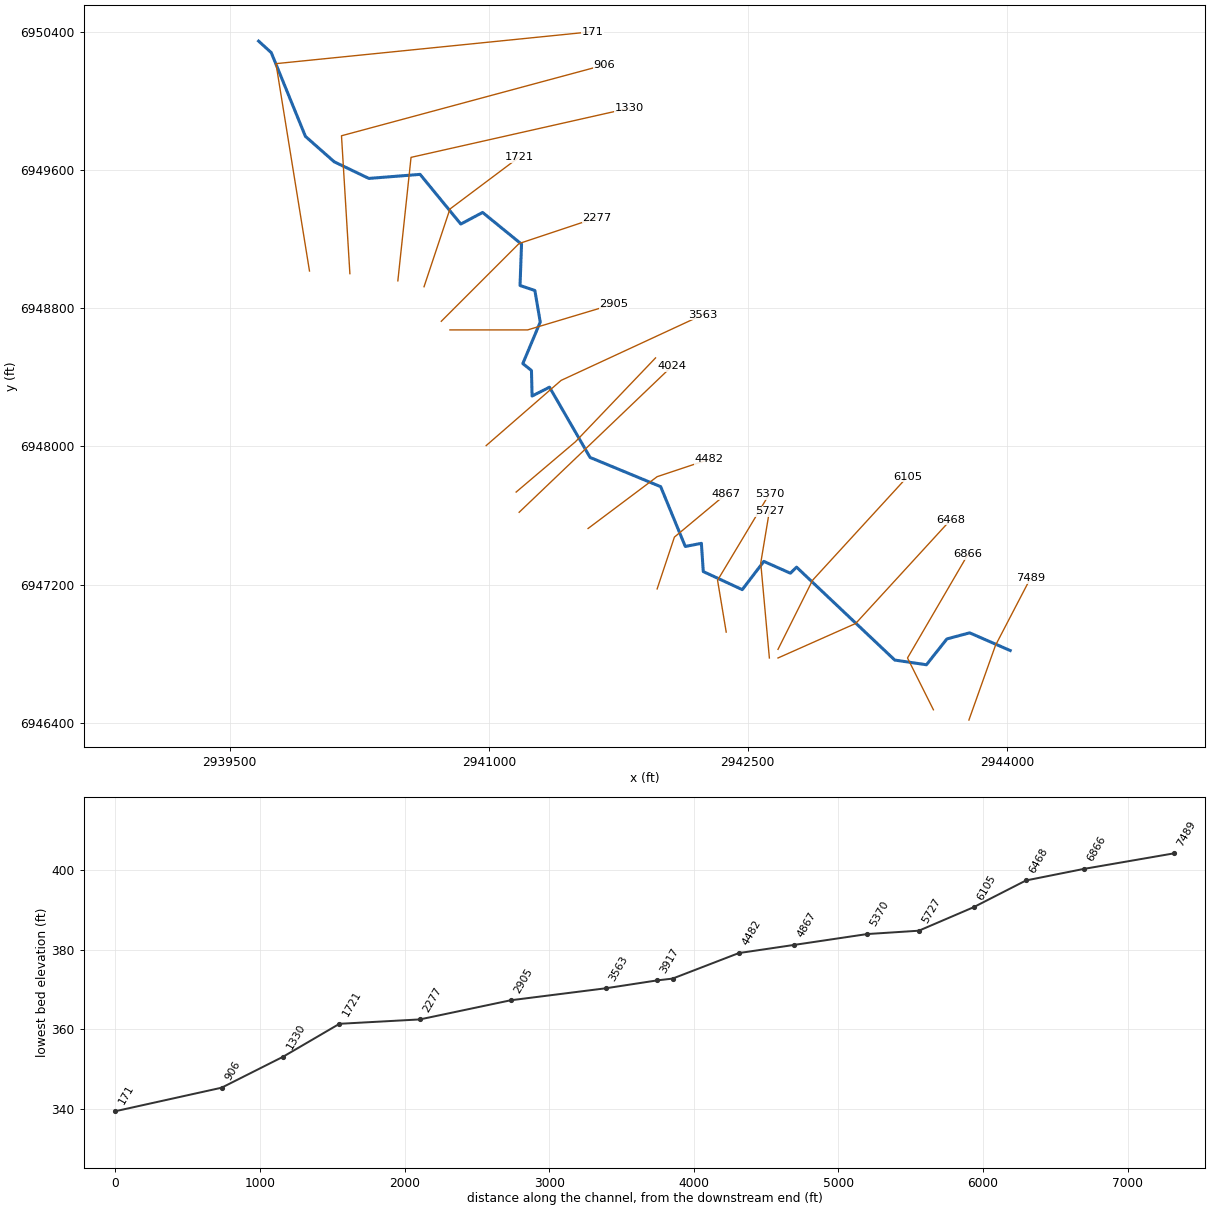
--- UNT 020 IN DRY CR WATERSHED.prj (project) ---

Proj Title=UNT 020 IN DRY CR WATERSHED Base Level Engineering
Current Plan=p01
Default Exp/Contr=0.3,0.1
English Units
Geom File=g01
Flow File=f01
Plan File=p01
BEGIN DESCRIPTION:
UNT 020 IN DRY CR WATERSHED
END DESCRIPTION:

--- UNT 020 IN DRY CR WATERSHED.p01 (plan) ---

Plan Title=Multiple Run
Short Identifier=Multiple
Geom File=g01
Flow File=f01
Subcritical Flow
K Sum by GR= 0
Std Step Tol= 0.01
Critical Tol= 0.01
Num of Std Step Trials= 20
Max Error Tol= 0.3
Flow Tol Ratio= 0.001
Split Flow NTrial= 30
Split Flow Tol= 0.02
Split Flow Ratio= 0.02
Log Output Level= 0
Friction Slope Method= 1
Unsteady Friction Slope Method= 2
Unsteady Bridges Friction Slope Method= 1
Parabolic Critical Depth
Global Vel Dist=  1 , 1 , 1
Global Log Level= 0
CheckData=True
Encroach Param= -1, 0, 0, 0
BEGIN DESCRIPTION:
Multiple Run
END DESCRIPTION:

--- UNT 020 IN DRY CR WATERSHED.f01 (steady flow) ---

Flow Title=Multiple
Number of Profiles=7
Profile Names=10-year,25-year,50-year,1pct_min,100-year,1pct_plu,500-year
River Rch & RM= UNT 020 IN DRY C,Reach-1,7489
     694     953    1170     715    1426    2846    2124
River Rch & RM= UNT 020 IN DRY C,Reach-1,4482
     828    1147    1415     868    1733    3457    2603
Boundary for River Rch & Prof#=UNT 020 IN DRY C,Reach-1,1
Up Type=0
Dn Type=3
Dn Slope=0.005
Boundary for River Rch & Prof#=UNT 020 IN DRY C,Reach-1,2
Up Type=0
Dn Type=3
Dn Slope=0.005
Boundary for River Rch & Prof#=UNT 020 IN DRY C,Reach-1,3
Up Type=0
Dn Type=3
Dn Slope=0.005
Boundary for River Rch & Prof#=UNT 020 IN DRY C,Reach-1,4
Up Type=0
Dn Type=3
Dn Slope=0.005
Boundary for River Rch & Prof#=UNT 020 IN DRY C,Reach-1,5
Up Type=0
Dn Type=3
Dn Slope=0.005
Boundary for River Rch & Prof#=UNT 020 IN DRY C,Reach-1,6
Up Type=0
Dn Type=3
Dn Slope=0.005
Boundary for River Rch & Prof#=UNT 020 IN DRY C,Reach-1,7
Up Type=0
Dn Type=3
Dn Slope=0.005

--- UNT 020 IN DRY CR WATERSHED.g01 (geometry) ---

Geom Title=Existing Conditions

River Reach=UNT 020 IN DRY C,Reach-1
Reach XY= 30
      2944019.77      6946818.21      2943784.72      6946920.61
      2943652.92      6946885.28      2943534.61      6946735.82
      2943351.28      6946762.88      2942782.41      6947301.09
      2942746.54      6947266.04      2942592.85      6947334.43
      2942468.01      6947170.76      2942242.27      6947275.57
      2942231.22      6947438.95      2942137.96      6947420.92
      2941995.52      6947767.15      2941586.66      6947936.42
      2941351.63      6948343.34      2941250.81      6948292.02
      2941247.11      6948439.77      2941197.10      6948479.94
      2941298.09      6948720.58      2941266.85      6948903.25
      2941180.99      6948932.22      2941189.67      6949171.62
      2940964.21      6949355.28      2940837.85      6949288.01
      2940602.17      6949575.77      2940305.29      6949552.33
      2940104.77      6949648.68      2939938.11      6949795.82
      2939740.19      6950280.85      2939666.84      6950347.69

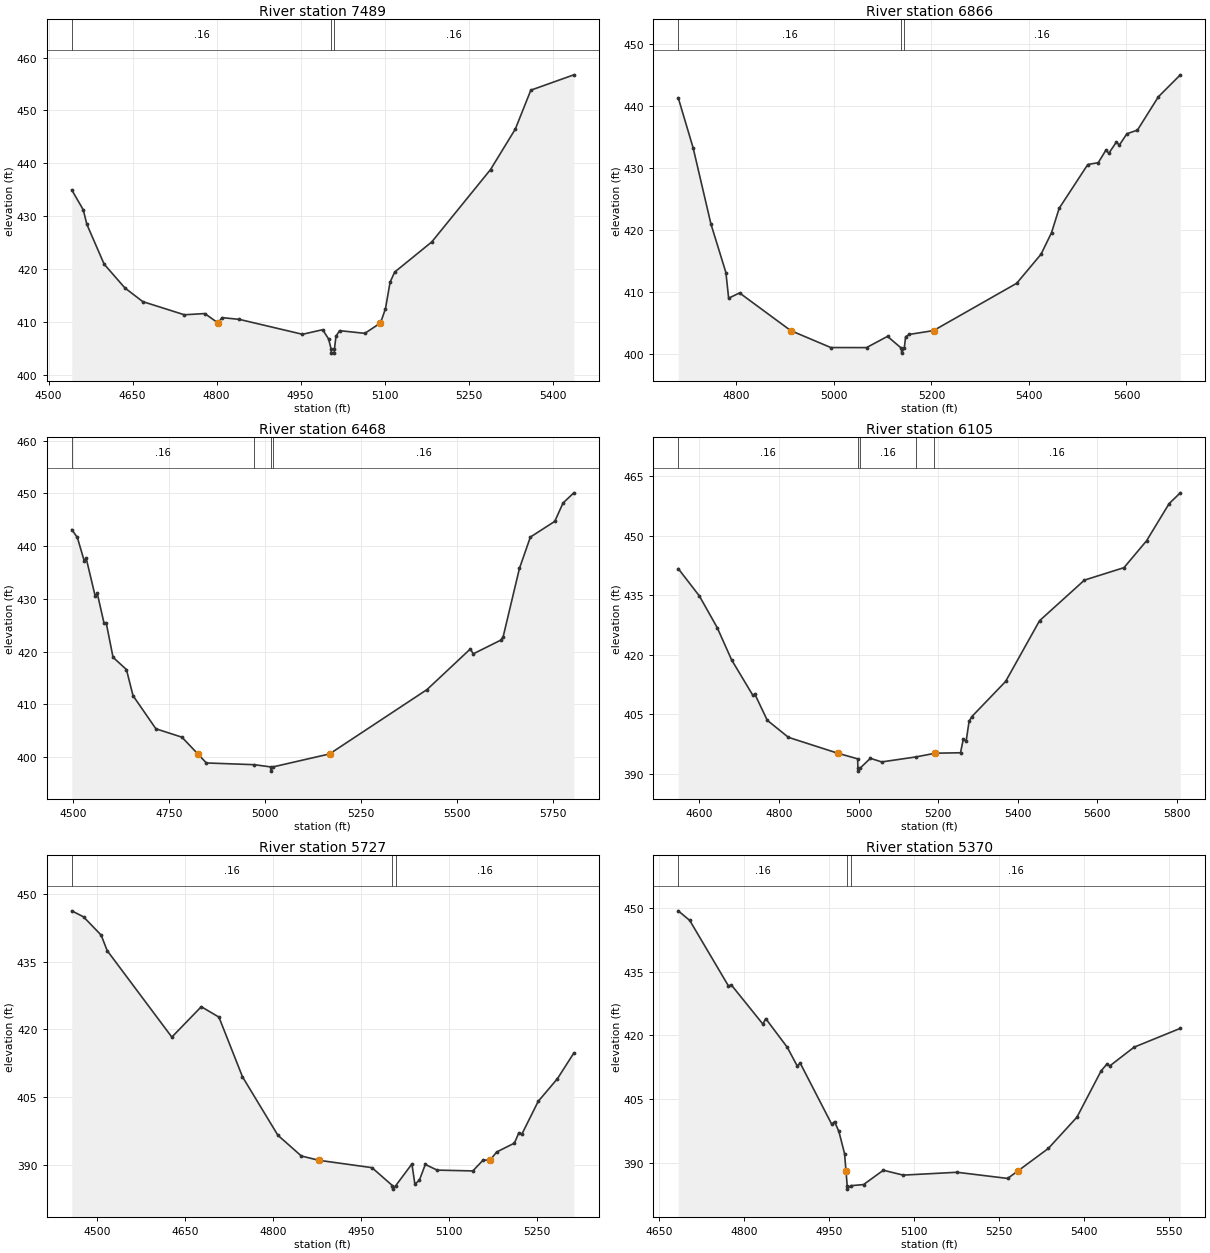
Type RM Length L Ch R = 1,7489,623,623,623
BEGIN DESCRIPTION:
UNT 020 IN DRY CR WATERSHED 14.0
END DESCRIPTION:
XS GIS Cut Line= 3
      2943780.59      6946415.64      2943934.31      6946847.61
      2944136.52      6947236.02
#Sta/Elev= 30
  4541.5  434.98  4562.0  431.21  4568.5  428.45  4599.3  420.94  4636.3  416.45
  4668.2  413.86  4742.5  411.37  4779.0  411.60  4802.7  409.82  4809.8  410.83
  4840.7  410.50  4953.4  407.68  4989.5  408.55  5000.0  406.80  5004.5  404.92
  5005.0  404.12  5010.0  404.12  5010.5  404.92  5013.2  407.29  5019.6  408.37
  5064.7  407.86  5092.7  409.82  5101.6  412.53  5109.8  417.52  5118.0  419.44
  5184.3  425.15  5289.2  438.83  5333.4  446.48  5361.1  453.83  5437.9  456.73
#Mann=3,-1,0
  4541.5    0.16       0  5004.5    0.07       0  5010.5    0.16       0
Bank Sta=4802.7,5092.7
Exp/Cntr=0.3,0.1

Type RM Length L Ch R = 1,6866,398,398,398
BEGIN DESCRIPTION:
UNT 020 IN DRY CR WATERSHED 13.0
END DESCRIPTION:
XS GIS Cut Line= 3
      2943575.00      6946475.00      2943425.00      6946775.00
      2943774.98      6947374.97
#Sta/Elev= 30
  4680.5  441.36  4711.2  433.25  4747.6  421.02  4778.3  413.20  4783.9  409.07
  4806.3  409.92  4911.3  403.85  4993.5  401.12  5066.8  401.11  5109.8  402.92
  5138.2  401.02  5138.7  400.22  5144.2  401.02  5147.0  402.87  5154.8  403.24
  5204.2  403.85  5374.8  411.47  5424.8  416.16  5446.3  419.63  5462.0  423.56
  5520.7  430.61  5542.2  430.91  5558.0  432.94  5563.8  432.41  5579.5  434.25
  5585.3  433.73  5601.0  435.57  5622.5  436.15  5665.5  441.52  5710.5  445.06
#Mann=3,-1,0
  4680.5    0.16       0  5138.2    0.07       0  5144.2    0.16       0
Bank Sta=4911.3,5204.2
Exp/Cntr=0.3,0.1

Type RM Length L Ch R = 1,6468,363,363,363
BEGIN DESCRIPTION:
UNT 020 IN DRY CR WATERSHED 12.0
END DESCRIPTION:
XS GIS Cut Line= 3
      2942674.98      6946774.99      2943125.00      6946975.00
      2943675.00      6947575.00
#Sta/Elev= 30
  4497.0  443.15  4511.4  441.67  4529.2  437.27  4534.6  437.68  4557.9  430.55
  4563.4  431.04  4581.1  425.34  4586.6  425.46  4604.4  418.93  4639.3  416.60
  4656.4  411.65  4715.9  405.37  4783.6  403.78  4825.1  400.60  4847.2  398.89
  4972.1  398.56  5014.5  398.14  5015.0  397.34  5020.5  398.14  5167.7  400.60
  5421.4  412.81  5534.2  420.52  5541.6  419.58  5612.6  422.16  5619.3  422.78
  5661.9  435.80  5690.3  441.73  5753.8  444.71  5775.3  448.20  5803.4  450.12
#Mann=4,-1,0
  4497.0    0.16       0  4972.1    0.12       0  5014.5    0.07       0
  5020.5    0.16       0
Bank Sta=4825.1,5167.7
Exp/Cntr=0.3,0.1

Type RM Length L Ch R = 1,6105,378,378,378
BEGIN DESCRIPTION:
UNT 020 IN DRY CR WATERSHED 11.0
END DESCRIPTION:
XS GIS Cut Line= 3
      2942675.01      6946825.02      2942875.00      6947225.00
      2943424.98      6947824.97
#Sta/Elev= 30
  4547.1  441.67  4600.2  434.77  4644.9  426.81  4681.2  418.66  4734.4  409.75
  4739.9  409.95  4770.7  403.44  4823.8  399.14  4947.6  395.14  4997.7  393.72
  4998.4  391.42  4998.9  390.62  5004.4  391.42  5029.7  393.85  5058.1  392.94
  5144.1  394.20  5190.3  395.09  5192.6  395.14  5256.1  395.25  5263.4  398.78
  5270.2  398.12  5277.6  403.16  5284.4  404.35  5369.5  413.24  5454.6  428.53
  5567.4  438.77  5666.7  441.91  5723.4  448.68  5780.2  458.07  5808.2  460.77
#Mann=5,-1,0
  4547.1    0.16       0  4998.4    0.07       0  5004.4    0.16       0
  5144.1    0.12       0  5190.3    0.16       0
Bank Sta=4947.6,5192.6
Exp/Cntr=0.3,0.1

Type RM Length L Ch R = 1,5727,357,357,357
BEGIN DESCRIPTION:
UNT 020 IN DRY CR WATERSHED 10.0
END DESCRIPTION:
XS GIS Cut Line= 3
      2942625.00      6946774.98      2942575.00      6947325.00
      2942625.00      6947624.98
#Sta/Elev= 30
  4456.2  446.21  4476.3  444.88  4506.4  440.83  4516.5  437.44  4626.9  418.32
  4677.1  425.03  4707.2  422.74  4747.4  409.55  4807.7  396.65  4847.8  392.06
  4877.6  391.11  4968.3  389.48  5003.0  385.54  5003.5  384.74  5009.0  385.54
  5036.4  390.30  5041.4  385.88  5049.0  386.66  5059.2  390.19  5079.4  388.94
  5140.3  388.76  5158.0  391.18  5169.5  391.11  5180.8  392.93  5211.2  394.90
  5218.8  397.18  5223.9  396.88  5251.8  404.12  5284.7  409.15  5312.6  414.81
#Mann=3,-1,0
  4456.2    0.16       0  5003.0    0.07       0  5009.0    0.16       0
Bank Sta=4877.6,5169.5
Exp/Cntr=0.3,0.1

Type RM Length L Ch R = 1,5370,503,503,503
BEGIN DESCRIPTION:
UNT 020 IN DRY CR WATERSHED 9.0
END DESCRIPTION:
XS GIS Cut Line= 3
      2942375.01      6946924.96      2942325.00      6947225.00
      2942625.01      6947725.02
#Sta/Elev= 30
  4683.2  449.26  4703.5  447.01  4771.9  431.63  4777.0  431.86  4832.8  422.66
  4837.8  423.95  4875.9  417.21  4893.6  412.79  4898.7  413.51  4954.4  399.15
  4959.5  399.75  4967.1  397.44  4977.2  392.21  4979.6  388.25  4981.8  384.70
  4982.3  383.90  4987.8  384.70  5010.7  384.97  5045.7  388.34  5080.7  387.19
  5175.9  387.86  5265.3  386.41  5284.3  388.25  5337.2  393.45  5387.8  400.80
  5430.5  411.66  5440.3  413.21  5446.1  412.86  5488.8  417.24  5570.5  421.66
#Mann=3,-1,0
  4683.2    0.16       0  4981.8    0.07       0  4987.8    0.16       0
Bank Sta=4979.6,5284.3
Exp/Cntr=0.3,0.1

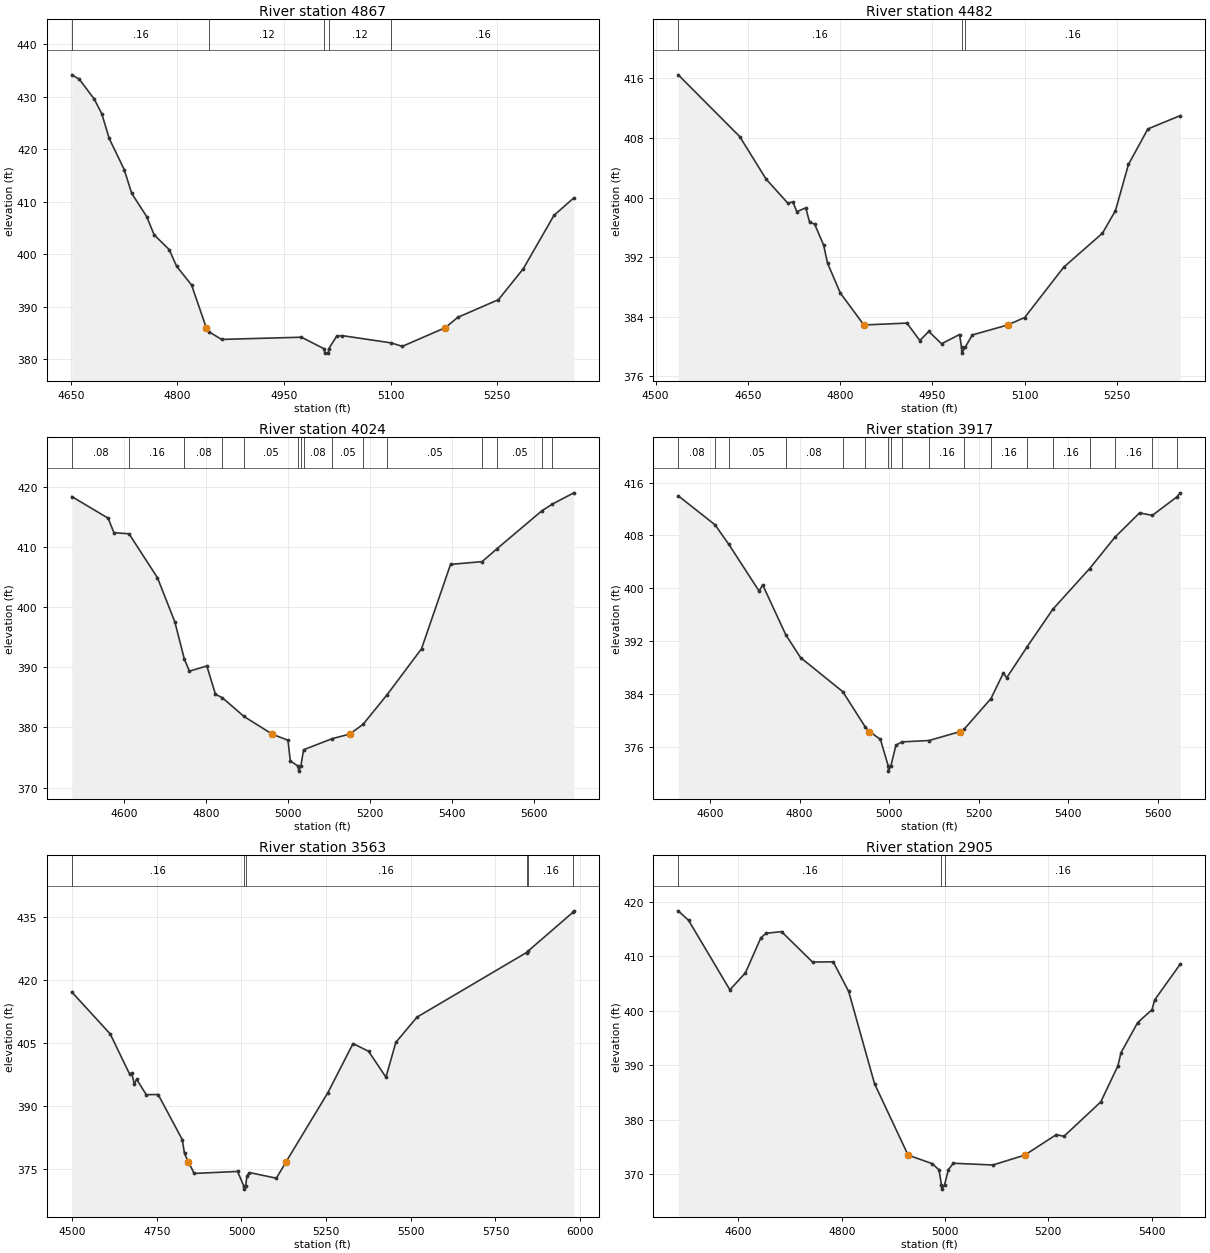
Type RM Length L Ch R = 1,4867,385,385,385
BEGIN DESCRIPTION:
UNT 020 IN DRY CR WATERSHED 8.0
END DESCRIPTION:
XS GIS Cut Line= 3
      2941974.99      6947174.97      2942075.00      6947475.00
      2942375.02      6947725.02
#Sta/Elev= 30
  4651.3  434.16  4661.9  433.33  4683.0  429.53  4693.5  426.77  4704.0  422.05
  4725.1  416.14  4735.7  411.59  4756.7  407.19  4767.3  403.70  4788.4  400.90
  4798.9  397.73  4820.0  394.15  4840.6  386.03  4844.7  385.23  4862.2  383.80
  4974.7  384.22  5006.9  381.99  5007.4  381.19  5012.4  381.19  5012.9  381.99
  5024.2  384.41  5032.0  384.52  5100.9  383.14  5116.6  382.48  5177.1  386.03
  5194.7  388.00  5252.0  391.37  5287.1  397.29  5330.1  407.41  5358.1  410.74
#Mann=5,-1,0
  4651.3    0.16       0  4844.7    0.12       0  5006.9    0.07       0
  5012.9    0.12       0  5100.9    0.16       0
Bank Sta=4840.6,5177.1
Exp/Cntr=0.3,0.1

Type RM Length L Ch R = 1,4482,458,458,458
BEGIN DESCRIPTION:
UNT 020 IN DRY CR WATERSHED 7.0
END DESCRIPTION:
XS GIS Cut Line= 3
      2941575.03      6947525.02      2941975.00      6947825.00
      2942275.00      6947925.00
#Sta/Elev= 30
  4536.7  416.48  4636.7  408.19  4679.4  402.50  4714.8  399.26  4723.1  399.43
  4729.4  398.12  4744.0  398.62  4750.2  396.72  4758.5  396.44  4773.1  393.62
  4779.4  391.21  4800.2  387.20  4838.5  382.91  4908.5  383.16  4929.4  380.82
  4944.0  382.04  4964.8  380.39  4994.0  381.63  4997.2  379.93  4997.7  379.13
  5003.2  379.93  5014.8  381.57  5072.3  382.91  5099.9  383.91  5163.2  390.65
  5226.4  395.23  5247.5  398.26  5268.6  404.46  5300.2  409.22  5352.9  411.01
#Mann=3,-1,0
  4536.7    0.16       0  4997.2    0.07       0  5003.2    0.16       0
Bank Sta=4838.5,5072.3
Exp/Cntr=0.3,0.1

Type RM Length L Ch R = 1,4024,107,107,107
BEGIN DESCRIPTION:
Mapping XS 6d28b2bf
END DESCRIPTION:
XS GIS Cut Line= 3
      2941175.86      6947618.80      2941562.14      6947987.72
      2942060.66      6948464.56
#Sta/Elev= 30
  4473.0  418.43  4561.6  414.83  4575.8  412.42  4612.6  412.23  4681.8  404.93
  4724.2  397.58  4747.6  391.34  4759.8  389.37  4802.3  390.23  4823.3  385.52
  4840.0  384.95  4892.9  381.83  4961.5  378.89  5000.1  377.87  5005.7  374.44
  5025.4  373.53  5025.9  372.73  5031.4  373.53  5038.1  376.29  5108.0  378.14
  5150.3  378.89  5183.2  380.52  5242.1  385.48  5325.6  393.09  5396.4  407.14
  5473.4  407.60  5510.2  409.78  5618.5  416.03  5644.2  417.16  5697.0  419.05
#Mann=15,-1,0
  4473.0    0.08       0  4612.6    0.16       0  4747.6    0.08       0
  4840.0    0.16       0  4892.9    0.05       0  5025.4    0.04       0
  5031.4    0.05       0  5038.1    0.08       0  5108.0    0.05       0
  5183.2    0.08       0  5242.1    0.05       0  5473.4    0.08       0
  5510.2    0.05       0  5618.5    0.08       0  5644.2    0.05       0
Bank Sta=4961.5,5150.3
Exp/Cntr=0.3,0.1

Type RM Length L Ch R = 1,3917,354,354,354
BEGIN DESCRIPTION:
Mapping XS 618f0383
END DESCRIPTION:
XS GIS Cut Line= 3
      2941158.50      6947735.99      2941501.38      6948026.78
      2941965.80      6948512.91
#Sta/Elev= 30
  4529.0  414.01  4611.1  409.62  4642.0  406.65  4709.9  399.55  4717.6  400.53
  4769.3  392.95  4802.2  389.50  4896.7  384.32  4947.4  378.92  4956.1  378.28
  4980.8  377.09  4998.2  373.08  4998.7  372.28  5004.2  373.08  5015.4  376.21
  5028.5  376.71  5089.3  376.92  5159.2  378.28  5168.5  378.69  5227.7  383.27
  5255.6  387.16  5262.9  386.42  5308.4  391.11  5366.1  396.82  5448.4  402.99
  5504.5  407.71  5559.8  411.42  5588.4  411.04  5642.9  413.83  5650.9  414.46
#Mann=18,-1,0
  4529.0    0.08       0  4611.1    0.16       0  4642.0    0.05       0
  4769.3    0.08       0  4896.7    0.05       0  4947.4    0.16       0
  4998.2    0.07       0  5004.2    0.16       0  5028.5    0.08       0
  5089.3    0.16       0  5168.5    0.08       0  5227.7    0.16       0
  5308.4    0.05       0  5366.1    0.16       0  5448.4    0.08       0
  5504.5    0.16       0  5588.4    0.08       0  5642.9    0.16       0
Bank Sta=4956.1,5159.2
Exp/Cntr=0.3,0.1

Type RM Length L Ch R = 1,3563,658,658,658
BEGIN DESCRIPTION:
Mapping XS 2448d644
END DESCRIPTION:
XS GIS Cut Line= 3
      2940984.86      6948005.06      2941418.91      6948382.69
      2942241.81      6948763.82
#Sta/Elev= 30
  4499.1  417.13  4612.6  407.17  4669.6  397.67  4676.2  397.86  4683.8  395.22
  4690.5  396.41  4719.0  392.75  4754.1  392.78  4825.3  382.08  4831.9  378.78
  4842.8  376.86  4860.4  374.04  4988.6  374.51  5006.5  371.11  5007.0  370.31
  5012.5  371.11  5016.2  373.45  5023.7  374.24  5103.2  372.91  5132.2  376.86
  5255.2  393.22  5329.4  404.89  5375.3  403.05  5426.6  396.89  5455.8  405.17
  5518.3  411.16  5841.7  426.51  5845.1  426.77  5979.7  436.14  5981.3  436.41
#Mann=6,-1,0
  4499.1    0.16       0  5006.5    0.07       0  5012.5    0.16       0
  5841.7    0.08       0  5845.1    0.16       0  5979.7    0.05       0
Bank Sta=4842.8,5132.2
Exp/Cntr=0.3,0.1

Type RM Length L Ch R = 1,2905,628,628,628
BEGIN DESCRIPTION:
UNT 020 IN DRY CR WATERSHED 4.0
END DESCRIPTION:
XS GIS Cut Line= 3
      2940775.01      6948675.00      2941225.00      6948675.00
      2941724.99      6948825.00
#Sta/Elev= 30
  4483.5  418.38  4503.5  416.64  4583.5  403.88  4613.5  406.99  4643.5  413.44
  4653.5  414.26  4683.5  414.56  4743.5  408.98  4783.5  409.02  4813.5  403.58
  4863.5  386.66  4928.5  373.54  4975.3  371.98  4988.3  370.83  4993.1  368.10
  4993.6  367.30  4999.1  368.10  5006.6  370.90  5016.1  372.05  5092.7  371.73
  5154.2  373.54  5215.4  377.30  5230.2  376.99  5301.5  383.31  5334.6  389.91
  5340.7  392.34  5372.9  397.86  5400.7  400.24  5405.9  402.04  5455.5  408.62
#Mann=3,-1,0
  4483.5    0.16       0  4993.1    0.07       0  4999.1    0.16       0
Bank Sta=4928.5,5154.2
Exp/Cntr=0.3,0.1

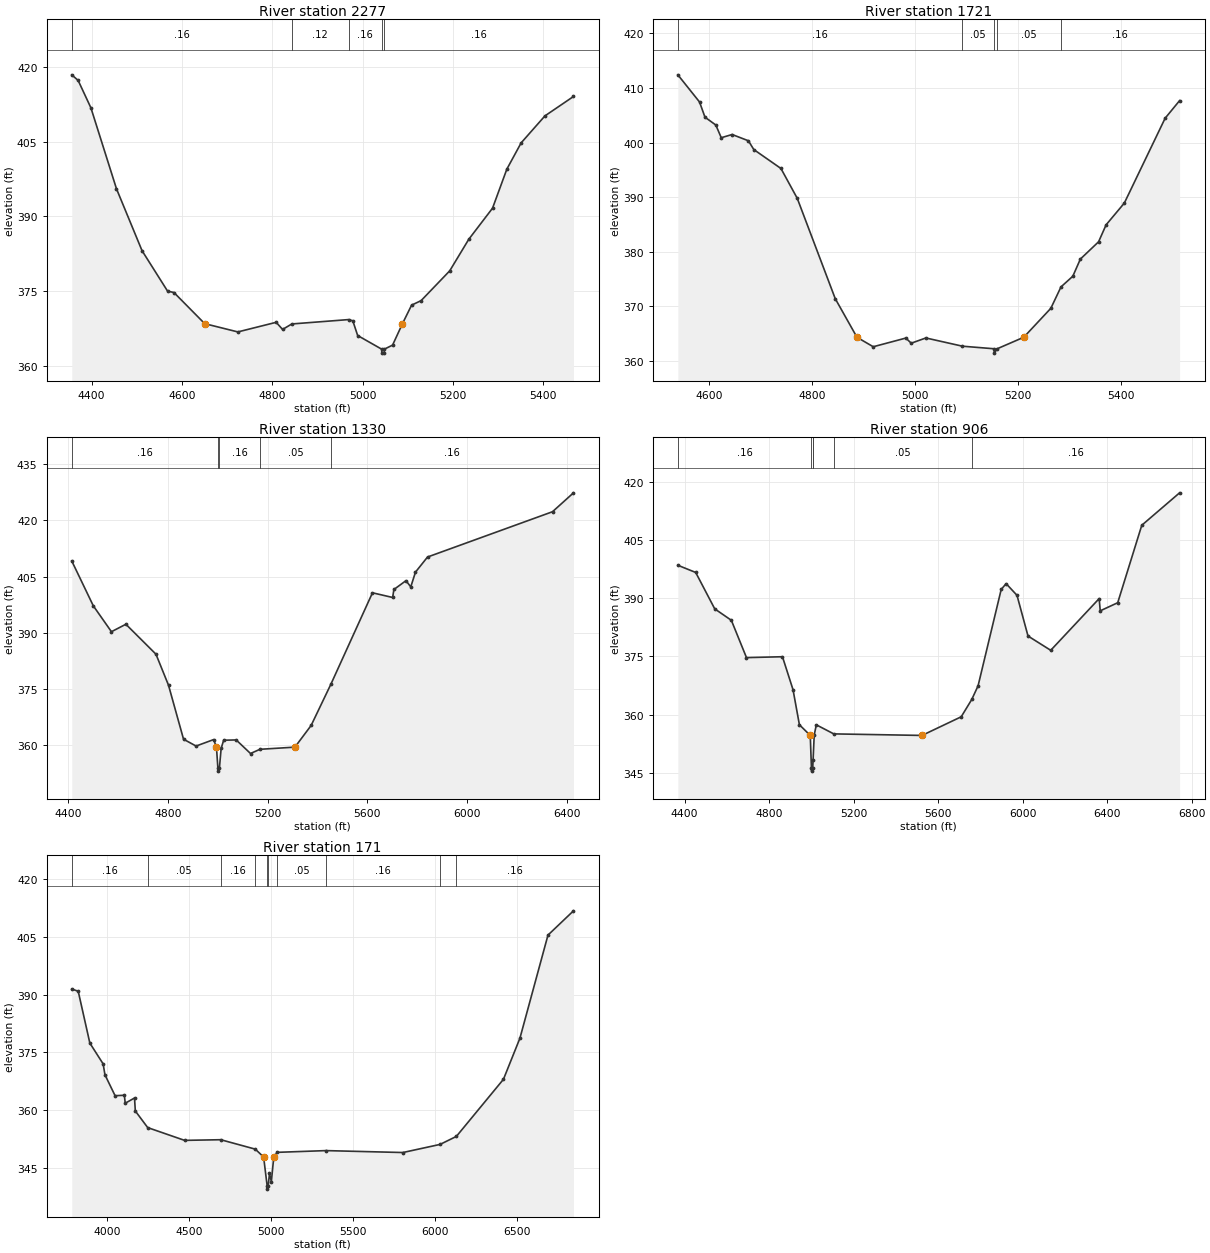
Type RM Length L Ch R = 1,2277,556,556,556
BEGIN DESCRIPTION:
UNT 020 IN DRY CR WATERSHED 3.0
END DESCRIPTION:
XS GIS Cut Line= 3
      2940725.01      6948725.01      2941175.00      6949175.00
      2941624.97      6949324.99
#Sta/Elev= 30
  4356.1  418.41  4370.2  417.29  4398.5  411.78  4455.1  395.52  4511.7  383.08
  4568.2  374.96  4582.4  374.67  4650.4  368.42  4723.8  366.76  4808.6  368.69
  4822.8  367.26  4843.3  368.36  4969.0  369.24  4978.3  368.99  4989.0  366.04
  5042.1  363.30  5042.6  362.50  5047.7  362.50  5048.2  363.30  5066.3  364.11
  5088.2  368.42  5108.4  372.14  5129.5  373.05  5192.8  379.03  5234.9  385.36
  5287.6  391.62  5319.3  399.47  5350.9  404.74  5403.6  410.16  5466.8  414.06
#Mann=5,-1,0
  4356.1    0.16       0  4843.3    0.12       0  4969.0    0.16       0
  5042.1    0.07       0  5048.2    0.16       0
Bank Sta=4650.4,5088.2
Exp/Cntr=0.3,0.1

Type RM Length L Ch R = 1,1721,391,391,391
BEGIN DESCRIPTION:
UNT 020 IN DRY CR WATERSHED 2.0
END DESCRIPTION:
XS GIS Cut Line= 3
      2940625.02      6948925.05      2940775.00      6949375.00
      2941175.01      6949675.00
#Sta/Elev= 30
  4540.0  412.42  4582.1  407.44  4592.7  404.65  4613.7  403.22  4624.3  400.89
  4645.4  401.48  4677.0  400.33  4687.5  398.72  4740.2  395.25  4771.9  389.77
  4845.6  371.39  4887.8  364.31  4919.4  362.57  4982.7  364.16  4993.2  363.22
  5021.6  364.18  5092.7  362.67  5154.0  362.20  5154.5  361.40  5160.1  362.20
  5211.7  364.31  5264.3  369.62  5284.0  373.54  5307.0  375.50  5321.6  378.64
  5357.0  381.81  5371.6  384.92  5407.0  388.91  5486.2  404.46  5514.3  407.69
#Mann=5,-1,0
  4540.0    0.16       0  5092.7    0.05       0  5154.0    0.07       0
  5160.1    0.05       0  5284.0    0.16       0
Bank Sta=4887.8,5211.7
Exp/Cntr=0.3,0.1

Type RM Length L Ch R = 1,1330,424,424,424
BEGIN DESCRIPTION:
Mapping XS fb8a4a63
END DESCRIPTION:
XS GIS Cut Line= 3
      2940473.38      6948959.03      2940549.77      6949674.28
      2941811.82      6949958.59
#Sta/Elev= 30
  4413.8  409.17  4500.3  397.20  4573.0  390.30  4631.0  392.29  4751.7  384.30
  4802.0  376.03  4862.3  361.63  4912.6  359.81  4983.0  361.53  4994.4  359.52
  5000.1  353.92  5000.6  353.12  5006.2  353.92  5013.2  359.18  5023.2  361.36
  5073.5  361.44  5131.0  357.82  5168.9  358.94  5309.2  359.52  5374.2  365.30
  5453.9  376.36  5620.3  400.68  5701.2  399.43  5706.3  401.56  5754.7  403.91
  5774.0  402.26  5792.8  406.19  5841.2  410.22  6342.6  422.30  6426.8  427.34
#Mann=5,-1,0
  4413.8    0.16       0  5000.1    0.07       0  5006.2    0.16       0
  5168.9    0.05       0  5453.9    0.16       0
Bank Sta=4994.4,5309.2
Exp/Cntr=0.3,0.1

Type RM Length L Ch R = 1,906,735,735,735
BEGIN DESCRIPTION:
Mapping XS 3d259cb8
END DESCRIPTION:
XS GIS Cut Line= 3
      2940195.60      6949000.70      2940146.99      6949799.28
      2941667.81      6950209.00
#Sta/Elev= 30
  4367.9  398.56  4452.4  396.70  4542.5  387.30  4621.2  384.34  4692.8  374.70
  4863.1  374.93  4913.2  366.40  4943.3  357.36  4994.7  354.60  5000.3  346.18
  5000.8  345.38  5006.4  346.18  5008.1  348.25  5013.4  354.71  5023.4  357.34
  5106.0  355.00  5523.6  354.60  5709.3  359.42  5759.2  363.89  5789.1  367.42
  5898.6  392.32  5921.9  393.81  5973.3  390.80  6025.5  380.28  6133.0  376.59
  6362.3  389.95  6367.4  386.79  6450.1  388.88  6564.0  408.89  6743.0  417.27
#Mann=6,-1,0
  4367.9    0.16       0  5000.3    0.07       0  5006.4    0.16       0
  5008.1    0.07       0  5106.0    0.05       0  5759.2    0.16       0
Bank Sta=4994.7,5523.6
Exp/Cntr=0.3,0.1

Type RM Length L Ch R = 1,171,0,0,0
BEGIN DESCRIPTION:
UNT 020 IN DRY CR WATERSHED 1.0
END DESCRIPTION:
XS GIS Cut Line= 3
      2939961.62      6949016.13      2939767.53      6950217.04
      2941599.70      6950402.20
#Sta/Elev= 30
  3783.5  391.48  3822.9  390.90  3893.8  377.43  3974.8  372.02  3985.9  369.18
  4047.6  363.76  4104.2  363.87  4109.3  361.80  4166.0  363.16  4171.0  359.78
  4246.4  355.47  4471.2  352.15  4691.6  352.32  4902.1  349.87  4952.9  347.82
  4974.6  340.28  4975.1  339.48  4980.7  340.28  4988.7  343.58  5000.0  341.43
  5014.8  347.82  5035.5  349.04  5333.4  349.49  5801.5  348.99  6028.4  351.10
  6127.7  353.18  6414.6  368.02  6515.1  378.71  6686.0  405.49  6841.5  411.80
#Mann=10,-1,0
  3783.5    0.16       0  4246.4    0.05       0  4691.6    0.16       0
  4902.1    0.12       0  4974.6    0.07       0  4980.7    0.12       0
  5035.5    0.05       0  5333.4    0.16       0  6028.4    0.05       0
  6127.7    0.16       0
Bank Sta=4952.9,5014.8
Exp/Cntr=0.3,0.1

Chan Stop Cuts=-1