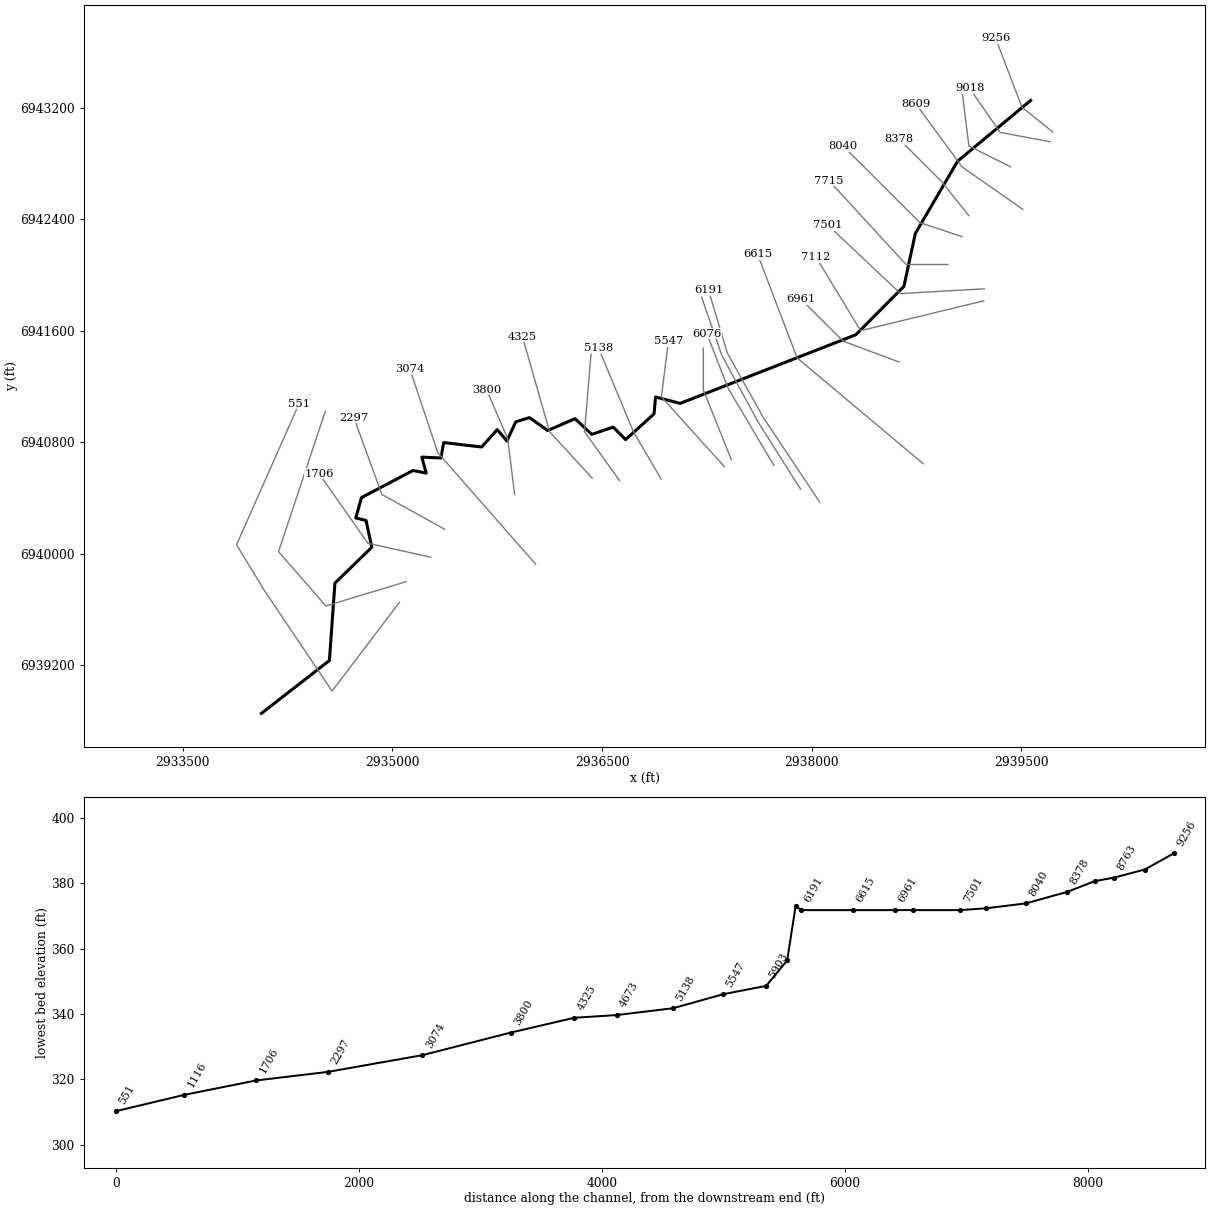
--- UNT 021 IN DRY CR WATERSHED.prj (project) ---

Proj Title=UNT 021 IN DRY CR WATERSHED Base Level Engineering
Current Plan=p01
Default Exp/Contr=0.3,0.1
English Units
Geom File=g01
Flow File=f01
Plan File=p01
BEGIN DESCRIPTION:
UNT 021 IN DRY CR WATERSHED
END DESCRIPTION:

--- UNT 021 IN DRY CR WATERSHED.p01 (plan) ---

Plan Title=Multiple Run
Short Identifier=Multiple
Geom File=g01
Flow File=f01
Subcritical Flow
K Sum by GR= 0
Std Step Tol= 0.01
Critical Tol= 0.01
Num of Std Step Trials= 20
Max Error Tol= 0.3
Flow Tol Ratio= 0.001
Split Flow NTrial= 30
Split Flow Tol= 0.02
Split Flow Ratio= 0.02
Log Output Level= 0
Friction Slope Method= 1
Unsteady Friction Slope Method= 2
Unsteady Bridges Friction Slope Method= 1
Parabolic Critical Depth
Global Vel Dist=  1 , 1 , 1
Global Log Level= 0
CheckData=True
Encroach Param= -1, 0, 0, 0
BEGIN DESCRIPTION:
Multiple Run
END DESCRIPTION:

--- UNT 021 IN DRY CR WATERSHED.f01 (steady flow) ---

Flow Title=Multiple
Number of Profiles=7
Profile Names=10-year,25-year,50-year,1pct_min,100-year,1pct_plu,500-year
River Rch & RM= UNT 021 IN DRY C,Reach-1,9256
     392     519     622     372     742    1481    1056
River Rch & RM= UNT 021 IN DRY C,Reach-1,6961
     812    1123    1384     849    1694    3381    2542
Boundary for River Rch & Prof#=UNT 021 IN DRY C,Reach-1,1
Up Type=0
Dn Type=3
Dn Slope=0.005
Boundary for River Rch & Prof#=UNT 021 IN DRY C,Reach-1,2
Up Type=0
Dn Type=3
Dn Slope=0.005
Boundary for River Rch & Prof#=UNT 021 IN DRY C,Reach-1,3
Up Type=0
Dn Type=3
Dn Slope=0.005
Boundary for River Rch & Prof#=UNT 021 IN DRY C,Reach-1,4
Up Type=0
Dn Type=3
Dn Slope=0.005
Boundary for River Rch & Prof#=UNT 021 IN DRY C,Reach-1,5
Up Type=0
Dn Type=3
Dn Slope=0.005
Boundary for River Rch & Prof#=UNT 021 IN DRY C,Reach-1,6
Up Type=0
Dn Type=3
Dn Slope=0.005
Boundary for River Rch & Prof#=UNT 021 IN DRY C,Reach-1,7
Up Type=0
Dn Type=3
Dn Slope=0.005

--- UNT 021 IN DRY CR WATERSHED.g01 (geometry) ---

Geom Title=Existing Conditions

River Reach=UNT 021 IN DRY C,Reach-1
Reach XY= 30
      2939566.51      6943251.88      2939044.10      6942816.22
      2938741.71      6942297.67      2938659.95      6941918.04
      2938315.59      6941570.71      2937059.00      6941078.40
      2936883.06      6941124.41      2936872.14      6941002.94
      2936668.59      6940818.39      2936580.09      6940908.47
      2936427.28      6940856.15      2936306.17      6940968.55
      2936111.17      6940883.51      2935981.32      6940976.39
      2935883.06      6940946.19      2935819.39      6940808.80
      2935750.38      6940890.03      2935638.74      6940765.52
      2935367.32      6940797.24      2935347.42      6940686.46
      2935210.56      6940693.22      2935242.13      6940578.61
      2935147.89      6940596.88      2934779.28      6940402.63
      2934738.31      6940256.65      2934811.62      6940238.70
      2934852.91      6940045.93      2934589.14      6939789.18
      2934549.58      6939233.56      2934063.34      6938854.49

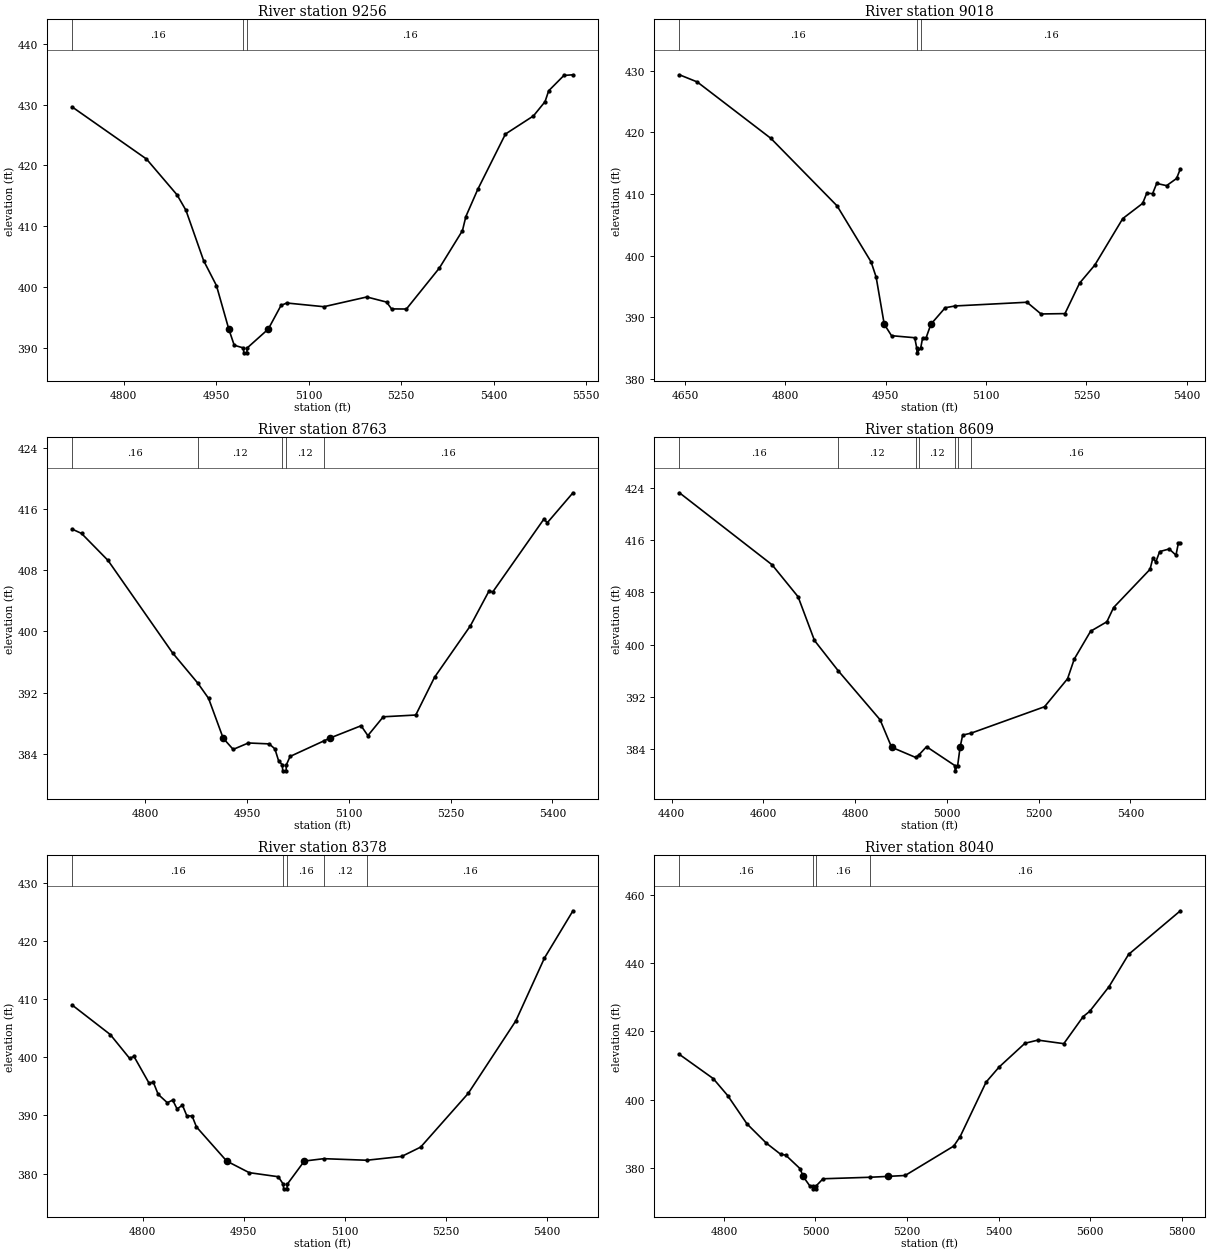
Type RM Length L Ch R = 1,9256,238,238,238
BEGIN DESCRIPTION:
UNT 021 IN DRY CR WATERSHED 20.0
END DESCRIPTION:
XS GIS Cut Line= 3
      2939724.98      6943025.02      2939504.43      6943203.31
      2939316.18      6943697.36
#Sta/Elev= 30
  4716.4  429.63  4837.1  421.06  4886.7  415.17  4901.1  412.64  4929.8  404.36
  4950.6  400.26  4970.6  393.11  4979.4  390.46  4994.4  390.01  4994.9  389.21
  4999.9  389.21  5000.4  390.01  5034.6  393.11  5055.3  397.00  5064.6  397.40
  5124.8  396.79  5194.4  398.39  5226.5  397.55  5234.5  396.43  5258.6  396.41
  5312.1  403.15  5349.5  409.29  5355.0  411.60  5374.3  416.07  5419.2  425.16
  5464.6  428.14  5483.4  430.48  5489.3  432.27  5514.0  434.79  5528.7  434.90
#Mann=3,-1,0
  4716.4    0.16       0  4994.4    0.07       0  5000.4    0.16       0
Bank Sta=4970.6,5034.6
Exp/Cntr=0.3,0.1

Type RM Length L Ch R = 1,9018,255,255,255
BEGIN DESCRIPTION:
Mapping XS db8869ff
END DESCRIPTION:
XS GIS Cut Line= 3
      2939706.76      6942955.21      2939348.72      6943022.48
      2939129.75      6943339.01
#Sta/Elev= 30
  4641.4  429.34  4668.0  428.18  4778.1  419.04  4877.2  408.09  4928.1  399.00
  4935.6  396.55  4947.7  388.91  4958.6  387.05  4993.3  386.72  4996.3  385.07
  4996.8  384.27  5002.3  385.07  5005.1  386.70  5010.3  386.70  5017.5  388.91
  5038.9  391.58  5053.8  391.87  5161.2  392.47  5182.2  390.57  5218.0  390.63
  5239.8  395.56  5262.6  398.49  5304.5  406.04  5334.2  408.50  5340.3  410.14
  5349.1  410.08  5355.2  411.73  5370.0  411.37  5384.9  412.53  5390.6  414.10
#Mann=3,-1,0
  4641.4    0.16       0  4996.3    0.07       0  5002.3    0.16       0
Bank Sta=4947.7,5017.5
Exp/Cntr=0.3,0.1

Type RM Length L Ch R = 1,8763,154,154,154
BEGIN DESCRIPTION:
UNT 021 IN DRY CR WATERSHED 19.0
END DESCRIPTION:
XS GIS Cut Line= 3
      2939425.04      6942774.98      2939125.00      6942925.00
      2939075.00      6943325.03
#Sta/Elev= 30
  4691.8  413.35  4705.8  412.78  4744.9  409.25  4840.0  397.18  4877.3  393.22
  4893.1  391.24  4914.7  386.03  4929.4  384.57  4951.8  385.41  4982.5  385.29
  4990.9  384.64  4996.5  383.05  5001.9  382.57  5002.4  381.77  5007.4  381.77
  5007.9  382.57  5013.3  383.65  5063.1  385.68  5071.5  386.03  5118.0  387.66
  5128.0  386.37  5150.7  388.83  5198.6  389.06  5226.3  393.99  5279.2  400.72
  5306.9  405.31  5312.0  405.12  5387.5  414.65  5392.6  414.18  5430.4  418.09
#Mann=5,-1,0
  4691.8    0.16       0  4877.3    0.12       0  5001.9    0.07       0
  5007.9    0.12       0  5063.1    0.16       0
Bank Sta=4914.7,5071.5
Exp/Cntr=0.3,0.1

Type RM Length L Ch R = 1,8609,231,231,231
BEGIN DESCRIPTION:
Mapping XS 3c222d44
END DESCRIPTION:
XS GIS Cut Line= 3
      2939510.43      6942470.54      2939075.57      6942775.21
      2938744.81      6943228.37
#Sta/Elev= 30
  4417.1  423.24  4619.1  412.23  4675.8  407.34  4711.5  400.66  4763.1  396.04
  4854.5  388.54  4879.6  384.34  4932.0  382.78  4938.4  383.11  4955.8  384.42
  5017.6  381.53  5018.1  380.73  5023.6  381.53  5028.9  384.34  5034.5  386.19
  5053.3  386.50  5213.0  390.53  5263.2  394.81  5277.8  397.82  5313.4  402.07
  5348.9  403.52  5363.6  405.70  5443.0  411.54  5449.3  413.30  5455.5  412.65
  5464.0  414.25  5484.8  414.65  5499.5  413.70  5504.7  415.53  5509.1  415.53
#Mann=7,-1,0
  4417.1    0.16       0  4763.1    0.12       0  4932.0    0.16       0
  4938.4    0.12       0  5017.6    0.07       0  5023.6    0.12       0
  5053.3    0.16       0
Bank Sta=4879.6,5028.9
Exp/Cntr=0.3,0.1

Type RM Length L Ch R = 1,8378,338,338,338
BEGIN DESCRIPTION:
UNT 021 IN DRY CR WATERSHED 18.0
END DESCRIPTION:
XS GIS Cut Line= 3
      2939124.98      6942425.02      2938925.00      6942675.00
      2938625.00      6942975.00
#Sta/Elev= 30
  4694.9  408.98  4751.7  403.90  4780.5  399.80  4786.9  400.15  4809.3  395.56
  4815.7  395.71  4822.9  393.63  4836.5  392.19  4844.5  392.64  4851.0  391.12
  4859.0  391.76  4865.4  389.97  4873.4  389.89  4879.8  388.03  4924.7  382.17
  4958.2  380.18  5001.4  379.48  5008.8  378.20  5009.3  377.40  5014.3  377.40
  5014.8  378.20  5040.1  382.17  5069.1  382.58  5132.9  382.31  5184.7  382.96
  5213.0  384.57  5283.7  393.80  5354.4  406.25  5396.9  417.03  5439.3  425.15
#Mann=5,-1,0
  4694.9    0.16       0  5008.8    0.07       0  5014.8    0.16       0
  5069.1    0.12       0  5132.9    0.16       0
Bank Sta=4924.7,5040.1
Exp/Cntr=0.3,0.1

Type RM Length L Ch R = 1,8040,325,325,325
BEGIN DESCRIPTION:
UNT 021 IN DRY CR WATERSHED 17.0
END DESCRIPTION:
XS GIS Cut Line= 3
      2939075.03      6942274.99      2938775.00      6942375.00
      2938224.98      6942925.02
#Sta/Elev= 30
  4702.9  413.27  4776.7  406.20  4808.3  401.22  4850.5  392.92  4892.7  387.29
  4924.3  383.99  4934.8  383.80  4966.5  379.80  4973.0  377.54  4987.5  374.79
  4995.1  374.70  4995.6  373.90  5000.6  373.90  5001.1  374.70  5016.5  376.85
  5118.7  377.29  5157.4  377.54  5195.9  377.81  5302.0  386.42  5316.1  389.22
  5372.7  405.16  5401.0  409.56  5457.6  416.54  5485.8  417.46  5542.4  416.42
  5584.8  424.36  5599.0  425.89  5641.4  433.16  5683.8  442.55  5797.0  455.34
#Mann=4,-1,0
  4702.9    0.16       0  4995.1    0.07       0  5001.1    0.16       0
  5118.7    0.16       0
Bank Sta=4973,5157.4
Exp/Cntr=0.3,0.1

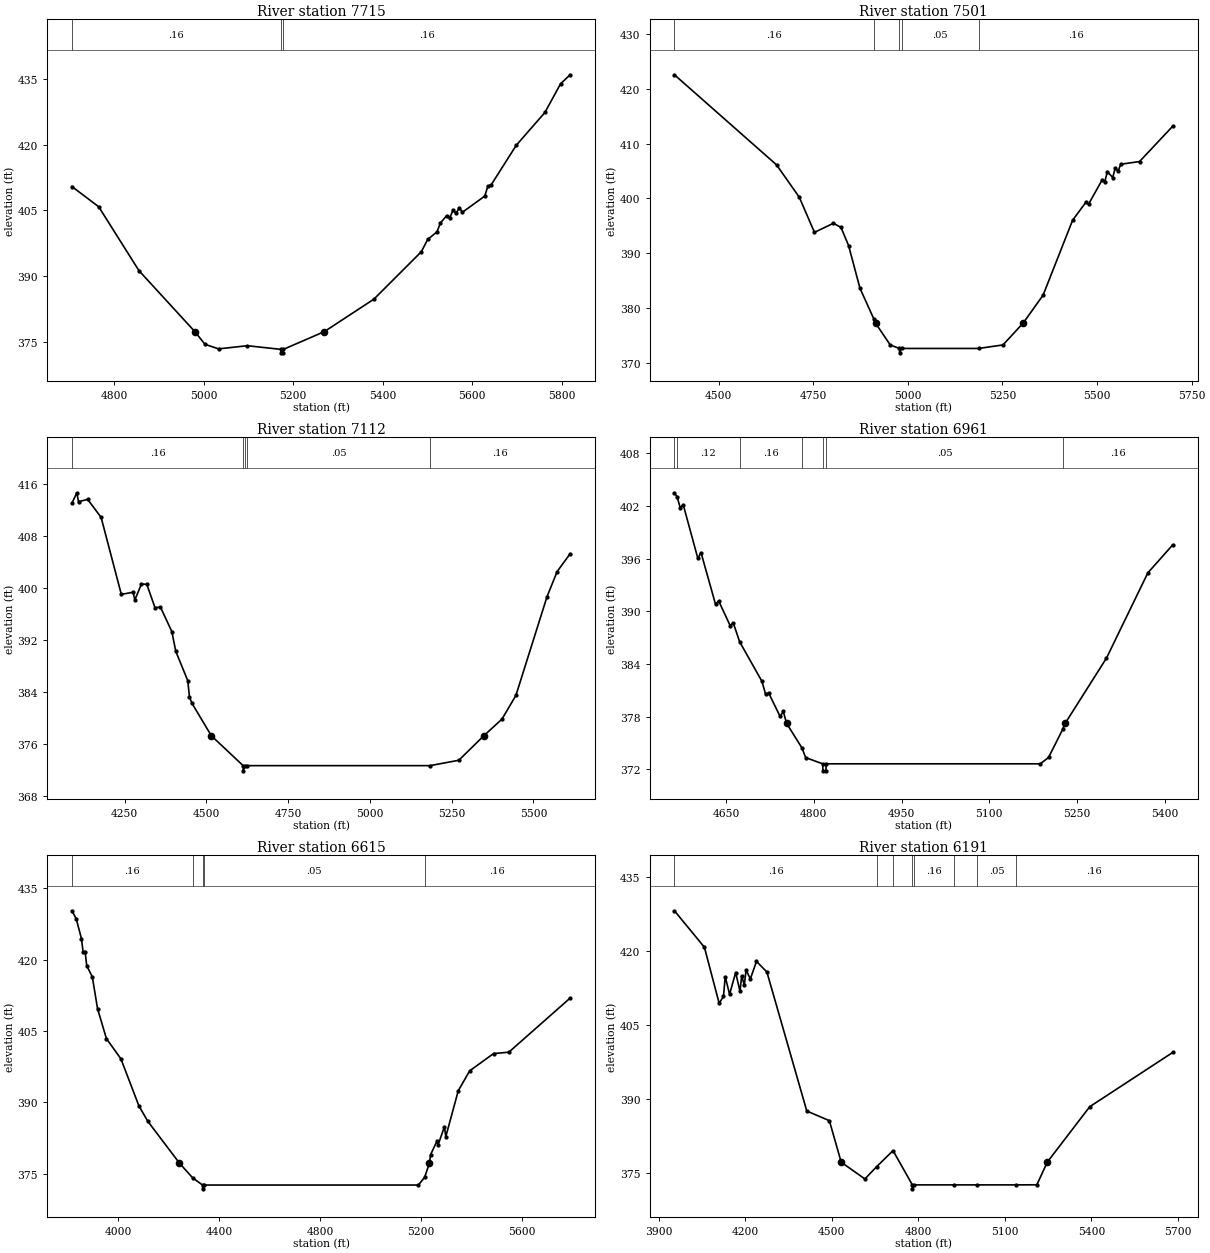
Type RM Length L Ch R = 1,7715,214,214,214
BEGIN DESCRIPTION:
UNT 021 IN DRY CR WATERSHED 16.0
END DESCRIPTION:
XS GIS Cut Line= 3
      2938974.98      6942075.00      2938675.00      6942075.00
      2938125.02      6942674.98
#Sta/Elev= 30
  4705.1  410.47  4765.1  405.83  4855.1  391.21  4980.1  377.26  5002.6  374.36
  5033.1  373.32  5097.3  374.04  5172.0  373.21  5172.5  372.41  5177.5  372.41
  5178.0  373.21  5269.4  377.26  5380.3  384.69  5486.4  395.55  5500.5  398.35
  5521.5  400.11  5528.9  402.11  5543.1  403.82  5549.9  403.24  5557.3  405.12
  5564.0  404.32  5571.4  405.64  5578.2  404.58  5628.2  408.28  5635.0  410.53
  5642.4  410.83  5698.5  419.89  5762.6  427.41  5797.7  433.98  5819.0  436.04
#Mann=3,-1,0
  4705.1    0.16       0  5172.0    0.07       0  5178.0    0.16       0
Bank Sta=4980.1,5269.4
Exp/Cntr=0.3,0.1

Type RM Length L Ch R = 1,7501,389,389,389
BEGIN DESCRIPTION:
Mapping XS a338698c
END DESCRIPTION:
XS GIS Cut Line= 3
      2939234.42      6941900.21      2938635.47      6941866.35
      2938114.64      6942358.54
#Sta/Elev= 30
  4383.3  422.53  4653.1  406.11  4713.2  400.21  4753.3  393.80  4803.4  395.46
  4823.4  394.70  4843.5  391.39  4873.5  383.62  4910.4  377.98  4914.8  377.25
  4953.6  373.27  4977.9  372.64  4978.4  371.84  4983.9  372.64  5186.8  372.64
  5251.4  373.28  5304.6  377.25  5357.4  382.35  5435.4  396.01  5470.6  399.30
  5477.9  398.98  5513.1  403.32  5520.4  403.02  5527.3  404.87  5541.4  403.80
  5548.3  405.58  5555.6  404.93  5562.5  406.22  5612.2  406.71  5699.8  413.14
#Mann=5,-1,0
  4383.3    0.16       0  4910.4    0.05       0  4977.9   0.033       0
  4983.9    0.05       0  5186.8    0.16       0
Bank Sta=4914.8,5304.6
Exp/Cntr=0.3,0.1

Type RM Length L Ch R = 1,7112,151,151,151
BEGIN DESCRIPTION:
UNT 021 IN DRY CR WATERSHED 15.0
END DESCRIPTION:
XS GIS Cut Line= 3
      2939231.82      6941814.27      2938350.00      6941600.00
      2938031.27      6942126.81
#Sta/Elev= 30
  4088.8  413.01  4103.9  414.63  4109.1  413.26  4137.0  413.61  4178.1  410.85
  4239.9  399.00  4276.1  399.32  4281.2  398.14  4301.6  400.60  4317.9  400.53
  4342.8  396.96  4359.6  397.03  4394.3  393.28  4406.5  390.22  4443.1  385.71
  4448.3  383.18  4456.0  382.23  4515.0  377.25  4612.3  372.64  4612.8  371.84
  4618.3  372.64  4623.3  372.64  5184.0  372.64  5271.8  373.47  5348.4  377.25
  5403.7  379.80  5446.3  383.45  5541.4  398.64  5572.4  402.51  5612.0  405.24
#Mann=5,-1,0
  4088.8    0.16       0  4612.3   0.033       0  4618.3    0.16       0
  4623.3    0.05       0  5184.0    0.16       0
Bank Sta=4515,5348.4
Exp/Cntr=0.3,0.1

Type RM Length L Ch R = 1,6961,346,346,346
BEGIN DESCRIPTION:
UNT 021 IN DRY CR WATERSHED 14.0
END DESCRIPTION:
XS GIS Cut Line= 3
      2938624.97      6941375.01      2938225.00      6941525.00
      2937925.02      6941824.98
#Sta/Elev= 30
  4561.9  403.51  4566.6  403.02  4571.7  401.82  4577.0  402.13  4601.9  396.04
  4607.3  396.70  4632.2  390.79  4637.5  391.19  4657.1  388.38  4662.4  388.70
  4673.3  386.54  4711.4  382.04  4717.6  380.59  4723.0  380.70  4742.5  378.03
  4747.9  378.62  4753.5  377.25  4779.9  374.44  4786.1  373.35  4815.2  372.64
  4815.7  371.84  4820.7  371.84  4821.2  372.64  5187.1  372.64  5201.2  373.36
  5225.5  376.58  5229.6  377.25  5300.2  384.68  5370.9  394.39  5413.3  397.57
#Mann=7,-1,0
  4561.9    0.16       0  4566.6    0.12       0  4673.3    0.16       0
  4779.9    0.05       0  4815.2   0.033       0  4821.2    0.05       0
  5225.5    0.16       0
Bank Sta=4753.5,5229.6
Exp/Cntr=0.3,0.1

Type RM Length L Ch R = 1,6615,424,424,424
BEGIN DESCRIPTION:
Mapping XS 1f8b1ce9
END DESCRIPTION:
XS GIS Cut Line= 3
      2938798.55      6940645.14      2937895.76      6941404.69
      2937613.65      6942146.87
#Sta/Elev= 30
  3816.6  430.25  3833.7  428.59  3854.6  424.36  3861.1  421.55  3868.9  421.69
  3875.4  418.72  3897.5  416.37  3918.3  409.67  3953.4  403.39  4010.6  399.17
  4082.1  389.26  4117.3  386.03  4242.7  377.24  4295.2  374.14  4334.1  372.64
  4334.6  371.84  4340.1  372.64  5189.3  372.64  5214.1  374.27  5233.1  377.24
  5237.6  379.01  5262.4  381.82  5267.7  381.12  5292.5  384.90  5297.9  382.80
  5347.4  392.47  5392.6  396.63  5487.3  400.26  5547.5  400.54  5790.4  411.91
#Mann=5,-1,0
  3816.6    0.16       0  4295.2    0.05       0  4334.1   0.033       0
  4340.1    0.05       0  5214.1    0.16       0
Bank Sta=4242.7,5233.1
Exp/Cntr=0.3,0.1

Type RM Length L Ch R = 1,6191,45,45,45
BEGIN DESCRIPTION:
Mapping XS 103bd61a
END DESCRIPTION:
XS GIS Cut Line= 4
      2938056.33      6940371.73      2937652.71      6940979.34
      2937396.63      6941439.41      2937262.20      6941890.41
#Sta/Elev= 30
  3954.7  428.17  4058.6  420.78  4109.7  409.41  4124.7  410.83  4130.7  414.83
  4145.8  411.24  4166.8  415.66  4181.9  411.85  4187.9  415.01  4196.9  413.09
  4202.9  416.16  4217.9  414.37  4239.0  417.92  4275.1  415.77  4413.4  387.60
  4491.6  385.65  4532.6  377.24  4614.8  373.84  4655.2  376.32  4712.3  379.58
  4779.2  372.64  4779.7  371.84  4785.2  372.64  4924.6  372.64  5004.2  372.64
  5137.0  372.64  5210.7  372.66  5246.7  377.24  5393.9  388.48  5681.3  399.46
#Mann=8,-1,0
  3954.7    0.16       0  4655.2    0.05       0  4712.3    0.16       0
  4779.2    0.07       0  4785.2    0.16       0  4924.6    0.16       0
  5004.2    0.05       0  5137.0    0.16       0
Bank Sta=4532.6,5246.7
Exp/Cntr=0.3,0.1

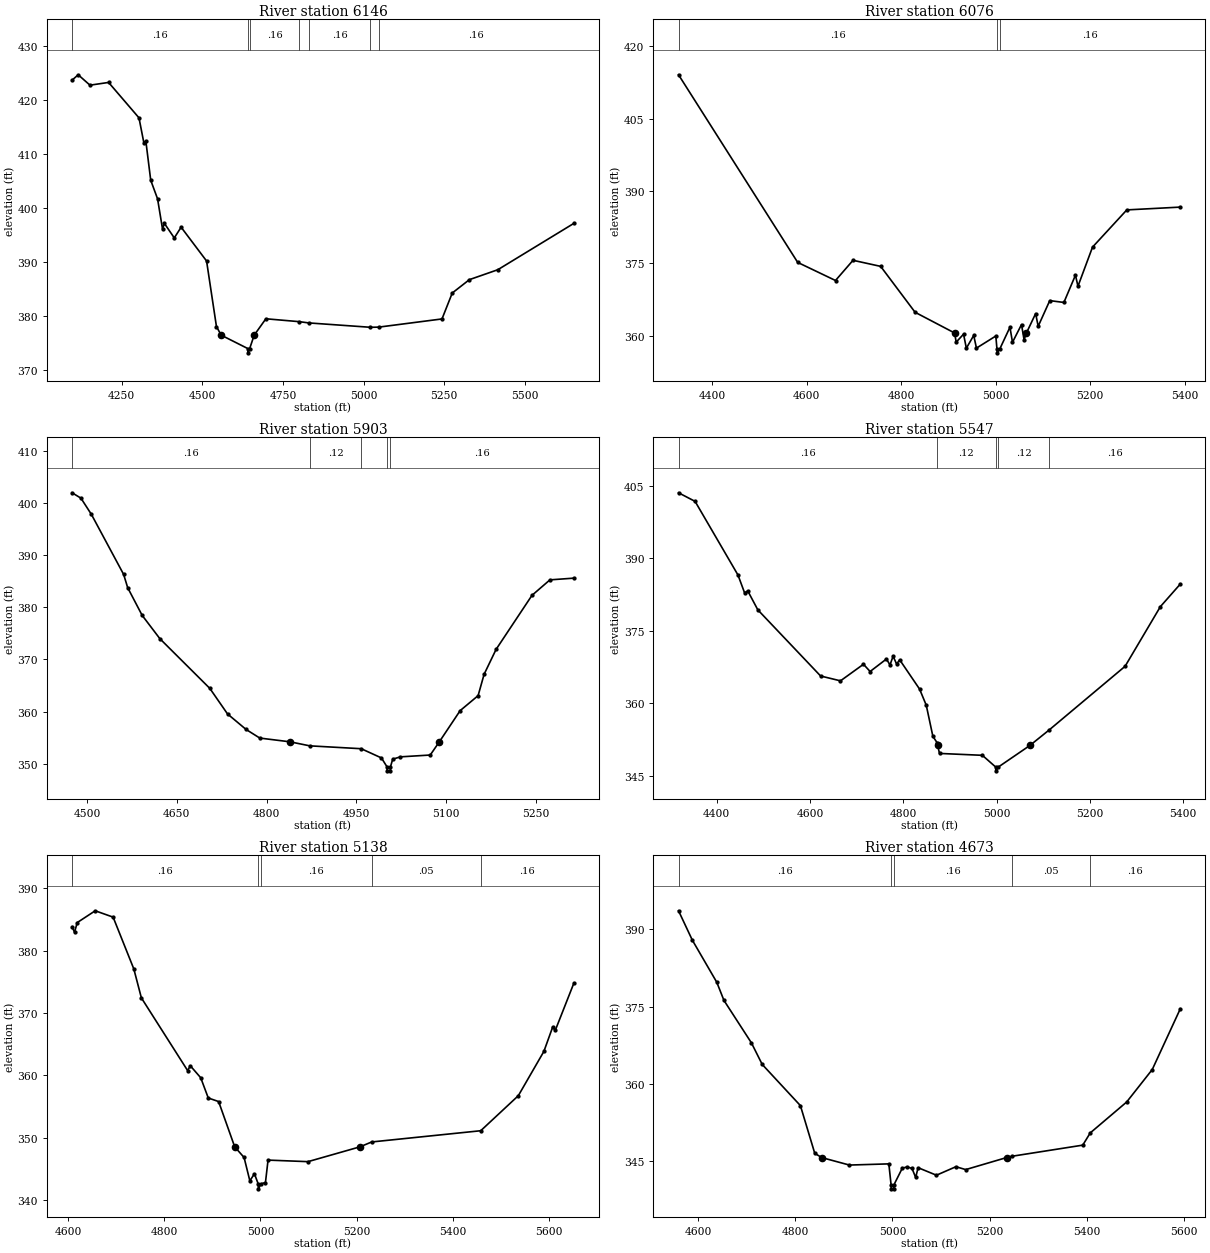
Type RM Length L Ch R = 1,6146,70,70,70
BEGIN DESCRIPTION:
Mapping XS 4396576f
END DESCRIPTION:
XS GIS Cut Line= 4
      2937920.05      6940463.75      2937617.98      6940942.89
      2937357.57      6941422.05      2937212.13      6941841.06
#Sta/Elev= 30
  4096.5  423.73  4115.5  424.73  4152.0  422.80  4209.7  423.31  4303.9  416.74
  4319.1  412.08  4325.1  412.47  4340.3  405.16  4361.5  401.71  4376.8  396.13
  4382.7  397.15  4413.3  394.46  4434.5  396.45  4513.4  390.18  4544.0  378.02
  4558.7  376.42  4641.0  373.94  4641.5  373.14  4647.0  373.94  4661.0  376.42
  4697.2  379.46  4801.4  378.92  4830.3  378.69  5021.4  377.88  5046.9  377.91
  5243.1  379.43  5274.9  384.24  5328.0  386.72  5416.1  388.56  5651.8  397.16
#Mann=7,-1,0
  4096.5    0.16       0  4641.0    0.07       0  4647.0    0.16       0
  4801.4    0.05       0  4830.3    0.16       0  5021.4    0.05       0
  5046.9    0.16       0
Bank Sta=4558.7,4661
Exp/Cntr=0.3,0.1

Type RM Length L Ch R = 1,6076,173,173,173
BEGIN DESCRIPTION:
Mapping XS 45cc48d2
END DESCRIPTION:
XS GIS Cut Line= 3
      2937729.08      6940633.89      2937402.71      6941185.94
      2937249.95      6941578.24
#Sta/Elev= 30
  4328.7  414.08  4581.0  375.17  4661.0  371.42  4698.1  375.61  4756.6  374.35
  4829.5  364.83  4913.1  360.54  4916.5  358.64  4932.1  360.29  4938.0  357.38
  4953.6  360.03  4959.4  357.40  5000.4  359.91  5002.8  357.22  5003.3  356.42
  5008.8  357.22  5030.3  361.73  5035.7  358.61  5054.8  362.29  5060.2  359.13
  5065.2  360.54  5084.7  364.56  5090.1  361.93  5114.6  367.25  5144.5  366.87
  5169.0  372.53  5174.3  370.23  5205.1  378.34  5277.7  386.06  5391.0  386.64
#Mann=3,-1,0
  4328.7    0.16       0  5002.8    0.07       0  5008.8    0.16       0
Bank Sta=4913.1,5065.2
Exp/Cntr=0.3,0.1

Type RM Length L Ch R = 1,5903,356,356,356
BEGIN DESCRIPTION:
UNT 021 IN DRY CR WATERSHED 11.0
END DESCRIPTION:
XS GIS Cut Line= 3
      2937425.00      6940675.00      2937225.00      6941175.00
      2937225.00      6941474.98
#Sta/Elev= 30
  4474.9  401.92  4489.7  400.89  4507.2  397.78  4561.1  386.27  4567.8  383.74
  4592.0  378.43  4621.6  373.96  4705.1  364.43  4734.7  359.53  4765.7  356.56
  4788.6  354.91  4839.2  354.19  4872.1  353.42  4958.1  352.87  4991.9  351.10
  5001.0  349.43  5001.5  348.63  5006.5  348.63  5007.0  349.43  5010.7  350.86
  5023.4  351.31  5073.4  351.66  5088.6  354.19  5123.4  360.17  5153.4  363.04
  5163.4  367.13  5183.4  371.90  5243.4  382.26  5273.4  385.23  5313.4  385.56
#Mann=5,-1,0
  4474.9    0.16       0  4872.1    0.12       0  4958.1    0.16       0
  5001.0    0.07       0  5007.0    0.16       0
Bank Sta=4839.2,5088.6
Exp/Cntr=0.3,0.1

Type RM Length L Ch R = 1,5547,409,409,409
BEGIN DESCRIPTION:
UNT 021 IN DRY CR WATERSHED 10.0
END DESCRIPTION:
XS GIS Cut Line= 3
      2937375.00      6940625.00      2936925.00      6941125.00
      2936975.00      6941525.00
#Sta/Elev= 30
  4318.3  403.55  4353.8  401.77  4445.7  386.55  4459.9  382.86  4466.7  383.26
  4488.3  379.34  4622.9  365.66  4665.5  364.66  4714.8  368.09  4729.0  366.59
  4764.1  369.18  4771.6  367.94  4778.3  369.74  4785.8  368.15  4792.5  369.00
  4835.1  362.95  4849.4  359.62  4863.6  353.18  4872.4  351.90  4873.8  351.31
  4877.8  349.65  4969.7  349.26  4998.1  346.85  4998.6  346.05  5004.1  346.85
  5071.6  351.30  5113.0  354.51  5275.7  367.67  5351.3  380.00  5394.1  384.68
#Mann=5,-1,0
  4318.3    0.16       0  4872.4    0.12       0  4998.1    0.07       0
  5004.1    0.12       0  5113.0    0.16       0
Bank Sta=4873.8,5071.6
Exp/Cntr=0.3,0.1

Type RM Length L Ch R = 1,5138,465,465,465
BEGIN DESCRIPTION:
UNT 021 IN DRY CR WATERSHED 9.0
END DESCRIPTION:
XS GIS Cut Line= 3
      2936922.65      6940535.80      2936725.00      6940875.00
      2936474.99      6941475.02
#Sta/Elev= 30
  4608.7  383.83  4613.8  382.95  4619.5  384.50  4656.8  386.39  4694.0  385.37
  4737.0  377.06  4752.7  372.42  4848.7  360.77  4854.5  361.52  4876.0  359.61
  4891.7  356.36  4913.2  355.79  4946.6  348.53  4966.1  346.82  4978.1  343.07
  4987.6  344.21  4995.4  342.59  4995.9  341.79  5001.4  342.59  5010.5  342.80
  5015.9  346.40  5098.8  346.15  5207.0  348.53  5231.3  349.31  5457.8  351.11
  5535.9  356.73  5589.0  363.83  5607.4  367.77  5612.8  367.23  5651.3  374.78
#Mann=5,-1,0
  4608.7    0.16       0  4995.4    0.07       0  5001.4    0.16       0
  5231.3    0.05       0  5457.8    0.16       0
Bank Sta=4946.6,5207
Exp/Cntr=0.3,0.1

Type RM Length L Ch R = 1,4673,348,348,348
BEGIN DESCRIPTION:
UNT 021 IN DRY CR WATERSHED 8.0
END DESCRIPTION:
XS GIS Cut Line= 3
      2936625.01      6940524.99      2936375.00      6940875.00
      2936425.00      6941474.99
#Sta/Elev= 30
  4560.0  393.59  4588.3  387.91  4638.7  379.73  4653.4  376.22  4709.9  367.99
  4732.1  363.81  4810.7  355.82  4840.2  346.58  4854.5  345.75  4911.5  344.30
  4992.6  344.53  4997.2  340.49  4997.7  339.69  5002.7  339.69  5003.2  340.49
  5020.2  343.68  5030.3  343.95  5040.3  343.64  5047.8  341.89  5052.8  343.79
  5090.5  342.33  5130.6  343.98  5150.7  343.42  5234.7  345.75  5246.2  346.01
  5391.5  348.16  5406.9  350.53  5481.8  356.52  5534.5  362.82  5592.2  374.60
#Mann=5,-1,0
  4560.0    0.16       0  4997.2    0.07       0  5003.2    0.16       0
  5246.2    0.05       0  5406.9    0.16       0
Bank Sta=4854.5,5234.7
Exp/Cntr=0.3,0.1

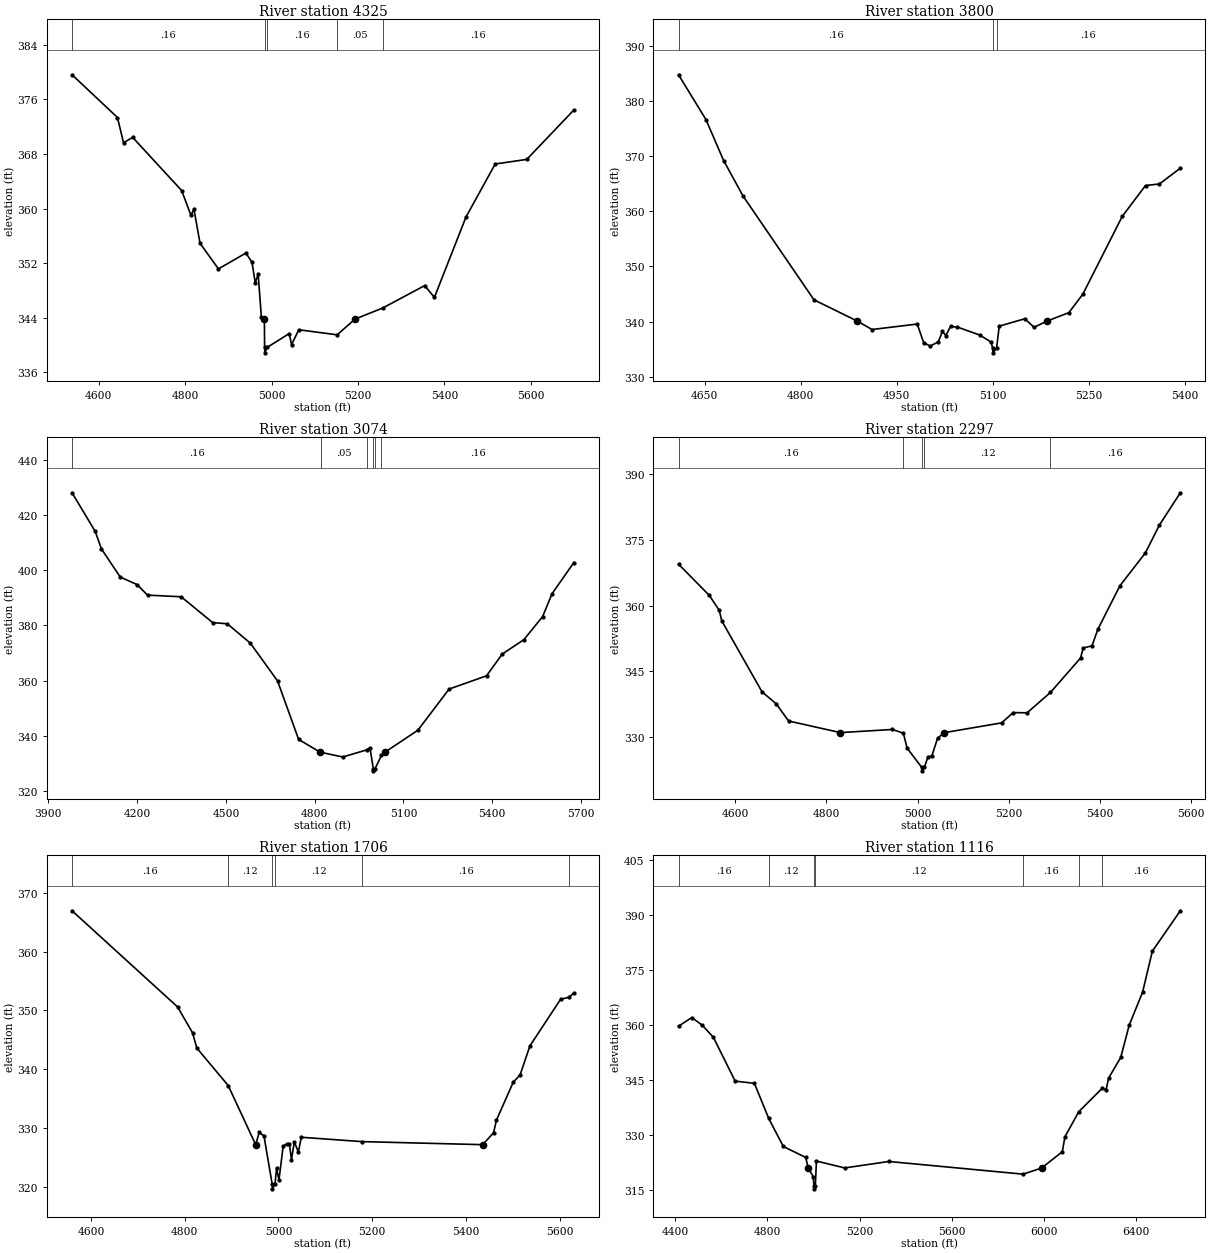
Type RM Length L Ch R = 1,4325,525,525,525
BEGIN DESCRIPTION:
UNT 021 IN DRY CR WATERSHED 7.0
END DESCRIPTION:
XS GIS Cut Line= 3
      2936429.91      6940541.55      2936125.00      6940875.00
      2935930.78      6941557.14
#Sta/Elev= 30
  4538.3  379.60  4643.3  373.34  4657.4  369.64  4678.5  370.43  4791.9  362.64
  4813.5  358.99  4820.2  359.95  4834.4  354.91  4877.0  351.16  4940.5  353.48
  4954.7  352.12  4962.1  349.12  4968.9  350.37  4976.3  344.12  4983.3  343.80
  4983.8  339.66  4984.3  338.86  4989.8  339.66  5040.9  341.69  5046.1  340.05
  5062.9  342.24  5151.7  341.50  5193.0  343.80  5257.2  345.43  5354.1  348.71
  5376.8  346.99  5449.7  358.75  5517.4  366.53  5590.4  367.20  5699.4  374.44
#Mann=5,-1,0
  4538.3    0.16       0  4983.8    0.07       0  4989.8    0.16       0
  5151.7    0.05       0  5257.2    0.16       0
Bank Sta=4983.3,5193
Exp/Cntr=0.3,0.1

Type RM Length L Ch R = 1,3800,726,726,726
BEGIN DESCRIPTION:
UNT 021 IN DRY CR WATERSHED 6.0
END DESCRIPTION:
XS GIS Cut Line= 3
      2935875.00      6940425.02      2935825.00      6940825.00
      2935674.99      6941175.01
#Sta/Elev= 30
  4609.0  384.83  4651.8  376.70  4679.5  369.23  4709.8  362.80  4820.6  343.94
  4887.7  340.11  4911.3  338.55  4981.9  339.54  4991.9  336.17  5002.0  335.54
  5014.8  336.30  5021.2  338.19  5026.6  337.46  5033.9  339.10  5044.7  338.99
  5079.2  337.56  5097.3  336.27  5099.8  335.11  5100.3  334.31  5105.8  335.11
  5110.0  339.16  5149.9  340.50  5164.4  338.95  5185.2  340.11  5218.8  341.61
  5240.6  344.97  5302.2  359.11  5338.5  364.71  5360.2  364.99  5392.9  367.86
#Mann=3,-1,0
  4609.0    0.16       0  5099.8    0.07       0  5105.8    0.16       0
Bank Sta=4887.7,5185.2
Exp/Cntr=0.3,0.1

Type RM Length L Ch R = 1,3074,777,777,777
BEGIN DESCRIPTION:
UNT 021 IN DRY CR WATERSHED 5.0
END DESCRIPTION:
XS GIS Cut Line= 3
      2936025.03      6939924.97      2935325.00      6940725.00
      2935125.00      6941324.99
#Sta/Elev= 30
  3980.2  427.98  4058.5  413.98  4079.4  407.68  4143.0  397.49  4200.0  394.76
  4235.1  390.96  4349.0  390.36  4455.3  381.01  4504.6  380.60  4582.5  373.59
  4674.5  359.92  4745.7  338.76  4816.6  334.26  4821.5  334.08  4894.7  332.41
  4975.9  334.98  4986.8  335.76  4998.0  328.20  4998.5  327.40  5004.0  328.20
  5025.6  332.97  5039.0  334.26  5148.7  342.09  5254.1  356.98  5380.6  361.77
  5433.3  369.60  5507.1  374.87  5570.3  383.22  5601.9  391.46  5675.7  402.74
#Mann=6,-1,0
  3980.2    0.16       0  4821.5    0.05       0  4975.9    0.12       0
  4998.0    0.07       0  5004.0    0.12       0  5025.6    0.16       0
Bank Sta=4816.6,5039
Exp/Cntr=0.3,0.1

Type RM Length L Ch R = 1,2297,591,591,591
BEGIN DESCRIPTION:
UNT 021 IN DRY CR WATERSHED 4.0
END DESCRIPTION:
XS GIS Cut Line= 3
      2935374.96      6940175.02      2934925.00      6940425.00
      2934724.99      6940975.02
#Sta/Elev= 30
  4475.9  369.47  4543.4  362.33  4565.1  358.94  4570.8  356.50  4658.9  340.32
  4689.8  337.60  4717.2  333.66  4830.7  331.01  4944.9  331.73  4968.8  330.87
  4976.9  327.49  5008.9  323.08  5009.4  322.28  5014.9  323.08  5022.6  325.44
  5031.2  325.67  5043.8  329.75  5058.8  331.01  5184.2  333.23  5209.4  335.58
  5240.0  335.53  5291.3  340.19  5357.1  348.03  5363.1  350.32  5382.3  350.83
  5395.0  354.58  5443.5  364.54  5499.4  372.06  5530.0  378.39  5575.9  385.77
#Mann=5,-1,0
  4475.9    0.16       0  4968.8    0.12       0  5008.9    0.07       0
  5014.9    0.12       0  5291.3    0.16       0
Bank Sta=4830.7,5058.8
Exp/Cntr=0.3,0.1

Type RM Length L Ch R = 1,1706,590,590,590
BEGIN DESCRIPTION:
UNT 021 IN DRY CR WATERSHED 3.0
END DESCRIPTION:
XS GIS Cut Line= 3
      2935274.97      6939975.01      2934825.00      6940075.00
      2934474.98      6940575.02
#Sta/Elev= 30
  4559.3  366.93  4784.6  350.58  4816.6  346.17  4825.6  343.59  4892.6  337.22
  4951.3  327.16  4958.8  329.23  4969.0  328.65  4986.5  320.45  4987.0  319.65
  4992.6  320.45  4995.9  323.16  5001.0  321.17  5010.0  326.89  5017.7  327.29
  5023.3  327.29  5027.7  324.62  5033.8  327.64  5042.5  325.89  5048.6  328.42
  5178.3  327.68  5436.0  327.16  5459.2  329.19  5465.3  331.33  5501.1  337.76
  5515.9  339.04  5536.8  343.96  5602.2  351.87  5620.7  352.24  5630.6  352.96
#Mann=6,-1,0
  4559.3    0.16       0  4892.6    0.12       0  4986.5    0.07       0
  4992.6    0.12       0  5178.3    0.16       0  5620.7    0.12       0
Bank Sta=4951.3,5436
Exp/Cntr=0.3,0.1

Type RM Length L Ch R = 1,1116,565,565,565
BEGIN DESCRIPTION:
UNT 021 IN DRY CR WATERSHED 2.0
END DESCRIPTION:
XS GIS Cut Line= 4
      2935099.97      6939799.99      2934525.00      6939625.00
      2934185.67      6940014.28      2934519.88      6941020.40
#Sta/Elev= 30
  4414.6  359.67  4472.1  362.03  4518.3  359.89  4566.1  356.61  4660.2  344.67
  4743.8  344.06  4806.1  334.47  4869.3  326.82  4966.3  323.83  4977.4  320.93
  4999.2  318.59  5002.1  316.05  5002.6  315.25  5008.2  316.05  5013.0  322.84
  5135.7  320.96  5327.5  322.72  5909.8  319.26  5990.2  320.93  6080.2  325.39
  6091.3  329.44  6151.2  336.29  6252.5  342.67  6270.2  342.35  6280.9  345.49
  6333.6  351.14  6370.5  359.97  6428.5  368.97  6470.8  380.16  6592.2  391.19
#Mann=7,-1,0
  4414.6    0.16       0  4806.1    0.12       0  5002.1    0.07       0
  5008.2    0.12       0  5909.8    0.16       0  6151.2    0.12       0
  6252.5    0.16       0
Bank Sta=4977.4,5990.2
Exp/Cntr=0.3,0.1

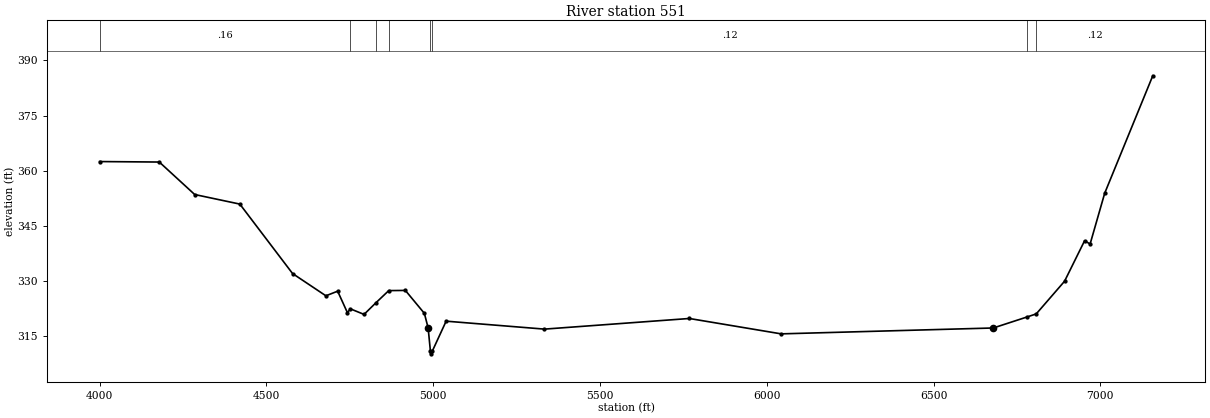
Type RM Length L Ch R = 1,551,0,0,0
BEGIN DESCRIPTION:
UNT 021 IN DRY CR WATERSHED 1.0
END DESCRIPTION:
XS GIS Cut Line= 5
      2935049.99      6939649.99      2934568.79      6939014.36
      2934080.60      6939742.25      2933885.30      6940063.91
      2934332.67      6941076.83
#Sta/Elev= 30
  4000.0  362.50  4178.9  362.37  4285.0  353.54  4420.3  350.94  4578.4  332.06
  4678.3  326.01  4713.6  327.26  4742.8  321.43  4751.8  322.46  4792.7  320.95
  4828.4  324.12  4866.8  327.42  4916.6  327.47  4973.6  321.23  4984.9  317.26
  4991.6  311.03  4992.1  310.23  4997.7  311.03  5038.8  319.11  5333.7  316.95
  5767.9  319.84  6043.2  315.66  6679.2  317.26  6779.0  320.21  6808.0  321.09
  6892.9  329.97  6952.9  340.97  6969.5  340.09  7013.2  353.89  7157.3  385.82
#Mann=8,-1,0
  4000.0    0.16       0  4751.8    0.12       0  4828.4    0.16       0
  4866.8    0.12       0  4991.6    0.07       0  4997.7    0.12       0
  6779.0    0.16       0  6808.0    0.12       0
Bank Sta=4984.9,6679.2
Exp/Cntr=0.3,0.1

Chan Stop Cuts=-1