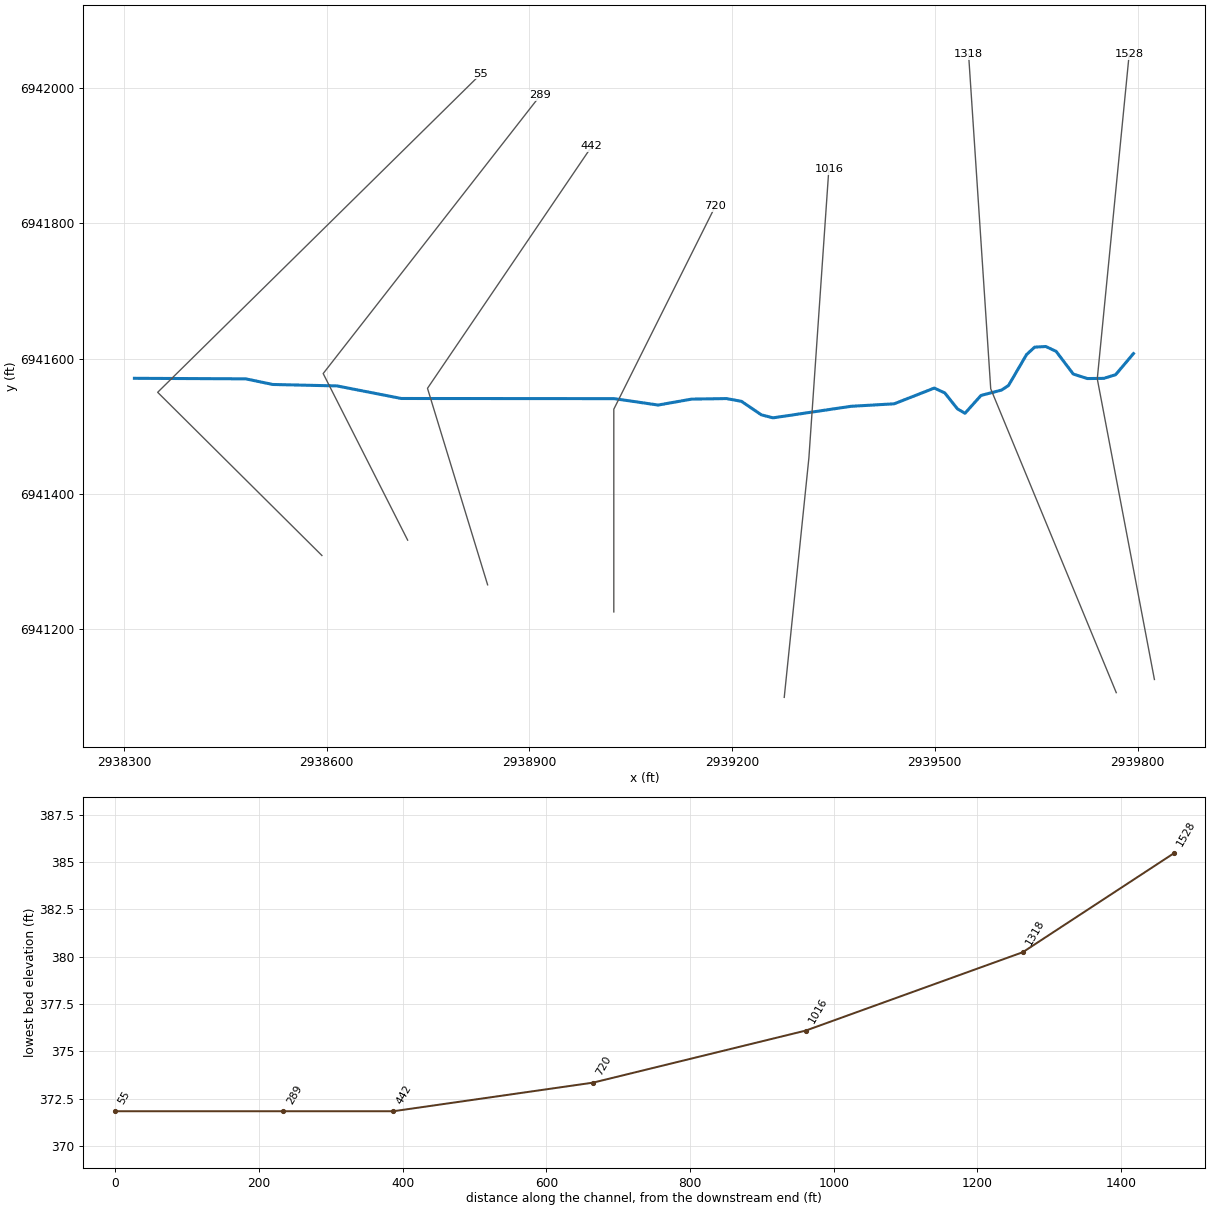
--- UNT 022 IN DRY CR WATERSHED.prj (project) ---

Proj Title=UNT 022 IN DRY CR WATERSHED Base Level Engineering
Current Plan=p01
Default Exp/Contr=0.3,0.1
English Units
Geom File=g01
Flow File=f01
Plan File=p01
BEGIN DESCRIPTION:
UNT 022 IN DRY CR WATERSHED
END DESCRIPTION:

--- UNT 022 IN DRY CR WATERSHED.p01 (plan) ---

Plan Title=Multiple Run
Short Identifier=Multiple
Geom File=g01
Flow File=f01
Subcritical Flow
K Sum by GR= 0
Std Step Tol= 0.01
Critical Tol= 0.01
Num of Std Step Trials= 20
Max Error Tol= 0.3
Flow Tol Ratio= 0.001
Split Flow NTrial= 30
Split Flow Tol= 0.02
Split Flow Ratio= 0.02
Log Output Level= 0
Friction Slope Method= 1
Unsteady Friction Slope Method= 2
Unsteady Bridges Friction Slope Method= 1
Parabolic Critical Depth
Global Vel Dist=  1 , 1 , 1
Global Log Level= 0
CheckData=True
Encroach Param= -1, 0, 0, 0
BEGIN DESCRIPTION:
Multiple Run
END DESCRIPTION:

--- UNT 022 IN DRY CR WATERSHED.f01 (steady flow) ---

Flow Title=Multiple
Number of Profiles=7
Profile Names=10-year,25-year,50-year,1pct_min,100-year,1pct_plu,500-year
River Rch & RM= UNT 022 IN DRY C,Reach-1,1528
     296     385     455     270     538    1074     749
Boundary for River Rch & Prof#=UNT 022 IN DRY C,Reach-1,1
Up Type=0
Dn Type=3
Dn Slope=0.005
Boundary for River Rch & Prof#=UNT 022 IN DRY C,Reach-1,2
Up Type=0
Dn Type=3
Dn Slope=0.005
Boundary for River Rch & Prof#=UNT 022 IN DRY C,Reach-1,3
Up Type=0
Dn Type=3
Dn Slope=0.005
Boundary for River Rch & Prof#=UNT 022 IN DRY C,Reach-1,4
Up Type=0
Dn Type=3
Dn Slope=0.005
Boundary for River Rch & Prof#=UNT 022 IN DRY C,Reach-1,5
Up Type=0
Dn Type=3
Dn Slope=0.005
Boundary for River Rch & Prof#=UNT 022 IN DRY C,Reach-1,6
Up Type=0
Dn Type=3
Dn Slope=0.005
Boundary for River Rch & Prof#=UNT 022 IN DRY C,Reach-1,7
Up Type=0
Dn Type=3
Dn Slope=0.005

--- UNT 022 IN DRY CR WATERSHED.g01 (geometry) ---

Geom Title=Existing Conditions

River Reach=UNT 022 IN DRY C,Reach-1
Reach XY= 30
      2939793.94      6941607.24      2939767.59      6941576.04
      2939750.16      6941570.63      2939725.82      6941570.34
      2939704.92      6941577.00      2939679.56      6941610.57
      2939664.36      6941617.76      2939647.79      6941616.83
      2939635.85      6941605.90      2939609.08      6941560.08
      2939598.87      6941553.36      2939568.37      6941545.34
      2939544.70      6941518.95      2939533.49      6941525.47
      2939514.78      6941549.09      2939499.27      6941556.26
      2939439.84      6941532.96      2939376.18      6941529.28
      2939260.58      6941512.22      2939243.36      6941516.62
      2939213.94      6941536.63      2939191.85      6941540.72
      2939140.20      6941539.93      2939090.60      6941531.14
      2939025.59      6941540.61      2938710.64      6941540.84
      2938615.46      6941559.44      2938520.35      6941561.59
      2938480.26      6941569.92      2938315.59      6941570.71

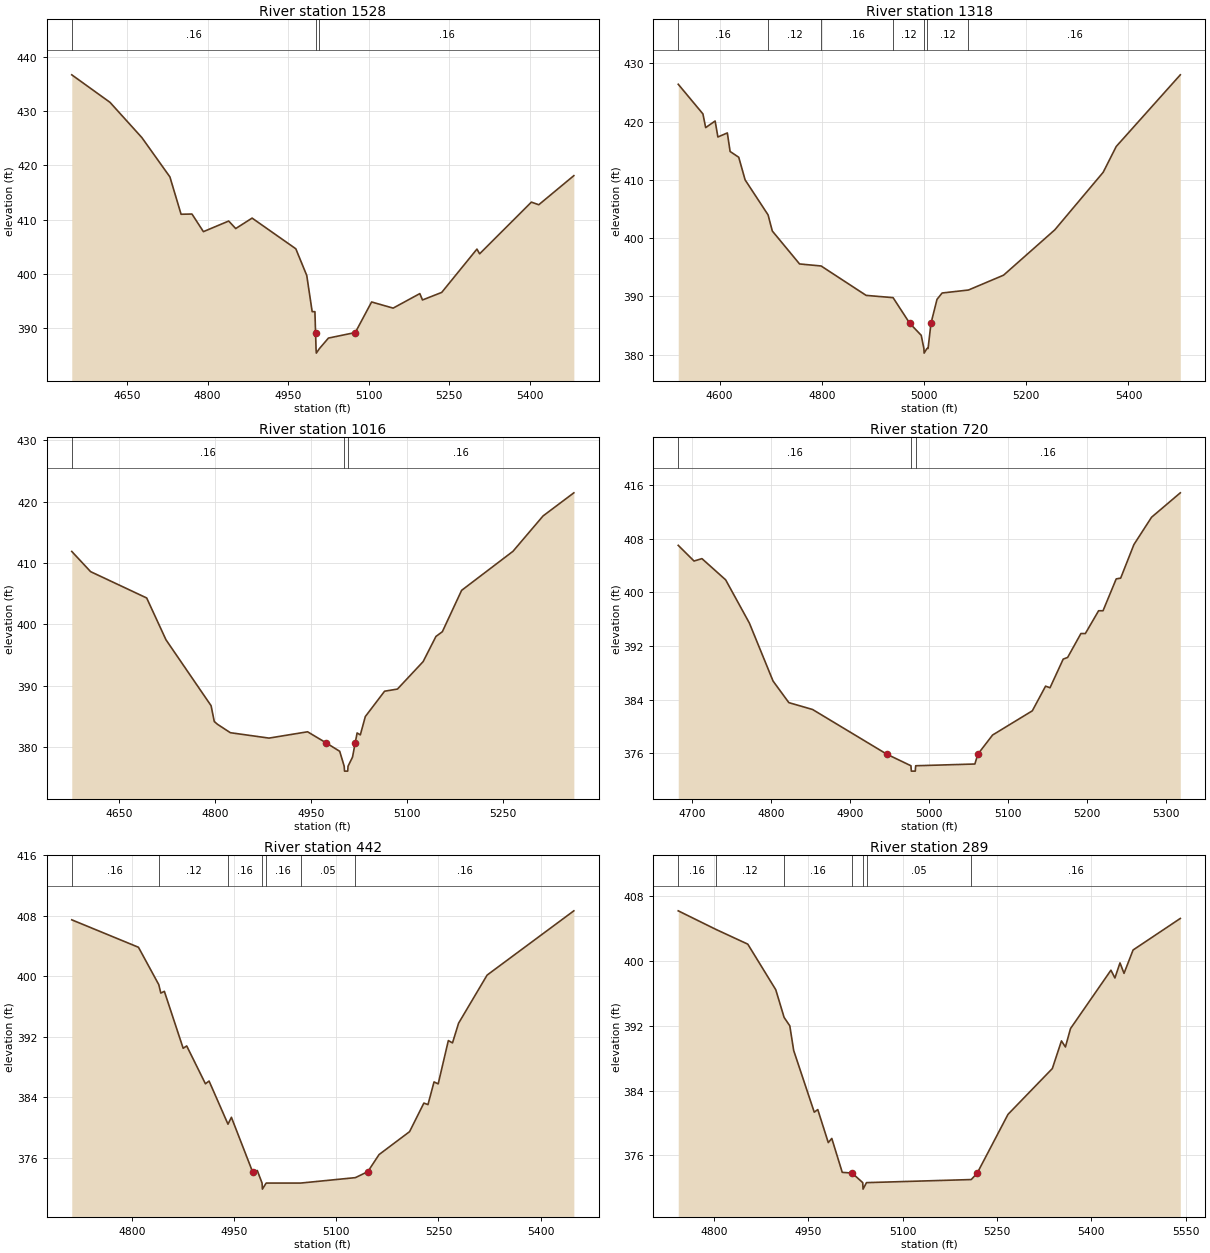
Type RM Length L Ch R = 1,1528,210,210,210
BEGIN DESCRIPTION:
UNT 022 IN DRY CR WATERSHED 3.0
END DESCRIPTION:
XS GIS Cut Line= 3
      2939825.00      6941125.02      2939740.45      6941569.95
      2939787.62      6942049.94
#Sta/Elev= 30
  4547.1  436.66  4618.3  431.60  4677.7  425.11  4729.9  417.88  4750.7  411.01
  4771.0  411.05  4792.3  407.81  4839.4  409.76  4852.5  408.38  4883.0  410.30
  4964.4  404.66  4984.8  399.75  4994.9  393.09  5000.0  393.09  5001.2  389.25
  5002.1  386.26  5002.6  385.46  5008.1  386.26  5025.2  388.23  5075.2  389.25
  5105.6  394.87  5145.7  393.74  5195.4  396.41  5200.4  395.24  5236.2  396.63
  5301.8  404.60  5306.8  403.73  5403.2  413.24  5417.0  412.76  5482.3  418.11
#Mann=3,-1,0
  4547.1    0.16       0  5002.1    0.07       0  5008.1    0.16       0
Bank Sta=5001.2,5075.2
Exp/Cntr=0.3,0.1

Type RM Length L Ch R = 1,1318,302,302,302
BEGIN DESCRIPTION:
Mapping XS 6e036e4c
END DESCRIPTION:
XS GIS Cut Line= 3
      2939768.53      6941105.55      2939582.77      6941555.19
      2939550.00      6942050.11
#Sta/Elev= 30
  4519.0  426.43  4567.3  421.34  4572.7  418.98  4591.2  420.12  4596.6  417.37
  4615.1  418.07  4620.5  414.88  4637.4  413.89  4649.9  410.00  4694.8  403.99
  4703.1  401.22  4756.4  395.56  4798.6  395.21  4886.7  390.16  4939.4  389.77
  4972.0  385.37  4994.5  383.30  4999.7  381.04  5000.2  380.24  5005.7  381.04
  5007.9  381.04  5013.6  385.37  5025.4  389.48  5035.4  390.57  5086.9  391.08
  5155.6  393.63  5255.9  401.42  5350.6  411.31  5376.1  415.74  5501.5  428.05
#Mann=7,-1,0
  4519.0    0.16       0  4694.8    0.12       0  4798.6    0.16       0
  4939.4    0.12       0  4999.7    0.07       0  5005.7    0.12       0
  5086.9    0.16       0
Bank Sta=4972,5013.6
Exp/Cntr=0.3,0.1

Type RM Length L Ch R = 1,1016,296,296,296
BEGIN DESCRIPTION:
Mapping XS a9da4d23
END DESCRIPTION:
XS GIS Cut Line= 3
      2939277.21      6941098.57      2939313.67      6941452.76
      2939343.19      6941879.88
#Sta/Elev= 30
  4576.1  411.89  4605.5  408.60  4693.1  404.31  4723.3  397.49  4793.7  386.76
  4798.7  384.18  4803.7  383.73  4823.8  382.36  4884.2  381.48  4944.4  382.51
  4972.5  380.76  4994.6  379.33  5001.6  376.90  5002.1  376.10  5007.1  376.10
  5007.6  376.90  5014.6  378.38  5018.9  380.76  5021.8  382.32  5026.8  382.00
  5034.6  384.99  5064.7  389.12  5084.8  389.47  5124.9  393.94  5144.9  398.04
  5154.9  398.81  5185.0  405.55  5265.2  411.91  5312.2  417.67  5360.3  421.44
#Mann=3,-1,0
  4576.1    0.16       0  5001.6    0.07       0  5007.6    0.16       0
Bank Sta=4972.5,5018.9
Exp/Cntr=0.3,0.1

Type RM Length L Ch R = 1,720,278,278,278
BEGIN DESCRIPTION:
UNT 022 IN DRY CR WATERSHED 2.0
END DESCRIPTION:
XS GIS Cut Line= 3
      2939025.00      6941225.02      2939025.00      6941525.00
      2939175.01      6941825.01
#Sta/Elev= 30
  4682.9  407.01  4702.9  404.67  4712.9  405.03  4742.9  401.87  4772.9  395.43
  4802.9  386.78  4822.9  383.56  4852.9  382.54  4946.8  375.88  4977.4  374.15
  4977.9  373.35  4982.9  373.35  4983.4  374.15  5058.3  374.41  5062.1  375.88
  5080.7  378.73  5131.0  382.34  5147.8  386.02  5153.4  385.78  5170.1  390.05
  5175.7  390.30  5192.5  393.86  5198.1  393.86  5214.9  397.26  5220.5  397.26
  5237.2  402.01  5242.8  402.12  5259.6  407.13  5281.9  411.20  5318.3  414.84
#Mann=3,-1,0
  4682.9    0.16       0  4977.4    0.07       0  4983.4    0.16       0
Bank Sta=4946.8,5062.1
Exp/Cntr=0.3,0.1

Type RM Length L Ch R = 1,442,153,153,153
BEGIN DESCRIPTION:
Mapping XS 1b3f339d
END DESCRIPTION:
XS GIS Cut Line= 3
      2938838.26      6941265.10      2938749.29      6941555.89
      2938992.36      6941913.99
#Sta/Elev= 30
  4711.9  407.46  4809.8  403.83  4839.6  398.89  4842.6  397.77  4847.8  398.00
  4875.4  390.47  4880.6  390.78  4908.1  385.77  4913.4  386.14  4941.2  380.43
  4946.2  381.34  4977.2  374.15  4984.2  374.30  4991.2  372.64  4991.7  371.84
  4997.2  372.64  5047.7  372.64  5128.2  373.36  5146.4  374.15  5162.9  376.41
  5207.7  379.44  5228.7  383.22  5234.7  383.02  5243.6  386.02  5249.7  385.76
  5264.6  391.49  5270.7  391.18  5279.6  393.78  5321.5  400.15  5448.8  408.65
#Mann=7,-1,0
  4711.9    0.16       0  4839.6    0.12       0  4941.2    0.16       0
  4991.2    0.07       0  4997.2    0.16       0  5047.7    0.05       0
  5128.2    0.16       0
Bank Sta=4977.2,5146.4
Exp/Cntr=0.3,0.1

Type RM Length L Ch R = 1,289,234,234,234
BEGIN DESCRIPTION:
Mapping XS afe8e0d4
END DESCRIPTION:
XS GIS Cut Line= 3
      2938719.92      6941331.24      2938594.92      6941577.76
      2938916.12      6941989.24
#Sta/Elev= 30
  4743.1  406.16  4803.0  403.87  4853.7  402.05  4898.2  396.43  4911.5  393.01
  4920.5  391.98  4926.7  388.93  4959.4  381.33  4965.0  381.65  4981.7  377.58
  4987.3  378.09  5003.9  373.91  5020.0  373.82  5020.2  373.78  5036.5  372.64
  5037.0  371.84  5042.5  372.64  5209.0  373.02  5218.3  373.78  5267.5  381.06
  5338.0  386.71  5352.5  390.12  5358.8  389.37  5366.9  391.64  5431.2  398.84
  5437.5  397.88  5445.6  399.74  5452.0  398.45  5466.4  401.33  5541.5  405.22
#Mann=7,-1,0
  4743.1    0.16       0  4803.0    0.12       0  4911.5    0.16       0
  5020.0    0.05       0  5036.5    0.07       0  5042.5    0.05       0
  5209.0    0.16       0
Bank Sta=5020.2,5218.3
Exp/Cntr=0.3,0.1

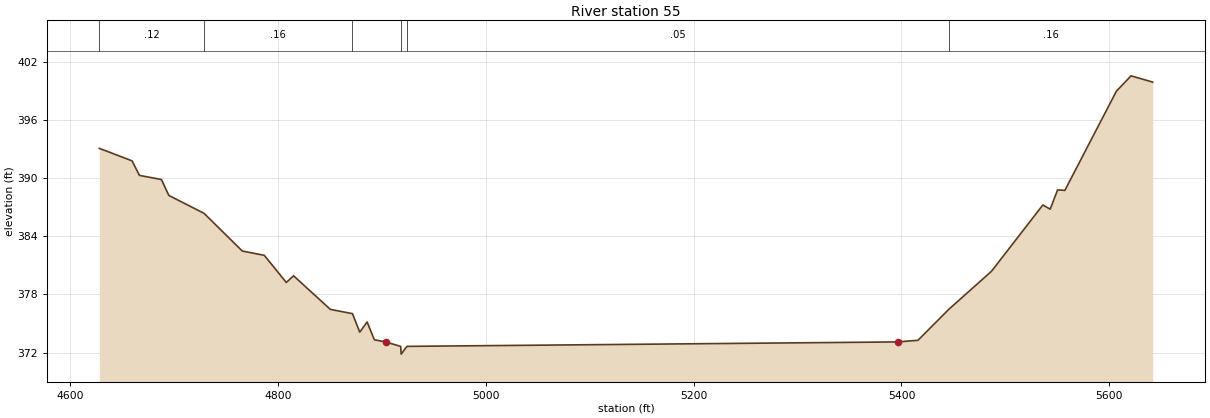
Type RM Length L Ch R = 1,55,0,0,0
BEGIN DESCRIPTION:
UNT 022 IN DRY CR WATERSHED 1.0
END DESCRIPTION:
XS GIS Cut Line= 3
      2938593.03      6941308.51      2938350.00      6941550.00
      2938828.35      6942021.25
#Sta/Elev= 30
  4627.8  393.09  4659.3  391.80  4666.4  390.30  4687.6  389.87  4694.7  388.23
  4728.6  386.38  4765.4  382.49  4786.6  382.04  4807.8  379.24  4814.8  379.93
  4850.2  376.46  4871.5  376.02  4878.5  374.11  4885.6  375.16  4892.6  373.32
  4903.3  373.10  4917.9  372.64  4918.4  371.84  4923.9  372.64  5396.2  373.10
  5415.9  373.27  5445.7  376.48  5486.6  380.39  5536.1  387.24  5543.2  386.81
  5550.3  388.80  5557.3  388.75  5606.9  398.99  5621.0  400.58  5641.9  399.93
#Mann=6,-1,0
  4627.8    0.12       0  4728.6    0.16       0  4871.5    0.05       0
  4917.9   0.033       0  4923.9    0.05       0  5445.7    0.16       0
Bank Sta=4903.3,5396.2
Exp/Cntr=0.3,0.1

Chan Stop Cuts=-1