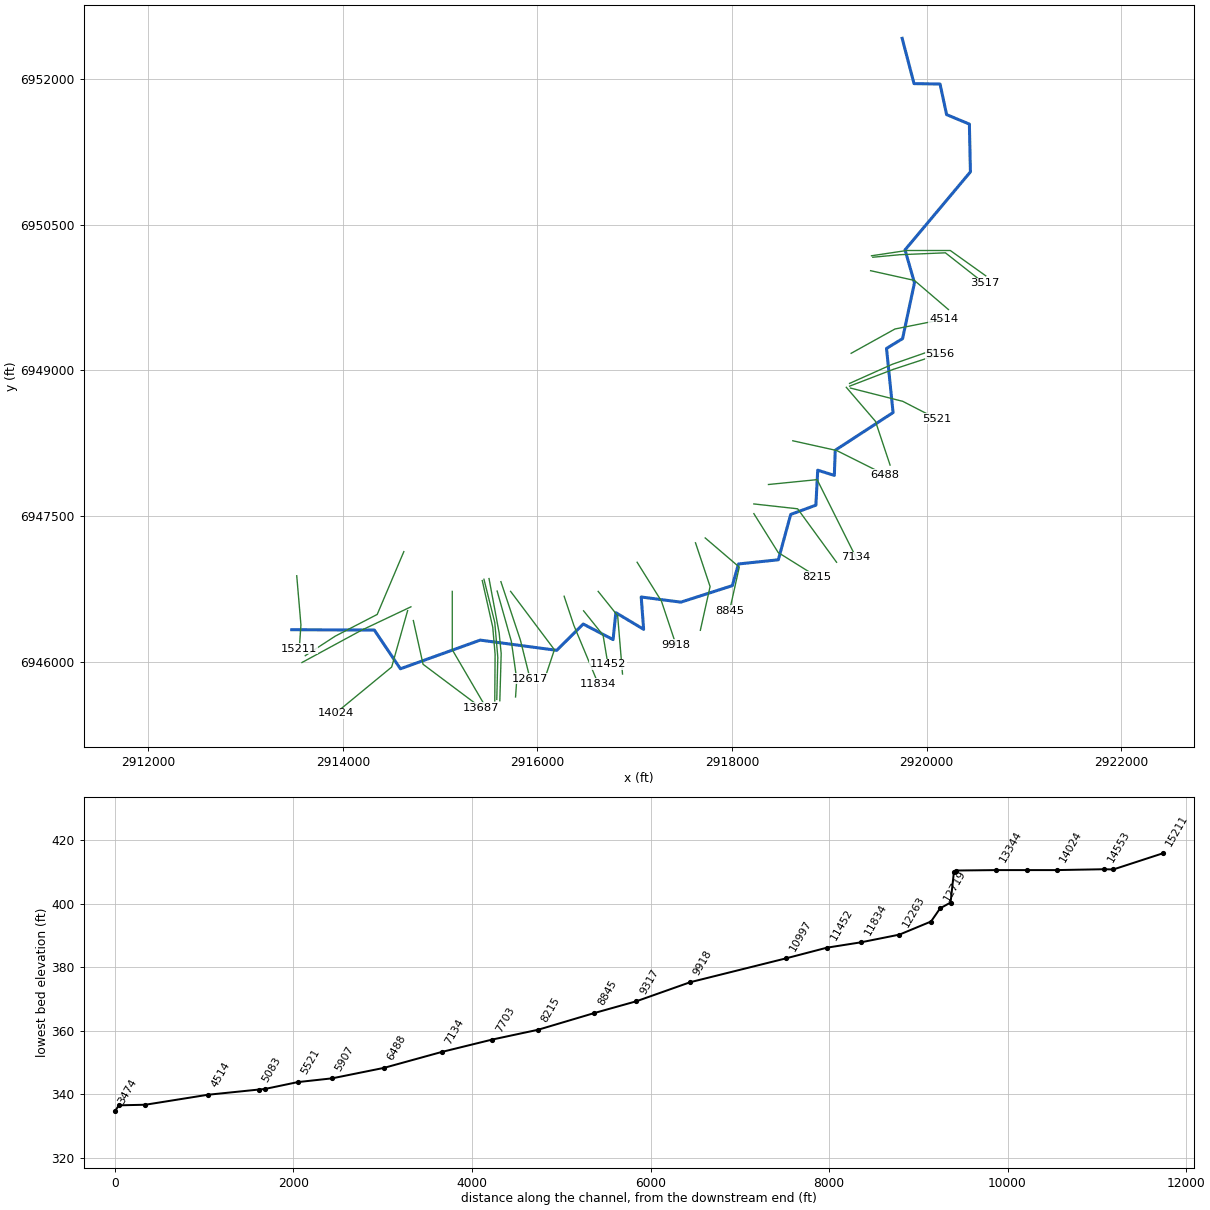
--- UNT 023 IN DRY CR WATERSHED.prj (project) ---

Proj Title=UNT 023 IN DRY CR WATERSHED Base Level Engineering
Current Plan=p01
Default Exp/Contr=0.3,0.1
English Units
Geom File=g01
Flow File=f01
Plan File=p01
BEGIN DESCRIPTION:
UNT 023 IN DRY CR WATERSHED
END DESCRIPTION:

--- UNT 023 IN DRY CR WATERSHED.p01 (plan) ---

Plan Title=Multiple Run
Short Identifier=Multiple
Geom File=g01
Flow File=f01
Subcritical Flow
K Sum by GR= 0
Std Step Tol= 0.01
Critical Tol= 0.01
Num of Std Step Trials= 20
Max Error Tol= 0.3
Flow Tol Ratio= 0.001
Split Flow NTrial= 30
Split Flow Tol= 0.02
Split Flow Ratio= 0.02
Log Output Level= 0
Friction Slope Method= 1
Unsteady Friction Slope Method= 2
Unsteady Bridges Friction Slope Method= 1
Parabolic Critical Depth
Global Vel Dist=  1 , 1 , 1
Global Log Level= 0
CheckData=True
Encroach Param= -1, 0, 0, 0
BEGIN DESCRIPTION:
Multiple Run
END DESCRIPTION:

--- UNT 023 IN DRY CR WATERSHED.f01 (steady flow) ---

Flow Title=Multiple
Number of Profiles=7
Profile Names=10-year,25-year,50-year,1pct_min,100-year,1pct_plu,500-year
River Rch & RM= UNT 023 IN DRY C,Reach-1,15211
     631     852    1034     625    1246    2486    1810
River Rch & RM= UNT 023 IN DRY C,Reach-1,9918
     952    1315    1620     991    1978    3946    2952
Boundary for River Rch & Prof#=UNT 023 IN DRY C,Reach-1,1
Up Type=0
Dn Type=3
Dn Slope=0.005
Boundary for River Rch & Prof#=UNT 023 IN DRY C,Reach-1,2
Up Type=0
Dn Type=3
Dn Slope=0.005
Boundary for River Rch & Prof#=UNT 023 IN DRY C,Reach-1,3
Up Type=0
Dn Type=3
Dn Slope=0.005
Boundary for River Rch & Prof#=UNT 023 IN DRY C,Reach-1,4
Up Type=0
Dn Type=3
Dn Slope=0.005
Boundary for River Rch & Prof#=UNT 023 IN DRY C,Reach-1,5
Up Type=0
Dn Type=3
Dn Slope=0.005
Boundary for River Rch & Prof#=UNT 023 IN DRY C,Reach-1,6
Up Type=0
Dn Type=3
Dn Slope=0.005
Boundary for River Rch & Prof#=UNT 023 IN DRY C,Reach-1,7
Up Type=0
Dn Type=3
Dn Slope=0.005

--- UNT 023 IN DRY CR WATERSHED.g01 (geometry) ---

Geom Title=Existing Conditions

River Reach=UNT 023 IN DRY C,Reach-1
Reach XY= 30
      2913475.59      6946330.71      2914324.12      6946327.15
      2914592.01      6945928.67      2915412.32      6946223.81
      2916198.89      6946118.70      2916471.13      6946389.14
      2916778.01      6946229.11      2916806.14      6946506.24
      2917092.05      6946334.78      2917067.13      6946667.39
      2917474.46      6946614.33      2918003.78      6946784.39
      2918066.88      6947007.30      2918476.48      6947050.30
      2918603.50      6947516.91      2918862.38      6947612.22
      2918881.43      6947972.20      2919051.91      6947918.79
      2919061.54      6948177.39      2919655.74      6948565.20
      2919588.44      6949225.04      2919753.42      6949325.97
      2919875.84      6949900.40      2919778.72      6950239.06
      2920450.90      6951041.90      2920440.10      6951533.46
      2920206.03      6951630.96      2920138.61      6951945.78
      2919871.26      6951949.84      2919749.14      6952415.88

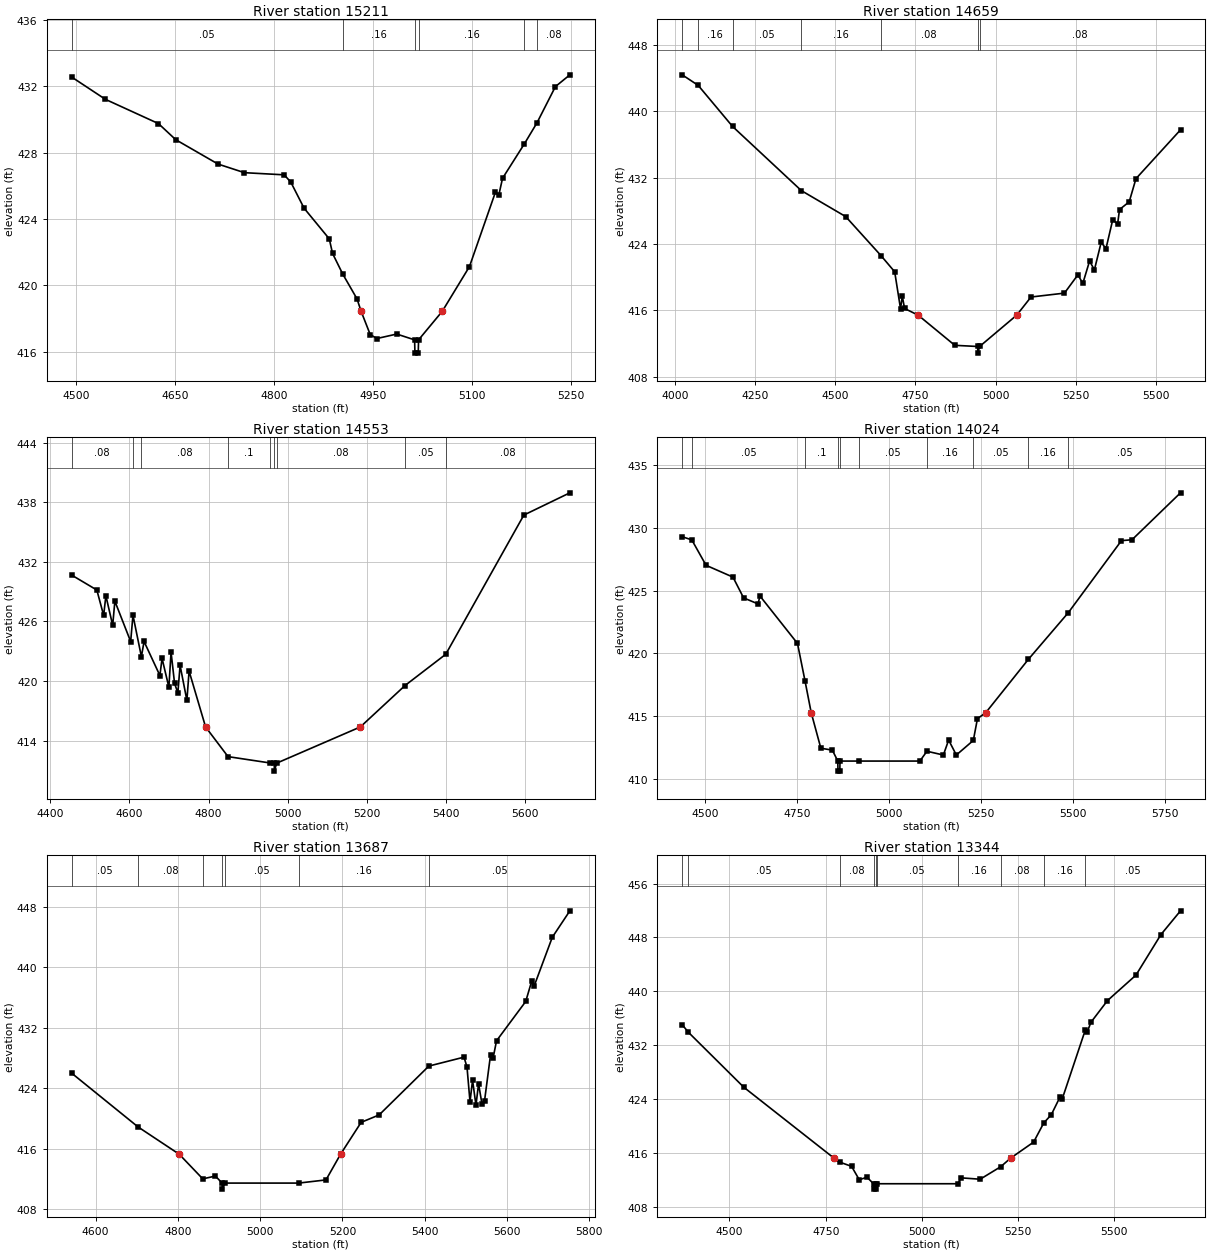
Type RM Length L Ch R = 1,15211,552,552,552
BEGIN DESCRIPTION:
UNT 023 IN DRY CR WATERSHED 24.0
END DESCRIPTION:
XS GIS Cut Line= 3
      2913526.45      6946886.18      2913569.67      6946380.83
      2913552.49      6946133.12
#Sta/Elev= 30
  4492.8  432.56  4544.2  431.21  4624.5  429.75  4650.7  428.78  4714.8  427.31
  4754.9  426.79  4815.2  426.66  4825.2  426.22  4845.3  424.65  4883.5  422.80
  4888.5  421.92  4903.9  420.68  4925.6  419.18  4931.8  418.43  4945.6  417.03
  4955.7  416.79  4985.8  417.06  5012.9  416.71  5013.4  415.91  5018.4  415.91
  5018.9  416.71  5054.8  418.43  5096.1  421.13  5135.4  425.61  5140.5  425.43
  5146.2  426.45  5179.5  428.54  5198.5  429.80  5226.4  431.98  5248.3  432.69
#Mann=6,-1,0
  4492.8    0.05       0  4903.9    0.16       0  5012.9    0.07       0
  5018.9    0.16       0  5179.5    0.05       0  5198.5    0.08       0
Bank Sta=4931.8,5054.8
Exp/Cntr=0.3,0.1

Type RM Length L Ch R = 1,14659,106,106,106
BEGIN DESCRIPTION:
Mapping XS 156c86b3
END DESCRIPTION:
XS GIS Cut Line= 4
      2914627.14      6947133.98      2914353.71      6946488.14
      2913921.41      6946264.18      2913614.14      6946063.68
#Sta/Elev= 30
  4022.2  444.38  4072.0  443.11  4179.3  438.16  4394.0  430.43  4532.4  427.30
  4642.3  422.61  4685.3  420.65  4703.6  416.18  4709.0  417.72  4716.1  416.23
  4758.7  415.42  4872.9  411.79  4944.3  411.65  4944.8  410.85  4950.3  411.65
  5066.0  415.42  5110.7  417.61  5215.1  418.08  5257.2  420.29  5272.4  419.24
  5293.5  421.94  5308.6  420.89  5329.7  424.19  5344.8  423.45  5365.9  426.94
  5381.0  426.40  5387.0  428.15  5417.2  429.08  5438.3  431.87  5577.3  437.75
#Mann=7,-1,0
  4022.2    0.05       0  4072.0    0.16       0  4179.3    0.05       0
  4394.0    0.16       0  4642.3    0.08       0  4944.3    0.07       0
  4950.3    0.08       0
Bank Sta=4758.7,5066
Exp/Cntr=0.3,0.1

Type RM Length L Ch R = 1,14553,529,529,529
BEGIN DESCRIPTION:
Mapping XS 91f73bbe
END DESCRIPTION:
XS GIS Cut Line= 3
      2914700.03      6946566.25      2914189.64      6946324.08
      2913580.24      6945993.33
#Sta/Elev= 30
  4453.9  430.67  4517.7  429.16  4534.9  426.60  4540.5  428.59  4557.7  425.60
  4563.2  428.04  4603.1  423.97  4608.9  426.62  4630.2  422.45  4636.9  423.98
  4676.9  420.55  4682.4  422.27  4699.6  419.37  4705.1  422.91  4714.0  419.75
  4722.3  418.80  4727.9  421.57  4745.1  418.04  4750.6  421.00  4792.3  415.37
  4849.0  412.38  4955.4  411.74  4965.6  411.72  4966.1  410.92  4971.6  411.72
  5183.1  415.37  5295.9  419.54  5398.8  422.69  5596.0  436.71  5712.2  438.95
#Mann=9,-1,0
  4453.9    0.08       0  4608.9    0.05       0  4630.2    0.08       0
  4849.0     0.1       0  4955.4    0.08       0  4965.6    0.07       0
  4971.6    0.08       0  5295.9    0.05       0  5398.8    0.08       0
Bank Sta=4792.3,5183.1
Exp/Cntr=0.3,0.1

Type RM Length L Ch R = 1,14024,337,337,337
BEGIN DESCRIPTION:
Mapping XS d290ca9a
END DESCRIPTION:
XS GIS Cut Line= 3
      2914666.20      6946527.17      2914502.14      6945946.48
      2913924.06      6945469.95
#Sta/Elev= 30
  4438.3  429.28  4464.3  429.03  4503.0  427.01  4576.1  426.07  4604.9  424.42
  4644.1  423.94  4649.3  424.57  4751.2  420.80  4771.5  417.84  4788.4  415.30
  4814.6  412.47  4845.8  412.32  4860.6  411.45  4861.1  410.65  4866.1  410.65
  4866.6  411.45  4917.2  411.45  5083.4  411.45  5102.6  412.23  5147.2  411.93
  5161.5  413.12  5182.4  411.93  5228.5  413.09  5239.7  414.82  5262.4  415.30
  5377.8  419.53  5486.5  423.25  5630.6  428.97  5659.3  429.04  5790.9  432.77
#Mann=10,-1,0
  4438.3    0.08       0  4464.3    0.05       0  4771.5     0.1       0
  4860.6   0.033       0  4866.6     0.1       0  4917.2    0.05       0
  5102.6    0.16       0  5228.5    0.05       0  5377.8    0.16       0
  5486.5    0.05       0
Bank Sta=4788.4,5262.4
Exp/Cntr=0.3,0.1

Type RM Length L Ch R = 1,13687,343,343,343
BEGIN DESCRIPTION:
UNT 023 IN DRY CR WATERSHED 23.0
END DESCRIPTION:
XS GIS Cut Line= 3
      2914725.00      6946425.00      2914825.00      6945975.00
      2915425.02      6945524.98
#Sta/Elev= 30
  4541.6  426.01  4703.0  418.89  4803.2  415.27  4860.4  412.01  4891.2  412.38
  4907.4  411.45  4907.9  410.65  4913.4  411.45  5093.5  411.45  5159.9  411.87
  5195.3  415.27  5245.3  419.49  5289.0  420.47  5409.9  426.94  5495.3  428.12
  5502.6  426.82  5509.9  422.21  5516.1  425.06  5524.4  421.76  5530.7  424.59
  5539.0  421.93  5545.3  422.36  5559.9  428.46  5566.1  428.02  5574.4  430.29
  5645.3  435.49  5659.9  438.19  5666.1  437.58  5709.9  443.99  5752.6  447.49
#Mann=7,-1,0
  4541.6    0.05       0  4703.0    0.08       0  4860.4    0.05       0
  4907.4   0.033       0  4913.4    0.05       0  5093.5    0.16       0
  5409.9    0.05       0
Bank Sta=4803.2,5195.3
Exp/Cntr=0.3,0.1

Type RM Length L Ch R = 1,13344,446,446,446
BEGIN DESCRIPTION:
UNT 023 IN DRY CR WATERSHED 22.0
END DESCRIPTION:
XS GIS Cut Line= 3
      2915125.00      6946725.02      2915125.00      6946125.00
      2915474.98      6945525.04
#Sta/Elev= 30
  4377.2  435.05  4393.5  433.91  4537.2  425.77  4771.7  415.24  4786.2  414.66
  4817.2  414.03  4837.2  412.04  4857.2  412.42  4874.2  411.45  4874.7  410.65
  4879.7  410.65  4880.2  411.45  4882.9  411.45  5093.0  411.45  5102.5  412.32
  5151.3  412.12  5204.8  413.98  5230.2  415.24  5290.2  417.63  5316.6  420.48
  5336.1  421.69  5358.9  424.34  5364.6  424.05  5424.3  434.24  5429.1  433.92
  5439.1  435.41  5482.1  438.63  5556.1  442.41  5621.0  448.43  5671.8  451.95
#Mann=10,-1,0
  4377.2    0.08       0  4393.5    0.05       0  4786.2    0.08       0
  4874.2   0.033       0  4880.2    0.08       0  4882.9    0.05       0
  5093.0    0.16       0  5204.8    0.08       0  5316.6    0.16       0
  5424.3    0.05       0
Bank Sta=4771.7,5230.2
Exp/Cntr=0.3,0.1

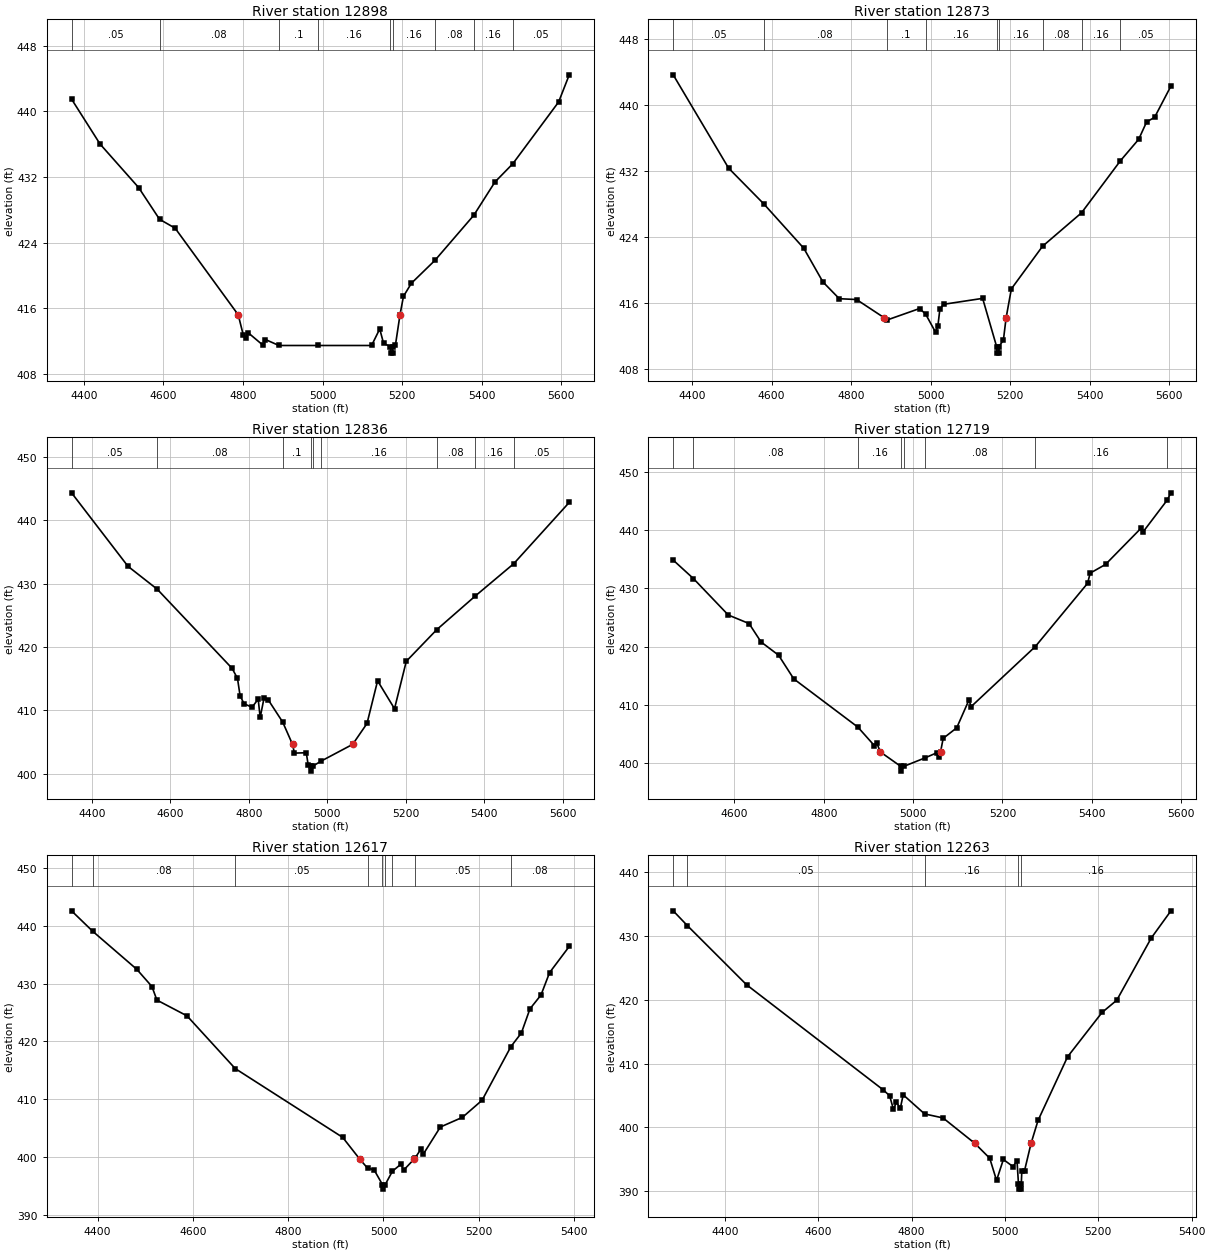
Type RM Length L Ch R = 1,12898,25,25,25
BEGIN DESCRIPTION:
Mapping XS 12af4909
END DESCRIPTION:
XS GIS Cut Line= 4
      2915433.43      6946836.20      2915541.06      6946357.07
      2915565.37      6946079.29      2915561.91      6945598.32
#Sta/Elev= 30
  4369.1  441.48  4440.8  436.00  4537.7  430.70  4590.3  426.83  4629.4  425.75
  4788.0  415.19  4800.8  412.71  4807.8  412.38  4812.9  413.01  4851.1  411.45
  4856.3  412.18  4890.4  411.45  4988.4  411.45  5123.2  411.45  5143.7  413.47
  5153.3  411.71  5170.3  411.32  5170.8  410.52  5175.8  410.52  5176.3  411.32
  5183.3  411.55  5194.6  415.19  5203.3  417.44  5223.3  419.04  5282.3  421.82
  5380.2  427.33  5433.3  431.38  5478.1  433.60  5593.3  441.13  5620.0  444.44
#Mann=9,-1,0
  4369.1    0.05       0  4590.3    0.08       0  4890.4     0.1       0
  4988.4    0.16       0  5170.3    0.07       0  5176.3    0.16       0
  5282.3    0.08       0  5380.2    0.16       0  5478.1    0.05       0
Bank Sta=4788,5194.6
Exp/Cntr=0.3,0.1

Type RM Length L Ch R = 1,12873,37,37,37
BEGIN DESCRIPTION:
Mapping XS 644b1ae5
END DESCRIPTION:
XS GIS Cut Line= 4
      2915450.78      6946850.13      2915561.89      6946405.68
      2915593.14      6946048.04      2915582.73      6945613.99
#Sta/Elev= 30
  4352.4  443.67  4491.7  432.37  4580.2  428.04  4680.7  422.67  4728.8  418.59
  4770.0  416.56  4813.4  416.46  4883.3  414.24  4888.9  413.96  4971.8  415.37
  4987.0  414.70  5012.0  412.50  5017.8  413.22  5022.8  415.26  5032.0  415.88
  5130.4  416.60  5165.5  410.77  5166.0  409.97  5171.0  409.97  5171.5  410.77
  5182.6  411.55  5189.4  414.24  5202.6  417.75  5281.0  422.91  5379.0  426.96
  5476.9  433.27  5522.7  435.86  5542.7  437.97  5562.7  438.52  5603.7  442.30
#Mann=9,-1,0
  4352.4    0.05       0  4580.2    0.08       0  4888.9     0.1       0
  4987.0    0.16       0  5165.5    0.07       0  5171.5    0.16       0
  5281.0    0.08       0  5379.0    0.16       0  5476.9    0.05       0
Bank Sta=4883.3,5189.4
Exp/Cntr=0.3,0.1

Type RM Length L Ch R = 1,12836,117,117,117
BEGIN DESCRIPTION:
Mapping XS 15ffb493
END DESCRIPTION:
XS GIS Cut Line= 4
      2915502.87      6946857.06      2915607.03      6946298.04
      2915627.87      6946086.23      2915613.98      6945600.11
#Sta/Elev= 30
  4348.6  444.30  4492.4  432.71  4566.9  429.10  4757.6  416.62  4771.3  415.04
  4777.9  412.31  4788.1  411.04  4808.4  410.49  4824.0  411.77  4829.1  408.89
  4839.0  411.96  4849.1  411.71  4886.4  408.16  4911.5  404.64  4916.3  403.26
  4946.5  403.32  4951.5  401.35  4957.5  401.22  4958.0  400.42  4963.5  401.22
  4984.9  402.02  5064.7  404.64  5101.2  407.93  5128.2  414.66  5171.3  410.26
  5201.3  417.74  5279.0  422.73  5377.0  428.03  5474.9  433.12  5616.4  442.79
#Mann=9,-1,0
  4348.6    0.05       0  4566.9    0.08       0  4886.4     0.1       0
  4957.5    0.07       0  4963.5     0.1       0  4984.9    0.16       0
  5279.0    0.08       0  5377.0    0.16       0  5474.9    0.05       0
Bank Sta=4911.5,5064.7
Exp/Cntr=0.3,0.1

Type RM Length L Ch R = 1,12719,102,102,102
BEGIN DESCRIPTION:
Mapping XS 9cdde1cc
END DESCRIPTION:
XS GIS Cut Line= 4
      2915586.45      6946728.40      2915732.28      6946211.07
      2915787.83      6945818.71      2915775.74      6945639.08
#Sta/Elev= 30
  4463.2  434.85  4508.6  431.67  4586.5  425.42  4633.0  423.95  4659.8  420.79
  4699.0  418.52  4733.0  414.45  4876.5  406.16  4913.4  402.98  4918.6  403.48
  4926.7  401.90  4972.8  399.40  4973.3  398.60  4978.8  399.40  5027.2  400.89
  5054.0  401.78  5059.1  400.96  5061.5  401.90  5067.4  404.23  5097.7  406.04
  5125.0  410.80  5130.1  409.69  5273.7  420.01  5390.6  430.87  5396.3  432.61
  5430.7  434.11  5509.8  440.30  5514.8  439.70  5568.7  445.16  5577.0  446.41
#Mann=8,-1,0
  4463.2    0.05       0  4508.6    0.08       0  4876.5    0.16       0
  4972.8    0.07       0  4978.8    0.16       0  5027.2    0.08       0
  5273.7    0.16       0  5568.7    0.05       0
Bank Sta=4926.7,5061.5
Exp/Cntr=0.3,0.1

Type RM Length L Ch R = 1,12617,354,354,354
BEGIN DESCRIPTION:
UNT 023 IN DRY CR WATERSHED 20.0
END DESCRIPTION:
XS GIS Cut Line= 3
      2915625.00      6946825.00      2915825.00      6946225.00
      2915925.01      6945824.96
#Sta/Elev= 30
  4345.2  442.58  4389.5  439.05  4482.2  432.46  4513.9  429.49  4524.4  427.14
  4587.6  424.41  4688.7  415.30  4914.4  403.39  4950.4  399.61  4966.5  398.08
  4980.2  397.79  4997.8  395.24  4998.3  394.44  5003.8  395.24  5018.9  397.55
  5036.9  398.77  5042.1  397.70  5064.1  399.61  5067.0  399.91  5078.2  401.30
  5083.3  400.45  5119.4  405.18  5165.8  406.86  5207.0  409.81  5267.6  419.10
  5289.5  421.45  5307.5  425.62  5330.7  428.02  5348.7  431.89  5390.0  436.42
#Mann=9,-1,0
  4345.2    0.05       0  4389.5    0.08       0  4688.7    0.05       0
  4966.5    0.08       0  4997.8    0.07       0  5003.8    0.08       0
  5018.9    0.16       0  5067.0    0.05       0  5267.6    0.08       0
Bank Sta=4950.4,5064.1
Exp/Cntr=0.3,0.1

Type RM Length L Ch R = 1,12263,429,429,429
BEGIN DESCRIPTION:
UNT 023 IN DRY CR WATERSHED 19.0
END DESCRIPTION:
XS GIS Cut Line= 3
      2915724.99      6946725.01      2916175.00      6946125.00
      2916075.01      6945825.04
#Sta/Elev= 30
  4289.3  433.98  4319.5  431.67  4446.6  422.37  4739.3  405.88  4752.9  404.97
  4761.2  402.81  4767.4  403.96  4775.8  402.98  4782.0  405.11  4827.9  402.11
  4867.4  401.48  4935.2  397.51  4967.4  395.16  4982.0  391.68  4996.6  394.96
  5017.4  393.84  5025.8  394.80  5029.0  391.11  5029.5  390.31  5034.5  390.31
  5035.0  391.11  5036.2  393.22  5042.0  393.22  5056.0  397.51  5070.9  401.09
  5134.2  411.08  5208.0  418.03  5239.6  419.96  5313.4  429.71  5355.5  433.97
#Mann=5,-1,0
  4289.3    0.08       0  4319.5    0.05       0  4827.9    0.16       0
  5029.0    0.07       0  5035.0    0.16       0
Bank Sta=4935.2,5056
Exp/Cntr=0.3,0.1

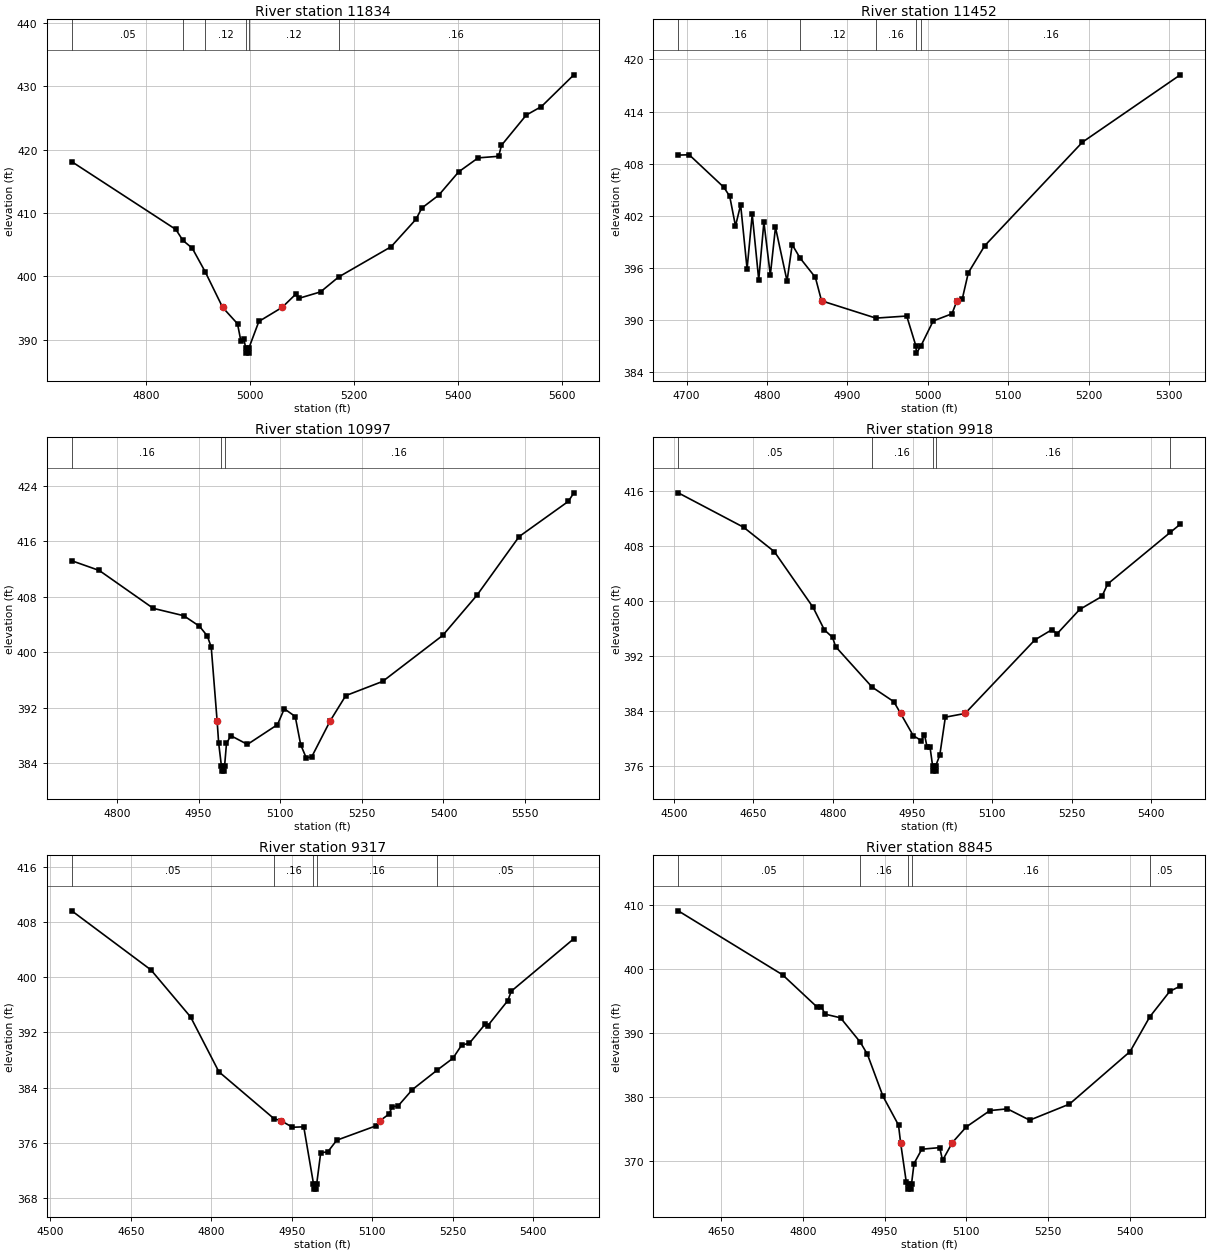
Type RM Length L Ch R = 1,11834,382,382,382
BEGIN DESCRIPTION:
UNT 023 IN DRY CR WATERSHED 18.0
END DESCRIPTION:
XS GIS Cut Line= 3
      2916274.99      6946675.03      2916375.00      6946375.00
      2916625.02      6945774.96
#Sta/Elev= 30
  4656.4  418.09  4856.7  407.40  4870.3  405.67  4888.3  404.44  4913.2  400.72
  4946.8  395.10  4975.4  392.52  4981.9  389.78  4987.3  390.17  4991.3  388.69
  4991.8  387.89  4996.8  387.89  4997.3  388.69  5016.5  392.89  5061.2  395.10
  5088.0  397.23  5093.4  396.53  5135.2  397.55  5170.0  399.90  5271.1  404.68
  5318.8  409.00  5330.2  410.78  5362.7  412.81  5401.1  416.49  5438.5  418.69
  5478.0  418.94  5483.4  420.67  5531.1  425.44  5560.4  426.79  5622.7  431.79
#Mann=6,-1,0
  4656.4    0.05       0  4870.3    0.16       0  4913.2    0.12       0
  4991.3    0.07       0  4997.3    0.12       0  5170.0    0.16       0
Bank Sta=4946.8,5061.2
Exp/Cntr=0.3,0.1

Type RM Length L Ch R = 1,11452,455,455,455
BEGIN DESCRIPTION:
UNT 023 IN DRY CR WATERSHED 17.0
END DESCRIPTION:
XS GIS Cut Line= 3
      2916475.00      6946525.00      2916675.00      6946275.00
      2916725.00      6945975.00
#Sta/Elev= 30
  4689.6  408.99  4703.2  409.03  4746.4  405.28  4753.6  404.25  4760.8  400.83
  4767.2  403.27  4775.2  395.89  4781.6  402.17  4789.7  394.64  4796.1  401.27
  4804.1  395.18  4810.5  400.68  4824.9  394.50  4831.3  398.68  4841.2  397.13
  4860.1  394.92  4867.8  392.22  4935.4  390.23  4973.7  390.47  4985.2  387.00
  4985.7  386.20  4991.2  387.00  5006.6  389.90  5030.0  390.73  5036.1  392.22
  5042.7  392.40  5050.3  395.45  5070.6  398.55  5192.2  410.48  5313.9  418.23
#Mann=5,-1,0
  4689.6    0.16       0  4841.2    0.12       0  4935.4    0.16       0
  4985.2    0.07       0  4991.2    0.16       0
Bank Sta=4867.8,5036.1
Exp/Cntr=0.3,0.1

Type RM Length L Ch R = 1,10997,1079,1079,1079
BEGIN DESCRIPTION:
UNT 023 IN DRY CR WATERSHED 16.0
END DESCRIPTION:
XS GIS Cut Line= 3
      2916624.98      6946725.03      2916825.00      6946475.00
      2916875.00      6945874.97
#Sta/Elev= 30
  4717.2  413.18  4767.7  411.78  4866.9  406.32  4922.9  405.26  4951.8  403.74
  4966.2  402.34  4973.4  400.72  4984.2  390.11  4987.0  386.94  4992.0  383.66
  4992.5  382.86  4997.5  382.86  4998.0  383.66  5001.4  386.85  5009.4  387.97
  5039.9  386.71  5095.1  389.56  5107.6  391.85  5127.7  390.73  5137.7  386.67
  5147.8  384.79  5157.8  384.89  5192.0  390.12  5220.5  393.74  5288.3  395.79
  5398.6  402.42  5461.4  408.20  5539.1  416.67  5629.4  421.74  5639.5  422.97
#Mann=3,-1,0
  4717.2    0.16       0  4992.0    0.07       0  4998.0    0.16       0
Bank Sta=4984.2,5192
Exp/Cntr=0.3,0.1

Type RM Length L Ch R = 1,9918,601,601,601
BEGIN DESCRIPTION:
UNT 023 IN DRY CR WATERSHED 15.0
END DESCRIPTION:
XS GIS Cut Line= 3
      2917025.01      6947024.98      2917275.00      6946625.00
      2917424.99      6946175.02
#Sta/Elev= 30
  4508.5  415.78  4631.7  410.77  4689.5  407.23  4762.6  399.12  4783.8  395.85
  4799.2  394.76  4805.1  393.40  4873.8  387.52  4914.7  385.40  4927.5  383.69
  4951.3  380.46  4966.6  379.74  4972.5  380.62  4977.2  378.86  4982.8  378.86
  4987.7  376.10  4988.2  375.30  4993.3  375.30  4993.8  376.10  5001.3  377.62
  5011.8  383.15  5049.0  383.69  5180.5  394.39  5212.1  395.85  5222.6  395.30
  5264.8  398.81  5306.9  400.72  5317.5  402.51  5435.8  410.04  5454.5  411.22
#Mann=5,-1,0
  4508.5    0.05       0  4873.8    0.16       0  4987.7    0.07       0
  4993.8    0.16       0  5435.8    0.05       0
Bank Sta=4927.5,5049
Exp/Cntr=0.3,0.1

Type RM Length L Ch R = 1,9317,472,472,472
BEGIN DESCRIPTION:
UNT 023 IN DRY CR WATERSHED 14.0
END DESCRIPTION:
XS GIS Cut Line= 3
      2917624.98      6947225.05      2917775.00      6946775.00
      2917674.99      6946324.97
#Sta/Elev= 30
  4540.2  409.61  4687.8  401.05  4761.6  394.24  4814.3  386.30  4917.0  379.51
  4930.2  379.21  4951.3  378.27  4972.4  378.33  4990.5  370.11  4991.0  369.31
  4996.1  369.31  4996.6  370.11  5004.0  374.58  5017.2  374.71  5033.8  376.39
  5106.8  378.47  5114.4  379.21  5131.1  380.17  5137.5  381.27  5147.8  381.32
  5174.7  383.72  5220.9  386.54  5250.2  388.25  5266.8  390.19  5280.9  390.43
  5310.4  393.20  5315.5  393.00  5352.6  396.61  5359.0  397.97  5475.6  405.57
#Mann=5,-1,0
  4540.2    0.05       0  4917.0    0.16       0  4990.5    0.07       0
  4996.6    0.16       0  5220.9    0.05       0
Bank Sta=4930.2,5114.4
Exp/Cntr=0.3,0.1

Type RM Length L Ch R = 1,8845,630,630,630
BEGIN DESCRIPTION:
UNT 023 IN DRY CR WATERSHED 13.0
END DESCRIPTION:
XS GIS Cut Line= 3
      2917724.97      6947275.03      2918075.00      6946975.00
      2917975.00      6946525.00
#Sta/Elev= 30
  4571.2  409.09  4762.8  399.09  4826.4  394.03  4834.1  394.10  4840.7  392.94
  4869.2  392.37  4905.5  388.56  4918.6  386.66  4947.2  380.10  4975.7  375.60
  4979.5  372.87  4990.0  366.68  4993.5  366.39  4994.0  365.59  4999.1  365.59
  4999.6  366.39  5004.2  369.59  5018.5  371.83  5051.4  372.08  5056.6  370.09
  5074.6  372.87  5100.1  375.31  5143.6  377.87  5175.6  378.14  5216.6  376.37
  5289.6  378.88  5401.0  387.10  5437.2  392.53  5474.0  396.52  5493.2  397.32
#Mann=5,-1,0
  4571.2    0.05       0  4905.5    0.16       0  4993.5    0.07       0
  4999.6    0.16       0  5437.2    0.05       0
Bank Sta=4979.5,5074.6
Exp/Cntr=0.3,0.1

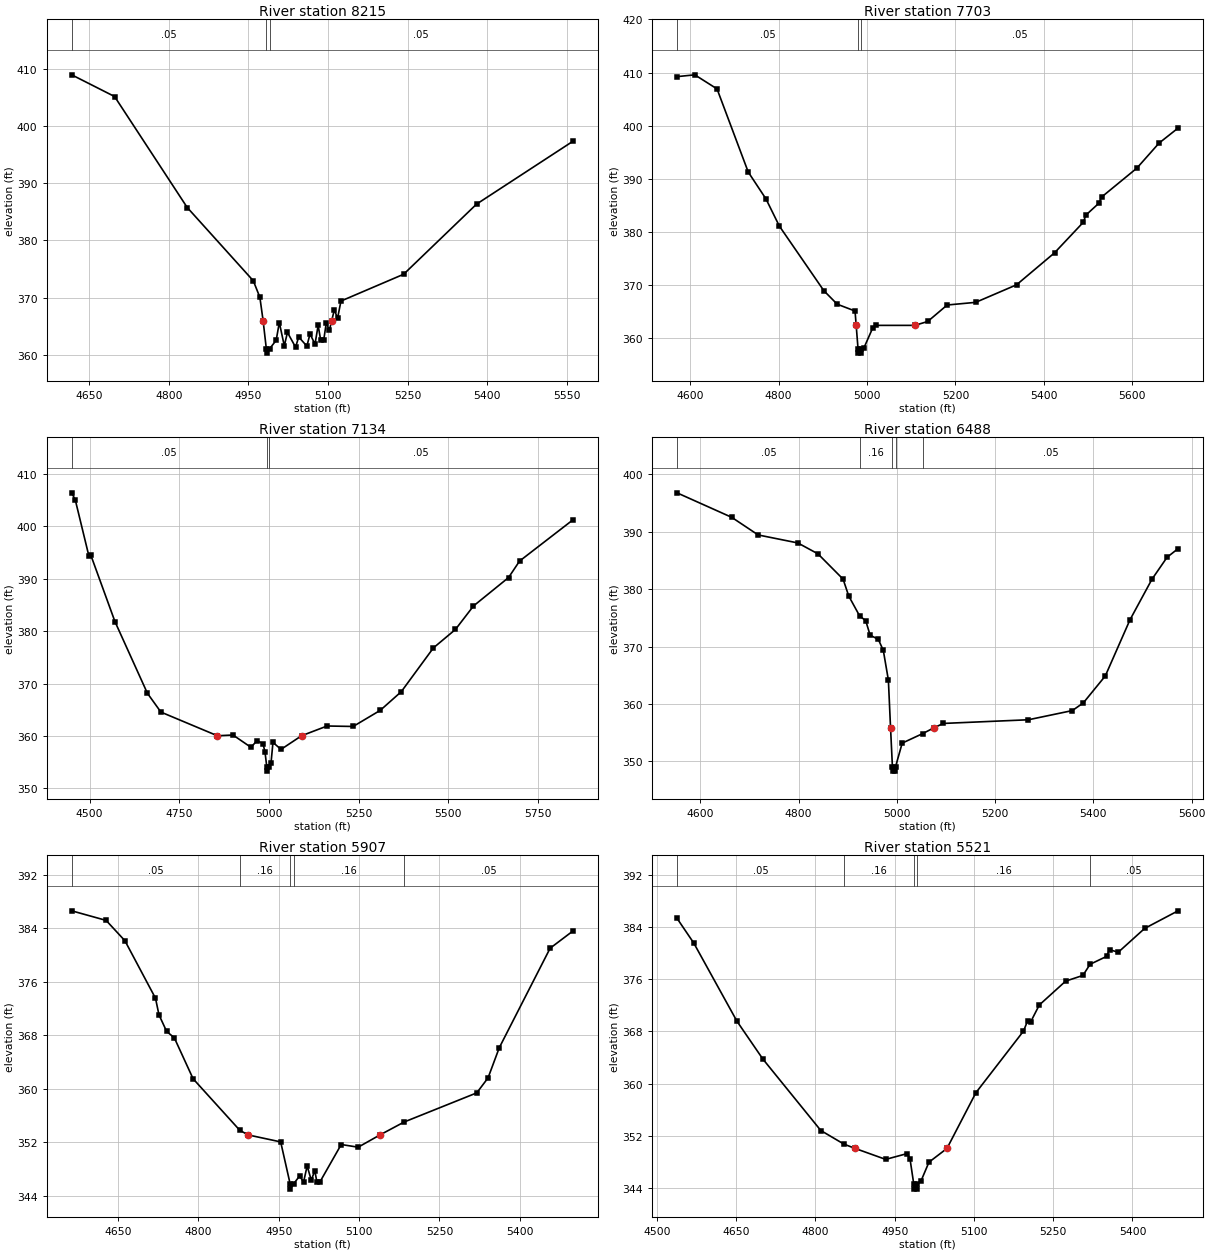
Type RM Length L Ch R = 1,8215,512,512,512
BEGIN DESCRIPTION:
UNT 023 IN DRY CR WATERSHED 12.0
END DESCRIPTION:
XS GIS Cut Line= 3
      2918225.02      6947524.96      2918475.00      6947125.00
      2918875.04      6946874.97
#Sta/Elev= 30
  4617.4  408.94  4698.1  405.15  4834.9  385.76  4959.3  372.96  4971.7  370.07
  4977.8  365.97  4983.8  361.12  4984.3  360.32  4990.3  361.12  5002.4  362.56
  5008.3  365.67  5017.7  361.59  5023.6  363.94  5038.9  361.36  5044.8  363.14
  5060.2  361.54  5066.1  363.68  5075.5  361.88  5081.4  365.17  5086.1  362.65
  5092.0  362.65  5096.7  365.58  5102.6  364.33  5106.9  365.97  5112.0  367.92
  5117.9  366.37  5124.4  369.42  5242.4  374.10  5379.7  386.35  5560.8  397.31
#Mann=3,-1,0
  4617.4    0.05       0  4983.8    0.03       0  4990.3    0.05       0
Bank Sta=4977.8,5106.9
Exp/Cntr=0.3,0.1

Type RM Length L Ch R = 1,7703,569,569,569
BEGIN DESCRIPTION:
UNT 023 IN DRY CR WATERSHED 11.0
END DESCRIPTION:
XS GIS Cut Line= 3
      2918225.01      6947625.00      2918675.00      6947575.00
      2919074.98      6947025.03
#Sta/Elev= 30
  4570.5  409.24  4610.7  409.58  4661.0  406.93  4731.5  391.30  4771.7  386.23
  4801.9  381.13  4902.5  368.98  4932.7  366.44  4973.0  365.16  4975.6  362.46
  4979.8  358.04  4980.3  357.24  4985.8  357.24  4986.3  358.04  4993.1  358.22
  5013.2  362.02  5020.7  362.46  5108.2  362.46  5137.3  363.19  5181.3  366.29
  5245.8  366.79  5338.2  370.09  5424.0  376.10  5488.9  381.83  5495.1  383.21
  5524.4  385.44  5530.6  386.60  5610.2  392.03  5660.4  396.74  5703.3  399.56
#Mann=3,-1,0
  4570.5    0.05       0  4979.8    0.03       0  4986.3    0.05       0
Bank Sta=4975.6,5108.2
Exp/Cntr=0.3,0.1

Type RM Length L Ch R = 1,7134,646,646,646
BEGIN DESCRIPTION:
UNT 023 IN DRY CR WATERSHED 10.0
END DESCRIPTION:
XS GIS Cut Line= 3
      2918375.05      6947825.00      2918875.00      6947875.00
      2919275.01      6947074.97
#Sta/Elev= 30
  4450.0  406.34  4460.0  404.97  4497.7  394.35  4502.7  394.57  4570.5  381.81
  4661.0  368.15  4698.7  364.56  4856.2  360.05  4899.7  360.19  4949.9  357.84
  4966.4  359.12  4983.2  358.55  4988.8  357.01  4993.9  354.11  4994.4  353.31
  5000.4  354.11  5005.6  354.78  5011.1  358.79  5033.5  357.45  5090.8  360.05
  5162.1  361.91  5234.7  361.82  5310.2  364.89  5368.9  368.45  5458.4  376.79
  5519.8  380.30  5570.2  384.78  5668.0  390.20  5698.7  393.34  5846.9  401.16
#Mann=3,-1,0
  4450.0    0.05       0  4993.9    0.03       0  5000.4    0.05       0
Bank Sta=4856.2,5090.8
Exp/Cntr=0.3,0.1

Type RM Length L Ch R = 1,6488,581,581,581
BEGIN DESCRIPTION:
UNT 023 IN DRY CR WATERSHED 9.0
END DESCRIPTION:
XS GIS Cut Line= 3
      2918624.98      6948275.00      2919075.00      6948175.00
      2919574.99      6947925.01
#Sta/Elev= 30
  4552.3  396.79  4663.7  392.52  4717.5  389.45  4798.2  388.06  4839.2  386.16
  4890.4  381.75  4901.9  378.81  4924.1  375.34  4936.5  374.51  4945.4  371.99
  4962.1  371.26  4972.3  369.33  4982.6  364.17  4987.0  355.88  4990.8  349.10
  4991.3  348.30  4996.8  348.30  4997.3  349.10  5010.7  353.18  5052.7  354.85
  5076.1  355.88  5094.4  356.61  5267.7  357.25  5357.1  358.85  5379.5  360.19
  5424.2  364.88  5474.5  374.67  5519.2  381.73  5550.0  385.56  5572.3  387.06
#Mann=5,-1,0
  4552.3    0.05       0  4924.1    0.16       0  4990.8    0.07       0
  4997.3    0.16       0  5052.7    0.05       0
Bank Sta=4987,5076.1
Exp/Cntr=0.3,0.1

Type RM Length L Ch R = 1,5907,386,386,386
BEGIN DESCRIPTION:
UNT 023 IN DRY CR WATERSHED 8.0
END DESCRIPTION:
XS GIS Cut Line= 3
      2919175.03      6948824.97      2919475.00      6948475.00
      2919625.01      6948024.98
#Sta/Elev= 30
  4563.6  386.61  4627.8  385.18  4662.9  382.14  4720.0  373.54  4726.5  371.06
  4740.8  368.58  4755.1  367.63  4790.2  361.50  4877.1  353.82  4892.6  353.11
  4953.7  352.06  4971.3  345.80  4971.8  345.00  4977.9  345.80  4988.9  346.95
  4996.5  346.07  5003.1  348.47  5010.8  346.33  5017.4  347.77  5021.2  346.11
  5027.2  346.11  5066.7  351.67  5098.3  351.27  5139.2  353.11  5184.3  355.04
  5319.7  359.39  5340.8  361.63  5361.8  366.15  5456.7  381.02  5498.9  383.57
#Mann=5,-1,0
  4563.6    0.05       0  4877.1    0.16       0  4971.3    0.07       0
  4977.9    0.16       0  5184.3    0.05       0
Bank Sta=4892.6,5139.2
Exp/Cntr=0.3,0.1

Type RM Length L Ch R = 1,5521,365,365,365
BEGIN DESCRIPTION:
Mapping XS 95e805dd
END DESCRIPTION:
XS GIS Cut Line= 3
      2919217.48      6948817.36      2919755.69      6948680.63
      2920105.08      6948500.51
#Sta/Elev= 30
  4537.9  385.34  4569.6  381.55  4651.5  369.54  4700.4  363.76  4810.1  352.80
  4853.9  350.71  4875.1  350.05  4932.9  348.37  4973.9  349.27  4979.0  348.42
  4986.0  344.61  4986.5  343.81  4992.1  343.81  4992.6  344.61  4999.6  345.03
  5014.8  347.94  5048.9  350.05  5103.7  358.60  5193.7  368.04  5201.5  369.60
  5207.1  369.42  5223.7  372.05  5273.6  375.71  5306.2  376.58  5319.8  378.29
  5351.0  379.50  5356.6  380.53  5373.2  380.14  5423.1  383.79  5486.3  386.49
#Mann=5,-1,0
  4537.9    0.05       0  4853.9    0.16       0  4986.0    0.07       0
  4992.6    0.16       0  5319.8    0.05       0
Bank Sta=4875.1,5048.9
Exp/Cntr=0.3,0.1

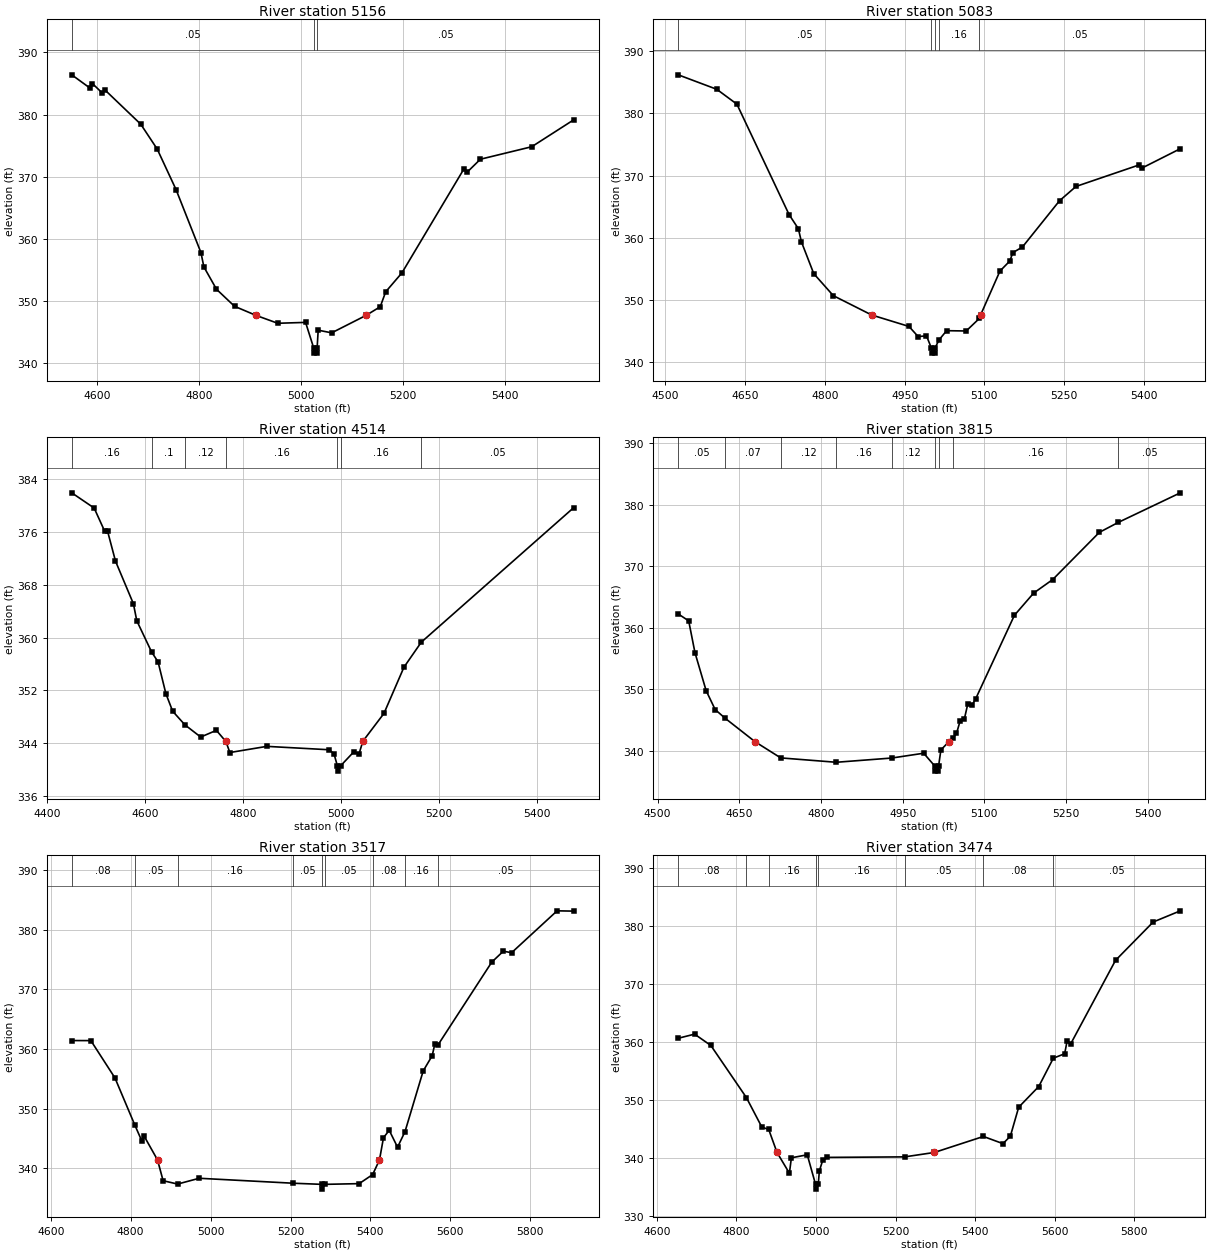
Type RM Length L Ch R = 1,5156,73,73,73
BEGIN DESCRIPTION:
Mapping XS e3a36d6a
END DESCRIPTION:
XS GIS Cut Line= 3
      2919208.78      6948836.87      2919660.20      6949010.49
      2920135.42      6949166.73
#Sta/Elev= 30
  4550.7  386.40  4585.7  384.31  4591.1  385.00  4610.3  383.49  4615.7  383.97
  4685.9  378.46  4718.1  374.47  4755.0  367.96  4803.8  357.83  4809.6  355.52
  4834.3  351.93  4869.6  349.19  4911.7  347.73  4954.3  346.46  5008.9  346.60
  5024.9  342.46  5025.4  341.66  5031.0  341.66  5031.5  342.46  5033.6  345.35
  5060.0  344.92  5127.5  347.73  5155.2  349.12  5165.9  351.52  5197.7  354.56
  5319.6  371.33  5324.9  370.70  5351.4  372.83  5452.1  374.84  5534.6  379.18
#Mann=3,-1,0
  4550.7    0.05       0  5024.9    0.04       0  5031.5    0.05       0
Bank Sta=4911.7,5127.5
Exp/Cntr=0.3,0.1

Type RM Length L Ch R = 1,5083,569,569,569
BEGIN DESCRIPTION:
Mapping XS ff865b1c
END DESCRIPTION:
XS GIS Cut Line= 3
      2919208.77      6948865.08      2919649.35      6949062.58
      2920085.53      6949214.48
#Sta/Elev= 30
  4524.0  386.21  4596.6  383.88  4634.4  381.49  4732.6  363.73  4750.0  361.47
  4755.8  359.35  4779.0  354.24  4815.8  350.70  4888.0  347.59  4958.2  345.75
  4975.4  344.12  4991.1  344.24  5000.4  342.26  5000.9  341.46  5006.5  341.46
  5007.0  342.26  5014.8  343.60  5029.0  345.07  5065.8  345.02  5090.6  347.04
  5092.9  347.59  5129.3  354.65  5148.1  356.29  5153.4  357.61  5171.6  358.52
  5241.4  365.96  5272.4  368.26  5391.5  371.73  5396.8  371.23  5468.7  374.33
#Mann=5,-1,0
  4524.0    0.05       0  5000.4    0.04       0  5007.0    0.05       0
  5014.8    0.16       0  5090.6    0.05       0
Bank Sta=4888,5092.9
Exp/Cntr=0.3,0.1

Type RM Length L Ch R = 1,4514,699,699,699
BEGIN DESCRIPTION:
UNT 023 IN DRY CR WATERSHED 6.0
END DESCRIPTION:
XS GIS Cut Line= 3
      2919225.04      6949175.02      2919675.00      6949425.00
      2920174.96      6949524.99
#Sta/Elev= 30
  4450.7  381.86  4496.4  379.56  4518.1  376.02  4523.9  376.03  4539.9  371.55
  4576.5  365.10  4583.4  362.53  4613.8  357.79  4626.8  356.33  4642.8  351.51
  4656.6  348.87  4681.6  346.81  4713.8  344.97  4745.8  345.98  4764.8  344.33
  4765.4  344.26  4773.3  342.63  4848.8  343.56  4975.6  343.05  4985.8  342.45
  4992.7  340.62  4993.2  339.82  4999.3  340.62  5026.6  342.76  5036.8  342.40
  5044.7  344.33  5087.8  348.54  5128.6  355.52  5164.0  359.30  5475.3  379.64
#Mann=7,-1,0
  4450.7    0.16       0  4613.8     0.1       0  4681.6    0.12       0
  4765.4    0.16       0  4992.7    0.07       0  4999.3    0.16       0
  5164.0    0.05       0
Bank Sta=4764.8,5044.7
Exp/Cntr=0.3,0.1

Type RM Length L Ch R = 1,3815,298,298,298
BEGIN DESCRIPTION:
UNT 023 IN DRY CR WATERSHED 5.0
END DESCRIPTION:
XS GIS Cut Line= 3
      2919425.03      6950024.99      2919875.00      6949925.00
      2920224.98      6949625.01
#Sta/Elev= 30
  4537.8  362.24  4557.0  361.11  4568.5  355.95  4589.0  349.77  4605.6  346.69
  4624.0  345.27  4678.9  341.46  4726.0  338.83  4828.0  338.12  4929.9  338.81
  4988.5  339.59  5009.1  337.48  5009.6  336.68  5015.3  336.68  5015.8  337.48
  5020.1  340.13  5034.7  341.46  5042.0  342.04  5048.7  342.80  5055.3  344.80
  5063.0  345.10  5069.5  347.61  5077.2  347.39  5083.8  348.41  5155.1  362.02
  5190.3  365.62  5225.4  367.83  5311.0  375.50  5346.2  377.14  5459.7  381.93
#Mann=9,-1,0
  4537.8    0.05       0  4624.0    0.07       0  4726.0    0.12       0
  4828.0    0.16       0  4929.9    0.12       0  5009.1    0.07       0
  5015.8    0.12       0  5042.0    0.16       0  5346.2    0.05       0
Bank Sta=4678.9,5034.7
Exp/Cntr=0.3,0.1

Type RM Length L Ch R = 1,3517,43,43,43
BEGIN DESCRIPTION:
Mapping XS d3bf9dfe
END DESCRIPTION:
XS GIS Cut Line= 4
      2919447.36      6950163.38      2919725.12      6950189.42
      2920193.87      6950208.95      2920593.16      6949894.30
#Sta/Elev= 30
  4652.6  361.40  4700.4  361.39  4760.7  355.13  4810.2  347.26  4828.3  344.51
  4833.3  345.42  4867.2  341.39  4881.2  337.90  4917.5  337.34  4971.5  338.31
  5206.5  337.48  5278.4  337.29  5278.9  336.49  5285.1  337.29  5371.8  337.41
  5405.6  338.93  5422.7  341.39  5432.7  345.12  5447.1  346.35  5467.9  343.52
  5486.6  346.14  5532.1  356.31  5554.6  358.86  5561.0  360.77  5568.3  360.58
  5703.7  374.55  5732.6  376.38  5753.4  376.13  5867.2  383.15  5909.1  383.10
#Mann=9,-1,0
  4652.6    0.08       0  4810.2    0.05       0  4917.5    0.16       0
  5206.5    0.05       0  5278.4    0.07       0  5285.1    0.05       0
  5405.6    0.08       0  5486.6    0.16       0  5568.3    0.05       0
Bank Sta=4867.2,5422.7
Exp/Cntr=0.3,0.1

Type RM Length L Ch R = 1,3474,29,29,29
BEGIN DESCRIPTION:
Mapping XS 326bc026
END DESCRIPTION:
XS GIS Cut Line= 4
      2919434.34      6950178.57      2919796.74      6950232.83
      2920243.79      6950232.83      2920608.35      6949972.42
#Sta/Elev= 30
  4653.8  360.64  4694.9  361.35  4735.7  359.40  4825.0  350.42  4863.9  345.32
  4881.1  344.92  4902.0  340.95  4933.1  337.37  4938.1  340.03  4978.0  340.55
  4998.9  335.43  4999.4  334.63  5005.6  335.43  5008.4  337.78  5016.8  339.60
  5028.5  340.10  5222.6  340.19  5297.3  340.95  5420.6  343.71  5469.7  342.47
  5488.3  343.76  5509.2  348.75  5559.6  352.32  5596.3  357.21  5624.7  357.97
  5630.8  360.14  5639.4  359.61  5752.5  374.07  5847.1  380.68  5915.3  382.61
#Mann=8,-1,0
  4653.8    0.08       0  4825.0    0.05       0  4881.1    0.16       0
  4998.9    0.07       0  5005.6    0.16       0  5222.6    0.05       0
  5420.6    0.08       0  5596.3    0.05       0
Bank Sta=4902,5297.3
Exp/Cntr=0.3,0.1