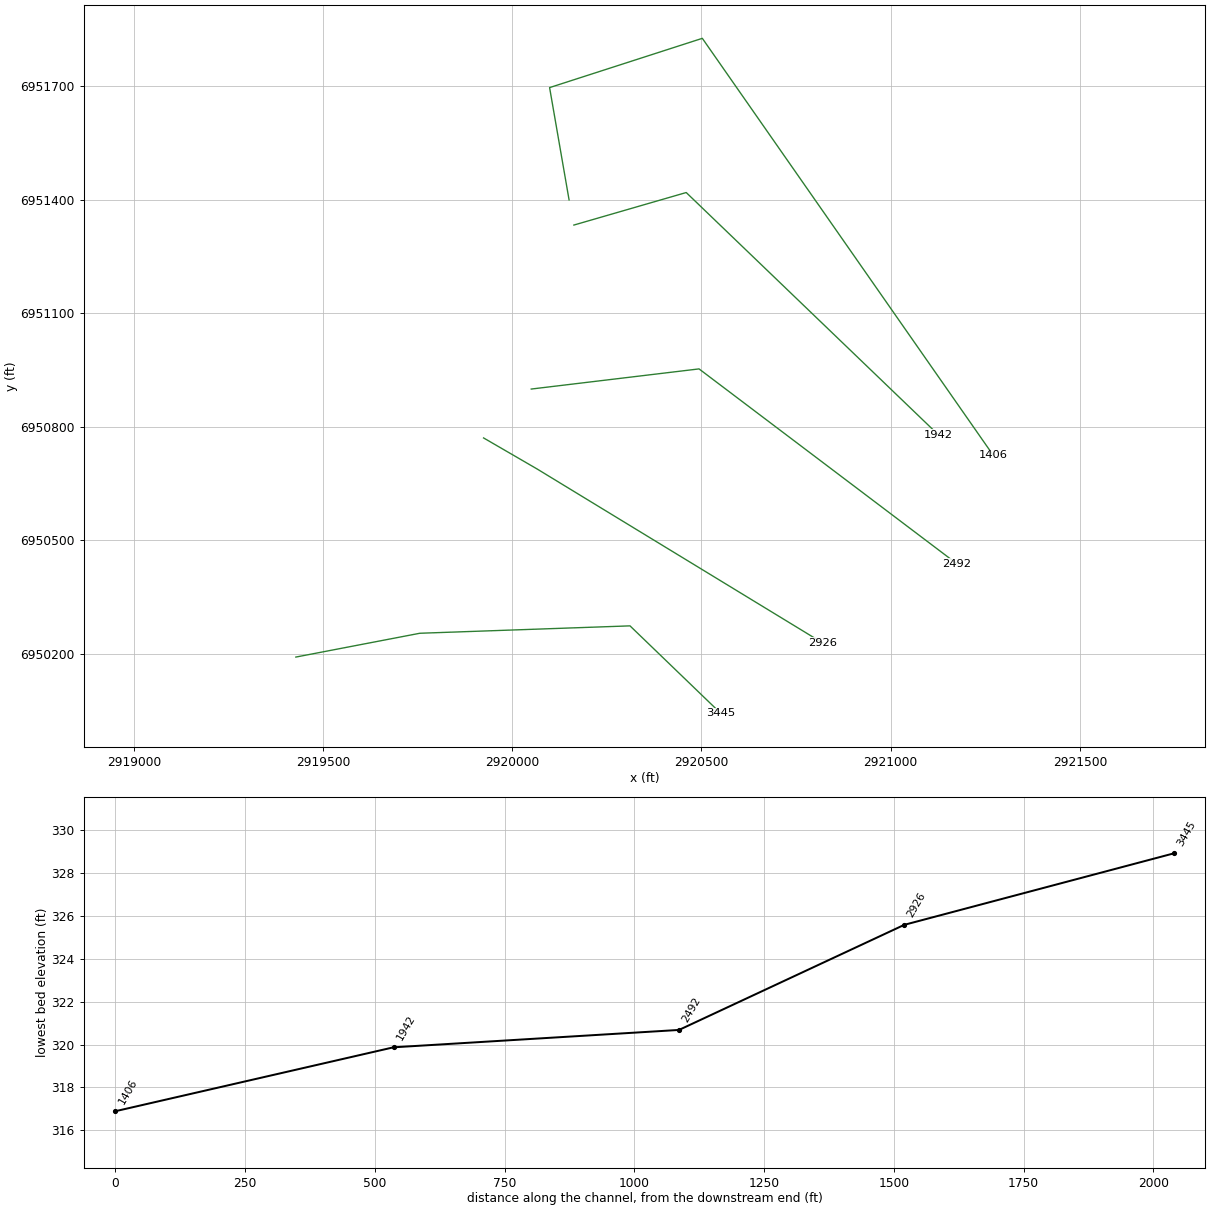
HEC-RAS study UNT 023 IN DRY CR WATERSHED.prj: UNT 023 IN DRY CR WATERSHED Base Level Engineering

--- UNT 023 IN DRY CR WATERSHED.g01 (geometry) --- (continued)

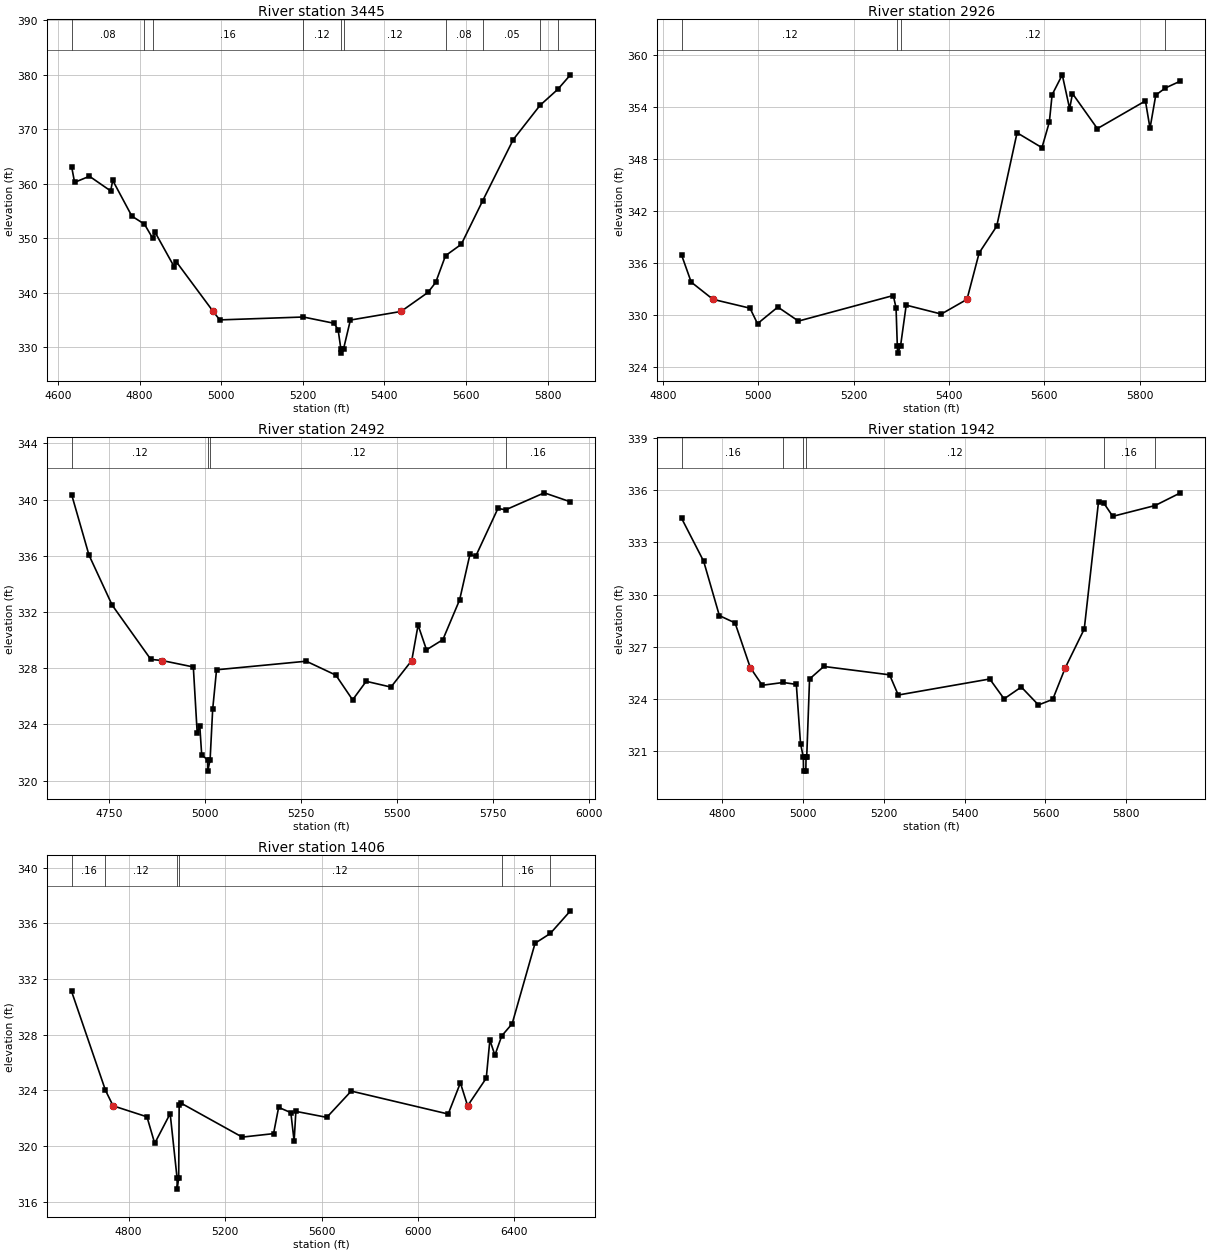
Type RM Length L Ch R = 1,3445,519,519,519
BEGIN DESCRIPTION:
Mapping XS 1a26913e
END DESCRIPTION:
XS GIS Cut Line= 4
      2919427.84      6950191.60      2919755.51      6950254.53
      2920311.06      6950274.06      2920550.99      6950042.78
#Sta/Elev= 30
  4633.2  363.16  4640.5  360.26  4676.9  361.38  4728.9  358.69  4734.0  360.62
  4780.9  354.06  4811.7  352.59  4831.8  350.02  4837.9  351.08  4884.8  344.74
  4889.9  345.68  4980.2  336.56  4996.4  335.01  5201.3  335.54  5276.5  334.39
  5286.5  333.21  5293.2  329.71  5293.7  328.91  5299.9  329.71  5316.6  334.98
  5440.7  336.56  5506.7  340.05  5525.7  341.89  5549.8  346.80  5588.5  348.89
  5640.8  356.87  5715.8  368.11  5781.5  374.40  5825.2  377.35  5856.0  380.00
#Mann=10,-1,0
  4633.2    0.08       0  4811.7    0.05       0  4831.8    0.16       0
  5201.3    0.12       0  5293.2    0.07       0  5299.9    0.12       0
  5549.8    0.08       0  5640.8    0.05       0  5781.5    0.16       0
  5825.2    0.05       0
Bank Sta=4980.2,5440.7
Exp/Cntr=0.3,0.1

Type RM Length L Ch R = 1,2926,434,434,434
BEGIN DESCRIPTION:
Mapping XS a31819e1
END DESCRIPTION:
XS GIS Cut Line= 3
      2919924.04      6950770.78      2920065.55      6950688.70
      2920819.22      6950229.56
#Sta/Elev= 30
  4839.6  336.88  4859.6  333.78  4905.3  331.79  4982.9  330.77  4998.7  328.98
  5041.3  330.90  5084.5  329.28  5283.4  332.23  5289.2  330.82  5291.9  326.38
  5292.4  325.58  5298.6  326.38  5310.5  331.12  5384.1  330.09  5438.0  331.79
  5463.5  337.15  5500.3  340.23  5543.0  351.02  5595.2  349.30  5610.7  352.26
  5616.5  355.41  5637.8  357.71  5653.3  353.79  5659.2  355.55  5711.4  351.50
  5812.2  354.70  5821.8  351.54  5833.9  355.37  5854.0  356.19  5885.7  356.99
#Mann=4,-1,0
  4839.6    0.12       0  5291.9    0.07       0  5298.6    0.12       0
  5854.0    0.16       0
Bank Sta=4905.3,5438
Exp/Cntr=0.3,0.1

Type RM Length L Ch R = 1,2492,550,550,550
BEGIN DESCRIPTION:
Mapping XS 4331ef21
END DESCRIPTION:
XS GIS Cut Line= 3
      2920050.03      6950900.00      2920493.50      6950953.24
      2921174.22      6950438.80
#Sta/Elev= 30
  4652.3  340.36  4697.6  336.05  4758.0  332.49  4858.7  328.63  4887.9  328.55
  4969.5  328.09  4979.6  323.38  4986.3  323.90  4991.3  321.84  5006.5  321.48
  5007.0  320.68  5013.2  321.48  5019.9  325.07  5030.0  327.89  5263.8  328.50
  5340.9  327.51  5384.6  325.75  5420.0  327.07  5484.5  326.66  5538.7  328.55
  5555.2  331.07  5577.1  329.31  5619.7  330.03  5663.4  332.86  5690.5  336.12
  5705.1  335.95  5763.3  339.37  5783.4  339.27  5884.0  340.48  5952.2  339.84
#Mann=4,-1,0
  4652.3    0.12       0  5006.5    0.07       0  5013.2    0.12       0
  5783.4    0.16       0
Bank Sta=4887.9,5538.7
Exp/Cntr=0.3,0.1

Type RM Length L Ch R = 1,1942,536,536,536
BEGIN DESCRIPTION:
Mapping XS fad4fc7f
END DESCRIPTION:
XS GIS Cut Line= 3
      2920162.75      6951333.44      2920459.64      6951419.38
      2921125.69      6950779.36
#Sta/Elev= 30
  4700.8  334.38  4755.2  331.92  4794.0  328.80  4832.8  328.38  4870.3  325.82
  4900.0  324.80  4951.7  324.96  4984.2  324.85  4994.6  321.45  5001.5  320.67
  5002.0  319.87  5007.7  319.87  5008.2  320.67  5009.9  320.67  5016.9  325.16
  5052.1  325.88  5214.7  325.40  5236.1  324.24  5462.2  325.16  5497.7  324.02
  5540.2  324.70  5582.6  323.67  5617.9  323.99  5649.2  325.82  5695.8  328.03
  5731.1  335.35  5743.5  335.28  5766.3  334.50  5870.9  335.12  5933.6  335.85
#Mann=6,-1,0
  4700.8    0.16       0  4951.7    0.12       0  5001.5    0.07       0
  5008.2    0.12       0  5743.5    0.16       0  5870.9    0.12       0
Bank Sta=4870.3,5649.2
Exp/Cntr=0.3,0.1

Type RM Length L Ch R = 1,1406,0,0,0
BEGIN DESCRIPTION:
UNT 023 IN DRY CR WATERSHED 3.0
END DESCRIPTION:
XS GIS Cut Line= 4
      2920150.00      6951400.00      2920098.53      6951696.73
      2920502.18      6951826.94      2921270.76      6950725.34
#Sta/Elev= 30
  4563.6  331.10  4704.1  323.99  4735.6  322.88  4876.1  322.09  4908.2  320.18
  4972.3  322.32  5000.9  317.69  5001.4  316.89  5007.6  317.69  5009.6  322.96
  5018.7  323.06  5271.2  320.63  5401.0  320.88  5422.1  322.77  5472.7  322.39
  5486.3  320.34  5493.6  322.48  5621.8  322.05  5723.1  323.94  6125.2  322.29
  6175.8  324.53  6205.8  322.88  6283.1  324.87  6298.0  327.61  6318.9  326.52
  6347.3  327.91  6390.4  328.78  6485.5  334.57  6548.5  335.27  6632.1  336.90
#Mann=6,-1,0
  4563.6    0.16       0  4704.1    0.12       0  5000.9    0.07       0
  5007.6    0.12       0  6347.3    0.16       0  6548.5    0.12       0
Bank Sta=4735.6,6205.8
Exp/Cntr=0.3,0.1

Chan Stop Cuts=-1