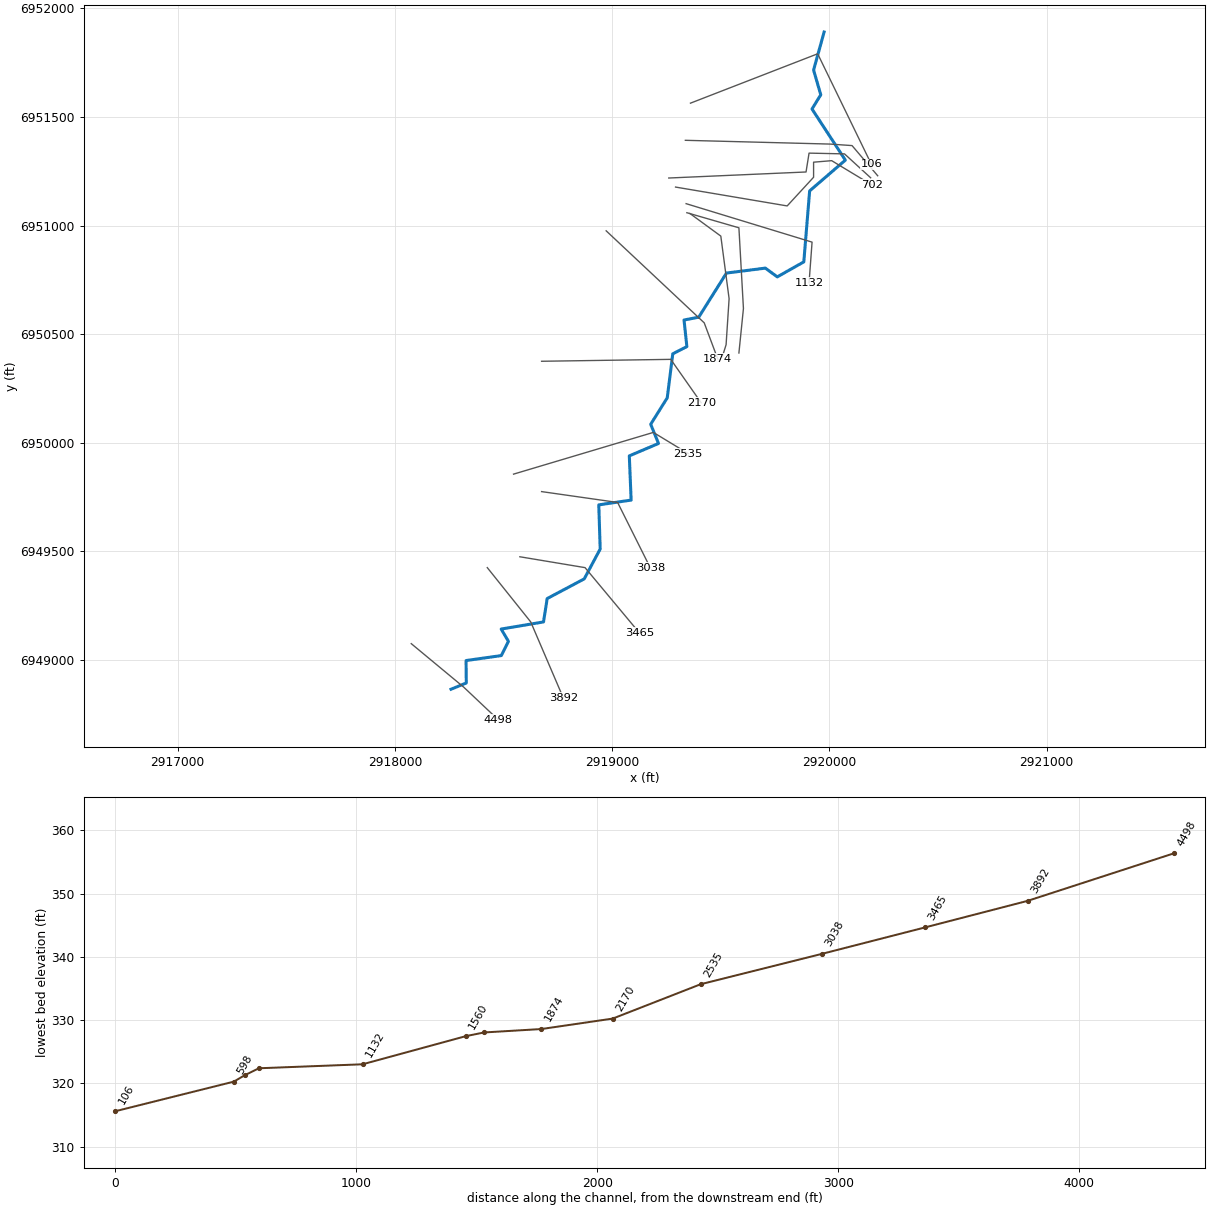
--- UNT 024 IN DRY CR WATERSHED.prj (project) ---

Proj Title=UNT 024 IN DRY CR WATERSHED Base Level Engineering
Current Plan=p01
Default Exp/Contr=0.3,0.1
English Units
Geom File=g01
Flow File=f01
Plan File=p01
BEGIN DESCRIPTION:
UNT 024 IN DRY CR WATERSHED
END DESCRIPTION:

--- UNT 024 IN DRY CR WATERSHED.p01 (plan) ---

Plan Title=Multiple Run
Short Identifier=Multiple
Geom File=g01
Flow File=f01
Subcritical Flow
K Sum by GR= 0
Std Step Tol= 0.01
Critical Tol= 0.01
Num of Std Step Trials= 20
Max Error Tol= 0.3
Flow Tol Ratio= 0.001
Split Flow NTrial= 30
Split Flow Tol= 0.02
Split Flow Ratio= 0.02
Log Output Level= 0
Friction Slope Method= 1
Unsteady Friction Slope Method= 2
Unsteady Bridges Friction Slope Method= 1
Parabolic Critical Depth
Global Vel Dist=  1 , 1 , 1
Global Log Level= 0
CheckData=True
Encroach Param= -1, 0, 0, 0
BEGIN DESCRIPTION:
Multiple Run
END DESCRIPTION:

--- UNT 024 IN DRY CR WATERSHED.f01 (steady flow) ---

Flow Title=Multiple
Number of Profiles=7
Profile Names=10-year,25-year,50-year,1pct_min,100-year,1pct_plu,500-year
River Rch & RM= UNT 024 IN DRY C,Reach-1,4498
     266     339     396     231     460     919     622
River Rch & RM= UNT 024 IN DRY C,Reach-1,2170
     516     688     827     495     987    1970    1408
Boundary for River Rch & Prof#=UNT 024 IN DRY C,Reach-1,1
Up Type=0
Dn Type=3
Dn Slope=0.005
Boundary for River Rch & Prof#=UNT 024 IN DRY C,Reach-1,2
Up Type=0
Dn Type=3
Dn Slope=0.005
Boundary for River Rch & Prof#=UNT 024 IN DRY C,Reach-1,3
Up Type=0
Dn Type=3
Dn Slope=0.005
Boundary for River Rch & Prof#=UNT 024 IN DRY C,Reach-1,4
Up Type=0
Dn Type=3
Dn Slope=0.005
Boundary for River Rch & Prof#=UNT 024 IN DRY C,Reach-1,5
Up Type=0
Dn Type=3
Dn Slope=0.005
Boundary for River Rch & Prof#=UNT 024 IN DRY C,Reach-1,6
Up Type=0
Dn Type=3
Dn Slope=0.005
Boundary for River Rch & Prof#=UNT 024 IN DRY C,Reach-1,7
Up Type=0
Dn Type=3
Dn Slope=0.005

--- UNT 024 IN DRY CR WATERSHED.g01 (geometry) ---

Geom Title=Existing Conditions

River Reach=UNT 024 IN DRY C,Reach-1
Reach XY= 30
      2918258.16      6948865.16      2918328.30      6948893.89
      2918327.25      6948997.20      2918489.66      6949020.13
      2918522.23      6949085.63      2918488.99      6949142.24
      2918683.81      6949174.99      2918700.75      6949282.55
      2918871.29      6949373.19      2918944.73      6949510.56
      2918938.28      6949713.89      2919087.20      6949735.92
      2919078.82      6949939.41      2919213.23      6949996.57
      2919177.22      6950084.90      2919253.44      6950206.60
      2919278.94      6950409.32      2919343.75      6950442.56
      2919330.73      6950564.96      2919398.43      6950577.98
      2919526.04      6950781.10      2919705.15      6950803.77
      2919759.90      6950763.45      2919882.11      6950832.48
      2919908.98      6951159.31      2920073.37      6951300.89
      2919919.87      6951536.40      2919960.23      6951601.68
      2919927.12      6951715.54      2919975.59      6951890.71

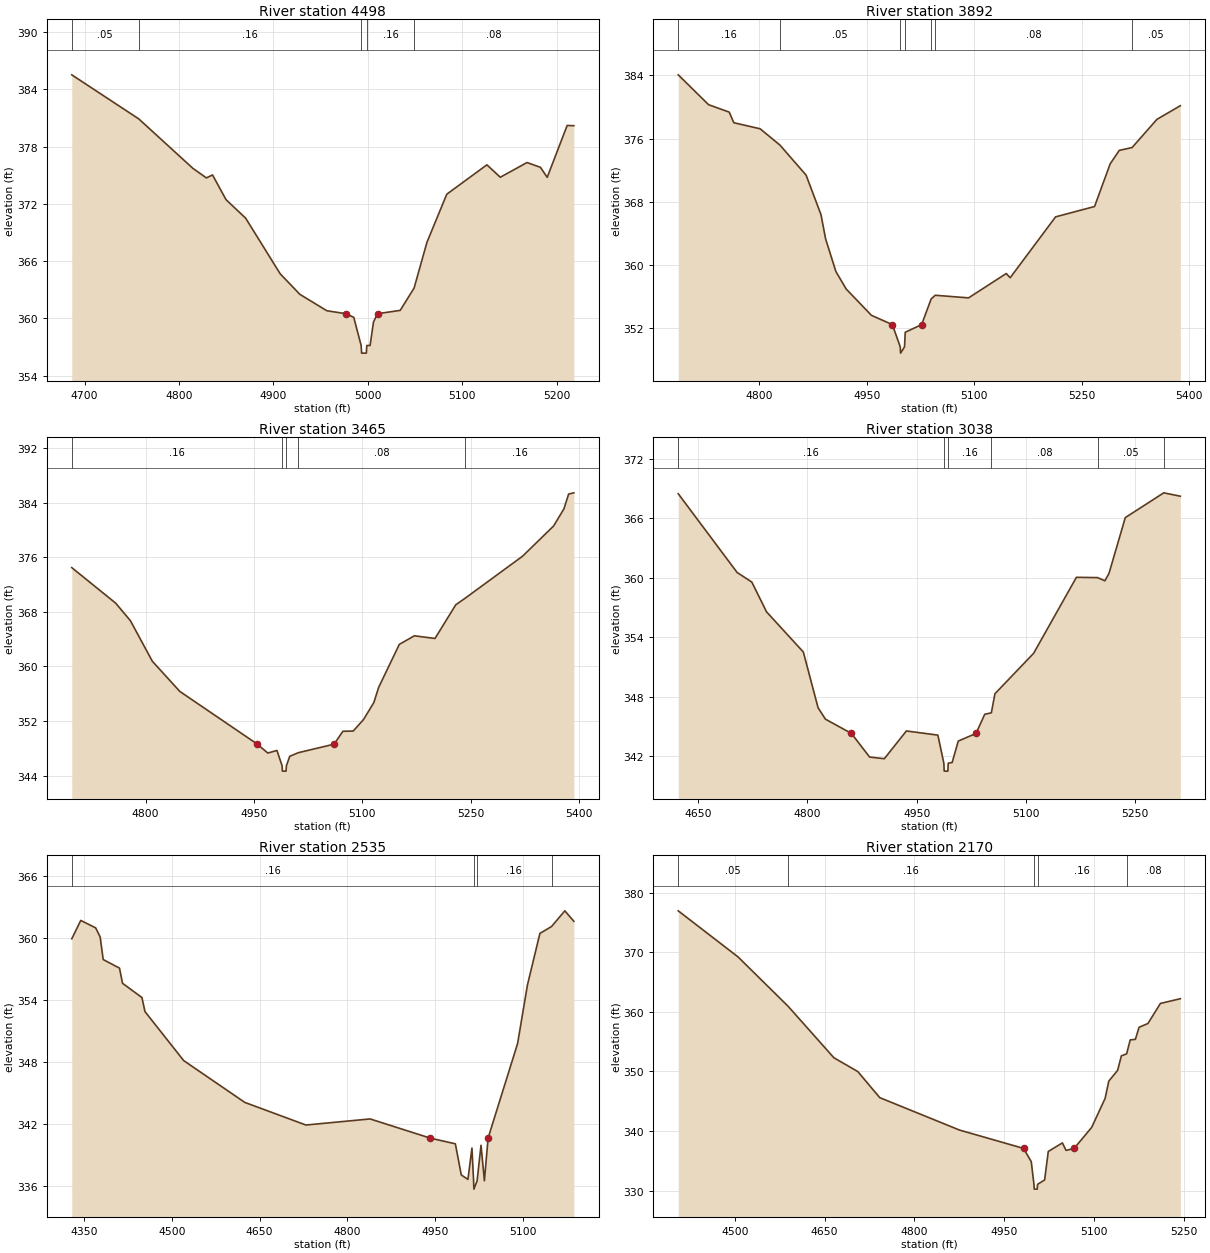
Type RM Length L Ch R = 1,4498,606,606,606
BEGIN DESCRIPTION:
UNT 024 IN DRY CR WATERSHED 7.0
END DESCRIPTION:
XS GIS Cut Line= 3
      2918075.02      6949074.99      2918316.36      6948874.90
      2918475.03      6948724.97
#Sta/Elev= 30
  4686.5  385.52  4757.5  380.90  4814.8  375.72  4829.1  374.72  4835.6  375.03
  4849.9  372.44  4870.7  370.50  4907.2  364.68  4928.1  362.52  4956.7  360.80
  4977.0  360.49  4985.2  360.11  4993.0  357.16  4993.5  356.36  4998.5  356.36
  4999.0  357.16  5002.5  357.16  5006.1  359.63  5010.4  360.49  5034.4  360.84
  5049.1  363.18  5062.7  367.97  5083.7  373.01  5126.2  376.09  5140.4  374.79
  5168.7  376.33  5182.9  375.83  5190.1  374.78  5211.2  380.21  5218.3  380.19
#Mann=5,-1,0
  4686.5    0.05       0  4757.5    0.16       0  4993.0    0.07       0
  4999.0    0.16       0  5049.1    0.08       0
Bank Sta=4977,5010.4
Exp/Cntr=0.3,0.1

Type RM Length L Ch R = 1,3892,427,427,427
BEGIN DESCRIPTION:
UNT 024 IN DRY CR WATERSHED 6.0
END DESCRIPTION:
XS GIS Cut Line= 3
      2918425.02      6949424.97      2918625.00      6949175.00
      2918775.00      6948825.01
#Sta/Elev= 30
  4687.0  384.07  4729.4  380.29  4758.2  379.35  4764.6  378.01  4801.4  377.24
  4829.0  375.18  4865.5  371.38  4886.3  366.38  4892.7  363.33  4907.1  359.18
  4921.5  356.97  4956.7  353.64  4985.9  352.47  4996.9  349.66  4997.4  348.86
  5002.9  349.66  5003.9  351.50  5026.8  352.47  5040.1  355.72  5045.8  356.18
  5092.3  355.85  5144.9  358.93  5150.4  358.40  5213.8  366.10  5268.2  367.41
  5290.0  372.81  5302.7  374.51  5320.6  374.87  5355.3  378.44  5387.9  380.16
#Mann=7,-1,0
  4687.0    0.16       0  4829.0    0.05       0  4996.9   0.035       0
  5002.9    0.05       0  5040.1    0.12       0  5045.8    0.08       0
  5320.6    0.05       0
Bank Sta=4985.9,5026.8
Exp/Cntr=0.3,0.1

Type RM Length L Ch R = 1,3465,427,427,427
BEGIN DESCRIPTION:
UNT 024 IN DRY CR WATERSHED 5.0
END DESCRIPTION:
XS GIS Cut Line= 3
      2918575.00      6949475.00      2918875.00      6949425.00
      2919125.03      6949124.96
#Sta/Elev= 30
  4697.9  374.47  4758.7  369.26  4779.0  366.70  4809.4  360.75  4847.4  356.33
  4954.7  348.60  4969.1  347.30  4981.8  347.68  4988.9  345.45  4989.4  344.65
  4994.4  344.65  4994.9  345.45  4999.5  346.82  5011.3  347.35  5060.9  348.60
  5073.0  350.49  5087.3  350.52  5101.6  352.21  5115.9  354.70  5122.4  356.89
  5151.1  363.22  5171.9  364.48  5200.5  364.09  5229.2  369.02  5242.4  370.00
  5321.6  376.14  5364.6  380.57  5378.9  383.09  5385.4  385.25  5392.6  385.43
#Mann=5,-1,0
  4697.9    0.16       0  4988.9    0.07       0  4994.9    0.16       0
  5011.3    0.08       0  5242.4    0.16       0
Bank Sta=4954.7,5060.9
Exp/Cntr=0.3,0.1

Type RM Length L Ch R = 1,3038,503,503,503
BEGIN DESCRIPTION:
UNT 024 IN DRY CR WATERSHED 4.0
END DESCRIPTION:
XS GIS Cut Line= 3
      2918675.00      6949775.00      2919025.00      6949725.00
      2919175.02      6949424.96
#Sta/Elev= 30
  4622.7  368.45  4703.5  360.51  4723.7  359.54  4743.9  356.54  4794.4  352.49
  4814.6  346.87  4824.7  345.72  4860.4  344.28  4885.3  341.90  4905.5  341.73
  4935.8  344.53  4979.0  344.11  4987.2  341.28  4987.7  340.48  4992.7  340.48
  4993.2  341.28  4998.6  341.35  5007.0  343.51  5031.4  344.28  5043.3  346.21
  5052.4  346.36  5057.3  348.28  5110.4  352.36  5169.1  360.02  5198.2  359.99
  5208.2  359.67  5213.8  360.41  5236.2  366.04  5289.0  368.54  5311.7  368.20
#Mann=6,-1,0
  4622.7    0.16       0  4987.2    0.07       0  4993.2    0.16       0
  5052.4    0.08       0  5198.2    0.05       0  5289.0    0.16       0
Bank Sta=4860.4,5031.4
Exp/Cntr=0.3,0.1

Type RM Length L Ch R = 1,2535,365,365,365
BEGIN DESCRIPTION:
UNT 024 IN DRY CR WATERSHED 3.0
END DESCRIPTION:
XS GIS Cut Line= 3
      2918545.86      6949855.40      2919189.41      6950047.46
      2919349.96      6949950.03
#Sta/Elev= 30
  4328.4  359.93  4343.8  361.71  4369.3  360.99  4377.0  360.11  4382.2  357.92
  4410.1  357.09  4415.3  355.62  4448.5  354.24  4453.7  352.88  4520.0  348.13
  4624.6  344.08  4729.2  341.89  4839.1  342.48  4942.1  340.62  4985.0  340.07
  4995.1  337.06  5006.5  336.62  5013.4  339.66  5016.2  336.48  5016.7  335.68
  5022.2  336.48  5028.9  339.93  5034.7  336.49  5041.0  340.62  5091.5  349.78
  5108.4  355.46  5129.7  360.45  5149.6  361.12  5172.4  362.64  5187.8  361.63
#Mann=4,-1,0
  4328.4    0.16       0  5016.2    0.07       0  5022.2    0.16       0
  5149.6    0.08       0
Bank Sta=4942.1,5041
Exp/Cntr=0.3,0.1

Type RM Length L Ch R = 1,2170,296,296,296
BEGIN DESCRIPTION:
UNT 024 IN DRY CR WATERSHED 2.0
END DESCRIPTION:
XS GIS Cut Line= 3
      2918675.01      6950375.00      2919269.55      6950383.78
      2919409.76      6950183.85
#Sta/Elev= 30
  4405.4  376.95  4505.4  369.21  4589.1  360.92  4665.4  352.30  4705.4  349.98
  4742.1  345.60  4875.4  340.16  4982.4  337.08  4995.2  334.85  4999.7  331.05
  5000.2  330.25  5005.2  330.25  5005.7  331.05  5017.5  331.79  5023.6  336.57
  5047.2  338.01  5053.3  336.75  5066.8  337.08  5096.2  340.62  5118.6  345.49
  5124.7  348.37  5139.5  350.19  5145.7  352.61  5154.5  352.95  5160.5  355.29
  5169.2  355.39  5175.3  357.41  5190.1  358.04  5211.0  361.41  5244.2  362.20
#Mann=5,-1,0
  4405.4    0.05       0  4589.1    0.16       0  4999.7    0.07       0
  5005.7    0.16       0  5154.5    0.08       0
Bank Sta=4982.4,5066.8
Exp/Cntr=0.3,0.1

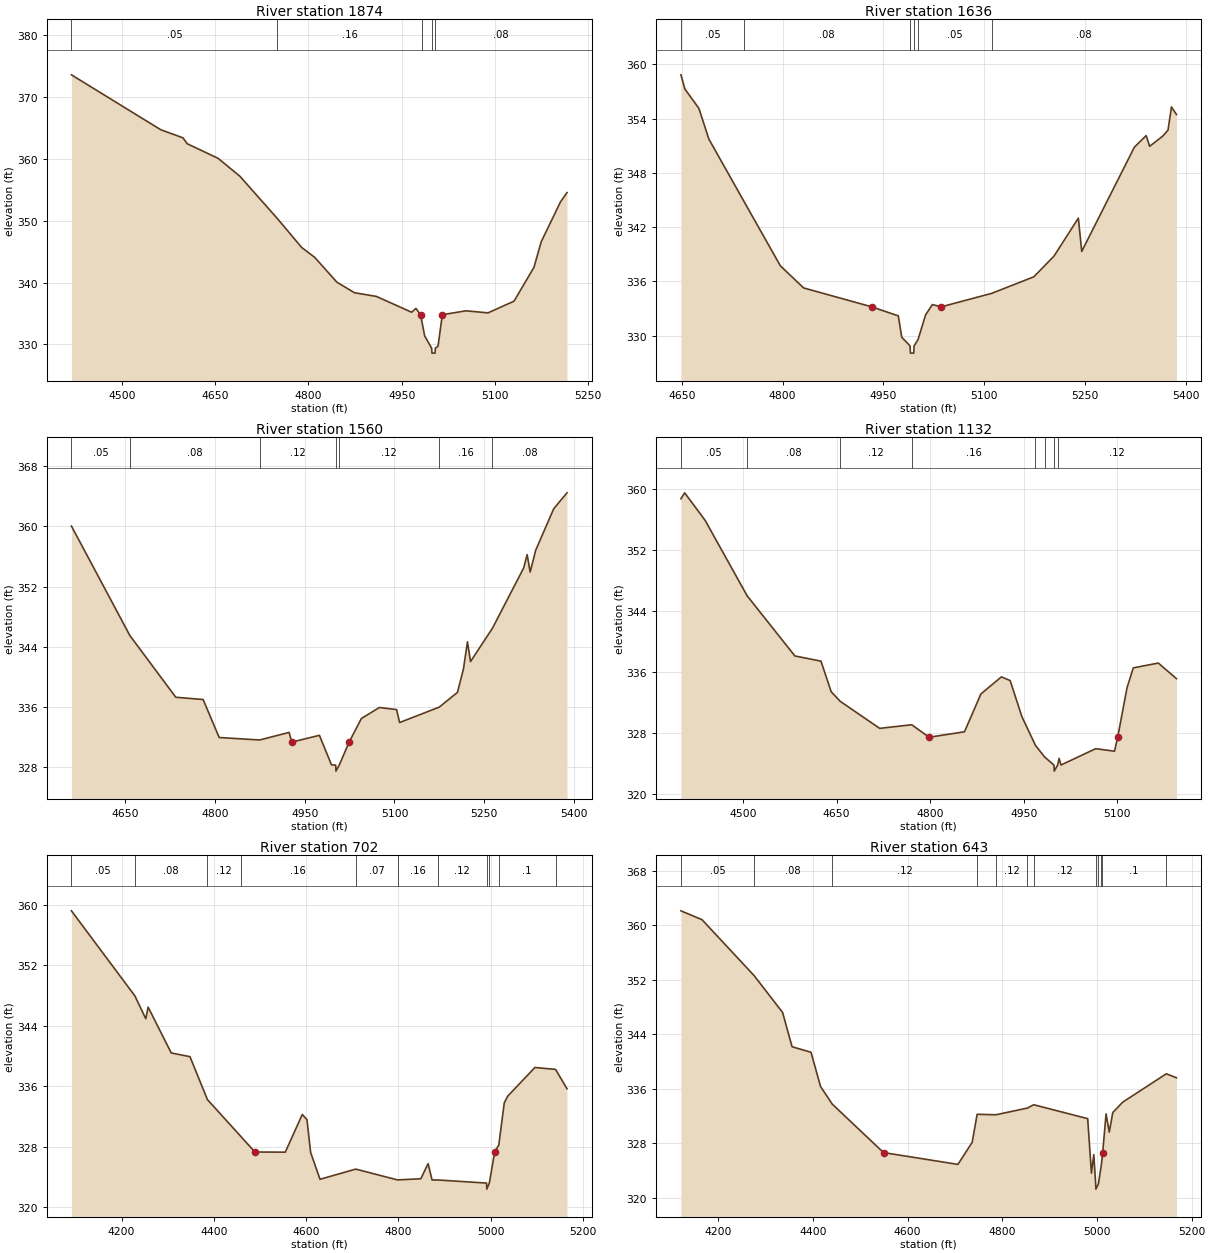
Type RM Length L Ch R = 1,1874,238,238,238
BEGIN DESCRIPTION:
Mapping XS 8e5ed716
END DESCRIPTION:
XS GIS Cut Line= 3
      2918972.27      6950975.52      2919423.64      6950551.93
      2919486.14      6950385.26
#Sta/Elev= 30
  4418.8  373.59  4562.5  364.71  4598.1  363.41  4605.0  362.45  4654.7  360.09
  4689.9  357.18  4750.2  350.33  4789.1  345.68  4810.1  344.08  4845.7  340.07
  4874.1  338.36  4909.2  337.77  4965.9  335.21  4972.8  335.83  4980.3  334.81
  4983.2  333.31  4986.9  331.39  4998.1  329.40  4998.6  328.60  5003.6  328.60
  5004.1  329.40  5008.4  329.72  5015.3  334.81  5053.2  335.44  5088.8  335.11
  5130.6  337.00  5162.7  342.47  5174.3  346.59  5205.4  353.06  5215.8  354.55
#Mann=5,-1,0
  4418.8    0.05       0  4750.2    0.16       0  4983.2    0.08       0
  4998.1    0.07       0  5004.1    0.08       0
Bank Sta=4980.3,5015.3
Exp/Cntr=0.3,0.1

Type RM Length L Ch R = 1,1636,76,76,76
BEGIN DESCRIPTION:
Mapping XS dbf20245
END DESCRIPTION:
XS GIS Cut Line= 5
      2919357.69      6951055.38      2919500.03      6950951.23
      2919538.22      6950663.04      2919524.33      6950451.23
      2919506.96      6950395.63
#Sta/Elev= 30
  4648.7  358.84  4654.7  357.26  4675.5  355.13  4690.2  351.75  4742.2  344.89
  4796.8  337.71  4831.4  335.27  4932.7  333.18  4972.3  332.18  4977.4  329.82
  4989.8  328.86  4990.3  328.06  4995.3  328.06  4995.8  328.86  5001.7  329.57
  5012.9  332.29  5023.0  333.43  5036.2  333.18  5111.3  334.67  5174.0  336.50
  5204.0  338.79  5240.3  342.99  5245.3  339.31  5323.7  350.84  5341.2  352.12
  5346.4  350.93  5366.0  352.07  5373.7  352.72  5378.9  355.29  5386.3  354.45
#Mann=6,-1,0
  4648.7    0.05       0  4742.2    0.08       0  4989.8    0.07       0
  4995.8    0.08       0  5001.7    0.05       0  5111.3    0.08       0
Bank Sta=4932.7,5036.2
Exp/Cntr=0.3,0.1

Type RM Length L Ch R = 1,1560,428,428,428
BEGIN DESCRIPTION:
Mapping XS 01d2359c
END DESCRIPTION:
XS GIS Cut Line= 4
      2919343.77      6951058.87      2919583.36      6950989.43
      2919604.20      6950617.90      2919583.36      6950413.02
#Sta/Elev= 30
  4560.6  360.05  4658.3  345.48  4734.9  337.29  4780.5  336.99  4807.3  331.94
  4874.9  331.61  4924.1  332.62  4928.5  331.33  4974.7  332.23  4994.8  328.31
  5001.8  328.27  5002.3  327.47  5007.8  328.27  5024.3  331.33  5044.8  334.47
  5074.9  335.93  5103.6  335.65  5108.6  333.93  5174.8  335.98  5205.2  337.94
  5215.2  341.05  5221.9  344.66  5227.0  342.03  5263.5  346.45  5315.7  354.47
  5321.6  356.25  5326.6  353.94  5335.8  356.83  5366.0  362.36  5388.1  364.47
#Mann=7,-1,0
  4560.6    0.05       0  4658.3    0.08       0  4874.9    0.12       0
  5001.8    0.07       0  5007.8    0.12       0  5174.8    0.16       0
  5263.5    0.08       0
Bank Sta=4928.5,5024.3
Exp/Cntr=0.3,0.1

Type RM Length L Ch R = 1,1132,430,430,430
BEGIN DESCRIPTION:
Mapping XS 4238fca7
END DESCRIPTION:
XS GIS Cut Line= 3
      2919340.28      6951100.55      2919920.17      6950923.46
      2919906.28      6950736.00
#Sta/Elev= 30
  4400.5  358.69  4406.5  359.47  4439.3  355.87  4506.8  345.97  4583.2  338.11
  4625.0  337.43  4641.4  333.42  4656.0  332.16  4719.1  328.63  4770.5  329.10
  4798.4  327.47  4855.0  328.18  4881.4  333.14  4914.2  335.37  4928.2  334.89
  4947.1  330.16  4968.8  326.40  4983.4  324.89  4998.4  323.83  4998.9  323.03
  5004.4  323.83  5006.7  324.70  5009.7  323.83  5065.4  325.97  5095.5  325.64
  5100.6  327.47  5115.6  333.96  5125.6  336.55  5165.7  337.18  5194.8  335.14
#Mann=8,-1,0
  4400.5    0.05       0  4506.8    0.08       0  4656.0    0.12       0
  4770.5    0.16       0  4968.8    0.07       0  4983.4    0.12       0
  4998.4    0.07       0  5004.4    0.12       0
Bank Sta=4798.4,5100.6
Exp/Cntr=0.3,0.1

Type RM Length L Ch R = 1,702,59,59,59
BEGIN DESCRIPTION:
Mapping XS 0e257415
END DESCRIPTION:
XS GIS Cut Line= 6
      2919291.68      6951176.93      2919805.58      6951090.12
      2919927.11      6951222.07      2919927.11      6951291.51
      2920010.45      6951298.46      2920194.48      6951187.34
#Sta/Elev= 30
  4091.3  359.21  4228.9  347.95  4252.4  344.94  4257.5  346.47  4307.6  340.41
  4348.2  339.92  4386.0  334.24  4458.4  329.37  4488.9  327.31  4554.7  327.29
  4591.6  332.28  4601.7  331.59  4609.7  327.24  4630.0  323.70  4707.3  325.05
  4798.0  323.62  4848.4  323.77  4864.2  325.77  4872.8  323.61  4885.5  323.61
  4990.9  323.20  4991.4  322.40  4996.9  323.20  5008.5  327.31  5017.4  328.23
  5029.3  333.81  5036.8  334.70  5095.7  338.49  5140.4  338.24  5165.2  335.68
#Mann=11,-1,0
  4091.3    0.05       0  4228.9    0.08       0  4386.0    0.12       0
  4458.4    0.16       0  4707.3    0.07       0  4798.0    0.16       0
  4885.5    0.12       0  4990.9    0.07       0  4996.9    0.12       0
  5017.4     0.1       0  5140.4    0.12       0
Bank Sta=4488.9,5008.5
Exp/Cntr=0.3,0.1

Type RM Length L Ch R = 1,643,45,45,45
BEGIN DESCRIPTION:
Mapping XS a38a15f3
END DESCRIPTION:
XS GIS Cut Line= 5
      2919260.43      6951218.60      2919892.39      6951246.37
      2919906.28      6951333.18      2920069.47      6951329.71
      2920189.77      6951219.73
#Sta/Elev= 30
  4121.1  362.13  4165.7  360.83  4275.8  352.62  4335.9  347.22  4355.9  342.19
  4395.9  341.38  4416.0  336.37  4440.8  333.77  4549.1  326.66  4706.2  324.93
  4736.3  328.16  4746.8  332.28  4786.7  332.21  4852.8  333.19  4866.3  333.68
  4980.3  331.64  4988.2  323.64  4993.2  326.37  4997.1  322.10  4997.6  321.30
  5003.1  322.10  5009.3  324.95  5010.5  325.71  5012.0  326.66  5019.1  332.34
  5025.9  329.67  5033.3  332.54  5054.3  334.06  5146.4  338.22  5167.8  337.64
#Mann=12,-1,0
  4121.1    0.05       0  4275.8    0.08       0  4440.8    0.12       0
  4746.8    0.16       0  4786.7    0.12       0  4852.8    0.16       0
  4866.3    0.12       0  4997.1    0.07       0  5003.1    0.12       0
  5009.3    0.16       0  5010.5     0.1       0  5146.4    0.12       0
Bank Sta=4549.1,5012
Exp/Cntr=0.3,0.1

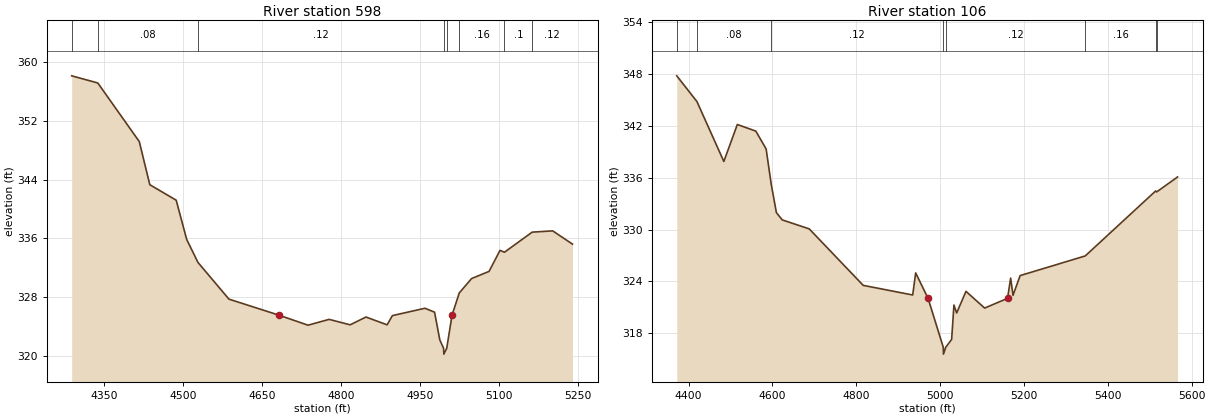
Type RM Length L Ch R = 1,598,492,492,492
BEGIN DESCRIPTION:
Mapping XS 494a2c10
END DESCRIPTION:
XS GIS Cut Line= 4
      2919336.85      6951392.21      2920003.50      6951374.85
      2920104.20      6951367.90      2920222.26      6951229.01
#Sta/Elev= 30
  4289.0  358.09  4338.5  357.12  4417.2  349.16  4437.2  343.30  4487.2  341.20
  4507.2  335.86  4528.6  332.74  4587.3  327.76  4681.8  325.59  4737.3  324.22
  4777.3  325.01  4817.3  324.27  4847.3  325.33  4887.4  324.27  4897.4  325.52
  4959.1  326.52  4977.4  325.99  4987.4  322.21  4994.5  321.09  4995.0  320.29
  5000.5  321.09  5010.6  325.59  5024.3  328.60  5047.6  330.55  5080.8  331.53
  5101.6  334.38  5110.0  334.13  5162.6  336.86  5201.6  337.03  5239.1  335.23
#Mann=8,-1,0
  4289.0    0.05       0  4338.5    0.08       0  4528.6    0.12       0
  4994.5    0.07       0  5000.5    0.12       0  5024.3    0.16       0
  5110.0     0.1       0  5162.6    0.12       0
Bank Sta=4681.8,5010.6
Exp/Cntr=0.3,0.1

Type RM Length L Ch R = 1,106,0,0,0
BEGIN DESCRIPTION:
UNT 024 IN DRY CR WATERSHED 1.0
END DESCRIPTION:
XS GIS Cut Line= 3
      2919360.31      6951563.23      2919945.96      6951790.50
      2920193.60      6951281.11
#Sta/Elev= 30
  4371.8  347.75  4419.9  344.78  4484.1  337.86  4516.3  342.13  4560.5  341.36
  4585.0  339.30  4597.1  335.24  4609.5  331.95  4623.5  331.11  4687.9  330.07
  4816.6  323.55  4934.6  322.44  4941.7  324.99  4971.3  322.05  5007.5  316.41
  5008.0  315.61  5013.5  316.41  5027.5  317.31  5033.0  321.28  5039.5  320.36
  5061.7  322.86  5106.2  320.93  5160.8  322.05  5168.3  324.39  5173.9  322.40
  5190.9  324.68  5346.2  326.95  5514.1  334.45  5516.6  334.34  5566.4  336.07
#Mann=8,-1,0
  4371.8    0.05       0  4419.9    0.08       0  4597.1    0.12       0
  5007.5    0.07       0  5013.5    0.12       0  5346.2    0.16       0
  5514.1     0.1       0  5516.6    0.12       0
Bank Sta=4971.3,5160.8
Exp/Cntr=0.3,0.1

Chan Stop Cuts=-1