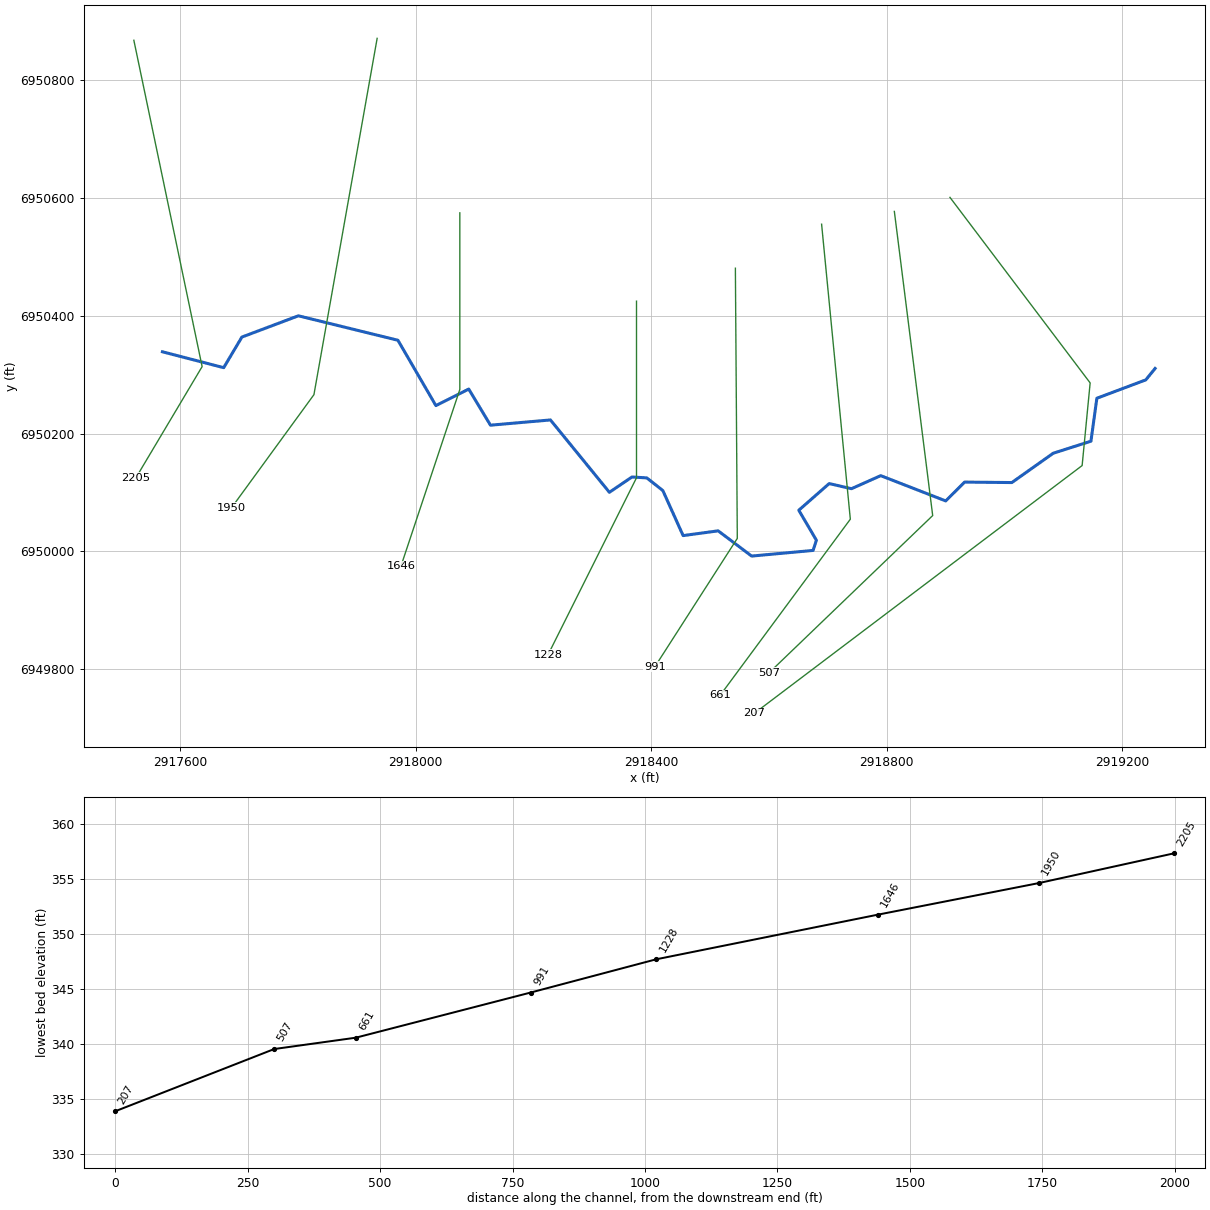
--- UNT 025 IN DRY CR WATERSHED.prj (project) ---

Proj Title=UNT 025 IN DRY CR WATERSHED Base Level Engineering
Current Plan=p01
Default Exp/Contr=0.3,0.1
English Units
Geom File=g01
Flow File=f01
Plan File=p01
BEGIN DESCRIPTION:
UNT 025 IN DRY CR WATERSHED
END DESCRIPTION:

--- UNT 025 IN DRY CR WATERSHED.p01 (plan) ---

Plan Title=Multiple Run
Short Identifier=Multiple
Geom File=g01
Flow File=f01
Subcritical Flow
K Sum by GR= 0
Std Step Tol= 0.01
Critical Tol= 0.01
Num of Std Step Trials= 20
Max Error Tol= 0.3
Flow Tol Ratio= 0.001
Split Flow NTrial= 30
Split Flow Tol= 0.02
Split Flow Ratio= 0.02
Log Output Level= 0
Friction Slope Method= 1
Unsteady Friction Slope Method= 2
Unsteady Bridges Friction Slope Method= 1
Parabolic Critical Depth
Global Vel Dist=  1 , 1 , 1
Global Log Level= 0
CheckData=True
Encroach Param= -1, 0, 0, 0
BEGIN DESCRIPTION:
Multiple Run
END DESCRIPTION:

--- UNT 025 IN DRY CR WATERSHED.f01 (steady flow) ---

Flow Title=Multiple
Number of Profiles=7
Profile Names=10-year,25-year,50-year,1pct_min,100-year,1pct_plu,500-year
River Rch & RM= UNT 025 IN DRY C,Reach-1,2205
     315     408     481     283     564    1125     776
Boundary for River Rch & Prof#=UNT 025 IN DRY C,Reach-1,1
Up Type=0
Dn Type=3
Dn Slope=0.005
Boundary for River Rch & Prof#=UNT 025 IN DRY C,Reach-1,2
Up Type=0
Dn Type=3
Dn Slope=0.005
Boundary for River Rch & Prof#=UNT 025 IN DRY C,Reach-1,3
Up Type=0
Dn Type=3
Dn Slope=0.005
Boundary for River Rch & Prof#=UNT 025 IN DRY C,Reach-1,4
Up Type=0
Dn Type=3
Dn Slope=0.005
Boundary for River Rch & Prof#=UNT 025 IN DRY C,Reach-1,5
Up Type=0
Dn Type=3
Dn Slope=0.005
Boundary for River Rch & Prof#=UNT 025 IN DRY C,Reach-1,6
Up Type=0
Dn Type=3
Dn Slope=0.005
Boundary for River Rch & Prof#=UNT 025 IN DRY C,Reach-1,7
Up Type=0
Dn Type=3
Dn Slope=0.005

--- UNT 025 IN DRY CR WATERSHED.g01 (geometry) ---

Geom Title=Existing Conditions

River Reach=UNT 025 IN DRY C,Reach-1
Reach XY= 30
      2917569.99      6950339.01      2917674.04      6950312.01
      2917704.93      6950363.97      2917800.88      6950400.10
      2917969.88      6950358.57      2918034.36      6950247.59
      2918090.11      6950275.69      2918127.03      6950214.36
      2918228.89      6950223.26      2918328.95      6950100.37
      2918367.29      6950126.38      2918392.52      6950124.85
      2918419.72      6950103.35      2918454.16      6950026.89
      2918513.63      6950034.96      2918570.51      6949992.12
      2918674.87      6950001.71      2918680.44      6950019.01
      2918650.60      6950069.96      2918702.18      6950115.21
      2918740.01      6950106.51      2918789.68      6950128.67
      2918900.04      6950085.76      2918932.11      6950117.71
      2919012.33      6950116.94      2919082.64      6950166.75
      2919146.66      6950187.16      2919156.67      6950260.08
      2919239.81      6950291.31      2919255.59      6950310.71

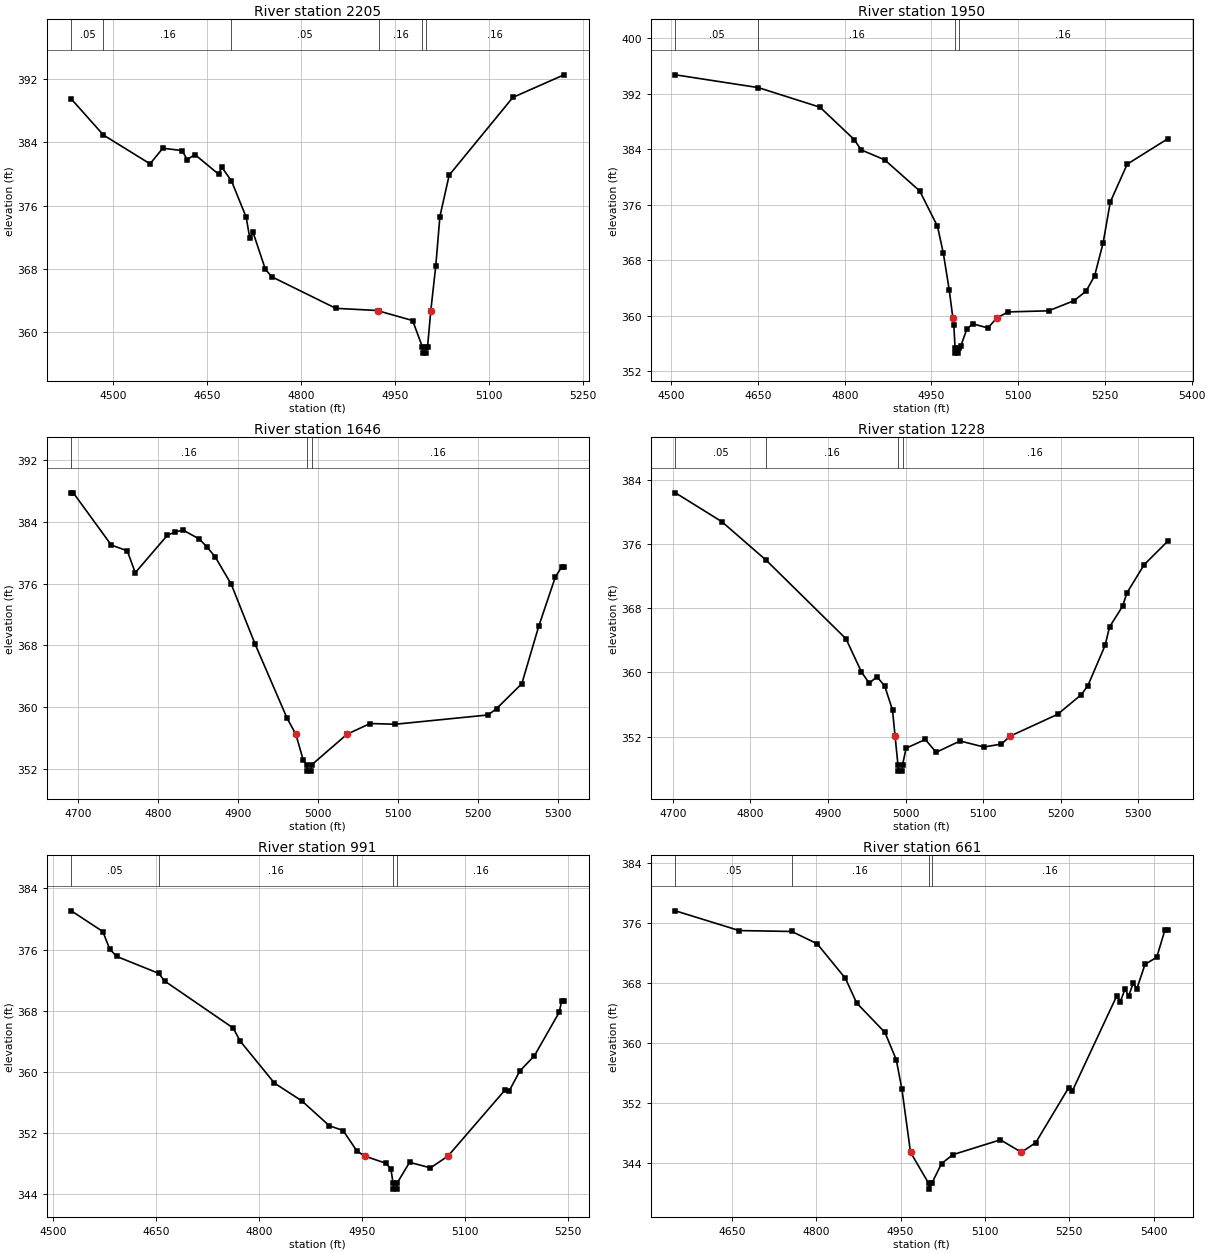
Type RM Length L Ch R = 1,2205,255,255,255
BEGIN DESCRIPTION:
UNT 025 IN DRY CR WATERSHED 4.0
END DESCRIPTION:
XS GIS Cut Line= 3
      2917521.49      6950867.95      2917637.42      6950313.85
      2917524.99      6950124.98
#Sta/Elev= 30
  4433.9  389.51  4485.0  384.95  4559.5  381.29  4579.9  383.27  4610.6  382.97
  4618.8  381.83  4631.0  382.47  4668.8  379.98  4673.9  380.86  4689.4  379.13
  4712.8  374.54  4718.7  371.84  4723.9  372.59  4743.4  367.94  4753.6  366.98
  4855.8  362.98  4922.5  362.70  4924.3  362.64  4978.4  361.43  4993.9  358.10
  4994.4  357.30  4999.4  357.30  4999.9  358.10  5002.2  358.10  5007.4  362.70
  5015.3  368.34  5021.9  374.61  5036.7  379.86  5138.3  389.71  5219.8  392.57
#Mann=6,-1,0
  4433.9    0.05       0  4485.0    0.16       0  4689.4    0.05       0
  4924.3    0.16       0  4993.9    0.07       0  4999.9    0.16       0
Bank Sta=4922.5,5007.4
Exp/Cntr=0.3,0.1

Type RM Length L Ch R = 1,1950,304,304,304
BEGIN DESCRIPTION:
Mapping XS a20a849c
END DESCRIPTION:
XS GIS Cut Line= 3
      2917934.61      6950871.24      2917827.26      6950266.16
      2917687.40      6950074.25
#Sta/Elev= 30
  4507.2  394.72  4650.5  392.88  4757.3  390.05  4816.5  385.38  4828.4  383.90
  4869.0  382.47  4929.6  377.99  4960.4  372.89  4970.6  368.98  4980.7  363.73
  4987.1  359.63  4988.7  358.60  4990.8  355.40  4991.3  354.60  4996.3  354.60
  4996.8  355.40  5001.0  355.68  5011.2  358.08  5021.4  358.82  5047.8  358.23
  5062.5  359.63  5082.3  360.54  5152.6  360.70  5196.6  362.16  5217.5  363.54
  5232.1  365.73  5246.8  370.46  5259.3  376.39  5288.5  381.84  5359.2  385.53
#Mann=4,-1,0
  4507.2    0.05       0  4650.5    0.16       0  4990.8    0.07       0
  4996.8    0.16       0
Bank Sta=4987.1,5062.5
Exp/Cntr=0.3,0.1

Type RM Length L Ch R = 1,1646,418,418,418
BEGIN DESCRIPTION:
UNT 025 IN DRY CR WATERSHED 3.0
END DESCRIPTION:
XS GIS Cut Line= 3
      2918075.00      6950574.95      2918075.00      6950275.00
      2917974.99      6949974.98
#Sta/Elev= 30
  4691.0  387.75  4693.5  387.75  4741.0  380.99  4761.0  380.25  4771.0  377.41
  4811.0  382.24  4821.0  382.70  4831.0  382.91  4851.0  381.78  4861.0  380.71
  4871.0  379.45  4891.0  375.93  4921.0  368.14  4961.0  358.55  4971.9  356.50
  4981.0  353.18  4985.5  352.53  4986.0  351.73  4991.0  351.73  4991.5  352.53
  5035.8  356.50  5064.7  357.89  5096.4  357.80  5212.3  359.00  5222.9  359.82
  5254.5  363.05  5275.6  370.47  5296.6  376.91  5304.5  378.16  5307.2  378.16
#Mann=3,-1,0
  4691.0    0.16       0  4985.5    0.07       0  4991.5    0.16       0
Bank Sta=4971.9,5035.8
Exp/Cntr=0.3,0.1

Type RM Length L Ch R = 1,1228,237,237,237
BEGIN DESCRIPTION:
UNT 025 IN DRY CR WATERSHED 2.0
END DESCRIPTION:
XS GIS Cut Line= 3
      2918375.00      6950424.97      2918375.00      6950125.00
      2918224.99      6949824.98
#Sta/Elev= 30
  4703.2  382.40  4763.2  378.79  4820.5  373.97  4923.2  364.19  4943.2  360.04
  4953.2  358.65  4963.2  359.46  4973.2  358.28  4983.2  355.30  4986.5  352.06
  4990.2  348.48  4990.7  347.68  4995.7  347.68  4996.2  348.48  5000.7  350.54
  5025.5  351.63  5039.5  350.03  5070.3  351.44  5101.0  350.69  5123.4  351.05
  5135.3  352.06  5196.0  354.76  5226.8  357.23  5235.2  358.35  5257.5  363.40
  5263.1  365.67  5279.9  368.24  5285.5  369.91  5307.8  373.44  5338.6  376.41
#Mann=4,-1,0
  4703.2    0.05       0  4820.5    0.16       0  4990.2    0.07       0
  4996.2    0.16       0
Bank Sta=4986.5,5135.3
Exp/Cntr=0.3,0.1

Type RM Length L Ch R = 1,991,330,330,330
BEGIN DESCRIPTION:
Mapping XS f4baf2a2
END DESCRIPTION:
XS GIS Cut Line= 3
      2918542.90      6950480.90      2918546.16      6950022.19
      2918406.27      6949804.24
#Sta/Elev= 30
  4526.1  381.07  4572.0  378.36  4582.0  376.08  4592.0  375.11  4653.4  372.89
  4662.0  371.89  4762.0  365.73  4772.0  364.04  4822.0  358.53  4862.0  356.20
  4902.0  352.95  4922.0  352.33  4942.0  349.67  4953.3  348.99  4984.8  348.03
  4991.8  347.24  4994.8  345.46  4995.3  344.66  5000.3  344.66  5000.8  345.46
  5018.9  348.17  5049.3  347.44  5074.9  348.99  5158.3  357.67  5164.3  357.55
  5179.5  360.12  5200.6  362.09  5236.9  367.80  5240.4  369.29  5243.8  369.29
#Mann=4,-1,0
  4526.1    0.05       0  4653.4    0.16       0  4994.8    0.07       0
  5000.8    0.16       0
Bank Sta=4953.3,5074.9
Exp/Cntr=0.3,0.1

Type RM Length L Ch R = 1,661,154,154,154
BEGIN DESCRIPTION:
Mapping XS 06bcc8e6
END DESCRIPTION:
XS GIS Cut Line= 3
      2918689.29      6950555.66      2918738.08      6950054.72
      2918516.85      6949755.42
#Sta/Elev= 30
  4549.9  377.64  4663.3  375.01  4756.7  374.89  4801.8  373.25  4852.0  368.64
  4872.1  365.35  4922.3  361.43  4942.4  357.80  4952.5  353.84  4967.7  345.47
  4999.7  341.36  5000.2  340.56  5005.7  341.36  5022.8  343.96  5042.9  345.15
  5127.5  347.13  5164.7  345.47  5190.2  346.75  5248.7  354.07  5255.0  353.59
  5334.3  366.32  5340.5  365.54  5349.0  367.23  5355.2  366.29  5363.6  368.02
  5369.8  367.24  5384.4  370.50  5405.3  371.46  5419.9  375.11  5425.4  375.07
#Mann=4,-1,0
  4549.9    0.05       0  4756.7    0.16       0  4999.7    0.07       0
  5005.7    0.16       0
Bank Sta=4967.7,5164.7
Exp/Cntr=0.3,0.1

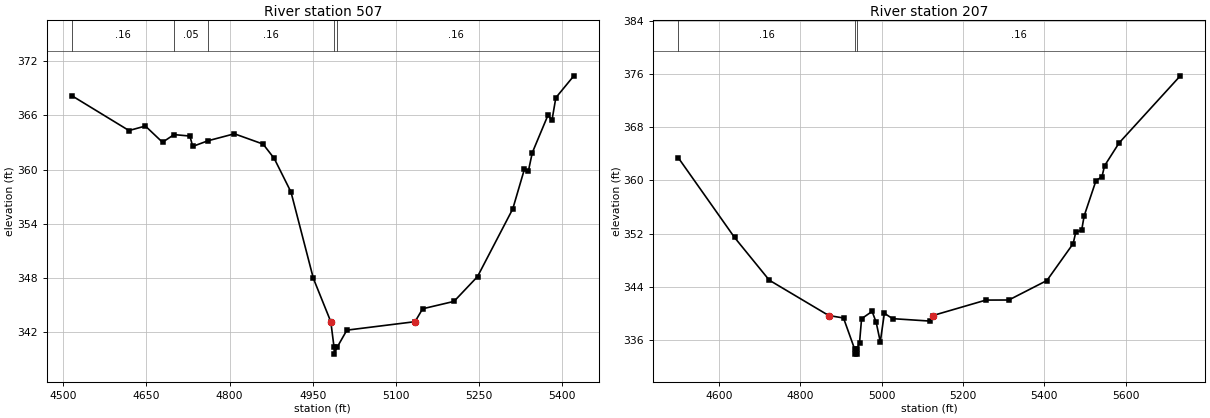
Type RM Length L Ch R = 1,507,300,300,300
BEGIN DESCRIPTION:
Mapping XS c26abcbb
END DESCRIPTION:
XS GIS Cut Line= 3
      2918812.83      6950577.37      2918877.93      6950060.90
      2918600.15      6949793.97
#Sta/Elev= 30
  4515.3  368.20  4618.5  364.33  4648.1  364.83  4679.0  363.03  4699.8  363.88
  4728.4  363.72  4733.5  362.57  4761.2  363.20  4808.7  363.97  4860.4  362.83
  4880.5  361.24  4910.8  357.51  4951.1  347.94  4982.6  343.13  4988.4  340.33
  4988.9  339.53  4994.4  340.33  5011.6  342.19  5134.6  343.13  5148.3  344.56
  5204.9  345.38  5247.3  348.13  5310.9  355.64  5332.0  360.06  5339.2  359.87
  5346.1  361.87  5374.4  366.03  5381.6  365.45  5388.6  367.97  5421.1  370.40
#Mann=5,-1,0
  4515.3    0.16       0  4699.8    0.05       0  4761.2    0.16       0
  4988.4    0.07       0  4994.4    0.16       0
Bank Sta=4982.6,5134.6
Exp/Cntr=0.3,0.1

Type RM Length L Ch R = 1,207,0,0,0
BEGIN DESCRIPTION:
UNT 025 IN DRY CR WATERSHED 1.0
END DESCRIPTION:
XS GIS Cut Line= 4
      2918907.24      6950601.20      2919145.29      6950286.16
      2919131.68      6950145.81      2918575.01      6949725.01
#Sta/Elev= 30
  4500.5  363.39  4638.8  351.41  4724.2  344.99  4870.3  339.68  4906.6  339.31
  4933.7  334.68  4934.2  333.88  4939.2  333.88  4939.7  334.68  4946.0  335.59
  4951.0  339.20  4976.9  340.30  4986.9  338.65  4997.0  335.72  5007.0  340.02
  5027.1  339.21  5120.0  338.84  5126.3  339.68  5256.6  342.00  5312.8  342.01
  5406.4  344.94  5470.9  350.48  5477.2  352.18  5491.8  352.51  5498.0  354.66
  5527.1  359.96  5541.7  360.53  5548.0  362.17  5583.8  365.61  5734.2  375.69
#Mann=3,-1,0
  4500.5    0.16       0  4933.7    0.07       0  4939.7    0.16       0
Bank Sta=4870.3,5126.3
Exp/Cntr=0.3,0.1

Chan Stop Cuts=-1