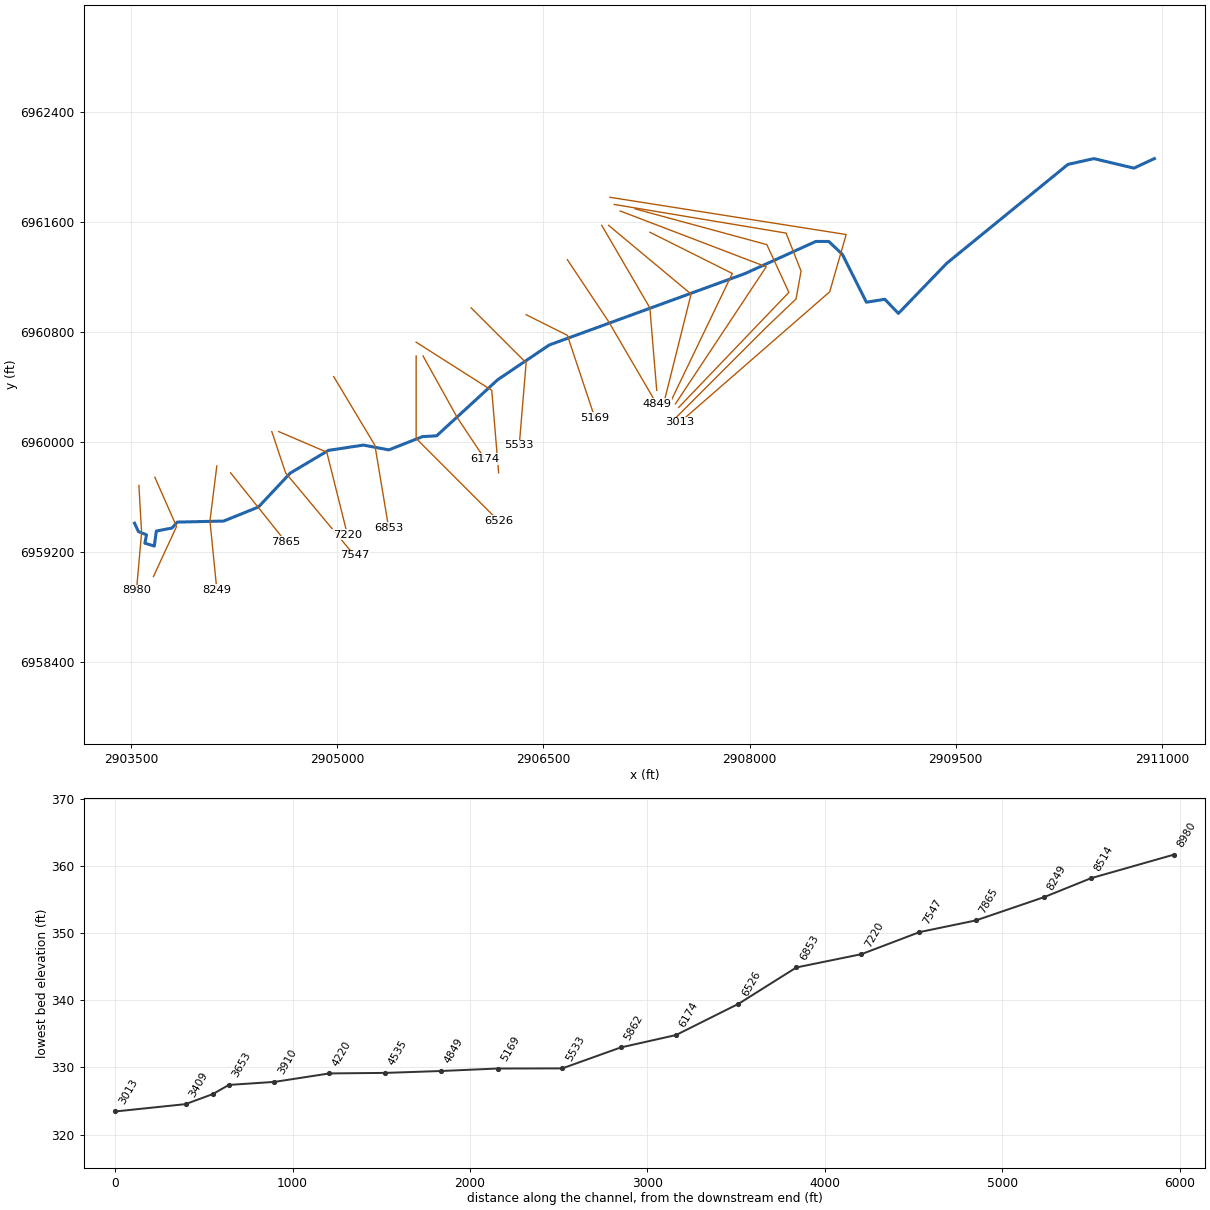
--- UNT 026 IN DRY CR WATERSHED.prj (project) ---

Proj Title=UNT 026 IN DRY CR WATERSHED Base Level Engineering
Current Plan=p01
Default Exp/Contr=0.3,0.1
English Units
Geom File=g01
Flow File=f01
Plan File=p01
Y Axis Title=Elevation
X Axis Title(PF)=Main Channel Distance
X Axis Title(XS)=Station
BEGIN DESCRIPTION:
UNT 026 IN DRY CR WATERSHED
END DESCRIPTION:
DSS Export Rating Curves= 0
DSS Export Rating Curve Sorted= 0
DSS Export Volume Flow Curves= 0
DXF OffsetX= 0
DXF OffsetY= 0
DXF ScaleX= 1
DXF ScaleY= 10

--- UNT 026 IN DRY CR WATERSHED.p01 (plan) ---

Plan Title=Multiple Run
Short Identifier=Multiple
Geom File=g01
Flow File=f01
Subcritical Flow
K Sum by GR= 0
Std Step Tol= 0.01
Critical Tol= 0.01
Num of Std Step Trials= 20
Max Error Tol= 0.3
Flow Tol Ratio= 0.001
Split Flow NTrial= 30
Split Flow Tol= 0.02
Split Flow Ratio= 0.02
Log Output Level= 0
Friction Slope Method= 1
Unsteady Friction Slope Method= 2
Unsteady Bridges Friction Slope Method= 1
Parabolic Critical Depth
Global Vel Dist=  1 , 1 , 1
Global Log Level= 0
CheckData=True
Encroach Param= -1, 0, 0, 0
BEGIN DESCRIPTION:
Multiple Run
END DESCRIPTION:

--- UNT 026 IN DRY CR WATERSHED.f01 (steady flow) ---

Flow Title=Multiple
Number of Profiles=7
Profile Names=10-year,25-year,50-year,1pct_min,100-year,1pct_plu,500-year
River Rch & RM= UNT 026 IN DRY C,Reach-1,8980
     541     723     870     521    1040    2075    1487
River Rch & RM= UNT 026 IN DRY C,Reach-1,3910
     791    1078    1314     796    1588    3169    2324
Boundary for River Rch & Prof#=UNT 026 IN DRY C,Reach-1,1
Up Type=0
Dn Type=3
Dn Slope=0.005
Boundary for River Rch & Prof#=UNT 026 IN DRY C,Reach-1,2
Up Type=0
Dn Type=3
Dn Slope=0.005
Boundary for River Rch & Prof#=UNT 026 IN DRY C,Reach-1,3
Up Type=0
Dn Type=3
Dn Slope=0.005
Boundary for River Rch & Prof#=UNT 026 IN DRY C,Reach-1,4
Up Type=0
Dn Type=3
Dn Slope=0.005
Boundary for River Rch & Prof#=UNT 026 IN DRY C,Reach-1,5
Up Type=0
Dn Type=3
Dn Slope=0.005
Boundary for River Rch & Prof#=UNT 026 IN DRY C,Reach-1,6
Up Type=0
Dn Type=3
Dn Slope=0.005
Boundary for River Rch & Prof#=UNT 026 IN DRY C,Reach-1,7
Up Type=0
Dn Type=3
Dn Slope=0.005

--- UNT 026 IN DRY CR WATERSHED.g01 (geometry) ---

Geom Title=Existing Conditions
Program Version=5.07

River Reach=UNT 026 IN DRY C,Reach-1
Reach XY= 30
      2903526.41      6959408.46      2903554.62       6959347.7
      2903613.21      6959323.83      2903601.86      6959262.77
      2903670.36      6959242.45      2903684.86      6959351.11
       2903799.3       6959373.5       2903837.1      6959416.42
      2904174.51      6959423.95      2904428.07       6959526.3
      2904658.93      6959772.75       2904936.7      6959938.03
      2905190.61      6959976.68      2905376.12      6959941.78
       2905621.4      6960038.23       2905724.2      6960044.25
      2906169.12      6960452.69      2906543.32      6960704.81
      2907965.01      6961223.26       2908482.7      6961457.96
      2908576.45      6961457.96      2908675.41      6961364.21
      2908850.59      6961015.71      2908984.25      6961037.39
      2909083.15      6960934.42      2909435.24      6961299.55
      2910316.52      6962018.32      2910505.51       6962060.5
      2910796.23      6961991.01      2910945.59      6962060.71

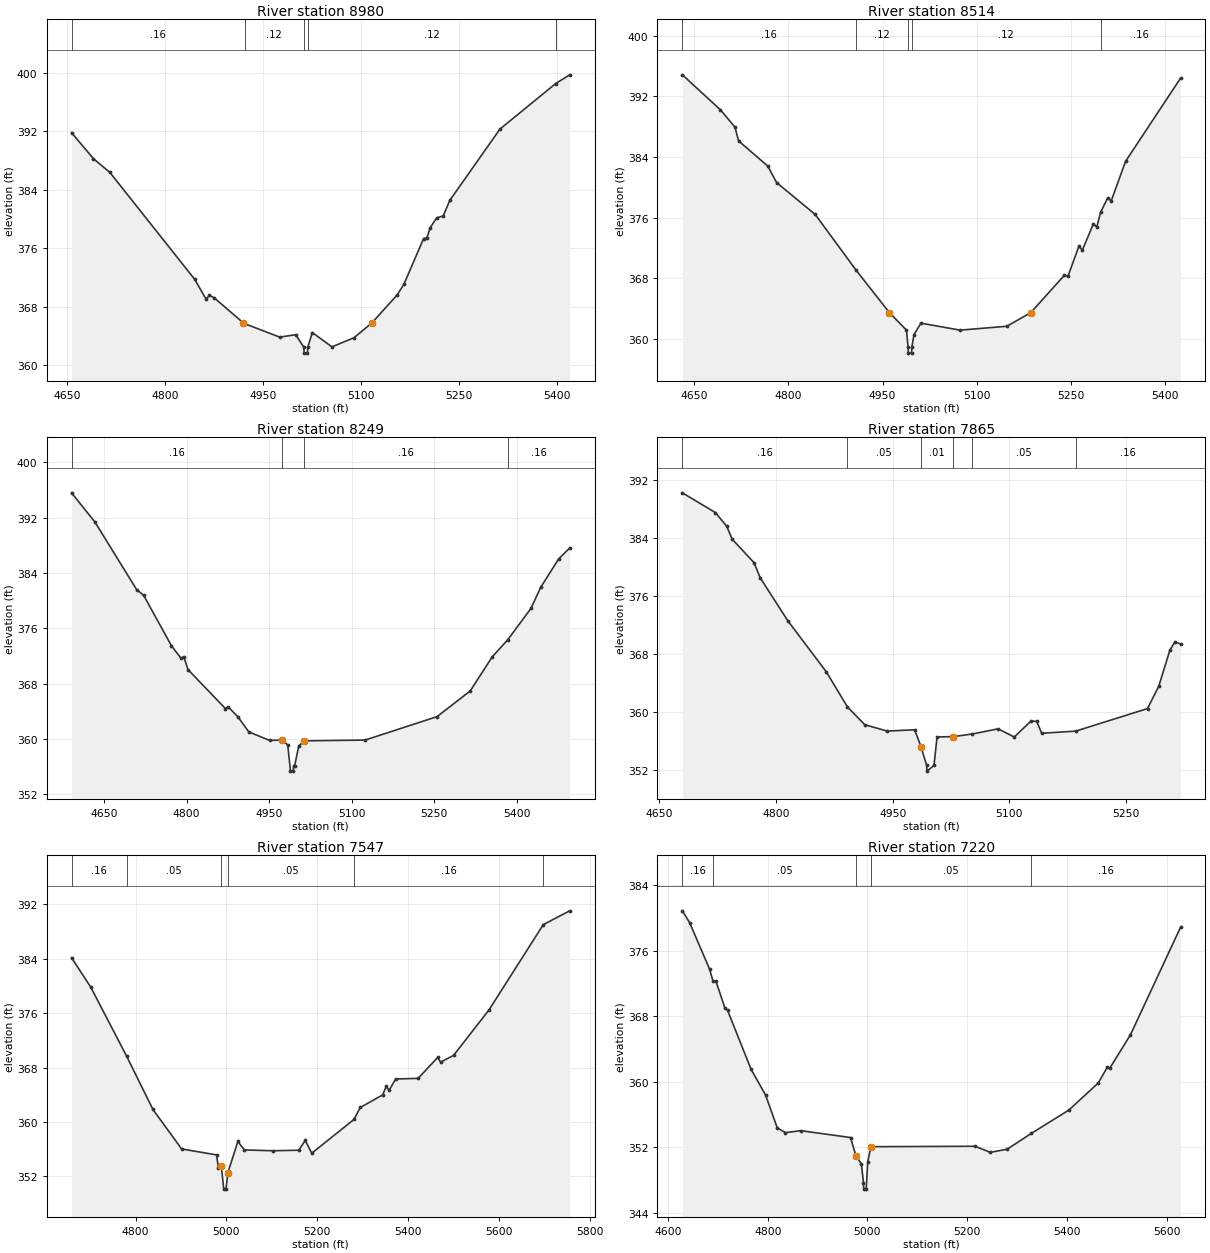
Type RM Length L Ch R = 1 ,8980    ,466,466,466
BEGIN DESCRIPTION:
UNT 026 IN DRY CR WATERSHED 18.0
END DESCRIPTION:
XS GIS Cut Line= 3
      2903558.07      6959683.54      2903577.72       6959340.4
      2903540.71      6958921.84
#Sta/Elev= 30
  4656.3   391.8  4689.9  388.24  4714.9  386.38  4845.2  371.74  4862.6  369.03
  4867.6  369.56  4875.2  369.21  4919.6   365.8    4922  365.68  4975.4  363.85
    5000  364.18  5012.5  362.46    5013  361.66    5018  361.66  5018.5  362.46
  5025.5  364.47  5055.6  362.52  5089.2  363.75    5117   365.8    5156  369.66
    5166  371.09  5196.2  377.33  5201.2   377.4  5206.2   378.8  5216.2  380.15
  5226.3  380.42  5236.3  382.54  5313.2  392.29  5398.6  398.51  5420.2  399.71
#Mann= 5 ,-1 , 0
  4656.3     .16       0    4922     .12       0  5012.5     .07       0
  5018.5     .12       0  5398.6     .16       0
Bank Sta=4919.6,5117
XS Rating Curve= 0 ,0
Exp/Cntr=0.3,0.1

Type RM Length L Ch R = 1 ,8514    ,265,265,265
BEGIN DESCRIPTION:
Mapping XS c6f26122
END DESCRIPTION:
XS GIS Cut Line= 3
      2903674.14      6959742.16      2903832.13      6959384.49
      2903663.73      6959019.91
#Sta/Elev= 30
  4631.4  394.84  4691.9  390.23  4715.2  387.94  4720.7  386.14  4767.3  382.81
  4781.3  380.64  4842.7  376.44  4907.1  369.17  4960.8   363.5    4988  361.19
  4990.5  358.96    4991  358.16    4996  358.16  4996.5  358.96    5000   360.6
  5010.9  362.11  5073.3  361.19  5147.6   361.7  5185.8   363.5  5239.4  368.44
  5244.9  368.29  5262.3  372.25  5267.8  371.73  5285.3   375.2  5290.8  374.78
  5296.8   376.7  5308.2  378.64  5313.7  378.21  5336.6  383.44    5424  394.39
#Mann= 5 ,-1 , 0
  4631.4     .16       0  4907.1     .12       0  4990.5     .07       0
  4996.5     .12       0  5296.8     .16       0
Bank Sta=4960.8,5185.8
XS Rating Curve= 0 ,0
Exp/Cntr=0.3,0.1

Type RM Length L Ch R = 1 ,8249    ,384,384,384
BEGIN DESCRIPTION:
UNT 026 IN DRY CR WATERSHED 17.0
END DESCRIPTION:
XS GIS Cut Line= 3
      2904124.99      6959824.96        2904075.        6959425.
        2904125.      6958924.96
#Sta/Elev= 30
    4591  395.58  4633.8  391.32  4709.4  381.57    4722  380.77  4772.4  373.49
    4790  371.65    4795   371.9  4802.6  370.03  4870.6  364.39  4875.7  364.63
  4893.3   363.2  4913.4     361  4951.2  359.78  4973.9  359.84    4984  359.13
    4989  355.34    4994  355.34  4994.5  356.14  4996.6  356.14  5004.1     359
  5014.2  359.72  5124.7  359.83  5255.4  363.22  5315.7  366.93  5355.9  371.88
    5384  374.34  5426.2  378.87  5443.8   381.9  5476.5  386.02  5496.6   387.6
#Mann= 4 ,-1 , 0
    4591     .16       0  4973.9     .07       0  5014.2     .16       0
    5384     .16       0
Bank Sta=4973.9,5014.2
XS Rating Curve= 0 ,0
Exp/Cntr=0.3,0.1

Type RM Length L Ch R = 1 ,7865    ,318,318,318
BEGIN DESCRIPTION:
UNT 026 IN DRY CR WATERSHED 16.0
END DESCRIPTION:
XS GIS Cut Line= 3
      2904224.98      6959775.02        2904425.        6959525.
      2904624.98      6959275.03
#Sta/Elev= 30
  4679.6  390.24    4722  387.52  4736.5  385.65  4743.7  383.84  4771.7  380.61
  4779.7  378.51  4814.9  372.64  4864.5  365.58  4891.8  360.73  4914.1  358.27
    4943   357.4  4978.2  357.58  4986.2  355.27  4993.6  352.68  4994.1  351.88
    5003  352.68    5007  356.59  5027.8  356.64  5051.9  356.99  5085.4  357.71
  5106.2  356.58  5127.8  358.79    5135  358.73  5141.5   357.1    5185  357.39
  5277.5   360.5  5291.9  363.57  5306.3  368.57  5312.7  369.68  5319.9  369.42
#Mann= 6 ,-1 , 0
  4679.6     .16       0  4891.8     .05       0  4986.2     .01       0
  5027.8     .05       0  5051.9     .05       0    5185     .16       0
Bank Sta=4986.2,5027.8
XS Rating Curve= 0 ,0
Exp/Cntr=0.3,0.1

Type RM Length L Ch R = 1 ,7547    ,327,327,327
BEGIN DESCRIPTION:
UNT 026 IN DRY CR WATERSHED 15.0
END DESCRIPTION:
XS GIS Cut Line= 3
      2904525.01      6960074.96        2904625.        6959775.
      2905124.99      6959175.01
#Sta/Elev= 30
  4659.1  384.15  4701.2  379.85  4780.6  369.65  4838.3  361.85  4901.5  356.05
  4978.5  355.17  4982.4  353.28    4989   353.5  4994.3  350.14  4999.3  350.14
  5003.3  352.53  5025.4  357.15  5039.7   355.9  5103.5  355.78  5159.5  355.86
  5173.8   357.3  5188.1  355.42  5281.2  360.39  5294.9  362.14  5344.3  363.99
  5352.1  365.23  5358.6  364.67    5373  366.33  5422.4  366.42  5465.4  369.49
  5471.9  368.81  5500.5   369.8  5578.6  376.49  5698.1  389.02  5756.3  391.05
#Mann= 6 ,-1 , 0
  4659.1     .16       0  4780.6     .05       0    4989     .03       0
  5003.3     .05       0  5281.2     .16       0  5698.1     .05       0
Bank Sta=4989,5003.3
XS Rating Curve= 0 ,0
Exp/Cntr=0.3,0.1

Type RM Length L Ch R = 1 ,7220    ,367,367,367
BEGIN DESCRIPTION:
UNT 026 IN DRY CR WATERSHED 14.0
END DESCRIPTION:
XS GIS Cut Line= 3
      2904574.96      6960075.02        2904925.        6959925.
        2905075.        6959325.
#Sta/Elev= 30
  4628.8   380.9  4643.4  379.45  4683.2  373.79  4690.1  372.33  4695.9  372.33
  4714.1  369.02  4719.5  368.72  4766.7   361.5  4795.7  358.37  4819.2  354.34
  4835.6  353.77  4866.4  354.01  4966.1  353.17    4977  350.93  4987.9  349.94
  4992.1  347.66  4992.6  346.86  4997.6  346.86  5000.6  350.17  5006.9  352.05
  5215.8   352.1  5246.7  351.36  5280.2  351.74  5328.7  353.67  5403.9  356.52
  5463.2  359.85  5481.2  361.77  5486.4  361.67  5527.6  365.73  5628.1  378.88
#Mann= 5 ,-1 , 0
  4628.8     .16       0  4690.1     .05       0    4977     .03       0
  5006.9     .05       0  5328.7     .16       0
Bank Sta=4977,5006.9
XS Rating Curve= 0 ,0
Exp/Cntr=0.3,0.1

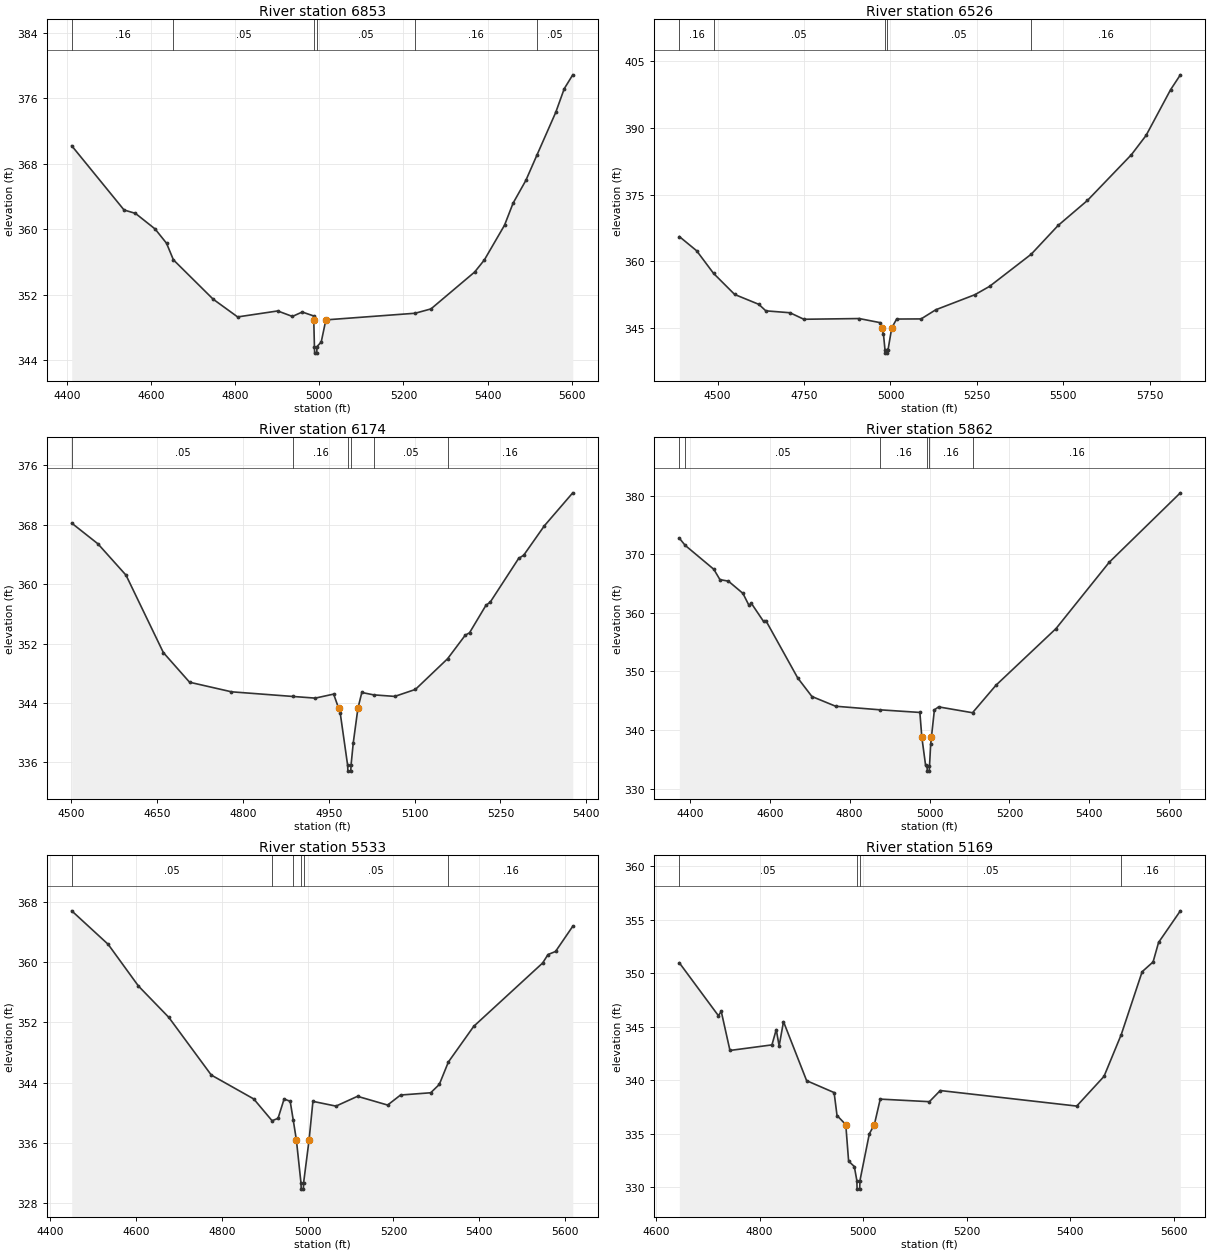
Type RM Length L Ch R = 1 ,6853    ,327,327,327
BEGIN DESCRIPTION:
UNT 026 IN DRY CR WATERSHED 13.0
END DESCRIPTION:
XS GIS Cut Line= 3
      2904975.02      6960474.96        2905275.        6959975.
        2905375.      6959375.03
#Sta/Elev= 30
  4411.3   370.2  4535.7  362.36  4562.9  361.94  4609.5  360.04  4636.7   358.3
  4653.1  356.27  4747.5  351.47  4805.8   349.3  4901.1  350.03    4936  349.36
  4959.4   349.9  4986.6  349.42  4986.8  348.94  4988.4  345.68  4988.9  344.88
  4993.9  344.88  4994.4  345.68  5004.5  346.23  5015.6  348.94  5227.9  349.75
  5265.5  350.28  5369.5  354.79  5392.3  356.25  5440.4   360.5  5460.7  363.19
  5491.1  365.97  5517.6  369.08  5562.1  374.27  5582.4  377.17  5602.6  378.86
#Mann= 6 ,-1 , 0
  4411.3     .16       0  4653.1     .05       0  4988.4     .03       0
  4994.4     .05       0  5227.9     .16       0  5517.6     .05       0
Bank Sta=4986.8,5015.6
XS Rating Curve= 0 ,0
Exp/Cntr=0.3,0.1

Type RM Length L Ch R = 1 ,6526    ,352,352,352
BEGIN DESCRIPTION:
UNT 026 IN DRY CR WATERSHED 12.0
END DESCRIPTION:
XS GIS Cut Line= 3
        2905575.      6960624.99        2905575.        6960025.
      2906174.98      6959425.02
#Sta/Elev= 30
  4389.6  365.59  4439.6  362.41  4488.6  357.33  4549.6  352.61  4619.6  350.39
  4639.6  348.94  4709.6  348.51  4749.6  347.05  4909.6  347.21  4969.6   346.3
  4974.4  345.13  4979.6  343.85  4984.1  340.26  4984.6  339.46  4989.6  339.46
  4990.1  340.26  4993.1  340.26  5003.7  345.13  5017.9   347.1  5088.6  347.13
    5131  349.18  5244.2  352.56  5286.6  354.43  5406.9  361.63  5484.6  368.07
  5569.4  373.68  5696.7  383.95  5739.1  388.27  5809.8   398.5  5838.1  401.84
#Mann= 5 ,-1 , 0
  4389.6     .16       0  4488.6     .05       0  4984.1     .03       0
  4990.1     .05       0  5406.9     .16       0
Bank Sta=4974.4,5003.7
XS Rating Curve= 0 ,0
Exp/Cntr=0.3,0.1

Type RM Length L Ch R = 1 ,6174    ,312,312,312
BEGIN DESCRIPTION:
UNT 026 IN DRY CR WATERSHED 11.0
END DESCRIPTION:
XS GIS Cut Line= 3
      2905625.01      6960624.99        2905875.        6960175.
      2906074.99      6959875.02
#Sta/Elev= 30
    4501  368.21  4546.7  365.43  4595.9   361.2  4661.1  350.78  4706.9  346.79
  4780.1   345.5  4887.9  344.87  4926.5  344.65  4958.6  345.19  4967.3  343.28
    4970  342.69    4983  335.62  4983.5  334.82  4988.5  334.82    4989  335.62
  4992.9  338.66    5001  343.28  5007.8  345.41  5028.3  345.09  5065.3  344.88
  5101.4  345.82  5157.6  349.95  5188.5  353.12    5196  353.45  5224.6  357.14
  5232.1  357.57  5281.7  363.45  5290.7   363.9  5326.7  367.85  5376.3  372.29
#Mann= 6 ,-1 , 0
    4501     .05       0  4887.9     .16       0    4983     .07       0
    4989     .16       0  5028.3     .05       0  5157.6     .16       0
Bank Sta=4967.3,5001
XS Rating Curve= 0 ,0
Exp/Cntr=0.3,0.1

Type RM Length L Ch R = 1 ,5862    ,329,329,329
BEGIN DESCRIPTION:
UNT 026 IN DRY CR WATERSHED 10.0
END DESCRIPTION:
XS GIS Cut Line= 3
      2905574.99        6960725.        2906125.        6960375.
        2906175.      6959775.01
#Sta/Elev= 30
  4373.7  372.75  4388.2  371.53  4460.1  367.43  4475.3  365.67  4496.5  365.41
  4532.9  363.32  4548.1  361.26    4554  361.62  4584.5  358.53  4590.4  358.66
    4670  348.88  4705.6  345.71  4764.9  344.05  4875.8  343.44  4975.7  342.99
  4980.7  338.73  4990.1  333.94  4993.8  333.77  4994.3  332.97  4999.3  332.97
  4999.8  333.77  5002.8   337.6  5004.6  338.73  5012.1  343.44  5022.7  343.94
  5107.5  342.94  5166.1  347.63  5316.6  357.32  5449.6  368.63  5627.7  380.49
#Mann= 6 ,-1 , 0
  4373.7     .16       0  4388.2     .05       0  4875.8     .16       0
  4993.8     .03       0  4999.8     .16       0  5107.5     .16       0
Bank Sta=4980.7,5004.6
XS Rating Curve= 0 ,0
Exp/Cntr=0.3,0.1

Type RM Length L Ch R = 1 ,5533    ,364,364,364
BEGIN DESCRIPTION:
UNT 026 IN DRY CR WATERSHED 9.0
END DESCRIPTION:
XS GIS Cut Line= 3
      2905974.97      6960975.03        2906375.        6960575.
        2906325.      6959975.01
#Sta/Elev= 30
  4450.1  366.77    4535  362.33  4605.7  356.79  4676.4  352.64  4775.4  344.99
  4874.4  341.82  4917.1  338.93    4931  339.25  4945.1  341.81  4959.3  341.51
  4966.4  339.03  4973.8  336.36  4984.5  330.66    4985  329.86    4990  329.86
  4990.5  330.66  5003.3  336.36  5012.3   341.5    5066  340.87  5116.2  342.17
  5186.4  341.01  5216.5  342.34  5286.8  342.64  5306.8  343.74    5328  346.72
  5387.1  351.45  5547.7  359.85  5560.2  360.97  5577.8  361.38  5617.9  364.72
#Mann= 6 ,-1 , 0
  4450.1     .05       0  4917.1     .16       0  4966.4     .05       0
  4984.5     .03       0  4990.5     .05       0    5328     .16       0
Bank Sta=4973.8,5003.3
XS Rating Curve= 0 ,0
Exp/Cntr=0.3,0.1

Type RM Length L Ch R = 1 ,5169    ,320,320,320
BEGIN DESCRIPTION:
UNT 026 IN DRY CR WATERSHED 8.0
END DESCRIPTION:
XS GIS Cut Line= 3
      2906375.03      6960924.99        2906675.        6960775.
      2906874.99      6960175.03
#Sta/Elev= 30
  4644.8  350.96  4720.2  346.03  4725.8  346.42  4742.6  342.78  4823.7   343.3
    4832  344.73  4837.6   343.2    4846  345.47  4890.7  339.96  4943.8  338.85
  4949.4  336.71  4966.3  335.86  4971.8  332.45  4982.8  331.95  4987.7  330.64
  4988.2  329.84  4993.2  329.84  4993.7  330.64  5011.8     335  5021.5  335.86
  5032.9  338.24  5127.8     338  5148.8  339.04  5412.4  337.59  5465.1  340.36
  5498.4  344.26  5538.8  350.13  5559.9  351.04  5570.5  352.86  5612.6  355.81
#Mann= 4 ,-1 , 0
  4644.8     .05       0  4987.7     .03       0  4993.7     .05       0
  5498.4     .16       0
Bank Sta=4966.3,5021.5
XS Rating Curve= 0 ,0
Exp/Cntr=0.3,0.1

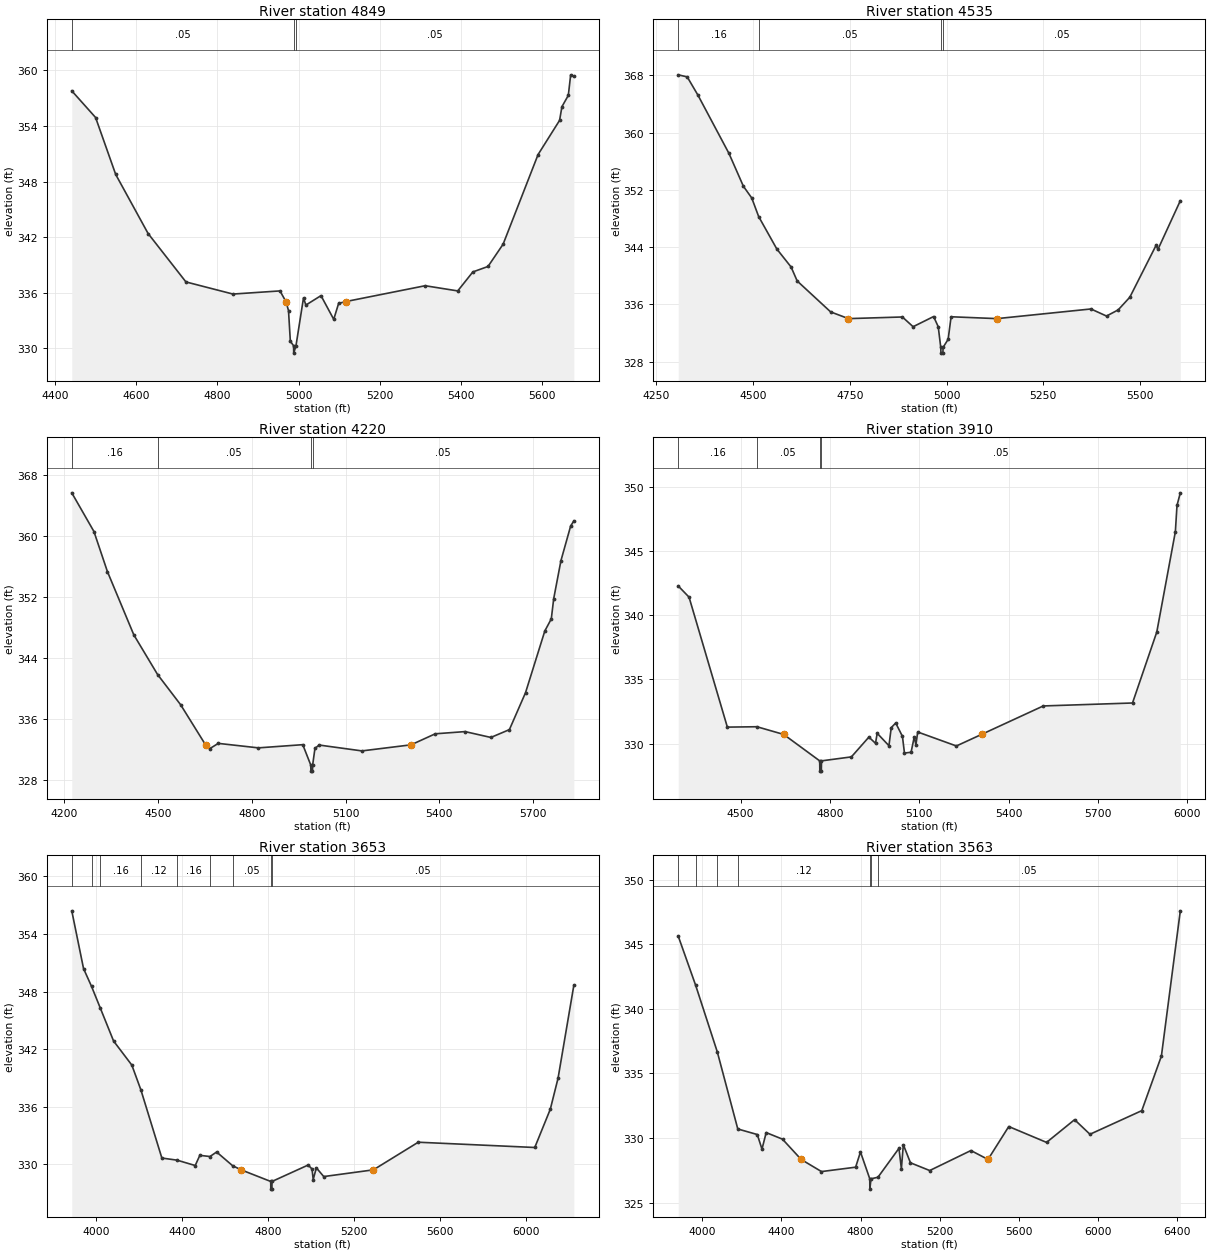
Type RM Length L Ch R = 1 ,4849    ,314,314,314
BEGIN DESCRIPTION:
UNT 026 IN DRY CR WATERSHED 7.0
END DESCRIPTION:
XS GIS Cut Line= 3
      2906675.01      6961324.98        2906975.        6960875.
      2907324.98      6960275.03
#Sta/Elev= 30
    4442   357.8  4500.6  354.92  4550.1  348.77  4629.8  342.39  4722.9  337.16
  4838.6  335.85  4954.3  336.19  4968.9  335.04  4975.3  334.07  4979.8  330.76
  4987.7  330.27  4988.2  329.47  4993.7  330.27  5012.2  335.44    5018  334.66
  5055.2  335.68  5086.6  333.12  5098.6  334.84  5116.3  335.04  5311.5  336.75
  5391.7  336.19  5428.9  338.24  5466.2  338.83  5503.4  341.24  5589.4  350.92
  5642.3  354.61  5648.1  356.09  5663.8  357.31  5669.6  359.53  5677.4  359.35
#Mann= 3 ,-1 , 0
    4442     .05       0  4987.7     .03       0  4993.7     .05       0
Bank Sta=4968.9,5116.3
XS Rating Curve= 0 ,0
Exp/Cntr=0.3,0.1

Type RM Length L Ch R = 1 ,4535    ,315,315,315
BEGIN DESCRIPTION:
UNT 026 IN DRY CR WATERSHED 6.0
END DESCRIPTION:
XS GIS Cut Line= 3
      2906924.99      6961575.01        2907275.        6960975.
        2907325.      6960375.02
#Sta/Elev= 30
    4307  368.07  4330.2  367.78  4357.9  365.23  4438.1  357.08  4475.3   352.5
  4496.8  350.87  4514.7  348.27  4561.7  343.73  4598.5  341.22  4614.2  339.27
  4700.6  334.95  4746.7  334.01  4885.9  334.24  4913.6  332.88  4966.5   334.3
  4978.5  332.88    4985  329.99  4985.5  329.19  4990.5  329.19    4991  329.99
  5004.1  331.12  5011.7  334.27  5130.2  334.01  5372.9  335.36  5413.1  334.37
  5443.2  335.23  5473.3     337    5541  344.24    5546  343.69  5603.7  350.48
#Mann= 4 ,-1 , 0
    4307     .16       0  4514.7     .05       0    4985     .03       0
    4991     .05       0
Bank Sta=4746.7,5130.2
XS Rating Curve= 0 ,0
Exp/Cntr=0.3,0.1

Type RM Length L Ch R = 1 ,4220    ,310,310,310
BEGIN DESCRIPTION:
UNT 026 IN DRY CR WATERSHED 5.0
END DESCRIPTION:
XS GIS Cut Line= 3
      2906975.02      6961574.98        2907575.        6961075.
        2907375.      6960275.01
#Sta/Elev= 30
  4224.5  365.72  4295.4  360.63  4338.4  355.37    4423  347.03  4498.9  341.82
  4572.7  337.84  4652.3  332.57  4665.1  332.05  4693.1  332.76  4821.3  332.17
  4963.2  332.59  4988.8  329.91  4989.3  329.11  4994.3  329.11  4994.8  329.91
  5002.2  332.11  5015.8  332.54  5152.4  331.77  5309.5  332.57  5386.9  334.02
  5482.2  334.31  5564.7  333.54    5624  334.57  5675.5  339.42  5737.3  347.55
    5758  349.14  5765.7   351.8  5788.9  356.81  5819.8  361.34  5830.1  362.03
#Mann= 4 ,-1 , 0
  4224.5     .16       0  4498.9     .05       0  4988.8     .03       0
  4994.8     .05       0
Bank Sta=4652.3,5309.5
XS Rating Curve= 0 ,0
Exp/Cntr=0.3,0.1

Type RM Length L Ch R = 1 ,3910    ,257,257,257
BEGIN DESCRIPTION:
UNT 026 IN DRY CR WATERSHED 4.0
END DESCRIPTION:
XS GIS Cut Line= 3
        2907275.        6961525.        2907875.        6961225.
      2907435.03      6960310.33
#Sta/Elev= 30
  4290.7  342.28    4327  341.41  4455.6  331.28  4554.8  331.31  4644.8  330.71
  4765.7  328.65  4766.2  327.85  4771.2  327.85  4771.7  328.65  4872.1  328.96
  4930.8   330.5  4953.1  330.02  4958.7   330.8  4998.2  329.83  5005.9  331.24
  5020.9   331.6  5043.5  330.56  5050.3  329.26  5072.5  329.32  5083.2  330.52
  5088.8   329.9  5094.7   330.9  5224.6  329.81    5309  330.71  5516.4  332.93
    5816  333.16  5897.5  338.69  5959.9  346.51  5965.4  348.56  5976.5  349.54
#Mann= 4 ,-1 , 0
  4290.7     .16       0  4554.8     .05       0  4765.7     .03       0
  4771.7     .05       0
Bank Sta=4644.8,5309
XS Rating Curve= 0 ,0
Exp/Cntr=0.3,0.1

Type RM Length L Ch R = 1 ,3653    ,90,90,90
BEGIN DESCRIPTION:
Mapping XS 8acc3769
END DESCRIPTION:
XS GIS Cut Line= 3
      2907059.11      6961679.59      2908121.56      6961273.36
      2907461.08      6960276.48
#Sta/Elev= 30
  3888.5  356.41  3943.2  350.39  3980.4  348.53  4021.9  346.23  4082.8  342.84
  4167.6  340.33  4209.8  337.74  4307.2  330.64  4377.8  330.42  4462.2  329.86
  4483.6  330.92  4530.7   330.8  4561.7  331.27    4636  329.84  4675.7  329.41
  4813.1   328.2  4813.6   327.4  4818.6   327.4  4819.1   328.2  4986.8  329.91
  5005.1   329.5  5010.5   328.4  5025.1  329.62  5059.5  328.71  5290.3  329.41
  5498.7  332.29  6040.2  331.74  6112.4  335.73  6148.5  338.97  6221.8  348.65
#Mann= 9 ,-1 , 0
  3888.5     .16       0  3980.4     .12       0  4021.9     .16       0
  4209.8     .12       0  4377.8     .16       0  4530.7     .12       0
    4636     .05       0  4813.1     .03       0  4819.1     .05       0
Bank Sta=4675.7,5290.3
XS Rating Curve= 0 ,0
Exp/Cntr=0.3,0.1

Type RM Length L Ch R = 1 ,3563    ,154,154,154
BEGIN DESCRIPTION:
Mapping XS fb9e350d
END DESCRIPTION:
XS GIS Cut Line= 4
      2907166.77      6961695.16      2908125.94      6961434.75
      2908286.53      6961087.53      2907484.48       6960250.4
#Sta/Elev= 30
  3879.1  345.64  3967.1  341.83  4076.6  336.66  4179.9   330.7  4278.3  330.27
  4302.1  329.14  4323.3  330.42  4405.7  329.91  4499.9  328.34  4602.6   327.4
  4775.1  327.74  4799.5  328.92  4846.5  326.84    4847  326.04  4852.5  326.84
  4887.8  326.96  4993.9   329.2  5006.1  327.62    5016  329.48    5052  328.08
  5149.2  327.48  5357.3  329.03  5443.6  328.34  5548.5  330.89  5739.4  329.66
  5880.9  331.42  5958.6  330.29  6220.3  332.12  6319.4  336.35  6414.9   347.6
#Mann= 7 ,-1 , 0
  3879.1     .16       0  3967.1     .12       0  4076.6     .16       0
  4179.9     .12       0  4846.5     .03       0  4852.5     .12       0
  4887.8     .05       0
Bank Sta=4499.9,5443.6
XS Rating Curve= 0 ,0
Exp/Cntr=0.3,0.1

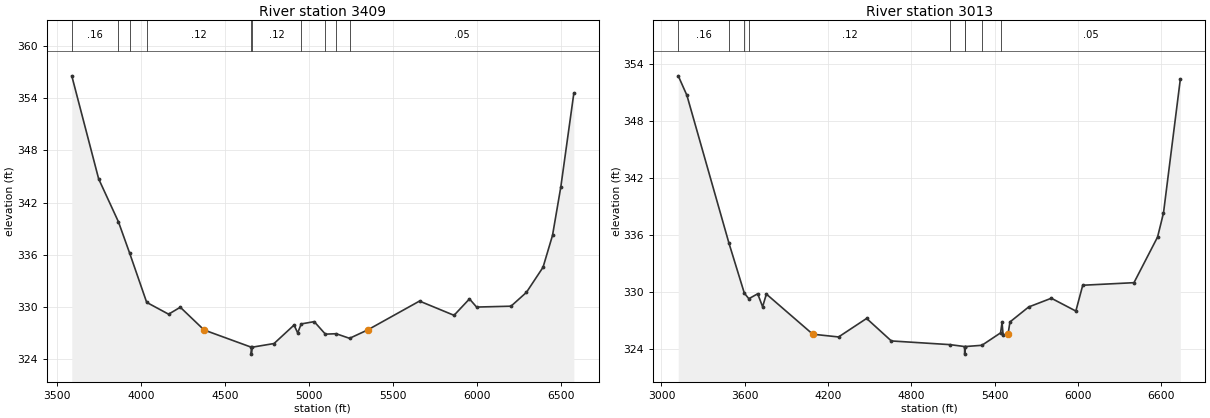
Type RM Length L Ch R = 1 ,3409    ,396,396,396
BEGIN DESCRIPTION:
Mapping XS afc0d5e9
END DESCRIPTION:
XS GIS Cut Line= 6
      2907015.76        6961727.      2908265.76      6961518.66
      2908375.13      6961242.62      2908338.68       6961039.5
      2908119.93      6960831.16      2907469.47      6960180.71
#Sta/Elev= 30
  3586.8  356.59  3747.1  344.72  3865.1  339.77  3932.5  336.13  4033.3   330.5
  4163.9  329.14  4233.7  329.94  4375.5  327.32  4656.5  325.34    4657  324.54
  4662.5  325.34  4792.4  325.76  4911.8  327.89  4933.3  326.98  4954.4  328.02
    5032  328.28  5098.4  326.84  5162.5  326.89  5242.4  326.36  5349.8  327.32
  5659.4  330.65  5865.2  329.01  5957.2   330.9  5999.6  329.96  6204.7  330.06
  6296.6  331.65  6395.6  334.54  6452.1  338.21  6501.6  343.79  6579.3  354.59
#Mann= 10 ,-1 , 0
  3586.8     .16       0  3865.1     .12       0  3932.5     .16       0
  4033.3     .12       0  4656.5     .03       0  4662.5     .12       0
  4954.4     .05       0  5098.4     .07       0  5162.5     .12       0
  5242.4     .05       0
Bank Sta=4375.5,5349.8
XS Rating Curve= 0 ,0
Exp/Cntr=0.3,0.1

Type RM Length L Ch R = 1 ,3013    ,0,0,0
BEGIN DESCRIPTION:
UNT 026 IN DRY CR WATERSHED 3.0
END DESCRIPTION:
XS GIS Cut Line= 4
      2906984.53      6961779.08      2908703.26      6961508.25
      2908583.47      6961091.58      2907494.93      6960143.66
#Sta/Elev= 30
  3120.7  352.78    3183  350.73  3486.2  335.14    3597  329.87  3629.4  329.29
  3693.1  329.81  3728.6  328.44  3755.5  329.78  4089.9  325.55  4275.7  325.26
  4477.7  327.21  4655.7  324.84  5078.8  324.45  5183.6  324.25  5184.1  323.45
  5189.6  324.25  5308.2  324.38  5442.8  325.69  5453.4  326.79    5461  325.49
  5496.6  325.55  5510.4  326.84  5645.2  328.42  5808.5  329.34  5985.1  327.99
  6034.7  330.71  6403.8  330.98  6573.7  335.79  6616.4  338.32  6737.6  352.41
#Mann= 9 ,-1 , 0
  3120.7     .16       0  3486.2     .12       0    3597     .16       0
  3629.4     .12       0  5078.8     .07       0  5183.6     .07       0
  5189.6     .07       0  5308.2     .12       0  5442.8     .05       0
Bank Sta=4089.9,5496.6
XS Rating Curve= 0 ,0
Exp/Cntr=0.3,0.1
LCMann Table=0

Chan Stop Cuts=-1
Use User Specified Reach Order=0
Composite Channel Slope=5