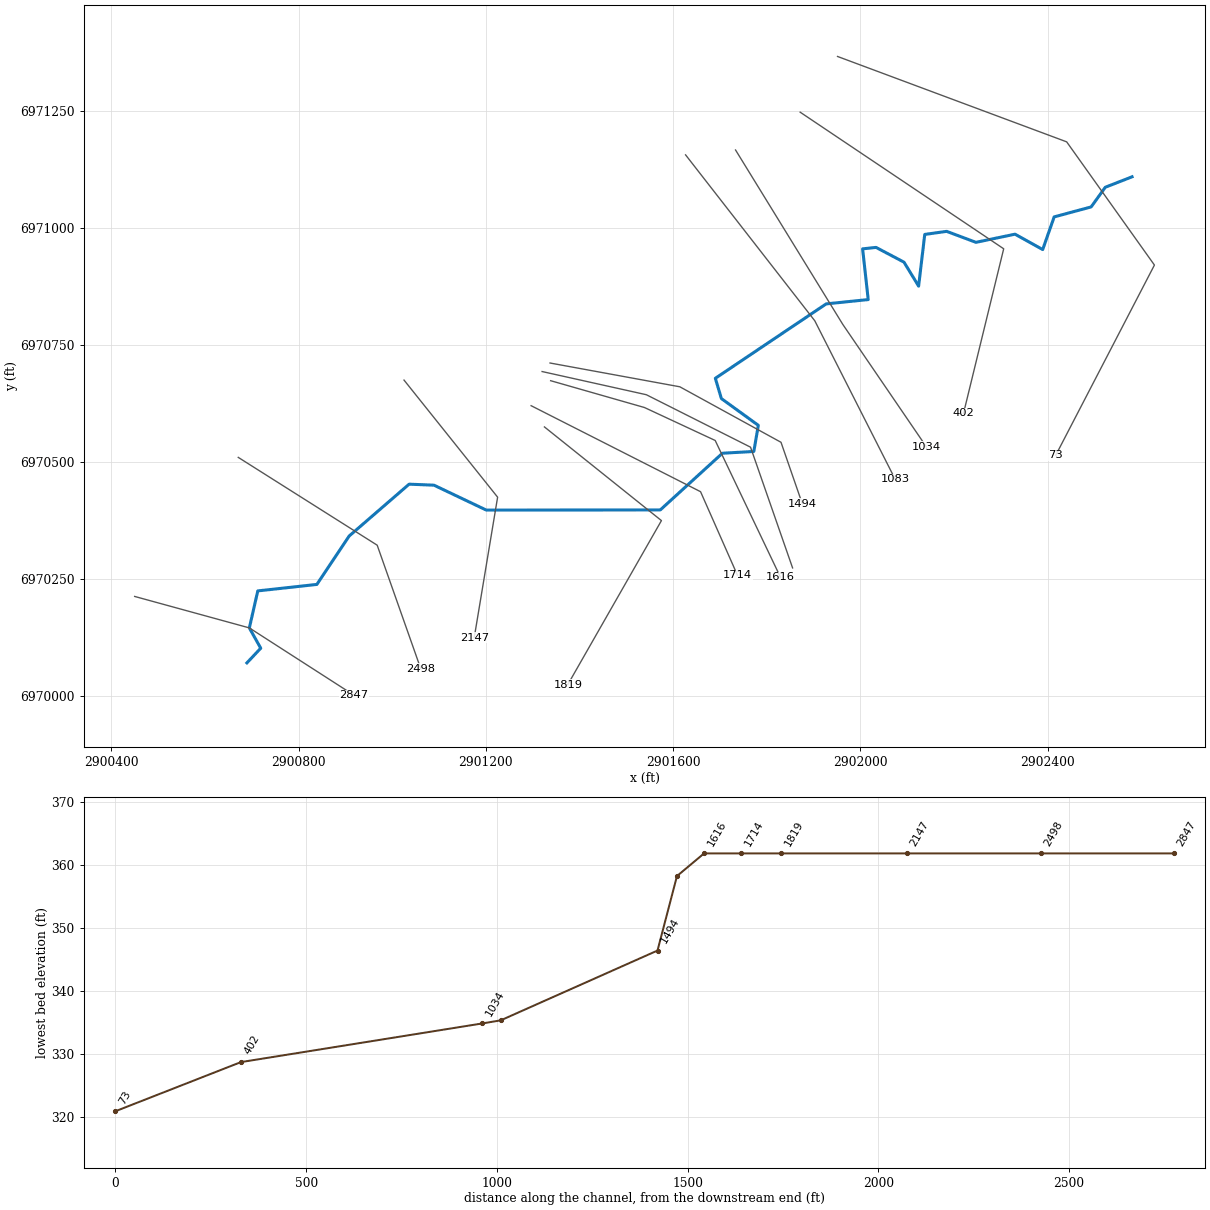
--- UNT 027 IN DRY CR WATERSHED.prj (project) ---

Proj Title=UNT 027 IN DRY CR WATERSHED Base Level Engineering
Current Plan=p01
Default Exp/Contr=0.3,0.1
English Units
Geom File=g01
Flow File=f01
Plan File=p01
BEGIN DESCRIPTION:
UNT 027 IN DRY CR WATERSHED
END DESCRIPTION:

--- UNT 027 IN DRY CR WATERSHED.p01 (plan) ---

Plan Title=Multiple Run
Short Identifier=Multiple
Geom File=g01
Flow File=f01
Subcritical Flow
K Sum by GR= 0
Std Step Tol= 0.01
Critical Tol= 0.01
Num of Std Step Trials= 20
Max Error Tol= 0.3
Flow Tol Ratio= 0.001
Split Flow NTrial= 30
Split Flow Tol= 0.02
Split Flow Ratio= 0.02
Log Output Level= 0
Friction Slope Method= 1
Unsteady Friction Slope Method= 2
Unsteady Bridges Friction Slope Method= 1
Parabolic Critical Depth
Global Vel Dist=  1 , 1 , 1
Global Log Level= 0
CheckData=True
Encroach Param= -1, 0, 0, 0
BEGIN DESCRIPTION:
Multiple Run
END DESCRIPTION:

--- UNT 027 IN DRY CR WATERSHED.f01 (steady flow) ---

Flow Title=Multiple
Number of Profiles=7
Profile Names=10-year,25-year,50-year,1pct_min,100-year,1pct_plu,500-year
River Rch & RM= UNT 027 IN DRY C,Reach-1,2847
     194     244     283     164     326     651     434
Boundary for River Rch & Prof#=UNT 027 IN DRY C,Reach-1,1
Up Type=0
Dn Type=3
Dn Slope=0.005
Boundary for River Rch & Prof#=UNT 027 IN DRY C,Reach-1,2
Up Type=0
Dn Type=3
Dn Slope=0.005
Boundary for River Rch & Prof#=UNT 027 IN DRY C,Reach-1,3
Up Type=0
Dn Type=3
Dn Slope=0.005
Boundary for River Rch & Prof#=UNT 027 IN DRY C,Reach-1,4
Up Type=0
Dn Type=3
Dn Slope=0.005
Boundary for River Rch & Prof#=UNT 027 IN DRY C,Reach-1,5
Up Type=0
Dn Type=3
Dn Slope=0.005
Boundary for River Rch & Prof#=UNT 027 IN DRY C,Reach-1,6
Up Type=0
Dn Type=3
Dn Slope=0.005
Boundary for River Rch & Prof#=UNT 027 IN DRY C,Reach-1,7
Up Type=0
Dn Type=3
Dn Slope=0.005

--- UNT 027 IN DRY CR WATERSHED.g01 (geometry) ---

Geom Title=Existing Conditions

River Reach=UNT 027 IN DRY C,Reach-1
Reach XY= 30
      2900689.37      6970071.27      2900718.88      6970102.52
      2900694.57      6970145.92      2900712.59      6970224.91
      2900838.74      6970238.74      2900907.90      6970342.10
      2901035.94      6970452.78      2901089.10      6970450.61
      2901200.87      6970397.44      2901572.57      6970397.79
      2901705.28      6970518.80      2901772.40      6970522.63
      2901782.00      6970578.37      2901703.10      6970635.53
      2901690.17      6970678.80      2901927.02      6970837.65
      2902016.76      6970846.88      2902004.86      6970955.15
      2902033.53      6970958.23      2902093.26      6970926.71
      2902124.50      6970875.57      2902137.59      6970986.00
      2902184.47      6970992.51      2902246.96      6970969.07
      2902330.47      6970986.47      2902389.58      6970953.66
      2902414.11      6971023.38      2902493.13      6971044.68
      2902523.29      6971086.62      2902580.56      6971109.00

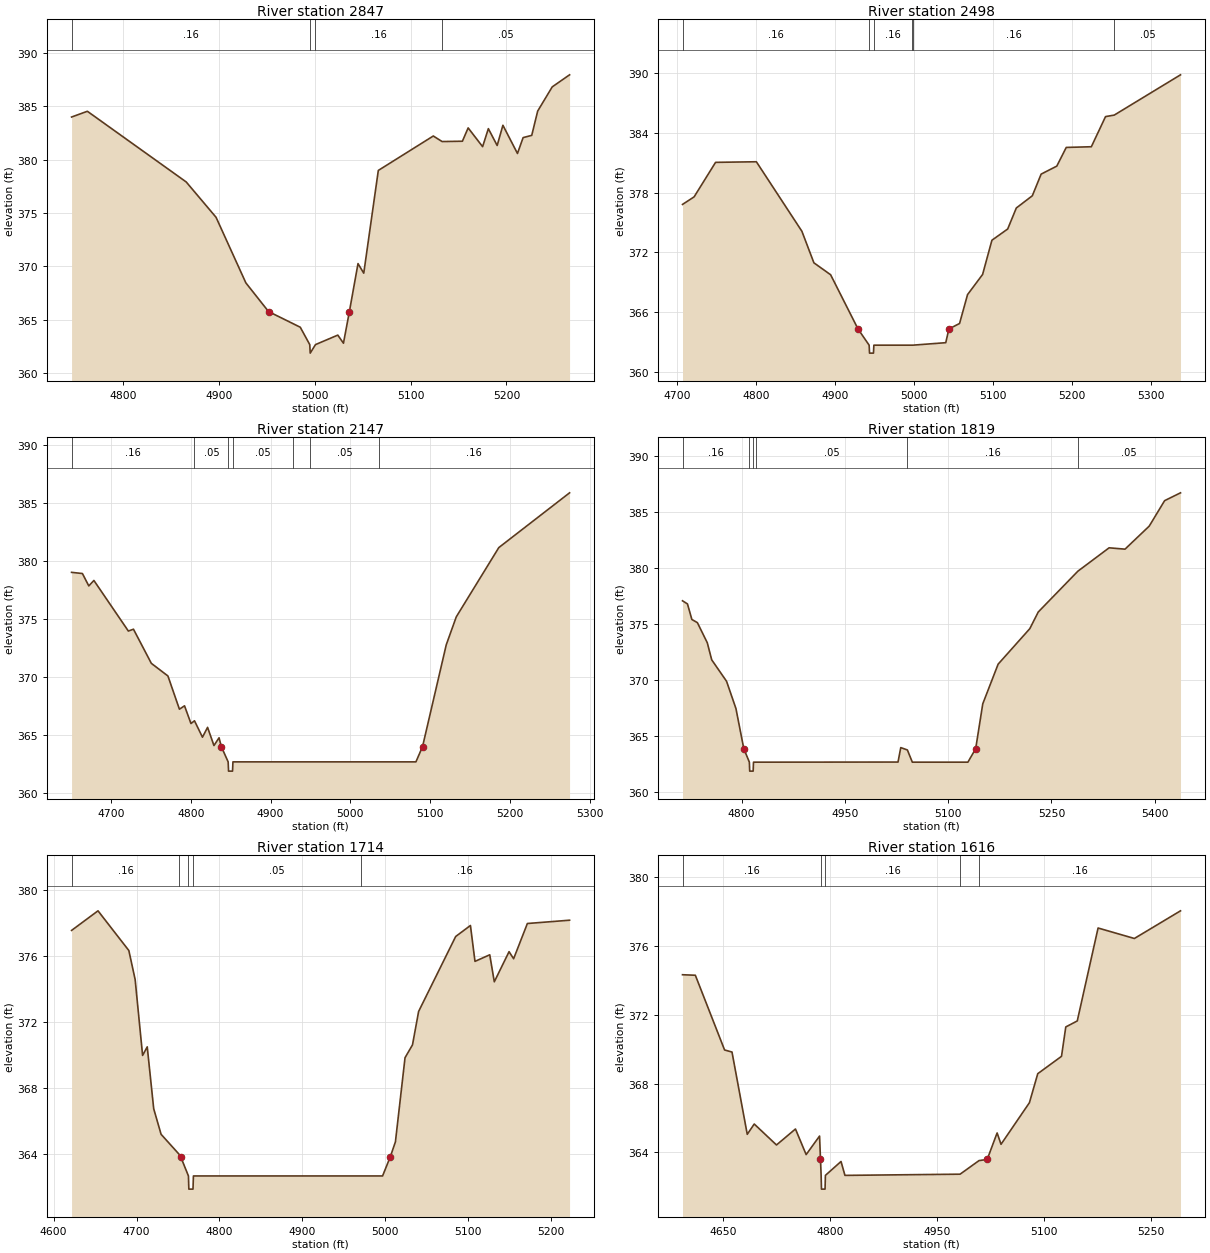
Type RM Length L Ch R = 1,2847,349,349,349
BEGIN DESCRIPTION:
UNT 027 IN DRY CR WATERSHED 6.0
END DESCRIPTION:
XS GIS Cut Line= 3
      2900449.51      6970213.10      2900694.57      6970145.92
      2900918.26      6970002.16
#Sta/Elev= 30
  4745.9  384.01  4762.4  384.55  4865.6  377.92  4896.8  374.60  4927.9  368.45
  4951.6  365.76  4984.7  364.29  4994.6  362.66  4995.1  361.86  5000.6  362.66
  5023.9  363.55  5029.8  362.79  5036.0  365.76  5045.0  370.26  5051.0  369.36
  5066.2  379.00  5123.6  382.23  5132.8  381.71  5154.0  381.74  5160.0  382.99
  5175.1  381.23  5181.1  382.92  5190.3  381.34  5196.3  383.24  5211.5  380.59
  5217.4  382.08  5226.4  382.29  5232.6  384.57  5247.8  386.84  5265.9  387.97
#Mann=4,-1,0
  4745.9    0.16       0  4994.6    0.07       0  5000.6    0.16       0
  5132.8    0.05       0
Bank Sta=4951.6,5036
Exp/Cntr=0.3,0.1

Type RM Length L Ch R = 1,2498,351,351,351
BEGIN DESCRIPTION:
Mapping XS 6a4871c1
END DESCRIPTION:
XS GIS Cut Line= 3
      2900670.85      6970509.97      2900967.71      6970322.48
      2901060.90      6970058.45
#Sta/Elev= 30
  4706.6  376.81  4721.3  377.57  4748.5  381.04  4800.2  381.10  4857.9  374.11
  4873.1  370.94  4894.3  369.74  4929.0  364.29  4943.1  362.66  4943.6  361.86
  4948.6  361.86  4949.1  362.66  4997.6  362.66  4998.4  362.66  5040.2  362.91
  5044.2  364.29  5057.7  364.84  5067.8  367.74  5086.9  369.77  5098.7  373.21
  5118.7  374.34  5129.6  376.45  5149.9  377.68  5161.1  379.86  5180.9  380.66
  5192.9  382.54  5224.7  382.61  5242.7  385.64  5253.7  385.79  5337.7  389.84
#Mann=6,-1,0
  4706.6    0.16       0  4943.1    0.07       0  4949.1    0.16       0
  4997.6    0.05       0  4998.4    0.16       0  5253.7    0.05       0
Bank Sta=4929,5044.2
Exp/Cntr=0.3,0.1

Type RM Length L Ch R = 1,2147,328,328,328
BEGIN DESCRIPTION:
UNT 027 IN DRY CR WATERSHED 5.0
END DESCRIPTION:
XS GIS Cut Line= 3
      2901025.01      6970674.98      2901225.00      6970425.00
      2901175.00      6970124.98
#Sta/Elev= 30
  4650.5  379.03  4664.1  378.93  4672.1  377.86  4678.5  378.33  4721.7  373.96
  4728.1  374.12  4750.5  371.17  4771.3  370.08  4785.7  367.21  4792.1  367.50
  4800.2  365.97  4804.6  366.21  4814.6  364.79  4821.0  365.64  4829.0  364.07
  4835.4  364.74  4838.2  363.98  4846.8  362.66  4847.3  361.86  4852.3  361.86
  4852.8  362.66  4927.7  362.66  4949.8  362.66  5035.4  362.66  5082.2  362.66
  5090.5  363.98  5120.2  372.77  5132.8  375.19  5186.1  381.17  5274.8  385.90
#Mann=7,-1,0
  4650.5    0.16       0  4804.6    0.05       0  4846.8   0.033       0
  4852.8    0.05       0  4927.7    0.07       0  4949.8    0.05       0
  5035.4    0.16       0
Bank Sta=4838.2,5090.5
Exp/Cntr=0.3,0.1

Type RM Length L Ch R = 1,1819,105,105,105
BEGIN DESCRIPTION:
UNT 027 IN DRY CR WATERSHED 4.0
END DESCRIPTION:
XS GIS Cut Line= 3
      2901325.00      6970575.00      2901575.00      6970375.00
      2901374.99      6970024.98
#Sta/Elev= 30
  4714.2  377.07  4721.4  376.79  4727.8  375.40  4735.8  375.12  4750.2  373.32
  4756.6  371.80  4778.2  369.88  4791.8  367.45  4803.2  363.87  4811.3  362.66
  4811.8  361.86  4816.8  361.86  4817.3  362.66  4821.1  362.66  5027.2  362.67
  5031.2  363.96  5040.8  363.75  5048.0  362.66  5128.7  362.66  5140.0  363.86
  5150.3  367.87  5172.6  371.41  5218.6  374.58  5230.9  376.07  5288.4  379.71
  5333.8  381.80  5356.9  381.68  5392.1  383.74  5414.4  386.01  5437.5  386.71
#Mann=6,-1,0
  4714.2    0.16       0  4811.3   0.033       0  4817.3    0.16       0
  4821.1    0.05       0  5040.8    0.16       0  5288.4    0.05       0
Bank Sta=4803.2,5140
Exp/Cntr=0.3,0.1

Type RM Length L Ch R = 1,1714,98,98,98
BEGIN DESCRIPTION:
Mapping XS b4593297
END DESCRIPTION:
XS GIS Cut Line= 3
      2901296.58      6970620.32      2901658.60      6970436.70
      2901737.39      6970258.47
#Sta/Elev= 30
  4621.6  377.57  4653.5  378.76  4690.7  376.35  4698.3  374.59  4707.3  369.98
  4712.9  370.50  4720.7  366.74  4729.6  365.19  4751.8  363.95  4753.3  363.82
  4762.6  362.66  4763.1  361.86  4768.1  361.86  4768.6  362.66  4970.3  362.66
  4996.8  362.66  5006.1  363.82  5012.3  364.73  5023.9  369.84  5032.9  370.62
  5040.3  372.65  5085.0  377.20  5102.8  377.87  5108.3  375.69  5126.1  376.09
  5131.6  374.45  5149.4  376.28  5154.9  375.85  5171.5  377.99  5222.4  378.19
#Mann=5,-1,0
  4621.6    0.16       0  4751.8    0.05       0  4762.6    0.07       0
  4768.6    0.05       0  4970.3    0.16       0
Bank Sta=4753.3,5006.1
Exp/Cntr=0.3,0.1

Type RM Length L Ch R = 1,1616,71,71,71
BEGIN DESCRIPTION:
Mapping XS 898fc6e5
END DESCRIPTION:
XS GIS Cut Line= 4
      2901338.30      6970673.68      2901538.81      6970616.39
      2901689.85      6970546.08      2901829.19      6970254.39
#Sta/Elev= 30
  4593.2  374.34  4611.2  374.31  4652.2  369.96  4662.6  369.84  4684.0  365.05
  4693.8  365.65  4725.0  364.43  4751.6  365.36  4766.6  363.87  4785.4  364.95
  4786.7  363.59  4787.6  362.66  4788.1  361.86  4793.1  361.86  4793.6  362.66
  4815.5  363.47  4821.0  362.66  4982.5  362.73  5009.0  363.52  5020.5  363.59
  5034.4  365.13  5039.9  364.47  5079.7  366.89  5091.4  368.58  5124.7  369.59
  5130.7  371.30  5146.8  371.65  5176.0  377.06  5226.9  376.45  5291.6  378.06
#Mann=5,-1,0
  4593.2    0.16       0  4787.6   0.035       0  4793.6    0.16       0
  4982.5    0.05       0  5009.0    0.16       0
Bank Sta=4786.7,5020.5
Exp/Cntr=0.3,0.1

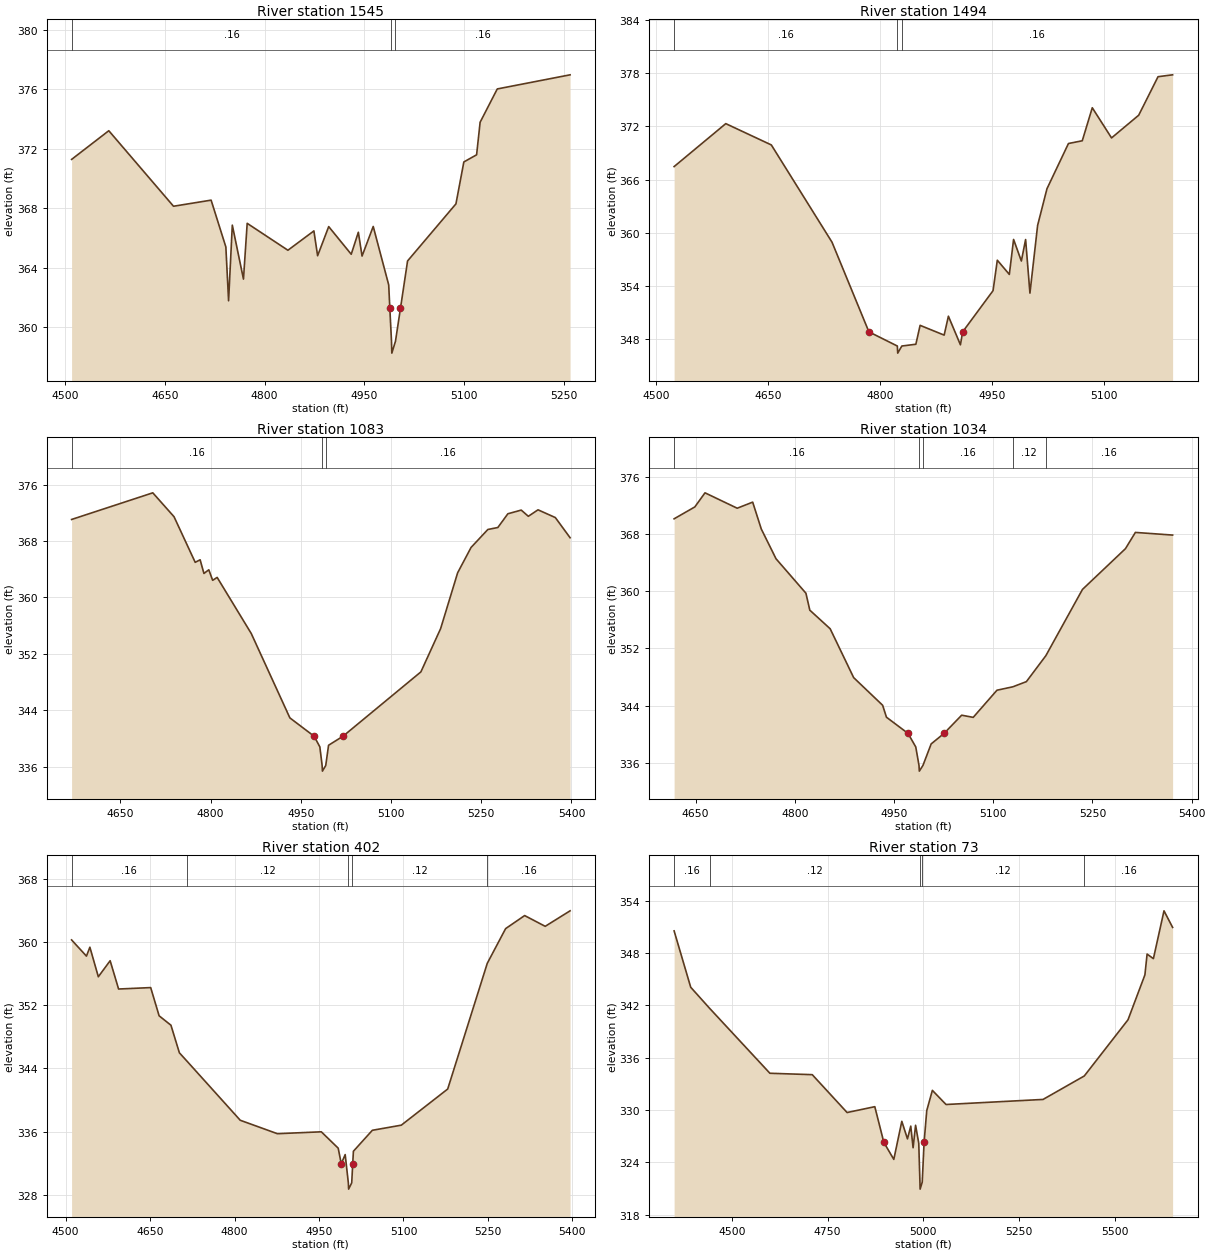
Type RM Length L Ch R = 1,1545,51,51,51
BEGIN DESCRIPTION:
Mapping XS e88bf983
END DESCRIPTION:
XS GIS Cut Line= 4
      2901320.05      6970693.22      2901542.72      6970643.74
      2901765.37      6970531.76      2901855.20      6970273.99
#Sta/Elev= 30
  4509.5  371.29  4565.5  373.22  4662.9  368.14  4719.5  368.55  4741.7  365.40
  4745.8  361.78  4751.4  366.87  4768.2  363.24  4773.8  366.99  4835.1  365.18
  4874.2  366.48  4879.8  364.81  4896.5  366.77  4930.4  364.91  4941.1  366.39
  4946.7  364.79  4963.5  366.78  4986.8  362.85  4988.5  361.27  4991.0  359.06
  4991.5  358.26  4997.0  359.06  5004.5  361.27  5015.2  364.46  5088.0  368.30
  5099.9  371.12  5119.1  371.60  5124.4  373.79  5150.2  376.03  5259.8  376.98
#Mann=3,-1,0
  4509.5    0.16       0  4991.0    0.07       0  4997.0    0.16       0
Bank Sta=4988.5,5004.5
Exp/Cntr=0.3,0.1

Type RM Length L Ch R = 1,1494,411,411,411
BEGIN DESCRIPTION:
Mapping XS 1181ec2a
END DESCRIPTION:
XS GIS Cut Line= 4
      2901336.95      6970711.45      2901614.33      6970660.66
      2901830.48      6970542.17      2901876.06      6970410.63
#Sta/Elev= 30
  4523.8  367.46  4593.0  372.30  4654.0  369.90  4735.3  358.94  4784.7  348.84
  4822.8  347.24  4823.3  346.44  4828.8  347.24  4847.6  347.44  4853.3  349.57
  4885.5  348.47  4891.2  350.60  4907.3  347.38  4910.3  348.84  4951.0  353.48
  4956.7  356.91  4972.8  355.31  4978.5  359.25  4988.9  356.82  4994.6  359.24
  5000.4  353.20  5010.7  360.84  5023.2  364.96  5052.0  370.06  5070.5  370.37
  5083.9  374.09  5109.7  370.69  5146.1  373.25  5172.0  377.59  5191.5  377.80
#Mann=3,-1,0
  4523.8    0.16       0  4822.8    0.07       0  4828.8    0.16       0
Bank Sta=4784.7,4910.3
Exp/Cntr=0.3,0.1

Type RM Length L Ch R = 1,1083,49,49,49
BEGIN DESCRIPTION:
Mapping XS bb243d74
END DESCRIPTION:
XS GIS Cut Line= 3
      2901626.55      6971155.84      2901902.61      6970801.65
      2902074.47      6970463.14
#Sta/Elev= 30
  4569.0  371.06  4704.0  374.84  4739.3  371.45  4774.5  364.98  4782.7  365.34
  4789.0  363.40  4797.1  363.92  4803.5  362.43  4811.0  362.84  4867.7  354.88
  4931.9  342.91  4972.2  340.31  4981.7  338.80  4985.5  336.16  4986.0  335.36
  4991.5  336.16  4996.2  339.03  5020.2  340.31  5149.7  349.44  5182.5  355.58
  5210.8  363.50  5233.1  367.09  5261.0  369.64  5277.6  369.92  5294.3  371.87
  5316.5  372.39  5328.3  371.51  5344.4  372.43  5373.2  371.33  5397.7  368.47
#Mann=3,-1,0
  4569.0    0.16       0  4985.5    0.07       0  4991.5    0.16       0
Bank Sta=4972.2,5020.2
Exp/Cntr=0.3,0.1

Type RM Length L Ch R = 1,1034,632,632,632
BEGIN DESCRIPTION:
Mapping XS c1539cbc
END DESCRIPTION:
XS GIS Cut Line= 3
      2901733.35      6971166.21      2901962.50      6970793.84
      2902141.08      6970532.45
#Sta/Elev= 30
  4617.4  370.10  4648.7  371.76  4664.1  373.73  4712.8  371.58  4736.2  372.43
  4749.2  368.68  4771.5  364.52  4816.7  359.71  4822.6  357.34  4853.4  354.74
  4888.9  347.92  4932.7  344.06  4938.5  342.39  4971.1  340.13  4982.8  338.24
  4987.7  335.66  4988.2  334.86  4993.7  335.66  5006.1  338.66  5025.6  340.13
  5052.2  342.67  5069.7  342.37  5105.6  346.16  5129.7  346.64  5150.1  347.36
  5179.5  350.98  5234.9  360.24  5299.9  365.93  5314.9  368.20  5371.2  367.83
#Mann=5,-1,0
  4617.4    0.16       0  4987.7    0.07       0  4993.7    0.16       0
  5129.7    0.12       0  5179.5    0.16       0
Bank Sta=4971.1,5025.6
Exp/Cntr=0.3,0.1

Type RM Length L Ch R = 1,402,329,329,329
BEGIN DESCRIPTION:
Mapping XS 425ee1f3
END DESCRIPTION:
XS GIS Cut Line= 3
      2901871.37      6971246.96      2902306.25      6970955.30
      2902220.33      6970603.78
#Sta/Elev= 30
  4510.5  360.25  4536.9  358.20  4543.0  359.33  4558.0  355.59  4579.0  357.62
  4594.0  354.04  4651.0  354.22  4666.0  350.65  4687.0  349.46  4702.0  345.97
  4715.3  344.93  4810.1  337.44  4876.1  335.74  4954.1  335.98  4984.1  333.91
  4989.5  331.94  4996.5  333.10  5002.1  329.53  5002.6  328.73  5008.1  329.53
  5009.9  331.94  5011.1  333.52  5044.7  336.17  5096.2  336.82  5178.6  341.39
  5248.9  357.29  5281.5  361.68  5315.3  363.33  5351.8  361.97  5396.0  363.93
#Mann=5,-1,0
  4510.5    0.16       0  4715.3    0.12       0  5002.1    0.07       0
  5008.1    0.12       0  5248.9    0.16       0
Bank Sta=4989.5,5009.9
Exp/Cntr=0.3,0.1

Type RM Length L Ch R = 1,73,0,0,0
BEGIN DESCRIPTION:
UNT 027 IN DRY CR WATERSHED 1.0
END DESCRIPTION:
XS GIS Cut Line= 4
      2901951.25      6971365.88      2902440.80      6971183.60
      2902628.30      6970920.57      2902417.39      6970514.36
#Sta/Elev= 30
  4348.6  350.53  4392.0  344.07  4441.5  341.65  4599.0  334.21  4709.7  334.05
  4800.8  329.71  4873.2  330.38  4896.9  326.28  4922.9  324.34  4943.8  328.70
  4958.6  326.69  4967.2  328.15  4973.3  325.67  4979.8  328.25  4988.1  326.19
  4991.2  321.73  4991.7  320.93  4997.2  321.73  5002.0  326.28  5009.0  329.93
  5023.7  332.25  5059.4  330.63  5313.0  331.21  5420.8  333.90  5535.1  340.34
  5579.3  345.49  5585.0  347.87  5601.5  347.35  5629.2  352.83  5651.7  350.93
#Mann=5,-1,0
  4348.6    0.16       0  4441.5    0.12       0  4991.2    0.07       0
  4997.2    0.12       0  5420.8    0.16       0
Bank Sta=4896.9,5002
Exp/Cntr=0.3,0.1

Chan Stop Cuts=-1