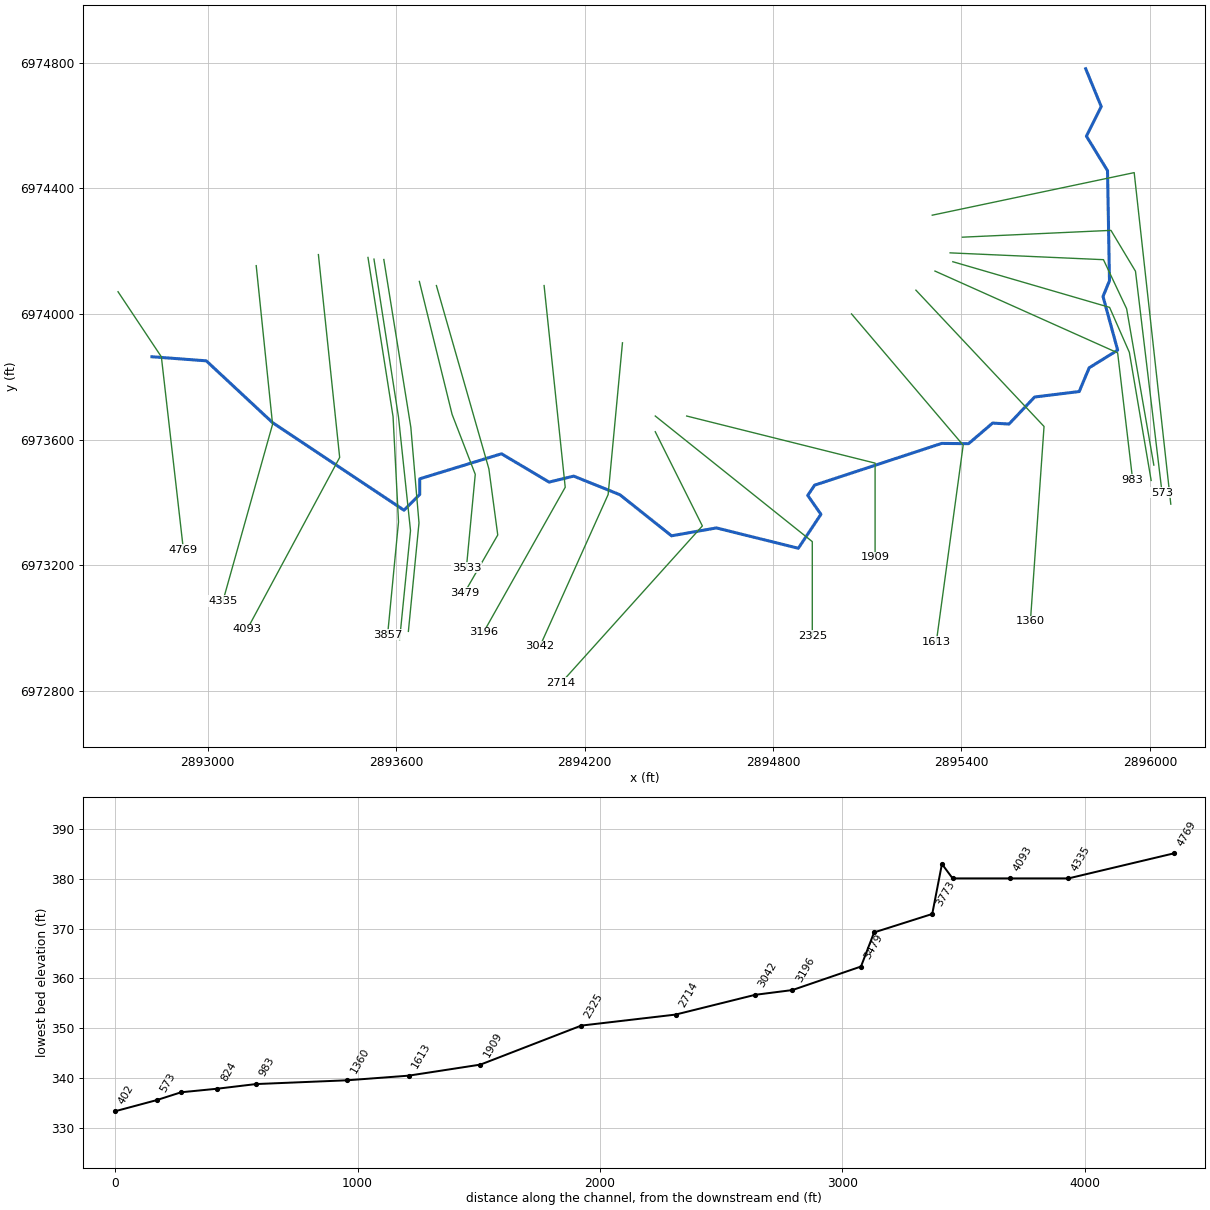
--- UNT 028 IN DRY CR WATERSHED.prj (project) ---

Proj Title=UNT 028 IN DRY CR WATERSHED Base Level Engineering
Current Plan=p01
Default Exp/Contr=0.3,0.1
English Units
Geom File=g01
Flow File=f01
Plan File=p01
BEGIN DESCRIPTION:
UNT 028 IN DRY CR WATERSHED
END DESCRIPTION:

--- UNT 028 IN DRY CR WATERSHED.p01 (plan) ---

Plan Title=Multiple Run
Short Identifier=Multiple
Geom File=g01
Flow File=f01
Subcritical Flow
K Sum by GR= 0
Std Step Tol= 0.01
Critical Tol= 0.01
Num of Std Step Trials= 20
Max Error Tol= 0.3
Flow Tol Ratio= 0.001
Split Flow NTrial= 30
Split Flow Tol= 0.02
Split Flow Ratio= 0.02
Log Output Level= 0
Friction Slope Method= 1
Unsteady Friction Slope Method= 2
Unsteady Bridges Friction Slope Method= 1
Parabolic Critical Depth
Global Vel Dist=  1 , 1 , 1
Global Log Level= 0
CheckData=True
Encroach Param= -1, 0, 0, 0
BEGIN DESCRIPTION:
Multiple Run
END DESCRIPTION:

--- UNT 028 IN DRY CR WATERSHED.f01 (steady flow) ---

Flow Title=Multiple
Number of Profiles=7
Profile Names=10-year,25-year,50-year,1pct_min,100-year,1pct_plu,500-year
River Rch & RM= UNT 028 IN DRY C,Reach-1,4769
     210     265     308     178     356     710     475
Boundary for River Rch & Prof#=UNT 028 IN DRY C,Reach-1,1
Up Type=0
Dn Type=3
Dn Slope=0.005
Boundary for River Rch & Prof#=UNT 028 IN DRY C,Reach-1,2
Up Type=0
Dn Type=3
Dn Slope=0.005
Boundary for River Rch & Prof#=UNT 028 IN DRY C,Reach-1,3
Up Type=0
Dn Type=3
Dn Slope=0.005
Boundary for River Rch & Prof#=UNT 028 IN DRY C,Reach-1,4
Up Type=0
Dn Type=3
Dn Slope=0.005
Boundary for River Rch & Prof#=UNT 028 IN DRY C,Reach-1,5
Up Type=0
Dn Type=3
Dn Slope=0.005
Boundary for River Rch & Prof#=UNT 028 IN DRY C,Reach-1,6
Up Type=0
Dn Type=3
Dn Slope=0.005
Boundary for River Rch & Prof#=UNT 028 IN DRY C,Reach-1,7
Up Type=0
Dn Type=3
Dn Slope=0.005

--- UNT 028 IN DRY CR WATERSHED.g01 (geometry) ---

Geom Title=Existing Conditions

River Reach=UNT 028 IN DRY C,Reach-1
Reach XY= 30
      2892822.23      6973863.70      2892995.40      6973850.68
      2893206.34      6973654.06      2893625.00      6973375.00
      2893675.00      6973425.00      2893675.00      6973475.00
      2893935.47      6973554.75      2894086.95      6973464.59
      2894165.28      6973483.62      2894312.46      6973424.34
      2894476.77      6973293.57      2894619.81      6973318.63
      2894880.56      6973253.89      2894952.48      6973362.02
      2894910.49      6973422.23      2894932.47      6973454.79
      2895336.89      6973587.78      2895422.48      6973586.84
      2895499.17      6973652.47      2895551.44      6973649.50
      2895632.96      6973735.49      2895774.96      6973752.97
      2895806.75      6973828.59      2895897.35      6973884.73
      2895850.73      6974055.73      2895871.33      6974105.58
      2895865.09      6974456.14      2895797.85      6974566.21
      2895845.11      6974660.27      2895795.59      6974780.71

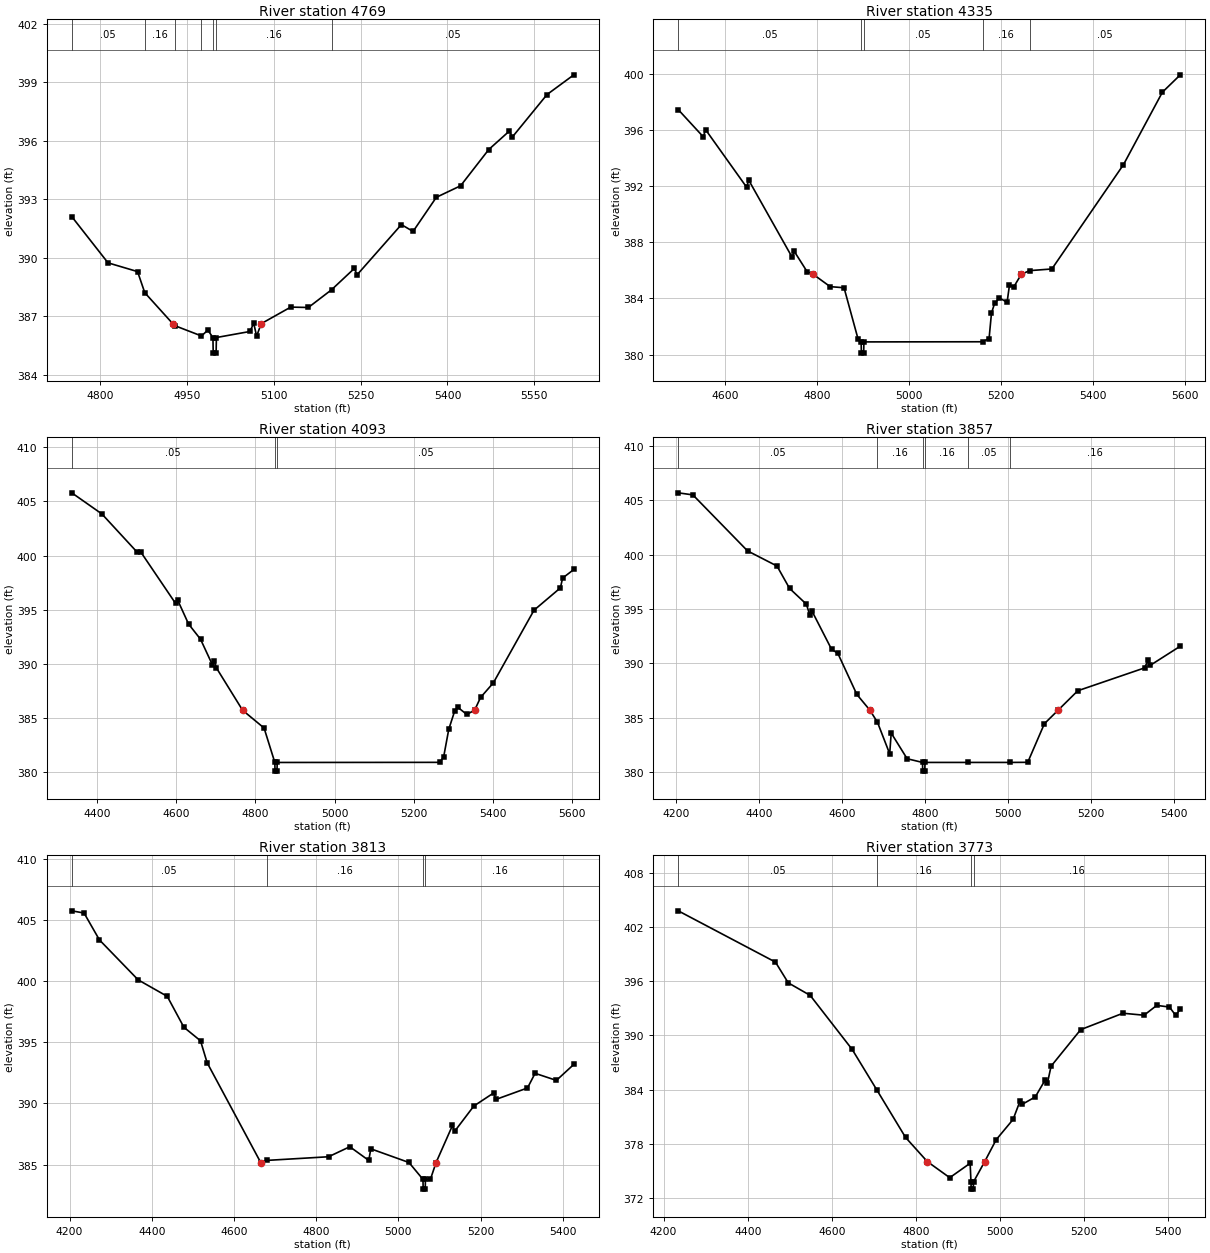
Type RM Length L Ch R = 1,4769,434,434,434
BEGIN DESCRIPTION:
UNT 028 IN DRY CR WATERSHED 10.0
END DESCRIPTION:
XS GIS Cut Line= 3
      2892714.39      6974070.73      2892852.42      6973863.37
      2892922.58      6973248.96
#Sta/Elev= 30
  4750.9  392.12  4813.5  389.75  4864.6  389.30  4877.0  388.22  4925.4  386.63
  4928.8  386.53  4975.0  386.00  4986.0  386.30  4994.8  385.92  4995.3  385.12
  5000.3  385.12  5000.8  385.92  5058.7  386.23  5065.3  386.65  5070.3  385.99
  5078.2  386.63  5129.2  387.48  5159.7  387.46  5199.8  388.37  5239.0  389.46
  5244.0  389.14  5320.4  391.71  5340.6  391.36  5380.8  393.11  5422.7  393.70
  5471.4  395.56  5507.1  396.51  5512.1  396.20  5572.1  398.38  5618.4  399.39
#Mann=7,-1,0
  4750.9    0.05       0  4877.0    0.16       0  4928.8    0.05       0
  4975.0    0.16       0  4994.8    0.07       0  5000.8    0.16       0
  5199.8    0.05       0
Bank Sta=4925.4,5078.2
Exp/Cntr=0.3,0.1

Type RM Length L Ch R = 1,4335,242,242,242
BEGIN DESCRIPTION:
Mapping XS aee02ce6
END DESCRIPTION:
XS GIS Cut Line= 3
      2893154.37      6974153.80      2893206.45      6973648.57
      2893048.46      6973086.05
#Sta/Elev= 30
  4498.1  397.46  4552.6  395.52  4557.6  396.03  4646.6  391.94  4651.6  392.42
  4745.6  386.95  4750.6  387.35  4778.4  385.91  4791.6  385.72  4828.6  384.84
  4858.8  384.76  4889.0  381.14  4896.0  380.90  4896.5  380.10  4901.5  380.10
  4902.0  380.90  5160.0  380.91  5174.3  381.14  5179.5  382.95  5186.3  383.65
  5196.7  384.03  5213.5  383.73  5218.7  384.96  5227.8  384.81  5244.4  385.72
  5262.3  385.98  5310.9  386.10  5466.7  393.54  5551.3  398.70  5590.3  399.94
#Mann=5,-1,0
  4498.1    0.05       0  4896.0   0.033       0  4902.0    0.05       0
  5160.0    0.16       0  5262.3    0.05       0
Bank Sta=4791.6,5244.4
Exp/Cntr=0.3,0.1

Type RM Length L Ch R = 1,4093,236,236,236
BEGIN DESCRIPTION:
Mapping XS de8fbaba
END DESCRIPTION:
XS GIS Cut Line= 3
      2893352.39      6974188.98      2893420.10      6973543.10
      2893125.85      6972996.26
#Sta/Elev= 30
  4335.2  405.80  4411.4  403.85  4499.6  400.36  4510.1  400.32  4597.8  395.59
  4602.8  395.92  4630.8  393.68  4661.0  392.28  4691.0  389.92  4696.0  390.29
  4701.2  389.63  4767.5  385.72  4821.8  384.08  4849.0  380.90  4849.5  380.10
  4854.5  380.10  4855.0  380.90  5266.4  380.91  5276.2  381.42  5289.1  383.96
  5303.7  385.61  5311.8  386.00  5334.5  385.34  5354.5  385.72  5369.5  386.90
  5401.9  388.25  5504.8  394.96  5571.5  397.02  5577.2  397.93  5605.6  398.72
#Mann=3,-1,0
  4335.2    0.05       0  4849.0   0.033       0  4855.0    0.05       0
Bank Sta=4767.5,5354.5
Exp/Cntr=0.3,0.1

Type RM Length L Ch R = 1,3857,44,44,44
BEGIN DESCRIPTION:
Mapping XS f540e601
END DESCRIPTION:
XS GIS Cut Line= 4
      2893510.27      6974179.86      2893590.13      6973672.88
      2893607.49      6973337.81      2893572.85      6972979.23
#Sta/Elev= 30
  4205.5  405.69  4240.8  405.50  4372.4  400.35  4443.3  398.96  4473.6  396.90
  4514.1  395.45  4522.1  394.47  4527.2  394.84  4574.9  391.29  4589.7  390.94
  4635.6  387.15  4666.9  385.71  4685.3  384.59  4714.7  381.69  4718.3  383.60
  4756.7  381.24  4793.7  380.90  4794.2  380.10  4799.2  380.10  4799.7  380.90
  4902.9  380.90  5004.0  380.90  5047.1  380.91  5087.2  384.46  5120.4  385.71
  5167.6  387.49  5328.3  389.59  5336.8  390.28  5341.8  389.82  5414.5  391.59
#Mann=6,-1,0
  4205.5    0.05       0  4685.3    0.16       0  4793.7   0.033       0
  4799.7    0.16       0  4902.9    0.05       0  5004.0    0.16       0
Bank Sta=4666.9,5120.4
Exp/Cntr=0.3,0.1

Type RM Length L Ch R = 1,3813,40,40,40
BEGIN DESCRIPTION:
Mapping XS 65555cfd
END DESCRIPTION:
XS GIS Cut Line= 4
      2893529.37      6974174.59      2893607.49      6973671.14
      2893645.69      6973310.03      2893610.96      6972962.76
#Sta/Elev= 30
  4205.3  405.77  4235.2  405.59  4272.6  403.39  4366.8  400.12  4437.6  398.77
  4478.1  396.24  4518.6  395.13  4534.6  393.34  4665.3  385.15  4679.2  385.34
  4830.1  385.64  4881.8  386.46  4927.9  385.34  4932.9  386.29  5025.7  385.17
  5059.8  383.79  5060.3  382.99  5065.3  382.99  5065.8  383.79  5077.9  383.79
  5091.5  385.15  5131.6  388.20  5136.6  387.71  5183.5  389.79  5232.1  390.87
  5237.1  390.33  5314.1  391.27  5332.6  392.47  5384.4  391.89  5426.9  393.20
#Mann=4,-1,0
  4205.3    0.05       0  4679.2    0.16       0  5059.8    0.07       0
  5065.8    0.16       0
Bank Sta=4665.3,5091.5
Exp/Cntr=0.3,0.1

Type RM Length L Ch R = 1,3773,240,240,240
BEGIN DESCRIPTION:
Mapping XS 51c3721e
END DESCRIPTION:
XS GIS Cut Line= 4
      2893560.73      6974173.30      2893646.67      6973639.46
      2893672.71      6973334.77      2893638.93      6972989.23
#Sta/Elev= 30
  4234.8  403.82  4466.0  398.13  4496.4  395.83  4548.5  394.44  4648.4  388.44
  4707.0  383.95  4775.2  378.69  4826.9  376.01  4880.3  374.22  4928.8  375.82
  4930.8  373.75  4931.3  372.95  4936.3  372.95  4936.8  373.75  4963.5  376.01
  4990.7  378.43  5030.9  380.68  5047.7  382.75  5052.8  382.36  5083.7  383.18
  5107.7  385.10  5112.7  384.75  5121.3  386.59  5191.6  390.64  5292.1  392.46
  5342.3  392.24  5372.5  393.33  5402.6  393.15  5417.6  392.22  5428.5  392.93
#Mann=4,-1,0
  4234.8    0.05       0  4707.0    0.16       0  4930.8    0.07       0
  4936.8    0.16       0
Bank Sta=4826.9,4963.5
Exp/Cntr=0.3,0.1

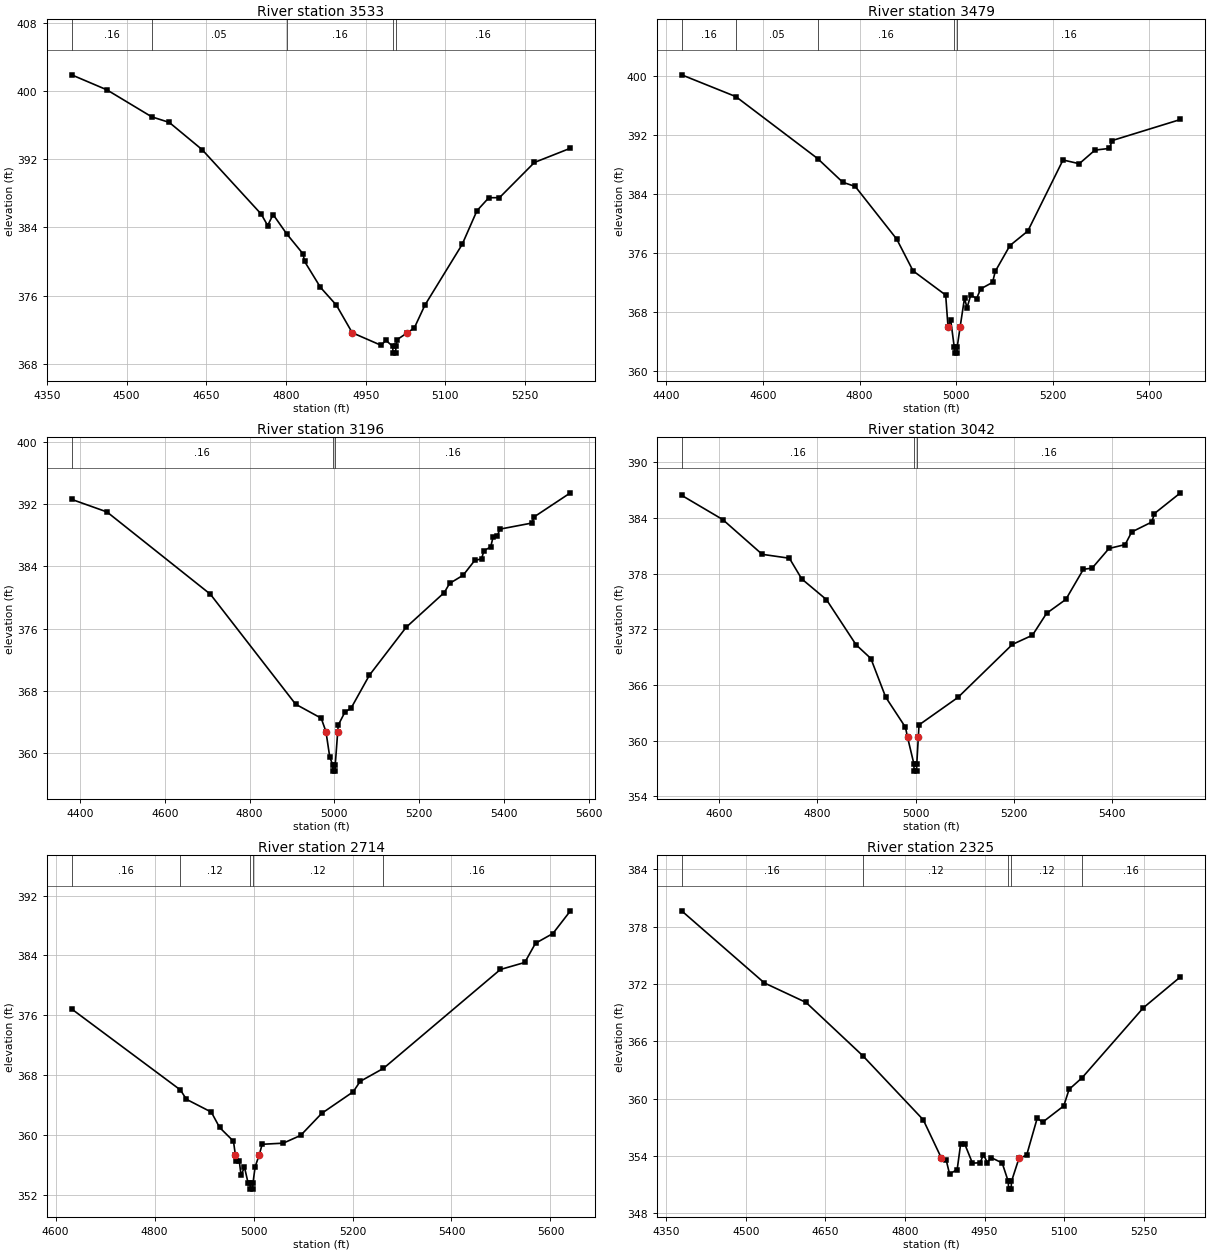
Type RM Length L Ch R = 1,3533,54,54,54
BEGIN DESCRIPTION:
Mapping XS cb37245b
END DESCRIPTION:
XS GIS Cut Line= 4
      2893673.90      6974103.44      2893778.07      6973680.26
      2893851.85      6973489.28      2893823.64      6973191.97
#Sta/Elev= 30
  4396.4  401.89  4462.8  400.13  4547.3  396.96  4580.2  396.31  4642.0  393.12
  4753.4  385.55  4765.5  384.21  4775.8  385.50  4801.4  383.23  4832.2  380.88
  4835.0  380.00  4865.0  376.95  4894.9  374.87  4924.8  371.63  4979.4  370.15
  4987.9  370.75  5001.0  370.04  5001.5  369.24  5006.5  369.24  5007.0  370.04
  5009.4  370.83  5028.5  371.63  5041.6  372.19  5061.5  374.86  5131.7  381.99
  5159.6  385.95  5181.9  387.47  5202.0  387.48  5267.8  391.61  5335.6  393.28
#Mann=5,-1,0
  4396.4    0.16       0  4547.3    0.05       0  4801.4    0.16       0
  5001.0    0.07       0  5007.0    0.16       0
Bank Sta=4924.8,5028.5
Exp/Cntr=0.3,0.1

Type RM Length L Ch R = 1,3479,283,283,283
BEGIN DESCRIPTION:
Mapping XS 8756595e
END DESCRIPTION:
XS GIS Cut Line= 4
      2893728.16      6974090.38      2893895.26      6973506.64
      2893923.47      6973296.14      2893817.12      6973111.66
#Sta/Elev= 30
  4431.8  400.21  4544.0  397.25  4713.3  388.83  4765.3  385.61  4791.1  385.04
  4877.0  377.88  4910.8  373.57  4978.3  370.28  4983.2  365.94  4988.7  366.89
  4996.1  363.19  4996.6  362.39  5001.6  362.39  5002.1  363.19  5008.2  365.94
  5017.3  369.87  5022.5  368.54  5030.3  370.30  5042.3  369.80  5050.7  371.12
  5075.3  372.00  5081.0  373.51  5111.3  377.01  5148.3  378.98  5221.2  388.64
  5254.8  388.13  5287.3  389.98  5317.3  390.21  5323.0  391.28  5464.3  394.14
#Mann=5,-1,0
  4431.8    0.16       0  4544.0    0.05       0  4713.3    0.16       0
  4996.1    0.07       0  5002.1    0.16       0
Bank Sta=4983.2,5008.2
Exp/Cntr=0.3,0.1

Type RM Length L Ch R = 1,3196,154,154,154
BEGIN DESCRIPTION:
Mapping XS d21bf4b6
END DESCRIPTION:
XS GIS Cut Line= 3
      2894071.04      6974090.38      2894138.31      6973448.05
      2893877.89      6972985.81
#Sta/Elev= 30
  4380.4  392.62  4463.8  391.00  4707.6  380.42  4908.7  366.27  4969.0  364.47
  4980.2  362.75  4989.1  359.51  4996.1  358.46  4996.6  357.66  5001.6  357.66
  5002.1  358.46  5008.0  362.75  5009.2  363.58  5025.3  365.29  5039.3  365.74
  5082.7  370.00  5169.3  376.16  5259.3  380.63  5271.9  381.81  5303.8  382.86
  5331.2  384.77  5347.1  384.96  5352.8  386.01  5368.7  386.50  5374.5  387.80
  5384.7  387.96  5390.4  388.79  5465.6  389.57  5471.3  390.37  5556.8  393.46
#Mann=3,-1,0
  4380.4    0.16       0  4996.1    0.07       0  5002.1    0.16       0
Bank Sta=4980.2,5008
Exp/Cntr=0.3,0.1

Type RM Length L Ch R = 1,3042,328,328,328
BEGIN DESCRIPTION:
UNT 028 IN DRY CR WATERSHED 8.0
END DESCRIPTION:
XS GIS Cut Line= 3
      2894320.60      6973908.09      2894275.00      6973425.00
      2894058.00      6972942.37
#Sta/Elev= 30
  4524.4  386.43  4607.9  383.82  4688.2  380.07  4743.5  379.65  4768.6  377.42
  4818.8  375.19  4879.1  370.32  4909.2  368.84  4939.3  364.68  4979.5  361.43
  4983.8  360.35  4996.6  357.50  4997.1  356.70  5002.1  356.70  5002.6  357.50
  5005.7  360.35  5007.1  361.68  5086.4  364.65  5197.0  370.36  5237.8  371.35
  5266.5  373.71  5305.7  375.21  5341.4  378.46  5359.1  378.58  5393.4  380.70
  5426.3  381.12  5439.6  382.48  5480.4  383.55  5485.9  384.47  5538.8  386.70
#Mann=3,-1,0
  4524.4    0.16       0  4996.6    0.07       0  5002.6    0.16       0
Bank Sta=4983.8,5005.7
Exp/Cntr=0.3,0.1

Type RM Length L Ch R = 1,2714,389,389,389
BEGIN DESCRIPTION:
UNT 028 IN DRY CR WATERSHED 7.0
END DESCRIPTION:
XS GIS Cut Line= 3
      2894424.99      6973625.03      2894575.00      6973325.00
      2894125.02      6972825.02
#Sta/Elev= 30
  4632.3  376.84  4852.2  366.00  4864.3  364.75  4914.6  363.04  4931.4  360.98
  4959.4  359.14  4963.4  357.24  4964.9  356.52  4971.1  356.52  4974.8  354.56
  4981.6  355.69  4989.0  353.53  4992.8  353.53  4993.3  352.73  4998.3  352.73
  4998.8  353.53  5003.2  355.72  5011.1  357.24  5017.4  358.73  5060.0  358.88
  5095.2  359.92  5137.8  362.87  5201.3  365.75  5215.5  367.15  5262.5  368.89
  5498.8  382.12  5548.1  383.06  5569.8  385.63  5604.9  386.93  5640.4  389.97
#Mann=5,-1,0
  4632.3    0.16       0  4852.2    0.12       0  4992.8    0.07       0
  4998.8    0.12       0  5262.5    0.16       0
Bank Sta=4963.4,5011.1
Exp/Cntr=0.3,0.1

Type RM Length L Ch R = 1,2325,416,416,416
BEGIN DESCRIPTION:
UNT 028 IN DRY CR WATERSHED 6.0
END DESCRIPTION:
XS GIS Cut Line= 3
      2894425.04      6973674.97      2894925.00      6973275.00
      2894925.00      6972974.97
#Sta/Elev= 30
  4378.9  379.65  4534.9  372.10  4613.4  370.06  4720.6  364.47  4834.3  357.78
  4868.7  353.75  4877.5  353.59  4883.9  352.10  4898.3  352.57  4904.7  355.20
  4912.7  355.22  4927.1  353.24  4941.5  353.28  4947.9  354.14  4955.1  353.29
  4962.3  353.82  4983.1  353.26  4994.6  351.32  4995.1  350.52  5000.1  350.52
  5000.6  351.32  5014.8  353.75  5029.2  354.07  5049.2  357.95  5059.2  357.52
  5099.2  359.23  5109.2  360.96  5133.8  362.18  5249.2  369.50  5319.2  372.74
#Mann=5,-1,0
  4378.9    0.16       0  4720.6    0.12       0  4994.6    0.07       0
  5000.6    0.12       0  5133.8    0.16       0
Bank Sta=4868.7,5014.8
Exp/Cntr=0.3,0.1

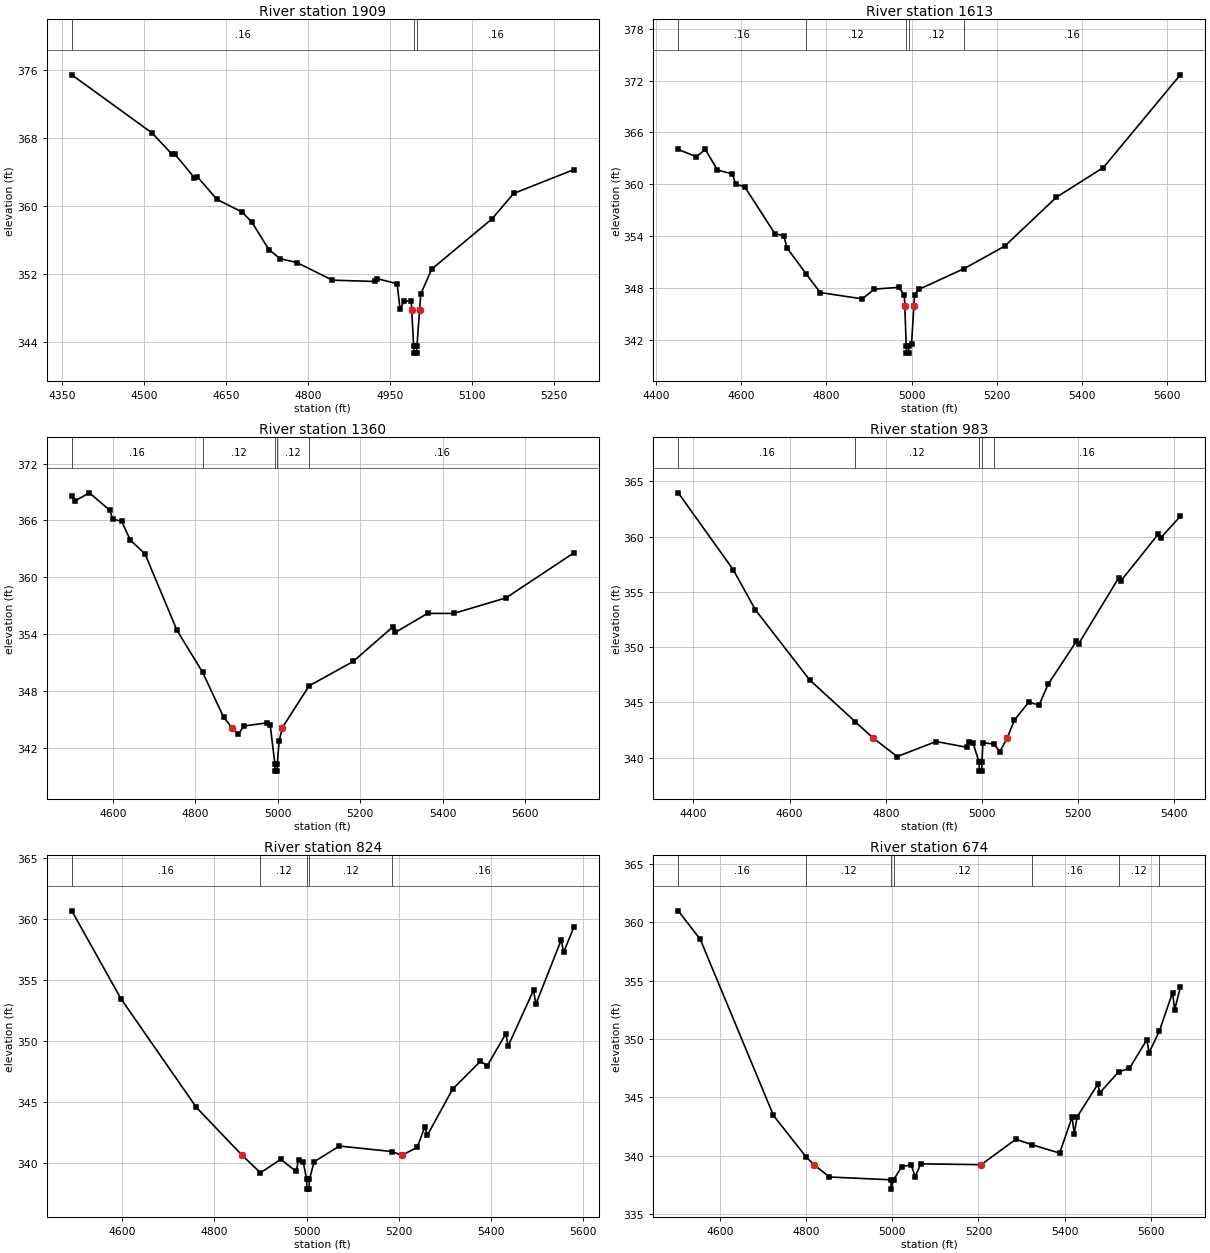
Type RM Length L Ch R = 1,1909,296,296,296
BEGIN DESCRIPTION:
UNT 028 IN DRY CR WATERSHED 5.0
END DESCRIPTION:
XS GIS Cut Line= 3
      2894525.03      6973674.99      2895125.00      6973525.00
      2895125.00      6973225.04
#Sta/Elev= 30
  4367.6  375.41  4514.5  368.57  4550.5  366.10  4555.7  366.12  4591.8  363.32
  4596.9  363.45  4633.0  360.77  4679.4  359.26  4697.4  358.05  4728.3  354.84
  4749.0  353.78  4779.9  353.32  4844.3  351.26  4921.6  351.11  4926.8  351.43
  4962.8  350.84  4968.0  347.88  4975.7  348.77  4988.5  348.81  4989.4  347.74
  4993.0  343.48  4993.5  342.68  4998.5  342.68  4999.0  343.48  5003.8  347.74
  5006.0  349.63  5026.0  352.56  5136.0  358.45  5176.0  361.46  5286.0  364.26
#Mann=3,-1,0
  4367.6    0.16       0  4993.0    0.07       0  4999.0    0.16       0
Bank Sta=4989.4,5003.8
Exp/Cntr=0.3,0.1

Type RM Length L Ch R = 1,1613,253,253,253
BEGIN DESCRIPTION:
UNT 028 IN DRY CR WATERSHED 4.0
END DESCRIPTION:
XS GIS Cut Line= 3
      2895050.01      6973999.98      2895405.46      6973582.11
      2895320.05      6972955.90
#Sta/Elev= 30
  4451.4  364.03  4494.2  363.19  4515.1  364.03  4543.6  361.65  4578.8  361.20
  4586.5  359.99  4607.3  359.74  4678.7  354.29  4699.6  354.04  4707.3  352.63
  4752.9  349.58  4785.3  347.47  4884.1  346.74  4912.6  347.87  4969.8  348.07
  4983.1  347.19  4984.1  345.92  4987.6  341.26  4988.1  340.46  4993.1  340.46
  4993.6  341.26  5000.0  341.52  5005.5  345.93  5007.2  347.24  5017.3  347.84
  5124.0  350.25  5219.1  352.84  5340.8  358.51  5451.2  361.94  5632.0  372.67
#Mann=5,-1,0
  4451.4    0.16       0  4752.9    0.12       0  4987.6    0.07       0
  4993.6    0.12       0  5124.0    0.16       0
Bank Sta=4984.1,5005.5
Exp/Cntr=0.3,0.1

Type RM Length L Ch R = 1,1360,377,377,377
BEGIN DESCRIPTION:
Mapping XS ca442bbc
END DESCRIPTION:
XS GIS Cut Line= 3
      2895254.95      6974075.75      2895662.94      6973641.71
      2895619.54      6973021.02
#Sta/Elev= 30
  4500.2  368.54  4507.8  368.06  4543.0  368.92  4592.8  367.06  4599.7  366.13
  4621.1  365.92  4642.2  363.93  4677.8  362.48  4755.5  354.39  4817.5  349.98
  4868.8  345.20  4888.4  344.13  4903.9  343.43  4918.1  344.30  4974.8  344.63
  4981.6  344.38  4992.8  340.33  4993.3  339.53  4998.3  339.53  4998.8  340.33
  5003.1  342.67  5011.0  344.13  5076.0  348.54  5182.8  351.11  5279.7  354.79
  5284.7  354.17  5363.3  356.19  5426.6  356.18  5553.7  357.83  5718.1  362.58
#Mann=5,-1,0
  4500.2    0.16       0  4817.5    0.12       0  4992.8    0.07       0
  4998.8    0.12       0  5076.0    0.16       0
Bank Sta=4888.4,5011
Exp/Cntr=0.3,0.1

Type RM Length L Ch R = 1,983,159,159,159
BEGIN DESCRIPTION:
Mapping XS 14570b81
END DESCRIPTION:
XS GIS Cut Line= 3
      2895315.72      6974136.51      2895897.32      6973876.09
      2895945.06      6973472.44
#Sta/Elev= 30
  4368.6  363.96  4482.6  357.02  4529.0  353.37  4641.7  347.03  4736.4  343.25
  4772.8  341.80  4823.7  340.09  4904.7  341.45  4968.4  340.93  4973.9  341.44
  4981.4  341.33  4994.0  339.57  4994.5  338.77  4999.5  338.77  5000.0  339.57
  5001.8  341.35  5024.3  341.22  5037.1  340.54  5052.8  341.80  5067.4  343.38
  5097.6  345.04  5118.3  344.72  5137.8  346.65  5196.1  350.51  5201.1  350.31
  5284.0  356.25  5289.0  356.00  5366.8  360.24  5371.9  359.90  5412.3  361.83
#Mann=5,-1,0
  4368.6    0.16       0  4736.4    0.12       0  4994.0    0.07       0
  5000.0    0.12       0  5024.3    0.16       0
Bank Sta=4772.8,5052.8
Exp/Cntr=0.3,0.1

Type RM Length L Ch R = 1,824,150,150,150
BEGIN DESCRIPTION:
Mapping XS 3c04c6c0
END DESCRIPTION:
XS GIS Cut Line= 4
      2895372.54      6974166.29      2895871.67      6974020.89
      2895934.61      6973877.66      2896004.02      6973469.85
#Sta/Elev= 30
  4490.4  360.65  4597.1  353.45  4760.9  344.54  4860.3  340.61  4900.1  339.18
  4944.0  340.28  4977.5  339.29  4982.7  340.23  4992.9  340.07  5000.3  338.64
  5000.8  337.84  5005.8  337.84  5006.3  338.64  5016.7  340.09  5071.3  341.37
  5186.0  340.92  5206.6  340.61  5240.4  341.26  5257.1  342.97  5262.1  342.24
  5317.3  346.04  5377.5  348.31  5392.6  347.96  5432.7  350.58  5437.7  349.57
  5492.9  354.14  5498.0  353.01  5553.1  358.27  5558.2  357.25  5580.4  359.31
#Mann=5,-1,0
  4490.4    0.16       0  4900.1    0.12       0  5000.3    0.07       0
  5006.3    0.12       0  5186.0    0.16       0
Bank Sta=4860.3,5206.6
Exp/Cntr=0.3,0.1

Type RM Length L Ch R = 1,674,101,101,101
BEGIN DESCRIPTION:
Mapping XS f3ffad3e
END DESCRIPTION:
XS GIS Cut Line= 4
      2895363.85      6974194.50      2895852.14      6974172.80
      2895925.92      6974016.55      2896012.51      6973518.69
#Sta/Elev= 30
  4502.2  361.00  4553.4  358.55  4723.6  343.44  4799.4  339.88  4817.7  339.22
  4853.7  338.16  4996.6  337.92  4997.1  337.12  5002.6  337.92  5021.7  339.05
  5043.8  339.19  5052.8  338.19  5066.0  339.29  5206.1  339.22  5287.1  341.40
  5323.6  340.94  5388.6  340.21  5417.5  343.29  5422.6  341.89  5429.2  343.31
  5477.1  346.11  5482.2  345.39  5525.6  347.18  5551.0  347.49  5591.3  349.94
  5596.4  348.82  5620.4  350.68  5651.0  353.98  5656.0  352.52  5669.1  354.43
#Mann=7,-1,0
  4502.2    0.16       0  4799.4    0.12       0  4996.6    0.07       0
  5002.6    0.12       0  5323.6    0.16       0  5525.6    0.12       0
  5620.4    0.16       0
Bank Sta=4817.7,5206.1
Exp/Cntr=0.3,0.1

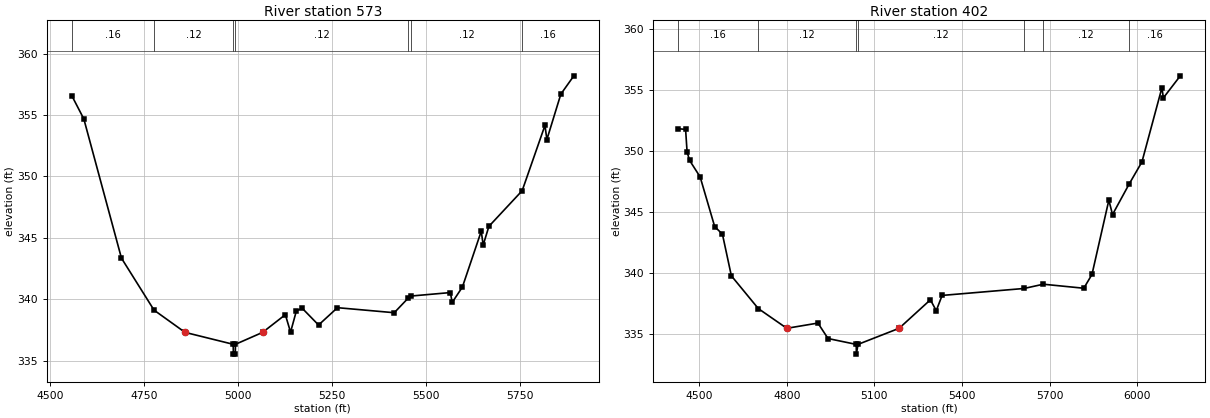
Type RM Length L Ch R = 1,573,171,171,171
BEGIN DESCRIPTION:
Mapping XS 1b390093
END DESCRIPTION:
XS GIS Cut Line= 4
      2895402.92      6974244.42      2895876.01      6974266.12
      2895954.14      6974135.91      2896038.77      6973430.61
#Sta/Elev= 30
  4557.0  356.58  4589.1  354.68  4689.2  343.35  4775.9  339.12  4858.4  337.31
  4986.5  336.34  4987.0  335.54  4992.0  335.54  4992.5  336.34  5064.7  337.31
  5125.2  338.75  5139.1  337.33  5154.7  339.07  5170.2  339.27  5213.6  337.91
  5263.9  339.32  5415.0  338.91  5452.4  340.11  5460.5  340.27  5564.2  340.55
  5569.2  339.75  5596.3  341.00  5646.5  345.55  5651.5  344.41  5666.8  345.94
  5755.3  348.84  5816.0  354.16  5821.0  353.00  5858.2  356.70  5892.8  358.19
#Mann=7,-1,0
  4557.0    0.16       0  4775.9    0.12       0  4986.5    0.07       0
  4992.5    0.12       0  5452.4    0.16       0  5460.5    0.12       0
  5755.3    0.16       0
Bank Sta=4858.4,5064.7
Exp/Cntr=0.3,0.1

Type RM Length L Ch R = 1,402,0,0,0
BEGIN DESCRIPTION:
UNT 028 IN DRY CR WATERSHED 3.0
END DESCRIPTION:
XS GIS Cut Line= 3
      2895307.00      6974314.45      2895950.00      6974450.00
      2896066.58      6973394.35
#Sta/Elev= 30
  4428.5  351.82  4453.7  351.76  4458.8  349.91  4467.3  349.22  4503.5  347.86
  4553.3  343.78  4579.8  343.16  4610.4  339.74  4702.7  337.05  4800.3  335.43
  4906.8  335.86  4941.4  334.59  5038.0  334.11  5038.5  333.31  5044.0  334.11
  5184.8  335.43  5291.9  337.77  5312.0  336.88  5332.1  338.13  5612.4  338.70
  5678.7  339.05  5817.2  338.72  5845.2  339.85  5903.0  345.95  5915.6  344.77
  5973.3  347.31  6016.3  349.09  6084.7  355.18  6089.7  354.35  6147.7  356.16
#Mann=7,-1,0
  4428.5    0.16       0  4702.7    0.12       0  5038.0    0.07       0
  5044.0    0.12       0  5612.4    0.16       0  5678.7    0.12       0
  5973.3    0.16       0
Bank Sta=4800.3,5184.8
Exp/Cntr=0.3,0.1

Chan Stop Cuts=-1