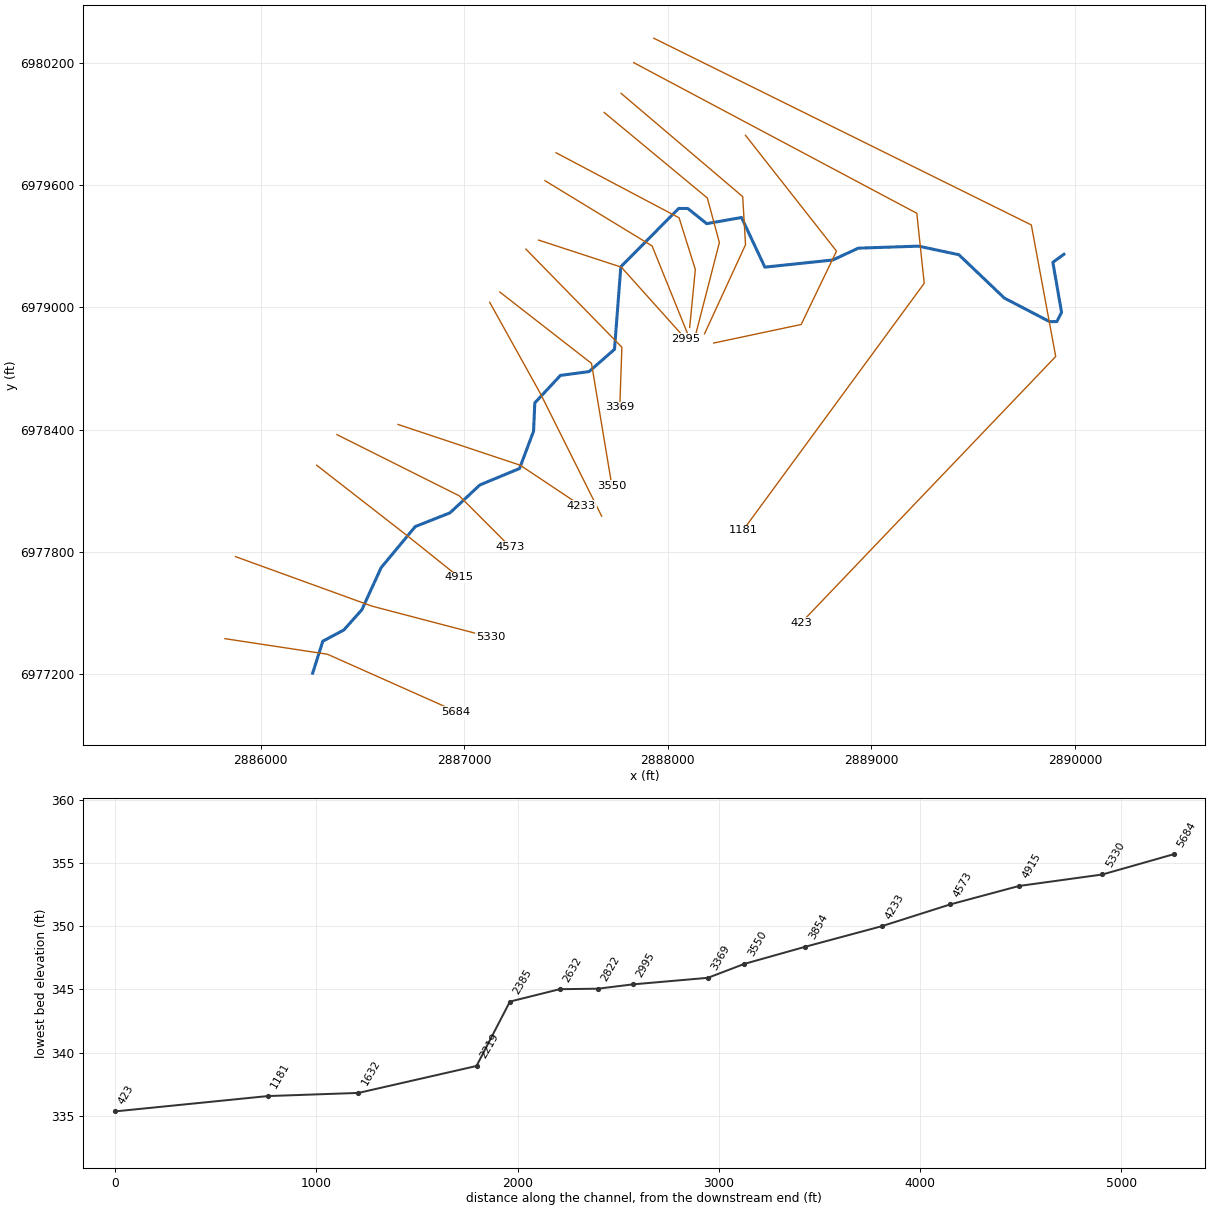
--- UNT 029 IN DRY CR WATERSHED.prj (project) ---

Proj Title=UNT 029 IN DRY CR WATERSHED Base Level Engineering
Current Plan=p01
Default Exp/Contr=0.3,0.1
English Units
Geom File=g01
Flow File=f01
Plan File=p01
BEGIN DESCRIPTION:
UNT 029 IN DRY CR WATERSHED
END DESCRIPTION:

--- UNT 029 IN DRY CR WATERSHED.p01 (plan) ---

Plan Title=Multiple Run
Short Identifier=Multiple
Geom File=g01
Flow File=f01
Subcritical Flow
K Sum by GR= 0
Std Step Tol= 0.01
Critical Tol= 0.01
Num of Std Step Trials= 20
Max Error Tol= 0.3
Flow Tol Ratio= 0.001
Split Flow NTrial= 30
Split Flow Tol= 0.02
Split Flow Ratio= 0.02
Log Output Level= 0
Friction Slope Method= 1
Unsteady Friction Slope Method= 2
Unsteady Bridges Friction Slope Method= 1
Parabolic Critical Depth
Global Vel Dist=  1 , 1 , 1
Global Log Level= 0
CheckData=True
Encroach Param= -1, 0, 0, 0
BEGIN DESCRIPTION:
Multiple Run
END DESCRIPTION:

--- UNT 029 IN DRY CR WATERSHED.f01 (steady flow) ---

Flow Title=Multiple
Number of Profiles=7
Profile Names=10-year,25-year,50-year,1pct_min,100-year,1pct_plu,500-year
River Rch & RM= UNT 029 IN DRY C,Reach-1,5684
     555     743     897     538    1074    2142    1541
Boundary for River Rch & Prof#=UNT 029 IN DRY C,Reach-1,1
Up Type=0
Dn Type=3
Dn Slope=0.005
Boundary for River Rch & Prof#=UNT 029 IN DRY C,Reach-1,2
Up Type=0
Dn Type=3
Dn Slope=0.005
Boundary for River Rch & Prof#=UNT 029 IN DRY C,Reach-1,3
Up Type=0
Dn Type=3
Dn Slope=0.005
Boundary for River Rch & Prof#=UNT 029 IN DRY C,Reach-1,4
Up Type=0
Dn Type=3
Dn Slope=0.005
Boundary for River Rch & Prof#=UNT 029 IN DRY C,Reach-1,5
Up Type=0
Dn Type=3
Dn Slope=0.005
Boundary for River Rch & Prof#=UNT 029 IN DRY C,Reach-1,6
Up Type=0
Dn Type=3
Dn Slope=0.005
Boundary for River Rch & Prof#=UNT 029 IN DRY C,Reach-1,7
Up Type=0
Dn Type=3
Dn Slope=0.005

--- UNT 029 IN DRY CR WATERSHED.g01 (geometry) ---

Geom Title=Existing Conditions

River Reach=UNT 029 IN DRY C,Reach-1
Reach XY= 30
      2886255.34      6977203.94      2886305.21      6977361.06
      2886408.17      6977415.66      2886497.06      6977515.29
      2886591.69      6977721.98      2886759.44      6977923.76
      2886930.01      6977991.17      2887076.68      6978128.07
      2887271.47      6978208.78      2887340.47      6978391.74
      2887346.53      6978531.02      2887472.58      6978665.95
      2887613.30      6978684.76      2887738.02      6978793.97
      2887769.12      6979199.24      2888053.15      6979485.62
      2888097.99      6979485.58      2888190.77      6979411.09
      2888361.97      6979441.30      2888476.57      6979197.46
      2888810.08      6979232.50      2888935.62      6979290.64
      2889231.33      6979300.58      2889429.63      6979258.39
      2889652.75      6979045.78      2889875.89      6978929.74
      2889910.87      6978930.25      2889934.02      6978975.82
      2889891.35      6979221.05      2889945.59      6979260.71

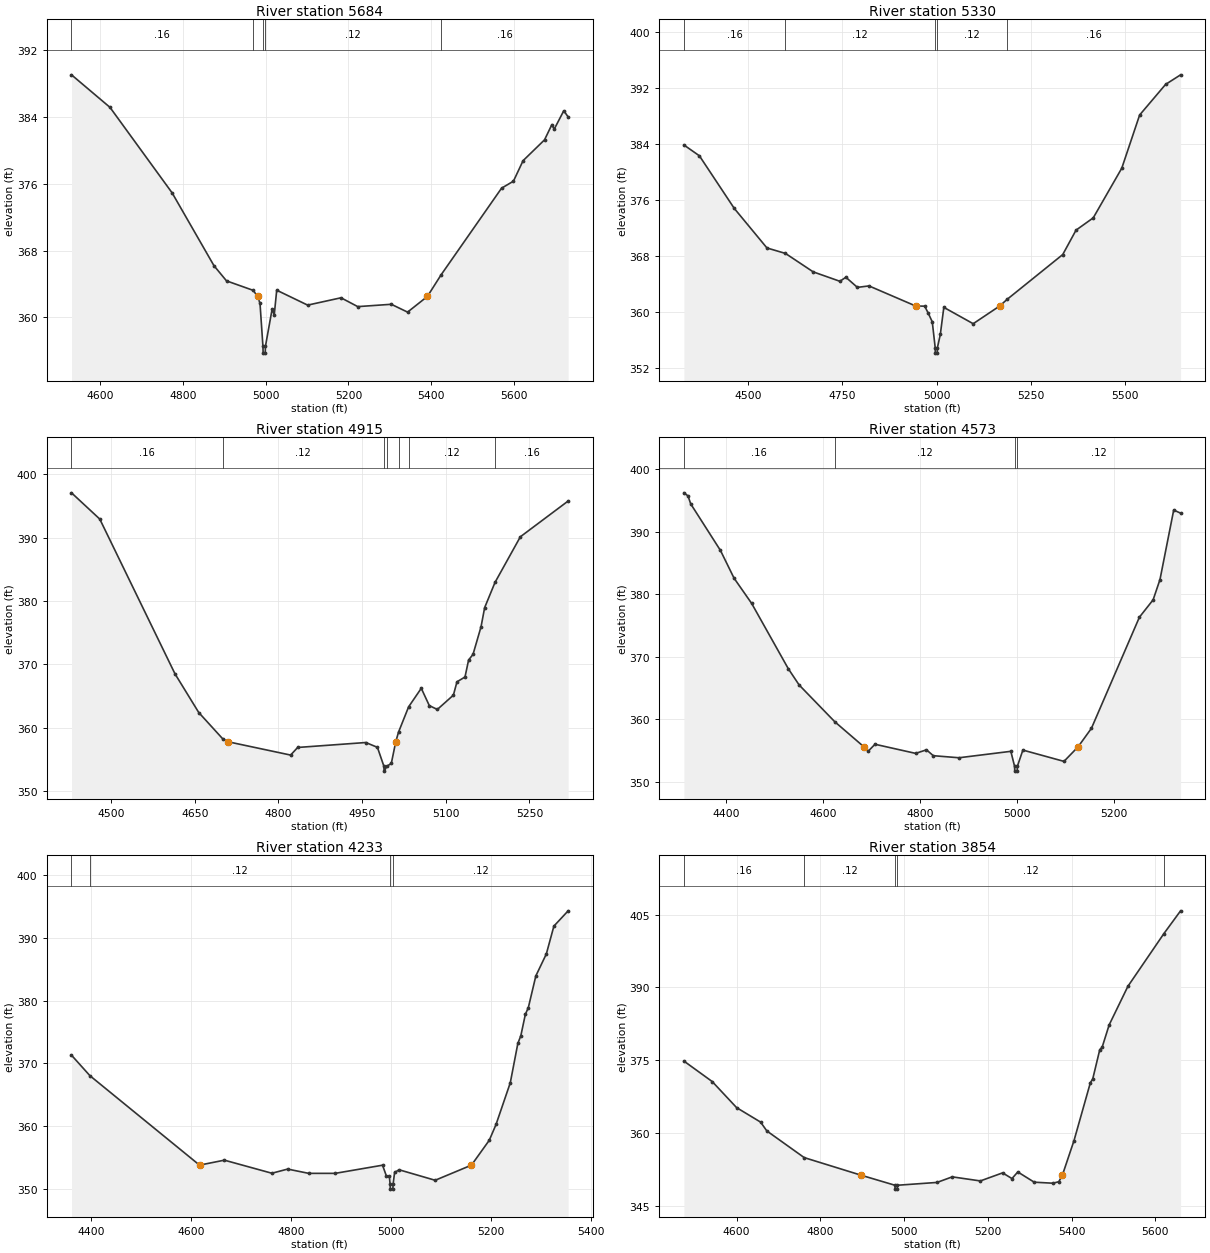
Type RM Length L Ch R = 1,5684,354,354,354
BEGIN DESCRIPTION:
UNT 029 IN DRY CR WATERSHED 9.0
END DESCRIPTION:
XS GIS Cut Line= 3
      2885824.40      6977373.39      2886327.83      6977297.01
      2886959.78      6977015.76
#Sta/Elev= 30
  4530.4  389.08  4623.4  385.18  4773.8  374.91  4874.9  366.18  4905.2  364.36
  4969.8  363.22  4980.3  362.49  4986.2  361.67  4993.3  356.49  4993.8  355.69
  4998.8  355.69  4999.3  356.49  5015.5  360.97  5020.6  360.26  5026.6  363.24
  5101.4  361.45  5182.0  362.33  5222.6  361.27  5303.7  361.55  5343.0  360.61
  5390.9  362.49  5424.3  365.10  5570.3  375.48  5599.0  376.32  5622.3  378.78
  5674.2  381.28  5692.0  383.11  5697.5  382.55  5720.7  384.77  5731.3  384.03
#Mann=5,-1,0
  4530.4    0.16       0  4969.8    0.12       0  4993.3    0.07       0
  4999.3    0.12       0  5424.3    0.16       0
Bank Sta=4980.3,5390.9
Exp/Cntr=0.3,0.1

Type RM Length L Ch R = 1,5330,415,415,415
BEGIN DESCRIPTION:
Mapping XS 4fb9eda3
END DESCRIPTION:
XS GIS Cut Line= 3
      2885876.42      6977776.18      2886546.58      6977533.12
      2887129.93      6977380.34
#Sta/Elev= 30
  4330.5  383.88  4371.5  382.33  4463.9  374.80  4550.5  369.14  4599.5  368.36
  4673.0  365.72  4743.8  364.37  4759.5  364.95  4790.1  363.50  4820.8  363.71
  4944.3  360.84  4968.5  360.81  4977.9  359.79  4988.5  358.57  4996.2  354.89
  4996.7  354.09  5001.7  354.09  5002.2  354.89  5009.8  356.76  5019.1  360.64
  5096.9  358.30  5167.2  360.84  5186.5  361.77  5334.2  368.20  5369.4  371.69
  5415.0  373.45  5490.6  380.56  5537.9  388.17  5606.7  392.55  5646.4  393.92
#Mann=5,-1,0
  4330.5    0.16       0  4599.5    0.12       0  4996.2    0.07       0
  5002.2    0.12       0  5186.5    0.16       0
Bank Sta=4944.3,5167.2
Exp/Cntr=0.3,0.1

Type RM Length L Ch R = 1,4915,342,342,342
BEGIN DESCRIPTION:
UNT 029 IN DRY CR WATERSHED 8.0
END DESCRIPTION:
XS GIS Cut Line= 3
      2886274.97      6978225.02      2886725.00      6977875.00
      2886975.01      6977674.99
#Sta/Elev= 30
  4429.1  397.05  4479.8  392.91  4614.6  368.52  4657.2  362.42  4700.0  358.29
  4709.1  357.82  4821.9  355.71  4834.5  356.91  4956.7  357.69  4977.5  356.93
  4989.0  353.98  4989.5  353.18  4995.0  353.98  5002.4  354.40  5010.4  357.82
  5015.3  359.32  5033.4  363.31  5056.1  366.24  5070.5  363.51  5084.9  362.90
  5113.7  365.16  5120.1  367.26  5134.5  368.02  5140.9  370.69  5148.9  371.59
  5163.3  375.96  5169.7  378.95  5188.3  382.93  5233.7  390.12  5319.4  395.76
#Mann=7,-1,0
  4429.1    0.16       0  4700.0    0.12       0  4989.0    0.07       0
  4995.0    0.12       0  5015.3    0.16       0  5033.4    0.12       0
  5188.3    0.16       0
Bank Sta=4709.1,5010.4
Exp/Cntr=0.3,0.1

Type RM Length L Ch R = 1,4573,340,340,340
BEGIN DESCRIPTION:
UNT 029 IN DRY CR WATERSHED 7.0
END DESCRIPTION:
XS GIS Cut Line= 3
      2886375.02      6978374.99      2886975.00      6978075.00
      2887225.03      6977824.97
#Sta/Elev= 30
  4312.6  396.26  4321.0  395.77  4326.6  394.49  4388.0  387.03  4416.0  382.60
  4452.3  378.56  4527.8  368.12  4550.2  365.51  4623.8  359.62  4683.7  355.62
  4692.7  354.91  4706.7  356.02  4790.5  354.56  4812.9  355.13  4826.9  354.19
  4880.0  353.86  4986.9  354.89  4994.5  352.52  4995.0  351.72  5000.0  351.72
  5000.5  352.52  5011.7  355.09  5096.5  353.28  5125.7  355.62  5153.1  358.57
  5252.1  376.36  5280.4  379.14  5294.5  382.38  5322.8  393.50  5337.0  393.01
#Mann=4,-1,0
  4312.6    0.16       0  4623.8    0.12       0  4994.5    0.07       0
  5000.5    0.12       0
Bank Sta=4683.7,5125.7
Exp/Cntr=0.3,0.1

Type RM Length L Ch R = 1,4233,379,379,379
BEGIN DESCRIPTION:
UNT 029 IN DRY CR WATERSHED 6.0
END DESCRIPTION:
XS GIS Cut Line= 3
      2886675.00      6978425.00      2887275.00      6978225.00
      2887574.99      6978025.01
#Sta/Elev= 30
  4361.0  371.32  4397.9  368.05  4617.0  353.82  4666.7  354.61  4761.6  352.53
  4793.2  353.19  4835.3  352.51  4888.1  352.51  4982.9  353.81  4990.8  352.04
  4996.5  352.04  4998.0  350.80  4998.5  350.00  5003.5  350.00  5004.0  350.80
  5007.0  352.65  5016.0  353.08  5088.1  351.41  5160.7  353.82  5196.3  357.78
  5209.8  360.29  5238.3  366.93  5253.4  373.19  5259.4  374.42  5268.4  377.81
  5274.4  378.90  5289.4  383.94  5310.4  387.44  5325.5  391.87  5354.0  394.30
#Mann=4,-1,0
  4361.0    0.16       0  4397.9    0.12       0  4998.0    0.07       0
  5004.0    0.12       0
Bank Sta=4617,5160.7
Exp/Cntr=0.3,0.1

Type RM Length L Ch R = 1,3854,304,304,304
BEGIN DESCRIPTION:
UNT 029 IN DRY CR WATERSHED 5.0
END DESCRIPTION:
XS GIS Cut Line= 3
      2887125.02      6979024.96      2887375.00      6978575.00
      2887675.02      6977974.96
#Sta/Elev= 30
  4474.5  374.78  4542.0  370.56  4600.3  365.18  4657.5  362.20  4672.4  360.38
  4761.6  354.88  4896.7  351.27  4978.2  349.18  4978.7  348.38  4983.7  348.38
  4984.2  349.18  5078.7  349.76  5115.0  350.91  5182.1  350.07  5235.2  351.73
  5257.6  350.56  5271.5  351.92  5310.7  349.81  5355.4  349.60  5369.4  349.91
  5378.0  351.27  5405.7  358.39  5444.8  370.34  5450.4  371.10  5467.2  377.14
  5472.8  377.62  5489.6  382.24  5534.3  390.19  5620.3  401.07  5660.1  405.76
#Mann=5,-1,0
  4474.5    0.16       0  4761.6    0.12       0  4978.2    0.07       0
  4984.2    0.12       0  5620.3    0.05       0
Bank Sta=4896.7,5378
Exp/Cntr=0.3,0.1

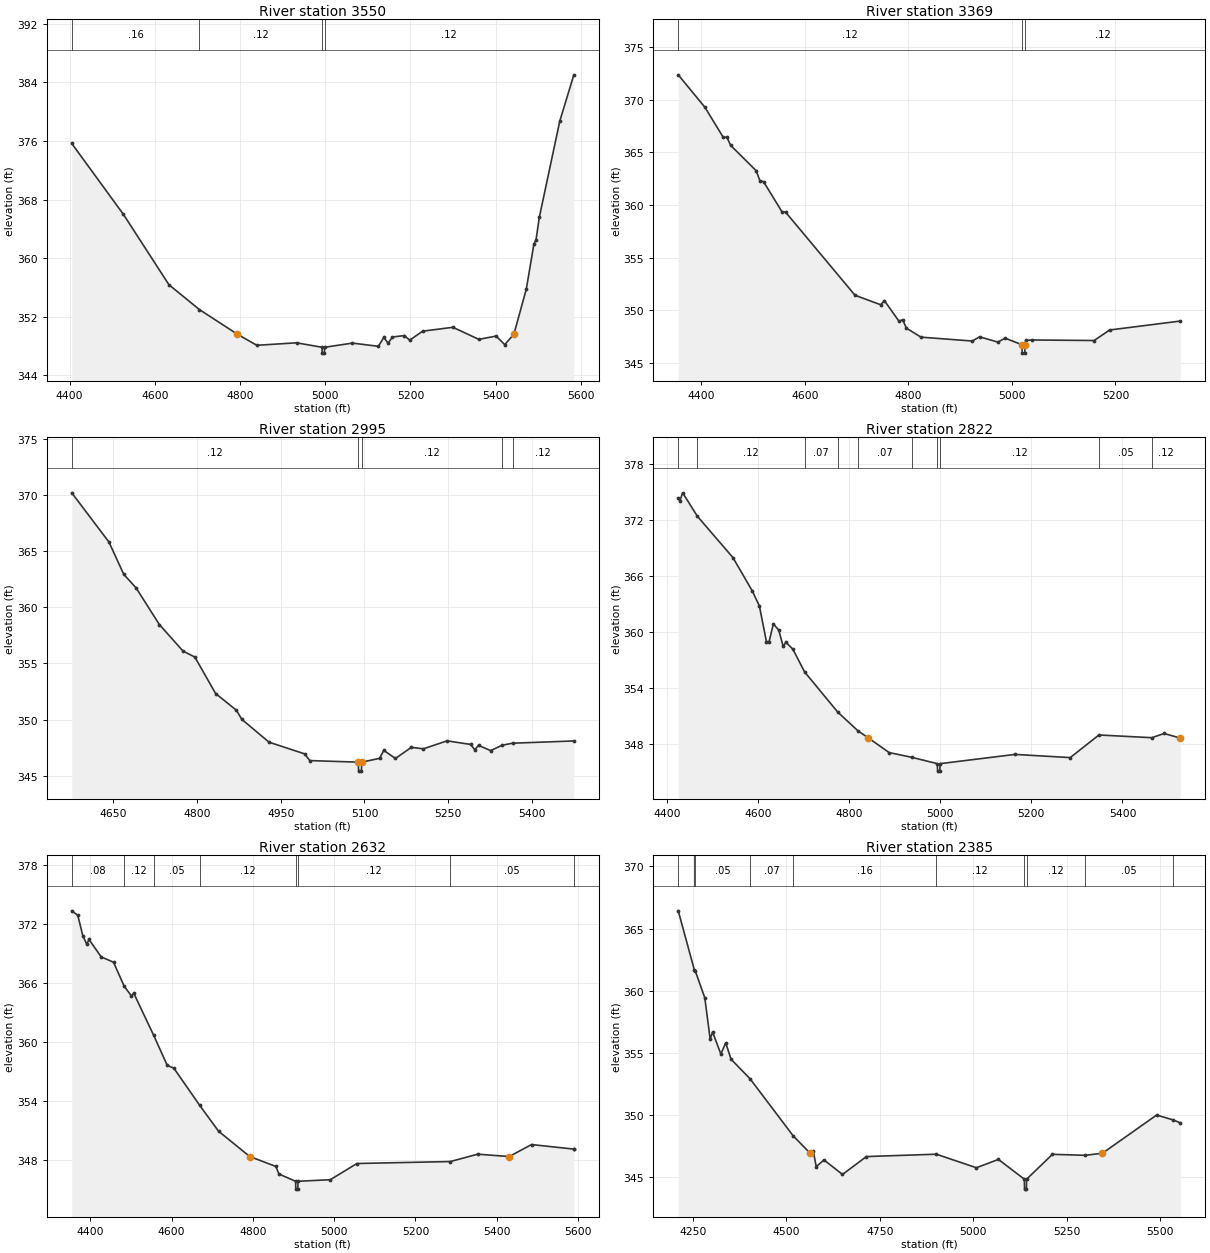
Type RM Length L Ch R = 1,3550,181,181,181
BEGIN DESCRIPTION:
UNT 029 IN DRY CR WATERSHED 4.0
END DESCRIPTION:
XS GIS Cut Line= 3
      2887174.98      6979075.01      2887625.00      6978725.00
      2887725.00      6978124.99
#Sta/Elev= 30
  4405.0  375.66  4526.3  365.97  4633.1  356.36  4704.6  352.97  4793.8  349.60
  4839.4  348.09  4932.6  348.43  4992.4  347.82  4992.9  347.02  4997.9  347.02
  4998.4  347.82  5063.8  348.39  5124.6  347.95  5137.3  349.16  5147.5  348.38
  5157.6  349.22  5185.5  349.42  5198.1  348.79  5228.6  350.02  5299.5  350.55
  5360.4  348.90  5400.9  349.35  5421.2  348.18  5442.7  349.60  5471.9  355.79
  5489.6  361.90  5494.7  362.51  5502.3  365.56  5550.4  378.72  5583.4  385.04
#Mann=4,-1,0
  4405.0    0.16       0  4704.6    0.12       0  4992.4    0.07       0
  4998.4    0.12       0
Bank Sta=4793.8,5442.7
Exp/Cntr=0.3,0.1

Type RM Length L Ch R = 1,3369,374,374,374
BEGIN DESCRIPTION:
Mapping XS 0d723259
END DESCRIPTION:
XS GIS Cut Line= 3
      2887302.95      6979285.94      2887774.29      6978804.19
      2887763.92      6978508.64
#Sta/Elev= 30
  4355.5  372.38  4407.1  369.29  4442.4  366.44  4449.6  366.44  4456.6  365.68
  4506.1  363.26  4513.1  362.32  4520.3  362.22  4555.6  359.38  4562.7  359.33
  4697.0  351.42  4746.6  350.52  4753.6  350.92  4781.9  348.95  4789.0  349.10
  4796.0  348.30  4824.3  347.44  4923.3  347.07  4937.5  347.47  4972.8  346.97
  4986.9  347.34  5019.3  346.72  5019.8  345.92  5024.8  345.92  5025.3  346.72
  5026.4  347.13  5038.7  347.17  5158.7  347.12  5188.8  348.12  5325.2  348.97
#Mann=3,-1,0
  4355.5    0.12       0  5019.3    0.07       0  5025.3    0.12       0
Bank Sta=5019.3,5025.3
Exp/Cntr=0.3,0.1

Type RM Length L Ch R = 1,2995,173,173,173
BEGIN DESCRIPTION:
Mapping XS 5c2ce8d6
END DESCRIPTION:
XS GIS Cut Line= 3
      2887365.43      6979330.23      2887771.68      6979197.42
      2888086.78      6978845.87
#Sta/Elev= 30
  4575.6  370.21  4642.1  365.83  4668.7  362.95  4690.9  361.73  4732.5  358.47
  4775.0  356.10  4796.1  355.57  4833.3  352.32  4870.5  350.83  4880.2  350.02
  4929.0  347.98  4992.7  346.94  5002.1  346.34  5089.0  346.20  5089.5  345.40
  5094.5  345.40  5095.0  346.20  5127.1  346.54  5134.6  347.25  5155.5  346.53
  5183.9  347.52  5205.6  347.39  5248.0  348.10  5290.1  347.78  5297.6  347.31
  5304.3  347.70  5326.0  347.23  5346.7  347.71  5365.5  347.89  5475.1  348.09
#Mann=5,-1,0
  4575.6    0.12       0  5089.0    0.07       0  5095.0    0.12       0
  5346.7    0.05       0  5365.5    0.12       0
Bank Sta=5089,5095
Exp/Cntr=0.3,0.1

Type RM Length L Ch R = 1,2822,190,190,190
BEGIN DESCRIPTION:
Mapping XS c386623e
END DESCRIPTION:
XS GIS Cut Line= 3
      2887396.70      6979621.89      2887922.72      6979301.58
      2888105.03      6978851.04
#Sta/Elev= 30
  4425.1  374.26  4428.8  374.03  4434.8  374.86  4467.1  372.35  4545.1  367.93
  4587.7  364.35  4603.2  362.74  4618.7  358.93  4624.5  358.92  4633.9  360.83
  4645.8  360.15  4655.4  358.41  4661.3  358.87  4676.8  358.11  4702.3  355.69
  4775.4  351.37  4819.9  349.36  4842.2  348.62  4887.9  347.05  4937.5  346.54
  4993.8  345.86  4994.3  345.06  4999.3  345.06  4999.8  345.86  5164.2  346.85
  5285.4  346.51  5348.4  348.93  5464.5  348.64  5491.4  349.09  5527.0  348.60
#Mann=10,-1,0
  4425.1    0.05       0  4467.1    0.12       0  4702.3    0.07       0
  4775.4    0.05       0  4819.9    0.07       0  4937.5    0.12       0
  4993.8    0.07       0  4999.8    0.12       0  5348.4    0.05       0
  5464.5    0.12       0
Bank Sta=4842.2,5527
Exp/Cntr=0.3,0.1

Type RM Length L Ch R = 1,2632,247,247,247
BEGIN DESCRIPTION:
Mapping XS 0d54e73f
END DESCRIPTION:
XS GIS Cut Line= 4
      2887451.06      6979759.07      2888055.25      6979439.62
      2888135.11      6979186.14      2888107.33      6978901.40
#Sta/Elev= 30
  4354.6  373.37  4369.4  372.91  4381.7  370.85  4391.4  369.96  4397.0  370.45
  4426.9  368.68  4457.4  368.13  4483.4  365.70  4501.4  364.70  4507.1  364.98
  4556.0  360.70  4589.5  357.63  4605.8  357.34  4669.4  353.55  4715.8  350.92
  4792.5  348.34  4856.8  347.33  4864.3  346.56  4905.3  345.82  4905.8  345.02
  4910.8  345.02  4911.3  345.82  4990.7  345.98  5056.2  347.63  5286.1  347.83
  5353.3  348.58  5430.9  348.34  5485.8  349.56  5589.4  349.10  5589.9  349.10
#Mann=8,-1,0
  4354.6    0.08       0  4483.4    0.12       0  4556.0    0.05       0
  4669.4    0.12       0  4905.3    0.07       0  4911.3    0.12       0
  5286.1    0.05       0  5589.4    0.12       0
Bank Sta=4792.5,5430.9
Exp/Cntr=0.3,0.1

Type RM Length L Ch R = 1,2385,166,166,166
BEGIN DESCRIPTION:
Mapping XS ed6447ee
END DESCRIPTION:
XS GIS Cut Line= 4
      2887687.17      6979957.00      2888194.14      6979536.84
      2888253.16      6979318.09      2888138.58      6978873.64
#Sta/Elev= 30
  4210.4  366.43  4253.4  361.69  4255.7  361.62  4281.5  359.43  4295.9  356.11
  4302.4  356.68  4324.5  354.91  4337.5  355.81  4351.8  354.49  4402.6  352.92
  4518.0  348.33  4563.5  346.93  4571.9  347.10  4579.8  345.85  4600.6  346.39
  4650.1  345.22  4714.1  346.66  4901.4  346.85  5008.5  345.76  5067.5  346.43
  5136.9  344.84  5137.4  344.04  5142.4  344.04  5142.9  344.84  5212.2  346.84
  5300.0  346.76  5346.1  346.93  5491.0  350.00  5535.3  349.61  5554.4  349.37
#Mann=10,-1,0
  4210.4    0.05       0  4253.4    0.08       0  4255.7    0.05       0
  4402.6    0.07       0  4518.0    0.16       0  4901.4    0.12       0
  5136.9    0.07       0  5142.9    0.12       0  5300.0    0.05       0
  5535.3    0.12       0
Bank Sta=4563.5,5346.1
Exp/Cntr=0.3,0.1

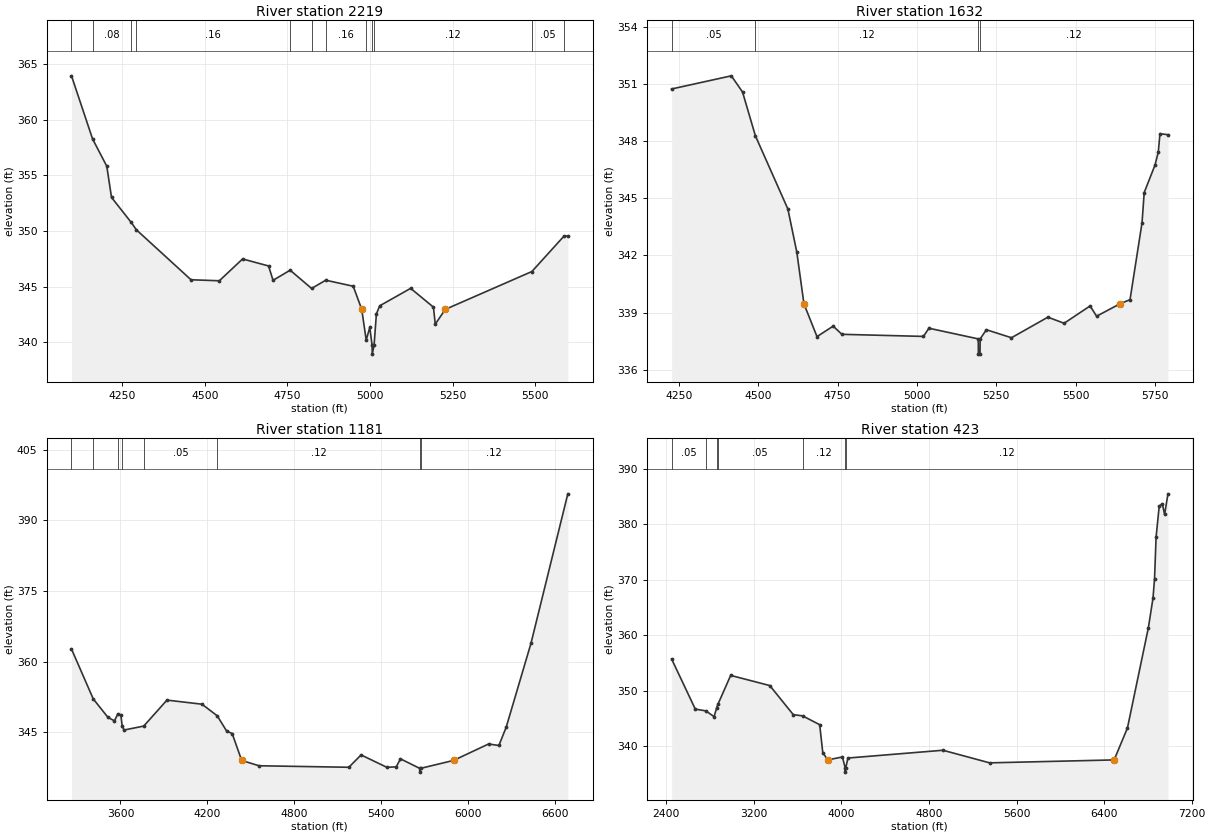
Type RM Length L Ch R = 1,2219,587,587,587
BEGIN DESCRIPTION:
Mapping XS 3bfe453f
END DESCRIPTION:
XS GIS Cut Line= 4
      2887770.51      6980050.74      2888367.75      6979543.78
      2888381.64      6979307.67      2888180.26      6978870.21
#Sta/Elev= 30
  4097.0  363.95  4160.8  358.28  4203.8  355.83  4218.1  353.03  4277.5  350.79
  4293.3  350.12  4458.6  345.63  4544.3  345.54  4614.6  347.50  4693.2  346.87
  4706.8  345.58  4758.5  346.49  4823.4  344.85  4866.2  345.59  4949.3  345.05
  4975.1  342.97  4988.6  340.21  4999.4  341.35  5006.4  339.75  5006.9  338.95
  5012.4  339.75  5019.4  342.56  5029.4  343.29  5123.1  344.86  5192.0  343.17
  5197.5  341.64  5227.9  342.97  5489.8  346.37  5586.9  349.55  5598.5  349.56
#Mann=12,-1,0
  4097.0    0.05       0  4160.8    0.08       0  4277.5    0.05       0
  4293.3    0.16       0  4758.5    0.12       0  4823.4    0.05       0
  4866.2    0.16       0  4988.6    0.12       0  5006.4    0.07       0
  5012.4    0.12       0  5489.8    0.05       0  5586.9    0.12       0
Bank Sta=4975.1,5227.9
Exp/Cntr=0.3,0.1

Type RM Length L Ch R = 1,1632,451,451,451
BEGIN DESCRIPTION:
Mapping XS 7cc71b76
END DESCRIPTION:
XS GIS Cut Line= 4
      2888381.52      6979844.74      2888828.54      6979276.19
      2888654.93      6978915.95      2888225.22      6978824.80
#Sta/Elev= 30
  4227.8  350.74  4415.7  351.43  4451.0  350.58  4491.5  348.28  4593.7  344.44
  4621.8  342.18  4644.3  339.46  4685.4  337.74  4736.3  338.29  4763.7  337.86
  5020.6  337.75  5037.7  338.18  5193.0  337.62  5193.5  336.82  5198.5  336.82
  5199.0  337.62  5218.7  338.10  5297.6  337.68  5412.2  338.76  5463.3  338.44
  5545.1  339.35  5565.5  338.81  5638.9  339.46  5670.8  339.68  5708.6  343.72
  5715.4  345.30  5749.5  346.75  5759.8  347.43  5765.0  348.39  5790.2  348.34
#Mann=4,-1,0
  4227.8    0.05       0  4491.5    0.12       0  5193.0    0.07       0
  5199.0    0.12       0
Bank Sta=4644.3,5638.9
Exp/Cntr=0.3,0.1

Type RM Length L Ch R = 1,1181,758,758,758
BEGIN DESCRIPTION:
Mapping XS 15f2abae
END DESCRIPTION:
XS GIS Cut Line= 4
      2887832.39      6980201.50      2889222.97      6979461.94
      2889259.43      6979118.19      2888369.38      6977905.44
#Sta/Elev= 30
  3262.0  362.69  3412.2  352.10  3514.1  348.17  3558.6  347.45  3582.4  348.95
  3602.5  348.70  3611.8  346.38  3624.5  345.50  3760.8  346.34  3920.8  351.85
  4162.5  350.98  4267.8  348.52  4332.7  345.28  4370.9  344.76  4436.5  339.05
  4556.2  337.92  5175.8  337.60  5260.5  340.22  5438.1  337.59  5502.9  337.69
  5532.2  339.39  5665.0  337.37  5665.5  336.57  5671.0  337.37  5898.2  339.05
  6140.3  342.54  6211.3  342.22  6261.5  346.07  6432.8  363.89  6687.0  395.61
#Mann=8,-1,0
  3262.0    0.05       0  3412.2    0.08       0  3582.4    0.05       0
  3611.8    0.16       0  3760.8    0.05       0  4267.8    0.12       0
  5665.0    0.07       0  5671.0    0.12       0
Bank Sta=4436.5,5898.2
Exp/Cntr=0.3,0.1

Type RM Length L Ch R = 1,423,0,0,0
BEGIN DESCRIPTION:
UNT 029 IN DRY CR WATERSHED 1.0
END DESCRIPTION:
XS GIS Cut Line= 4
      2887931.30      6980321.32      2889785.47      6979404.65
      2889905.26      6978758.81      2888655.24      6977451.50
#Sta/Elev= 30
  2448.9  355.73  2665.0  346.71  2761.2  346.39  2836.7  345.35  2860.7  346.95
  2871.5  347.56  2988.2  352.78  3345.5  350.95  3560.2  345.71  3645.8  345.49
  3801.5  343.90  3829.5  338.89  3875.0  337.56  4009.0  338.09  4034.1  336.16
  4034.6  335.36  4040.1  336.16  4059.5  337.90  4927.4  339.30  5353.9  337.03
  6491.3  337.56  6612.8  343.31  6803.7  361.34  6846.2  366.68  6860.4  370.21
  6874.5  377.69  6902.8  383.22  6931.1  383.70  6952.2  381.77  6982.9  385.48
#Mann=7,-1,0
  2448.9    0.05       0  2761.2    0.08       0  2860.7    0.16       0
  2871.5    0.05       0  3645.8    0.12       0  4034.1    0.07       0
  4040.1    0.12       0
Bank Sta=3875,6491.3
Exp/Cntr=0.3,0.1

Chan Stop Cuts=-1