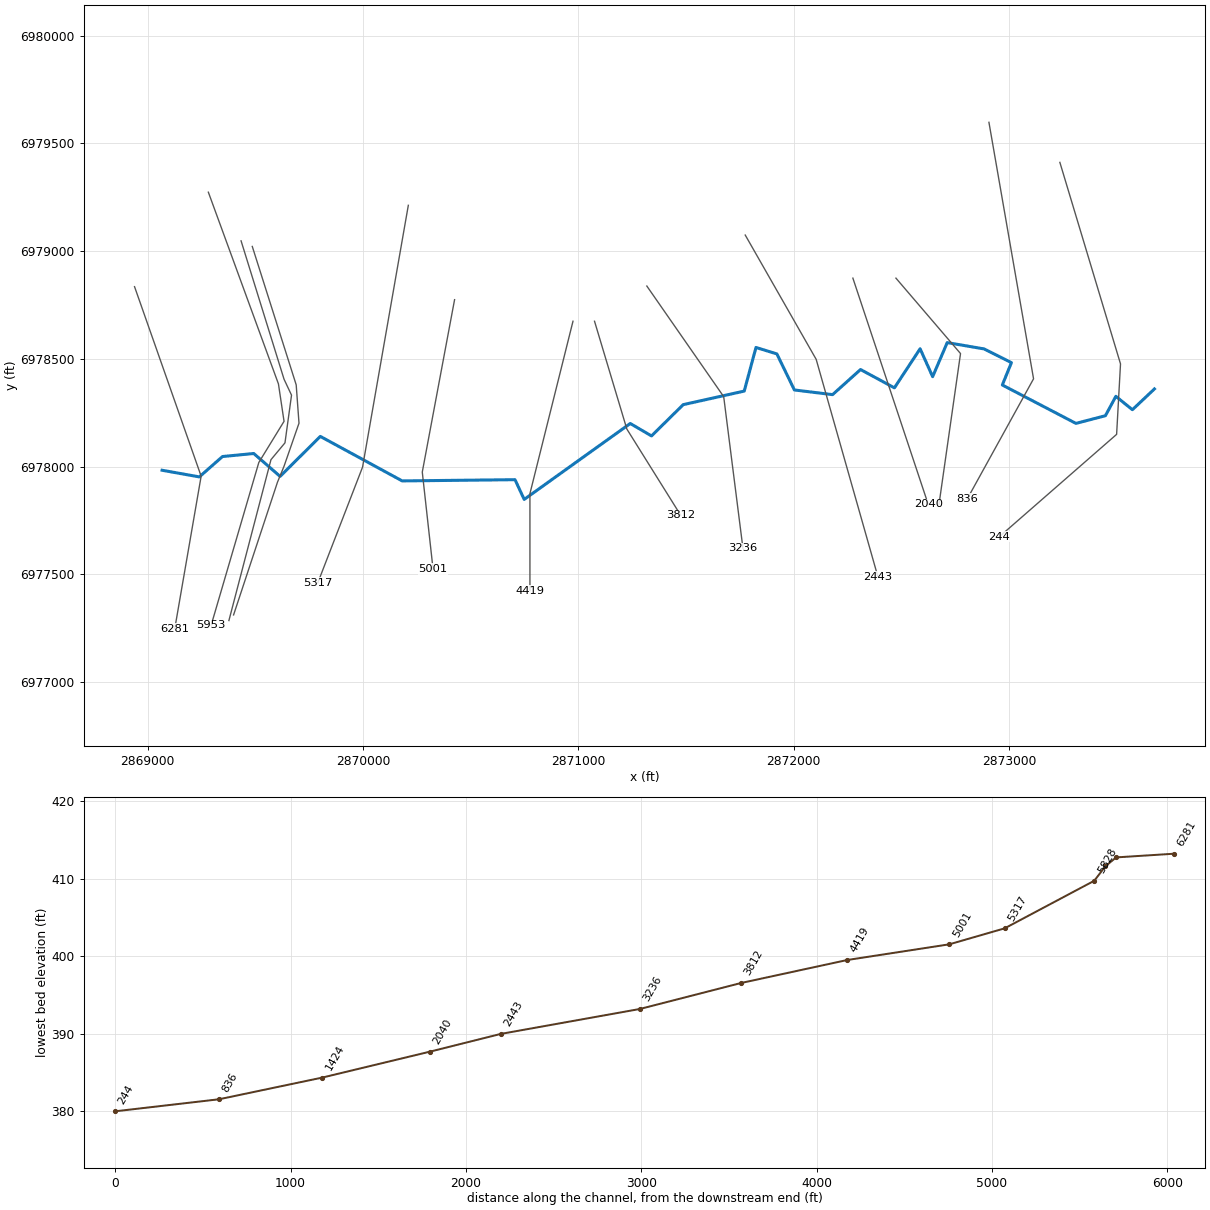
--- UNT 030 IN DRY CR WATERSHED.prj (project) ---

Proj Title=UNT 030 IN DRY CR WATERSHED Base Level Engineering
Current Plan=p01
Default Exp/Contr=0.3,0.1
English Units
Geom File=g01
Flow File=f01
Plan File=p01
BEGIN DESCRIPTION:
UNT 030 IN DRY CR WATERSHED
END DESCRIPTION:

--- UNT 030 IN DRY CR WATERSHED.p01 (plan) ---

Plan Title=Multiple Run
Short Identifier=Multiple
Geom File=g01
Flow File=f01
Subcritical Flow
K Sum by GR= 0
Std Step Tol= 0.01
Critical Tol= 0.01
Num of Std Step Trials= 20
Max Error Tol= 0.3
Flow Tol Ratio= 0.001
Split Flow NTrial= 30
Split Flow Tol= 0.02
Split Flow Ratio= 0.02
Log Output Level= 0
Friction Slope Method= 1
Unsteady Friction Slope Method= 2
Unsteady Bridges Friction Slope Method= 1
Parabolic Critical Depth
Global Vel Dist=  1 , 1 , 1
Global Log Level= 0
CheckData=True
Encroach Param= -1, 0, 0, 0
BEGIN DESCRIPTION:
Multiple Run
END DESCRIPTION:

--- UNT 030 IN DRY CR WATERSHED.f01 (steady flow) ---

Flow Title=Multiple
Number of Profiles=7
Profile Names=10-year,25-year,50-year,1pct_min,100-year,1pct_plu,500-year
River Rch & RM= UNT 030 IN DRY C,Reach-1,6281
     525     699     840     502    1002    1999    1426
River Rch & RM= UNT 030 IN DRY C,Reach-1,5317
     784    1067    1300     786    1569    3131    2292
Boundary for River Rch & Prof#=UNT 030 IN DRY C,Reach-1,1
Up Type=0
Dn Type=3
Dn Slope=0.005
Boundary for River Rch & Prof#=UNT 030 IN DRY C,Reach-1,2
Up Type=0
Dn Type=3
Dn Slope=0.005
Boundary for River Rch & Prof#=UNT 030 IN DRY C,Reach-1,3
Up Type=0
Dn Type=3
Dn Slope=0.005
Boundary for River Rch & Prof#=UNT 030 IN DRY C,Reach-1,4
Up Type=0
Dn Type=3
Dn Slope=0.005
Boundary for River Rch & Prof#=UNT 030 IN DRY C,Reach-1,5
Up Type=0
Dn Type=3
Dn Slope=0.005
Boundary for River Rch & Prof#=UNT 030 IN DRY C,Reach-1,6
Up Type=0
Dn Type=3
Dn Slope=0.005
Boundary for River Rch & Prof#=UNT 030 IN DRY C,Reach-1,7
Up Type=0
Dn Type=3
Dn Slope=0.005

--- UNT 030 IN DRY CR WATERSHED.g01 (geometry) ---

Geom Title=Existing Conditions

River Reach=UNT 030 IN DRY C,Reach-1
Reach XY= 30
      2869066.67      6977983.41      2869239.49      6977952.54
      2869347.10      6978047.06      2869492.14      6978061.14
      2869614.63      6977954.96      2869801.39      6978140.51
      2870181.73      6977933.93      2870705.72      6977939.62
      2870748.40      6977848.06      2871241.06      6978200.48
      2871339.65      6978142.67      2871486.91      6978287.83
      2871770.41      6978350.78      2871824.99      6978553.26
      2871921.99      6978523.42      2872003.36      6978355.96
      2872180.69      6978334.36      2872310.57      6978450.86
      2872467.92      6978365.80      2872587.35      6978547.32
      2872645.46      6978417.54      2872713.11      6978575.77
      2872884.09      6978546.59      2873011.37      6978482.84
      2872969.14      6978379.06      2873310.97      6978200.93
      2873447.95      6978236.46      2873496.51      6978326.46
      2873573.31      6978264.39      2873675.59      6978360.71

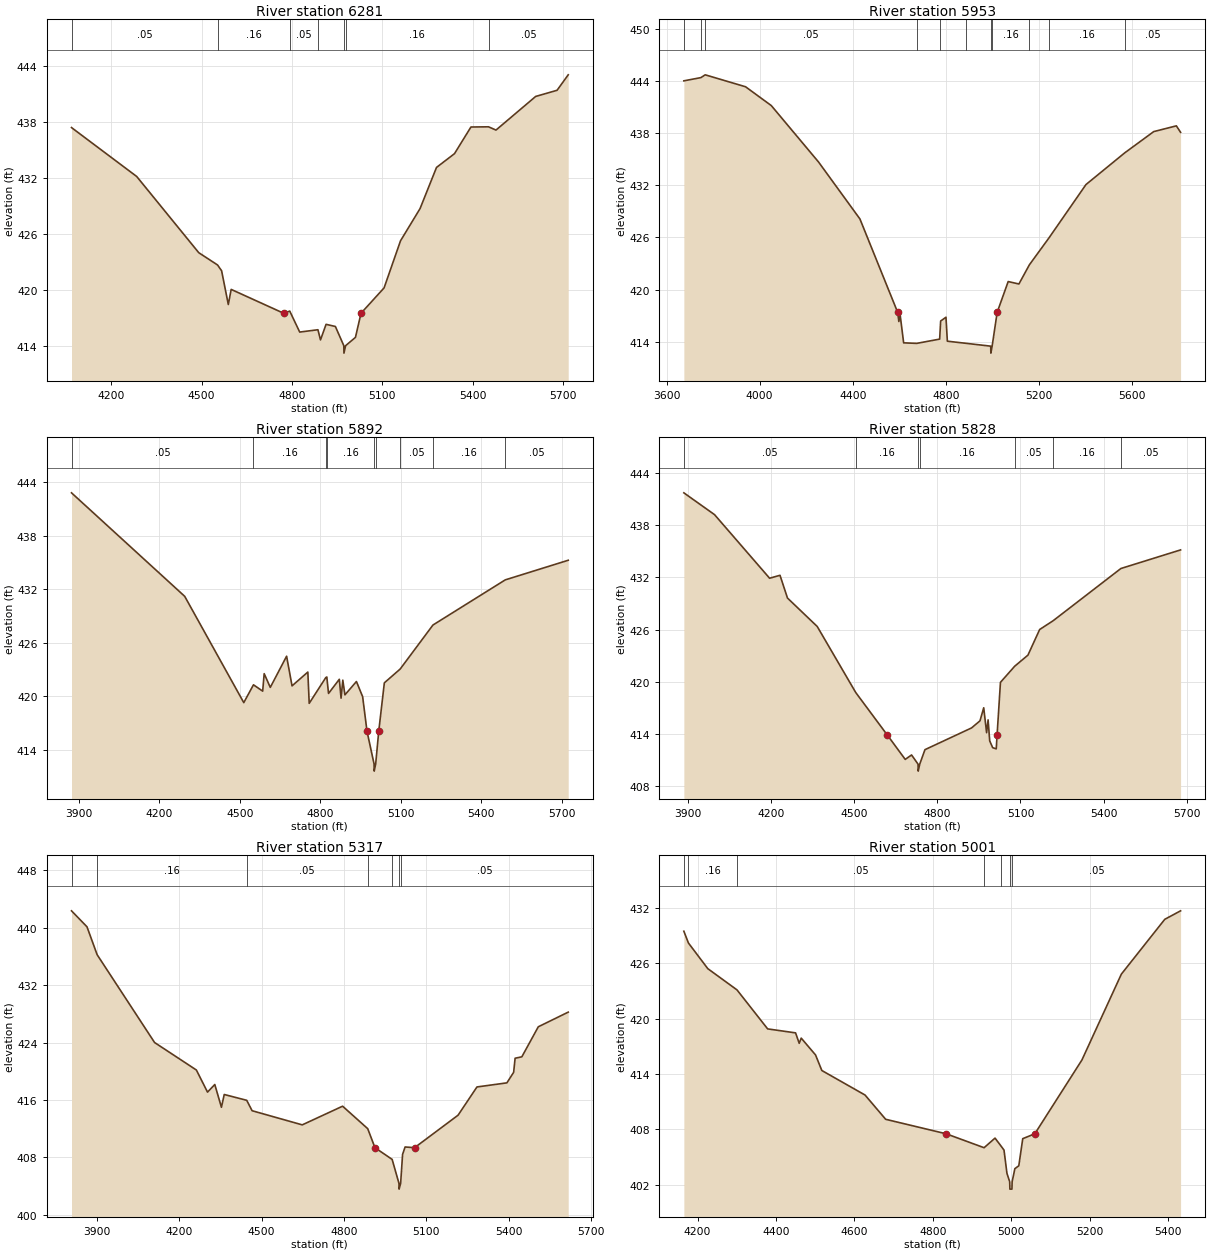
Type RM Length L Ch R = 1,6281,328,328,328
BEGIN DESCRIPTION:
UNT 030 IN DRY CR WATERSHED 9.0
END DESCRIPTION:
XS GIS Cut Line= 3
      2868938.51      6978835.44      2869247.89      6977955.86
      2869125.40      6977248.48
#Sta/Elev= 30
  4067.6  437.40  4284.2  432.15  4490.4  423.97  4552.9  422.65  4566.3  422.03
  4588.6  418.41  4598.1  420.03  4772.5  417.47  4792.7  417.70  4825.8  415.45
  4886.3  415.70  4894.9  414.61  4913.4  416.28  4944.3  416.05  4972.3  413.99
  4972.8  413.19  4978.3  413.99  5011.0  414.88  5029.5  417.47  5106.1  420.19
  5160.8  425.25  5225.6  428.70  5280.3  433.12  5340.1  434.60  5394.7  437.46
  5453.2  437.48  5477.9  437.13  5609.8  440.74  5680.8  441.40  5717.9  443.06
#Mann=7,-1,0
  4067.6    0.05       0  4552.9    0.16       0  4792.7    0.05       0
  4886.3    0.16       0  4972.3    0.07       0  4978.3    0.16       0
  5453.2    0.05       0
Bank Sta=4772.5,5029.5
Exp/Cntr=0.3,0.1

Type RM Length L Ch R = 1,5953,61,61,61
BEGIN DESCRIPTION:
Mapping XS a041ba7a
END DESCRIPTION:
XS GIS Cut Line= 5
      2869281.37      6979273.87      2869606.90      6978384.09
      2869632.94      6978210.48      2869515.76      6978019.51
      2869294.42      6977264.34
#Sta/Elev= 30
  3674.4  443.99  3747.6  444.36  3766.1  444.68  3939.4  443.31  4050.0  441.15
  4253.0  434.67  4430.8  428.13  4592.9  417.41  4598.0  416.35  4603.3  417.18
  4618.7  413.90  4674.8  413.84  4773.4  414.33  4777.6  416.41  4800.5  416.84
  4806.4  414.09  4885.6  413.85  4992.8  413.52  4993.3  412.72  4998.8  413.52
  5020.5  417.41  5067.8  420.94  5113.9  420.66  5158.8  422.86  5243.2  425.96
  5402.0  432.08  5568.5  435.72  5693.1  438.16  5790.3  438.82  5808.4  438.08
#Mann=11,-1,0
  3674.4    0.16       0  3747.6    0.12       0  3766.1    0.05       0
  4674.8    0.08       0  4773.4    0.05       0  4885.6    0.16       0
  4992.8    0.07       0  4998.8    0.16       0  5158.8    0.05       0
  5243.2    0.16       0  5568.5    0.05       0
Bank Sta=4592.9,5020.5
Exp/Cntr=0.3,0.1

Type RM Length L Ch R = 1,5892,64,64,64
BEGIN DESCRIPTION:
Mapping XS 9d88a2ad
END DESCRIPTION:
XS GIS Cut Line= 6
      2869433.31      6979048.11      2869632.94      6978405.79
      2869667.67      6978332.01      2869637.28      6978110.65
      2869572.18      6978032.53      2869376.86      6977285.95
#Sta/Elev= 30
  3872.7  442.83  4294.6  431.21  4514.7  419.28  4550.8  421.28  4585.1  420.57
  4590.7  422.53  4613.5  420.99  4674.3  424.49  4694.5  421.16  4753.4  422.71
  4758.5  419.20  4820.3  422.09  4824.1  422.16  4830.5  420.31  4870.7  421.90
  4877.2  419.78  4883.7  421.80  4891.6  420.15  4934.5  421.65  4957.6  419.95
  4973.9  416.06  5000.2  412.39  5000.7  411.59  5006.2  412.39  5017.6  416.06
  5038.5  421.50  5097.5  423.05  5219.6  427.99  5489.2  433.06  5723.7  435.26
#Mann=9,-1,0
  3872.7    0.05       0  4550.8    0.16       0  4820.3    0.05       0
  4824.1    0.16       0  5000.2    0.07       0  5006.2    0.16       0
  5097.5    0.05       0  5219.6    0.16       0  5489.2    0.05       0
Bank Sta=4973.9,5017.6
Exp/Cntr=0.3,0.1

Type RM Length L Ch R = 1,5828,511,511,511
BEGIN DESCRIPTION:
Mapping XS 0fb68eba
END DESCRIPTION:
XS GIS Cut Line= 6
      2869485.38      6979022.08      2869689.37      6978379.75
      2869702.39      6978201.80      2869632.94      6978002.15
      2869602.56      6977928.36      2869398.56      6977312.00
#Sta/Elev= 30
  3885.0  441.74  3995.7  439.23  4194.5  431.91  4232.0  432.25  4259.0  429.63
  4366.3  426.36  4505.3  418.76  4619.4  413.86  4684.0  411.06  4706.9  411.57
  4730.3  410.51  4730.8  409.71  4736.3  410.51  4755.2  412.18  4923.3  414.68
  4953.8  415.50  4967.3  417.00  4977.7  414.13  4983.1  415.61  4988.9  413.19
  4999.7  412.41  5012.5  412.27  5015.5  413.86  5027.7  419.93  5079.0  421.78
  5126.9  423.06  5169.2  426.01  5217.9  427.02  5462.4  433.03  5677.8  435.17
#Mann=7,-1,0
  3885.0    0.05       0  4505.3    0.16       0  4730.3    0.07       0
  4736.3    0.16       0  5079.0    0.05       0  5217.9    0.16       0
  5462.4    0.05       0
Bank Sta=4619.4,5015.5
Exp/Cntr=0.3,0.1

Type RM Length L Ch R = 1,5317,316,316,316
BEGIN DESCRIPTION:
Mapping XS caa7b803
END DESCRIPTION:
XS GIS Cut Line= 3
      2870210.19      6979213.04      2869997.53      6977997.81
      2869789.67      6977460.84
#Sta/Elev= 30
  3807.2  442.34  3863.7  440.11  3900.6  436.23  4109.8  424.00  4262.1  420.17
  4302.7  417.09  4329.2  418.15  4353.4  414.98  4363.6  416.76  4445.5  415.95
  4465.1  414.50  4647.8  412.53  4794.8  415.13  4886.3  412.00  4912.7  409.35
  4975.3  407.72  5000.1  404.38  5000.6  403.58  5006.2  404.38  5013.3  408.42
  5022.5  409.45  5057.0  409.35  5215.5  413.88  5284.3  417.81  5393.3  418.38
  5417.9  419.85  5423.2  421.81  5447.8  422.01  5507.7  426.19  5616.7  428.23
#Mann=7,-1,0
  3807.2    0.05       0  3900.6    0.16       0  4445.5    0.05       0
  4886.3    0.16       0  4975.3    0.05       0  5000.1    0.03       0
  5006.2    0.05       0
Bank Sta=4912.7,5057
Exp/Cntr=0.3,0.1

Type RM Length L Ch R = 1,5001,582,582,582
BEGIN DESCRIPTION:
UNT 030 IN DRY CR WATERSHED 8.0
END DESCRIPTION:
XS GIS Cut Line= 3
      2870425.01      6978775.04      2870275.00      6977975.00
      2870325.01      6977524.95
#Sta/Elev= 30
  4164.9  429.48  4176.6  428.20  4226.0  425.42  4300.4  423.12  4378.6  418.89
  4449.8  418.46  4459.1  417.33  4464.2  417.89  4500.7  416.07  4516.8  414.38
  4627.0  411.72  4679.6  409.09  4833.8  407.52  4930.6  406.01  4958.5  407.05
  4973.1  406.23  4981.4  405.75  4988.9  403.23  4995.9  402.32  4996.4  401.52
  5001.6  401.52  5002.1  402.32  5009.1  403.74  5019.1  404.05  5029.2  406.99
  5060.0  407.52  5180.1  415.52  5280.7  424.83  5391.4  430.77  5431.7  431.69
#Mann=7,-1,0
  4164.9    0.05       0  4176.6    0.16       0  4300.4    0.05       0
  4930.6    0.16       0  4973.1    0.05       0  4995.9    0.03       0
  5002.1    0.05       0
Bank Sta=4833.8,5060
Exp/Cntr=0.3,0.1

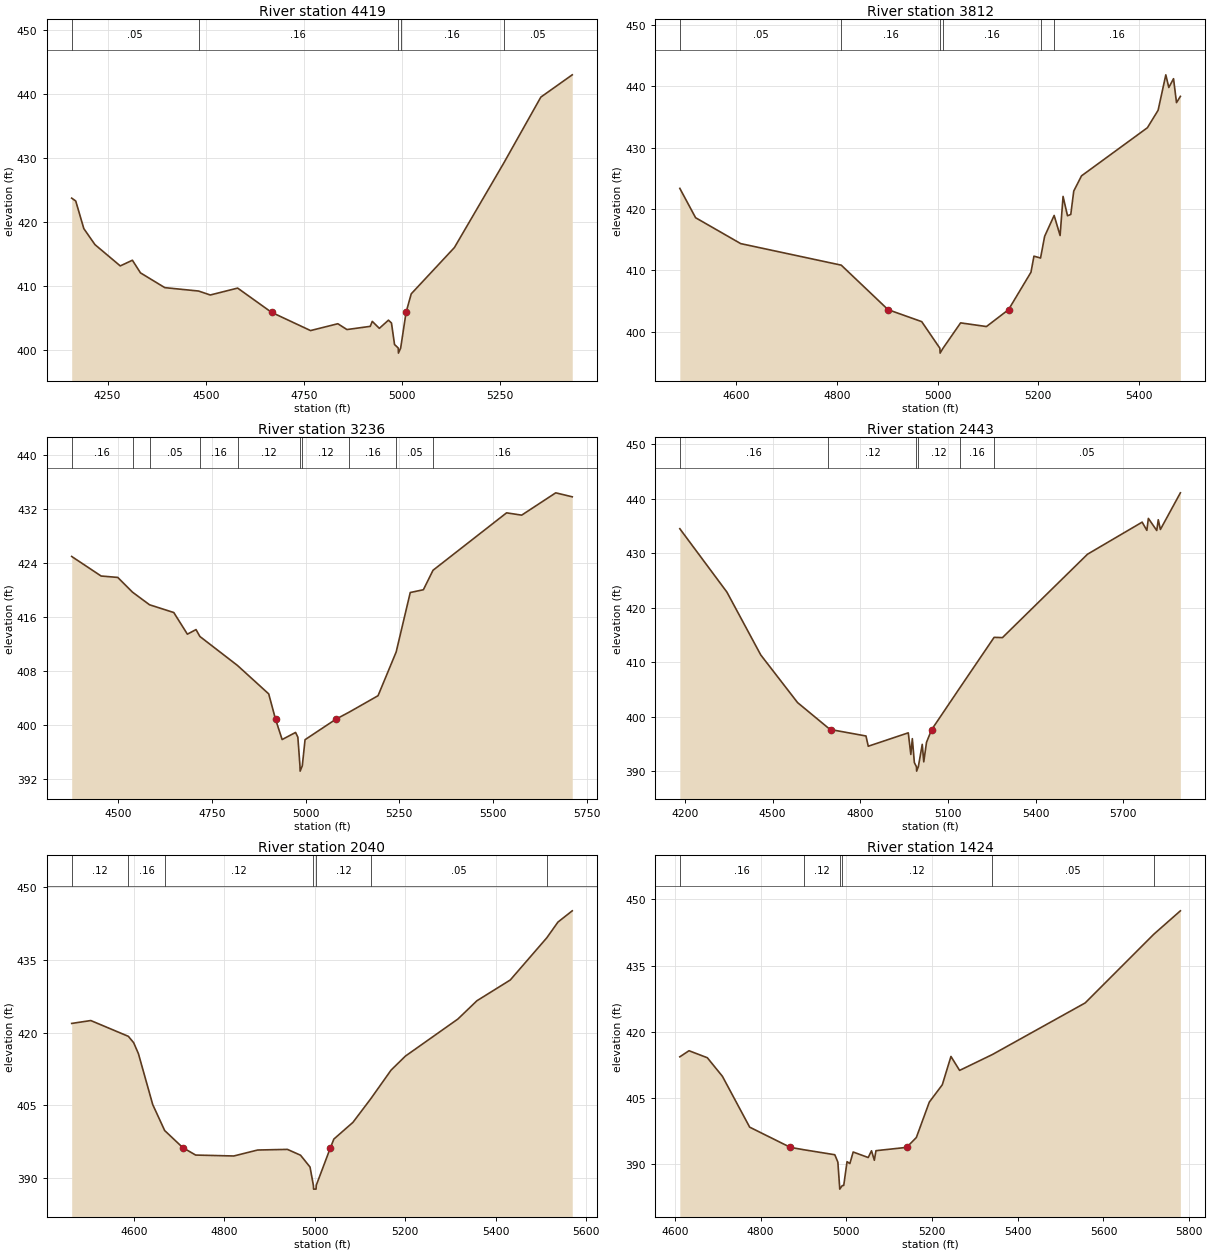
Type RM Length L Ch R = 1,4419,607,607,607
BEGIN DESCRIPTION:
UNT 030 IN DRY CR WATERSHED 7.0
END DESCRIPTION:
XS GIS Cut Line= 3
      2870975.00      6978675.01      2870775.00      6977875.00
      2870775.00      6977425.03
#Sta/Elev= 30
  4158.7  423.76  4169.0  423.31  4189.6  418.99  4218.0  416.48  4282.4  413.15
  4313.3  414.04  4333.9  412.06  4395.8  409.75  4481.6  409.22  4511.7  408.60
  4581.3  409.68  4667.5  405.89  4766.9  403.03  4836.4  404.10  4859.6  403.19
  4918.9  403.69  4924.1  404.47  4942.1  403.38  4965.3  404.66  4973.0  404.21
  4980.8  400.85  4990.2  400.30  4990.7  399.50  4996.4  400.30  5010.2  405.89
  5023.3  408.78  5133.3  416.03  5259.1  429.27  5353.3  439.57  5433.3  443.06
#Mann=5,-1,0
  4158.7    0.05       0  4481.6    0.16       0  4990.2    0.07       0
  4996.4    0.16       0  5259.1    0.05       0
Bank Sta=4667.5,5010.2
Exp/Cntr=0.3,0.1

Type RM Length L Ch R = 1,3812,576,576,576
BEGIN DESCRIPTION:
UNT 030 IN DRY CR WATERSHED 6.0
END DESCRIPTION:
XS GIS Cut Line= 3
      2871075.01      6978674.98      2871225.00      6978175.00
      2871475.00      6977775.00
#Sta/Elev= 30
  4488.3  423.37  4519.6  418.59  4609.2  414.37  4808.8  410.86  4901.7  403.61
  4968.5  401.66  5004.5  397.33  5005.0  396.53  5010.8  397.33  5045.7  401.46
  5097.0  400.86  5140.8  403.61  5185.4  409.71  5191.3  412.33  5204.4  412.02
  5212.5  415.56  5231.4  418.96  5243.2  415.69  5249.1  422.06  5257.9  418.91
  5264.4  419.12  5270.3  422.93  5285.7  425.41  5416.5  433.25  5437.8  436.10
  5453.1  441.87  5459.0  439.81  5468.4  441.24  5474.3  437.34  5482.0  438.36
#Mann=6,-1,0
  4488.3    0.05       0  4808.8    0.16       0  5004.5    0.07       0
  5010.8    0.16       0  5204.4    0.05       0  5231.4    0.16       0
Bank Sta=4901.7,5140.8
Exp/Cntr=0.3,0.1

Type RM Length L Ch R = 1,3236,793,793,793
BEGIN DESCRIPTION:
UNT 030 IN DRY CR WATERSHED 5.0
END DESCRIPTION:
XS GIS Cut Line= 3
      2871317.99      6978838.30      2871675.00      6978325.00
      2871764.39      6977621.30
#Sta/Elev= 30
  4376.5  424.93  4454.9  422.04  4499.4  421.83  4538.9  419.64  4584.0  417.79
  4648.7  416.64  4685.0  413.44  4708.0  414.12  4718.3  413.10  4818.6  408.81
  4901.8  404.61  4920.0  400.86  4937.6  397.86  4973.4  398.91  4979.5  398.21
  4985.1  393.99  4985.6  393.19  4991.4  393.99  4998.7  397.84  5080.7  400.86
  5116.9  401.93  5193.3  404.34  5241.6  410.80  5279.2  419.60  5314.2  420.01
  5339.9  422.89  5536.0  431.38  5576.3  431.04  5667.1  434.34  5711.1  433.75
#Mann=10,-1,0
  4376.5    0.16       0  4538.9    0.12       0  4584.0    0.05       0
  4718.3    0.16       0  4818.6    0.12       0  4985.1    0.07       0
  4991.4    0.12       0  5116.9    0.16       0  5241.6    0.05       0
  5339.9    0.16       0
Bank Sta=4920,5080.7
Exp/Cntr=0.3,0.1

Type RM Length L Ch R = 1,2443,403,403,403
BEGIN DESCRIPTION:
UNT 030 IN DRY CR WATERSHED 4.0
END DESCRIPTION:
XS GIS Cut Line= 3
      2871775.02      6979074.96      2872104.50      6978498.19
      2872391.26      6977489.20
#Sta/Elev= 30
  4182.5  434.48  4343.7  422.84  4459.6  411.30  4585.5  402.56  4690.6  397.90
  4700.9  397.59  4819.6  396.43  4827.4  394.55  4964.4  397.01  4973.1  393.04
  4978.3  395.94  4985.2  391.54  4992.4  390.78  4992.9  389.98  4998.8  390.78
  5012.2  394.90  5017.4  391.68  5026.8  395.27  5044.3  397.59  5140.7  405.26
  5258.2  414.54  5286.7  414.49  5577.8  429.80  5764.9  435.69  5780.9  434.18
  5786.1  436.38  5814.8  434.15  5820.0  436.13  5827.3  434.34  5895.7  441.07
#Mann=6,-1,0
  4182.5    0.16       0  4690.6    0.12       0  4992.4    0.07       0
  4998.8    0.12       0  5140.7    0.16       0  5258.2    0.05       0
Bank Sta=4700.9,5044.3
Exp/Cntr=0.3,0.1

Type RM Length L Ch R = 1,2040,616,616,616
BEGIN DESCRIPTION:
UNT 030 IN DRY CR WATERSHED 3.0
END DESCRIPTION:
XS GIS Cut Line= 3
      2872275.00      6978874.99      2872425.00      6978425.00
      2872625.00      6977824.99
#Sta/Elev= 30
  4462.5  421.89  4504.7  422.49  4587.8  419.23  4599.5  417.92  4610.1  415.64
  4641.7  405.14  4668.1  399.79  4708.1  396.27  4736.6  394.73  4820.9  394.54
  4873.6  395.77  4939.5  395.90  4968.5  394.70  4989.5  392.26  4996.9  388.50
  4997.4  387.70  5002.8  387.70  5003.3  388.50  5034.7  396.27  5042.2  398.03
  5084.4  401.48  5124.3  406.41  5168.7  412.26  5200.4  415.15  5316.3  422.79
  5358.5  426.57  5432.3  430.86  5513.0  439.56  5537.7  442.81  5569.3  445.13
#Mann=7,-1,0
  4462.5    0.12       0  4587.8    0.16       0  4668.1    0.12       0
  4996.9    0.07       0  5003.3    0.12       0  5124.3    0.05       0
  5513.0    0.16       0
Bank Sta=4708.1,5034.7
Exp/Cntr=0.3,0.1

Type RM Length L Ch R = 1,1424,588,588,588
BEGIN DESCRIPTION:
UNT 030 IN DRY CR WATERSHED 2.0
END DESCRIPTION:
XS GIS Cut Line= 3
      2872474.98      6978875.02      2872775.00      6978525.00
      2872675.00      6977825.01
#Sta/Elev= 30
  4611.4  414.33  4632.8  415.71  4675.6  414.12  4710.8  409.91  4774.4  398.39
  4869.4  393.81  4900.5  393.28  4973.1  392.14  4980.2  390.46  4984.1  385.15
  4984.6  384.35  4990.5  385.15  4993.9  385.19  5001.6  390.57  5008.2  390.14
  5015.9  392.76  5051.0  391.51  5058.7  393.04  5065.3  390.89  5069.1  393.06
  5140.6  393.81  5163.3  396.04  5193.6  404.07  5223.9  408.00  5244.1  414.41
  5264.3  411.25  5340.8  414.85  5557.3  426.54  5717.3  442.09  5779.5  447.41
#Mann=6,-1,0
  4611.4    0.16       0  4900.5    0.12       0  4984.1    0.07       0
  4990.5    0.12       0  5340.8    0.05       0  5717.3    0.16       0
Bank Sta=4869.4,5140.6
Exp/Cntr=0.3,0.1

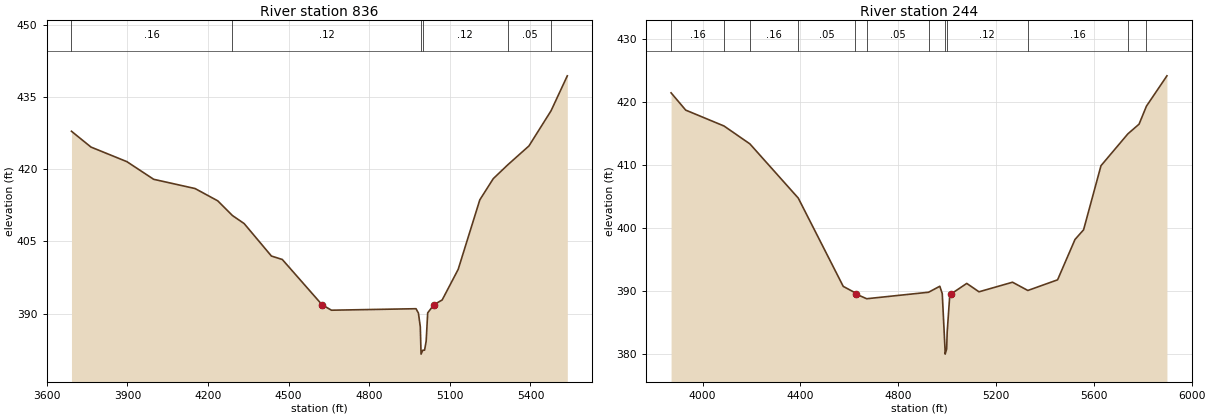
Type RM Length L Ch R = 1,836,592,592,592
BEGIN DESCRIPTION:
Mapping XS 4b6c07b4
END DESCRIPTION:
XS GIS Cut Line= 3
      2872906.95      6979598.26      2873114.21      6978407.84
      2872806.03      6977849.93
#Sta/Elev= 30
  3691.5  427.89  3764.2  424.60  3897.8  421.57  3997.5  417.90  4151.6  415.98
  4235.9  413.43  4290.7  410.37  4334.3  408.70  4435.8  401.95  4476.4  401.23
  4624.2  391.83  4659.1  390.69  4974.0  391.00  4983.0  390.09  4990.0  387.24
  4992.4  382.36  4992.9  381.56  4999.1  382.36  5005.9  382.39  5011.8  384.25
  5017.5  390.13  5040.5  391.83  5071.4  392.82  5130.9  399.17  5211.5  413.63
  5261.5  418.03  5315.3  420.90  5394.3  424.83  5476.7  432.15  5537.2  439.41
#Mann=6,-1,0
  3691.5    0.16       0  4290.7    0.12       0  4992.4    0.07       0
  4999.1    0.12       0  5315.3    0.05       0  5476.7    0.16       0
Bank Sta=4624.2,5040.5
Exp/Cntr=0.3,0.1

Type RM Length L Ch R = 1,244,0,0,0
BEGIN DESCRIPTION:
UNT 030 IN DRY CR WATERSHED 1.0
END DESCRIPTION:
XS GIS Cut Line= 4
      2873236.44      6979412.23      2873518.09      6978476.93
      2873500.00      6978150.00      2872954.76      6977674.46
#Sta/Elev= 30
  3871.2  421.47  3931.0  418.73  4087.6  416.21  4193.5  413.37  4391.3  404.77
  4575.2  390.76  4624.2  389.74  4629.2  389.51  4671.1  388.80  4924.2  389.83
  4970.1  390.78  4980.1  389.61  4991.4  380.81  4991.9  380.01  4998.1  380.81
  5000.2  383.48  5010.2  389.02  5014.3  389.51  5080.3  391.23  5130.4  389.90
  5267.5  391.42  5330.1  390.11  5451.7  391.80  5522.9  398.20  5558.0  399.74
  5629.2  409.91  5739.1  414.96  5784.9  416.50  5815.1  419.36  5898.9  424.17
#Mann=12,-1,0
  3871.2    0.16       0  4087.6    0.05       0  4193.5    0.16       0
  4391.3    0.05       0  4624.2    0.16       0  4671.1    0.05       0
  4924.2    0.12       0  4991.4    0.07       0  4998.1    0.12       0
  5330.1    0.16       0  5739.1    0.12       0  5815.1    0.16       0
Bank Sta=4629.2,5014.3
Exp/Cntr=0.3,0.1

Chan Stop Cuts=-1