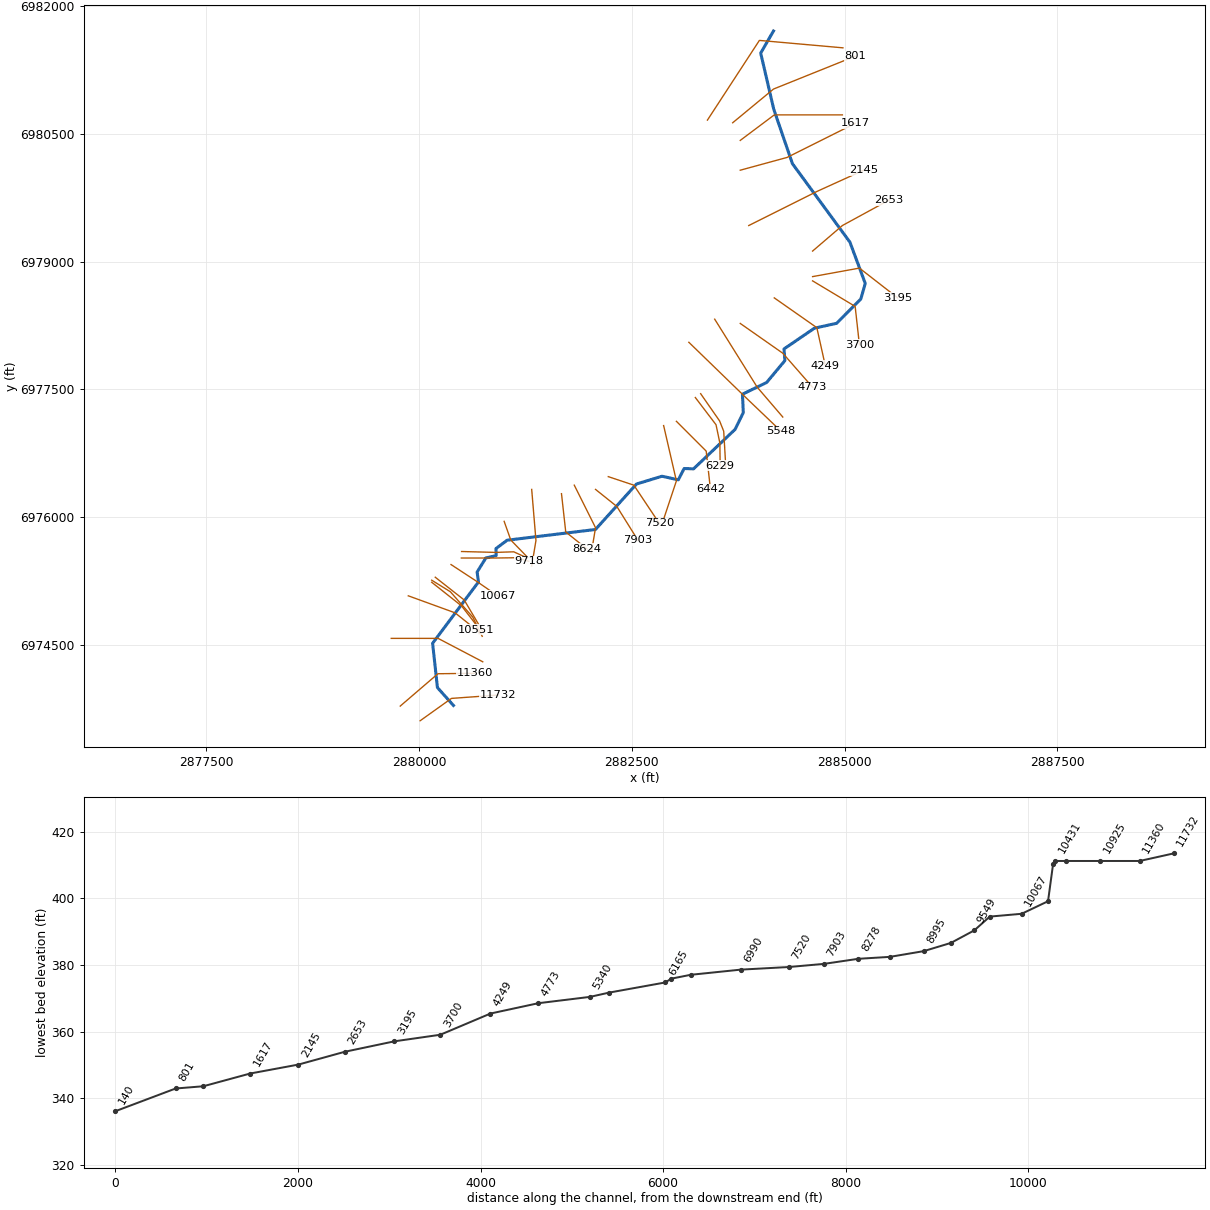
--- UNT 031 IN DRY CR WATERSHED.prj (project) ---

Proj Title=UNT 031 IN DRY CR WATERSHED Base Level Engineering
Current Plan=p01
Default Exp/Contr=0.3,0.1
English Units
Geom File=g01
Flow File=f01
Plan File=p01
BEGIN DESCRIPTION:
UNT 031 IN DRY CR WATERSHED
END DESCRIPTION:

--- UNT 031 IN DRY CR WATERSHED.p01 (plan) ---

Plan Title=Multiple Run
Short Identifier=Multiple
Geom File=g01
Flow File=f01
Subcritical Flow
K Sum by GR= 0
Std Step Tol= 0.01
Critical Tol= 0.01
Num of Std Step Trials= 20
Max Error Tol= 0.3
Flow Tol Ratio= 0.001
Split Flow NTrial= 30
Split Flow Tol= 0.02
Split Flow Ratio= 0.02
Log Output Level= 0
Friction Slope Method= 1
Unsteady Friction Slope Method= 2
Unsteady Bridges Friction Slope Method= 1
Parabolic Critical Depth
Global Vel Dist=  1 , 1 , 1
Global Log Level= 0
CheckData=True
Encroach Param= -1, 0, 0, 0
BEGIN DESCRIPTION:
Multiple Run
END DESCRIPTION:

--- UNT 031 IN DRY CR WATERSHED.f01 (steady flow) ---

Flow Title=Multiple
Number of Profiles=7
Profile Names=10-year,25-year,50-year,1pct_min,100-year,1pct_plu,500-year
River Rch & RM= UNT 031 IN DRY C,Reach-1,11732
     344     446     526     309     616    1230     847
River Rch & RM= UNT 031 IN DRY C,Reach-1,10356
     767    1045    1273     771    1539    3070    2251
Boundary for River Rch & Prof#=UNT 031 IN DRY C,Reach-1,1
Up Type=0
Dn Type=3
Dn Slope=0.005
Boundary for River Rch & Prof#=UNT 031 IN DRY C,Reach-1,2
Up Type=0
Dn Type=3
Dn Slope=0.005
Boundary for River Rch & Prof#=UNT 031 IN DRY C,Reach-1,3
Up Type=0
Dn Type=3
Dn Slope=0.005
Boundary for River Rch & Prof#=UNT 031 IN DRY C,Reach-1,4
Up Type=0
Dn Type=3
Dn Slope=0.005
Boundary for River Rch & Prof#=UNT 031 IN DRY C,Reach-1,5
Up Type=0
Dn Type=3
Dn Slope=0.005
Boundary for River Rch & Prof#=UNT 031 IN DRY C,Reach-1,6
Up Type=0
Dn Type=3
Dn Slope=0.005
Boundary for River Rch & Prof#=UNT 031 IN DRY C,Reach-1,7
Up Type=0
Dn Type=3
Dn Slope=0.005

--- UNT 031 IN DRY CR WATERSHED.g01 (geometry) ---

Geom Title=Existing Conditions

River Reach=UNT 031 IN DRY C,Reach-1
Reach XY= 30
      2880405.82      6973787.02      2880217.64      6973996.54
      2880160.82      6974517.08      2880700.13      6975238.41
      2880683.61      6975354.25      2880786.68      6975519.94
      2880907.06      6975546.62      2880905.99      6975630.44
      2881036.66      6975728.12      2882074.09      6975854.27
      2882556.30      6976388.59      2882856.06      6976479.72
      2883047.42      6976437.31      2883115.82      6976570.49
      2883226.46      6976566.58      2883714.76      6977030.60
      2883811.06      6977227.41      2883801.00      6977443.39
      2884084.86      6977581.00      2884299.46      6977838.36
      2884289.46      6977975.49      2884646.31      6978218.90
      2884906.77      6978276.49      2885191.69      6978562.32
      2885243.68      6978744.98      2885063.62      6979229.89
      2884388.03      6980151.72      2884168.53      6980792.04
      2884015.37      6981450.84      2884165.59      6981710.71

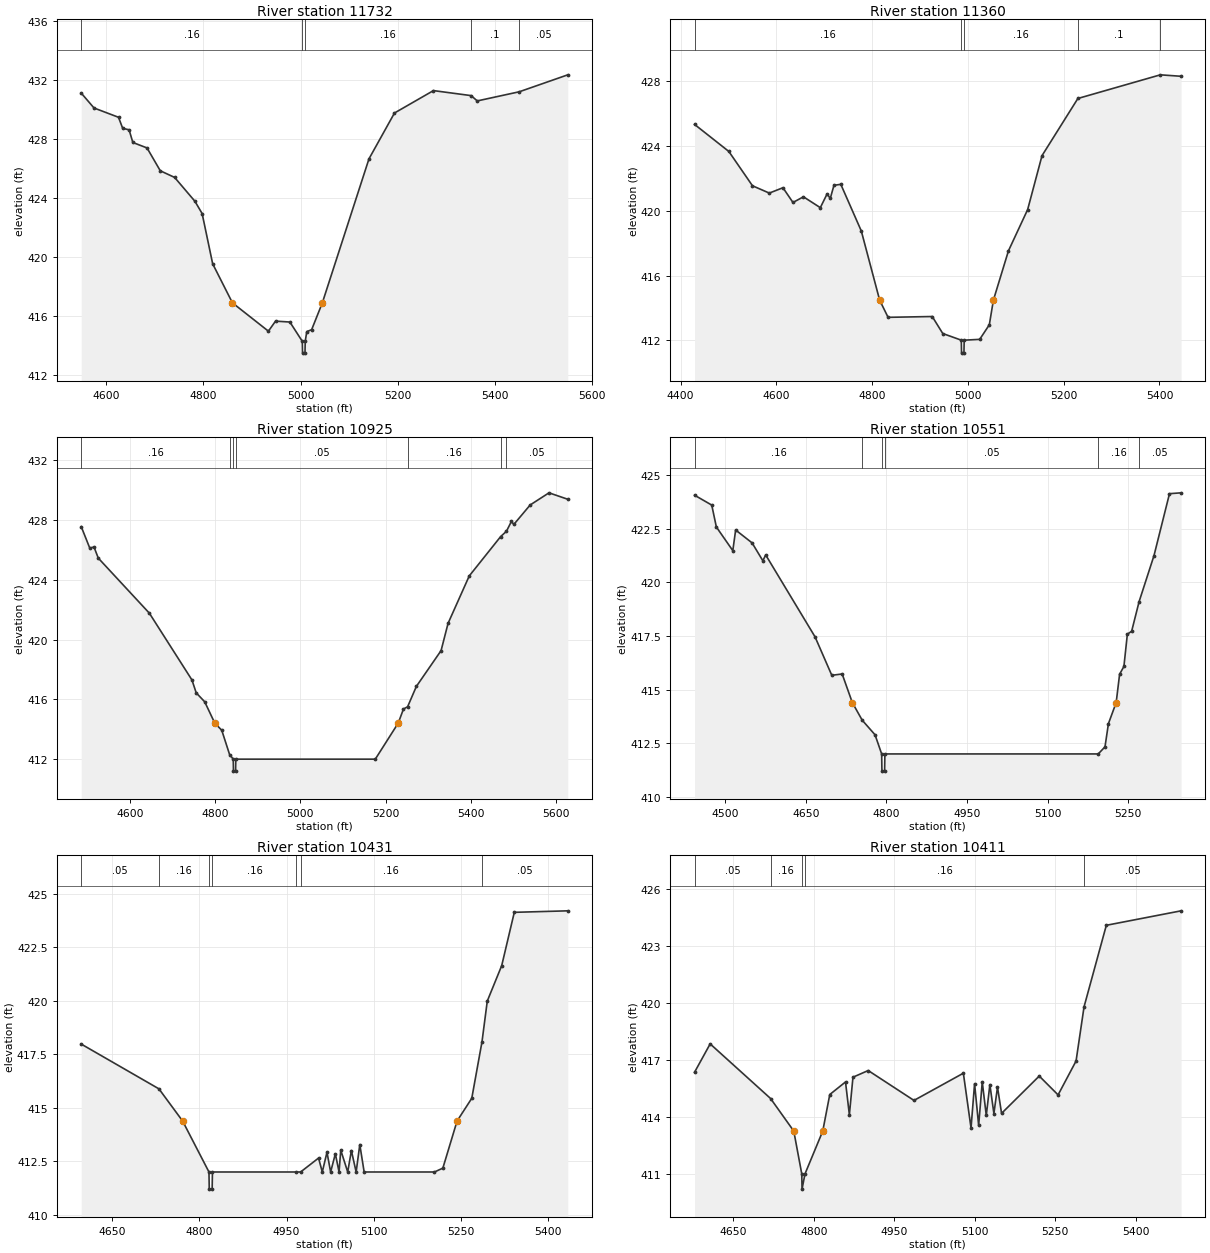
Type RM Length L Ch R = 1,11732,372,372,372
BEGIN DESCRIPTION:
UNT 031 IN DRY CR WATERSHED 24.0
END DESCRIPTION:
XS GIS Cut Line= 3
      2880014.81      6973607.41      2880382.14      6973869.60
      2880930.79      6973909.46
#Sta/Elev= 30
  4548.7  431.12  4575.0  430.11  4625.4  429.48  4634.0  428.73  4647.2  428.63
  4654.9  427.77  4684.1  427.40  4711.4  425.85  4740.9  425.40  4782.7  423.78
  4797.5  422.95  4819.2  419.54  4859.9  416.89  4933.9  414.97  4948.6  415.65
  4978.1  415.59  5003.7  414.28  5004.2  413.48  5009.2  413.48  5009.7  414.28
  5012.9  414.94  5022.9  415.07  5044.9  416.89  5140.9  426.66  5193.4  429.77
  5273.6  431.29  5351.1  430.95  5363.8  430.59  5450.2  431.21  5550.1  432.36
#Mann=5,-1,0
  4548.7    0.16       0  5003.7    0.07       0  5009.7    0.16       0
  5351.1     0.1       0  5450.2    0.05       0
Bank Sta=4859.9,5044.9
Exp/Cntr=0.3,0.1

Type RM Length L Ch R = 1,11360,435,435,435
BEGIN DESCRIPTION:
Mapping XS 9a76d3b7
END DESCRIPTION:
XS GIS Cut Line= 3
      2879780.42      6973779.27      2880223.17      6974159.51
      2880655.42      6974164.71
#Sta/Elev= 30
  4429.3  425.33  4500.9  423.66  4550.3  421.54  4585.4  421.09  4613.9  421.42
  4634.8  420.51  4656.7  420.86  4691.9  420.19  4706.1  421.04  4712.7  420.76
  4720.4  421.57  4734.7  421.63  4777.5  418.75  4815.8  414.48  4833.4  413.42
  4925.6  413.47  4947.6  412.42  4986.3  412.01  4986.8  411.21  4991.8  411.21
  4992.3  412.01  5024.7  412.06  5044.8  412.96  5053.3  414.48  5084.8  417.53
  5124.8  420.07  5154.8  423.40  5229.7  426.93  5401.9  428.39  5445.2  428.30
#Mann=5,-1,0
  4429.3    0.16       0  4986.3    0.07       0  4992.3    0.16       0
  5229.7     0.1       0  5401.9    0.16       0
Bank Sta=4815.8,5053.3
Exp/Cntr=0.3,0.1

Type RM Length L Ch R = 1,10925,374,374,374
BEGIN DESCRIPTION:
UNT 031 IN DRY CR WATERSHED 23.0
END DESCRIPTION:
XS GIS Cut Line= 3
      2879674.96      6974575.00      2880225.00      6974575.00
      2880750.00      6974300.00
#Sta/Elev= 30
  4485.4  427.54  4505.4  426.11  4515.4  426.18  4525.4  425.44  4645.4  421.76
  4745.4  417.30  4755.4  416.44  4775.4  415.84  4799.0  414.42  4815.4  413.94
  4833.8  412.32  4842.4  412.01  4842.9  411.21  4847.9  411.21  4848.4  412.01
  5176.0  412.01  5229.9  414.42  5242.2  415.36  5251.9  415.51  5272.5  416.87
  5330.5  419.26  5346.9  421.08  5396.7  424.25  5470.5  426.88  5484.0  427.23
  5495.7  427.89  5501.4  427.69  5539.8  428.99  5584.0  429.80  5628.1  429.37
#Mann=7,-1,0
  4485.4    0.16       0  4833.8    0.05       0  4842.4   0.033       0
  4848.4    0.05       0  5251.9    0.16       0  5470.5     0.1       0
  5484.0    0.05       0
Bank Sta=4799,5229.9
Exp/Cntr=0.3,0.1

Type RM Length L Ch R = 1,10551,120,120,120
BEGIN DESCRIPTION:
UNT 031 IN DRY CR WATERSHED 22.0
END DESCRIPTION:
XS GIS Cut Line= 3
      2879874.97      6975075.01      2880425.00      6974875.00
      2880674.98      6974675.02
#Sta/Elev= 30
  4443.0  424.05  4475.0  423.59  4483.6  422.57  4514.2  421.47  4519.5  422.43
  4550.1  421.83  4570.1  421.00  4575.4  421.27  4667.2  417.46  4698.4  415.67
  4717.7  415.73  4736.6  414.40  4755.0  413.58  4778.9  412.90  4791.2  412.01
  4791.7  411.21  4796.7  411.21  4797.2  412.01  5194.2  412.01  5206.8  412.34
  5213.2  413.42  5227.6  414.40  5234.0  415.72  5242.0  416.08  5248.4  417.58
  5256.4  417.72  5270.3  419.10  5298.0  421.24  5326.8  424.12  5348.4  424.16
#Mann=6,-1,0
  4443.0    0.16       0  4755.0    0.05       0  4791.2   0.033       0
  4797.2    0.05       0  5194.2    0.16       0  5270.3    0.05       0
Bank Sta=4736.6,5227.6
Exp/Cntr=0.3,0.1

Type RM Length L Ch R = 1,10431,20,20,20
BEGIN DESCRIPTION:
Mapping XS d0216c2a
END DESCRIPTION:
XS GIS Cut Line= 4
      2880150.24      6975234.17      2880500.94      6974956.38
      2880657.19      6974754.99      2880709.28      6974629.99
#Sta/Elev= 30
  4596.4  417.98  4730.2  415.89  4770.9  414.39  4816.3  412.01  4816.8  411.21
  4821.8  411.21  4822.3  412.01  4966.9  412.01  4974.1  412.01  5005.0  412.66
  5011.4  412.01  5019.5  412.93  5025.8  412.01  5033.9  412.86  5040.3  412.01
  5043.2  413.03  5055.2  412.01  5061.5  413.01  5069.7  412.01  5076.0  413.29
  5083.5  412.01  5204.6  412.01  5219.0  412.19  5243.5  414.39  5268.8  415.45
  5286.4  418.09  5295.5  419.99  5320.3  421.64  5342.0  424.13  5434.1  424.20
#Mann=7,-1,0
  4596.4    0.05       0  4730.2    0.16       0  4816.3    0.07       0
  4822.3    0.16       0  4966.9    0.05       0  4974.1    0.16       0
  5286.4    0.05       0
Bank Sta=4770.9,5243.5
Exp/Cntr=0.3,0.1

Type RM Length L Ch R = 1,10411,55,55,55
BEGIN DESCRIPTION:
Mapping XS 5b7a945e
END DESCRIPTION:
XS GIS Cut Line= 4
      2880150.28      6975258.45      2880369.00      6975123.05
      2880632.89      6974824.44      2880743.69      6974599.38
#Sta/Elev= 30
  4577.9  416.35  4607.0  417.84  4719.6  414.97  4762.8  413.26  4777.7  411.01
  4778.2  410.21  4783.7  411.01  4816.8  413.26  4829.9  415.18  4859.2  415.84
  4866.4  414.12  4873.1  416.09  4901.5  416.44  4986.8  414.87  5078.8  416.30
  5093.1  413.42  5099.7  415.75  5107.3  413.56  5114.0  415.84  5121.5  414.08
  5128.2  415.70  5135.7  414.18  5142.4  415.57  5150.0  414.19  5220.2  416.15
  5255.3  415.16  5288.8  416.94  5303.7  419.79  5345.2  424.07  5484.5  424.83
#Mann=5,-1,0
  4577.9    0.05       0  4719.6    0.16       0  4777.7    0.07       0
  4783.7    0.16       0  5303.7    0.05       0
Bank Sta=4762.8,4816.8
Exp/Cntr=0.3,0.1

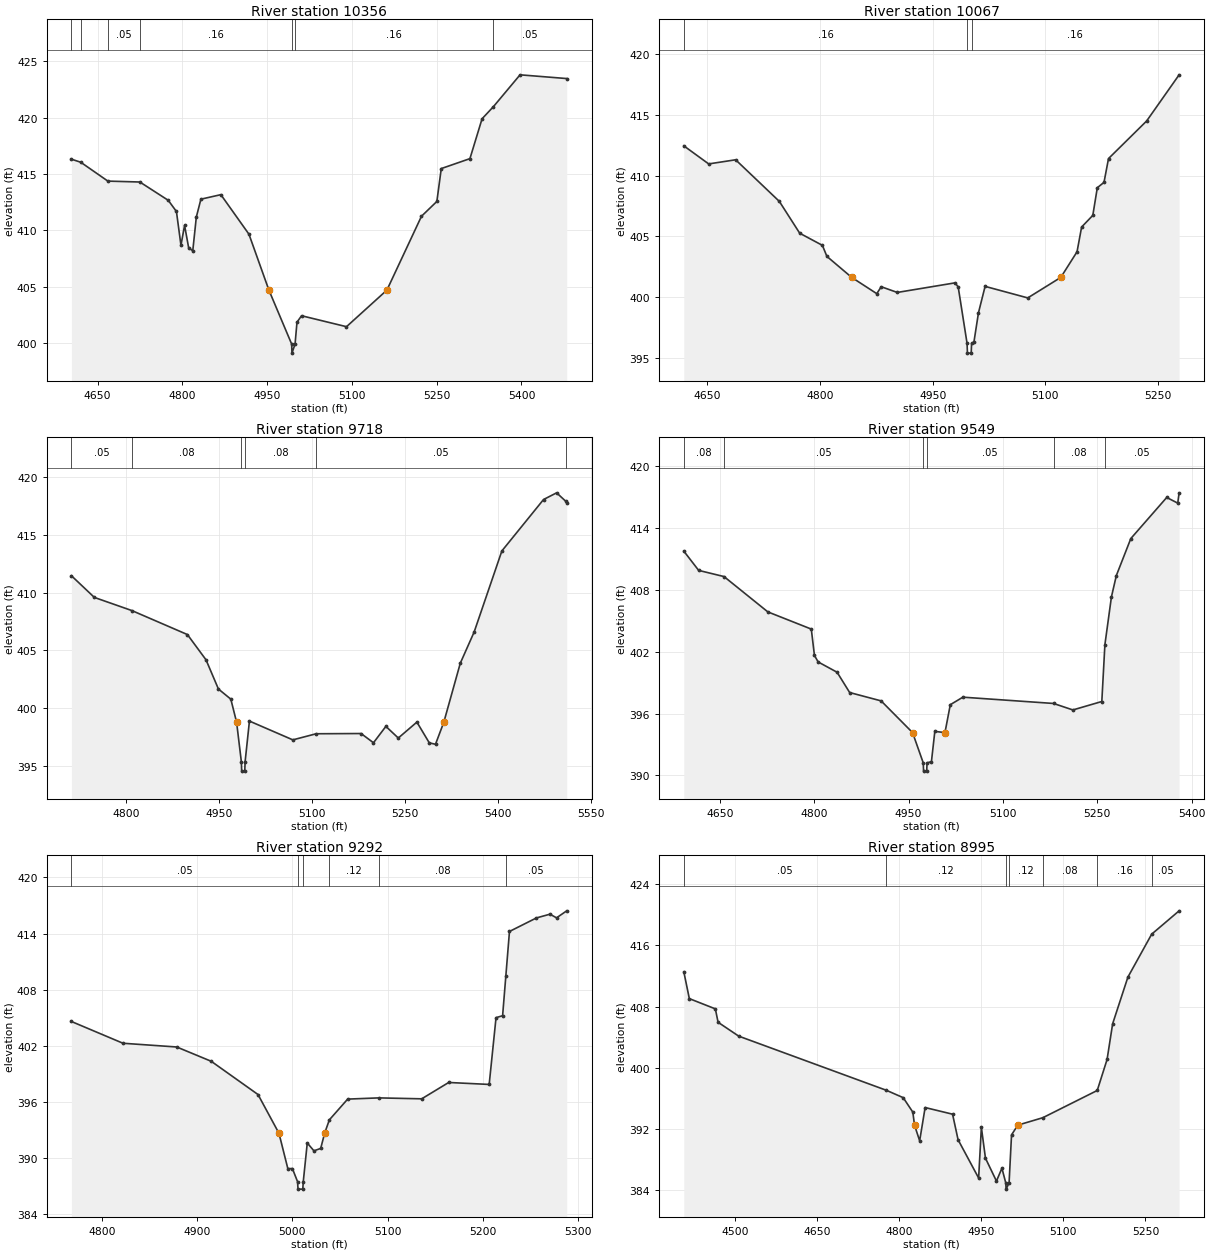
Type RM Length L Ch R = 1,10356,289,289,289
BEGIN DESCRIPTION:
Mapping XS 9a74448e
END DESCRIPTION:
XS GIS Cut Line= 3
      2880191.93      6975293.18      2880532.19      6975025.83
      2880757.90      6974643.86
#Sta/Elev= 30
  4603.7  416.31  4620.2  416.04  4668.2  414.37  4724.8  414.29  4775.0  412.67
  4789.5  411.68  4797.5  408.69  4803.9  410.45  4811.1  408.47  4818.4  408.20
  4824.7  411.19  4832.8  412.77  4868.1  413.17  4917.8  409.67  4953.1  404.72
  4993.4  399.94  4993.9  399.14  4999.4  399.94  5002.8  401.88  5010.9  402.45
  5090.4  401.48  5161.9  404.72  5223.1  411.26  5250.3  412.57  5258.1  415.48
  5308.8  416.36  5330.3  419.89  5350.5  420.97  5397.5  423.78  5480.1  423.45
#Mann=7,-1,0
  4603.7    0.05       0  4620.2    0.08       0  4668.2    0.05       0
  4724.8    0.16       0  4993.4    0.07       0  4999.4    0.16       0
  5350.5    0.05       0
Bank Sta=4953.1,5161.9
Exp/Cntr=0.3,0.1

Type RM Length L Ch R = 1,10067,349,349,349
BEGIN DESCRIPTION:
UNT 031 IN DRY CR WATERSHED 20.0
END DESCRIPTION:
XS GIS Cut Line= 3
      2880377.30      6975442.18      2880679.38      6975244.27
      2880924.97      6975075.02
#Sta/Elev= 30
  4618.7  412.45  4651.8  410.96  4687.7  411.30  4745.9  407.87  4773.0  405.25
  4803.2  404.25  4809.2  403.34  4842.2  401.61  4875.6  400.27  4881.5  400.84
  4902.9  400.37  4979.8  401.16  4984.0  400.82  4995.8  396.17  4996.3  395.37
  5001.3  395.37  5001.8  396.17  5004.9  396.27  5011.0  398.70  5019.8  400.87
  5076.6  399.92  5120.6  401.61  5142.2  403.72  5148.3  405.76  5163.2  406.72
  5169.2  409.00  5178.1  409.44  5184.1  411.40  5234.9  414.50  5278.1  418.30
#Mann=3,-1,0
  4618.7    0.16       0  4995.8    0.07       0  5001.8    0.16       0
Bank Sta=4842.2,5120.6
Exp/Cntr=0.3,0.1

Type RM Length L Ch R = 1,9718,169,169,169
BEGIN DESCRIPTION:
Mapping XS 3c246434
END DESCRIPTION:
XS GIS Cut Line= 4
      2880498.00      6975519.01      2880904.21      6975519.01
      2881147.26      6975522.48      2881290.70      6975481.00
#Sta/Elev= 30
  4712.1  411.47  4749.1  409.59  4809.6  408.45  4899.1  406.37  4929.1  404.18
  4949.1  401.65  4969.1  400.77  4978.4  398.77  4986.1  395.33  4986.6  394.53
  4991.6  394.53  4992.1  395.33  4999.1  398.87  5069.1  397.24  5106.7  397.77
  5179.1  397.79  5199.1  396.99  5219.1  398.41  5239.1  397.40  5269.1  398.78
  5289.1  396.98  5299.1  396.86  5312.5  398.77  5339.1  403.89  5361.4  406.59
  5406.1  413.62  5473.3  418.08  5494.4  418.66  5509.5  417.91  5510.7  417.79
#Mann=6,-1,0
  4712.1    0.05       0  4809.6    0.08       0  4986.1    0.07       0
  4992.1    0.08       0  5106.7    0.05       0  5509.5    0.16       0
Bank Sta=4978.4,5312.5
Exp/Cntr=0.3,0.1

Type RM Length L Ch R = 1,9549,257,257,257
BEGIN DESCRIPTION:
Mapping XS b099ea2a
END DESCRIPTION:
XS GIS Cut Line= 4
      2880501.42      6975595.39      2880900.74      6975584.98
      2881114.28      6975591.92      2881272.92      6975519.50
#Sta/Elev= 30
  4592.6  411.77  4616.2  409.90  4656.5  409.30  4726.2  405.87  4795.3  404.20
  4800.3  401.64  4806.2  401.01  4836.3  400.01  4856.3  398.04  4906.3  397.23
  4956.3  394.15  4973.3  391.21  4973.8  390.41  4978.8  390.41  4979.3  391.21
  4986.3  391.33  4991.7  394.27  5007.8  394.15  5016.3  396.86  5036.3  397.59
  5180.4  396.98  5211.2  396.35  5257.2  397.17  5262.1  402.69  5272.5  407.33
  5280.3  409.40  5303.3  412.99  5360.4  416.98  5377.9  416.43  5380.1  417.43
#Mann=6,-1,0
  4592.6    0.08       0  4656.5    0.05       0  4973.3    0.03       0
  4979.3    0.05       0  5180.4    0.08       0  5262.1    0.05       0
Bank Sta=4956.3,5007.8
Exp/Cntr=0.3,0.1

Type RM Length L Ch R = 1,9292,297,297,297
BEGIN DESCRIPTION:
UNT 031 IN DRY CR WATERSHED 19.0
END DESCRIPTION:
XS GIS Cut Line= 3
      2881001.43      6975949.55      2881078.93      6975730.98
      2881279.23      6975524.19
#Sta/Elev= 30
  4768.1  404.58  4822.2  402.25  4878.6  401.85  4914.8  400.32  4963.9  396.76
  4985.9  392.61  4995.2  388.83  5000.0  388.83  5005.4  387.43  5005.9  386.63
  5010.9  386.63  5011.4  387.43  5015.6  391.57  5022.6  390.73  5029.7  390.99
  5033.8  392.61  5038.8  394.05  5058.0  396.27  5090.7  396.40  5135.7  396.30
  5164.0  398.05  5206.5  397.84  5213.7  404.99  5220.6  405.20  5224.0  409.46
  5227.8  414.22  5256.1  415.67  5270.3  416.07  5277.2  415.68  5287.9  416.43
#Mann=6,-1,0
  4768.1    0.05       0  5005.4    0.03       0  5011.4    0.05       0
  5038.8    0.12       0  5090.7    0.08       0  5224.0    0.05       0
Bank Sta=4985.9,5033.8
Exp/Cntr=0.3,0.1

Type RM Length L Ch R = 1,8995,371,371,371
BEGIN DESCRIPTION:
UNT 031 IN DRY CR WATERSHED 18.0
END DESCRIPTION:
XS GIS Cut Line= 3
      2881325.00      6976325.02      2881375.00      6975725.00
      2881325.01      6975425.04
#Sta/Elev= 30
  4405.5  412.57  4415.6  409.06  4463.2  407.72  4468.2  405.97  4505.9  404.16
  4776.2  397.08  4806.9  396.12  4824.5  394.23  4827.6  392.53  4837.0  390.48
  4847.0  394.83  4897.2  393.96  4907.3  390.62  4944.9  385.62  4949.9  392.24
  4957.4  388.21  4977.5  385.22  4987.5  386.90  4994.6  384.97  4995.1  384.17
  5000.6  384.97  5005.1  391.26  5016.6  392.53  5062.3  393.50  5161.9  397.06
  5179.9  401.11  5190.1  405.78  5218.0  411.87  5261.5  417.48  5311.7  420.53
#Mann=7,-1,0
  4405.5    0.05       0  4776.2    0.12       0  4994.6    0.07       0
  5000.6    0.12       0  5062.3    0.08       0  5161.9    0.16       0
  5261.5    0.05       0
Bank Sta=4827.6,5016.6
Exp/Cntr=0.3,0.1

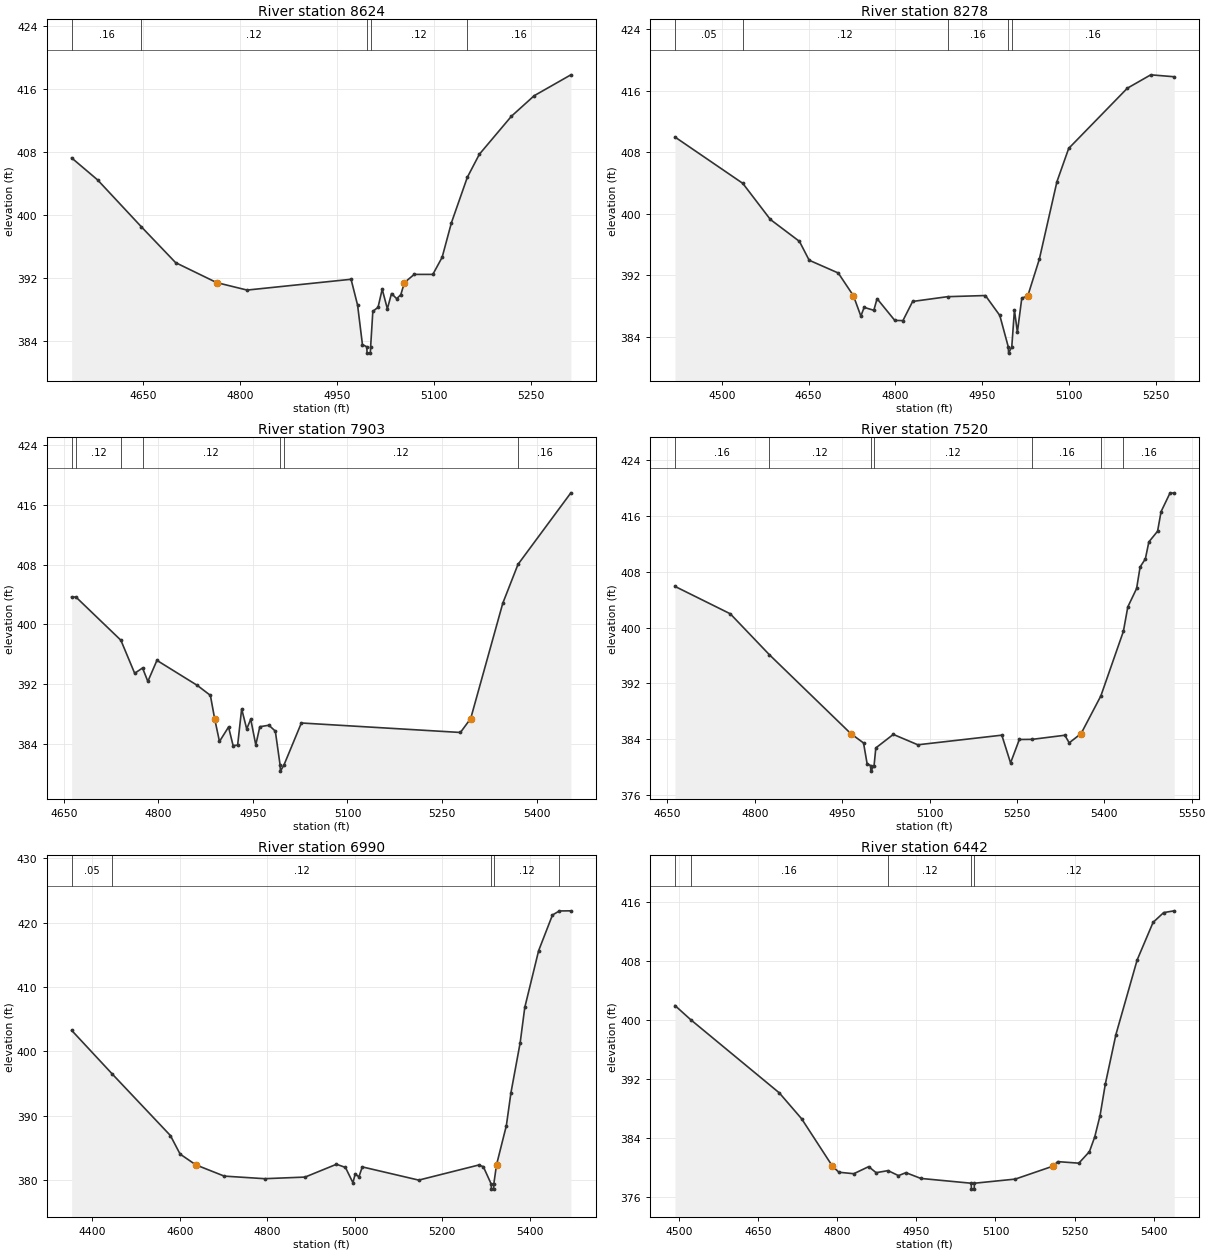
Type RM Length L Ch R = 1,8624,346,346,346
BEGIN DESCRIPTION:
UNT 031 IN DRY CR WATERSHED 17.0
END DESCRIPTION:
XS GIS Cut Line= 3
      2881675.00      6976274.97      2881725.00      6975825.00
      2881975.00      6975625.00
#Sta/Elev= 30
  4539.2  407.22  4579.4  404.43  4647.0  398.49  4700.2  393.93  4763.7  391.40
  4810.8  390.45  4971.8  391.82  4981.9  388.54  4989.4  383.54  4996.1  383.25
  4996.6  382.45  5001.6  382.45  5002.1  383.25  5005.5  387.75  5013.6  388.27
  5020.0  390.56  5028.0  388.07  5034.4  390.01  5042.4  389.36  5048.8  389.86
  5054.4  391.40  5069.6  392.44  5098.4  392.44  5112.8  394.61  5127.2  399.00
  5151.8  404.76  5170.4  407.68  5220.1  412.51  5255.3  415.11  5312.1  417.76
#Mann=5,-1,0
  4539.2    0.16       0  4647.0    0.12       0  4996.1    0.07       0
  5002.1    0.12       0  5151.8    0.16       0
Bank Sta=4763.7,5054.4
Exp/Cntr=0.3,0.1

Type RM Length L Ch R = 1,8278,375,375,375
BEGIN DESCRIPTION:
UNT 031 IN DRY CR WATERSHED 16.0
END DESCRIPTION:
XS GIS Cut Line= 3
      2881825.00      6976375.00      2882075.00      6975875.00
      2882024.99      6975574.96
#Sta/Elev= 30
  4419.1  409.97  4536.3  403.95  4584.0  399.25  4634.3  396.40  4651.1  393.95
  4701.4  392.29  4727.7  389.32  4740.5  386.68  4746.1  387.82  4762.9  387.44
  4768.5  388.95  4799.2  386.12  4813.2  386.10  4830.0  388.59  4890.3  389.21
  4955.8  389.36  4980.7  386.77  4995.4  382.67  4995.9  381.87  5001.4  382.67
  5006.0  387.47  5011.1  384.60  5018.7  389.01  5029.1  389.32  5049.1  394.10
  5079.5  404.17  5099.8  408.49  5201.2  416.32  5241.7  418.06  5282.3  417.81
#Mann=5,-1,0
  4419.1    0.05       0  4536.3    0.12       0  4890.3    0.16       0
  4995.4    0.07       0  5001.4    0.16       0
Bank Sta=4727.7,5029.1
Exp/Cntr=0.3,0.1

Type RM Length L Ch R = 1,7903,383,383,383
BEGIN DESCRIPTION:
UNT 031 IN DRY CR WATERSHED 15.0
END DESCRIPTION:
XS GIS Cut Line= 3
      2882075.00      6976325.00      2882325.00      6976125.00
      2882575.03      6975724.96
#Sta/Elev= 30
  4662.5  403.70  4669.4  403.67  4740.6  397.89  4762.5  393.46  4775.0  394.17
  4783.4  392.37  4797.8  395.19  4861.8  391.84  4882.6  390.50  4889.3  387.40
  4897.0  384.32  4911.4  386.26  4918.6  383.78  4925.8  383.82  4932.2  388.69
  4940.2  386.00  4946.6  387.31  4954.6  383.86  4961.0  386.30  4975.4  386.50
  4985.6  385.71  4993.2  381.15  4993.7  380.35  4999.2  381.15  5026.9  386.80
  5279.2  385.53  5295.5  387.40  5346.4  402.85  5370.5  408.05  5454.4  417.64
#Mann=7,-1,0
  4662.5    0.16       0  4669.4    0.12       0  4740.6    0.16       0
  4775.0    0.12       0  4993.2    0.07       0  4999.2    0.12       0
  5370.5    0.16       0
Bank Sta=4889.3,5295.5
Exp/Cntr=0.3,0.1

Type RM Length L Ch R = 1,7520,530,530,530
BEGIN DESCRIPTION:
UNT 031 IN DRY CR WATERSHED 14.0
END DESCRIPTION:
XS GIS Cut Line= 3
      2882225.00      6976475.00      2882525.00      6976375.00
      2882825.02      6975924.97
#Sta/Elev= 30
  4663.0  405.92  4757.9  401.99  4824.9  396.13  4964.8  384.80  4986.7  383.45
  4992.8  380.49  4998.8  380.21  4999.3  379.41  5004.8  380.21  5007.8  382.74
  5037.8  384.68  5079.9  383.19  5224.1  384.57  5239.1  380.59  5254.2  383.95
  5276.2  383.97  5332.3  384.56  5339.8  383.47  5360.2  384.80  5394.1  390.20
  5432.8  399.47  5440.4  402.98  5455.5  405.62  5461.5  408.71  5470.5  409.86
  5476.5  412.30  5491.5  413.84  5497.5  416.65  5512.6  419.28  5520.1  419.35
#Mann=7,-1,0
  4663.0    0.16       0  4824.9    0.12       0  4998.8    0.07       0
  5004.8    0.12       0  5276.2    0.16       0  5394.1    0.12       0
  5432.8    0.16       0
Bank Sta=4964.8,5360.2
Exp/Cntr=0.3,0.1

Type RM Length L Ch R = 1,6990,548,548,548
BEGIN DESCRIPTION:
UNT 031 IN DRY CR WATERSHED 13.0
END DESCRIPTION:
XS GIS Cut Line= 3
      2882875.00      6977075.01      2883025.00      6976425.00
      2882875.01      6975975.04
#Sta/Elev= 30
  4352.4  403.27  4445.7  396.46  4578.2  386.94  4600.4  384.06  4636.3  382.39
  4701.3  380.64  4793.7  380.24  4886.1  380.49  4957.9  382.48  4978.4  381.99
  4995.5  379.61  5000.7  380.97  5009.2  380.52  5016.9  382.07  5146.0  380.02
  5283.0  382.36  5293.6  382.11  5311.6  379.42  5312.1  378.62  5317.1  378.62
  5317.6  379.42  5323.8  382.39  5346.3  388.48  5356.8  393.59  5377.9  401.36
  5388.4  406.82  5420.1  415.64  5451.7  421.17  5467.4  421.80  5493.8  421.82
#Mann=5,-1,0
  4352.4    0.05       0  4445.7    0.12       0  5311.6    0.07       0
  5317.6    0.12       0  5467.4    0.16       0
Bank Sta=4636.3,5323.8
Exp/Cntr=0.3,0.1

Type RM Length L Ch R = 1,6442,213,213,213
BEGIN DESCRIPTION:
UNT 031 IN DRY CR WATERSHED 12.0
END DESCRIPTION:
XS GIS Cut Line= 3
      2883025.01      6977124.99      2883375.00      6976775.00
      2883425.00      6976325.03
#Sta/Elev= 30
  4491.6  401.96  4521.3  400.05  4689.6  390.12  4732.0  386.61  4790.4  380.19
  4802.7  379.36  4831.0  379.16  4859.3  380.12  4873.4  379.30  4896.1  379.58
  4915.8  378.90  4930.0  379.30  4958.3  378.52  5053.9  377.87  5054.4  377.07
  5059.5  377.07  5060.0  377.87  5137.5  378.43  5209.3  380.19  5218.0  380.80
  5258.2  380.59  5278.3  382.15  5288.4  384.15  5298.5  387.05  5308.5  391.32
  5328.6  398.03  5368.9  408.14  5399.1  413.23  5419.2  414.56  5439.3  414.80
#Mann=5,-1,0
  4491.6    0.05       0  4521.3    0.16       0  4896.1    0.12       0
  5053.9    0.07       0  5060.0    0.12       0
Bank Sta=4790.4,5209.3
Exp/Cntr=0.3,0.1

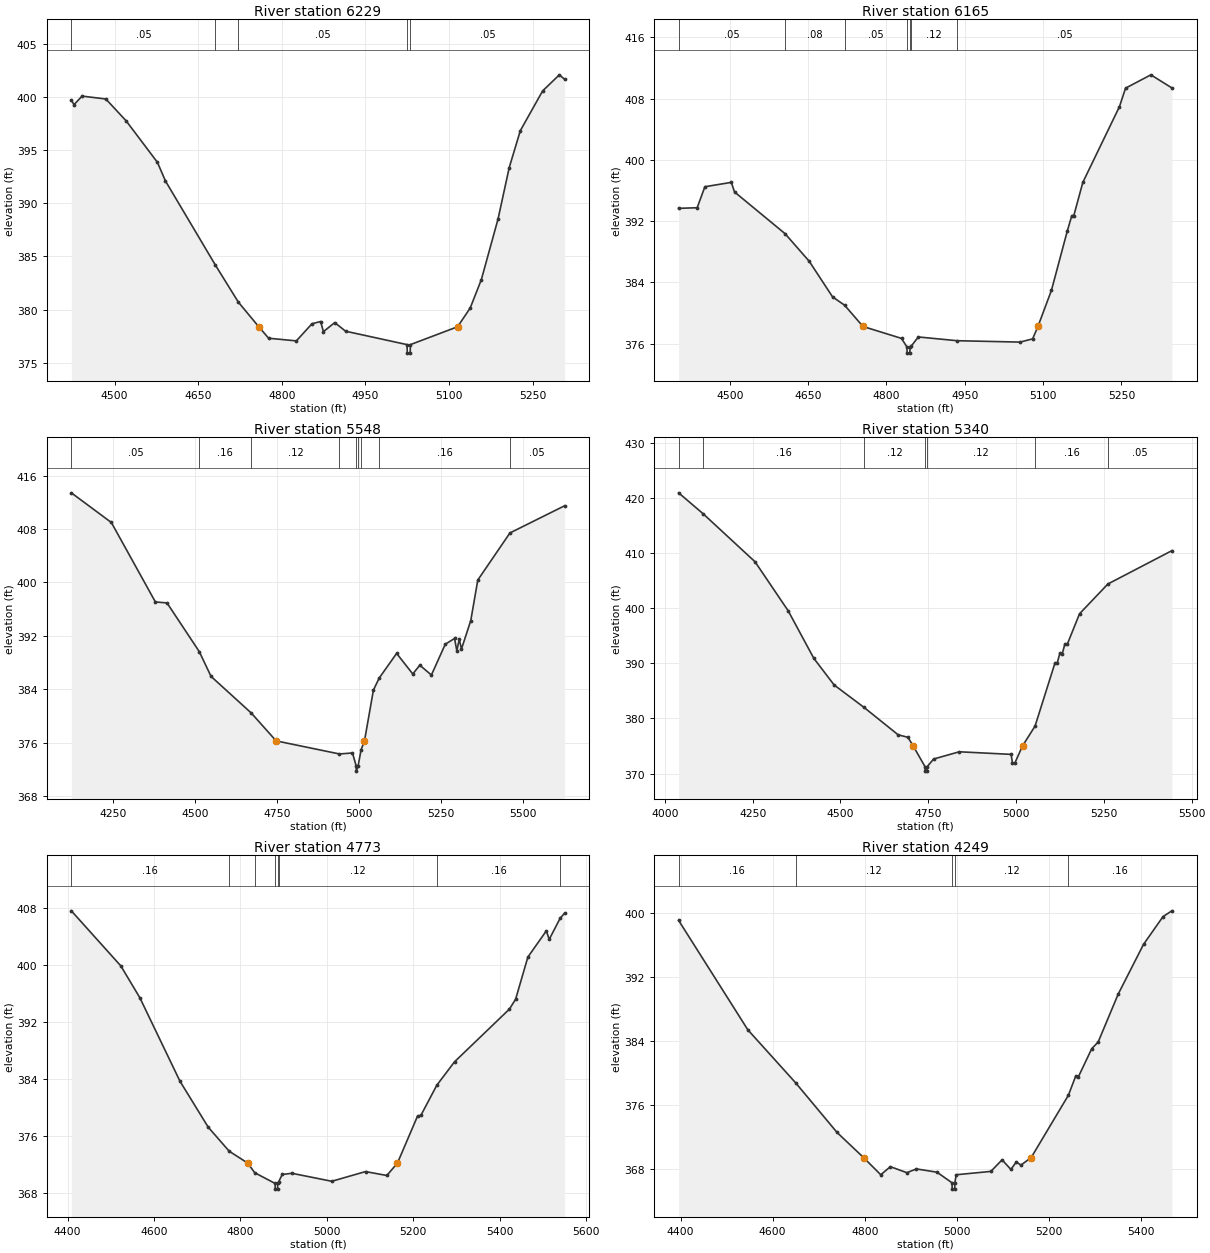
Type RM Length L Ch R = 1,6229,64,64,64
BEGIN DESCRIPTION:
Mapping XS f423017d
END DESCRIPTION:
XS GIS Cut Line= 4
      2883247.48      6977404.29      2883490.53      6977084.85
      2883535.67      6976869.58      2883539.14      6976605.65
#Sta/Elev= 30
  4422.2  399.68  4427.0  399.26  4441.5  400.06  4484.1  399.79  4520.5  397.74
  4576.7  393.84  4591.2  392.08  4680.9  384.17  4722.0  380.70  4758.6  378.39
  4776.3  377.31  4826.1  377.06  4854.1  378.67  4869.6  378.88  4874.7  377.93
  4895.0  378.78  4914.4  377.97  5024.7  376.71  5025.2  375.91  5030.3  375.91
  5030.8  376.71  5115.5  378.39  5138.1  380.15  5158.1  382.82  5188.1  388.52
  5208.1  393.34  5228.1  396.82  5268.1  400.55  5298.1  402.06  5307.5  401.64
#Mann=5,-1,0
  4422.2    0.05       0  4680.9    0.16       0  4722.0    0.05       0
  5024.7    0.04       0  5030.8    0.05       0
Bank Sta=4758.6,5115.5
Exp/Cntr=0.3,0.1

Type RM Length L Ch R = 1,6165,617,617,617
BEGIN DESCRIPTION:
Mapping XS beaf94d3
END DESCRIPTION:
XS GIS Cut Line= 5
      2883309.97      6977449.43      2883532.19      6977129.99
      2883580.81      6977008.46      2883594.69      6976772.35
      2883605.11      6976584.88
#Sta/Elev= 30
  4402.2  393.67  4437.7  393.75  4452.5  396.49  4503.1  397.06  4509.2  395.81
  4605.9  390.37  4652.4  386.75  4696.9  382.12  4720.0  381.03  4755.1  378.26
  4829.0  376.70  4839.2  375.58  4839.7  374.78  4844.8  374.78  4845.3  375.58
  4847.1  375.66  4861.1  376.89  4935.3  376.40  5055.9  376.22  5079.9  376.64
  5090.1  378.26  5116.0  382.99  5146.1  390.67  5154.9  392.72  5158.7  392.72
  5176.1  397.07  5246.2  406.95  5257.8  409.35  5306.3  411.09  5346.5  409.38
#Mann=7,-1,0
  4402.2    0.05       0  4605.9    0.08       0  4720.0    0.05       0
  4839.2    0.04       0  4845.3    0.05       0  4847.1    0.12       0
  4935.3    0.05       0
Bank Sta=4755.1,5090.1
Exp/Cntr=0.3,0.1

Type RM Length L Ch R = 1,5548,208,208,208
BEGIN DESCRIPTION:
Mapping XS fe024fde
END DESCRIPTION:
XS GIS Cut Line= 3
      2883171.07      6978053.62      2883862.06      6977383.46
      2884253.60      6977009.24
#Sta/Elev= 30
  4122.8  413.41  4244.8  408.97  4379.1  397.07  4414.6  396.92  4513.1  389.62
  4548.8  385.92  4671.6  380.43  4747.4  376.26  4940.5  374.30  4980.2  374.45
  4991.3  372.53  4991.8  371.73  4997.4  372.53  5006.6  374.96  5016.8  376.26
  5044.0  383.86  5061.5  385.66  5114.8  389.36  5164.1  386.28  5185.5  387.60
  5220.8  386.12  5263.2  390.74  5291.5  391.60  5298.4  389.75  5305.7  391.49
  5312.6  390.03  5340.9  394.28  5362.3  400.35  5460.3  407.40  5627.0  411.47
#Mann=9,-1,0
  4122.8    0.05       0  4513.1    0.16       0  4671.6    0.12       0
  4940.5    0.16       0  4991.3    0.07       0  4997.4    0.16       0
  5006.6    0.12       0  5061.5    0.16       0  5460.3    0.05       0
Bank Sta=4747.4,5016.8
Exp/Cntr=0.3,0.1

Type RM Length L Ch R = 1,5340,567,567,567
BEGIN DESCRIPTION:
UNT 031 IN DRY CR WATERSHED 10.0
END DESCRIPTION:
XS GIS Cut Line= 3
      2883474.99      6978325.01      2883975.00      6977525.00
      2884275.01      6977174.99
#Sta/Elev= 30
  4039.3  420.94  4109.5  417.12  4256.9  408.43  4351.2  399.54  4424.3  390.91
  4482.1  386.08  4566.4  382.05  4664.3  377.04  4692.0  376.59  4707.2  375.02
  4740.9  371.25  4741.4  370.45  4746.5  370.45  4747.0  371.25  4765.1  372.64
  4838.3  373.96  4986.0  373.49  4989.8  371.93  4996.4  371.89  5018.4  375.02
  5054.1  378.62  5110.6  390.02  5117.2  390.07  5124.8  391.83  5131.4  391.68
  5139.1  393.53  5145.7  393.44  5180.8  399.00  5261.5  404.40  5443.7  410.45
#Mann=7,-1,0
  4039.3    0.05       0  4109.5    0.16       0  4566.4    0.12       0
  4740.9    0.07       0  4747.0    0.12       0  5054.1    0.16       0
  5261.5    0.05       0
Bank Sta=4707.2,5018.4
Exp/Cntr=0.3,0.1

Type RM Length L Ch R = 1,4773,524,524,524
BEGIN DESCRIPTION:
UNT 031 IN DRY CR WATERSHED 9.0
END DESCRIPTION:
XS GIS Cut Line= 3
      2883775.04      6978274.97      2884275.00      6977925.00
      2884625.01      6977524.99
#Sta/Elev= 30
  4408.6  407.55  4523.2  399.83  4567.2  395.37  4660.1  383.67  4725.5  377.23
  4774.1  373.86  4816.9  372.20  4833.1  370.85  4880.2  369.35  4880.7  368.55
  4885.9  368.55  4886.4  369.35  4888.4  369.56  4896.8  370.60  4919.1  370.77
  5011.5  369.65  5089.6  371.01  5138.9  370.46  5163.5  372.20  5210.1  378.80
  5217.7  378.88  5254.6  383.11  5295.6  386.39  5422.7  393.78  5437.0  395.16
  5465.4  401.07  5508.2  404.75  5514.8  403.55  5540.1  406.51  5550.4  407.22
#Mann=8,-1,0
  4408.6    0.16       0  4774.1    0.12       0  4833.1    0.16       0
  4880.2    0.07       0  4886.4    0.16       0  4888.4    0.12       0
  5254.6    0.16       0  5540.1    0.05       0
Bank Sta=4816.9,5163.5
Exp/Cntr=0.3,0.1

Type RM Length L Ch R = 1,4249,549,549,549
BEGIN DESCRIPTION:
UNT 031 IN DRY CR WATERSHED 8.0
END DESCRIPTION:
XS GIS Cut Line= 3
      2884175.00      6978575.00      2884675.00      6978225.00
      2884775.00      6977775.00
#Sta/Elev= 30
  4395.8  399.09  4546.2  385.39  4650.1  378.75  4739.8  372.55  4797.5  369.40
  4834.8  367.25  4855.7  368.26  4891.5  367.51  4912.4  367.98  4956.9  367.57
  4989.5  366.25  4990.0  365.45  4995.3  365.45  4995.8  366.25  4998.7  367.25
  5074.0  367.67  5098.3  369.12  5117.5  367.91  5129.1  368.85  5139.3  368.46
  5161.5  369.40  5242.3  377.20  5258.4  379.63  5263.5  379.45  5293.0  383.03
  5307.0  383.87  5350.6  389.88  5405.6  396.10  5447.9  399.57  5467.1  400.29
#Mann=5,-1,0
  4395.8    0.16       0  4650.1    0.12       0  4989.5    0.07       0
  4995.8    0.12       0  5242.3    0.16       0
Bank Sta=4797.5,5161.5
Exp/Cntr=0.3,0.1

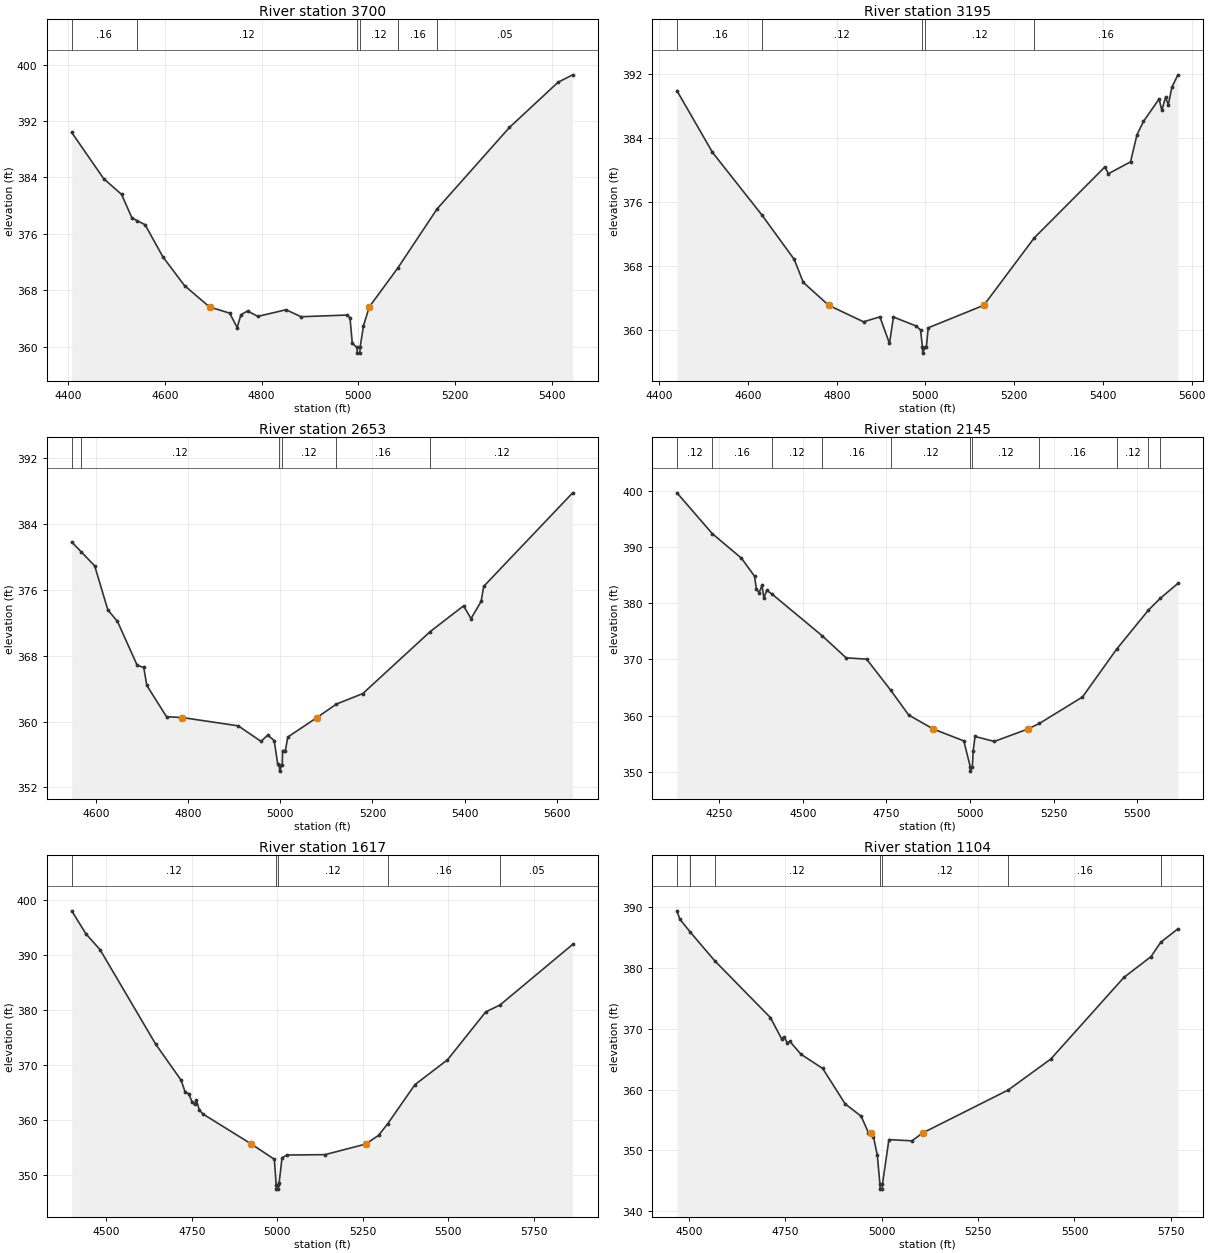
Type RM Length L Ch R = 1,3700,505,505,505
BEGIN DESCRIPTION:
UNT 031 IN DRY CR WATERSHED 7.0
END DESCRIPTION:
XS GIS Cut Line= 3
      2884624.96      6978775.02      2885125.00      6978475.00
      2885175.00      6978025.01
#Sta/Elev= 30
  4407.5  390.37  4473.6  383.82  4510.6  381.59  4531.9  378.28  4542.2  377.88
  4559.1  377.30  4596.1  372.73  4640.8  368.66  4692.6  365.63  4734.1  364.76
  4749.6  362.71  4757.4  364.53  4771.0  365.06  4792.4  364.30  4850.7  365.24
  4881.8  364.25  4977.0  364.49  4982.9  364.11  4987.7  360.47  4997.5  359.89
  4998.0  359.09  5003.3  359.09  5003.8  359.89  5010.8  362.96  5022.7  365.63
  5082.2  371.20  5163.1  379.54  5312.6  391.08  5413.2  397.49  5443.4  398.54
#Mann=6,-1,0
  4407.5    0.16       0  4542.2    0.12       0  4997.5    0.07       0
  5003.8    0.12       0  5082.2    0.16       0  5163.1    0.05       0
Bank Sta=4692.6,5022.7
Exp/Cntr=0.3,0.1

Type RM Length L Ch R = 1,3195,542,542,542
BEGIN DESCRIPTION:
UNT 031 IN DRY CR WATERSHED 6.0
END DESCRIPTION:
XS GIS Cut Line= 3
      2884624.99      6978825.00      2885175.00      6978925.00
      2885624.99      6978575.01
#Sta/Elev= 30
  4440.0  389.95  4520.0  382.24  4631.4  374.40  4704.3  368.84  4724.6  365.97
  4781.9  363.10  4860.5  361.03  4897.4  361.65  4919.0  358.32  4927.9  361.63
  4978.7  360.51  4988.9  360.02  4993.3  357.91  4993.8  357.11  4999.6  357.91
  5002.2  357.91  5006.3  360.28  5131.6  363.10  5245.2  371.53  5404.4  380.41
  5412.6  379.57  5462.3  381.05  5476.8  384.44  5491.3  386.10  5526.6  388.91
  5532.9  387.49  5541.1  389.13  5547.4  388.20  5555.5  390.40  5569.1  391.94
#Mann=5,-1,0
  4440.0    0.16       0  4631.4    0.12       0  4993.3    0.07       0
  4999.6    0.12       0  5245.2    0.16       0
Bank Sta=4781.9,5131.6
Exp/Cntr=0.3,0.1

Type RM Length L Ch R = 1,2653,508,508,508
BEGIN DESCRIPTION:
UNT 031 IN DRY CR WATERSHED 5.0
END DESCRIPTION:
XS GIS Cut Line= 3
      2884625.02      6979125.02      2884975.00      6979425.00
      2885524.96      6979724.98
#Sta/Elev= 30
  4547.3  381.82  4567.8  380.63  4597.2  378.91  4625.7  373.57  4646.6  372.17
  4689.4  366.84  4703.7  366.57  4710.3  364.39  4753.1  360.59  4787.4  360.49
  4908.9  359.48  4958.3  357.59  4972.6  358.36  4986.8  357.70  4994.5  354.82
  4998.0  354.78  4998.5  353.98  5004.3  354.78  5005.0  356.48  5011.1  356.48
  5016.3  358.12  5079.7  360.49  5121.6  362.12  5179.1  363.40  5325.6  370.94
  5397.9  374.06  5414.0  372.51  5435.9  374.59  5441.6  376.43  5634.7  387.79
#Mann=6,-1,0
  4547.3    0.16       0  4567.8    0.12       0  4998.0    0.07       0
  5004.3    0.12       0  5121.6    0.16       0  5325.6    0.12       0
Bank Sta=4787.4,5079.7
Exp/Cntr=0.3,0.1

Type RM Length L Ch R = 1,2145,528,528,528
BEGIN DESCRIPTION:
UNT 031 IN DRY CR WATERSHED 4.0
END DESCRIPTION:
XS GIS Cut Line= 3
      2883874.96      6979424.98      2884675.00      6979825.00
      2885224.98      6980074.99
#Sta/Elev= 30
  4123.2  399.63  4228.9  392.37  4316.1  388.01  4355.2  384.81  4360.8  382.53
  4369.2  381.88  4377.6  383.21  4383.2  380.90  4391.6  382.30  4407.3  381.64
  4557.3  374.23  4629.2  370.29  4690.6  370.05  4762.7  364.52  4816.4  360.12
  4889.8  357.63  4981.3  355.52  5000.5  350.94  5001.0  350.14  5006.9  350.94
  5009.3  353.72  5014.9  356.30  5072.6  355.42  5172.9  357.63  5207.4  358.62
  5336.2  363.32  5438.2  371.81  5533.6  378.78  5569.1  380.88  5621.8  383.52
#Mann=11,-1,0
  4123.2    0.12       0  4228.9    0.16       0  4407.3    0.12       0
  4557.3    0.16       0  4762.7    0.12       0  5000.5    0.07       0
  5006.9    0.12       0  5207.4    0.16       0  5438.2    0.12       0
  5533.6    0.16       0  5569.1    0.12       0
Bank Sta=4889.8,5172.9
Exp/Cntr=0.3,0.1

Type RM Length L Ch R = 1,1617,513,513,513
BEGIN DESCRIPTION:
UNT 031 IN DRY CR WATERSHED 3.0
END DESCRIPTION:
XS GIS Cut Line= 3
      2883774.99      6980075.00      2884325.00      6980225.00
      2885124.98      6980624.99
#Sta/Elev= 30
  4399.1  397.97  4440.6  393.80  4482.0  390.92  4644.4  373.79  4718.7  367.25
  4730.8  365.07  4741.2  364.78  4751.5  363.19  4758.4  362.86  4763.6  363.59
  4772.3  361.81  4782.6  361.10  4924.4  355.64  4991.6  352.87  4996.7  348.26
  4997.2  347.46  5002.7  347.46  5003.2  348.26  5005.5  348.63  5013.9  353.14
  5027.9  353.65  5139.7  353.72  5258.4  355.64  5296.2  357.22  5323.1  359.35
  5402.4  366.42  5497.5  370.92  5609.3  379.62  5651.4  380.89  5863.6  391.88
#Mann=5,-1,0
  4399.1    0.12       0  4996.7    0.07       0  5003.2    0.12       0
  5323.1    0.16       0  5651.4    0.05       0
Bank Sta=4924.4,5258.4
Exp/Cntr=0.3,0.1

Type RM Length L Ch R = 1,1104,303,303,303
BEGIN DESCRIPTION:
UNT 031 IN DRY CR WATERSHED 2.0
END DESCRIPTION:
XS GIS Cut Line= 3
      2883775.04      6980425.03      2884175.00      6980725.00
      2884975.05      6980725.00
#Sta/Elev= 30
  4468.5  389.41  4475.7  388.06  4503.5  385.88  4566.1  381.22  4711.2  371.84
  4740.3  368.33  4746.6  368.72  4754.9  367.65  4761.2  367.96  4790.3  365.82
  4846.6  363.49  4904.9  357.67  4946.6  355.62  4965.3  352.93  4971.7  352.87
  4978.5  352.23  4988.5  349.18  4995.2  344.44  4995.7  343.64  5001.2  343.64
  5001.7  344.44  5018.5  351.79  5078.5  351.58  5105.8  352.87  5328.0  359.94
  5438.5  365.03  5628.5  378.47  5698.5  381.87  5724.1  384.26  5768.5  386.45
#Mann=7,-1,0
  4468.5    0.12       0  4503.5    0.07       0  4566.1    0.12       0
  4995.2    0.07       0  5001.7    0.12       0  5328.0    0.16       0
  5724.1    0.05       0
Bank Sta=4971.7,5105.8
Exp/Cntr=0.3,0.1

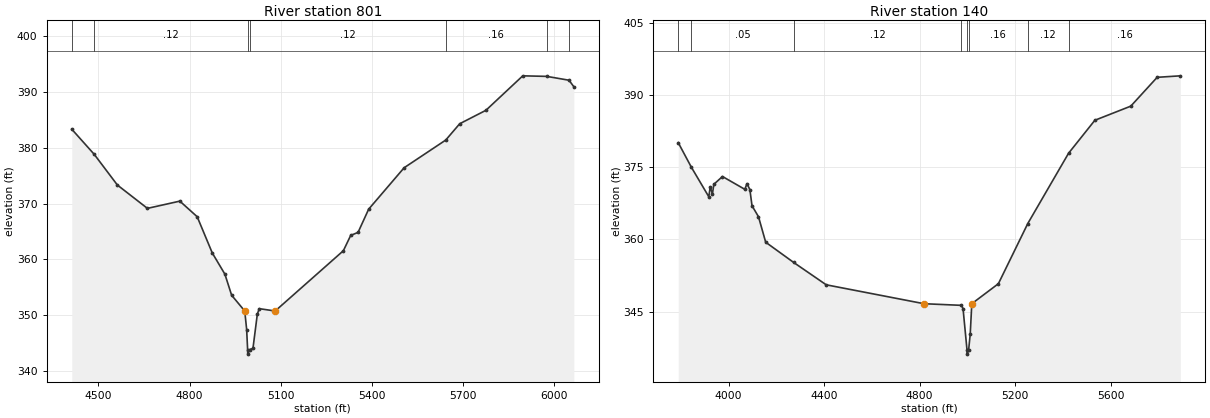
Type RM Length L Ch R = 1,801,661,661,661
BEGIN DESCRIPTION:
Mapping XS 8283a7c5
END DESCRIPTION:
XS GIS Cut Line= 3
      2883686.35      6980632.42      2884165.53      6981028.26
      2885123.90      6981413.69
#Sta/Elev= 30
  4412.0  383.34  4486.0  378.83  4562.3  373.32  4661.3  369.13  4768.1  370.43
  4825.3  367.63  4875.0  361.13  4916.6  357.32  4938.8  353.54  4982.0  350.71
  4988.3  347.39  4991.5  343.77  4992.0  342.97  4998.0  343.77  5009.1  344.00
  5023.5  350.16  5029.9  351.13  5082.3  350.71  5307.0  361.53  5331.2  364.28
  5355.4  364.82  5390.3  368.98  5507.2  376.42  5644.3  381.39  5690.4  384.32
  5776.7  386.73  5898.2  392.92  5977.3  392.82  6050.6  392.13  6066.5  390.96
#Mann=7,-1,0
  4412.0    0.05       0  4486.0    0.12       0  4991.5    0.07       0
  4998.0    0.12       0  5644.3    0.16       0  5977.3     0.1       0
  6050.6    0.16       0
Bank Sta=4982,5082.3
Exp/Cntr=0.3,0.1

Type RM Length L Ch R = 1,140,0,0,0
BEGIN DESCRIPTION:
UNT 031 IN DRY CR WATERSHED 1.0
END DESCRIPTION:
XS GIS Cut Line= 3
      2883389.47      6980663.64      2884000.00      6981600.00
      2884981.62      6981512.78
#Sta/Elev= 30
  3788.7  380.11  3843.7  375.00  3916.8  368.86  3922.7  370.94  3931.9  369.41
  3937.8  371.45  3974.1  373.07  4067.6  370.41  4076.7  371.59  4088.8  370.35
  4097.8  366.99  4124.9  364.71  4155.1  359.41  4272.2  355.21  4408.6  350.56
  4818.3  346.63  4975.0  346.29  4981.8  345.62  4998.6  336.95  4999.1  336.15
  5005.1  336.95  5011.9  340.31  5018.5  346.63  5129.9  350.79  5253.0  363.29
  5423.8  377.90  5534.0  384.76  5684.6  387.70  5795.0  393.69  5892.0  394.00
#Mann=8,-1,0
  3788.7    0.16       0  3843.7    0.05       0  4272.2    0.12       0
  4975.0    0.16       0  4998.6    0.07       0  5005.1    0.16       0
  5253.0    0.12       0  5423.8    0.16       0
Bank Sta=4818.3,5018.5
Exp/Cntr=0.3,0.1

Chan Stop Cuts=-1