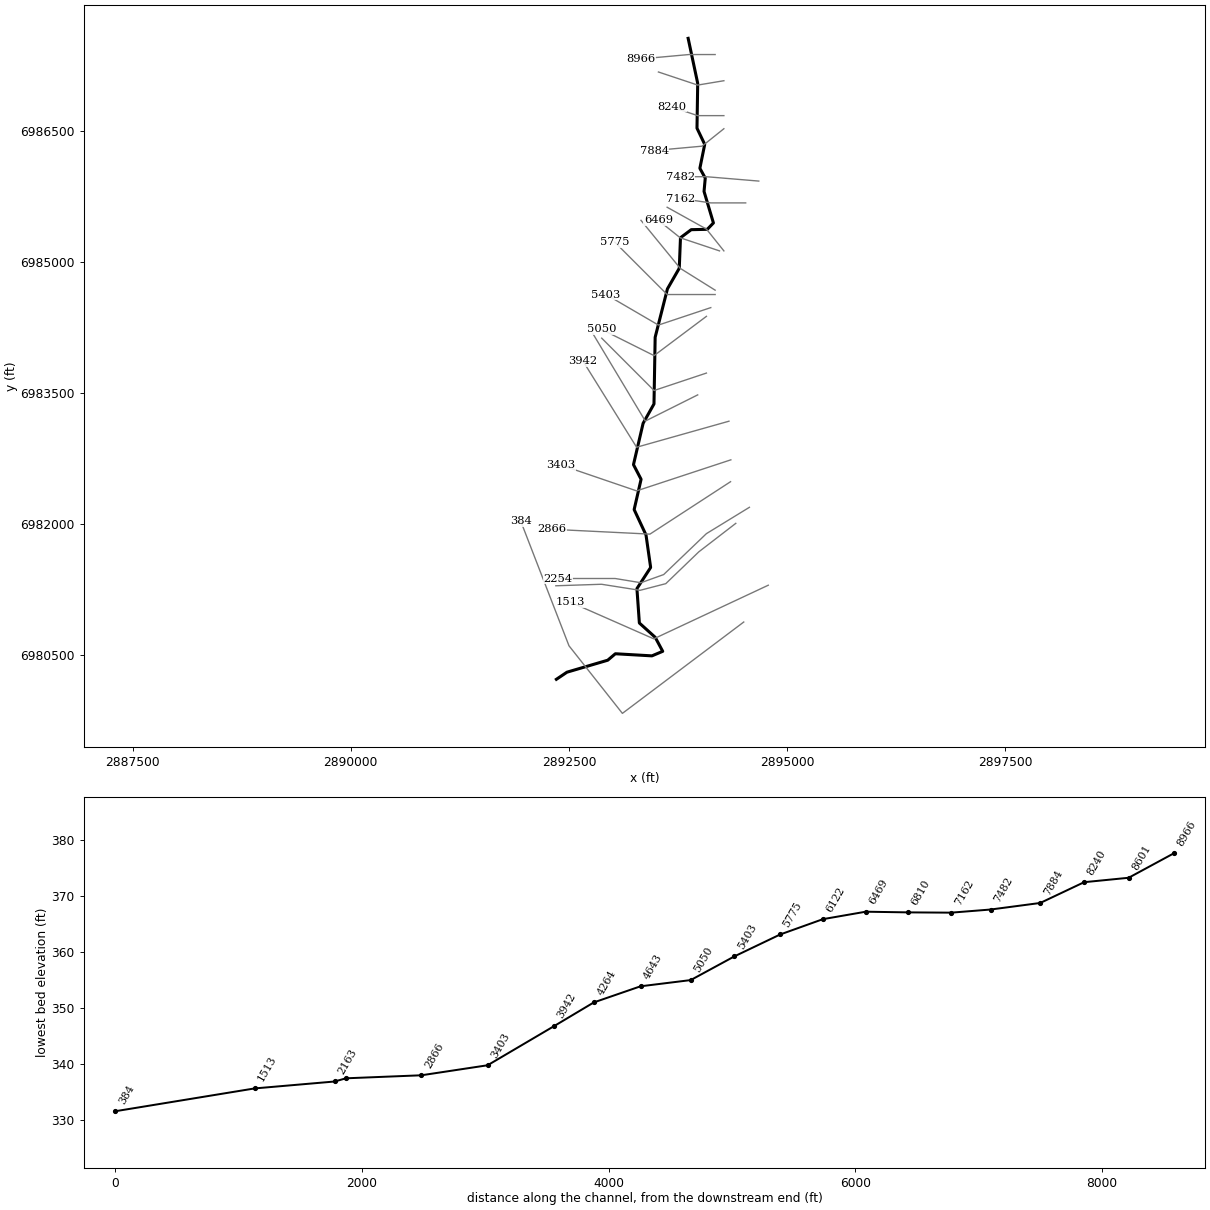
--- UNT 032 IN DRY CR WATERSHED.prj (project) ---

Proj Title=UNT 032 IN DRY CR WATERSHED Base Level Engineering
Current Plan=p01
Default Exp/Contr=0.3,0.1
English Units
Geom File=g01
Flow File=f01
Plan File=p01
BEGIN DESCRIPTION:
UNT 032 IN DRY CR WATERSHED
END DESCRIPTION:

--- UNT 032 IN DRY CR WATERSHED.p01 (plan) ---

Plan Title=Multiple Run
Short Identifier=Multiple
Geom File=g01
Flow File=f01
Subcritical Flow
K Sum by GR= 0
Std Step Tol= 0.01
Critical Tol= 0.01
Num of Std Step Trials= 20
Max Error Tol= 0.3
Flow Tol Ratio= 0.001
Split Flow NTrial= 30
Split Flow Tol= 0.02
Split Flow Ratio= 0.02
Log Output Level= 0
Friction Slope Method= 1
Unsteady Friction Slope Method= 2
Unsteady Bridges Friction Slope Method= 1
Parabolic Critical Depth
Global Vel Dist=  1 , 1 , 1
Global Log Level= 0
CheckData=True
Encroach Param= -1, 0, 0, 0
BEGIN DESCRIPTION:
Multiple Run
END DESCRIPTION:

--- UNT 032 IN DRY CR WATERSHED.f01 (steady flow) ---

Flow Title=Multiple
Number of Profiles=7
Profile Names=10-year,25-year,50-year,1pct_min,100-year,1pct_plu,500-year
River Rch & RM= UNT 032 IN DRY C,Reach-1,8966
     551     741     896     540    1077    2148    1556
River Rch & RM= UNT 032 IN DRY C,Reach-1,3403
     696     948    1155     700    1397    2786    2045
Boundary for River Rch & Prof#=UNT 032 IN DRY C,Reach-1,1
Up Type=0
Dn Type=3
Dn Slope=0.005
Boundary for River Rch & Prof#=UNT 032 IN DRY C,Reach-1,2
Up Type=0
Dn Type=3
Dn Slope=0.005
Boundary for River Rch & Prof#=UNT 032 IN DRY C,Reach-1,3
Up Type=0
Dn Type=3
Dn Slope=0.005
Boundary for River Rch & Prof#=UNT 032 IN DRY C,Reach-1,4
Up Type=0
Dn Type=3
Dn Slope=0.005
Boundary for River Rch & Prof#=UNT 032 IN DRY C,Reach-1,5
Up Type=0
Dn Type=3
Dn Slope=0.005
Boundary for River Rch & Prof#=UNT 032 IN DRY C,Reach-1,6
Up Type=0
Dn Type=3
Dn Slope=0.005
Boundary for River Rch & Prof#=UNT 032 IN DRY C,Reach-1,7
Up Type=0
Dn Type=3
Dn Slope=0.005

--- UNT 032 IN DRY CR WATERSHED.g01 (geometry) ---

Geom Title=Existing Conditions

River Reach=UNT 032 IN DRY C,Reach-1
Reach XY= 30
      2893865.59      6987560.71      2893975.08      6987045.37
      2893966.93      6986530.76      2894055.50      6986345.50
      2893999.84      6986071.41      2894061.64      6985959.33
      2894047.70      6985806.43      2894155.23      6985445.23
      2894085.07      6985372.15      2893900.78      6985368.15
      2893777.68      6985275.74      2893763.85      6984926.06
      2893628.13      6984689.65      2893487.56      6984135.19
      2893474.07      6983371.03      2893349.45      6983149.12
      2893239.11      6982675.61      2893326.26      6982507.78
      2893246.78      6982160.72      2893382.73      6981869.53
      2893435.84      6981497.32      2893278.57      6981255.08
      2893306.61      6980860.98      2893488.01      6980697.13
      2893574.14      6980536.43      2893450.56      6980484.43
      2893031.45      6980508.62      2892943.97      6980434.61
      2892476.80      6980297.27      2892355.55      6980215.69

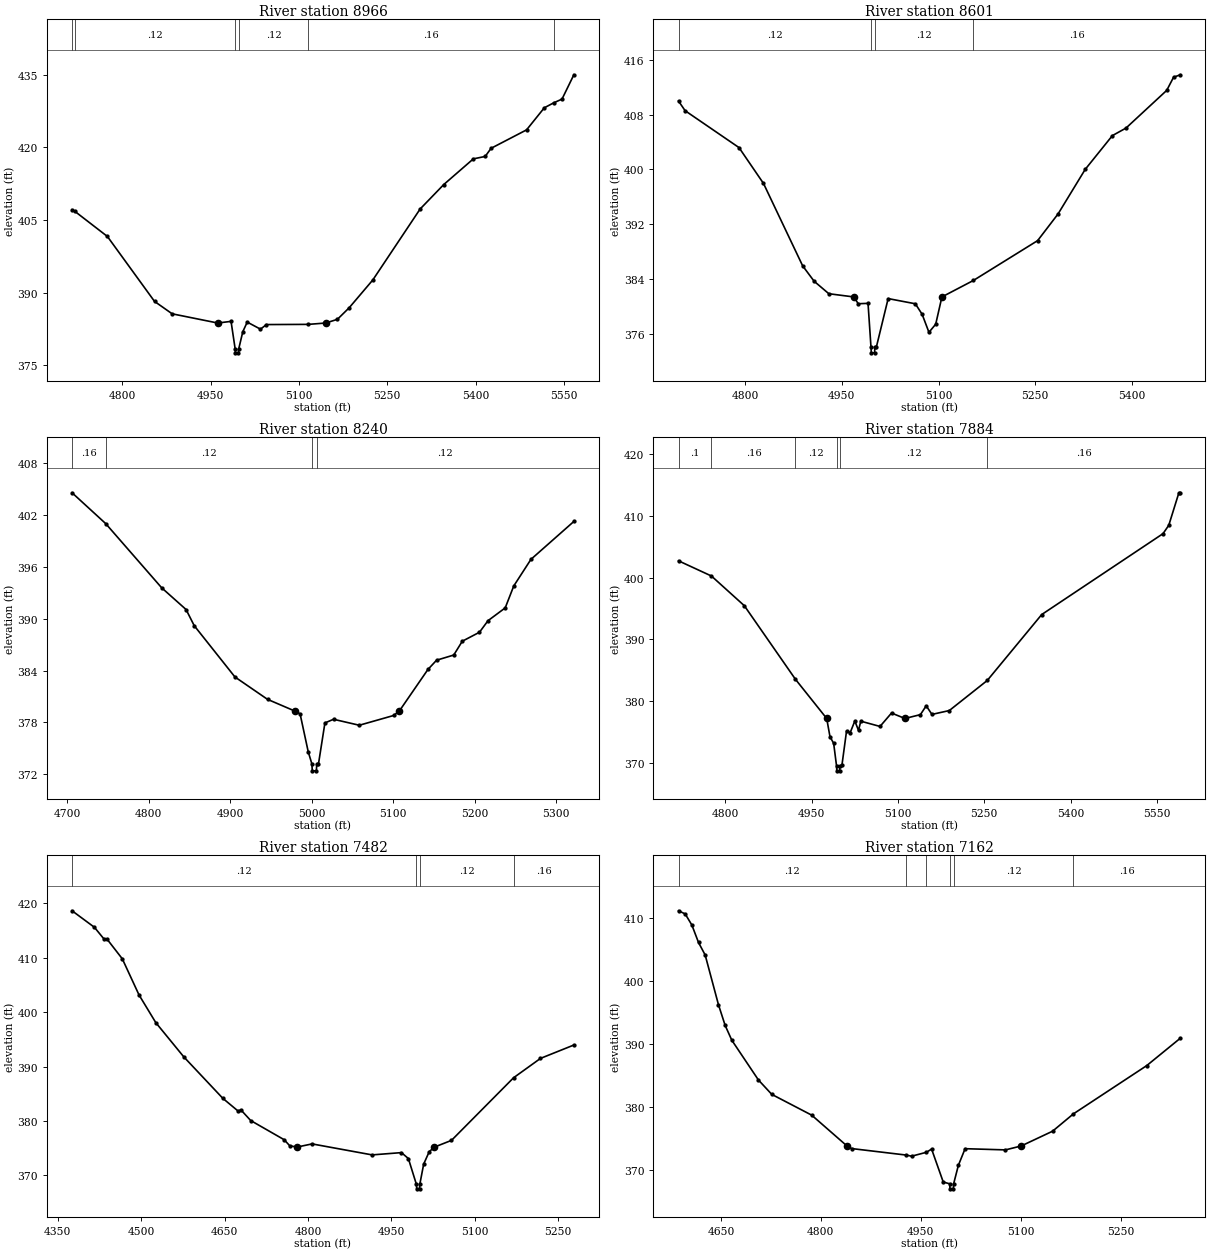
Type RM Length L Ch R = 1,8966,365,365,365
BEGIN DESCRIPTION:
UNT 032 IN DRY CR WATERSHED 17.0
END DESCRIPTION:
XS GIS Cut Line= 3
      2894174.95      6987375.00      2893875.00      6987375.00
      2893325.02      6987325.00
#Sta/Elev= 30
  4714.8  407.09  4719.5  406.77  4774.8  401.58  4854.8  388.17  4884.8  385.60
  4962.2  383.70  4984.8  384.04  4991.8  378.34  4992.3  377.54  4997.3  377.54
  4997.8  378.34  5004.8  381.92  5012.3  383.89  5034.8  382.43  5044.9  383.38
  5116.0  383.42  5145.6  383.70  5165.4  384.46  5185.5  386.86  5225.6  392.60
  5305.9  407.25  5346.1  412.31  5396.3  417.61  5416.4  418.11  5426.4  419.79
  5486.7  423.60  5516.8  428.16  5532.7  429.18  5546.9  429.96  5567.0  434.98
#Mann=6,-1,0
  4714.8    0.16       0  4719.5    0.12       0  4991.8    0.07       0
  4997.8    0.12       0  5116.0    0.16       0  5532.7    0.05       0
Bank Sta=4962.2,5145.6
Exp/Cntr=0.3,0.1

Type RM Length L Ch R = 1,8601,361,361,361
BEGIN DESCRIPTION:
UNT 032 IN DRY CR WATERSHED 16.0
END DESCRIPTION:
XS GIS Cut Line= 3
      2894275.02      6987075.00      2893975.00      6987025.00
      2893525.00      6987175.00
#Sta/Elev= 30
  4696.6  409.99  4706.8  408.58  4790.4  403.19  4828.4  397.95  4889.2  385.90
  4907.0  383.65  4929.8  381.83  4968.5  381.36  4975.4  380.37  4990.6  380.42
  4995.2  373.99  4995.7  373.19  5000.7  373.19  5001.2  373.99  5003.4  373.99
  5021.8  381.12  5064.0  380.36  5074.5  378.83  5085.1  376.19  5095.6  377.38
  5105.2  381.36  5154.1  383.77  5253.7  389.59  5285.4  393.49  5327.5  400.00
  5369.7  404.94  5390.8  406.04  5454.0  411.55  5464.6  413.47  5475.1  413.83
#Mann=4,-1,0
  4696.6    0.12       0  4995.2    0.07       0  5001.2    0.12       0
  5154.1    0.16       0
Bank Sta=4968.5,5105.2
Exp/Cntr=0.3,0.1

Type RM Length L Ch R = 1,8240,356,356,356
BEGIN DESCRIPTION:
UNT 032 IN DRY CR WATERSHED 15.0
END DESCRIPTION:
XS GIS Cut Line= 3
      2894275.00      6986675.00      2893975.00      6986675.00
      2893675.03      6986774.99
#Sta/Elev= 30
  4705.7  404.60  4746.9  401.04  4815.7  393.60  4845.7  391.08  4855.7  389.21
  4905.7  383.27  4945.7  380.68  4979.1  379.33  4985.7  379.00  4995.7  374.61
  5000.2  373.20  5000.7  372.40  5005.7  372.40  5006.2  373.20  5008.3  373.20
  5016.2  377.95  5026.8  378.37  5058.4  377.68  5100.6  378.81  5107.6  379.33
  5142.7  384.14  5153.3  385.21  5174.4  385.81  5184.9  387.41  5206.0  388.45
  5216.5  389.79  5237.6  391.27  5248.1  393.81  5269.2  396.89  5321.9  401.28
#Mann=4,-1,0
  4705.7    0.16       0  4746.9    0.12       0  5000.2    0.07       0
  5006.2    0.12       0
Bank Sta=4979.1,5107.6
Exp/Cntr=0.3,0.1

Type RM Length L Ch R = 1,7884,402,402,402
BEGIN DESCRIPTION:
UNT 032 IN DRY CR WATERSHED 14.0
END DESCRIPTION:
XS GIS Cut Line= 3
      2894274.98      6986524.98      2894025.00      6986325.00
      2893474.99      6986275.00
#Sta/Elev= 30
  4718.5  402.70  4775.7  400.24  4832.9  395.43  4921.8  383.51  4976.1  377.17
  4981.8  374.22  4988.2  373.14  4993.2  369.49  4993.7  368.69  4998.7  368.69
  4999.2  369.49  5002.6  369.61  5010.6  375.15  5017.0  374.89  5025.0  376.76
  5031.4  375.24  5035.4  376.73  5068.8  375.88  5088.8  378.05  5112.1  377.17
  5139.0  377.79  5149.1  379.22  5159.1  377.83  5189.2  378.45  5255.2  383.32
  5349.9  394.00  5560.8  407.10  5570.8  408.45  5588.4  413.72  5590.9  413.72
#Mann=6,-1,0
  4718.5     0.1       0  4775.7    0.16       0  4921.8    0.12       0
  4993.2    0.07       0  4999.2    0.12       0  5255.2    0.16       0
Bank Sta=4976.1,5112.1
Exp/Cntr=0.3,0.1

Type RM Length L Ch R = 1,7482,320,320,320
BEGIN DESCRIPTION:
UNT 032 IN DRY CR WATERSHED 13.0
END DESCRIPTION:
XS GIS Cut Line= 3
      2894675.02      6985925.00      2894075.00      6985975.00
      2893775.00      6985975.00
#Sta/Elev= 30
  4375.9  418.64  4416.1  415.60  4433.6  413.41  4438.6  413.45  4466.2  409.81
  4496.3  403.16  4526.4  398.08  4576.6  391.80  4646.9  384.16  4674.5  381.81
  4679.5  382.03  4697.0  380.08  4757.2  376.55  4767.3  375.43  4780.3  375.20
  4807.4  375.78  4915.3  373.76  4968.0  374.18  4980.5  373.09  4995.0  368.32
  4995.5  367.52  5000.5  367.52  5001.0  368.32  5008.0  372.07  5018.0  374.36
  5027.4  375.20  5058.0  376.43  5169.6  387.94  5218.0  391.50  5278.0  393.96
#Mann=4,-1,0
  4375.9    0.12       0  4995.0    0.07       0  5001.0    0.12       0
  5169.6    0.16       0
Bank Sta=4780.3,5027.4
Exp/Cntr=0.3,0.1

Type RM Length L Ch R = 1,7162,352,352,352
BEGIN DESCRIPTION:
UNT 032 IN DRY CR WATERSHED 12.0
END DESCRIPTION:
XS GIS Cut Line= 3
      2894525.00      6985675.00      2894125.00      6985675.00
      2893775.05      6985724.99
#Sta/Elev= 30
  4586.3  411.08  4596.3  410.58  4606.3  408.82  4616.3  406.05  4626.3  404.06
  4646.3  396.16  4656.3  392.89  4666.3  390.54  4706.3  384.23  4726.3  381.95
  4786.3  378.65  4839.3  373.76  4846.3  373.35  4928.1  372.32  4936.3  372.14
  4958.5  372.76  4966.3  373.27  4983.8  368.04  4993.4  367.76  4993.9  366.96
  4998.9  366.96  4999.4  367.76  5006.5  370.69  5016.6  373.33  5077.2  373.14
  5100.8  373.76  5147.9  376.10  5179.3  378.86  5289.3  386.51  5339.8  390.86
#Mann=6,-1,0
  4586.3    0.12       0  4928.1    0.16       0  4958.5    0.12       0
  4993.4    0.07       0  4999.4    0.12       0  5179.3    0.16       0
Bank Sta=4839.3,5100.8
Exp/Cntr=0.3,0.1

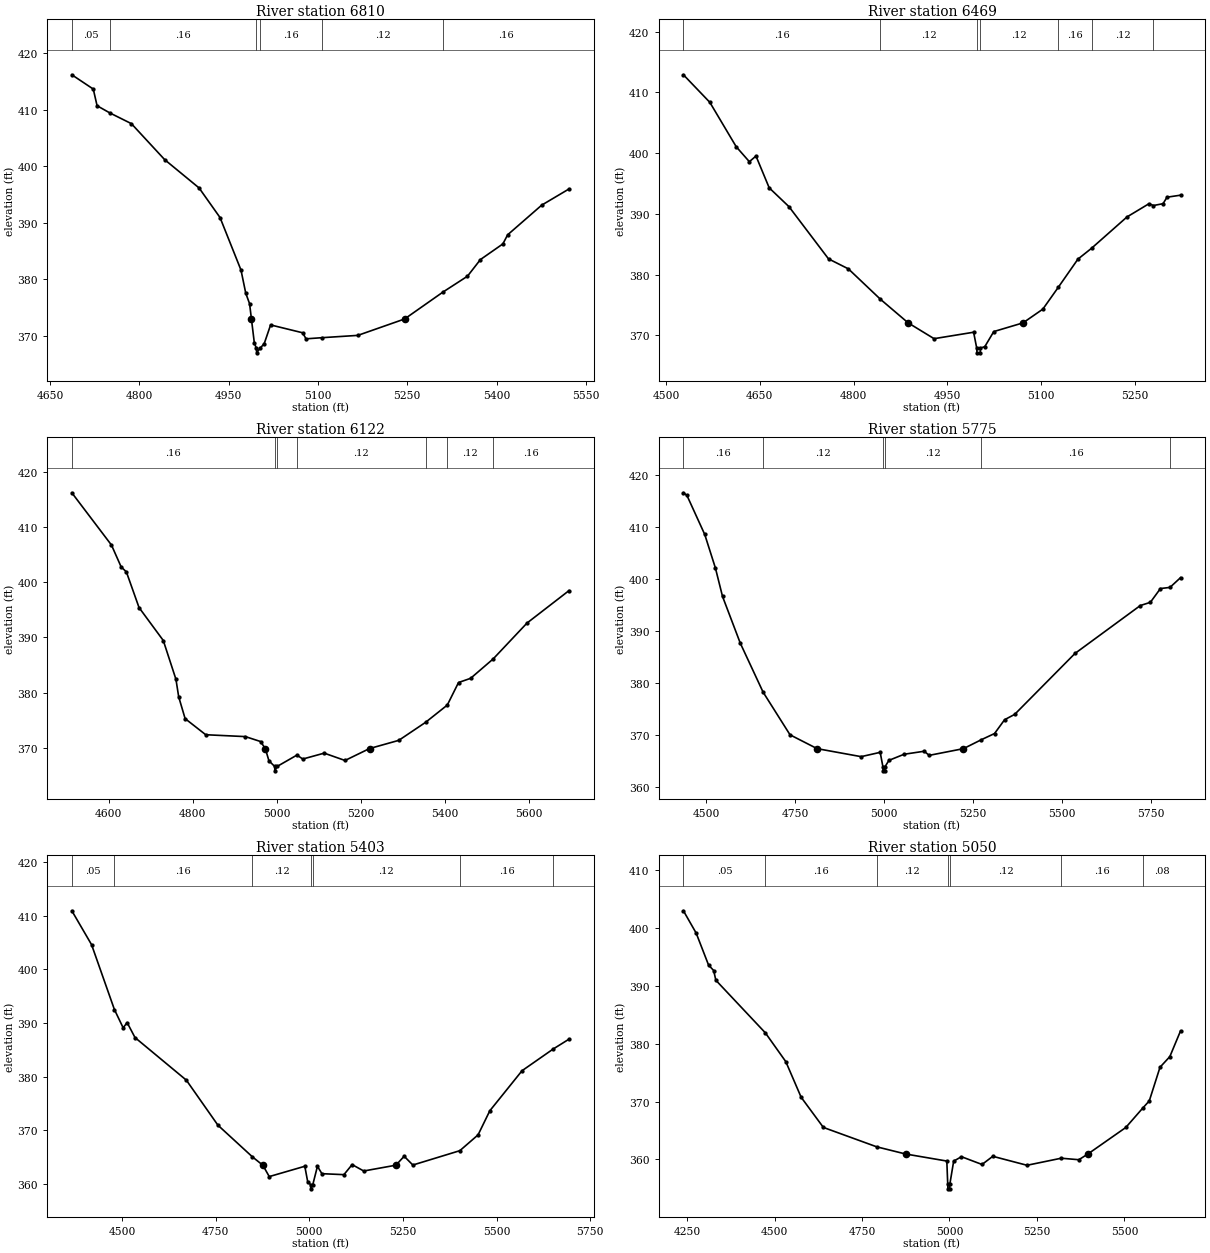
Type RM Length L Ch R = 1,6810,341,341,341
BEGIN DESCRIPTION:
UNT 032 IN DRY CR WATERSHED 11.0
END DESCRIPTION:
XS GIS Cut Line= 3
      2894274.97      6985125.04      2894075.00      6985375.00
      2893624.99      6985625.00
#Sta/Elev= 30
  4686.8  416.22  4722.8  413.69  4729.2  410.74  4750.6  409.47  4786.8  407.57
  4842.8  401.19  4900.5  396.19  4935.7  390.95  4970.9  381.65  4978.9  377.55
  4985.3  375.71  4988.4  373.00  4993.3  368.75  4996.7  367.81  4997.2  367.01
  5002.7  367.81  5009.8  368.61  5020.6  371.95  5074.4  370.56  5080.1  369.49
  5106.7  369.69  5167.1  370.10  5245.6  373.00  5310.4  377.79  5351.2  380.57
  5373.0  383.52  5410.7  386.29  5418.7  387.90  5475.9  393.15  5521.7  396.01
#Mann=6,-1,0
  4686.8    0.05       0  4750.6    0.16       0  4996.7    0.07       0
  5002.7    0.16       0  5106.7    0.12       0  5310.4    0.16       0
Bank Sta=4988.4,5245.6
Exp/Cntr=0.3,0.1

Type RM Length L Ch R = 1,6469,347,347,347
BEGIN DESCRIPTION:
UNT 032 IN DRY CR WATERSHED 10.0
END DESCRIPTION:
XS GIS Cut Line= 3
      2894225.04      6985124.99      2893775.00      6985275.00
      2893525.03      6985474.98
#Sta/Elev= 30
  4528.0  412.88  4570.2  408.35  4612.4  401.04  4633.4  398.58  4644.0  399.51
  4665.1  394.28  4696.7  391.18  4759.9  382.59  4791.6  380.95  4842.8  375.95
  4887.2  372.06  4928.6  369.46  4991.8  370.52  4996.7  367.93  4997.2  367.13
  5002.2  367.13  5002.7  367.93  5009.6  368.14  5024.0  370.63  5070.7  372.06
  5102.4  374.32  5127.0  377.90  5158.5  382.55  5180.3  384.34  5236.9  389.49
  5272.1  391.67  5279.2  391.37  5294.5  391.67  5300.9  392.74  5322.5  393.07
#Mann=7,-1,0
  4528.0    0.16       0  4842.8    0.12       0  4996.7    0.07       0
  5002.7    0.12       0  5127.0    0.16       0  5180.3    0.12       0
  5279.2    0.16       0
Bank Sta=4887.2,5070.7
Exp/Cntr=0.3,0.1

Type RM Length L Ch R = 1,6122,347,347,347
BEGIN DESCRIPTION:
UNT 032 IN DRY CR WATERSHED 9.0
END DESCRIPTION:
XS GIS Cut Line= 3
      2894174.98      6984675.01      2893775.00      6984925.00
      2893325.01      6985474.99
#Sta/Elev= 30
  4512.6  416.24  4606.9  406.75  4629.9  402.79  4642.3  401.89  4672.4  395.42
  4730.1  389.44  4760.2  382.40  4766.7  379.23  4782.0  375.27  4831.0  372.35
  4925.3  372.01  4961.3  371.12  4972.7  369.84  4981.3  367.63  4994.9  366.60
  4995.4  365.80  5000.9  366.60  5048.0  368.66  5061.8  367.94  5112.8  369.01
  5162.3  367.68  5220.5  369.84  5290.1  371.33  5353.7  374.59  5405.5  377.73
  5432.2  381.82  5460.9  382.58  5514.6  386.10  5595.1  392.61  5694.9  398.49
#Mann=7,-1,0
  4512.6    0.16       0  4994.9    0.07       0  5000.9    0.16       0
  5048.0    0.12       0  5353.7    0.16       0  5405.5    0.12       0
  5514.6    0.16       0
Bank Sta=4972.7,5220.5
Exp/Cntr=0.3,0.1

Type RM Length L Ch R = 1,5775,372,372,372
BEGIN DESCRIPTION:
UNT 032 IN DRY CR WATERSHED 8.0
END DESCRIPTION:
XS GIS Cut Line= 3
      2894175.04      6984625.00      2893625.00      6984625.00
      2893024.98      6985225.02
#Sta/Elev= 30
  4435.5  416.57  4445.5  416.05  4495.5  408.55  4525.5  402.10  4545.5  396.63
  4595.5  387.63  4659.7  378.20  4735.5  369.99  4811.7  367.33  4935.5  365.79
  4989.1  366.62  4996.7  363.86  4997.2  363.06  5002.2  363.06  5002.7  363.86
  5013.8  365.08  5056.3  366.25  5112.8  366.83  5127.0  366.04  5223.3  367.33
  5274.0  369.06  5310.8  370.24  5339.1  372.90  5367.4  373.92  5537.1  385.65
  5720.9  394.87  5749.2  395.49  5777.5  398.14  5804.3  398.36  5834.1  400.24
#Mann=6,-1,0
  4435.5    0.16       0  4659.7    0.12       0  4996.7    0.07       0
  5002.7    0.12       0  5274.0    0.16       0  5804.3    0.05       0
Bank Sta=4811.7,5223.3
Exp/Cntr=0.3,0.1

Type RM Length L Ch R = 1,5403,353,353,353
BEGIN DESCRIPTION:
UNT 032 IN DRY CR WATERSHED 7.0
END DESCRIPTION:
XS GIS Cut Line= 3
      2894124.99      6984475.00      2893525.00      6984275.00
      2892924.97      6984625.02
#Sta/Elev= 30
  4366.0  410.88  4418.7  404.57  4479.6  392.51  4503.0  389.10  4513.6  390.08
  4534.6  387.29  4671.7  379.36  4756.0  370.98  4848.2  365.08  4875.8  363.54
  4893.0  361.42  4987.9  363.34  4995.8  360.39  5003.3  359.94  5003.8  359.14
  5009.3  359.94  5021.6  363.33  5033.6  361.96  5092.3  361.78  5114.2  363.65
  5145.2  362.46  5231.1  363.54  5253.1  365.20  5276.3  363.57  5401.7  366.24
  5450.4  369.18  5481.8  373.67  5567.8  381.12  5651.4  385.18  5693.1  386.99
#Mann=7,-1,0
  4366.0    0.05       0  4479.6    0.16       0  4848.2    0.12       0
  5003.3    0.07       0  5009.3    0.12       0  5401.7    0.16       0
  5651.4    0.05       0
Bank Sta=4875.8,5231.1
Exp/Cntr=0.3,0.1

Type RM Length L Ch R = 1,5050,407,407,407
BEGIN DESCRIPTION:
UNT 032 IN DRY CR WATERSHED 6.0
END DESCRIPTION:
XS GIS Cut Line= 3
      2894075.00      6984375.00      2893475.00      6983925.00
      2892875.01      6984224.99
#Sta/Elev= 30
  4239.6  402.96  4276.1  399.10  4311.5  393.58  4326.1  392.64  4332.3  390.96
  4473.8  381.87  4532.3  376.89  4576.1  370.74  4639.6  365.53  4792.0  362.18
  4874.5  360.94  4992.4  359.72  4995.0  355.72  4995.5  354.92  5000.5  354.92
  5001.0  355.72  5012.0  359.71  5034.3  360.47  5093.0  359.13  5123.8  360.54
  5221.6  358.99  5319.3  360.21  5369.7  359.95  5395.6  360.94  5503.9  365.52
  5553.2  368.93  5571.0  370.11  5601.7  375.93  5629.7  377.76  5660.4  382.21
#Mann=7,-1,0
  4239.6    0.05       0  4473.8    0.16       0  4792.0    0.12       0
  4995.0    0.07       0  5001.0    0.12       0  5319.3    0.16       0
  5553.2    0.08       0
Bank Sta=4874.5,5395.6
Exp/Cntr=0.3,0.1

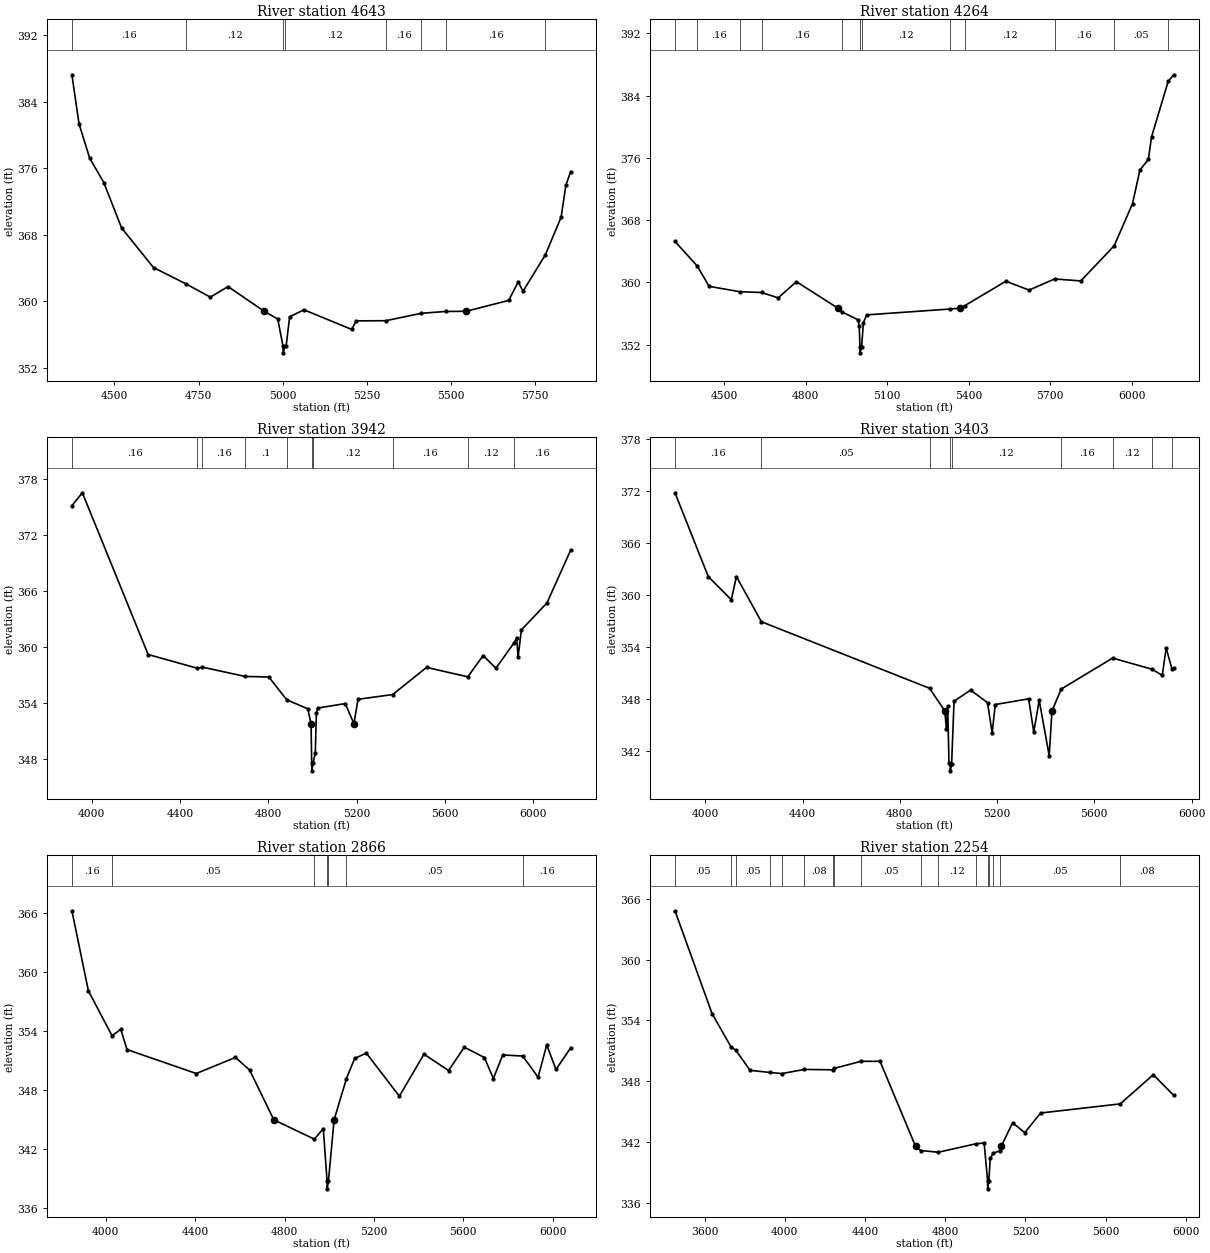
Type RM Length L Ch R = 1,4643,379,379,379
BEGIN DESCRIPTION:
UNT 032 IN DRY CR WATERSHED 5.0
END DESCRIPTION:
XS GIS Cut Line= 3
      2894074.96      6983724.99      2893475.00      6983525.00
      2892875.03      6984124.97
#Sta/Elev= 30
  4373.9  387.21  4394.9  381.34  4426.6  377.20  4468.7  374.25  4521.4  368.81
  4616.3  364.05  4713.2  362.08  4785.0  360.50  4837.7  361.77  4944.9  358.80
  4985.2  357.87  5000.7  354.61  5001.2  353.81  5006.7  354.61  5009.9  354.61
  5020.5  358.14  5062.9  358.98  5204.3  356.63  5218.4  357.65  5305.8  357.67
  5411.4  358.56  5483.7  358.78  5544.3  358.80  5671.0  360.11  5699.3  362.34
  5713.4  361.20  5779.6  365.57  5826.6  370.10  5840.7  373.94  5854.8  375.56
#Mann=8,-1,0
  4373.9    0.16       0  4713.2    0.12       0  5000.7    0.07       0
  5006.7    0.12       0  5305.8    0.16       0  5411.4    0.12       0
  5483.7    0.16       0  5779.6    0.05       0
Bank Sta=4944.9,5544.3
Exp/Cntr=0.3,0.1

Type RM Length L Ch R = 1,4264,322,322,322
BEGIN DESCRIPTION:
UNT 032 IN DRY CR WATERSHED 4.0
END DESCRIPTION:
XS GIS Cut Line= 3
      2893975.04      6983475.02      2893375.00      6983175.00
      2892774.98      6984175.04
#Sta/Elev= 30
  4318.1  365.26  4399.8  362.11  4443.9  359.48  4557.1  358.79  4637.0  358.69
  4698.3  358.00  4765.4  360.08  4918.1  356.68  4933.8  356.19  4991.9  355.18
  4996.7  354.43  4999.6  351.73  5000.1  350.93  5005.6  351.73  5012.3  354.83
  5024.0  355.81  5329.4  356.56  5369.7  356.68  5385.3  356.99  5537.1  360.14
  5622.6  359.00  5716.3  360.43  5813.1  360.18  5936.0  364.70  6003.6  370.12
  6030.8  374.44  6061.9  375.80  6073.5  378.68  6135.0  385.85  6155.2  386.69
#Mann=12,-1,0
  4318.1    0.12       0  4399.8    0.16       0  4557.1    0.12       0
  4637.0    0.16       0  4933.8    0.12       0  4999.6    0.07       0
  5005.6    0.12       0  5329.4    0.16       0  5385.3    0.12       0
  5716.3    0.16       0  5936.0    0.05       0  6135.0    0.16       0
Bank Sta=4918.1,5369.7
Exp/Cntr=0.3,0.1

Type RM Length L Ch R = 1,3942,539,539,539
BEGIN DESCRIPTION:
UNT 032 IN DRY CR WATERSHED 3.0
END DESCRIPTION:
XS GIS Cut Line= 3
      2894333.32      6983173.47      2893275.00      6982875.00
      2892662.27      6983859.26
#Sta/Elev= 30
  3910.7  375.13  3958.0  376.51  4256.0  359.17  4478.8  357.70  4500.9  357.82
  4695.6  356.82  4802.5  356.76  4884.1  354.31  4979.1  353.35  4993.9  351.75
  4996.9  347.50  4997.4  346.70  5002.9  347.50  5013.2  348.63  5018.0  352.86
  5023.9  353.43  5149.0  353.91  5188.1  351.75  5206.8  354.37  5363.7  354.88
  5517.2  357.79  5703.9  356.78  5773.4  359.06  5831.2  357.70  5913.4  360.42
  5925.6  360.99  5931.5  358.87  5946.8  361.81  6062.5  364.70  6169.7  370.35
#Mann=10,-1,0
  3910.7    0.16       0  4478.8    0.12       0  4500.9    0.16       0
  4695.6     0.1       0  4884.1    0.12       0  4996.9    0.07       0
  5002.9    0.12       0  5363.7    0.16       0  5703.9    0.12       0
  5913.4    0.16       0
Bank Sta=4993.9,5188.1
Exp/Cntr=0.3,0.1

Type RM Length L Ch R = 1,3403,537,537,537
BEGIN DESCRIPTION:
UNT 032 IN DRY CR WATERSHED 2.0
END DESCRIPTION:
XS GIS Cut Line= 3
      2894354.97      6982730.74      2893275.00      6982375.00
      2892410.59      6982669.98
#Sta/Elev= 30
  3875.7  371.84  4012.5  362.16  4107.3  359.48  4128.3  362.16  4230.9  356.94
  4922.4  349.25  4985.2  346.63  4991.6  344.50  4996.9  347.19  5002.2  340.65
  5007.1  340.51  5007.6  339.71  5013.1  340.51  5023.1  347.76  5091.1  349.04
  5160.7  347.59  5179.8  344.07  5192.4  347.37  5329.7  348.03  5350.9  344.18
  5373.1  347.87  5414.3  341.46  5425.7  346.63  5463.7  349.16  5675.0  352.74
  5837.1  351.45  5879.2  350.74  5895.1  353.90  5919.2  351.46  5926.1  351.58
#Mann=9,-1,0
  3875.7    0.16       0  4230.9    0.05       0  4922.4    0.12       0
  5007.1    0.07       0  5013.1    0.12       0  5463.7    0.16       0
  5675.0    0.12       0  5837.1    0.16       0  5919.2    0.12       0
Bank Sta=4985.2,5425.7
Exp/Cntr=0.3,0.1

Type RM Length L Ch R = 1,2866,612,612,612
BEGIN DESCRIPTION:
Mapping XS 2e02625e
END DESCRIPTION:
XS GIS Cut Line= 3
      2894351.50      6982480.21      2893427.92      6981879.54
      2892299.71      6981935.08
#Sta/Elev= 30
  3848.7  366.25  3922.3  358.10  4028.3  353.51  4067.2  354.18  4095.0  352.11
  4405.2  349.67  4580.5  351.31  4643.8  350.02  4752.2  344.95  4933.6  342.98
  4973.4  344.06  4990.3  338.72  4990.8  337.92  4996.4  338.72  5021.8  344.95
  5077.0  349.15  5113.5  351.20  5165.9  351.75  5313.8  347.36  5423.9  351.64
  5534.1  349.97  5604.1  352.35  5694.2  351.30  5734.3  349.16  5776.3  351.56
  5865.7  351.45  5934.5  349.29  5973.1  352.58  6014.6  350.08  6080.0  352.28
#Mann=7,-1,0
  3848.7    0.16       0  4028.3    0.05       0  4933.6    0.12       0
  4990.3    0.07       0  4996.4    0.12       0  5077.0    0.05       0
  5865.7    0.16       0
Bank Sta=4752.2,5021.8
Exp/Cntr=0.3,0.1

Type RM Length L Ch R = 1,2254,91,91,91
BEGIN DESCRIPTION:
Mapping XS e9b5d421
END DESCRIPTION:
XS GIS Cut Line= 6
      2894567.64      6982186.81      2894074.62      6981884.75
      2893585.04      6981416.00      2893324.62      6981322.25
      2893029.48      6981370.86      2892373.27      6981370.86
#Sta/Elev= 30
  3451.9  364.81  3637.0  354.66  3730.9  351.40  3756.2  351.03  3826.5  349.07
  3925.7  348.86  3985.2  348.75  4097.4  349.16  4242.4  349.12  4245.7  349.26
  4379.8  349.96  4475.1  349.96  4651.9  341.58  4677.5  341.16  4765.7  340.99
  4952.1  341.82  4994.4  341.90  5011.6  338.18  5012.1  337.38  5017.8  338.18
  5024.8  340.39  5040.3  340.90  5074.0  341.13  5079.7  341.58  5136.3  343.90
  5197.1  342.92  5275.8  344.86  5673.3  345.76  5838.3  348.64  5940.0  346.60
#Mann=17,-1,0
  3451.9    0.05       0  3730.9    0.08       0  3756.2    0.05       0
  3925.7    0.08       0  3985.2    0.05       0  4097.4    0.08       0
  4242.4    0.05       0  4245.7    0.08       0  4379.8    0.05       0
  4677.5    0.08       0  4765.7    0.12       0  4952.1    0.08       0
  5011.6    0.07       0  5017.8    0.08       0  5040.3    0.12       0
  5074.0    0.05       0  5673.3    0.08       0
Bank Sta=4651.9,5079.7
Exp/Cntr=0.3,0.1

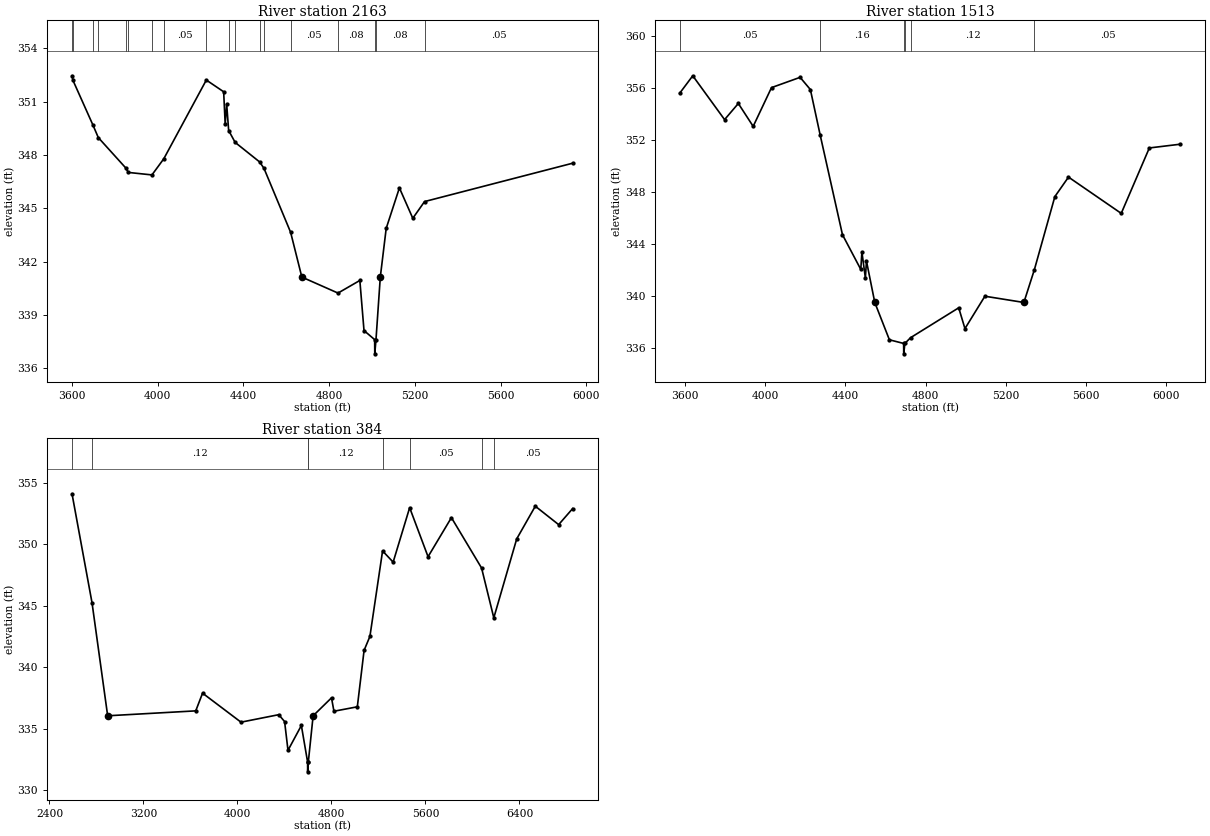
Type RM Length L Ch R = 1,2163,650,650,650
BEGIN DESCRIPTION:
Mapping XS accbd97b
END DESCRIPTION:
XS GIS Cut Line= 6
      2894411.42      6982002.79      2893987.81      6981676.41
      2893609.34      6981311.83      2893314.20      6981235.44
      2892873.23      6981304.88      2892349.46      6981287.54
#Sta/Elev= 30
  3600.5  352.46  3605.0  352.20  3698.0  349.69  3723.2  348.98  3850.6  347.28
  3863.4  347.02  3973.4  346.88  4028.7  347.79  4227.0  352.22  4307.9  351.56
  4315.1  349.72  4322.0  350.86  4331.2  349.38  4361.5  348.71  4475.7  347.61
  4496.0  347.25  4620.3  343.65  4672.6  341.13  4841.3  340.23  4943.2  340.94
  4962.6  338.12  5012.3  337.61  5012.8  336.81  5018.5  337.61  5038.6  341.13
  5066.1  343.87  5127.7  346.15  5190.2  344.44  5245.0  345.38  5936.1  347.54
#Mann=18,-1,0
  3600.5    0.05       0  3605.0    0.08       0  3698.0    0.05       0
  3723.2    0.16       0  3850.6    0.08       0  3863.4    0.16       0
  3973.4    0.08       0  4028.7    0.05       0  4227.0    0.08       0
  4331.2    0.05       0  4361.5    0.08       0  4475.7    0.05       0
  4496.0    0.08       0  4620.3    0.05       0  4841.3    0.08       0
  5012.3    0.07       0  5018.5    0.08       0  5245.0    0.05       0
Bank Sta=4672.6,5038.6
Exp/Cntr=0.3,0.1

Type RM Length L Ch R = 1,1513,1129,1129,1129
BEGIN DESCRIPTION:
Mapping XS 8188f217
END DESCRIPTION:
XS GIS Cut Line= 3
      2894783.97      6981294.11      2893471.49      6980679.54
      2892514.74      6981100.72
#Sta/Elev= 30
  3574.7  355.61  3639.8  356.95  3798.3  353.58  3866.8  354.82  3940.8  353.06
  4032.1  356.04  4174.6  356.83  4225.8  355.89  4274.8  352.38  4385.7  344.73
  4477.0  342.06  4482.5  343.40  4499.8  341.41  4505.3  342.70  4546.7  339.52
  4619.5  336.65  4690.4  336.37  4690.9  335.57  4696.6  336.37  4724.8  336.81
  4964.9  339.11  4995.9  337.51  5095.3  340.00  5289.5  339.52  5342.0  342.05
  5443.9  347.66  5511.8  349.16  5774.6  346.37  5914.6  351.40  6069.3  351.69
#Mann=6,-1,0
  3574.7    0.05       0  4274.8    0.16       0  4690.4    0.07       0
  4696.6    0.16       0  4724.8    0.12       0  5342.0    0.05       0
Bank Sta=4546.7,5289.5
Exp/Cntr=0.3,0.1

Type RM Length L Ch R = 1,384,0,0,0
BEGIN DESCRIPTION:
UNT 032 IN DRY CR WATERSHED 1.0
END DESCRIPTION:
XS GIS Cut Line= 4
      2894502.76      6980872.26      2893112.12      6979825.37
      2892500.00      6980600.00      2891946.36      6982030.13
#Sta/Elev= 30
  2591.8  354.12  2762.2  345.25  2895.2  336.06  3644.9  336.46  3703.0  337.90
  4030.1  335.54  4351.5  336.15  4401.2  335.59  4430.1  333.25  4543.9  335.27
  4596.9  332.30  4597.4  331.50  4603.1  332.30  4644.0  336.06  4800.4  337.52
  4821.2  336.43  5020.2  336.79  5077.7  341.38  5127.4  342.52  5235.1  349.47
  5325.1  348.56  5465.6  352.99  5622.2  349.00  5821.0  352.18  6077.8  348.08
  6181.8  344.03  6376.8  350.45  6535.0  353.11  6733.8  351.61  6853.3  352.92
#Mann=8,-1,0
  2591.8    0.16       0  2762.2    0.12       0  4596.9    0.07       0
  4603.1    0.12       0  5235.1    0.16       0  5465.6    0.05       0
  6077.8    0.08       0  6181.8    0.05       0
Bank Sta=2895.2,4644
Exp/Cntr=0.3,0.1

Chan Stop Cuts=-1