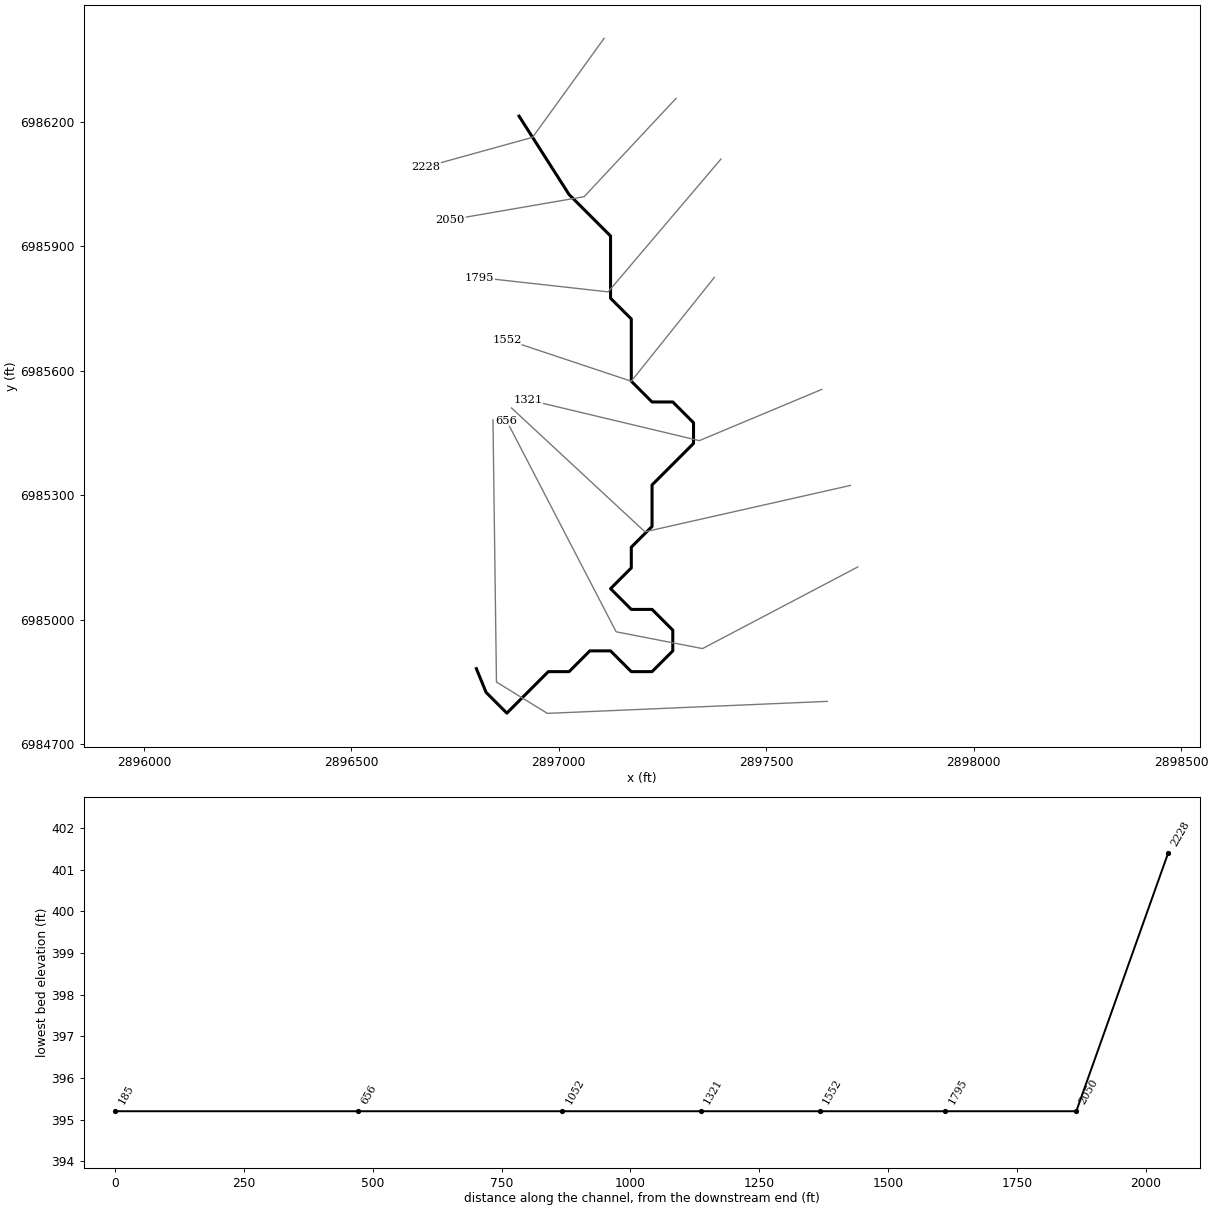
--- UNT 033 IN DRY CR WATERSHED.prj (project) ---

Proj Title=UNT 033 IN DRY CR WATERSHED Base Level Engineering
Current Plan=p01
Default Exp/Contr=0.3,0.1
English Units
Geom File=g01
Flow File=f01
Plan File=p01
BEGIN DESCRIPTION:
UNT 033 IN DRY CR WATERSHED
END DESCRIPTION:

--- UNT 033 IN DRY CR WATERSHED.p01 (plan) ---

Plan Title=Multiple Run
Short Identifier=Multiple
Geom File=g01
Flow File=f01
Subcritical Flow
K Sum by GR= 0
Std Step Tol= 0.01
Critical Tol= 0.01
Num of Std Step Trials= 20
Max Error Tol= 0.3
Flow Tol Ratio= 0.001
Split Flow NTrial= 30
Split Flow Tol= 0.02
Split Flow Ratio= 0.02
Log Output Level= 0
Friction Slope Method= 1
Unsteady Friction Slope Method= 2
Unsteady Bridges Friction Slope Method= 1
Parabolic Critical Depth
Global Vel Dist=  1 , 1 , 1
Global Log Level= 0
CheckData=True
Encroach Param= -1, 0, 0, 0
BEGIN DESCRIPTION:
Multiple Run
END DESCRIPTION:

--- UNT 033 IN DRY CR WATERSHED.f01 (steady flow) ---

Flow Title=Multiple
Number of Profiles=7
Profile Names=10-year,25-year,50-year,1pct_min,100-year,1pct_plu,500-year
River Rch & RM= UNT 033 IN DRY C,Reach-1,2228
      98     116     129      72     143     286     176
Boundary for River Rch & Prof#=UNT 033 IN DRY C,Reach-1,1
Up Type=0
Dn Type=3
Dn Slope=0.005
Boundary for River Rch & Prof#=UNT 033 IN DRY C,Reach-1,2
Up Type=0
Dn Type=3
Dn Slope=0.005
Boundary for River Rch & Prof#=UNT 033 IN DRY C,Reach-1,3
Up Type=0
Dn Type=3
Dn Slope=0.005
Boundary for River Rch & Prof#=UNT 033 IN DRY C,Reach-1,4
Up Type=0
Dn Type=3
Dn Slope=0.005
Boundary for River Rch & Prof#=UNT 033 IN DRY C,Reach-1,5
Up Type=0
Dn Type=3
Dn Slope=0.005
Boundary for River Rch & Prof#=UNT 033 IN DRY C,Reach-1,6
Up Type=0
Dn Type=3
Dn Slope=0.005
Boundary for River Rch & Prof#=UNT 033 IN DRY C,Reach-1,7
Up Type=0
Dn Type=3
Dn Slope=0.005

--- UNT 033 IN DRY CR WATERSHED.g01 (geometry) ---

Geom Title=Existing Conditions

River Reach=UNT 033 IN DRY C,Reach-1
Reach XY= 28
      2896904.50      6986213.89      2897025.00      6986025.00
      2897125.00      6985925.00      2897125.00      6985775.00
      2897175.00      6985725.00      2897175.00      6985575.00
      2897225.00      6985525.00      2897275.00      6985525.00
      2897325.00      6985475.00      2897325.00      6985425.00
      2897225.00      6985325.00      2897225.00      6985225.00
      2897175.00      6985175.00      2897175.00      6985125.00
      2897125.00      6985075.00      2897175.00      6985025.00
      2897225.00      6985025.00      2897275.00      6984975.00
      2897275.00      6984925.00      2897225.00      6984875.00
      2897175.00      6984875.00      2897125.00      6984925.00
      2897075.00      6984925.00      2897025.00      6984875.00
      2896975.00      6984875.00      2896875.00      6984775.00
      2896825.00      6984825.00      2896801.54      6984882.29

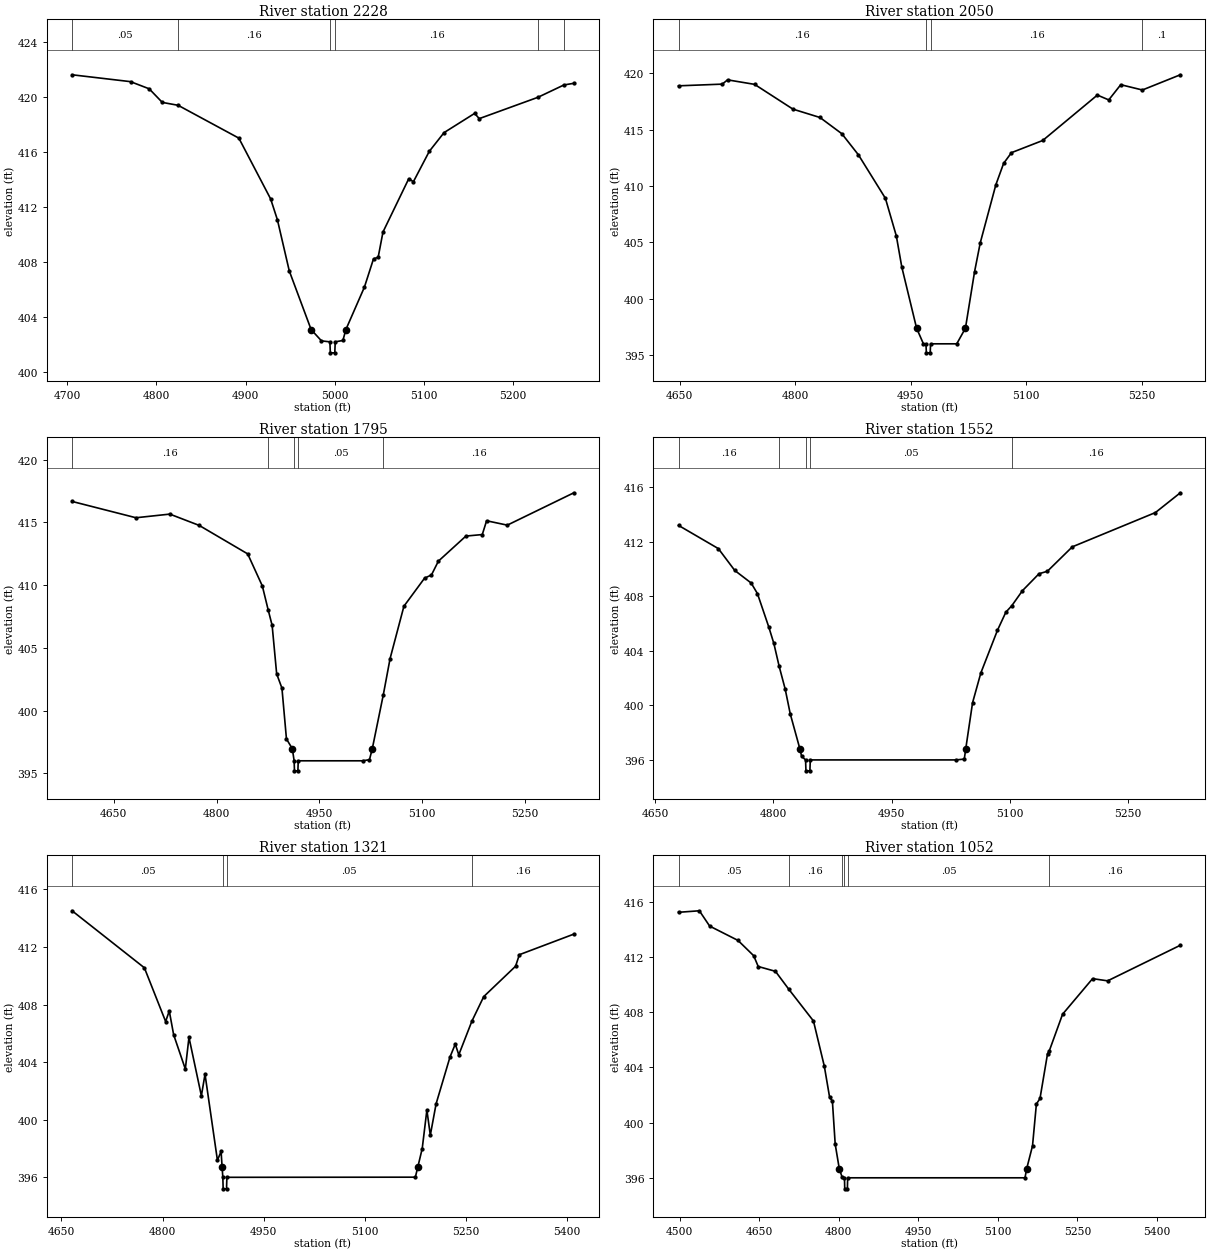
Type RM Length L Ch R = 1,2228,178,178,178
BEGIN DESCRIPTION:
UNT 033 IN DRY CR WATERSHED 3.0
END DESCRIPTION:
XS GIS Cut Line= 3
      2897109.52      6986401.48      2896937.02      6986162.91
      2896678.83      6986091.43
#Sta/Elev= 30
  4705.6  421.62  4771.1  421.12  4792.0  420.60  4806.7  419.61  4824.4  419.40
  4892.5  417.01  4928.1  412.59  4935.7  411.07  4949.0  407.35  4973.5  403.08
  4985.1  402.26  4994.5  402.19  4995.0  401.39  5000.0  401.39  5000.5  402.19
  5009.1  402.29  5012.4  403.08  5033.2  406.17  5043.4  408.23  5048.6  408.34
  5054.0  410.18  5082.9  414.06  5088.1  413.84  5105.9  416.05  5122.4  417.41
  5156.7  418.81  5161.9  418.43  5227.6  419.98  5256.8  420.88  5267.9  421.00
#Mann=6,-1,0
  4705.6    0.05       0  4824.4    0.16       0  4994.5    0.07       0
  5000.5    0.16       0  5227.6     0.1       0  5256.8    0.05       0
Bank Sta=4973.5,5012.4
Exp/Cntr=0.3,0.1

Type RM Length L Ch R = 1,2050,255,255,255
BEGIN DESCRIPTION:
Mapping XS 7f7a011f
END DESCRIPTION:
XS GIS Cut Line= 3
      2897283.07      6986256.94      2897061.34      6986019.79
      2896738.77      6985964.10
#Sta/Elev= 30
  4648.4  418.89  4705.2  419.04  4712.1  419.42  4747.2  419.02  4797.1  416.82
  4832.2  416.08  4860.6  414.64  4882.1  412.77  4917.2  408.91  4931.4  405.57
  4938.5  402.81  4957.7  397.39  4966.6  396.00  4969.9  396.00  4970.4  395.20
  4975.4  395.20  4975.9  396.00  5009.9  396.00  5021.2  397.39  5033.0  402.38
  5040.4  404.95  5060.7  410.11  5070.8  412.01  5081.0  412.96  5121.6  414.04
  5192.6  418.07  5207.4  417.64  5223.0  418.99  5251.1  418.52  5300.4  419.87
#Mann=4,-1,0
  4648.4    0.16       0  4969.9    0.07       0  4975.9    0.16       0
  5251.1     0.1       0
Bank Sta=4957.7,5021.2
Exp/Cntr=0.3,0.1

Type RM Length L Ch R = 1,1795,243,243,243
BEGIN DESCRIPTION:
Mapping XS b318d012
END DESCRIPTION:
XS GIS Cut Line= 3
      2897391.01      6986110.40      2897119.18      6985790.37
      2896808.38      6985824.90
#Sta/Elev= 30
  4589.1  416.67  4682.4  415.37  4731.8  415.66  4774.7  414.76  4845.5  412.49
  4866.9  409.93  4875.3  408.05  4881.2  406.79  4887.8  402.93  4895.5  401.79
  4902.1  397.74  4910.7  396.96  4913.3  396.00  4913.8  395.20  4918.8  395.20
  4919.3  396.00  5013.6  396.00  5023.3  396.09  5027.4  396.96  5043.5  401.26
  5053.4  404.15  5073.6  408.32  5103.8  410.56  5113.8  410.81  5123.9  411.91
  5164.1  413.91  5188.0  414.03  5194.3  415.13  5224.5  414.78  5321.7  417.36
#Mann=5,-1,0
  4589.1    0.16       0  4875.3    0.05       0  4913.3   0.033       0
  4919.3    0.05       0  5043.5    0.16       0
Bank Sta=4910.7,5027.4
Exp/Cntr=0.3,0.1

Type RM Length L Ch R = 1,1552,231,231,231
BEGIN DESCRIPTION:
UNT 033 IN DRY CR WATERSHED 2.0
END DESCRIPTION:
XS GIS Cut Line= 3
      2897375.03      6985825.03      2897175.00      6985575.00
      2896875.03      6985674.99
#Sta/Elev= 30
  4679.8  413.18  4730.3  411.48  4751.1  409.88  4771.9  408.96  4779.9  408.18
  4794.3  405.73  4800.7  404.53  4807.4  402.86  4815.1  401.18  4821.5  399.37
  4833.6  396.83  4835.9  396.27  4840.9  396.00  4841.4  395.20  4846.4  395.20
  4846.9  396.00  5031.6  396.00  5042.2  396.06  5044.1  396.83  5052.7  400.19
  5063.2  402.37  5084.3  405.50  5094.9  406.82  5102.5  407.30  5116.0  408.40
  5137.0  409.64  5147.6  409.82  5179.2  411.61  5284.6  414.12  5316.2  415.57
#Mann=5,-1,0
  4679.8    0.16       0  4807.4    0.05       0  4840.9   0.033       0
  4846.9    0.05       0  5102.5    0.16       0
Bank Sta=4833.6,5044.1
Exp/Cntr=0.3,0.1

Type RM Length L Ch R = 1,1321,269,269,269
BEGIN DESCRIPTION:
Mapping XS 199bf7a8
END DESCRIPTION:
XS GIS Cut Line= 3
      2897633.94      6985555.18      2897338.95      6985431.79
      2896926.36      6985530.12
#Sta/Elev= 30
  4665.9  414.51  4773.1  410.55  4804.6  406.82  4810.0  407.55  4816.5  405.90
  4833.8  403.52  4839.2  405.72  4857.6  401.66  4863.0  403.16  4881.4  397.18
  4886.8  397.80  4888.3  396.74  4889.4  396.00  4889.9  395.20  4894.9  395.20
  4895.4  396.00  5174.8  396.01  5178.6  396.74  5185.0  398.00  5191.9  400.67
  5197.0  398.93  5205.6  401.11  5226.2  404.36  5234.0  405.25  5239.2  404.51
  5258.6  406.84  5276.2  408.55  5323.4  410.66  5329.0  411.46  5409.8  412.89
#Mann=4,-1,0
  4665.9    0.05       0  4889.4   0.033       0  4895.4    0.05       0
  5258.6    0.16       0
Bank Sta=4888.3,5178.6
Exp/Cntr=0.3,0.1

Type RM Length L Ch R = 1,1052,396,396,396
BEGIN DESCRIPTION:
Mapping XS 1af883bf
END DESCRIPTION:
XS GIS Cut Line= 3
      2897703.30      6985323.82      2897207.86      6985212.01
      2896886.39      6985510.39
#Sta/Elev= 30
  4497.6  415.25  4536.9  415.36  4556.3  414.25  4609.8  413.21  4639.4  412.10
  4647.9  411.32  4680.4  410.97  4705.2  409.69  4752.1  407.37  4772.6  404.09
  4782.6  401.83  4787.8  401.57  4793.1  398.44  4800.8  396.66  4806.2  396.04
  4810.6  396.00  4811.1  395.20  4816.1  395.20  4816.6  396.00  5151.1  396.00
  5154.3  396.66  5165.3  398.32  5172.6  401.35  5179.4  401.75  5193.6  404.99
  5196.8  405.19  5222.0  407.86  5278.6  410.44  5307.0  410.28  5444.1  412.86
#Mann=6,-1,0
  4497.6    0.05       0  4705.2    0.16       0  4806.2    0.05       0
  4810.6   0.033       0  4816.6    0.05       0  5196.8    0.16       0
Bank Sta=4800.8,5154.3
Exp/Cntr=0.3,0.1

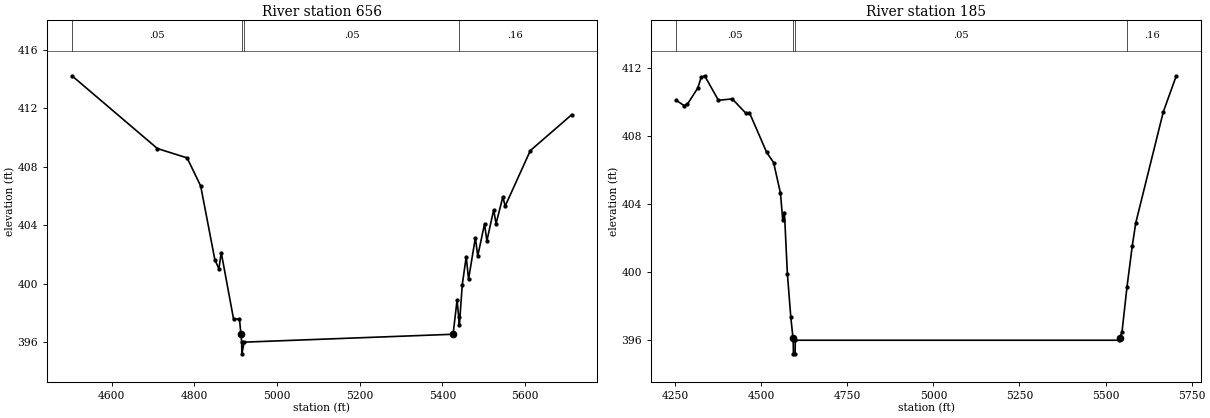
Type RM Length L Ch R = 1,656,471,471,471
BEGIN DESCRIPTION:
Mapping XS 512eb5d9
END DESCRIPTION:
XS GIS Cut Line= 4
      2897720.71      6985127.21      2897346.67      6984930.54
      2897138.46      6984971.03      2896874.34      6985479.98
#Sta/Elev= 30
  4504.4  414.23  4710.9  409.25  4782.7  408.61  4815.5  406.69  4849.8  401.64
  4859.6  401.02  4865.2  402.13  4895.0  397.58  4909.3  397.58  4912.8  396.54
  4914.6  396.00  4915.1  395.20  4920.6  396.00  5425.6  396.54  5435.3  398.88
  5439.1  397.73  5440.9  397.19  5447.8  399.93  5457.4  401.85  5463.0  400.30
  5479.5  403.15  5485.2  401.89  5501.6  404.09  5507.3  402.93  5523.8  405.06
  5529.4  404.10  5545.9  405.94  5551.5  405.31  5612.3  409.11  5712.5  411.57
#Mann=4,-1,0
  4504.4    0.05       0  4914.6   0.033       0  4920.6    0.05       0
  5439.1    0.16       0
Bank Sta=4912.8,5425.6
Exp/Cntr=0.3,0.1

Type RM Length L Ch R = 1,185,0,0,0
BEGIN DESCRIPTION:
UNT 033 IN DRY CR WATERSHED 1.0
END DESCRIPTION:
XS GIS Cut Line= 4
      2897647.42      6984803.30      2896972.66      6984774.39
      2896850.00      6984850.00      2896841.59      6985481.97
#Sta/Elev= 30
  4253.2  410.11  4275.6  409.80  4285.7  409.88  4315.7  410.83  4325.5  411.45
  4335.7  411.55  4375.7  410.11  4415.8  410.19  4455.8  409.34  4465.8  409.38
  4515.9  407.04  4535.9  406.45  4555.9  404.64  4562.4  403.08  4567.4  403.51
  4575.9  399.92  4585.9  397.35  4592.1  396.15  4592.9  396.00  4593.4  395.20
  4598.4  395.20  4598.9  396.00  5537.7  396.00  5540.8  396.15  5547.7  396.48
  5562.1  399.11  5577.7  401.57  5587.7  402.90  5667.7  409.43  5704.7  411.51
#Mann=4,-1,0
  4253.2    0.05       0  4592.9   0.033       0  4598.9    0.05       0
  5562.1    0.16       0
Bank Sta=4592.1,5540.8
Exp/Cntr=0.3,0.1

Chan Stop Cuts=-1