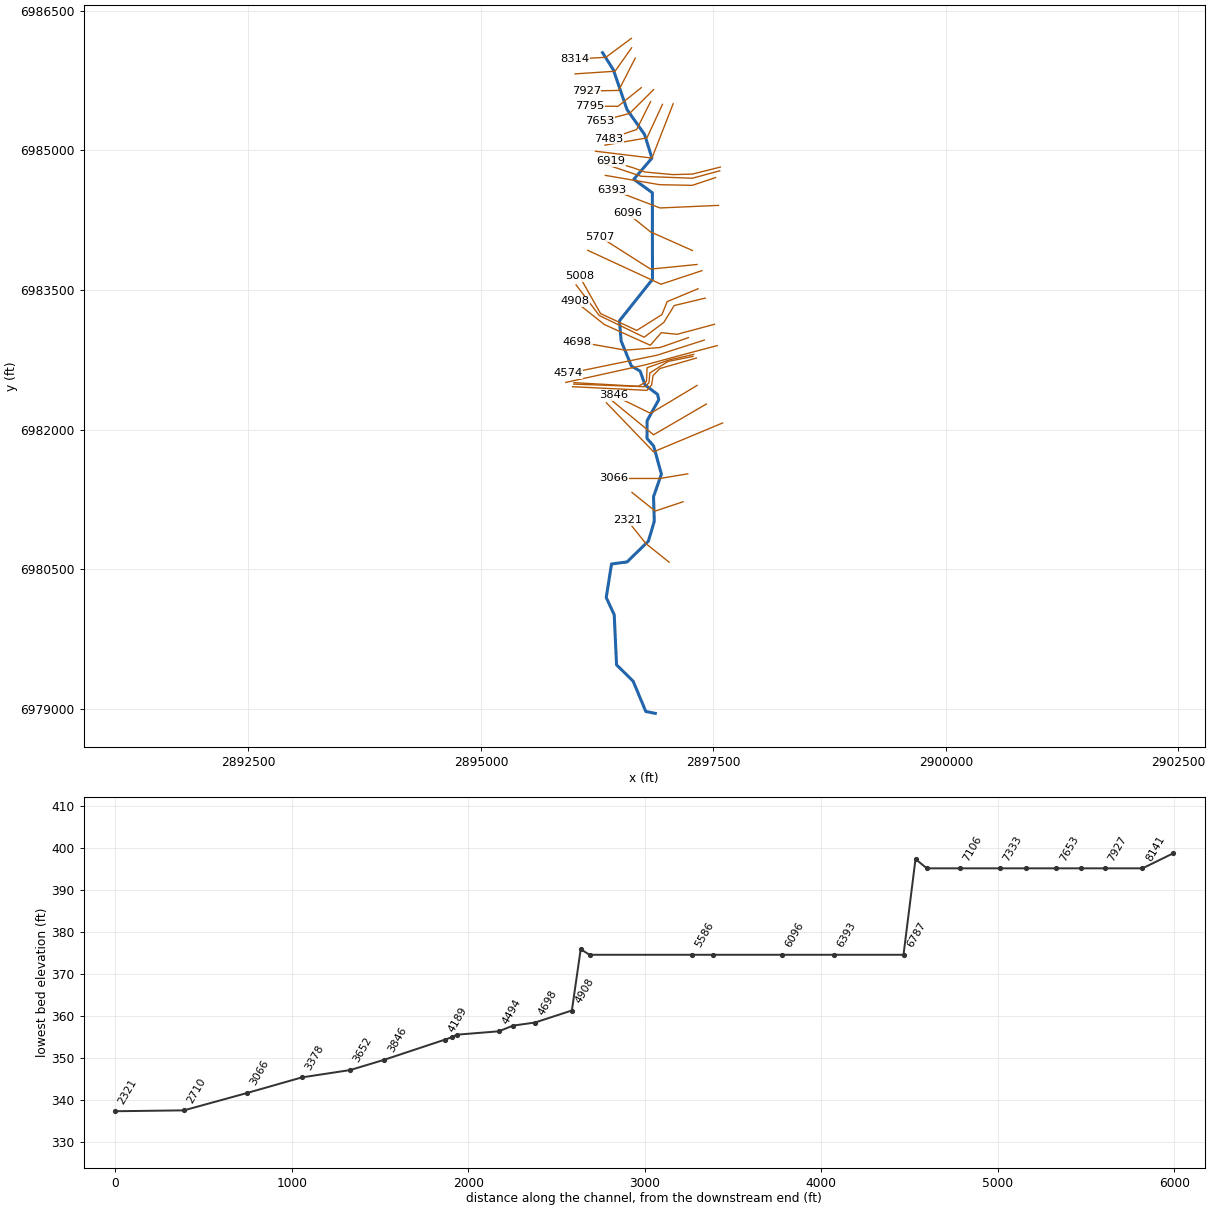
--- UNT 034 IN DRY CR WATERSHED.prj (project) ---

Proj Title=UNT 034 IN DRY CR WATERSHED Base Level Engineering
Current Plan=p01
Default Exp/Contr=0.3,0.1
English Units
Geom File=g01
Flow File=f01
Plan File=p01
BEGIN DESCRIPTION:
UNT 034 IN DRY CR WATERSHED
END DESCRIPTION:

--- UNT 034 IN DRY CR WATERSHED.p01 (plan) ---

Plan Title=Multiple Run
Short Identifier=Multiple
Geom File=g01
Flow File=f01
Subcritical Flow
K Sum by GR= 0
Std Step Tol= 0.01
Critical Tol= 0.01
Num of Std Step Trials= 20
Max Error Tol= 0.3
Flow Tol Ratio= 0.001
Split Flow NTrial= 30
Split Flow Tol= 0.02
Split Flow Ratio= 0.02
Log Output Level= 0
Friction Slope Method= 1
Unsteady Friction Slope Method= 2
Unsteady Bridges Friction Slope Method= 1
Parabolic Critical Depth
Global Vel Dist=  1 , 1 , 1
Global Log Level= 0
CheckData=True
Encroach Param= -1, 0, 0, 0
BEGIN DESCRIPTION:
Multiple Run
END DESCRIPTION:

--- UNT 034 IN DRY CR WATERSHED.f01 (steady flow) ---

Flow Title=Multiple
Number of Profiles=7
Profile Names=10-year,25-year,50-year,1pct_min,100-year,1pct_plu,500-year
River Rch & RM= UNT 034 IN DRY C,Reach-1,8314
      86     101     112      62     124     247     151
River Rch & RM= UNT 034 IN DRY C,Reach-1,6919
     364     475     564     334     666    1329     928
Boundary for River Rch & Prof#=UNT 034 IN DRY C,Reach-1,1
Up Type=0
Dn Type=3
Dn Slope=0.005
Boundary for River Rch & Prof#=UNT 034 IN DRY C,Reach-1,2
Up Type=0
Dn Type=3
Dn Slope=0.005
Boundary for River Rch & Prof#=UNT 034 IN DRY C,Reach-1,3
Up Type=0
Dn Type=3
Dn Slope=0.005
Boundary for River Rch & Prof#=UNT 034 IN DRY C,Reach-1,4
Up Type=0
Dn Type=3
Dn Slope=0.005
Boundary for River Rch & Prof#=UNT 034 IN DRY C,Reach-1,5
Up Type=0
Dn Type=3
Dn Slope=0.005
Boundary for River Rch & Prof#=UNT 034 IN DRY C,Reach-1,6
Up Type=0
Dn Type=3
Dn Slope=0.005
Boundary for River Rch & Prof#=UNT 034 IN DRY C,Reach-1,7
Up Type=0
Dn Type=3
Dn Slope=0.005

--- UNT 034 IN DRY CR WATERSHED.g01 (geometry) ---

Geom Title=Existing Conditions

River Reach=UNT 034 IN DRY C,Reach-1
Reach XY= 30
      2896308.38      6986050.95      2896425.00      6985866.14
      2896571.49      6985439.84      2896760.29      6985172.22
      2896839.71      6984918.31      2896644.62      6984690.64
      2896844.21      6984545.45      2896845.44      6983615.65
      2896490.48      6983169.74      2896507.73      6982954.30
      2896619.79      6982681.74      2896712.86      6982629.27
      2896765.48      6982479.58      2896899.85      6982379.06
      2896913.40      6982322.29      2896787.43      6982095.10
      2896786.71      6981905.36      2896857.86      6981824.09
      2896941.55      6981521.59      2896856.84      6981280.19
      2896864.71      6981014.76      2896801.84      6980802.26
      2896572.04      6980578.05      2896405.12      6980555.89
      2896347.94      6980196.17      2896433.86      6980010.36
      2896459.06      6979472.00      2896637.59      6979296.83
      2896773.83      6978970.71      2896875.59      6978950.71

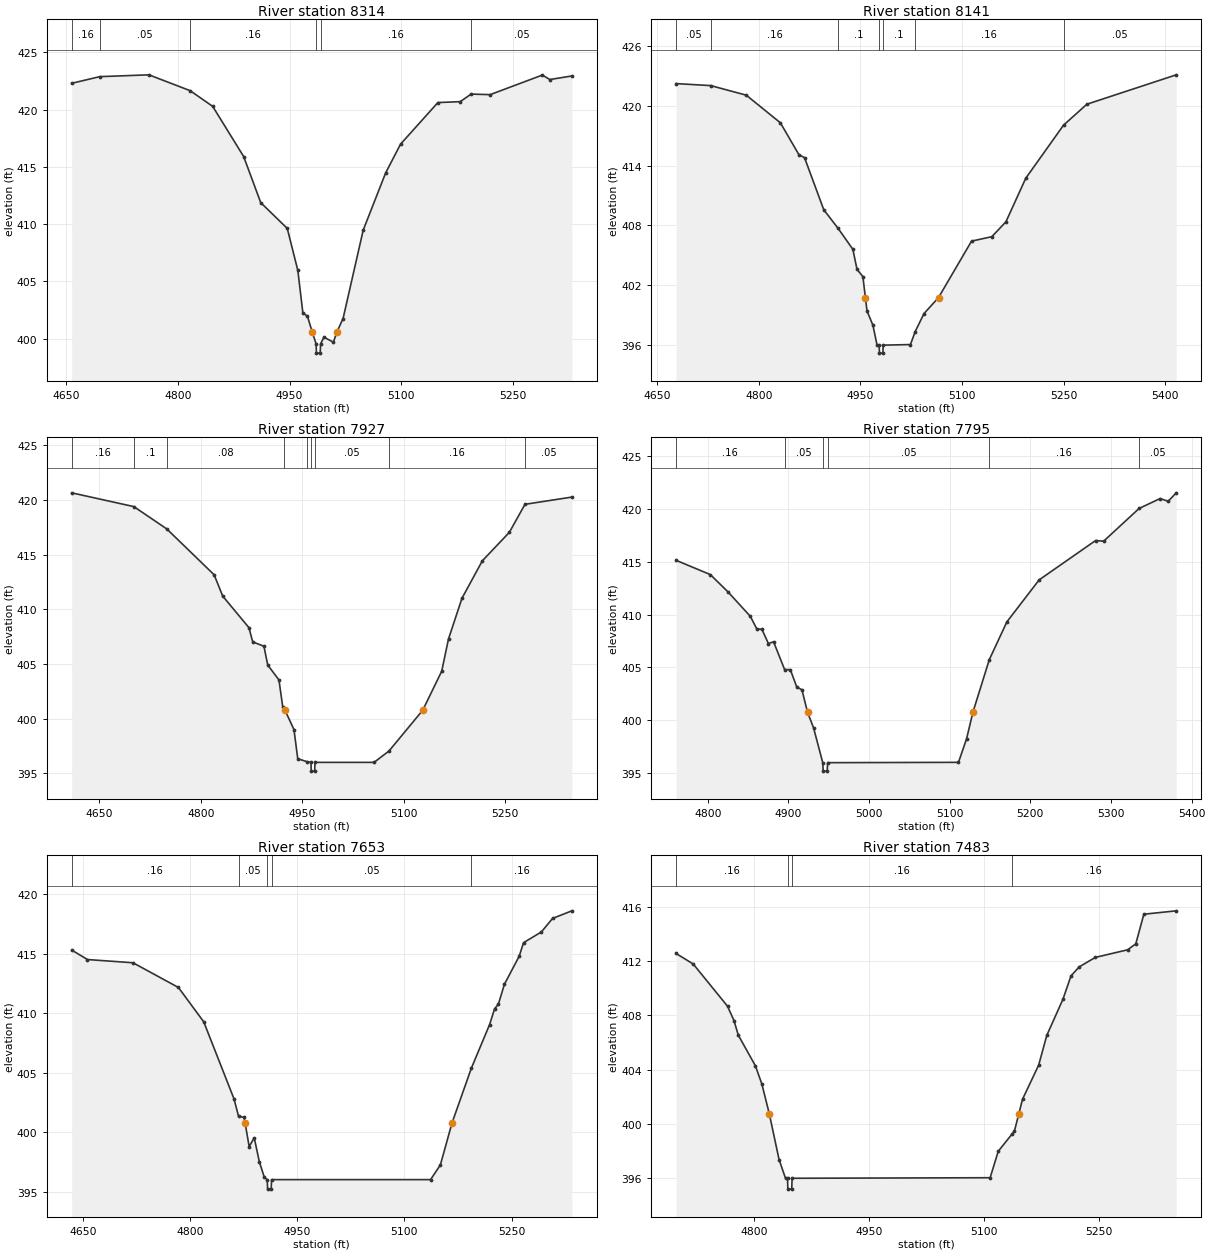
Type RM Length L Ch R = 1,8314,173,173,173
BEGIN DESCRIPTION:
UNT 034 IN DRY CR WATERSHED 18.0
END DESCRIPTION:
XS GIS Cut Line= 3
      2896618.66      6986205.16      2896343.76      6986001.03
      2896015.41      6985983.83
#Sta/Elev= 30
  4657.6  422.29  4695.2  422.87  4761.2  423.03  4816.5  421.65  4846.8  420.28
  4888.4  415.90  4911.3  411.88  4946.9  409.63  4961.1  405.96  4967.8  402.28
  4974.0  401.96  4980.5  400.58  4985.6  399.55  4986.1  398.75  4991.1  398.75
  4991.6  399.55  4996.1  400.15  5008.8  399.70  5013.4  400.58  5021.8  401.77
  5048.8  409.48  5078.9  414.47  5098.9  416.98  5149.0  420.61  5179.0  420.69
  5193.6  421.35  5219.1  421.30  5289.2  423.01  5299.2  422.62  5328.8  422.93
#Mann=6,-1,0
  4657.6    0.16       0  4695.2    0.05       0  4816.5    0.16       0
  4985.6    0.07       0  4991.6    0.16       0  5193.6    0.05       0
Bank Sta=4980.5,5013.4
Exp/Cntr=0.3,0.1

Type RM Length L Ch R = 1,8141,214,214,214
BEGIN DESCRIPTION:
Mapping XS 455d182d
END DESCRIPTION:
XS GIS Cut Line= 3
      2896620.86      6986103.18      2896442.92      6985851.45
      2896013.22      6985823.24
#Sta/Elev= 30
  4677.6  422.23  4728.8  422.03  4781.3  421.07  4831.7  418.30  4859.1  415.10
  4867.4  414.80  4895.8  409.58  4917.1  407.70  4938.8  405.61  4944.9  403.60
  4953.6  402.87  4957.3  400.77  4959.7  399.43  4968.4  398.00  4974.5  396.01
  4977.6  396.00  4978.1  395.20  4983.1  395.20  4983.6  396.00  5023.9  396.06
  5030.7  397.34  5043.9  399.17  5065.3  400.77  5114.1  406.43  5144.1  406.88
  5164.9  408.37  5194.2  412.74  5250.0  418.06  5284.4  420.16  5416.5  423.11
#Mann=7,-1,0
  4677.6    0.05       0  4728.8    0.16       0  4917.1     0.1       0
  4977.6    0.07       0  4983.6     0.1       0  5030.7    0.16       0
  5250.0    0.05       0
Bank Sta=4957.3,5065.3
Exp/Cntr=0.3,0.1

Type RM Length L Ch R = 1,7927,132,132,132
BEGIN DESCRIPTION:
Mapping XS 3c87098a
END DESCRIPTION:
XS GIS Cut Line= 3
      2896659.92      6985992.49      2896481.98      6985645.29
      2896132.58      6985638.78
#Sta/Elev= 30
  4609.1  420.65  4701.0  419.39  4749.7  417.35  4819.8  413.15  4832.4  411.21
  4871.2  408.32  4876.8  407.02  4893.4  406.62  4899.0  404.90  4915.6  403.54
  4921.2  401.07  4923.5  400.86  4924.6  400.76  4937.8  399.00  4943.4  396.33
  4957.4  396.06  4962.9  396.00  4963.4  395.20  4968.4  395.20  4968.9  396.00
  5056.2  396.00  5078.3  397.04  5128.2  400.77  5156.2  404.33  5166.3  407.29
  5186.3  411.02  5216.3  414.43  5256.3  417.04  5279.4  419.60  5348.7  420.26
#Mann=9,-1,0
  4609.1    0.16       0  4701.0     0.1       0  4749.7    0.08       0
  4923.5     0.1       0  4957.4    0.05       0  4962.9   0.033       0
  4968.9    0.05       0  5078.3    0.16       0  5279.4    0.05       0
Bank Sta=4924.6,5128.2
Exp/Cntr=0.3,0.1

Type RM Length L Ch R = 1,7795,142,142,142
BEGIN DESCRIPTION:
UNT 034 IN DRY CR WATERSHED 17.0
END DESCRIPTION:
XS GIS Cut Line= 3
      2896725.02      6985675.02      2896475.00      6985475.00
      2896174.99      6985475.00
#Sta/Elev= 30
  4760.7  415.13  4803.2  413.78  4824.8  412.17  4852.8  409.83  4860.8  408.65
  4867.2  408.60  4875.2  407.26  4881.6  407.43  4895.3  404.80  4902.4  404.79
  4910.4  403.15  4916.8  402.89  4923.7  400.77  4931.2  399.29  4942.6  396.00
  4943.1  395.20  4948.1  395.20  4948.6  396.00  5110.9  396.03  5120.9  398.25
  5128.8  400.77  5149.1  405.74  5170.9  409.31  5210.9  413.28  5280.9  417.00
  5290.9  416.94  5334.8  420.03  5360.9  420.97  5370.9  420.71  5380.9  421.51
#Mann=6,-1,0
  4760.7    0.16       0  4895.3    0.05       0  4942.6   0.033       0
  4948.6    0.05       0  5149.1    0.16       0  5334.8    0.05       0
Bank Sta=4923.7,5128.8
Exp/Cntr=0.3,0.1

Type RM Length L Ch R = 1,7653,170,170,170
BEGIN DESCRIPTION:
Mapping XS 4e091951
END DESCRIPTION:
XS GIS Cut Line= 3
      2896857.38      6985653.93      2896599.17      6985397.89
      2896273.63      6985313.25
#Sta/Elev= 30
  4634.4  415.32  4656.5  414.52  4720.2  414.25  4783.8  412.17  4819.2  409.28
  4861.6  402.79  4867.9  401.34  4875.8  401.23  4877.1  400.77  4882.8  398.78
  4889.9  399.52  4897.0  397.51  4904.1  396.18  4908.1  396.00  4908.6  395.20
  4913.6  395.20  4914.1  396.00  5136.7  396.00  5150.4  397.24  5166.7  400.77
  5193.7  405.37  5219.3  409.05  5226.3  410.38  5231.5  410.75  5240.0  412.44
  5260.7  414.80  5266.8  415.94  5291.7  416.84  5307.4  417.98  5334.4  418.62
#Mann=5,-1,0
  4634.4    0.16       0  4867.9    0.05       0  4908.1   0.033       0
  4914.1    0.05       0  5193.7    0.16       0
Bank Sta=4877.1,5166.7
Exp/Cntr=0.3,0.1

Type RM Length L Ch R = 1,7483,150,150,150
BEGIN DESCRIPTION:
UNT 034 IN DRY CR WATERSHED 16.0
END DESCRIPTION:
XS GIS Cut Line= 3
      2896825.01      6985525.02      2896675.00      6985225.00
      2896374.96      6985124.99
#Sta/Elev= 30
  4698.8  412.56  4721.2  411.78  4765.9  408.67  4774.3  407.61  4779.9  406.54
  4802.2  404.28  4810.6  402.94  4820.2  400.77  4833.0  397.38  4841.4  396.00
  4844.0  396.00  4844.5  395.20  4849.5  395.20  4850.0  396.00  5108.0  396.04
  5118.6  397.99  5136.6  399.26  5139.6  399.46  5145.5  400.77  5150.2  401.82
  5171.3  404.34  5181.8  406.52  5202.9  409.19  5213.4  410.91  5224.0  411.57
  5245.1  412.27  5287.2  412.83  5297.8  413.27  5308.3  415.45  5350.5  415.70
#Mann=4,-1,0
  4698.8    0.16       0  4844.0   0.033       0  4850.0    0.16       0
  5136.6    0.16       0
Bank Sta=4820.2,5145.5
Exp/Cntr=0.3,0.1

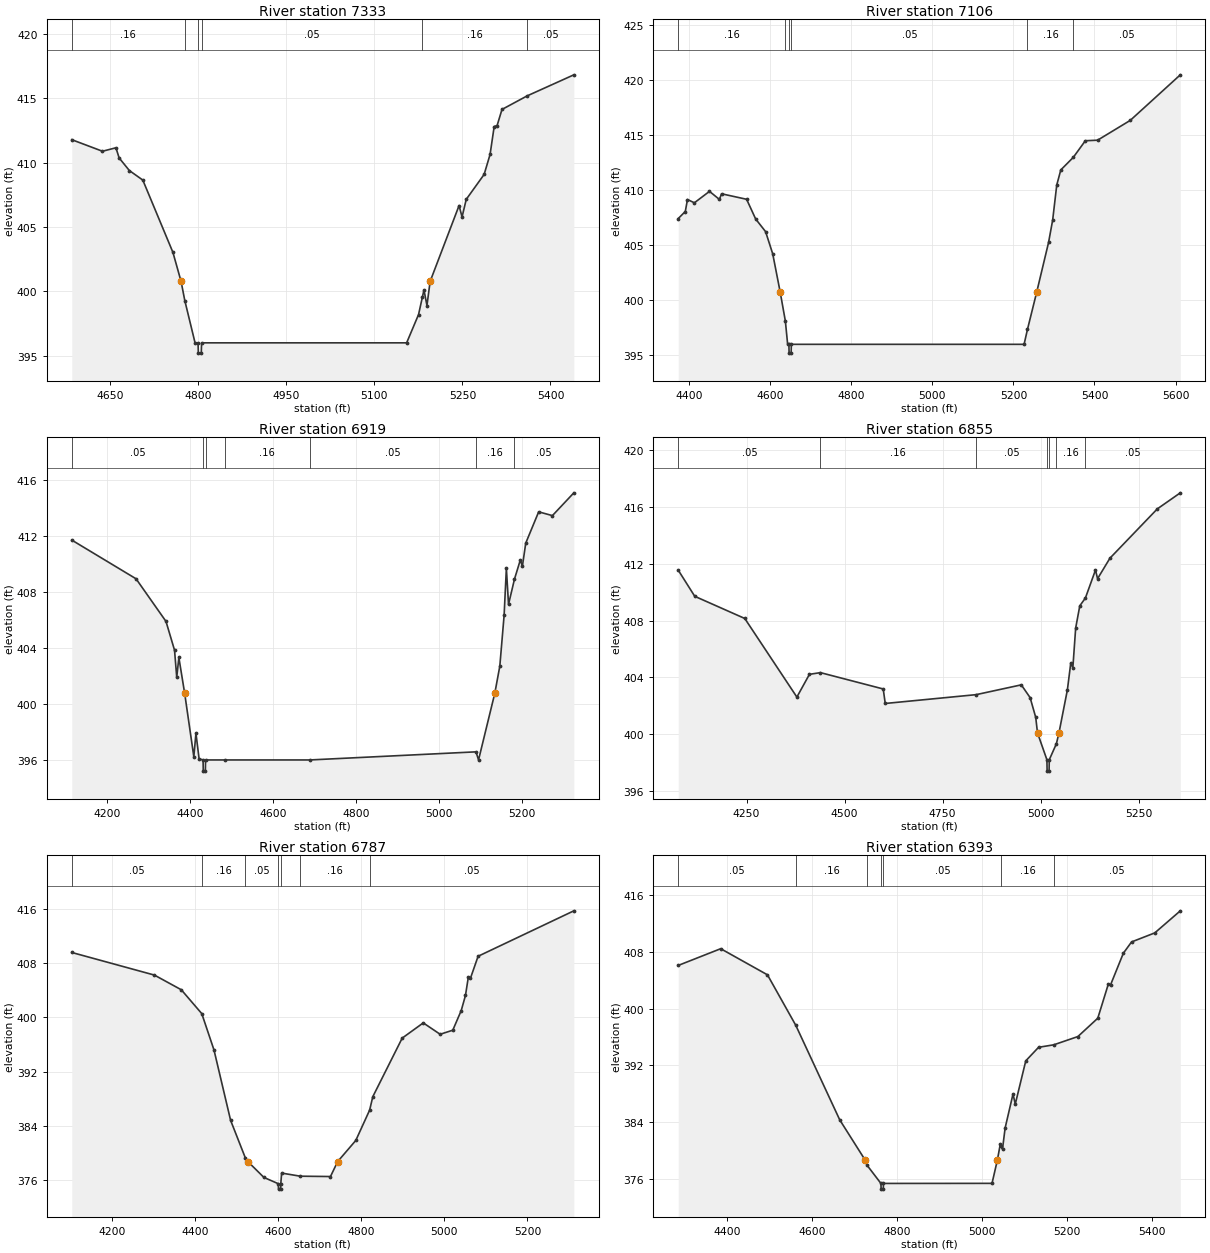
Type RM Length L Ch R = 1,7333,227,227,227
BEGIN DESCRIPTION:
Mapping XS c88d72cd
END DESCRIPTION:
XS GIS Cut Line= 3
      2896952.89      6985495.52      2896785.80      6985135.30
      2896334.40      6985057.18
#Sta/Elev= 30
  4584.6  411.79  4636.9  410.89  4659.8  411.16  4665.3  410.37  4682.7  409.39
  4705.6  408.65  4756.9  403.03  4770.8  400.77  4777.1  399.29  4794.6  396.00
  4799.7  396.00  4800.2  395.20  4805.2  395.20  4805.7  396.00  5155.0  396.00
  5175.3  398.20  5181.7  399.53  5184.5  400.11  5189.6  398.90  5195.0  400.77
  5244.3  406.67  5249.4  405.78  5256.5  407.15  5287.0  409.09  5297.1  410.64
  5304.1  412.81  5309.1  412.89  5317.4  414.14  5360.1  415.19  5439.8  416.83
#Mann=6,-1,0
  4584.6    0.16       0  4777.1    0.05       0  4799.7   0.033       0
  4805.7    0.05       0  5181.7    0.16       0  5360.1    0.05       0
Bank Sta=4770.8,5195
Exp/Cntr=0.3,0.1

Type RM Length L Ch R = 1,7106,187,187,187
BEGIN DESCRIPTION:
UNT 034 IN DRY CR WATERSHED 15.0
END DESCRIPTION:
XS GIS Cut Line= 3
      2897067.93      6985502.09      2896839.71      6984918.31
      2896232.38      6984992.08
#Sta/Elev= 30
  4373.2  407.43  4390.6  408.07  4396.0  409.16  4413.0  408.86  4450.3  409.90
  4474.7  409.17  4480.1  409.68  4541.9  409.18  4564.2  407.39  4588.7  406.24
  4606.3  404.22  4624.6  400.77  4637.5  398.11  4643.0  396.04  4646.2  396.00
  4646.7  395.20  4651.7  395.20  4652.2  396.00  5226.4  396.00  5234.7  397.35
  5257.7  400.77  5286.8  405.26  5296.9  407.29  5307.0  410.48  5317.0  411.85
  5347.8  412.99  5377.5  414.50  5407.7  414.55  5488.3  416.35  5611.8  420.49
#Mann=6,-1,0
  4373.2    0.16       0  4637.5    0.05       0  4646.2   0.033       0
  4652.2    0.05       0  5234.7    0.16       0  5347.8    0.05       0
Bank Sta=4624.6,5257.7
Exp/Cntr=0.3,0.1

Type RM Length L Ch R = 1,6919,64,64,64
BEGIN DESCRIPTION:
Mapping XS ca3c628c
END DESCRIPTION:
XS GIS Cut Line= 6
      2897575.39      6984821.41      2897275.07      6984746.33
      2897063.73      6984740.77      2896763.40      6984768.57
      2896632.70      6984815.85      2896393.57      6984885.36
#Sta/Elev= 30
  4114.8  411.73  4269.8  408.96  4342.0  405.91  4362.6  403.85  4367.9  401.91
  4373.0  403.33  4387.0  400.77  4409.1  396.23  4414.2  397.91  4421.8  396.08
  4431.4  396.00  4431.9  395.20  4436.9  395.20  4437.4  396.00  4483.4  396.00
  4689.0  396.00  5089.5  396.58  5095.6  396.00  5134.8  400.77  5146.9  402.71
  5157.3  406.36  5162.7  409.71  5167.9  407.13  5182.3  408.94  5196.2  410.29
  5201.4  409.87  5209.4  411.51  5240.6  413.75  5273.7  413.48  5325.4  415.11
#Mann=7,-1,0
  4114.8    0.05       0  4431.4   0.035       0  4437.4    0.05       0
  4483.4    0.16       0  4689.0    0.05       0  5089.5    0.16       0
  5182.3    0.05       0
Bank Sta=4387,5134.8
Exp/Cntr=0.3,0.1

Type RM Length L Ch R = 1,6855,68,68,68
BEGIN DESCRIPTION:
Mapping XS 7a57d4b0
END DESCRIPTION:
XS GIS Cut Line= 4
      2897568.73      6984781.51      2897273.60      6984701.66
      2896724.99      6984722.49      2896322.19      6984857.91
#Sta/Elev= 30
  4076.0  411.55  4118.1  409.71  4245.6  408.15  4378.4  402.62  4410.4  404.22
  4438.4  404.34  4598.5  403.19  4603.6  402.17  4835.2  402.79  4950.4  403.48
  4972.9  402.58  4987.2  401.19  4991.7  400.10  5015.7  398.21  5016.2  397.41
  5021.2  397.41  5021.7  398.21  5039.9  399.34  5046.4  400.10  5067.9  403.13
  5076.5  405.02  5081.8  404.68  5089.0  407.48  5099.5  409.04  5113.8  409.59
  5139.5  411.56  5144.8  410.95  5176.3  412.39  5297.1  415.86  5355.7  416.99
#Mann=7,-1,0
  4076.0    0.05       0  4438.4    0.16       0  4835.2    0.05       0
  5015.7   0.035       0  5021.7    0.05       0  5039.9    0.16       0
  5113.8    0.05       0
Bank Sta=4991.7,5046.4
Exp/Cntr=0.3,0.1

Type RM Length L Ch R = 1,6787,394,394,394
BEGIN DESCRIPTION:
Mapping XS ec6f1f2f
END DESCRIPTION:
XS GIS Cut Line= 4
      2897523.58      6984708.60      2897273.60      6984625.27
      2896922.90      6984632.21      2896338.02      6984732.58
#Sta/Elev= 30
  4103.9  409.58  4302.7  406.24  4367.4  404.07  4416.6  400.55  4446.0  395.18
  4486.0  384.78  4521.3  379.26  4527.5  378.70  4566.0  376.36  4600.7  375.43
  4601.2  374.63  4606.2  374.63  4606.7  375.43  4608.7  377.00  4653.5  376.54
  4726.2  376.49  4743.5  378.70  4787.1  381.82  4820.4  386.30  4828.0  388.28
  4898.7  396.93  4949.4  399.18  4990.0  397.50  5020.4  398.10  5040.7  401.00
  5050.9  403.23  5057.9  405.98  5063.0  405.79  5081.3  409.02  5311.6  415.73
#Mann=7,-1,0
  4103.9    0.05       0  4416.6    0.16       0  4521.3    0.05       0
  4600.7    0.03       0  4606.7    0.05       0  4653.5    0.16       0
  4820.4    0.05       0
Bank Sta=4527.5,4743.5
Exp/Cntr=0.3,0.1

Type RM Length L Ch R = 1,6393,297,297,297
BEGIN DESCRIPTION:
Mapping XS 7755f0ff
END DESCRIPTION:
XS GIS Cut Line= 3
      2897554.88      6984409.99      2896926.38      6984382.21
      2896409.71      6984579.86
#Sta/Elev= 30
  4284.4  406.05  4384.4  408.40  4494.5  404.73  4561.2  397.64  4664.7  384.36
  4724.9  378.68  4729.5  377.95  4761.7  375.43  4762.2  374.63  4767.2  374.63
  4767.7  375.43  5023.3  375.44  5035.8  378.68  5042.7  380.92  5045.0  380.63
  5048.0  380.26  5054.2  383.22  5072.7  387.98  5078.1  386.58  5102.8  392.65
  5132.9  394.55  5168.7  394.90  5225.5  396.06  5272.4  398.64  5297.1  403.41
  5302.5  403.33  5332.6  407.77  5351.9  409.35  5406.6  410.62  5466.7  413.72
#Mann=7,-1,0
  4284.4    0.05       0  4561.2    0.16       0  4729.5    0.05       0
  4761.7   0.033       0  4767.7    0.05       0  5045.0    0.16       0
  5168.7    0.05       0
Bank Sta=4724.9,5035.8
Exp/Cntr=0.3,0.1

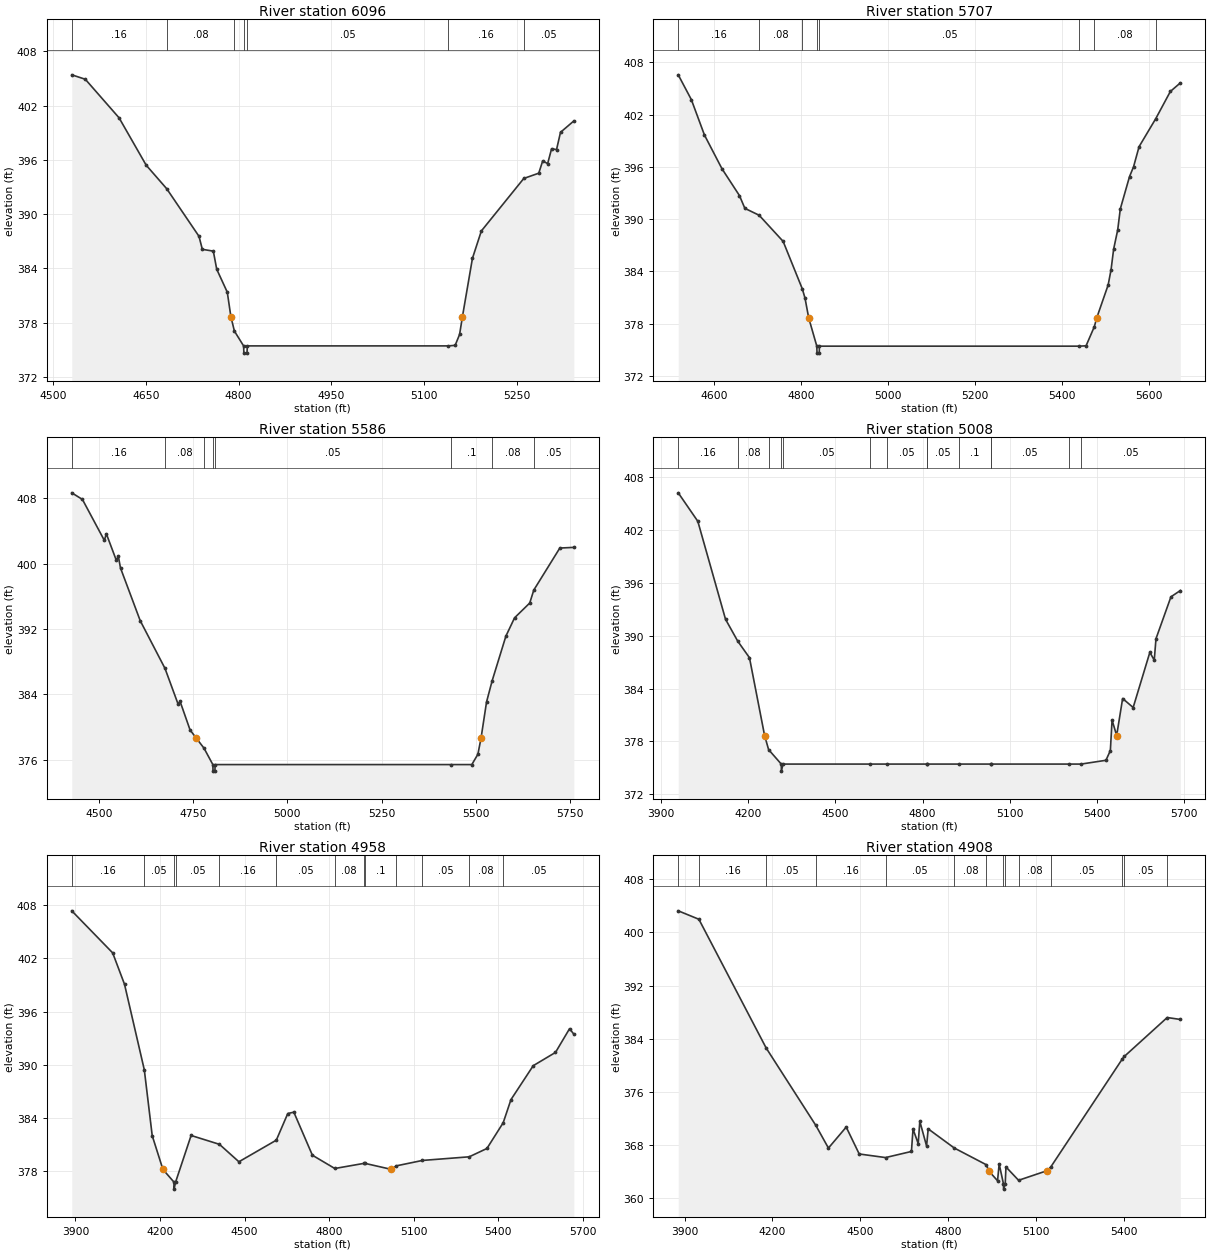
Type RM Length L Ch R = 1,6096,389,389,389
BEGIN DESCRIPTION:
UNT 034 IN DRY CR WATERSHED 12.0
END DESCRIPTION:
XS GIS Cut Line= 3
      2897274.99      6983925.01      2896825.00      6984125.00
      2896574.99      6984325.01
#Sta/Elev= 30
  4530.1  405.41  4552.0  404.92  4606.7  400.65  4650.5  395.42  4683.8  392.81
  4736.0  387.55  4741.4  386.11  4759.2  385.91  4764.7  383.91  4781.8  381.37
  4787.6  378.67  4793.3  377.07  4808.2  375.43  4808.7  374.63  4813.7  374.63
  4814.2  375.43  5139.6  375.43  5150.6  375.49  5157.8  376.70  5162.4  378.67
  5178.6  385.12  5193.0  388.14  5261.7  393.95  5285.9  394.53  5292.3  395.89
  5300.3  395.59  5306.7  397.24  5314.7  397.14  5321.1  399.05  5342.7  400.31
#Mann=7,-1,0
  4530.1    0.16       0  4683.8    0.08       0  4793.3    0.05       0
  4808.2   0.033       0  4814.2    0.05       0  5139.6    0.16       0
  5261.7    0.05       0
Bank Sta=4787.6,5162.4
Exp/Cntr=0.3,0.1

Type RM Length L Ch R = 1,5707,121,121,121
BEGIN DESCRIPTION:
UNT 034 IN DRY CR WATERSHED 11.0
END DESCRIPTION:
XS GIS Cut Line= 3
      2897324.98      6983775.00      2896825.00      6983725.00
      2896274.99      6984075.00
#Sta/Elev= 30
  4518.2  406.56  4548.3  403.72  4578.5  399.65  4618.7  395.79  4658.9  392.71
  4671.4  391.24  4704.2  390.45  4759.4  387.45  4803.5  382.00  4809.6  380.96
  4818.2  378.67  4836.8  375.43  4837.3  374.63  4842.3  374.63  4842.8  375.43
  5440.2  375.43  5455.9  375.47  5474.9  377.66  5480.4  378.67  5506.7  382.45
  5513.4  384.21  5519.3  386.56  5528.7  388.78  5534.6  391.17  5555.8  394.88
  5565.1  396.01  5577.8  398.32  5616.0  401.52  5649.7  404.65  5672.6  405.63
#Mann=8,-1,0
  4518.2    0.16       0  4704.2    0.08       0  4803.5    0.05       0
  4836.8   0.033       0  4842.8    0.05       0  5440.2     0.1       0
  5474.9    0.08       0  5616.0    0.05       0
Bank Sta=4818.2,5480.4
Exp/Cntr=0.3,0.1

Type RM Length L Ch R = 1,5586,578,578,578
BEGIN DESCRIPTION:
Mapping XS da9f1b70
END DESCRIPTION:
XS GIS Cut Line= 3
      2897377.74      6983708.59      2896936.79      6983562.77
      2896149.30      6983927.03
#Sta/Elev= 30
  4428.1  408.65  4456.4  407.84  4514.6  402.83  4519.8  403.65  4546.3  400.40
  4551.6  400.90  4557.4  399.46  4609.7  393.02  4675.5  387.18  4710.2  382.82
  4715.5  383.15  4741.9  379.67  4758.3  378.67  4779.0  377.43  4802.4  375.43
  4802.9  374.63  4807.9  374.63  4808.4  375.43  5433.3  375.43  5489.5  375.43
  5505.6  376.69  5514.0  378.67  5528.6  383.09  5543.6  385.70  5579.9  391.13
  5602.9  393.37  5643.2  395.18  5653.9  396.76  5723.0  401.90  5760.2  401.98
#Mann=8,-1,0
  4428.1    0.16       0  4675.5    0.08       0  4779.0    0.05       0
  4802.4   0.033       0  4808.4    0.05       0  5433.3     0.1       0
  5543.6    0.08       0  5653.9    0.05       0
Bank Sta=4758.3,5514
Exp/Cntr=0.3,0.1

Type RM Length L Ch R = 1,5008,50,50,50
BEGIN DESCRIPTION:
Mapping XS ac6e6e4b
END DESCRIPTION:
XS GIS Cut Line= 6
      2897336.14      6983514.18      2897002.77      6983375.27
      2896947.21      6983236.38      2896676.38      6983066.24
      2896287.49      6983246.80      2896061.81      6983646.07
#Sta/Elev= 30
  3959.8  406.21  4027.1  402.98  4122.4  391.86  4164.3  389.38  4204.7  387.50
  4256.7  378.67  4270.5  377.07  4314.0  375.43  4314.5  374.63  4320.0  375.43
  4620.3  375.43  4677.9  375.43  4813.9  375.43  4814.9  375.43  4924.3  375.43
  5034.6  375.43  5036.1  375.43  5303.4  375.43  5344.7  375.43  5430.2  375.86
  5445.4  376.96  5451.3  380.42  5467.1  378.67  5487.6  382.87  5523.8  381.85
  5581.2  388.11  5596.3  387.22  5602.3  389.66  5653.7  394.41  5685.9  395.12
#Mann=14,-1,0
  3959.8    0.16       0  4164.3    0.08       0  4270.5    0.05       0
  4314.0    0.07       0  4320.0    0.05       0  4620.3    0.16       0
  4677.9    0.05       0  4813.9    0.08       0  4814.9    0.05       0
  4924.3     0.1       0  5034.6    0.08       0  5036.1    0.05       0
  5303.4    0.08       0  5344.7    0.05       0
Bank Sta=4256.7,5467.1
Exp/Cntr=0.3,0.1

Type RM Length L Ch R = 1,4958,50,50,50
BEGIN DESCRIPTION:
Mapping XS 9371a18d
END DESCRIPTION:
XS GIS Cut Line= 6
      2897412.53      6983413.47      2897079.15      6983333.60
      2896968.04      6983153.05      2896756.24      6982993.32
      2896273.60      6983225.96      2896023.62      6983555.80
#Sta/Elev= 30
  3887.1  407.38  4032.2  402.63  4074.2  399.09  4144.5  389.42  4172.5  381.99
  4210.4  378.18  4249.5  376.75  4250.0  375.95  4255.5  376.75  4310.5  382.01
  4411.0  381.01  4480.1  379.04  4612.8  381.48  4653.5  384.49  4675.0  384.64
  4740.8  379.78  4820.3  378.28  4922.3  378.85  4928.6  378.85  5021.0  378.18
  5038.8  378.58  5131.2  379.19  5297.2  379.60  5360.0  380.54  5417.8  383.45
  5445.3  386.06  5524.3  389.89  5603.3  391.39  5653.2  394.07  5668.4  393.45
#Mann=13,-1,0
  3887.1    0.16       0  4144.5    0.05       0  4249.5    0.07       0
  4255.5    0.05       0  4411.0    0.16       0  4612.8    0.05       0
  4820.3    0.08       0  4922.3    0.05       0  4928.6     0.1       0
  5038.8    0.08       0  5131.2    0.05       0  5297.2    0.08       0
  5417.8    0.05       0
Bank Sta=4210.4,5021
Exp/Cntr=0.3,0.1

Type RM Length L Ch R = 1,4908,210,210,210
BEGIN DESCRIPTION:
Mapping XS ef234763
END DESCRIPTION:
XS GIS Cut Line= 6
      2897513.19      6983132.22      2897110.40      6983024.57
      2896940.27      6983041.93      2896822.21      6982906.52
      2896329.15      6983128.74      2896011.28      6983380.96
#Sta/Elev= 30
  3878.3  403.26  3948.8  401.99  4178.4  382.62  4348.1  370.96  4391.1  367.55
  4451.8  370.71  4496.2  366.66  4586.1  366.12  4674.5  367.04  4679.9  370.41
  4697.6  368.23  4703.1  371.58  4726.2  367.86  4731.7  370.44  4820.7  367.56
  4930.5  365.03  4938.0  364.14  4968.5  362.63  4974.0  365.16  4988.7  362.17
  4989.2  361.37  4994.7  362.17  4997.2  364.71  5040.3  362.70  5137.2  364.14
  5150.0  364.69  5394.9  380.99  5401.2  381.34  5547.8  387.20  5592.5  386.91
#Mann=14,-1,0
  3878.3    0.05       0  3948.8    0.16       0  4178.4    0.05       0
  4348.1    0.16       0  4586.1    0.05       0  4820.7    0.08       0
  4930.5     0.1       0  4988.7    0.07       0  4994.7     0.1       0
  5040.3    0.08       0  5150.0    0.05       0  5394.9    0.08       0
  5401.2    0.05       0  5547.8    0.16       0
Bank Sta=4938,5137.2
Exp/Cntr=0.3,0.1

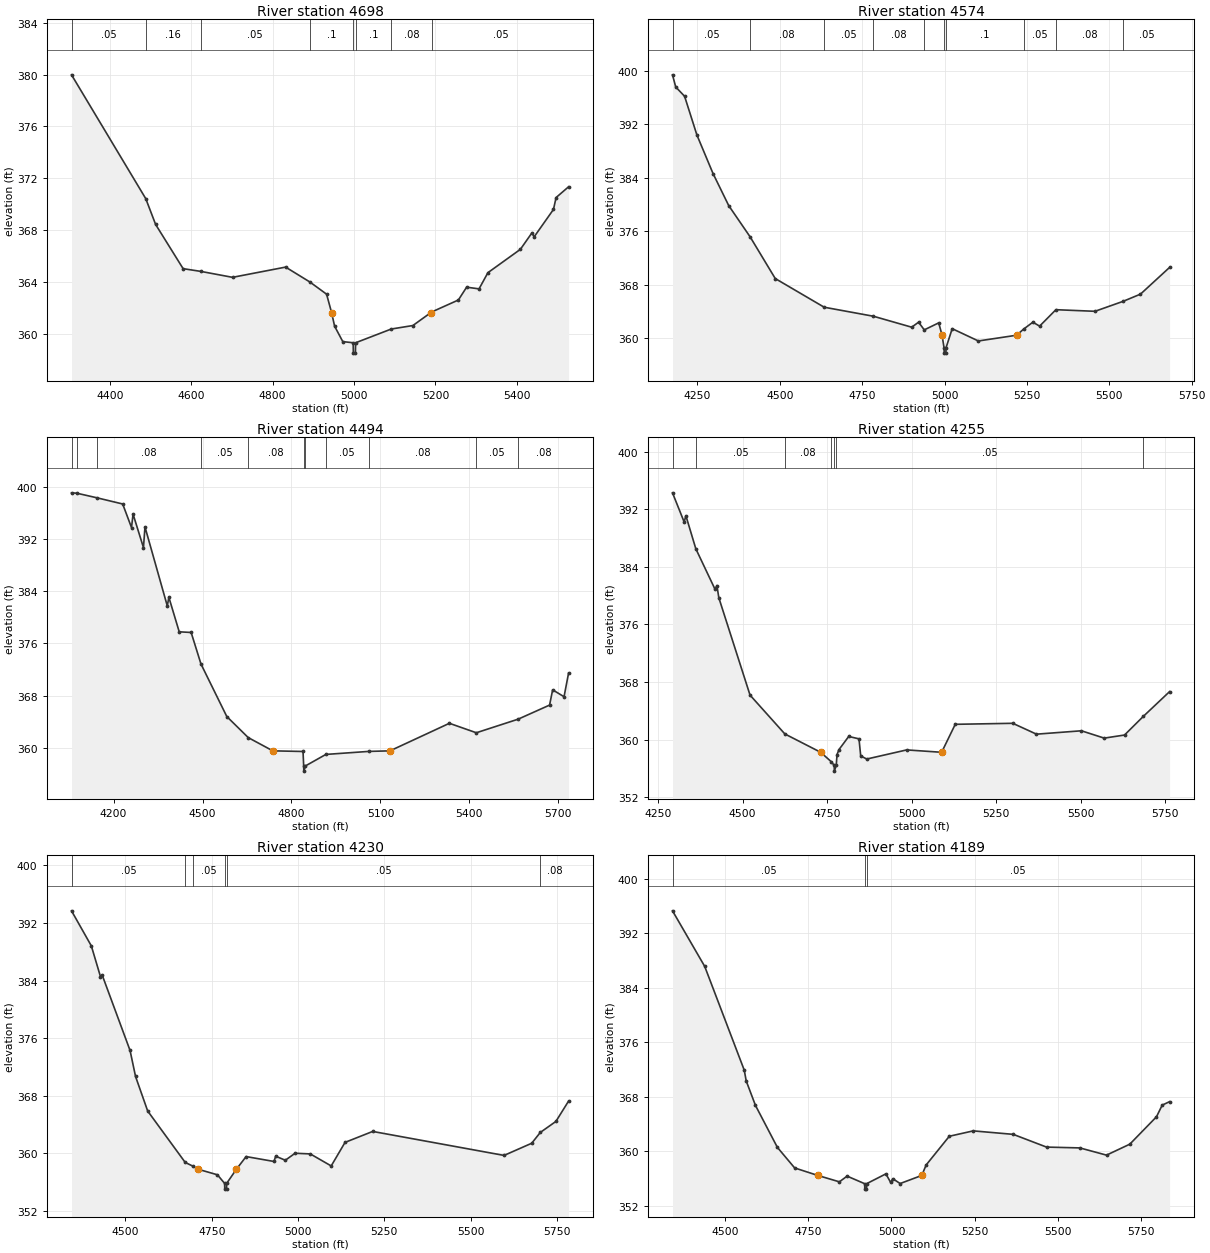
Type RM Length L Ch R = 1,4698,124,124,124
BEGIN DESCRIPTION:
Mapping XS ccc5cb73
END DESCRIPTION:
XS GIS Cut Line= 4
      2897232.37      6982988.79      2896926.35      6982882.44
      2896553.08      6982854.23      2896038.34      6982945.07
#Sta/Elev= 30
  4306.1  379.98  4488.5  370.42  4512.7  368.43  4580.2  365.02  4623.4  364.81
  4701.6  364.35  4832.0  365.14  4891.6  363.99  4932.6  363.05  4944.9  361.63
  4952.3  360.58  4972.4  359.39  4997.9  359.30  4998.4  358.50  5003.4  358.50
  5003.9  359.30  5091.5  360.36  5144.6  360.63  5188.8  361.63  5192.5  361.70
  5256.3  362.60  5276.6  363.59  5307.1  363.46  5328.9  364.71  5408.6  366.51
  5437.2  367.79  5442.3  367.47  5489.9  369.59  5496.4  370.51  5527.1  371.34
#Mann=8,-1,0
  4306.1    0.05       0  4488.5    0.16       0  4623.4    0.05       0
  4891.6     0.1       0  4997.9    0.07       0  5003.9     0.1       0
  5091.5    0.08       0  5192.5    0.05       0
Bank Sta=4944.9,5188.8
Exp/Cntr=0.3,0.1

Type RM Length L Ch R = 1,4574,80,80,80
BEGIN DESCRIPTION:
Mapping XS 497c0487
END DESCRIPTION:
XS GIS Cut Line= 3
      2897402.12      6982962.09      2896891.65      6982798.88
      2895938.44      6982604.77
#Sta/Elev= 30
  4174.3  399.42  4184.1  397.60  4211.0  396.21  4248.4  390.41  4297.3  384.65
  4344.9  379.85  4409.9  375.17  4486.2  368.93  4634.7  364.64  4784.1  363.29
  4900.3  361.65  4921.1  362.40  4938.4  361.25  4982.3  362.30  4992.4  360.45
  4998.5  358.57  4999.0  357.77  5004.0  357.77  5004.5  358.57  5023.2  361.43
  5102.6  359.59  5218.7  360.45  5240.1  361.37  5268.1  362.40  5288.5  361.81
  5338.0  364.27  5456.6  364.03  5541.9  365.52  5594.7  366.60  5683.0  370.60
#Mann=10,-1,0
  4174.3    0.05       0  4409.9    0.08       0  4634.7    0.05       0
  4784.1    0.08       0  4938.4     0.1       0  4998.5    0.07       0
  5004.5     0.1       0  5240.1    0.05       0  5338.0    0.08       0
  5541.9    0.05       0
Bank Sta=4992.4,5218.7
Exp/Cntr=0.3,0.1

Type RM Length L Ch R = 1,4494,239,239,239
BEGIN DESCRIPTION:
Mapping XS 3a356c26
END DESCRIPTION:
XS GIS Cut Line= 4
      2897540.97      6982903.05      2897134.71      6982795.41
      2896777.07      6982698.18      2895912.51      6982507.22
#Sta/Elev= 30
  4058.2  399.07  4076.3  399.01  4144.7  398.30  4230.7  397.36  4260.5  393.75
  4265.7  395.81  4300.8  390.68  4305.9  393.85  4381.2  381.73  4386.4  383.07
  4421.4  377.77  4461.6  377.67  4494.8  372.83  4581.8  364.79  4654.1  361.56
  4737.0  359.53  4838.9  359.43  4841.1  357.22  4841.6  356.42  4847.1  357.22
  4915.9  358.98  5059.7  359.44  5132.3  359.53  5332.5  363.75  5423.3  362.30
  5564.2  364.38  5670.3  366.54  5680.7  368.88  5719.1  367.82  5734.5  371.47
#Mann=11,-1,0
  4058.2    0.08       0  4076.3    0.05       0  4144.7    0.08       0
  4494.8    0.05       0  4654.1    0.08       0  4841.1    0.03       0
  4847.1    0.08       0  4915.9    0.05       0  5059.7    0.08       0
  5423.3    0.05       0  5564.2    0.08       0
Bank Sta=4737,5132.3
Exp/Cntr=0.3,0.1

Type RM Length L Ch R = 1,4255,25,25,25
BEGIN DESCRIPTION:
Mapping XS 43f55116
END DESCRIPTION:
XS GIS Cut Line= 6
      2897288.77      6982808.66      2897028.34      6982750.06
      2896787.46      6982665.43      2896780.95      6982517.86
      2896694.14      6982465.77      2896001.86      6982504.84
#Sta/Elev= 30
  4292.7  394.31  4327.2  390.25  4332.3  391.13  4361.7  386.53  4418.8  380.87
  4424.0  381.42  4429.8  379.71  4522.1  366.18  4625.1  360.78  4731.1  358.23
  4762.6  356.91  4771.1  356.41  4771.6  355.61  4777.1  356.41  4779.5  357.92
  4785.3  358.61  4814.0  360.43  4844.4  360.10  4849.5  357.73  4867.3  357.29
  4985.5  358.56  5088.9  358.23  5129.2  362.12  5299.4  362.26  5369.5  360.75
  5502.4  361.22  5569.9  360.20  5630.0  360.63  5685.3  363.21  5763.3  366.67
#Mann=7,-1,0
  4292.7    0.08       0  4361.7    0.05       0  4625.1    0.08       0
  4762.6    0.05       0  4771.1    0.03       0  4777.1    0.05       0
  5685.3    0.08       0
Bank Sta=4731.1,5088.9
Exp/Cntr=0.3,0.1

Type RM Length L Ch R = 1,4230,41,41,41
BEGIN DESCRIPTION:
Mapping XS ed7d513f
END DESCRIPTION:
XS GIS Cut Line= 6
      2897281.24      6982786.77      2897012.16      6982732.52
      2896816.84      6982608.82      2896808.16      6982504.65
      2896764.76      6982461.25      2895998.30      6982489.36
#Sta/Elev= 30
  4343.7  393.68  4401.1  388.81  4427.6  384.54  4432.7  384.74  4513.3  374.29
  4529.2  370.68  4564.3  365.89  4673.0  358.75  4697.0  358.19  4709.8  357.81
  4766.4  357.03  4787.2  355.84  4787.7  355.04  4792.7  355.04  4793.2  355.84
  4821.5  357.81  4849.5  359.56  4930.2  358.88  4935.2  359.61  4963.1  359.05
  4991.4  360.02  5035.4  359.93  5096.0  358.26  5136.1  361.53  5216.2  363.05
  5596.8  359.72  5676.9  361.41  5701.8  362.91  5747.0  364.44  5783.8  367.27
#Mann=6,-1,0
  4343.7    0.05       0  4673.0    0.08       0  4697.0    0.05       0
  4787.2    0.03       0  4793.2    0.05       0  5701.8    0.08       0
Bank Sta=4709.8,4821.5
Exp/Cntr=0.3,0.1

Type RM Length L Ch R = 1,4189,343,343,343
BEGIN DESCRIPTION:
Mapping XS bb2588b8
END DESCRIPTION:
XS GIS Cut Line= 6
      2897318.10      6982769.40      2896925.35      6982656.56
      2896851.57      6982580.61      2896836.37      6982480.78
      2896786.46      6982422.19      2895985.65      6982461.25
#Sta/Elev= 30
  4341.5  395.29  4438.4  387.13  4557.3  371.90  4563.2  370.32  4591.0  366.73
  4656.9  360.57  4708.9  357.55  4778.5  356.45  4843.4  355.51  4866.6  356.35
  4919.4  355.24  4919.9  354.44  4924.9  354.44  4925.4  355.24  4983.3  356.68
  4997.6  355.42  5004.1  355.97  5026.1  355.26  5091.2  356.45  5104.4  357.99
  5174.0  362.20  5246.0  362.99  5366.2  362.48  5466.4  360.61  5566.6  360.49
  5646.8  359.43  5716.9  361.04  5797.1  365.06  5814.3  366.77  5836.5  367.28
#Mann=3,-1,0
  4341.5    0.05       0  4919.4    0.03       0  4925.4    0.05       0
Bank Sta=4778.5,5091.2
Exp/Cntr=0.3,0.1

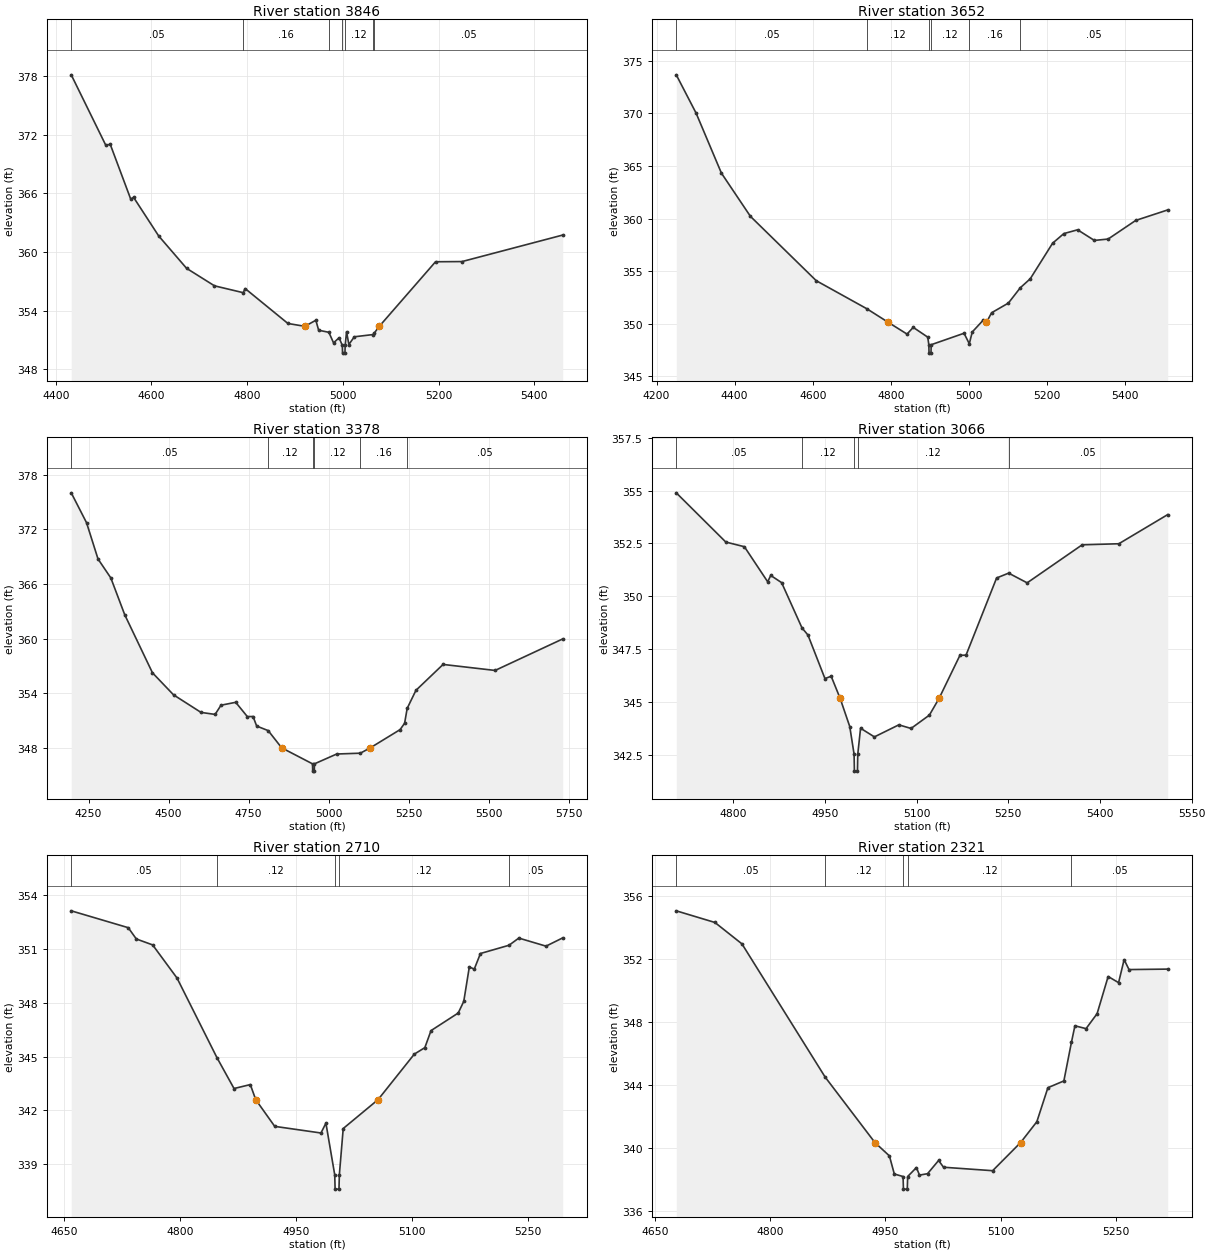
Type RM Length L Ch R = 1,3846,194,194,194
BEGIN DESCRIPTION:
UNT 034 IN DRY CR WATERSHED 7.0
END DESCRIPTION:
XS GIS Cut Line= 3
      2897324.97      6982474.98      2896825.00      6982175.00
      2896426.31      6982370.06
#Sta/Elev= 30
  4432.4  378.11  4504.3  370.94  4514.0  370.99  4556.8  365.39  4562.6  365.59
  4615.1  361.64  4673.4  358.33  4731.7  356.54  4791.7  355.84  4795.8  356.26
  4885.2  352.69  4920.6  352.40  4943.5  353.02  4949.4  352.00  4970.7  351.79
  4980.5  350.71  4992.1  351.23  4998.8  350.46  4999.3  349.66  5004.3  349.66
  5004.8  350.46  5007.7  351.85  5012.5  350.54  5023.9  351.33  5063.5  351.56
  5065.3  351.69  5076.1  352.40  5193.6  359.00  5249.0  359.02  5459.3  361.73
#Mann=7,-1,0
  4432.4    0.05       0  4791.7    0.16       0  4970.7    0.12       0
  4998.8    0.07       0  5004.8    0.12       0  5063.5    0.16       0
  5065.3    0.05       0
Bank Sta=4920.6,5076.1
Exp/Cntr=0.3,0.1

Type RM Length L Ch R = 1,3652,274,274,274
BEGIN DESCRIPTION:
UNT 034 IN DRY CR WATERSHED 6.0
END DESCRIPTION:
XS GIS Cut Line= 3
      2897425.02      6982275.01      2896856.93      6981944.71
      2896391.65      6982326.66
#Sta/Elev= 30
  4250.4  373.67  4301.3  370.02  4366.1  364.32  4440.4  360.21  4609.0  354.09
  4738.7  351.42  4793.5  350.13  4841.7  349.01  4857.5  349.65  4894.7  348.72
  4897.5  348.00  4898.0  347.20  4903.0  347.20  4903.5  348.00  4987.7  349.09
  5001.2  348.09  5008.7  349.21  5037.4  350.36  5045.2  350.13  5058.3  351.04
  5101.3  351.96  5131.9  353.42  5157.3  354.27  5214.7  357.66  5243.4  358.57
  5278.6  358.93  5321.6  357.92  5356.8  358.05  5427.5  359.82  5509.5  360.82
#Mann=6,-1,0
  4250.4    0.05       0  4738.7    0.12       0  4897.5    0.07       0
  4903.5    0.12       0  5001.2    0.16       0  5131.9    0.05       0
Bank Sta=4793.5,5045.2
Exp/Cntr=0.3,0.1

Type RM Length L Ch R = 1,3378,312,312,312
BEGIN DESCRIPTION:
Mapping XS 7e1f9056
END DESCRIPTION:
XS GIS Cut Line= 3
      2897599.16      6982071.46      2896857.21      6981761.48
      2896350.01      6982288.44
#Sta/Elev= 30
  4195.9  376.02  4243.8  372.73  4279.6  368.75  4319.6  366.67  4363.0  362.63
  4449.7  356.25  4515.5  353.83  4601.4  351.90  4645.4  351.68  4663.8  352.69
  4709.8  353.01  4746.1  351.44  4764.0  351.45  4775.3  350.40  4811.3  349.90
  4853.4  348.01  4949.8  346.25  4950.3  345.45  4955.3  345.45  4955.8  346.25
  5025.3  347.33  5099.1  347.42  5130.4  348.01  5223.4  350.01  5237.5  350.71
  5245.5  352.34  5272.8  354.32  5357.7  357.17  5520.2  356.51  5731.4  359.97
#Mann=6,-1,0
  4195.9    0.05       0  4811.3    0.12       0  4949.8    0.07       0
  4955.8    0.12       0  5099.1    0.16       0  5245.5    0.05       0
Bank Sta=4853.4,5130.4
Exp/Cntr=0.3,0.1

Type RM Length L Ch R = 1,3066,356,356,356
BEGIN DESCRIPTION:
UNT 034 IN DRY CR WATERSHED 5.0
END DESCRIPTION:
XS GIS Cut Line= 3
      2897225.03      6981525.00      2896925.00      6981475.00
      2896424.97      6981475.00
#Sta/Elev= 30
  4706.6  354.89  4787.7  352.56  4818.1  352.34  4856.2  350.68  4861.2  350.98
  4879.0  350.64  4912.3  348.50  4922.1  348.16  4949.9  346.10  4960.1  346.21
  4974.8  345.16  4990.5  343.83  4997.6  342.52  4998.1  341.72  5003.1  341.72
  5003.6  342.52  5008.2  343.75  5030.8  343.34  5070.8  343.91  5090.8  343.74
  5120.8  344.37  5136.6  345.16  5170.8  347.20  5180.8  347.21  5230.8  350.86
  5250.5  351.09  5280.8  350.63  5370.8  352.43  5430.8  352.48  5510.8  353.86
#Mann=5,-1,0
  4706.6    0.05       0  4912.3    0.12       0  4997.6    0.07       0
  5003.6    0.12       0  5250.5    0.05       0
Bank Sta=4974.8,5136.6
Exp/Cntr=0.3,0.1

Type RM Length L Ch R = 1,2710,389,389,389
BEGIN DESCRIPTION:
UNT 034 IN DRY CR WATERSHED 4.0
END DESCRIPTION:
XS GIS Cut Line= 3
      2897175.00      6981225.00      2896875.00      6981125.00
      2896624.98      6981325.01
#Sta/Elev= 30
  4658.8  353.13  4732.6  352.19  4743.1  351.56  4764.2  351.23  4795.8  349.38
  4847.4  344.95  4869.6  343.22  4890.7  343.44  4897.7  342.60  4922.3  341.11
  4982.2  340.74  4988.6  341.29  5000.0  338.41  5000.5  337.61  5005.5  337.61
  5006.0  338.41  5011.0  340.99  5056.1  342.60  5103.1  345.14  5116.7  345.50
  5124.7  346.45  5159.9  347.43  5167.1  348.08  5174.3  350.00  5180.7  349.88
  5188.7  350.75  5225.7  351.21  5238.4  351.61  5273.6  351.16  5295.2  351.62
#Mann=5,-1,0
  4658.8    0.05       0  4847.4    0.12       0  5000.0    0.07       0
  5006.0    0.12       0  5225.7    0.05       0
Bank Sta=4897.7,5056.1
Exp/Cntr=0.3,0.1

Type RM Length L Ch R = 1,2321,195,195,195
BEGIN DESCRIPTION:
UNT 034 IN DRY CR WATERSHED 3.0
END DESCRIPTION:
XS GIS Cut Line= 3
      2897024.99      6980575.00      2896775.00      6980775.00
      2896575.00      6981025.00
#Sta/Elev= 30
  4677.4  355.07  4727.8  354.33  4763.0  352.97  4871.3  344.52  4936.2  340.36
  4955.1  339.51  4961.5  338.36  4972.9  338.20  4973.4  337.40  4978.4  337.40
  4978.9  338.20  4990.3  338.77  4994.3  338.29  5004.8  338.38  5019.2  339.22
  5025.6  338.79  5089.6  338.57  5126.1  340.36  5147.2  341.68  5161.6  343.84
  5182.4  344.27  5192.3  346.73  5196.8  347.77  5211.3  347.59  5225.7  348.54
  5240.1  350.90  5253.7  350.51  5260.9  351.97  5267.3  351.34  5317.7  351.37
#Mann=5,-1,0
  4677.4    0.05       0  4871.3    0.12       0  4972.9    0.07       0
  4978.9    0.12       0  5192.3    0.05       0
Bank Sta=4936.2,5126.1
Exp/Cntr=0.3,0.1