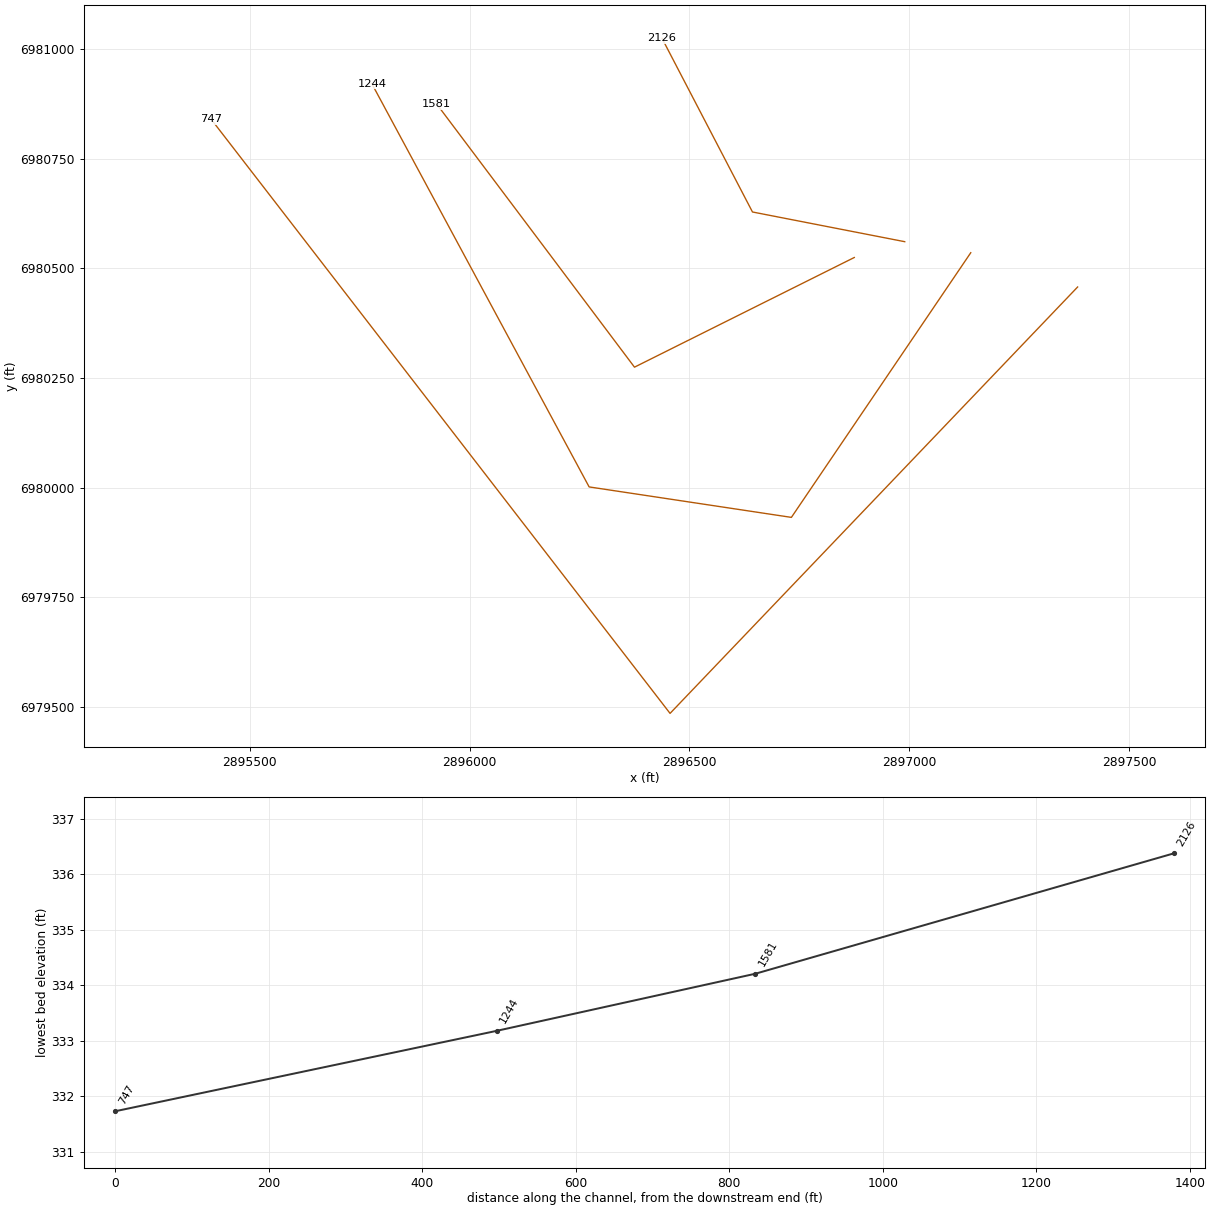
HEC-RAS study UNT 034 IN DRY CR WATERSHED.prj: UNT 034 IN DRY CR WATERSHED Base Level Engineering

--- UNT 034 IN DRY CR WATERSHED.g01 (geometry) --- (continued)

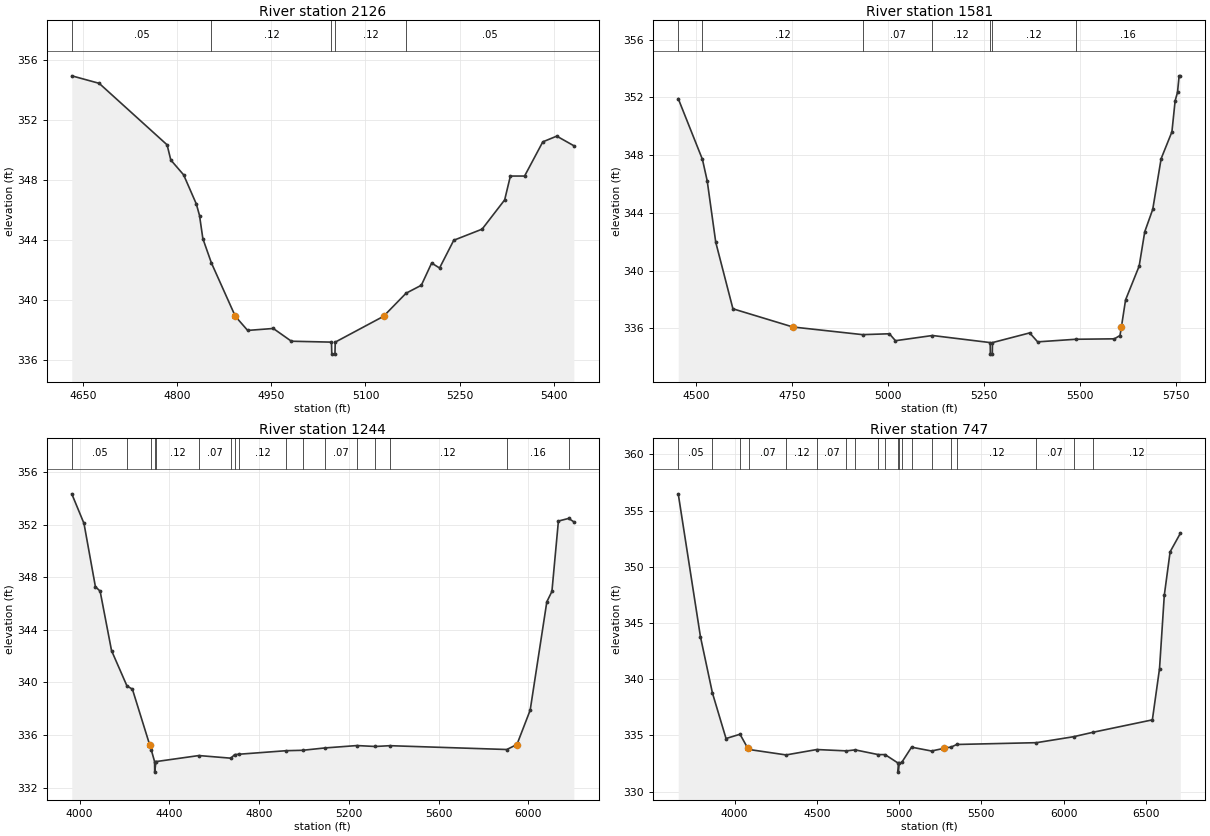
Type RM Length L Ch R = 1,2126,545,545,545
BEGIN DESCRIPTION:
Mapping XS d00f08f1
END DESCRIPTION:
XS GIS Cut Line= 3
      2896989.71      6980561.04      2896643.39      6980628.74
      2896437.65      6981024.59
#Sta/Elev= 30
  4632.6  354.93  4676.2  354.43  4784.3  350.33  4790.2  349.32  4810.6  348.33
  4830.8  346.39  4835.9  345.62  4841.2  344.08  4854.8  342.46  4892.9  338.90
  4912.5  337.96  4953.3  338.09  4982.1  337.24  5045.9  337.18  5046.4  336.38
  5051.4  336.38  5051.9  337.18  5128.7  338.90  5164.6  340.44  5188.9  340.97
  5205.3  342.45  5217.9  342.12  5240.5  343.97  5285.6  344.71  5321.5  346.66
  5330.6  348.25  5353.2  348.25  5382.2  350.53  5404.4  350.91  5431.6  350.27
#Mann=5,-1,0
  4632.6    0.05       0  4854.8    0.12       0  5045.9    0.07       0
  5051.9    0.12       0  5164.6    0.05       0
Bank Sta=4892.9,5128.7
Exp/Cntr=0.3,0.1

Type RM Length L Ch R = 1,1581,337,337,337
BEGIN DESCRIPTION:
UNT 034 IN DRY CR WATERSHED 2.0
END DESCRIPTION:
XS GIS Cut Line= 3
      2896875.01      6980525.00      2896375.00      6980275.00
      2895925.01      6980874.98
#Sta/Elev= 30
  4453.1  351.91  4516.2  347.70  4528.6  346.22  4550.9  341.96  4595.7  337.35
  4752.0  336.09  4933.7  335.56  5003.7  335.62  5019.4  335.14  5115.9  335.50
  5266.4  335.01  5266.9  334.21  5271.9  334.21  5272.4  335.01  5369.4  335.68
  5390.2  335.06  5489.5  335.24  5590.2  335.27  5604.8  335.50  5608.5  336.09
  5619.4  337.97  5654.8  340.31  5669.4  342.69  5690.2  344.24  5712.1  347.75
  5740.2  349.61  5748.6  351.76  5754.8  352.35  5759.0  353.49  5762.1  353.49
#Mann=7,-1,0
  4453.1    0.05       0  4516.2    0.12       0  4933.7    0.07       0
  5115.9    0.12       0  5266.4    0.07       0  5272.4    0.12       0
  5489.5    0.16       0
Bank Sta=4752,5608.5
Exp/Cntr=0.3,0.1

Type RM Length L Ch R = 1,1244,497,497,497
BEGIN DESCRIPTION:
Mapping XS 3f7b23af
END DESCRIPTION:
XS GIS Cut Line= 4
      2897139.91      6980535.85      2896731.93      6979932.56
      2896271.86      6980002.00      2895777.64      6980921.08
#Sta/Elev= 30
  3965.1  354.34  4019.5  352.09  4070.4  347.28  4091.4  346.94  4142.3  342.42
  4211.1  339.73  4235.2  339.49  4311.8  335.28  4318.9  334.90  4334.1  333.98
  4334.6  333.18  4340.1  333.98  4531.3  334.44  4674.0  334.24  4690.6  334.51
  4709.8  334.54  4921.0  334.81  4993.3  334.84  5093.8  335.02  5236.0  335.20
  5317.3  335.13  5382.4  335.19  5903.5  334.90  5948.6  335.28  6007.6  337.89
  6081.8  346.13  6104.5  346.92  6133.4  352.27  6179.2  352.47  6202.2  352.21
#Mann=17,-1,0
  3965.1    0.05       0  4211.1    0.16       0  4318.9    0.12       0
  4334.1    0.07       0  4340.1    0.12       0  4531.3    0.07       0
  4674.0    0.12       0  4690.6    0.07       0  4709.8    0.12       0
  4921.0    0.07       0  4993.3    0.12       0  5093.8    0.07       0
  5236.0    0.12       0  5317.3    0.07       0  5382.4    0.12       0
  5903.5    0.16       0  6179.2    0.05       0
Bank Sta=4311.8,5948.6
Exp/Cntr=0.3,0.1

Type RM Length L Ch R = 1,747,0,0,0
BEGIN DESCRIPTION:
UNT 034 IN DRY CR WATERSHED 1.0
END DESCRIPTION:
XS GIS Cut Line= 3
      2897382.99      6980457.75      2896455.93      6979485.77
      2895412.51      6980839.64
#Sta/Elev= 30
  3656.8  356.49  3791.7  343.79  3864.7  338.77  3947.4  334.72  4032.4  335.10
  4080.2  333.84  4084.4  333.75  4312.5  333.26  4499.3  333.74  4679.6  333.62
  4732.7  333.71  4872.8  333.29  4914.2  333.29  4994.1  332.53  4994.6  331.73
  5000.1  332.53  5015.4  332.59  5075.3  333.95  5196.6  333.61  5269.9  333.84
  5318.0  333.97  5349.9  334.19  5834.7  334.35  6060.2  334.88  6179.7  335.28
  6539.4  336.38  6582.9  340.94  6611.9  347.46  6647.3  351.33  6709.3  352.97
#Mann=20,-1,0
  3656.8    0.05       0  3864.7    0.16       0  4032.4    0.12       0
  4084.4    0.07       0  4312.5    0.12       0  4499.3    0.07       0
  4679.6    0.12       0  4732.7    0.16       0  4872.8    0.07       0
  4914.2    0.12       0  4994.1    0.07       0  5000.1    0.12       0
  5015.4    0.07       0  5075.3    0.16       0  5196.6    0.16       0
  5318.0    0.07       0  5349.9    0.12       0  5834.7    0.07       0
  6060.2    0.12       0  6179.7    0.12       0
Bank Sta=4080.2,5269.9
Exp/Cntr=0.3,0.1

Chan Stop Cuts=-1