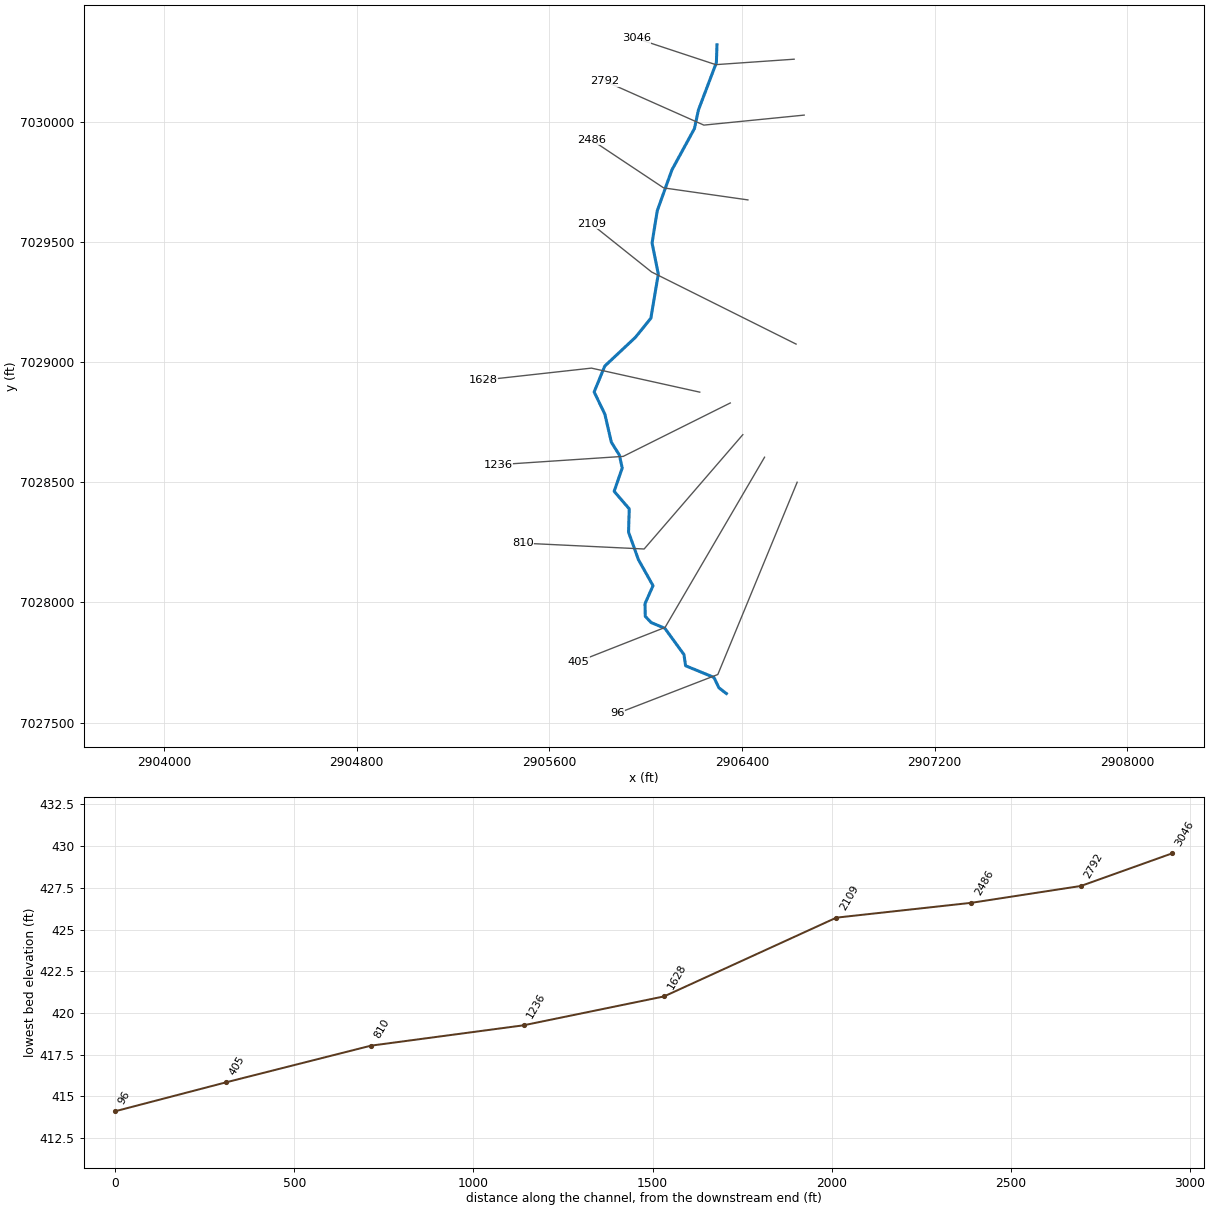
--- UNT 035 IN DRY CR WATERSHED.prj (project) ---

Proj Title=UNT 035 IN DRY CR WATERSHED Base Level Engineering
Current Plan=p01
Default Exp/Contr=0.3,0.1
English Units
Geom File=g01
Flow File=f01
Plan File=p01
BEGIN DESCRIPTION:
UNT 035 IN DRY CR WATERSHED
END DESCRIPTION:

--- UNT 035 IN DRY CR WATERSHED.p01 (plan) ---

Plan Title=Multiple Run
Short Identifier=Multiple
Geom File=g01
Flow File=f01
Subcritical Flow
K Sum by GR= 0
Std Step Tol= 0.01
Critical Tol= 0.01
Num of Std Step Trials= 20
Max Error Tol= 0.3
Flow Tol Ratio= 0.001
Split Flow NTrial= 30
Split Flow Tol= 0.02
Split Flow Ratio= 0.02
Log Output Level= 0
Friction Slope Method= 1
Unsteady Friction Slope Method= 2
Unsteady Bridges Friction Slope Method= 1
Parabolic Critical Depth
Global Vel Dist=  1 , 1 , 1
Global Log Level= 0
CheckData=True
Encroach Param= -1, 0, 0, 0
BEGIN DESCRIPTION:
Multiple Run
END DESCRIPTION:

--- UNT 035 IN DRY CR WATERSHED.f01 (steady flow) ---

Flow Title=Multiple
Number of Profiles=7
Profile Names=10-year,25-year,50-year,1pct_min,100-year,1pct_plu,500-year
River Rch & RM= UNT 035 IN DRY C,Reach-1,3046
     519     696     839     504    1005    2006    1445
River Rch & RM= UNT 035 IN DRY C,Reach-1,1628
     803    1102    1352     824    1644    3280    2435
Boundary for River Rch & Prof#=UNT 035 IN DRY C,Reach-1,1
Up Type=0
Dn Type=3
Dn Slope=0.005
Boundary for River Rch & Prof#=UNT 035 IN DRY C,Reach-1,2
Up Type=0
Dn Type=3
Dn Slope=0.005
Boundary for River Rch & Prof#=UNT 035 IN DRY C,Reach-1,3
Up Type=0
Dn Type=3
Dn Slope=0.005
Boundary for River Rch & Prof#=UNT 035 IN DRY C,Reach-1,4
Up Type=0
Dn Type=3
Dn Slope=0.005
Boundary for River Rch & Prof#=UNT 035 IN DRY C,Reach-1,5
Up Type=0
Dn Type=3
Dn Slope=0.005
Boundary for River Rch & Prof#=UNT 035 IN DRY C,Reach-1,6
Up Type=0
Dn Type=3
Dn Slope=0.005
Boundary for River Rch & Prof#=UNT 035 IN DRY C,Reach-1,7
Up Type=0
Dn Type=3
Dn Slope=0.005

--- UNT 035 IN DRY CR WATERSHED.g01 (geometry) ---

Geom Title=Existing Conditions

River Reach=UNT 035 IN DRY C,Reach-1
Reach XY= 30
      2906296.55      7030320.68      2906294.08      7030246.45
      2906219.51      7030049.08      2906202.93      7029971.81
      2906109.14      7029799.24      2906048.41      7029629.54
      2906026.93      7029495.68      2906052.88      7029366.25
      2906021.79      7029182.28      2905957.80      7029103.12
      2905830.40      7028983.27      2905786.40      7028875.68
      2905830.89      7028783.49      2905857.88      7028666.65
      2905890.98      7028613.43      2905903.04      7028559.44
      2905869.52      7028462.27      2905932.19      7028389.28
      2905929.26      7028292.31      2905970.32      7028177.95
      2906030.91      7028069.64      2905997.57      7027994.56
      2905998.76      7027941.99      2906022.85      7027916.44
      2906080.04      7027892.32      2906159.45      7027782.88
      2906166.16      7027736.46      2906283.82      7027687.99
      2906304.59      7027644.56      2906335.59      7027620.71

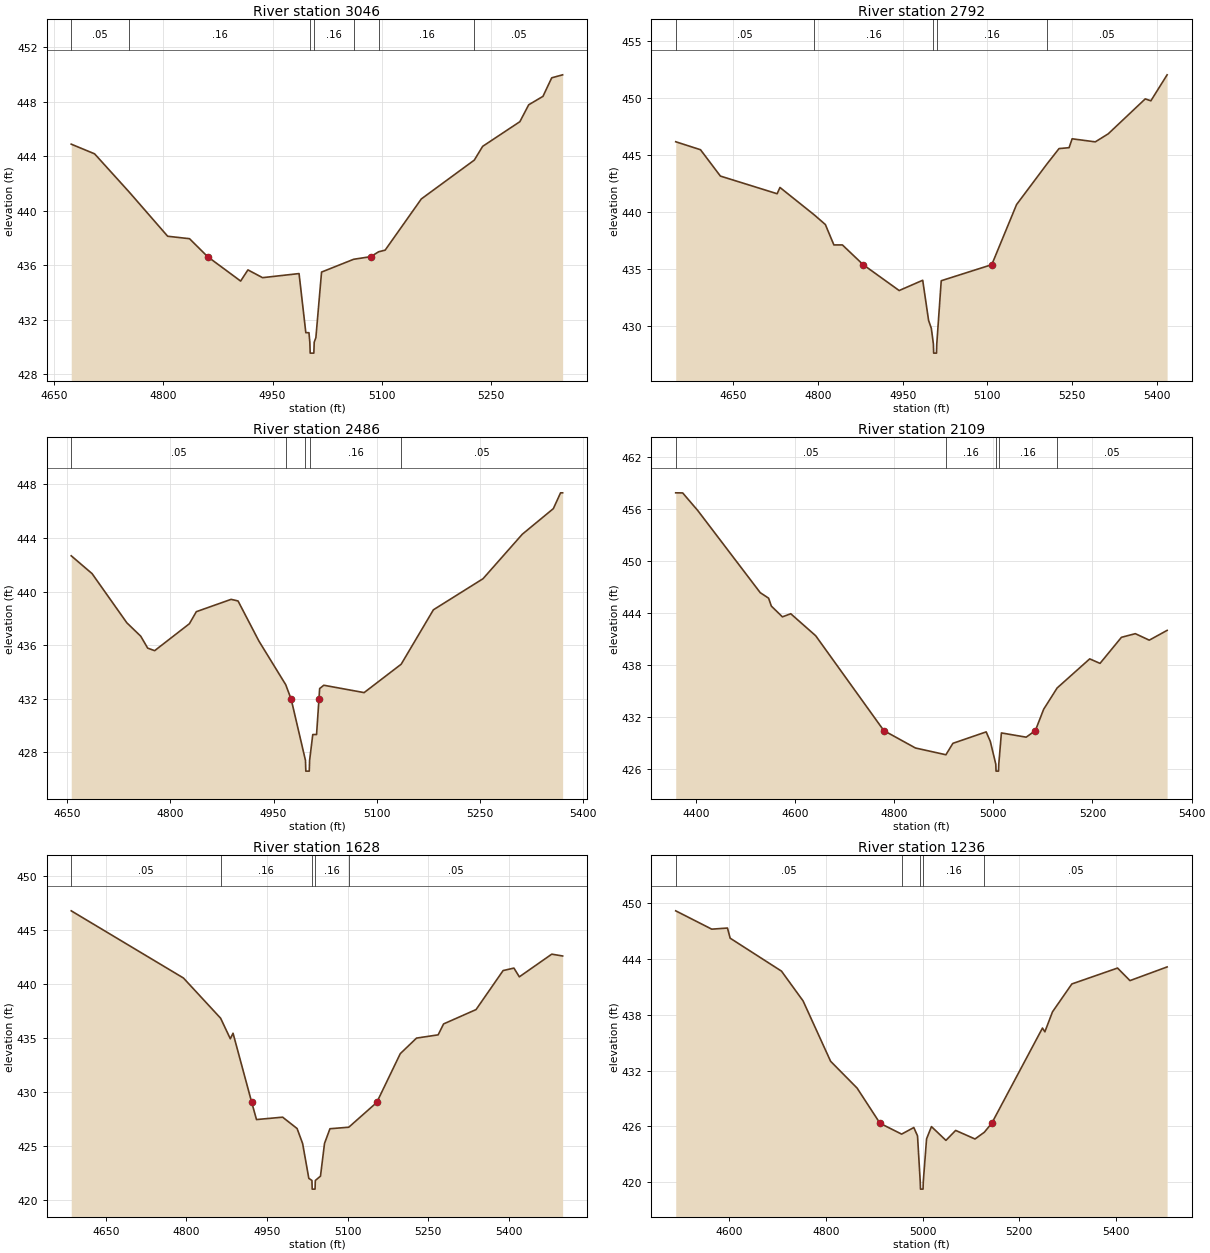
Type RM Length L Ch R = 1,3046,254,254,254
BEGIN DESCRIPTION:
UNT 035 IN DRY CR WATERSHED 5.0
END DESCRIPTION:
XS GIS Cut Line= 3
      2906617.05      7030260.51      2906291.44      7030237.82
      2905960.79      7030347.31
#Sta/Elev= 30
  4673.6  444.90  4705.7  444.19  4753.1  441.39  4806.0  438.14  4836.0  437.96
  4860.9  436.64  4906.2  434.85  4916.2  435.67  4936.3  435.10  4986.4  435.40
  4995.7  431.06  5000.0  431.06  5001.2  430.36  5001.7  429.56  5006.7  429.56
  5007.2  430.36  5009.5  430.70  5017.3  435.51  5061.4  436.45  5084.7  436.64
  5095.7  437.00  5104.6  437.12  5154.3  440.88  5227.0  443.73  5238.5  444.74
  5289.6  446.55  5301.7  447.79  5321.3  448.41  5333.3  449.77  5348.3  449.99
#Mann=7,-1,0
  4673.6    0.05       0  4753.1    0.16       0  5001.2    0.07       0
  5007.2    0.16       0  5061.4    0.12       0  5095.7    0.16       0
  5227.0    0.05       0
Bank Sta=4860.9,5084.7
Exp/Cntr=0.3,0.1

Type RM Length L Ch R = 1,2792,306,306,306
BEGIN DESCRIPTION:
Mapping XS 697bac3e
END DESCRIPTION:
XS GIS Cut Line= 3
      2906658.71      7030027.87      2906242.02      7029986.21
      2905829.64      7030169.87
#Sta/Elev= 30
  4548.1  446.15  4592.0  445.45  4627.2  443.14  4727.7  441.59  4732.7  442.14
  4793.1  439.75  4813.1  438.89  4828.2  437.10  4843.3  437.10  4880.0  435.37
  4943.8  433.10  4985.5  434.00  4995.9  430.48  5000.8  429.78  5004.4  428.41
  5004.9  427.61  5009.9  427.61  5010.4  428.41  5018.3  433.96  5107.8  435.37
  5151.7  440.64  5205.2  444.18  5226.9  445.55  5244.7  445.63  5250.1  446.41
  5291.1  446.14  5313.9  446.84  5379.6  449.91  5389.5  449.74  5418.3  452.02
#Mann=5,-1,0
  4548.1    0.05       0  4793.1    0.16       0  5004.4    0.07       0
  5010.4    0.16       0  5205.2    0.05       0
Bank Sta=4880,5107.8
Exp/Cntr=0.3,0.1

Type RM Length L Ch R = 1,2486,377,377,377
BEGIN DESCRIPTION:
UNT 035 IN DRY CR WATERSHED 4.0
END DESCRIPTION:
XS GIS Cut Line= 3
      2906424.98      7029675.00      2906075.00      7029725.00
      2905774.99      7029925.01
#Sta/Elev= 30
  4656.0  442.67  4686.3  441.34  4736.8  437.67  4757.0  436.67  4767.1  435.78
  4777.2  435.59  4827.7  437.60  4837.8  438.50  4888.3  439.42  4898.4  439.30
  4928.7  436.31  4967.7  433.05  4975.6  431.97  4996.4  427.40  4996.9  426.60
  5001.9  426.60  5002.4  427.40  5007.0  429.33  5012.5  429.33  5016.0  431.97
  5017.0  432.76  5023.0  433.01  5081.6  432.46  5135.5  434.58  5182.3  438.64
  5254.4  440.96  5311.5  444.28  5356.6  446.19  5367.1  447.37  5370.1  447.37
#Mann=5,-1,0
  4656.0    0.05       0  4967.7    0.16       0  4996.4    0.07       0
  5002.4    0.16       0  5135.5    0.05       0
Bank Sta=4975.6,5016
Exp/Cntr=0.3,0.1

Type RM Length L Ch R = 1,2109,481,481,481
BEGIN DESCRIPTION:
UNT 035 IN DRY CR WATERSHED 3.0
END DESCRIPTION:
XS GIS Cut Line= 3
      2906624.99      7029075.00      2906025.00      7029375.00
      2905774.97      7029575.02
#Sta/Elev= 30
  4359.5  457.84  4373.5  457.83  4404.2  455.78  4530.0  446.31  4546.8  445.68
  4552.4  444.76  4574.7  443.52  4591.5  443.88  4641.8  441.34  4779.2  430.39
  4843.0  428.38  4904.4  427.60  4918.5  428.92  4985.6  430.24  4994.0  429.13
  5005.0  426.51  5005.5  425.71  5010.5  425.71  5011.0  426.51  5016.3  430.12
  5066.3  429.63  5084.8  430.39  5101.5  432.85  5128.7  435.31  5194.4  438.67
  5215.2  438.15  5258.4  441.16  5286.4  441.58  5314.5  440.83  5350.5  441.96
#Mann=5,-1,0
  4359.5    0.05       0  4904.4    0.16       0  5005.0    0.07       0
  5011.0    0.16       0  5128.7    0.05       0
Bank Sta=4779.2,5084.8
Exp/Cntr=0.3,0.1

Type RM Length L Ch R = 1,1628,392,392,392
BEGIN DESCRIPTION:
UNT 035 IN DRY CR WATERSHED 2.0
END DESCRIPTION:
XS GIS Cut Line= 3
      2906225.01      7028875.00      2905775.00      7028975.00
      2905324.96      7028925.00
#Sta/Elev= 30
  4585.9  446.75  4794.6  440.53  4863.7  436.81  4881.7  434.91  4886.8  435.42
  4921.6  429.01  4930.4  427.43  4979.0  427.65  5005.9  426.60  5016.2  425.21
  5027.7  421.99  5033.5  421.79  5034.0  420.99  5039.3  420.99  5039.8  421.79
  5049.4  422.19  5056.9  425.22  5067.0  426.58  5102.0  426.72  5154.0  429.01
  5197.8  433.53  5228.0  434.97  5268.2  435.27  5278.3  436.28  5338.7  437.61
  5389.0  441.22  5409.1  441.45  5419.2  440.64  5479.5  442.74  5499.7  442.57
#Mann=5,-1,0
  4585.9    0.05       0  4863.7    0.16       0  5033.5    0.07       0
  5039.8    0.16       0  5102.0    0.05       0
Bank Sta=4921.6,5154
Exp/Cntr=0.3,0.1

Type RM Length L Ch R = 1,1236,426,426,426
BEGIN DESCRIPTION:
Mapping XS 54f4796b
END DESCRIPTION:
XS GIS Cut Line= 3
      2906351.73      7028829.95      2905907.30      7028607.73
      2905388.24      7028573.13
#Sta/Elev= 30
  4489.1  449.17  4563.7  447.20  4596.2  447.32  4601.8  446.23  4708.0  442.69
  4752.7  439.49  4809.7  433.00  4864.5  430.12  4911.9  426.34  4956.7  425.17
  4981.9  425.88  4989.6  424.98  4995.2  420.06  4995.7  419.26  5001.0  419.26
  5001.5  420.06  5008.3  424.66  5018.4  425.98  5048.4  424.50  5068.5  425.57
  5108.6  424.65  5127.8  425.37  5143.2  426.34  5248.2  436.57  5253.2  436.17
  5268.9  438.31  5309.0  441.31  5403.6  443.02  5429.3  441.67  5506.2  443.14
#Mann=5,-1,0
  4489.1    0.05       0  4956.7    0.16       0  4995.2    0.07       0
  5001.5    0.16       0  5127.8    0.05       0
Bank Sta=4911.9,5143.2
Exp/Cntr=0.3,0.1

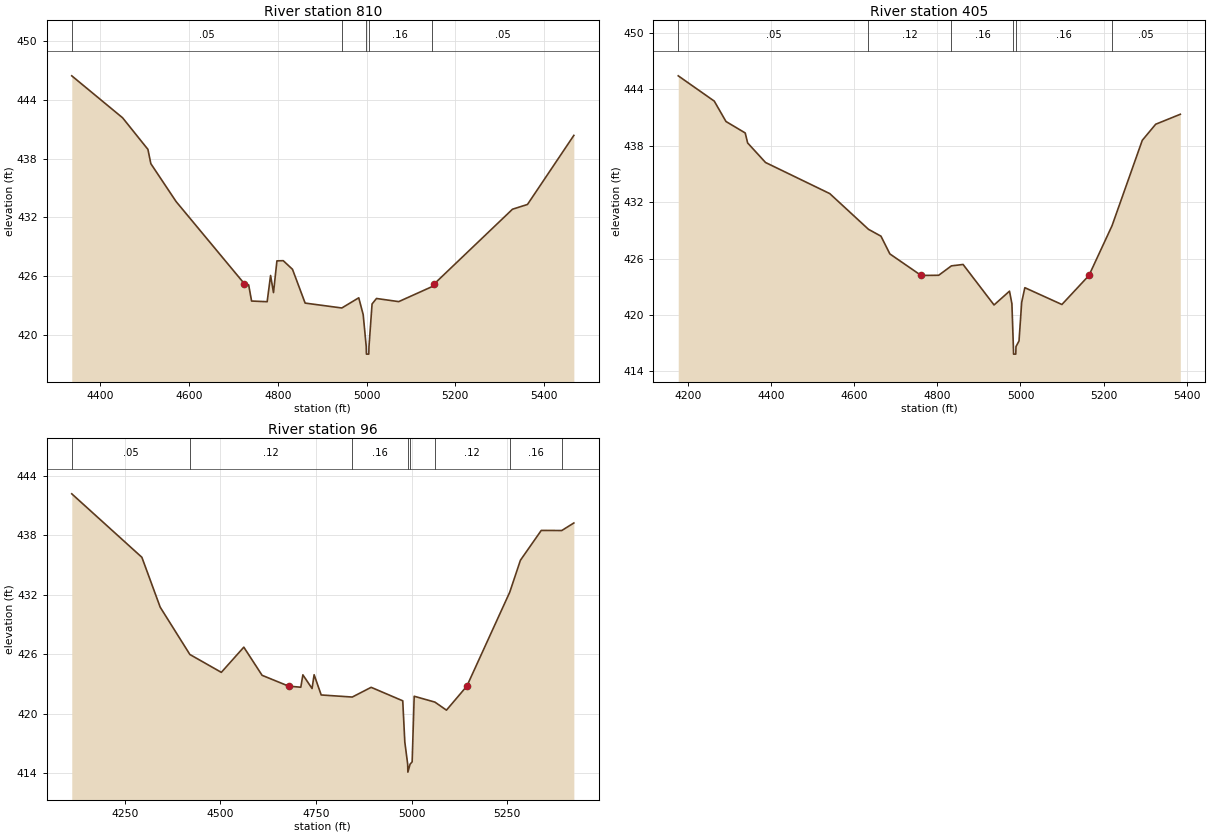
Type RM Length L Ch R = 1,810,405,405,405
BEGIN DESCRIPTION:
Mapping XS 9b2dfb04
END DESCRIPTION:
XS GIS Cut Line= 3
      2906403.84      7028698.03      2905994.11      7028222.32
      2905490.63      7028246.62
#Sta/Elev= 30
  4335.4  446.45  4450.1  442.16  4507.1  438.94  4513.7  437.48  4570.7  433.61
  4724.4  425.23  4734.2  425.11  4740.8  423.46  4775.9  423.39  4783.6  426.07
  4790.2  424.32  4797.9  427.56  4812.1  427.58  4833.0  426.70  4861.5  423.25
  4944.2  422.75  4982.4  423.79  4992.4  422.07  4999.2  418.84  4999.7  418.04
  5005.0  418.04  5005.5  418.84  5012.4  423.16  5022.4  423.72  5072.5  423.40
  5146.6  424.91  5153.1  425.23  5328.9  432.83  5362.8  433.32  5467.3  440.37
#Mann=5,-1,0
  4335.4    0.05       0  4944.2    0.16       0  4999.2    0.07       0
  5005.5    0.16       0  5146.6    0.05       0
Bank Sta=4724.4,5153.1
Exp/Cntr=0.3,0.1

Type RM Length L Ch R = 1,405,309,309,309
BEGIN DESCRIPTION:
Mapping XS 5ab70d0e
END DESCRIPTION:
XS GIS Cut Line= 3
      2906494.10      7028604.25      2906080.91      7027895.93
      2905719.88      7027753.60
#Sta/Elev= 30
  4176.5  445.45  4263.2  442.76  4291.4  440.59  4337.7  439.37  4343.5  438.31
  4386.5  436.23  4541.1  432.92  4634.3  429.12  4664.3  428.39  4685.8  426.50
  4761.0  424.21  4803.2  424.23  4833.8  425.23  4861.9  425.38  4936.4  421.07
  4973.6  422.54  4979.4  421.20  4982.9  416.64  4983.4  415.84  4988.7  415.84
  4989.2  416.64  4996.5  417.24  5002.9  421.35  5010.5  422.91  5099.7  421.12
  5164.8  424.21  5220.3  429.50  5293.1  438.59  5325.4  440.30  5384.6  441.36
#Mann=6,-1,0
  4176.5    0.05       0  4634.3    0.12       0  4833.8    0.16       0
  4982.9    0.07       0  4989.2    0.16       0  5220.3    0.05       0
Bank Sta=4761,5164.8
Exp/Cntr=0.3,0.1

Type RM Length L Ch R = 1,96,0,0,0
BEGIN DESCRIPTION:
UNT 035 IN DRY CR WATERSHED 1.0
END DESCRIPTION:
XS GIS Cut Line= 3
      2906629.53      7028500.10      2906300.00      7027700.00
      2905882.97      7027538.28
#Sta/Elev= 30
  4111.4  442.17  4294.7  435.77  4342.6  430.74  4420.2  425.97  4502.4  424.17
  4561.2  426.71  4609.0  423.87  4678.4  422.78  4710.2  422.67  4715.6  423.92
  4739.6  422.54  4745.0  423.93  4763.5  421.89  4844.7  421.68  4894.1  422.66
  4976.7  421.30  4982.1  417.14  4989.6  414.91  4990.1  414.11  4995.9  414.91
  5001.3  415.15  5006.6  421.76  5060.8  421.17  5091.0  420.36  5144.3  422.78
  5256.4  432.25  5284.3  435.47  5338.8  438.48  5392.4  438.47  5424.0  439.23
#Mann=8,-1,0
  4111.4    0.05       0  4420.2    0.12       0  4844.7    0.16       0
  4989.6    0.07       0  4995.9    0.16       0  5060.8    0.12       0
  5256.4    0.16       0  5392.4    0.05       0
Bank Sta=4678.4,5144.3
Exp/Cntr=0.3,0.1

Chan Stop Cuts=-1