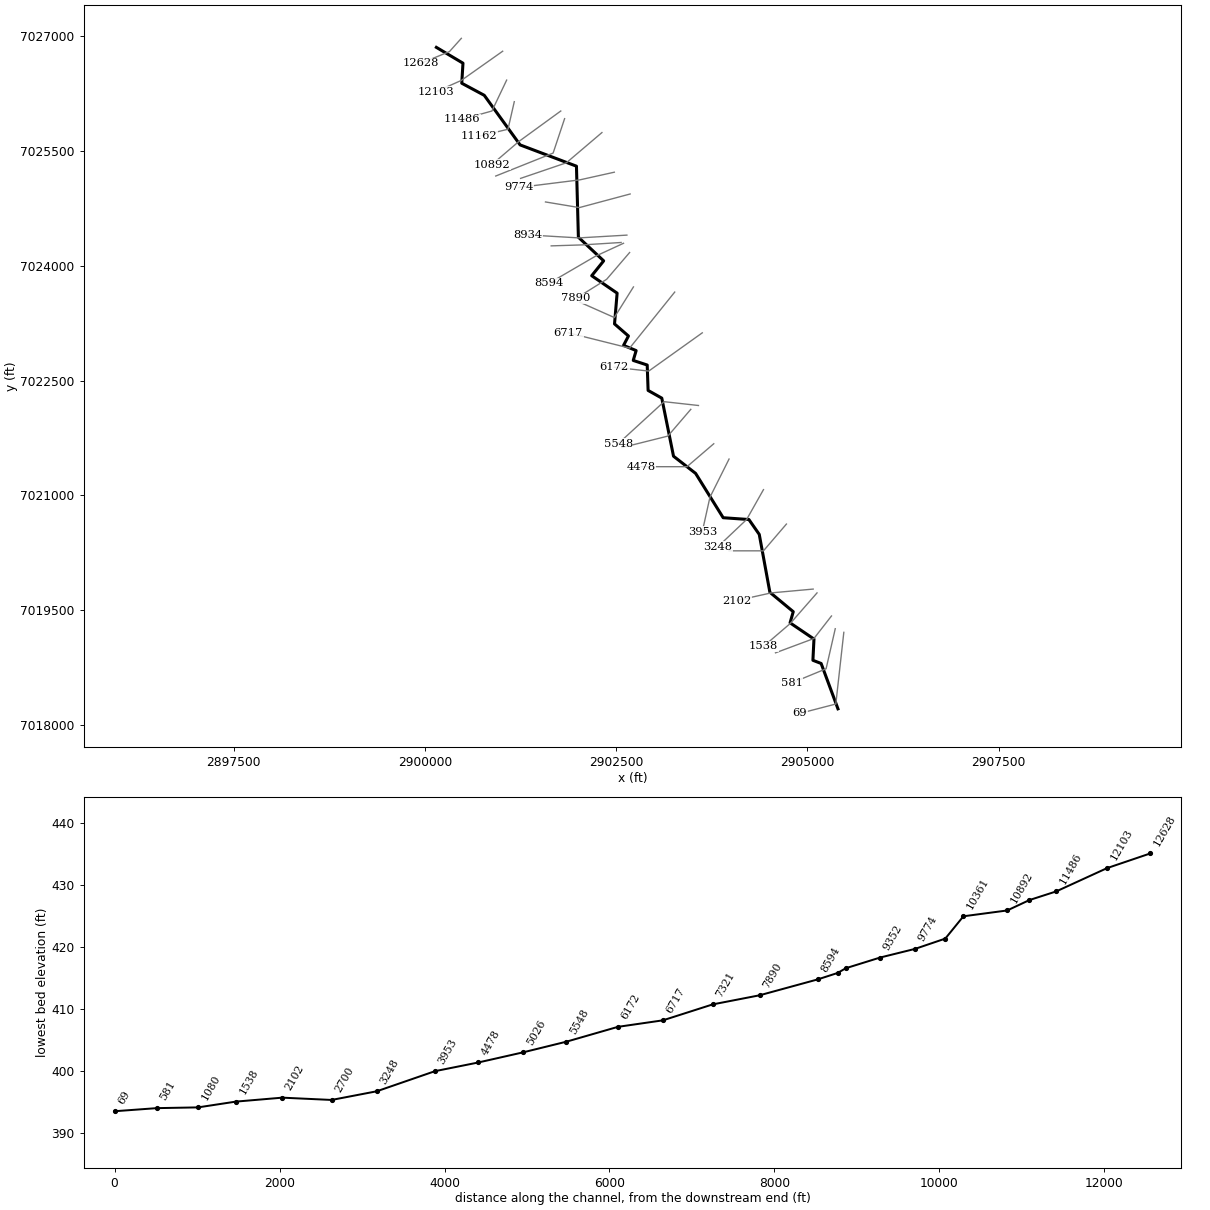
--- UNT 036 IN DRY CR WATERSHED.prj (project) ---

Proj Title=UNT 036 IN DRY CR WATERSHED Base Level Engineering
Current Plan=p01
Default Exp/Contr=0.3,0.1
English Units
Geom File=g01
Flow File=f01
Plan File=p01
Y Axis Title=Elevation
X Axis Title(PF)=Main Channel Distance
X Axis Title(XS)=Station
BEGIN DESCRIPTION:
UNT 036 IN DRY CR WATERSHED
END DESCRIPTION:
DSS Export Rating Curves= 0
DSS Export Rating Curve Sorted= 0
DSS Export Volume Flow Curves= 0
DXF OffsetX= 0
DXF OffsetY= 0
DXF ScaleX= 1
DXF ScaleY= 10

--- UNT 036 IN DRY CR WATERSHED.p01 (plan) ---

Plan Title=Multiple Run
Short Identifier=Multiple
Geom File=g01
Flow File=f01
Subcritical Flow
K Sum by GR= 0
Std Step Tol= 0.01
Critical Tol= 0.01
Num of Std Step Trials= 20
Max Error Tol= 0.3
Flow Tol Ratio= 0.001
Split Flow NTrial= 30
Split Flow Tol= 0.02
Split Flow Ratio= 0.02
Log Output Level= 0
Friction Slope Method= 1
Unsteady Friction Slope Method= 2
Unsteady Bridges Friction Slope Method= 1
Parabolic Critical Depth
Global Vel Dist=  1 , 1 , 1
Global Log Level= 0
CheckData=True
Encroach Param= -1, 0, 0, 0
BEGIN DESCRIPTION:
Multiple Run
END DESCRIPTION:

--- UNT 036 IN DRY CR WATERSHED.f01 (steady flow) ---

Flow Title=Multiple
Number of Profiles=7
Profile Names=10-year,25-year,50-year,1pct_min,100-year,1pct_plu,500-year
River Rch & RM= UNT 036 IN DRY C,Reach-1,12628
     563     760     922     557    1111    2218    1616
River Rch & RM= UNT 036 IN DRY C,Reach-1,12103
     824    1133    1391     850    1695    3382    2520
River Rch & RM= UNT 036 IN DRY C,Reach-1,8836
    1089    1519    1883    1159    2313    4615    3497
River Rch & RM= UNT 036 IN DRY C,Reach-1,5026
    1181    1648    2042    1255    2504    4997    3777
Boundary for River Rch & Prof#=UNT 036 IN DRY C,Reach-1,1
Up Type=0
Dn Type=3
Dn Slope=0.005
Boundary for River Rch & Prof#=UNT 036 IN DRY C,Reach-1,2
Up Type=0
Dn Type=3
Dn Slope=0.005
Boundary for River Rch & Prof#=UNT 036 IN DRY C,Reach-1,3
Up Type=0
Dn Type=3
Dn Slope=0.005
Boundary for River Rch & Prof#=UNT 036 IN DRY C,Reach-1,4
Up Type=0
Dn Type=3
Dn Slope=0.005
Boundary for River Rch & Prof#=UNT 036 IN DRY C,Reach-1,5
Up Type=0
Dn Type=3
Dn Slope=0.005
Boundary for River Rch & Prof#=UNT 036 IN DRY C,Reach-1,6
Up Type=0
Dn Type=3
Dn Slope=0.005
Boundary for River Rch & Prof#=UNT 036 IN DRY C,Reach-1,7
Up Type=0
Dn Type=3
Dn Slope=0.005

--- UNT 036 IN DRY CR WATERSHED.g01 (geometry) ---

Geom Title=Existing Conditions
Program Version=5.07

River Reach=UNT 036 IN DRY C,Reach-1
Reach XY= 30
      2900148.86      7026856.94      2900496.48      7026650.16
      2900480.55      7026388.09       2900774.7       7026230.1
      2901243.18      7025581.93        2901980.      7025303.61
      2902005.26      7024375.03      2902335.72      7024066.01
      2902179.52      7023871.58      2902511.62       7023643.7
      2902477.76      7023241.61      2902659.87      7023083.46
      2902595.57      7022960.76      2902760.54      7022892.91
      2902722.26      7022764.04      2902904.98      7022704.11
      2902916.74      7022372.03      2903095.61      7022271.29
      2903248.98      7021511.92      2903537.78      7021287.41
      2903898.16      7020707.86      2904234.46      7020684.26
      2904369.88      7020489.82      2904508.77      7019732.87
      2904814.32       7019479.4      2904772.65      7019333.57
      2905085.15      7019121.76      2905071.27      7018843.98
       2905178.9      7018802.32      2905398.78      7018209.43

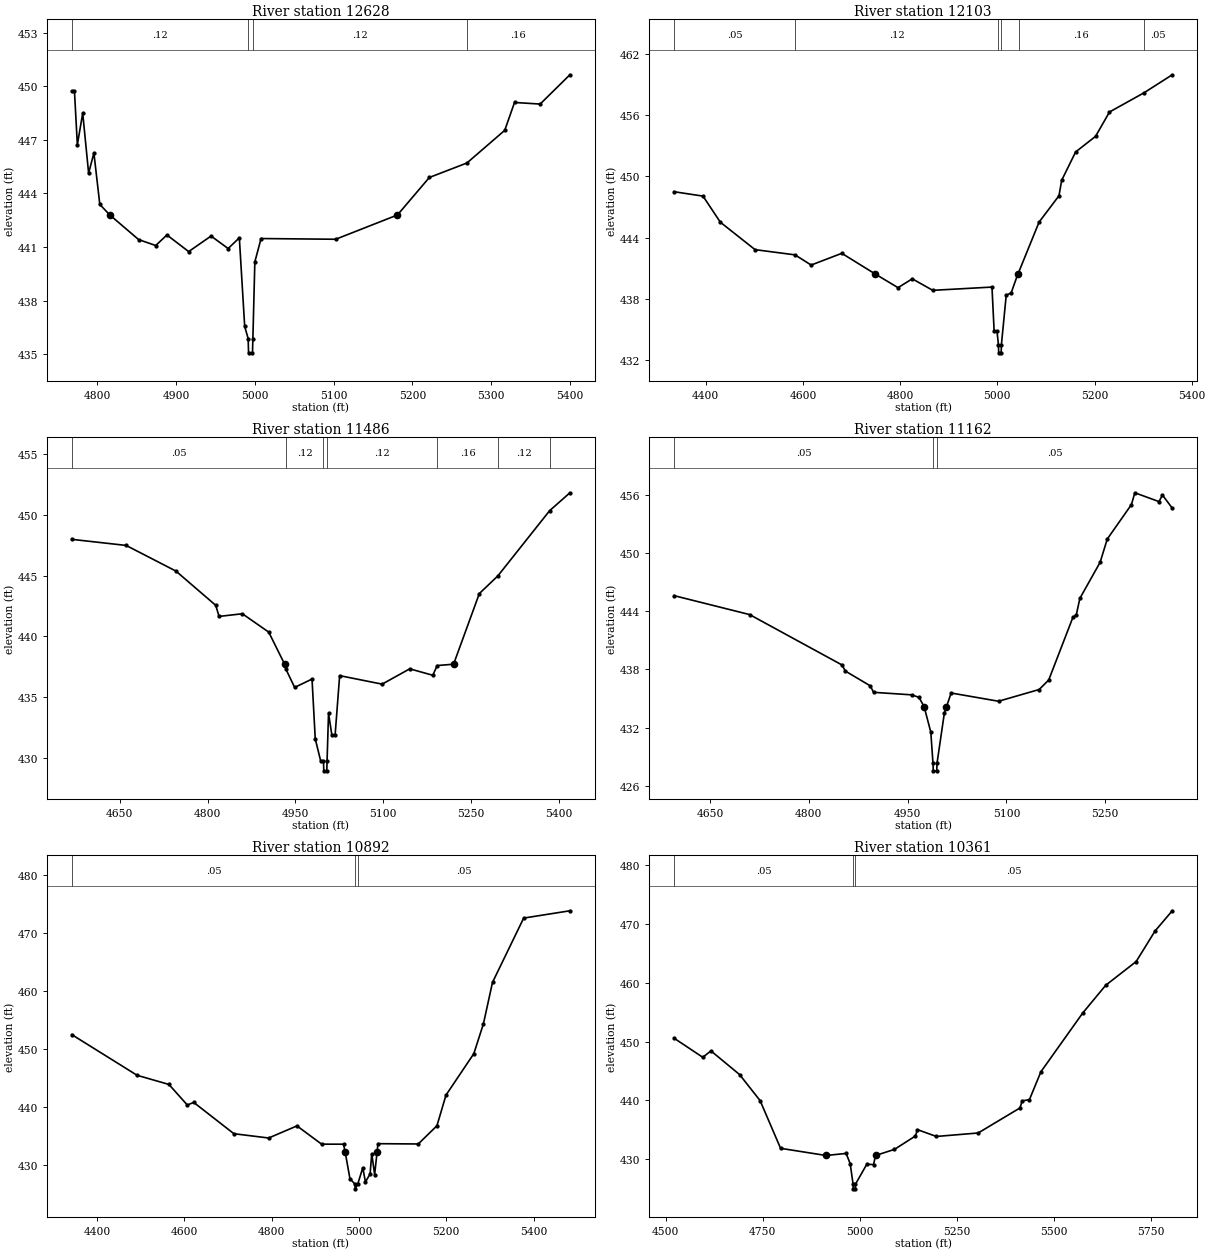
Type RM Length L Ch R = 1 ,12628   ,525,525,525
BEGIN DESCRIPTION:
UNT 036 IN DRY CR WATERSHED 21.0
END DESCRIPTION:
XS GIS Cut Line= 3
      2900475.03      7026975.03      2900319.83      7026801.92
      2899950.01      7026650.01
#Sta/Elev= 30
  4767.5  449.74  4770.9  449.74  4774.6  446.72  4781.4  448.49  4788.9  445.13
  4795.6  446.26  4803.1  443.38  4815.8  442.79  4852.4  441.41  4874.1  441.08
  4888.3  441.67  4915.9  440.74  4944.3  441.61    4966  440.91  4980.2  441.51
    4987  436.55  4991.4  435.87  4991.9  435.07  4996.9  435.07  4997.4  435.87
  4999.9  440.17  5007.8  441.47  5102.5  441.43  5180.9  442.79  5221.4  444.89
  5269.1   445.7  5317.1  447.53  5329.5  449.09    5362     449  5399.8  450.64
#Mann= 4 ,-1 , 0
  4767.5     .12       0  4991.4     .07       0  4997.4     .12       0
  5269.1     .16       0
Bank Sta=4815.8,5180.9
XS Rating Curve= 0 ,0
Exp/Cntr=0.3,0.1

Type RM Length L Ch R = 1 ,12103   ,617,617,617
BEGIN DESCRIPTION:
UNT 036 IN DRY CR WATERSHED 20.0
END DESCRIPTION:
XS GIS Cut Line= 3
      2901015.41      7026806.55        2900475.        7026425.
      2900143.01      7026277.03
#Sta/Elev= 30
  4334.9   448.5  4394.4  448.07  4430.1  445.51  4501.5  442.82  4583.7  442.31
  4616.9  441.31    4680  442.46  4747.8  440.46  4795.7  439.09    4825  439.96
  4867.1  438.83    4989  439.15  4993.4  434.86  4999.2  434.86  5002.3   433.5
  5002.8   432.7  5007.9   432.7  5008.4   433.5  5018.3  438.35  5028.5  438.58
  5042.4  440.45  5043.7  440.57  5085.9  445.52  5126.9  448.11  5132.4  449.62
  5161.1   452.4  5202.1  453.93  5230.8  456.32  5302.1  458.21  5359.9  459.97
#Mann= 6 ,-1 , 0
  4334.9     .05       0  4583.7     .12       0  5002.3     .07       0
  5008.4     .12       0  5043.7     .16       0  5302.1     .05       0
Bank Sta=4747.8,5042.4
XS Rating Curve= 0 ,0
Exp/Cntr=0.3,0.1

Type RM Length L Ch R = 1 ,11486   ,324,324,324
BEGIN DESCRIPTION:
UNT 036 IN DRY CR WATERSHED 19.0
END DESCRIPTION:
XS GIS Cut Line= 3
      2901067.44      7026428.88        2900875.        7026025.
      2900485.86      7025916.77
#Sta/Elev= 30
  4567.8  447.98  4660.7  447.48  4745.8  445.37  4813.9  442.55  4819.5  441.64
  4859.3  441.86  4904.4  440.35  4931.6  437.71  4933.7  437.31  4948.7   435.8
  4978.4  436.49  4983.9  431.57    4993  429.79    4998  429.74  4998.5  428.94
  5003.6  428.94  5004.1  429.74  5006.6  433.68  5012.4  431.85  5017.8  431.85
  5025.6  436.77  5098.2  436.07  5145.4  437.33  5184.8   436.8  5192.3   437.6
  5220.3  437.71  5264.3  443.52  5295.9  444.97  5384.5  450.34  5419.1  451.81
#Mann= 7 ,-1 , 0
  4567.8     .05       0  4933.7     .12       0    4998     .07       0
  5004.1     .12       0  5192.3     .16       0  5295.9     .12       0
  5384.5     .05       0
Bank Sta=4931.6,5220.3
XS Rating Curve= 0 ,0
Exp/Cntr=0.3,0.1

Type RM Length L Ch R = 1 ,11162   ,270,270,270
BEGIN DESCRIPTION:
Mapping XS db920c9f
END DESCRIPTION:
XS GIS Cut Line= 3
      2901167.29       7026146.8      2901084.82      7025786.56
      2900708.58      7025695.75
#Sta/Elev= 30
  4595.3   445.6    4710  443.65  4850.3  438.46  4855.4  437.83  4893.2  436.31
  4898.3  435.64  4956.2  435.38  4967.3  435.12  4975.1  434.15  4985.2  431.54
  4988.5  428.35    4989  427.55  4994.2  427.55  4994.7  428.35  5005.8  433.51
    5009  434.15  5016.1  435.57  5088.1  434.72  5149.8  435.93  5164.3  436.91
    5201  443.36  5206.2  443.63  5211.6  445.32  5242.4  449.04  5253.2  451.43
  5289.9  454.98  5295.1   456.2  5331.8  455.29    5337  455.97  5351.9  454.62
#Mann= 3 ,-1 , 0
  4595.3     .05       0  4988.5     .03       0  4994.7     .05       0
Bank Sta=4975.1,5009
XS Rating Curve= 0 ,0
Exp/Cntr=0.3,0.1

Type RM Length L Ch R = 1 ,10892   ,531,531,531
BEGIN DESCRIPTION:
UNT 036 IN DRY CR WATERSHED 18.0
END DESCRIPTION:
XS GIS Cut Line= 3
      2901775.01      7026025.01        2901225.        7025625.
      2900874.98      7025324.98
#Sta/Elev= 30
  4342.1  452.48  4491.7  445.46  4564.7  443.88  4606.8  440.33  4621.5  440.78
  4713.5  435.38  4793.1  434.64    4858  436.73  4914.4  433.58  4964.6  433.57
  4968.2   432.3  4979.3  427.64  4990.9  426.67  4991.4  425.87  4997.1  426.67
  5008.7  429.51  5014.8  427.06  5025.5  428.43  5029.3  431.94  5035.9  428.33
  5041.6   432.3  5043.6  433.66  5135.8  433.61  5178.6  436.75  5199.4  442.05
  5263.1  449.19  5285.1  454.34  5305.9  461.49  5377.3  472.58  5483.2  473.84
#Mann= 3 ,-1 , 0
  4342.1     .05       0  4990.9     .03       0  4997.1     .05       0
Bank Sta=4968.2,5041.6
XS Rating Curve= 0 ,0
Exp/Cntr=0.3,0.1

Type RM Length L Ch R = 1 ,10361   ,220,220,220
BEGIN DESCRIPTION:
UNT 036 IN DRY CR WATERSHED 17.0
END DESCRIPTION:
XS GIS Cut Line= 3
      2901825.01      7025925.03        2901675.        7025475.
      2900924.95      7025174.98
#Sta/Elev= 30
  4521.8  450.58  4595.6  447.33  4616.7  448.42  4690.5  444.38  4743.2  439.95
  4795.9  431.83  4912.8  430.61  4964.6  430.96  4975.1  429.21  4982.5  425.73
    4983  424.93  4988.2  424.93  4988.7  425.73  5017.7   429.1  5035.2  429.07
  5040.4  430.61  5089.1  431.65  5142.9  433.93  5148.3  435.01  5196.8  433.85
  5304.5  434.44  5412.2  438.71  5417.6   439.9  5436.4  440.12    5466  444.87
  5573.7  454.88    5633  459.61  5711.1  463.63  5759.5  468.81    5804  472.28
#Mann= 3 ,-1 , 0
  4521.8     .05       0  4982.5     .03       0  4988.7     .05       0
Bank Sta=4912.8,5040.4
XS Rating Curve= 0 ,0
Exp/Cntr=0.3,0.1

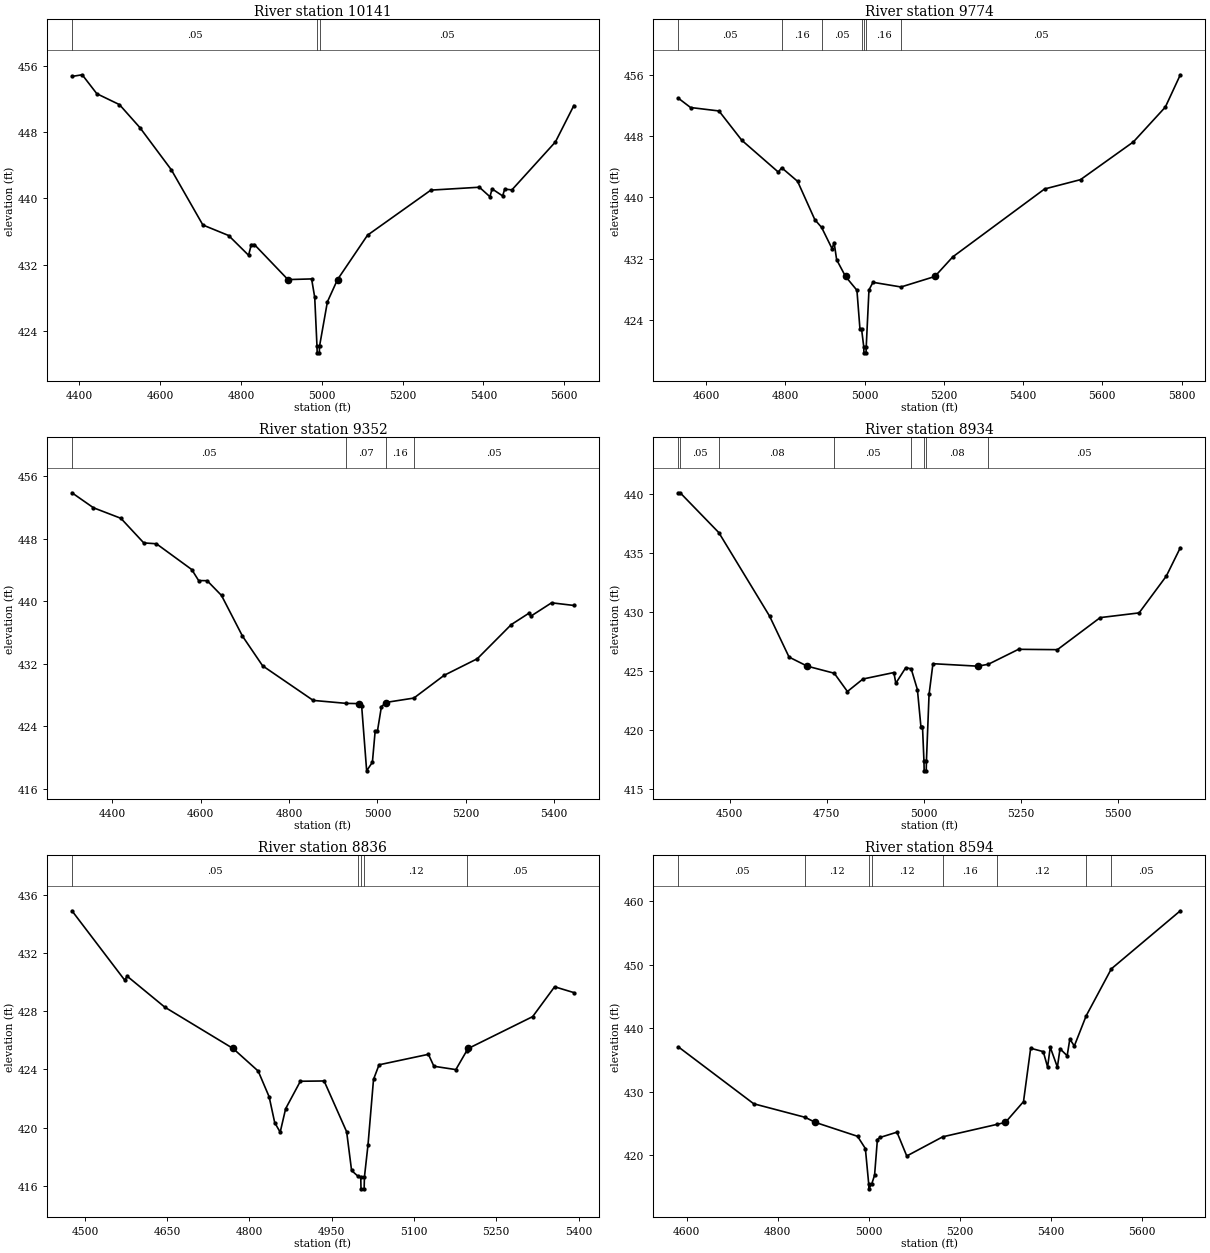
Type RM Length L Ch R = 1 ,10141   ,367,367,367
BEGIN DESCRIPTION:
Mapping XS 0a701026
END DESCRIPTION:
XS GIS Cut Line= 3
      2902313.14      7025743.18      2901848.71      7025348.19
      2901249.87      7025144.24
#Sta/Elev= 30
  4381.6  454.76    4407  454.96  4443.2  452.67  4499.2  451.35  4549.8  448.57
  4627.7  443.46  4705.7  436.79  4769.4  435.52  4818.8  433.13  4825.5  434.42
  4833.1  434.43  4916.2  430.19  4974.8  430.27  4982.5  428.04  4988.1  422.13
  4988.6  421.33  4993.9  421.33  4994.4  422.13  5013.9   427.5  5038.9  430.19
  5113.2  435.56    5270  441.01  5390.1  441.36  5416.2  440.21  5421.5  441.16
  5447.6  440.31  5452.8  441.13  5470.6  441.04  5578.3  446.84  5623.9  451.24
#Mann= 3 ,-1 , 0
  4381.6     .05       0  4988.1     .03       0  4994.4     .05       0
Bank Sta=4916.2,5038.9
XS Rating Curve= 0 ,0
Exp/Cntr=0.3,0.1

Type RM Length L Ch R = 1 ,9774    ,422,422,422
BEGIN DESCRIPTION:
UNT 036 IN DRY CR WATERSHED 16.0
END DESCRIPTION:
XS GIS Cut Line= 3
      2902474.99        7025225.        2902025.        7025125.
      2901224.99        7025025.
#Sta/Elev= 30
  4529.8  452.95  4560.5  451.74  4632.2  451.29  4689.8  447.46    4782   443.3
  4790.5  443.87  4830.7  442.09  4874.2  437.08  4891.4  436.06  4917.8  433.28
  4922.9  434.09  4929.3  431.84  4951.8  429.65  4980.5  427.85  4988.2  422.75
  4992.3  422.75  4997.7  420.47  4998.2  419.67  5003.5  419.67    5004  420.47
  5010.9  427.89    5021  428.89  5091.8  428.28  5177.2  429.65  5222.6  432.22
  5454.3  441.09    5545  442.31  5678.6  447.25  5759.2   451.8    5797  456.02
#Mann= 7 ,-1 , 0
  4529.8     .05       0  4790.5     .16       0  4891.4     .05       0
  4992.3     .16       0  4997.7     .07       0    5004     .16       0
  5091.8     .05       0
Bank Sta=4951.8,5177.2
XS Rating Curve= 0 ,0
Exp/Cntr=0.3,0.1

Type RM Length L Ch R = 1 ,9352    ,418,418,418
BEGIN DESCRIPTION:
Mapping XS edc1465d
END DESCRIPTION:
XS GIS Cut Line= 3
      2902682.01       7024940.2      2902017.98      7024762.26
      2901575.25      7024836.04
#Sta/Elev= 30
  4308.3  453.89    4357  451.97  4419.1  450.62  4470.9  447.47  4499.5  447.36
  4579.5  444.06  4595.1  442.65  4614.4  442.63  4646.9  440.74  4694.4  435.53
    4740  431.73  4854.5   427.3  4929.4  426.92  4957.4  426.89  4964.2  426.58
  4975.5  418.28  4988.5  419.38  4994.7  423.33  4999.8  423.33  5008.9  426.49
    5019  427.03  5019.1  427.04  5082.4   427.6  5150.9  430.51  5226.1  432.64
  5302.9  437.01  5342.7  438.46  5347.8  438.11  5394.2   439.8  5444.6  439.46
#Mann= 4 ,-1 , 0
  4308.3     .05       0  4929.4     .07       0  5019.1     .16       0
  5082.4     .05       0
Bank Sta=4957.4,5019
XS Rating Curve= 0 ,0
Exp/Cntr=0.3,0.1

Type RM Length L Ch R = 1 ,8934    ,98,98,98
BEGIN DESCRIPTION:
Mapping XS d050f663
END DESCRIPTION:
XS GIS Cut Line= 3
      2902639.54      7024402.45       2902011.9      7024365.99
      2901348.94      7024404.99
#Sta/Elev= 30
  4367.8  440.14  4372.9  440.12  4471.9  436.76  4602.7  429.67  4652.8   426.2
  4699.7  425.43  4769.2  424.83  4803.1  423.28  4843.1  424.34  4922.8  424.89
  4927.8  423.98  4953.3   425.3  4967.3  425.21  4983.4  423.44  4992.4  420.31
  4996.5  420.31  5000.3  417.35  5000.8  416.55  5006.1  416.55  5006.6  417.35
  5013.4  423.03  5023.4  425.64  5138.7  425.43    5166  425.59  5243.8  426.86
    5344  426.83  5454.2  429.55  5554.4  429.95  5624.5  433.07  5660.6  435.48
#Mann= 8 ,-1 , 0
  4367.8     .08       0  4372.9     .05       0  4471.9     .08       0
  4769.2     .05       0  4967.3     .08       0  5000.3     .07       0
  5006.6     .08       0    5166     .05       0
Bank Sta=4699.7,5138.7
XS Rating Curve= 0 ,0
Exp/Cntr=0.3,0.1

Type RM Length L Ch R = 1 ,8836    ,242,242,242
BEGIN DESCRIPTION:
Mapping XS cbd86259
END DESCRIPTION:
XS GIS Cut Line= 3
      2902563.95      7024306.09      2902063.99      7024274.84
      2901649.93      7024261.82
#Sta/Elev= 30
  4476.3  434.89  4572.2  430.14  4577.2  430.39  4645.6  428.27  4770.1  425.43
  4815.9  423.88  4835.9  422.11    4846  420.34    4856  419.68    4866   421.3
  4892.8  423.18  4936.1   423.2  4977.2  419.71  4986.2  417.05    4998  416.65
  5002.9  416.59  5003.4  415.79  5009.1  415.79  5009.6  416.59  5016.2  418.83
  5026.2  423.31  5036.3  424.31  5126.3  425.03  5136.3  424.21  5176.3  423.98
  5196.1  425.27  5198.9  425.43  5316.4  427.62  5356.4  429.67  5391.5  429.27
#Mann= 5 ,-1 , 0
  4476.3     .05       0    4998     .12       0  5002.9     .07       0
  5009.6     .12       0  5196.1     .05       0
Bank Sta=4770.1,5198.9
XS Rating Curve= 0 ,0
Exp/Cntr=0.3,0.1

Type RM Length L Ch R = 1 ,8594    ,704,704,704
BEGIN DESCRIPTION:
UNT 036 IN DRY CR WATERSHED 14.0
END DESCRIPTION:
XS GIS Cut Line= 3
      2902595.21      7024295.66        2902225.        7024125.
      2901624.98      7023774.99
#Sta/Elev= 30
  4582.1  437.09  4747.5  428.14  4860.3  426.01  4882.8  425.21  4975.5  423.02
  4992.7  421.09    5000  415.55  5000.5  414.75  5006.8  415.55  5012.9  416.89
  5019.1  422.51  5024.9  422.84  5062.1  423.67  5083.6  419.92  5162.6  422.94
  5282.5  424.91  5300.3  425.21    5340  428.48  5355.7  436.88  5383.4  436.35
  5392.9  433.92  5398.7  437.05  5414.4  433.91  5420.2   436.8  5435.9   435.7
  5441.7  438.32  5451.6  437.24  5477.6  441.98  5532.9  449.38  5684.4  458.52
#Mann= 8 ,-1 , 0
  4582.1     .05       0  4860.3     .12       0    5000     .07       0
  5006.8     .12       0  5162.6     .16       0  5282.5     .12       0
  5477.6     .16       0  5532.9     .05       0
Bank Sta=4882.8,5300.3
XS Rating Curve= 0 ,0
Exp/Cntr=0.3,0.1

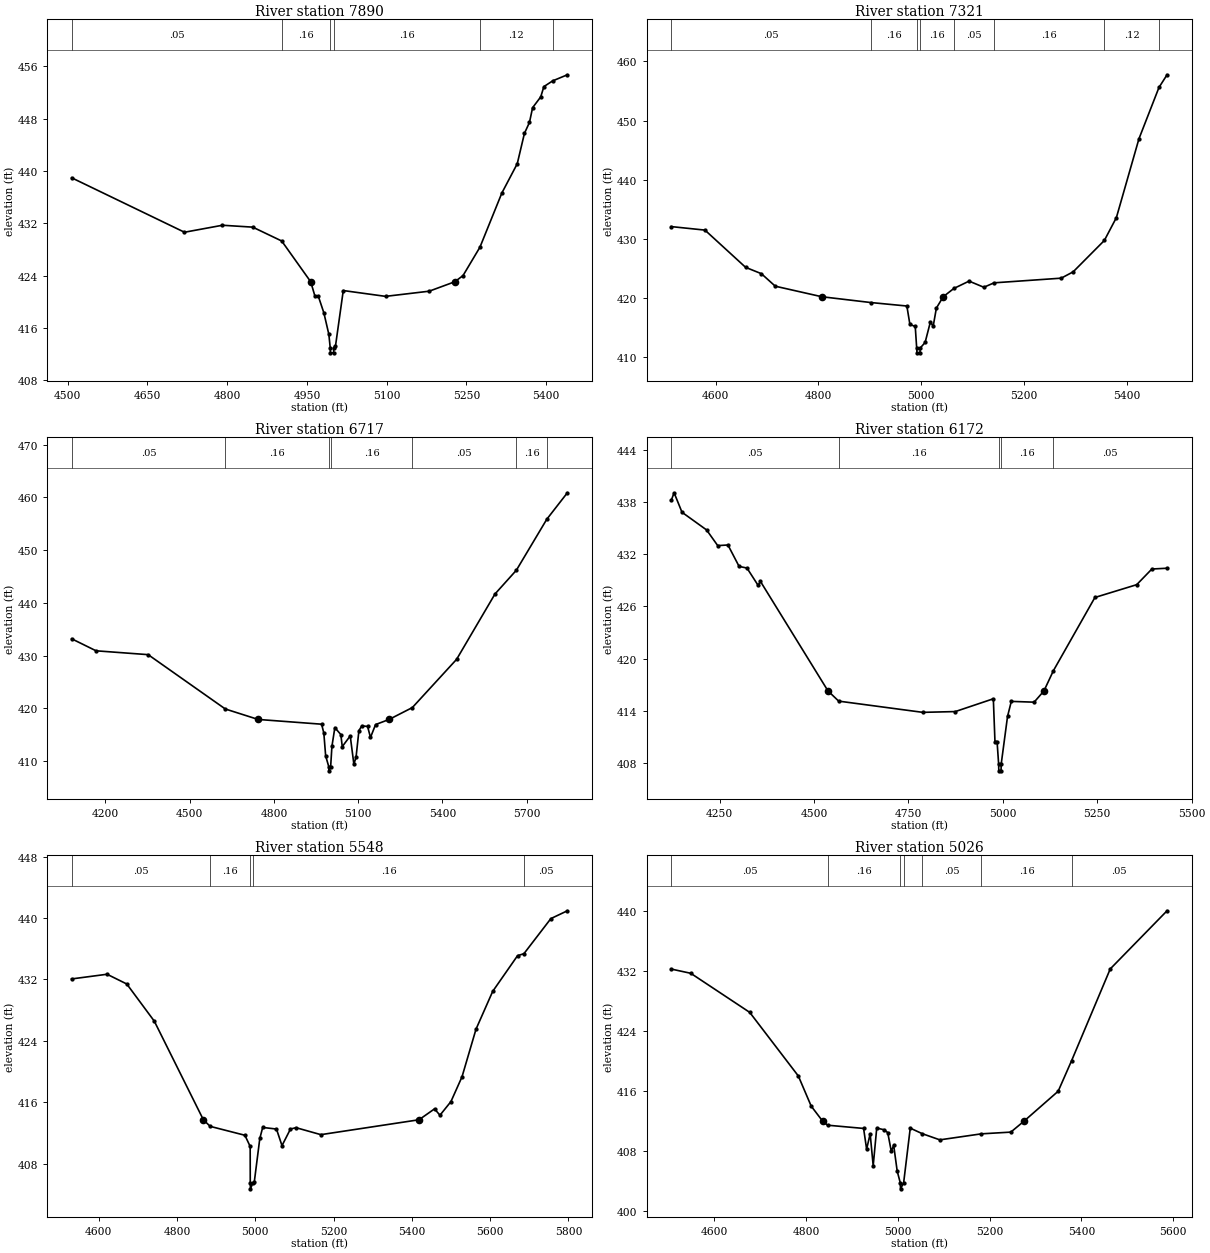
Type RM Length L Ch R = 1 ,7890    ,569,569,569
BEGIN DESCRIPTION:
UNT 036 IN DRY CR WATERSHED 13.0
END DESCRIPTION:
XS GIS Cut Line= 3
      2902674.97      7024174.96        2902375.        7023825.
      2901975.02      7023575.01
#Sta/Elev= 30
  4507.4  438.97  4719.7  430.64  4791.1  431.71  4848.1  431.42  4902.6   429.3
  4957.2  423.06    4965  420.89  4971.3  420.89  4981.9  418.31  4991.3  415.01
  4993.8  412.99  4994.3  412.19  5000.1  412.19  5000.6  412.99  5003.7  413.19
  5018.4  421.72    5098  420.83    5180  421.62  5228.1  423.06  5243.7  424.01
  5275.5  428.35  5316.8  436.65  5345.7  441.12  5359.2  445.76  5368.7  447.45
  5374.6   449.7  5389.9  451.35  5395.8  452.92  5412.4   453.8    5440  454.73
#Mann= 6 ,-1 , 0
  4507.4     .05       0  4902.6     .16       0  4993.8     .07       0
  5000.6     .16       0  5275.5     .12       0  5412.4     .05       0
Bank Sta=4957.2,5228.1
XS Rating Curve= 0 ,0
Exp/Cntr=0.3,0.1

Type RM Length L Ch R = 1 ,7321    ,604,604,604
BEGIN DESCRIPTION:
UNT 036 IN DRY CR WATERSHED 12.0
END DESCRIPTION:
XS GIS Cut Line= 3
        2902725.        7023725.        2902475.        7023325.
      2902025.03      7023524.98
#Sta/Elev= 30
  4513.9  432.07  4579.3  431.48  4658.4  425.18    4689  424.11  4716.1  421.99
  4806.5  420.21  4901.6  419.23    4972  418.64  4977.9  415.52  4988.3  415.18
  4991.1  411.52  4991.6  410.72  4997.4  410.72  4997.9  411.52  5007.5  412.48
  5017.7  415.94  5023.2  415.23  5029.4  418.29  5042.7  420.21  5063.4  421.61
    5093  422.85  5121.7  421.81  5141.5  422.56  5272.2  423.35  5295.4  424.42
  5356.1  429.73  5379.5   433.6  5423.3  446.91  5462.3  455.61    5478  457.75
#Mann= 8 ,-1 , 0
  4513.9     .05       0  4901.6     .16       0  4991.1     .03       0
  4997.9     .16       0  5063.4     .05       0  5141.5     .16       0
  5356.1     .12       0  5462.3     .05       0
Bank Sta=4806.5,5042.7
XS Rating Curve= 0 ,0
Exp/Cntr=0.3,0.1

Type RM Length L Ch R = 1 ,6717    ,545,545,545
BEGIN DESCRIPTION:
UNT 036 IN DRY CR WATERSHED 11.0
END DESCRIPTION:
XS GIS Cut Line= 3
      2903264.49      7023657.64        2902675.        7022925.
      2901874.97      7023125.01
#Sta/Elev= 30
  4079.9  433.18  4166.8   430.9  4352.3  430.17  4627.1  419.87    4744  417.89
  4969.9  416.99  4977.8   415.3  4984.3  410.99  4995.3  408.95  4995.8  408.15
  5002.1  408.95  5006.6  412.78    5017  416.34  5038.3  415.03  5043.4  412.74
  5071.8  414.77  5084.7  409.43  5092.4  410.68  5102.7  415.77    5113  416.68
  5133.6  416.56  5143.9  414.47    5162  416.92  5210.2  417.89  5292.9  420.14
  5450.6  429.29  5587.2  441.67  5663.4  446.18  5771.7  455.84  5844.9  460.85
#Mann= 7 ,-1 , 0
  4079.9     .05       0  4627.1     .16       0  4995.3     .07       0
  5002.1     .16       0  5292.9     .05       0  5663.4     .16       0
  5771.7     .05       0
Bank Sta=4744,5210.2
XS Rating Curve= 0 ,0
Exp/Cntr=0.3,0.1

Type RM Length L Ch R = 1 ,6172    ,624,624,624
BEGIN DESCRIPTION:
UNT 036 IN DRY CR WATERSHED 10.0
END DESCRIPTION:
XS GIS Cut Line= 3
      2903625.04      7023125.03        2902925.        7022625.
      2902475.05      7022674.99
#Sta/Elev= 30
  4121.8   438.2  4129.2  439.05  4150.1  436.81  4215.2  434.78  4244.7  432.98
  4271.8  433.05  4301.3  430.59  4322.2   430.4  4351.7  428.41  4357.8  428.87
  4536.8  416.28  4565.1  415.11  4787.9  413.82  4873.9  413.91  4974.7  415.38
    4979  410.47  4984.6  410.47  4988.7   407.9  4989.2   407.1  4995.1   407.1
  4995.6   407.9  5012.3  413.35  5022.3  415.08  5082.7  414.99  5108.7  416.28
  5133.7   418.6  5243.7  427.02  5354.4  428.49  5394.6  430.29  5434.8  430.38
#Mann= 5 ,-1 , 0
  4121.8     .05       0  4565.1     .16       0  4988.7     .07       0
  4995.6     .16       0  5133.7     .05       0
Bank Sta=4536.8,5108.7
XS Rating Curve= 0 ,0
Exp/Cntr=0.3,0.1

Type RM Length L Ch R = 1 ,5548    ,522,522,522
BEGIN DESCRIPTION:
UNT 036 IN DRY CR WATERSHED 9.0
END DESCRIPTION:
XS GIS Cut Line= 3
      2903574.99        7022175.        2903125.        7022225.
        2902525.        7021675.
#Sta/Elev= 30
  4530.7  432.06  4621.2  432.67  4671.6   431.4    4742  426.55  4867.3  413.71
  4884.7  412.85  4973.4  411.69  4986.9  410.23  4987.1  405.51  4987.6  404.71
  4994.1  405.51  4997.3  405.56  5011.5  411.27  5018.9  412.71  5054.1   412.5
  5068.2  410.34  5089.8   412.5    5104  412.68  5167.5  411.77  5418.3  413.71
    5458  415.13  5471.8   414.3  5499.9  416.08  5528.2  419.31    5564  425.52
  5606.6  430.44  5670.1  435.09  5686.4  435.35  5755.2  439.92  5797.4  440.94
#Mann= 5 ,-1 , 0
  4530.7     .05       0  4884.7     .16       0  4987.1     .07       0
  4994.1     .16       0  5686.4     .05       0
Bank Sta=4867.3,5418.3
XS Rating Curve= 0 ,0
Exp/Cntr=0.3,0.1

Type RM Length L Ch R = 1 ,5026    ,548,548,548
BEGIN DESCRIPTION:
UNT 036 IN DRY CR WATERSHED 8.0
END DESCRIPTION:
XS GIS Cut Line= 3
      2903475.01      7022125.01        2903175.        7021775.
      2902574.96      7021624.99
#Sta/Elev= 30
  4506.9  432.25  4549.2  431.69  4677.6  426.49  4783.5  418.02  4811.5  414.01
  4836.9  411.97  4847.2  411.47  4925.6  411.04  4932.2  408.28  4939.9  410.33
  4946.5  406.07  4954.2  411.09  4970.5  410.86  4978.2  410.48  4985.9  407.99
  4991.1   408.8  4998.8  405.35  5005.5   403.8    5006     403  5012.8   403.8
  5027.2  411.08  5053.4  410.34  5091.6  409.52    5182  410.32  5246.2  410.55
  5274.2  411.97  5349.3  415.99  5378.7  420.08  5462.7  432.27  5586.4  440.01
#Mann= 7 ,-1 , 0
  4506.9     .05       0  4847.2     .16       0  5005.5     .07       0
  5012.8     .16       0  5053.4     .05       0    5182     .16       0
  5378.7     .05       0
Bank Sta=4836.9,5274.2
XS Rating Curve= 0 ,0
Exp/Cntr=0.3,0.1

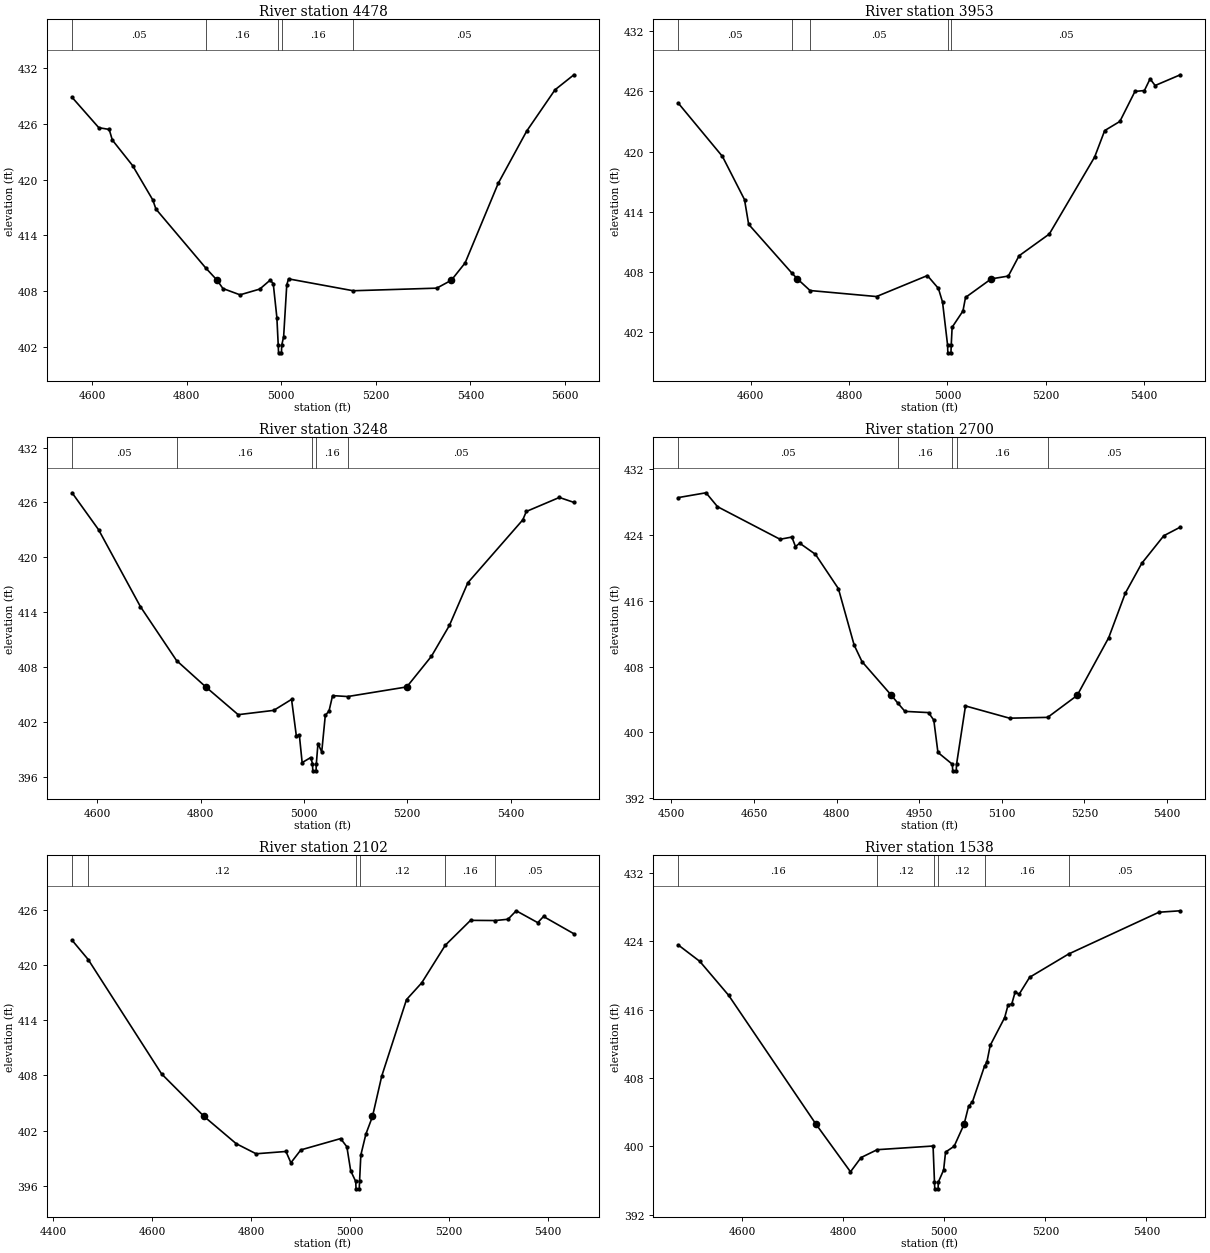
Type RM Length L Ch R = 1 ,4478    ,525,525,525
BEGIN DESCRIPTION:
UNT 036 IN DRY CR WATERSHED 7.0
END DESCRIPTION:
XS GIS Cut Line= 3
      2903775.01      7021675.01        2903425.        7021375.
      2902824.99        7021375.
#Sta/Elev= 30
  4557.7  428.88  4614.2  425.61  4636.2  425.42  4642.8  424.28  4685.6  421.53
  4728.4  417.82    4735  416.84  4840.2   410.5  4864.4  409.17  4876.6  408.28
  4912.8   407.6  4954.5  408.22  4976.4  409.18    4983  408.82  4990.7  405.15
  4993.6  402.15  4994.2  401.35  5000.4  401.35  5000.9  402.15    5005   403.1
  5011.6  408.68  5015.4  409.32    5152  408.04  5328.7  408.32  5359.5  409.17
  5388.7  411.04  5458.7  419.62  5518.7  425.23  5578.7  429.69  5618.7  431.31
#Mann= 5 ,-1 , 0
  4557.7     .05       0  4840.2     .16       0  4993.6     .07       0
  5000.9     .16       0    5152     .05       0
Bank Sta=4864.4,5359.5
XS Rating Curve= 0 ,0
Exp/Cntr=0.3,0.1

Type RM Length L Ch R = 1 ,3953    ,705,705,705
BEGIN DESCRIPTION:
UNT 036 IN DRY CR WATERSHED 6.0
END DESCRIPTION:
XS GIS Cut Line= 3
        2903975.        7021475.        2903725.        7020975.
        2903625.        7020525.
#Sta/Elev= 30
  4453.3  424.81  4542.7  419.52  4587.5  415.22  4595.9  412.76  4683.2  407.93
    4695  407.32  4720.7  406.16  4855.8  405.56  4959.2  407.65  4981.6  406.37
    4990  405.01  5000.2  400.75  5000.8  399.95  5007.1  399.95  5007.7  400.75
  5009.5   402.5  5031.5  404.12  5036.7  405.47  5088.9  407.32  5123.7   407.6
  5145.5  409.62    5207  411.79  5299.2  419.47  5319.6   422.1  5350.4  423.01
  5381.1     426  5400.3  426.09  5411.8  427.25  5422.1  426.59  5473.3  427.66
#Mann= 5 ,-1 , 0
  4453.3     .05       0  4683.2     .16       0  4720.7     .05       0
  5000.2     .03       0  5007.7     .05       0
Bank Sta=4695,5088.9
XS Rating Curve= 0 ,0
Exp/Cntr=0.3,0.1

Type RM Length L Ch R = 1 ,3248    ,548,548,548
BEGIN DESCRIPTION:
UNT 036 IN DRY CR WATERSHED 5.0
END DESCRIPTION:
XS GIS Cut Line= 3
        2904425.      7021074.99      2904204.61      7020684.26
      2903824.97      7020324.97
#Sta/Elev= 30
  4551.4  427.06  4602.7  423.03  4683.6  414.64  4753.6  408.75  4810.2  405.87
  4872.9  402.84  4941.7  403.31  4976.2  404.51  4985.5  400.51  4991.2  400.66
  4996.7  397.61  5013.2  398.16  5016.7  397.51  5017.3  396.71  5023.6  396.71
  5024.2  397.51  5027.3  399.69  5034.6  398.78  5041.5  402.76  5048.7  403.24
  5055.6  404.92  5084.9  404.82  5199.2  405.87    5247  409.22  5281.7  412.58
  5317.4  417.24  5423.7   424.1  5430.6  425.02  5494.5  426.55  5522.7  426.01
#Mann= 5 ,-1 , 0
  4551.4     .05       0  4753.6     .16       0  5016.7     .07       0
  5024.2     .16       0  5084.9     .05       0
Bank Sta=4810.2,5199.2
XS Rating Curve= 0 ,0
Exp/Cntr=0.3,0.1

Type RM Length L Ch R = 1 ,2700    ,598,598,598
BEGIN DESCRIPTION:
UNT 036 IN DRY CR WATERSHED 4.0
END DESCRIPTION:
XS GIS Cut Line= 3
      2904725.02      7020625.02        2904425.        7020275.
      2903975.01        7020275.
#Sta/Elev= 30
    4513  428.58    4563  429.16  4583.8  427.47  4697.4   423.5  4718.8  423.77
  4725.4  422.62  4733.1  423.02  4761.6  421.67  4803.3  417.49  4831.9  410.62
  4846.1  408.61  4899.7  404.49  4911.6  403.52  4924.1  402.55  4966.9   402.4
  4976.5  401.48    4984  397.55  5010.2  396.11  5010.8  395.31  5017.2  395.31
  5017.8  396.11    5034  403.21    5114  401.72  5183.2  401.82  5236.7  404.49
    5294  411.52    5324  416.92    5354  420.57    5394  423.93    5424  424.98
#Mann= 5 ,-1 , 0
    4513     .05       0  4911.6     .16       0  5010.2     .07       0
  5017.8     .16       0  5183.2     .05       0
Bank Sta=4899.7,5236.7
XS Rating Curve= 0 ,0
Exp/Cntr=0.3,0.1

Type RM Length L Ch R = 1 ,2102    ,564,564,564
BEGIN DESCRIPTION:
UNT 036 IN DRY CR WATERSHED 3.0
END DESCRIPTION:
XS GIS Cut Line= 3
      2905074.99        7019775.        2904525.        7019725.
      2904075.03      7019625.01
#Sta/Elev= 30
  4438.8  422.69  4471.4  420.59  4619.5  408.17  4705.4  403.54  4770.1  400.59
  4810.3  399.49  4870.6  399.74  4880.6  398.51  4900.7  399.91    4981  401.14
  4993.6  400.25  5001.3  397.64  5011.5  396.48  5012.1  395.68  5018.6  395.68
  5019.2  396.48  5021.8  399.35    5032  401.63  5045.3  403.54    5064  407.93
    5114  416.24  5144.7  418.06  5192.2  422.14  5243.3  424.85  5293.2  424.83
  5318.9  424.97  5335.5  425.89    5379   424.6  5390.6  425.27    5452  423.39
#Mann= 6 ,-1 , 0
  4438.8     .16       0  4471.4     .12       0  5011.5     .07       0
  5019.2     .12       0  5192.2     .16       0  5293.2     .05       0
Bank Sta=4705.4,5045.3
XS Rating Curve= 0 ,0
Exp/Cntr=0.3,0.1

Type RM Length L Ch R = 1 ,1538    ,458,458,458
BEGIN DESCRIPTION:
UNT 036 IN DRY CR WATERSHED 2.0
END DESCRIPTION:
XS GIS Cut Line= 3
      2905124.98      7019724.98        2904775.        7019325.
      2904424.96      7019024.97
#Sta/Elev= 30
  4474.4  423.55  4516.6  421.65  4573.6  417.68  4746.5  402.59  4814.6  397.03
  4835.5   398.7  4867.4  399.62  4977.9  400.05  4980.7  395.84  4981.3  395.04
  4987.8  395.04  4988.4  395.84  4998.8  397.25  5002.6  399.34  5019.6  400.02
  5039.2  402.59  5048.1  404.69  5055.8  405.22  5079.8  409.42  5084.4  409.87
  5090.9  411.82  5119.5  415.07  5126.1  416.52  5133.7   416.7  5140.3  418.08
    5148   417.8  5168.9  419.79  5245.9  422.51  5424.6   427.4  5466.9  427.57
#Mann= 6 ,-1 , 0
  4474.4     .16       0  4867.4     .12       0  4980.7     .07       0
  4988.4     .12       0  5079.8     .16       0  5245.9     .05       0
Bank Sta=4746.5,5039.2
XS Rating Curve= 0 ,0
Exp/Cntr=0.3,0.1

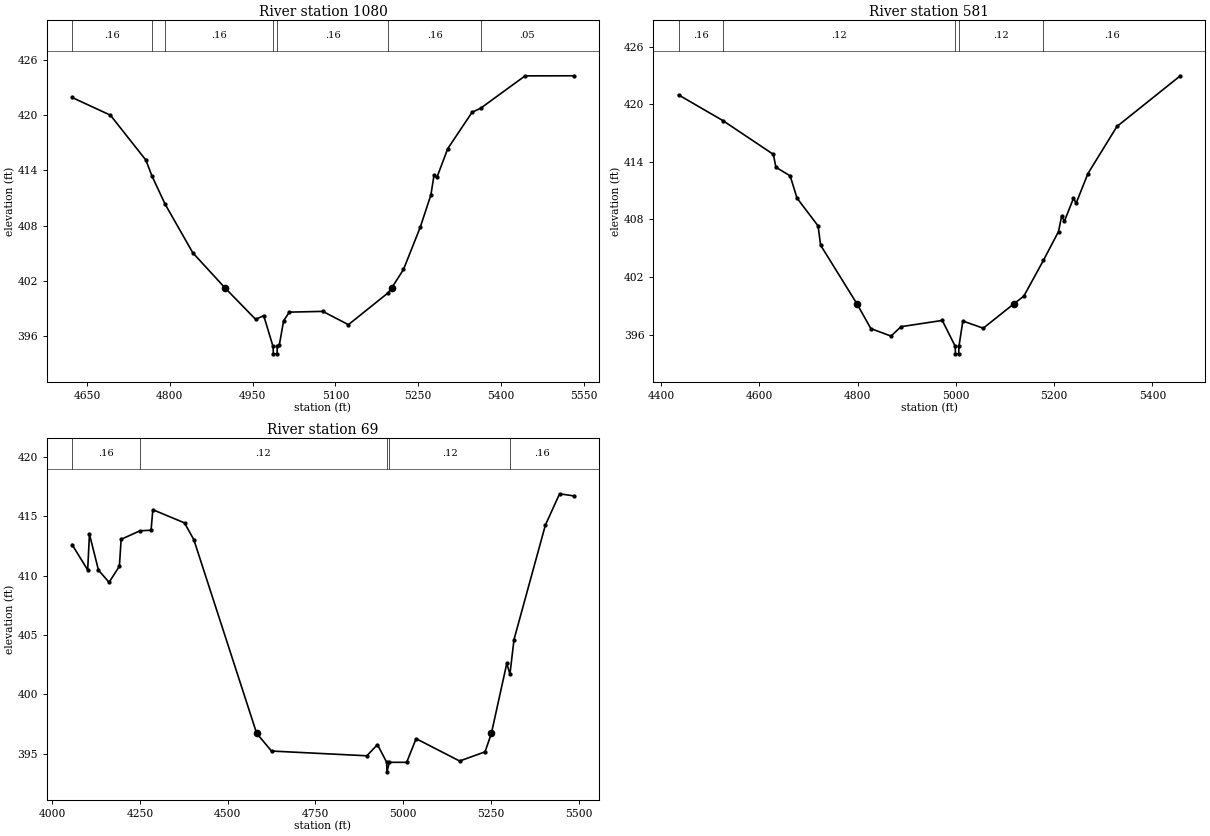
Type RM Length L Ch R = 1 ,1080    ,499,499,499
BEGIN DESCRIPTION:
Mapping XS 29915d53
END DESCRIPTION:
XS GIS Cut Line= 3
      2905313.97      7019423.25      2905084.82      7019129.01
       2904582.2       7018941.5
#Sta/Elev= 30
  4622.8  421.89  4692.3  419.97  4756.6   415.1  4767.4  413.41  4791.3  410.34
  4841.6  405.06  4899.7  401.27  4955.6  397.84  4970.1  398.25    4987  394.91
  4987.7  394.11  4994.2  394.11  4994.8  394.91  4998.3  395.04  5006.2  397.69
  5016.5  398.63  5077.2  398.71  5123.6  397.27    5196  400.74  5202.3  401.27
  5223.4  403.25  5253.7  407.81  5273.1  411.33  5278.7  413.44    5284  413.23
  5303.7  416.35  5347.8  420.29  5363.2  420.72  5443.8  424.23  5532.2  424.24
#Mann= 7 ,-1 , 0
  4622.8     .16       0  4767.4     .12       0  4791.3     .16       0
    4987     .07       0  4994.8     .16       0    5196     .16       0
  5363.2     .05       0
Bank Sta=4899.7,5202.3
XS Rating Curve= 0 ,0
Exp/Cntr=0.3,0.1

Type RM Length L Ch R = 1 ,581     ,512,512,512
BEGIN DESCRIPTION:
Mapping XS 0d14e8a6
END DESCRIPTION:
XS GIS Cut Line= 3
      2905363.46      7019256.59      2905243.68      7018733.18
      2904795.78      7018548.29
#Sta/Elev= 30
  4435.3  420.97  4525.6  418.29  4628.4  414.77  4633.5  413.43  4662.6  412.53
  4676.5  410.21  4719.4  407.32  4724.5  405.31  4798.8  399.18  4826.8  396.62
  4867.8  395.84  4888.3  396.82  4972.2  397.47  4998.4  394.79  4999.1  393.99
  5005.6  393.99  5006.2  394.79  5014.1  397.41  5055.6  396.66  5117.4  399.18
  5138.2     400  5178.1  403.73  5208.8  406.73  5215.3  408.37  5220.7  407.79
  5239.3   410.2  5244.7  409.68  5268.6  412.76  5327.8  417.68  5456.8  422.96
#Mann= 5 ,-1 , 0
  4435.3     .16       0  4525.6     .12       0  4998.4     .07       0
  5006.2     .12       0  5178.1     .16       0
Bank Sta=4798.8,5117.4
XS Rating Curve= 0 ,0
Exp/Cntr=0.3,0.1

Type RM Length L Ch R = 1 ,69      ,0,0,0
BEGIN DESCRIPTION:
UNT 036 IN DRY CR WATERSHED 1.0
END DESCRIPTION:
XS GIS Cut Line= 3
      2905475.44      7019209.71      2905370.68      7018272.24
      2904899.99        7018150.
#Sta/Elev= 30
  4056.7  412.61  4101.2  410.47  4106.2  413.48  4131.9  410.46  4162.1  409.43
  4191.5  410.78  4196.5  413.05  4249.8  413.76  4281.8  413.82  4286.8  415.54
  4377.1  414.43  4403.6  413.02  4582.6  396.73  4624.9  395.24  4896.6  394.84
  4926.8  395.78  4953.1  394.29  4953.7  393.49  4960.9  394.29    5010  394.29
  5036.9  396.28  5160.8   394.4  5233.2  395.17  5251.4  396.73  5295.2  402.61
  5304.2  401.71  5315.8  404.62  5405.2  414.25  5445.7  416.88  5486.3   416.7
#Mann= 5 ,-1 , 0
  4056.7     .16       0  4249.8     .12       0  4953.1     .07       0
  4960.9     .12       0  5304.2     .16       0
Bank Sta=4582.6,5251.4
XS Rating Curve= 0 ,0
Exp/Cntr=0.3,0.1
LCMann Table=0

Chan Stop Cuts=-1
Use User Specified Reach Order=0
Composite Channel Slope=5