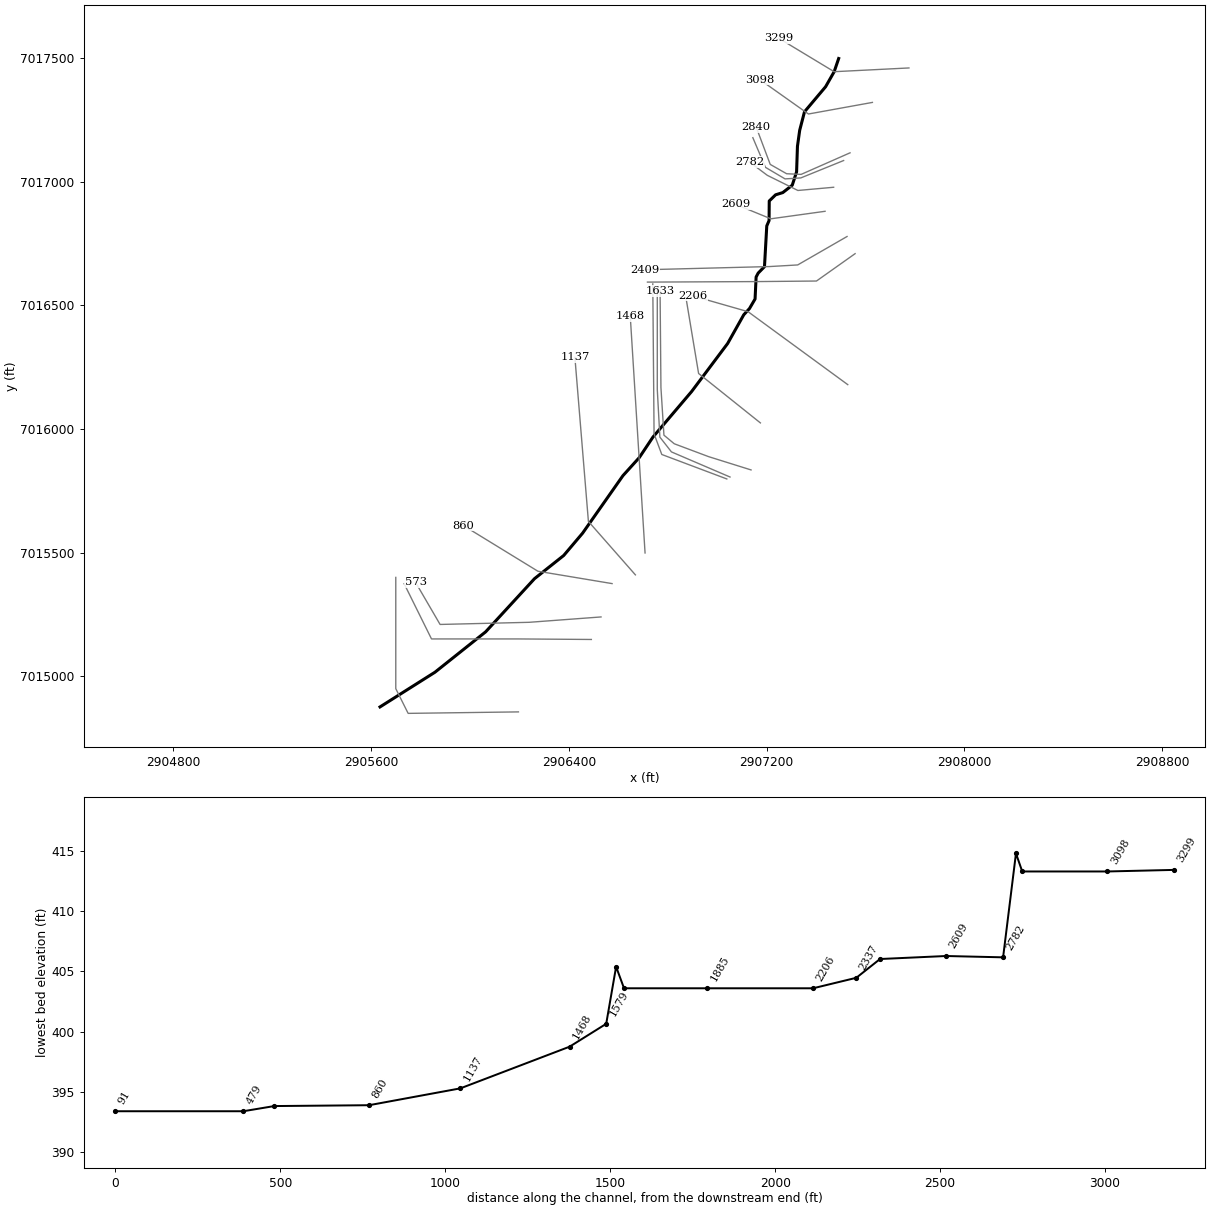
--- UNT 037 IN DRY CR WATERSHED.prj (project) ---

Proj Title=UNT 037 IN DRY CR WATERSHED Base Level Engineering
Current Plan=p01
Default Exp/Contr=0.3,0.1
English Units
Geom File=g01
Flow File=f01
Plan File=p01
BEGIN DESCRIPTION:
UNT 037 IN DRY CR WATERSHED
END DESCRIPTION:

--- UNT 037 IN DRY CR WATERSHED.p01 (plan) ---

Plan Title=Multiple Run
Short Identifier=Multiple
Geom File=g01
Flow File=f01
Subcritical Flow
K Sum by GR= 0
Std Step Tol= 0.01
Critical Tol= 0.01
Num of Std Step Trials= 20
Max Error Tol= 0.3
Flow Tol Ratio= 0.001
Split Flow NTrial= 30
Split Flow Tol= 0.02
Split Flow Ratio= 0.02
Log Output Level= 0
Friction Slope Method= 1
Unsteady Friction Slope Method= 2
Unsteady Bridges Friction Slope Method= 1
Parabolic Critical Depth
Global Vel Dist=  1 , 1 , 1
Global Log Level= 0
CheckData=True
Encroach Param= -1, 0, 0, 0
BEGIN DESCRIPTION:
Multiple Run
END DESCRIPTION:

--- UNT 037 IN DRY CR WATERSHED.f01 (steady flow) ---

Flow Title=Multiple
Number of Profiles=7
Profile Names=10-year,25-year,50-year,1pct_min,100-year,1pct_plu,500-year
River Rch & RM= UNT 037 IN DRY C,Reach-1,3299
     176     217     248     141     282     563     364
Boundary for River Rch & Prof#=UNT 037 IN DRY C,Reach-1,1
Up Type=0
Dn Type=3
Dn Slope=0.005
Boundary for River Rch & Prof#=UNT 037 IN DRY C,Reach-1,2
Up Type=0
Dn Type=3
Dn Slope=0.005
Boundary for River Rch & Prof#=UNT 037 IN DRY C,Reach-1,3
Up Type=0
Dn Type=3
Dn Slope=0.005
Boundary for River Rch & Prof#=UNT 037 IN DRY C,Reach-1,4
Up Type=0
Dn Type=3
Dn Slope=0.005
Boundary for River Rch & Prof#=UNT 037 IN DRY C,Reach-1,5
Up Type=0
Dn Type=3
Dn Slope=0.005
Boundary for River Rch & Prof#=UNT 037 IN DRY C,Reach-1,6
Up Type=0
Dn Type=3
Dn Slope=0.005
Boundary for River Rch & Prof#=UNT 037 IN DRY C,Reach-1,7
Up Type=0
Dn Type=3
Dn Slope=0.005

--- UNT 037 IN DRY CR WATERSHED.g01 (geometry) ---

Geom Title=Existing Conditions

River Reach=UNT 037 IN DRY C,Reach-1
Reach XY= 30
      2907491.64      7017499.15      2907473.41      7017445.77
      2907438.77      7017384.97      2907353.36      7017283.58
      2907333.91      7017208.58      2907324.89      7017144.00
      2907321.41      7017040.52      2907303.83      7016986.63
      2907265.63      7016956.77      2907236.47      7016947.75
      2907210.77      7016922.75      2907210.08      7016843.58
      2907200.77      7016821.94      2907191.51      7016657.14
      2907166.00      7016631.10      2907157.65      7016615.09
      2907153.44      7016526.36      2907130.87      7016487.69
      2907107.69      7016462.46      2907042.55      7016346.37
      2906896.71      7016151.93      2906740.46      7015967.90
      2906684.91      7015884.56      2906618.94      7015811.65
      2906455.74      7015579.01      2906379.35      7015488.73
      2906261.30      7015394.98      2906063.38      7015179.70
      2905858.52      7015016.51      2905636.20      7014876.10

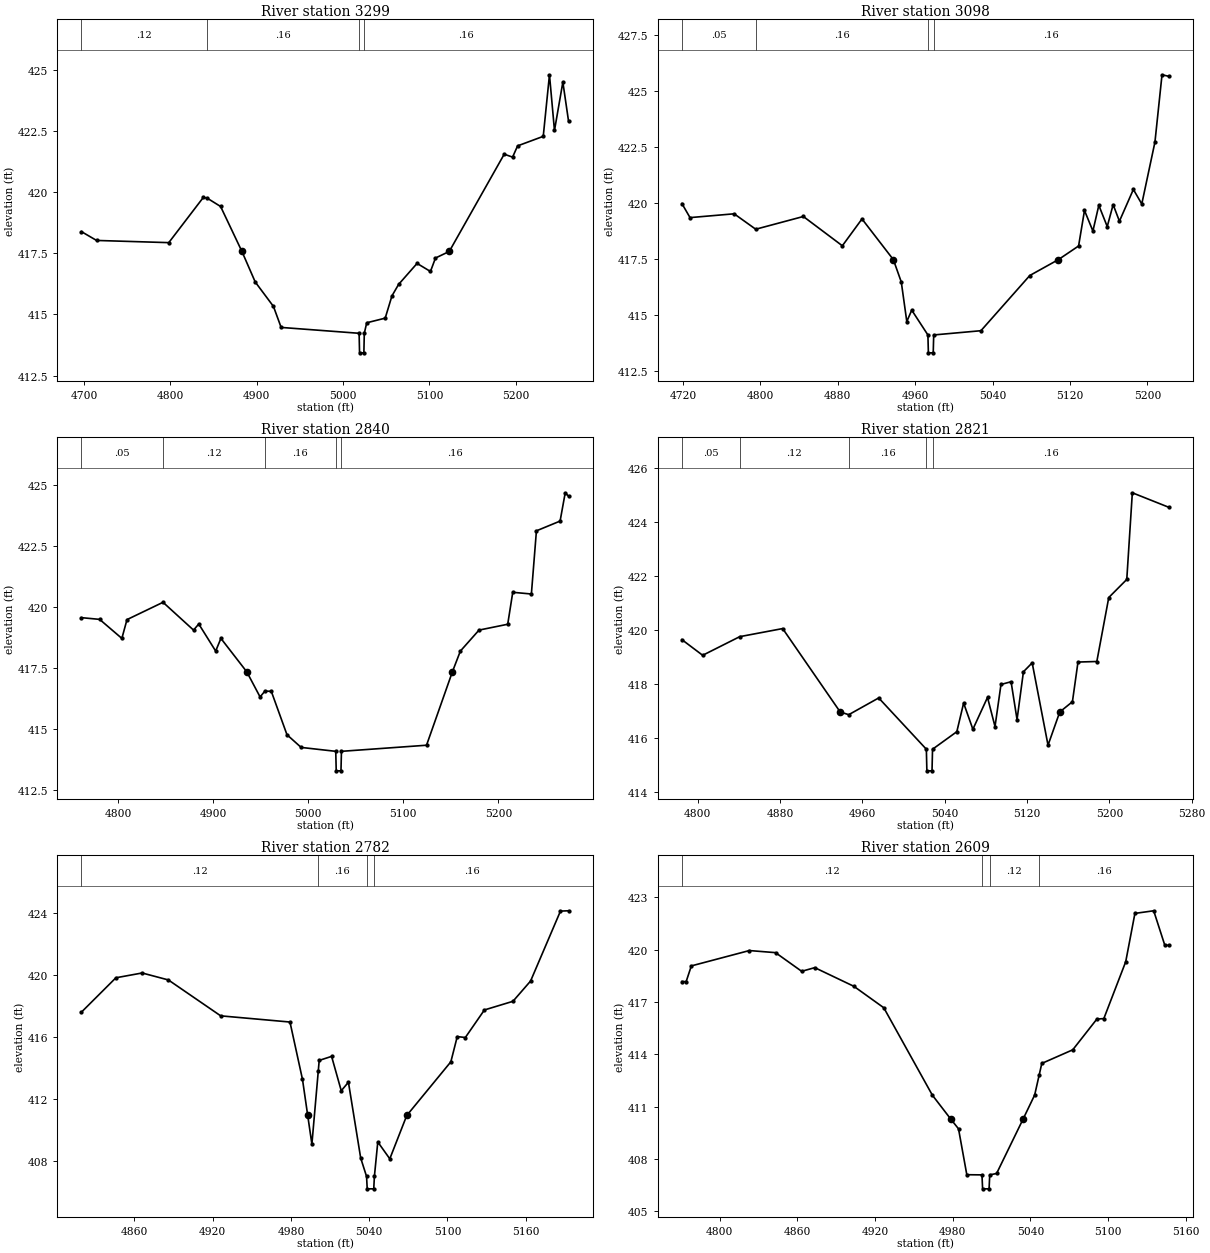
Type RM Length L Ch R = 1,3299,201,201,201
BEGIN DESCRIPTION:
UNT 037 IN DRY CR WATERSHED 1.0
END DESCRIPTION:
XS GIS Cut Line= 3
      2907775.93      7017460.96      2907473.41      7017445.77
      2907249.91      7017580.76
#Sta/Elev= 30
  4697.1  418.39  4714.6  418.03  4798.2  417.94  4838.2  419.79  4842.7  419.76
  4858.2  419.42  4882.9  417.58  4898.3  416.33  4919.4  415.33  4928.3  414.47
  5018.6  414.23  5019.1  413.43  5024.1  413.43  5024.6  414.23  5027.4  414.66
  5048.8  414.85  5056.6  415.76  5064.3  416.23  5085.7  417.09  5101.2  416.76
  5107.0  417.31  5123.0  417.58  5186.6  421.56  5196.3  421.44  5202.1  421.90
  5231.8  422.29  5239.0  424.81  5244.8  422.53  5254.5  424.51  5261.1  422.91
#Mann=4,-1,0
  4697.1    0.12       0  4842.7    0.16       0  5018.6    0.07       0
  5024.6    0.16       0
Bank Sta=4882.9,5123
Exp/Cntr=0.3,0.1

Type RM Length L Ch R = 1,3098,258,258,258
BEGIN DESCRIPTION:
Mapping XS 23201800
END DESCRIPTION:
XS GIS Cut Line= 3
      2907628.10      7017321.53      2907369.39      7017274.65
      2907173.20      7017413.55
#Sta/Elev= 30
  4719.0  419.98  4727.4  419.35  4773.0  419.52  4795.3  418.83  4844.5  419.40
  4884.8  418.09  4905.1  419.29  4937.5  417.47  4945.7  416.47  4951.4  414.70
  4956.5  415.21  4973.2  414.10  4973.7  413.30  4978.7  413.30  4979.2  414.10
  5028.0  414.29  5078.5  416.76  5108.0  417.47  5128.9  418.08  5135.0  419.67
  5143.7  418.75  5149.8  419.90  5158.5  418.95  5164.6  419.93  5171.1  419.19
  5185.5  420.61  5194.2  419.96  5207.8  422.73  5215.1  425.74  5222.3  425.67
#Mann=4,-1,0
  4719.0    0.05       0  4795.3    0.16       0  4973.2    0.07       0
  4979.2    0.16       0
Bank Sta=4937.5,5108
Exp/Cntr=0.3,0.1

Type RM Length L Ch R = 1,2840,19,19,19
BEGIN DESCRIPTION:
Mapping XS c8163554
END DESCRIPTION:
XS GIS Cut Line= 5
      2907537.69      7017117.65      2907339.77      7017030.40
      2907281.17      7017033.01      2907214.77      7017070.77
      2907158.08      7017221.52
#Sta/Elev= 30
  4761.4  419.58  4780.5  419.51  4803.9  418.73  4809.3  419.50  4847.2  420.21
  4879.3  419.07  4884.8  419.32  4902.6  418.21  4908.1  418.73  4935.3  417.36
  4949.3  416.33  4954.4  416.57  4961.1  416.56  4977.6  414.78  4992.5  414.26
  5028.9  414.10  5029.4  413.30  5034.4  413.30  5034.9  414.10  5124.4  414.35
  5151.6  417.36  5160.0  418.21  5179.6  419.07  5209.8  419.31  5215.1  420.62
  5234.7  420.55  5240.0  423.14  5264.9  423.54  5270.3  424.70  5273.8  424.56
#Mann=5,-1,0
  4761.4    0.05       0  4847.2    0.12       0  4954.4    0.16       0
  5028.9    0.07       0  5034.9    0.16       0
Bank Sta=4935.3,5151.6
Exp/Cntr=0.3,0.1

Type RM Length L Ch R = 1,2821,39,39,39
BEGIN DESCRIPTION:
Mapping XS a135a7b8
END DESCRIPTION:
XS GIS Cut Line= 5
      2907511.67      7017086.41      2907338.47      7017016.08
      2907274.66      7017012.17      2907195.24      7017059.05
      2907144.46      7017178.84
#Sta/Elev= 30
  4784.7  419.66  4804.9  419.08  4840.9  419.77  4882.6  420.07  4938.5  416.98
  4946.8  416.88  4975.9  417.50  5022.2  415.60  5022.7  414.80  5027.7  414.80
  5028.2  415.60  5051.8  416.25  5058.4  417.31  5067.4  416.34  5081.6  417.52
  5088.9  416.44  5094.7  418.00  5104.5  418.10  5110.3  416.70  5116.5  418.47
  5125.0  418.80  5140.4  415.75  5151.8  416.98  5164.1  417.36  5169.5  418.83
  5187.8  418.85  5199.4  421.22  5216.9  421.89  5222.3  425.10  5257.9  424.56
#Mann=5,-1,0
  4784.7    0.05       0  4840.9    0.12       0  4946.8    0.16       0
  5022.2    0.07       0  5028.2    0.16       0
Bank Sta=4938.5,5151.8
Exp/Cntr=0.3,0.1

Type RM Length L Ch R = 1,2782,173,173,173
BEGIN DESCRIPTION:
Mapping XS e8232930
END DESCRIPTION:
XS GIS Cut Line= 4
      2907471.29      7016978.32      2907326.75      7016965.30
      2907203.05      7017026.50      2907130.92      7017080.60
#Sta/Elev= 30
  4819.5  417.59  4845.9  419.81  4866.0  420.12  4886.1  419.67  4926.2  417.35
  4979.3  416.95  4988.9  413.24  4992.9  410.91  4996.1  409.06  5001.0  413.79
  5001.7  414.47  5011.2  414.73  5018.6  412.51  5024.1  413.06  5033.5  408.16
  5038.0  406.97  5038.5  406.17  5043.5  406.17  5044.0  406.97  5046.6  409.20
  5055.8  408.11  5068.8  410.91  5102.6  414.38  5107.5  416.01  5113.7  415.95
  5128.3  417.73  5150.2  418.29  5163.7  419.60  5186.6  424.12  5192.8  424.14
#Mann=4,-1,0
  4819.5    0.12       0  5001.0    0.16       0  5038.0    0.07       0
  5044.0    0.16       0
Bank Sta=4992.9,5068.8
Exp/Cntr=0.3,0.1

Type RM Length L Ch R = 1,2609,200,200,200
BEGIN DESCRIPTION:
Mapping XS a14a6f3a
END DESCRIPTION:
XS GIS Cut Line= 3
      2907436.59      7016881.10      2907217.37      7016850.72
      2907074.11      7016909.32
#Sta/Elev= 30
  4770.9  418.16  4774.2  418.16  4778.2  419.06  4823.0  419.94  4843.2  419.82
  4863.4  418.75  4873.5  418.96  4903.7  417.89  4926.8  416.66  4964.3  411.65
  4978.6  410.27  4984.5  409.72  4990.9  407.09  5002.6  407.08  5003.1  406.28
  5008.1  406.28  5008.6  407.08  5013.9  407.16  5034.3  410.27  5043.3  411.66
  5046.7  412.78  5048.8  413.47  5072.7  414.25  5091.3  416.01  5096.7  416.04
  5113.6  419.30  5120.7  422.07  5135.2  422.22  5143.8  420.24  5147.0  420.24
#Mann=4,-1,0
  4770.9    0.12       0  5002.6    0.07       0  5008.6    0.12       0
  5046.7    0.16       0
Bank Sta=4978.6,5034.3
Exp/Cntr=0.3,0.1

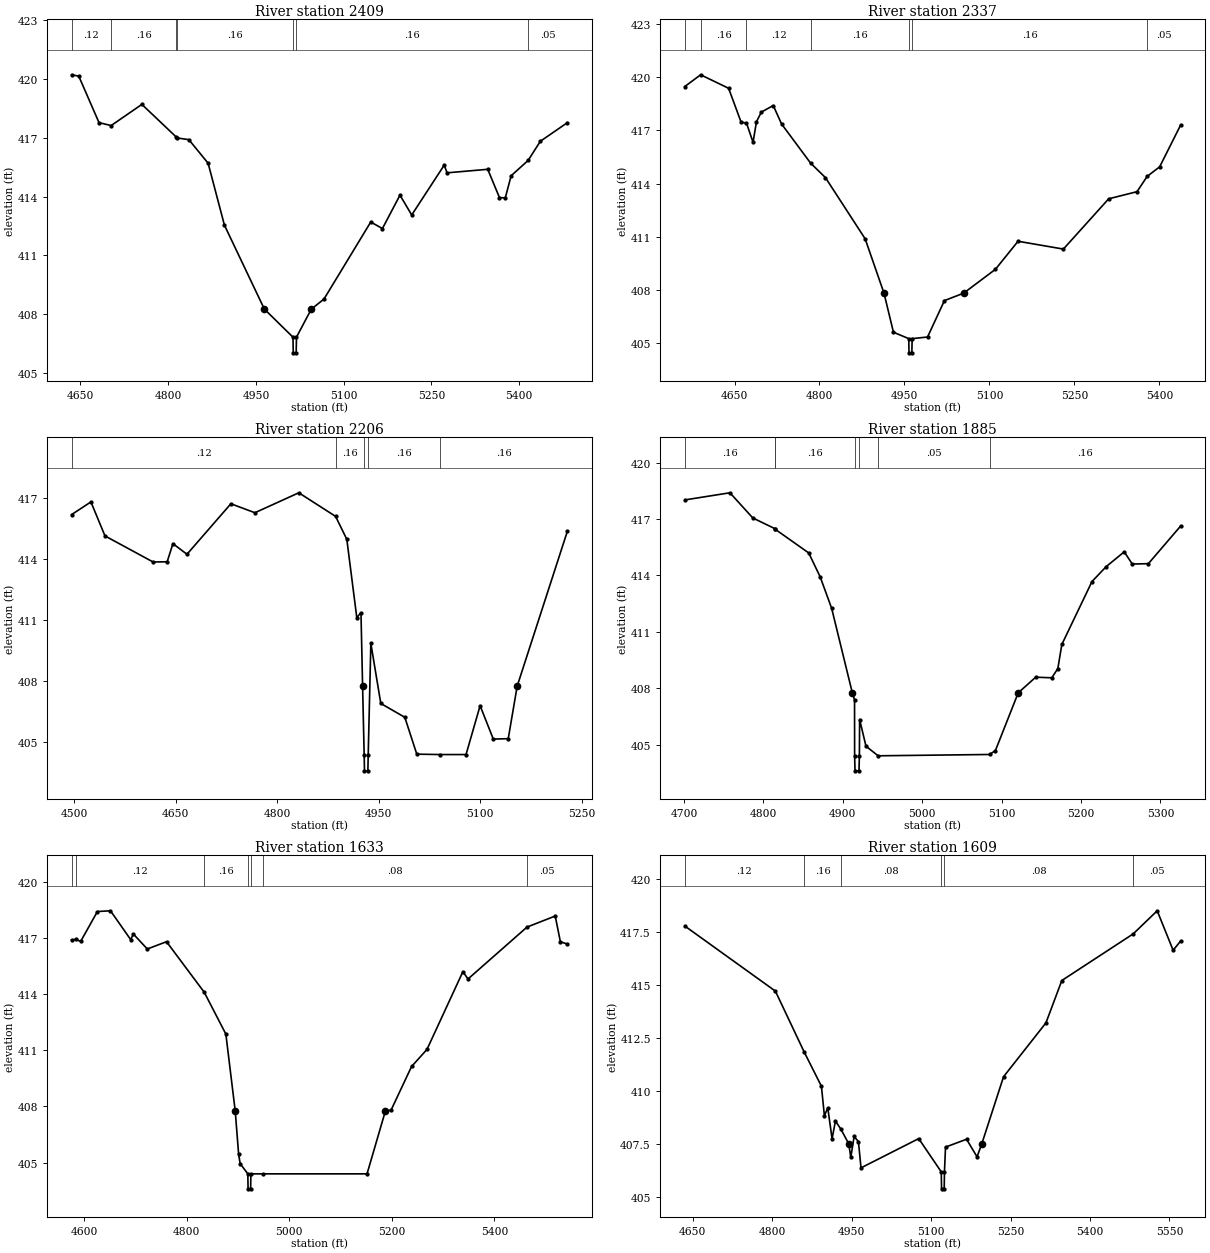
Type RM Length L Ch R = 1,2409,72,72,72
BEGIN DESCRIPTION:
Mapping XS abc99ca5
END DESCRIPTION:
XS GIS Cut Line= 4
      2907525.53      7016779.10      2907325.88      7016664.08
      2907213.03      7016657.57      2906708.74      7016644.59
#Sta/Elev= 30
  4634.9  420.21  4647.1  420.14  4681.7  417.77  4702.5  417.62  4755.0  418.70
  4814.0  417.03  4815.3  416.99  4835.4  416.90  4868.3  415.70  4896.2  412.54
  4964.5  408.26  5013.4  406.83  5013.9  406.03  5018.9  406.03  5019.4  406.83
  5044.8  408.26  5066.4  408.77  5146.4  412.70  5166.4  412.37  5196.4  414.07
  5216.5  413.06  5272.0  415.60  5277.0  415.21  5346.5  415.39  5366.5  413.95
  5376.5  413.93  5386.5  415.06  5415.5  415.84  5436.5  416.82  5482.8  417.77
#Mann=7,-1,0
  4634.9    0.12       0  4702.5    0.16       0  4814.0    0.12       0
  4815.3    0.16       0  5013.4    0.07       0  5019.4    0.16       0
  5415.5    0.05       0
Bank Sta=4964.5,5044.8
Exp/Cntr=0.3,0.1

Type RM Length L Ch R = 1,2337,131,131,131
BEGIN DESCRIPTION:
Mapping XS 9f9cc1ef
END DESCRIPTION:
XS GIS Cut Line= 4
      2907558.10      7016709.67      2907401.83      7016598.98
      2907169.63      7016596.81      2906718.04      7016594.65
#Sta/Elev= 30
  4562.3  419.46  4590.2  420.12  4639.6  419.36  4661.8  417.44  4671.1  417.41
  4682.7  416.32  4688.8  417.48  4697.4  418.02  4718.4  418.39  4733.1  417.35
  4784.3  415.15  4810.6  414.33  4880.6  410.89  4913.9  407.83  4930.6  405.63
  4957.6  405.27  4958.1  404.47  4963.1  404.47  4963.6  405.27  4990.8  405.36
  5020.6  407.41  5054.6  407.83  5110.6  409.17  5150.6  410.75  5230.6  410.31
  5310.6  413.14  5360.6  413.54  5378.5  414.40  5400.6  414.94  5437.6  417.29
#Mann=7,-1,0
  4562.3    0.12       0  4590.2    0.16       0  4671.1    0.12       0
  4784.3    0.16       0  4957.6    0.07       0  4963.6    0.16       0
  5378.5    0.05       0
Bank Sta=4913.9,5054.6
Exp/Cntr=0.3,0.1

Type RM Length L Ch R = 1,2206,321,321,321
BEGIN DESCRIPTION:
UNT 037 IN DRY CR WATERSHED 2.0
END DESCRIPTION:
XS GIS Cut Line= 3
      2907528.38      7016179.85      2907125.00      7016475.00
      2906900.92      7016539.10
#Sta/Elev= 30
  4496.0  416.19  4524.5  416.81  4545.3  415.14  4616.4  413.86  4637.2  413.87
  4645.7  414.76  4666.5  414.24  4731.4  416.72  4766.9  416.28  4831.8  417.26
  4886.2  416.10  4902.8  414.97  4917.5  411.13  4923.7  411.37  4926.1  407.76
  4928.4  404.40  4928.9  403.60  4933.9  403.60  4934.4  404.40  4938.3  409.86
  4953.0  406.91  4988.5  406.23  5006.2  404.42  5040.5  404.40  5079.0  404.40
  5099.8  406.80  5119.3  405.16  5141.4  405.18  5154.6  407.76  5228.9  415.38
#Mann=5,-1,0
  4496.0    0.12       0  4886.2    0.16       0  4928.4   0.033       0
  4934.4    0.16       0  5040.5    0.16       0
Bank Sta=4926.1,5154.6
Exp/Cntr=0.3,0.1

Type RM Length L Ch R = 1,1885,252,252,252
BEGIN DESCRIPTION:
UNT 037 IN DRY CR WATERSHED 3.0
END DESCRIPTION:
XS GIS Cut Line= 3
      2907174.98      7016025.02      2906925.00      7016225.00
      2906874.99      7016525.04
#Sta/Elev= 30
  4701.1  418.01  4757.9  418.39  4786.7  417.05  4814.6  416.48  4815.2  416.44
  4857.1  415.19  4871.6  413.91  4886.0  412.24  4912.0  407.75  4914.8  407.37
  4914.9  404.40  4915.4  403.60  4920.4  403.60  4920.9  404.40  4921.2  406.33
  4929.2  404.91  4944.5  404.40  5084.8  404.47  5092.2  404.68  5120.9  407.75
  5142.9  408.58  5163.2  408.55  5170.8  409.04  5175.8  410.32  5213.8  413.67
  5231.6  414.46  5254.4  415.25  5264.5  414.60  5284.8  414.62  5325.4  416.62
#Mann=7,-1,0
  4701.1    0.16       0  4814.6    0.12       0  4815.2    0.16       0
  4914.9   0.033       0  4920.9    0.16       0  4944.5    0.05       0
  5084.8    0.16       0
Bank Sta=4912,5120.9
Exp/Cntr=0.3,0.1

Type RM Length L Ch R = 1,1633,24,24,24
BEGIN DESCRIPTION:
Mapping XS 30808afa
END DESCRIPTION:
XS GIS Cut Line= 6
      2907137.21      7015834.81      2906965.35      7015888.62
      2906826.46      7015940.70      2906784.79      7015975.43
      2906772.64      7016168.13      2906769.17      7016558.77
#Sta/Elev= 30
  4576.1  416.88  4583.7  416.91  4593.8  416.81  4626.3  418.40  4651.8  418.44
  4691.2  416.90  4696.4  417.20  4723.6  416.40  4761.0  416.79  4834.6  414.09
  4876.7  411.86  4895.0  407.74  4901.6  405.44  4904.5  404.95  4919.5  404.40
  4920.0  403.60  4925.0  403.60  4925.5  404.40  4949.8  404.40  5151.9  404.40
  5187.5  407.74  5198.7  407.80  5238.7  410.13  5268.7  411.04  5338.7  415.19
  5348.7  414.80  5463.7  417.57  5518.7  418.16  5528.7  416.79  5542.5  416.66
#Mann=7,-1,0
  4576.1    0.16       0  4583.7    0.12       0  4834.6    0.16       0
  4919.5    0.07       0  4925.5    0.16       0  4949.8    0.08       0
  5463.7    0.05       0
Bank Sta=4895,5187.5
Exp/Cntr=0.3,0.1

Type RM Length L Ch R = 1,1609,30,30,30
BEGIN DESCRIPTION:
Mapping XS ad5db651
END DESCRIPTION:
XS GIS Cut Line= 5
      2907052.11      7015806.17      2906815.17      7015907.72
      2906768.30      7015967.61      2906757.88      7016160.32
      2906757.88      7016569.19
#Sta/Elev= 30
  4635.3  417.79  4806.2  414.72  4860.1  411.87  4893.1  410.23  4898.7  408.84
  4905.1  409.21  4913.2  407.75  4919.5  408.59  4930.0  408.20  4944.7  407.51
  4948.5  406.87  4954.8  407.86  4962.9  407.62  4967.8  406.38  5076.7  407.76
  5119.3  406.19  5119.8  405.39  5124.8  405.39  5125.3  406.19  5127.3  407.36
  5167.0  407.73  5186.8  406.90  5195.7  407.51  5236.8  410.68  5316.8  413.22
  5346.8  415.22  5481.5  417.42  5526.8  418.51  5556.8  416.65  5571.0  417.08
#Mann=6,-1,0
  4635.3    0.12       0  4860.1    0.16       0  4930.0    0.08       0
  5119.3    0.07       0  5125.3    0.08       0  5481.5    0.05       0
Bank Sta=4944.7,5195.7
Exp/Cntr=0.3,0.1

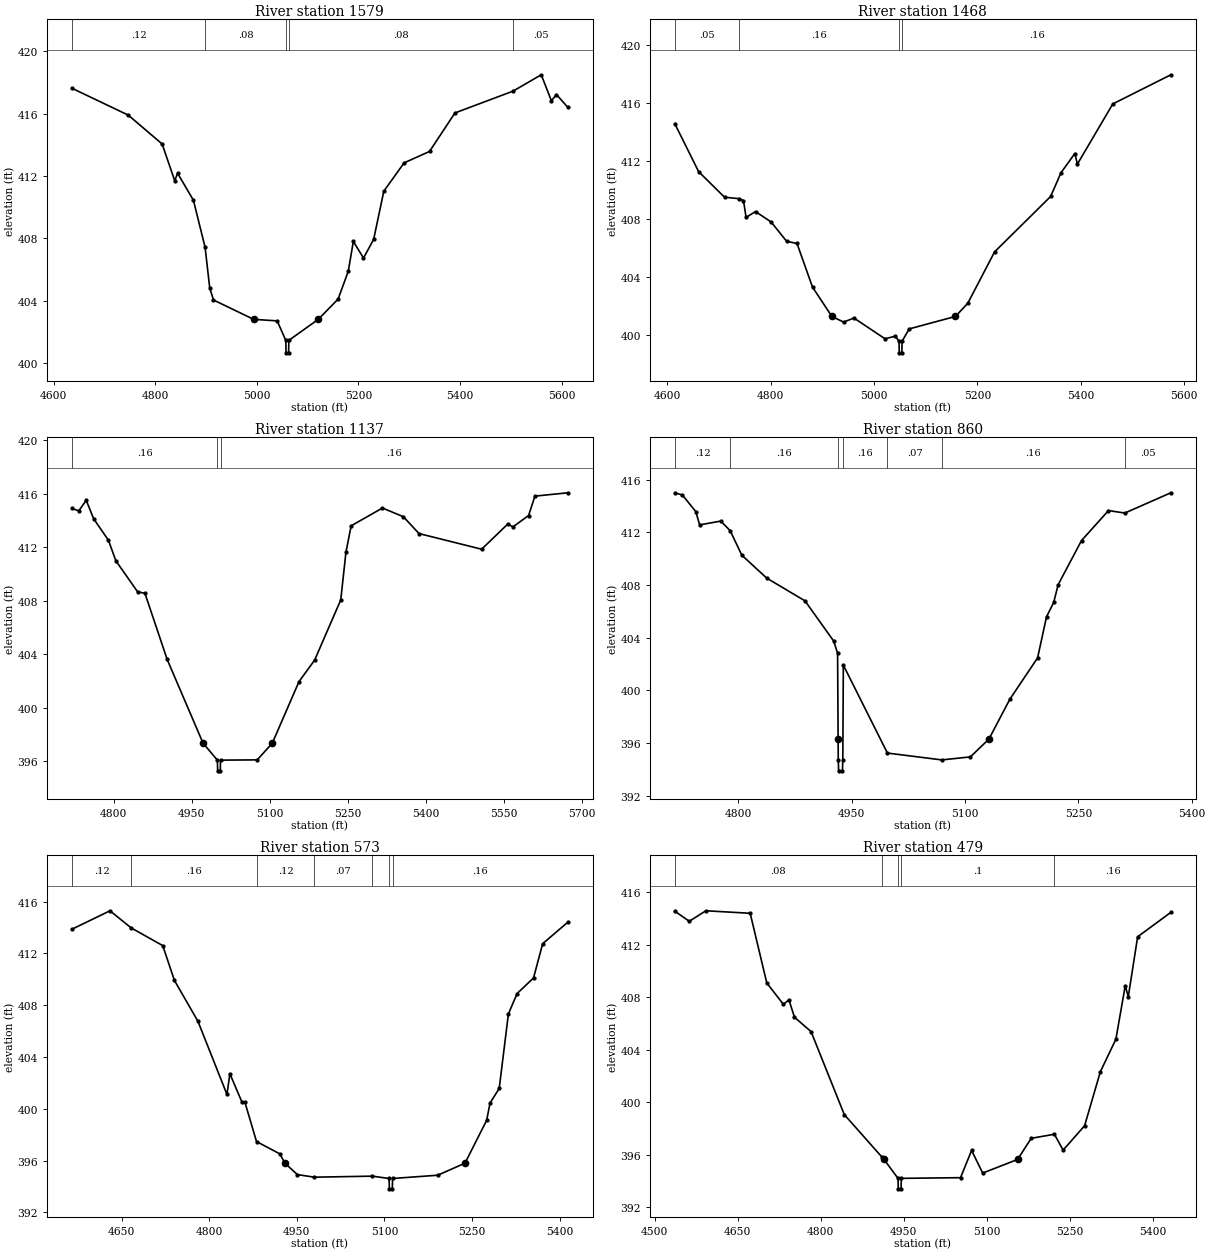
Type RM Length L Ch R = 1,1579,111,111,111
BEGIN DESCRIPTION:
Mapping XS 2b60f381
END DESCRIPTION:
XS GIS Cut Line= 4
      2907039.16      7015798.33      2906776.11      7015897.30
      2906744.86      7015980.63      2906739.65      7016587.36
#Sta/Elev= 30
  4635.6  417.63  4746.9  415.90  4813.5  414.05  4838.4  411.68  4843.8  412.18
  4875.1  410.44  4898.1  407.42  4907.2  404.82  4914.6  404.04  4993.6  402.80
  5040.0  402.70  5057.0  401.45  5057.5  400.65  5062.5  400.65  5063.0  401.45
  5121.0  402.80  5160.0  404.10  5180.0  405.88  5190.0  407.80  5210.0  406.73
  5230.0  407.93  5250.0  411.02  5290.0  412.84  5340.0  413.57  5390.0  416.04
  5504.4  417.44  5560.0  418.49  5580.0  416.82  5590.0  417.22  5612.4  416.40
#Mann=5,-1,0
  4635.6    0.12       0  4898.1    0.08       0  5057.0    0.07       0
  5063.0    0.08       0  5504.4    0.05       0
Bank Sta=4993.6,5121
Exp/Cntr=0.3,0.1

Type RM Length L Ch R = 1,1468,331,331,331
BEGIN DESCRIPTION:
Mapping XS ad30bb39
END DESCRIPTION:
XS GIS Cut Line= 3
      2906708.40      7015498.88      2906687.57      7015832.20
      2906648.51      7016457.21
#Sta/Elev= 30
  4614.2  414.55  4660.4  411.24  4710.5  409.48  4738.2  409.38  4747.2  409.25
  4752.2  408.09  4770.6  408.49  4800.7  407.77  4830.7  406.44  4850.8  406.29
  4880.8  403.28  4918.3  401.26  4941.0  400.87  4961.0  401.15  5021.1  399.72
  5041.1  399.90  5048.2  399.55  5048.7  398.75  5053.7  398.75  5054.2  399.55
  5067.9  400.40  5157.5  401.26  5181.4  402.17  5233.2  405.71  5341.7  409.53
  5361.8  411.17  5388.5  412.49  5393.5  411.76  5462.0  415.91  5574.4  417.92
#Mann=4,-1,0
  4614.2    0.05       0  4738.2    0.16       0  5048.2    0.07       0
  5054.2    0.16       0
Bank Sta=4918.3,5157.5
Exp/Cntr=0.3,0.1

Type RM Length L Ch R = 1,1137,277,277,277
BEGIN DESCRIPTION:
Mapping XS b2ddebba
END DESCRIPTION:
XS GIS Cut Line= 3
      2906669.35      7015410.31      2906479.24      7015626.47
      2906424.57      7016290.25
#Sta/Elev= 30
  4719.5  414.91  4733.0  414.73  4747.3  415.52  4761.5  414.14  4790.0  412.53
  4804.2  411.00  4846.0  408.68  4860.2  408.56  4902.9  403.62  4971.9  397.36
  4999.5  396.09  5000.0  395.29  5005.0  395.29  5005.5  396.09  5076.1  396.11
  5105.1  397.36  5156.4  401.96  5186.5  403.57  5236.7  408.07  5246.7  411.64
  5256.7  413.61  5316.9  414.94  5357.1  414.29  5387.2  413.03  5507.6  411.86
  5557.8  413.74  5567.8  413.53  5597.9  414.38  5610.1  415.83  5673.4  416.08
#Mann=3,-1,0
  4719.5    0.16       0  4999.5    0.07       0  5005.5    0.16       0
Bank Sta=4971.9,5105.1
Exp/Cntr=0.3,0.1

Type RM Length L Ch R = 1,860,287,287,287
BEGIN DESCRIPTION:
UNT 037 IN DRY CR WATERSHED 6.0
END DESCRIPTION:
XS GIS Cut Line= 3
      2906574.96      7015375.01      2906275.00      7015425.00
      2905974.70      7015609.03
#Sta/Elev= 30
  4716.1  415.01  4726.2  414.84  4743.9  413.58  4749.0  412.57  4776.9  412.86
  4789.3  412.14  4804.8  410.27  4837.7  408.53  4888.4  406.80  4926.4  403.74
  4931.5  402.82  4932.2  396.30  4932.4  394.69  4932.9  393.89  4937.9  393.89
  4938.4  394.69  4939.1  401.92  4997.4  395.24  5069.4  394.72  5107.2  394.95
  5131.7  396.30  5159.4  399.33  5196.1  402.47  5207.9  405.59  5217.4  406.68
  5223.3  408.03  5254.2  411.38  5289.9  413.66  5311.5  413.47  5372.4  415.01
#Mann=7,-1,0
  4716.1    0.12       0  4789.3    0.16       0  4932.4    0.07       0
  4938.4    0.16       0  4997.4    0.07       0  5069.4    0.16       0
  5311.5    0.05       0
Bank Sta=4932.2,5131.7
Exp/Cntr=0.3,0.1

Type RM Length L Ch R = 1,573,94,94,94
BEGIN DESCRIPTION:
Mapping XS 8c69755d
END DESCRIPTION:
XS GIS Cut Line= 4
      2906530.26      7015240.10      2906239.46      7015218.40
      2905879.22      7015209.72      2905780.02      7015380.09
#Sta/Elev= 30
  4564.8  413.86  4630.2  415.29  4666.4  413.97  4720.5  412.60  4740.5  409.91
  4780.7  406.76  4830.4  401.11  4835.4  402.71  4856.1  400.51  4861.1  400.51
  4881.0  397.47  4920.9  396.52  4929.6  395.80  4950.9  394.92  4980.0  394.72
  5079.1  394.80  5107.9  394.62  5108.4  393.82  5113.4  393.82  5113.9  394.62
  5191.0  394.87  5237.8  395.80  5274.9  399.11  5280.7  400.45  5296.4  401.57
  5312.1  407.32  5327.0  408.90  5355.1  410.10  5370.8  412.75  5413.9  414.41
#Mann=7,-1,0
  4564.8    0.12       0  4666.4    0.16       0  4881.0    0.12       0
  4980.0    0.07       0  5079.1    0.16       0  5107.9    0.07       0
  5113.9    0.16       0
Bank Sta=4929.6,5237.8
Exp/Cntr=0.3,0.1

Type RM Length L Ch R = 1,479,388,388,388
BEGIN DESCRIPTION:
Mapping XS 6b47fef5
END DESCRIPTION:
XS GIS Cut Line= 4
      2906491.15      7015148.96      2906196.06      7015151.13
      2905844.50      7015151.13      2905733.82      7015374.66
#Sta/Elev= 30
  4536.5  414.55  4562.7  413.78  4592.7  414.58  4672.7  414.39  4702.7  409.08
  4732.7  407.45  4742.7  407.79  4752.7  406.47  4782.7  405.37  4842.7  399.05
  4910.3  395.83  4914.5  395.63  4939.7  394.19  4940.2  393.39  4945.2  393.39
  4945.7  394.19  5052.7  394.24  5072.7  396.32  5092.7  394.59  5155.7  395.63
  5180.4  397.24  5222.2  397.55  5238.0  396.34  5276.8  398.20  5305.3  402.32
  5333.3  404.79  5350.2  408.87  5355.7  408.03  5372.6  412.60  5432.6  414.46
#Mann=5,-1,0
  4536.5    0.08       0  4910.3     0.1       0  4939.7    0.07       0
  4945.7     0.1       0  5222.2    0.16       0
Bank Sta=4914.5,5155.7
Exp/Cntr=0.3,0.1

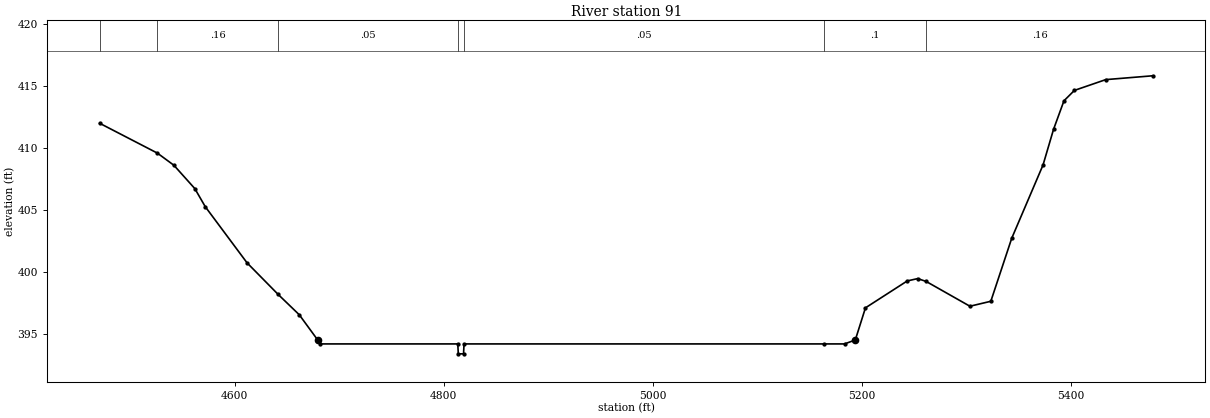
Type RM Length L Ch R = 1,91,0,0,0
BEGIN DESCRIPTION:
UNT 037 IN DRY CR WATERSHED 8.0
END DESCRIPTION:
XS GIS Cut Line= 4
      2906196.11      7014855.99      2905750.00      7014850.00
      2905700.00      7014950.00      2905700.00      7015400.05
#Sta/Elev= 30
  4470.6  411.99  4525.9  409.58  4541.7  408.60  4561.7  406.72  4571.7  405.26
  4611.7  400.73  4641.5  398.18  4661.7  396.54  4679.3  394.51  4681.7  394.19
  4813.4  394.19  4813.9  393.39  4818.9  393.39  4819.4  394.19  5163.9  394.19
  5183.6  394.19  5193.9  394.51  5203.6  397.10  5243.6  399.27  5253.6  399.46
  5261.7  399.23  5303.6  397.23  5323.6  397.63  5343.6  402.71  5373.6  408.63
  5383.6  411.49  5393.6  413.80  5403.6  414.64  5433.6  415.51  5478.6  415.82
#Mann=7,-1,0
  4470.6    0.08       0  4525.9    0.16       0  4641.5    0.05       0
  4813.4   0.033       0  4819.4    0.05       0  5163.9     0.1       0
  5261.7    0.16       0
Bank Sta=4679.3,5193.9
Exp/Cntr=0.3,0.1

Chan Stop Cuts=-1