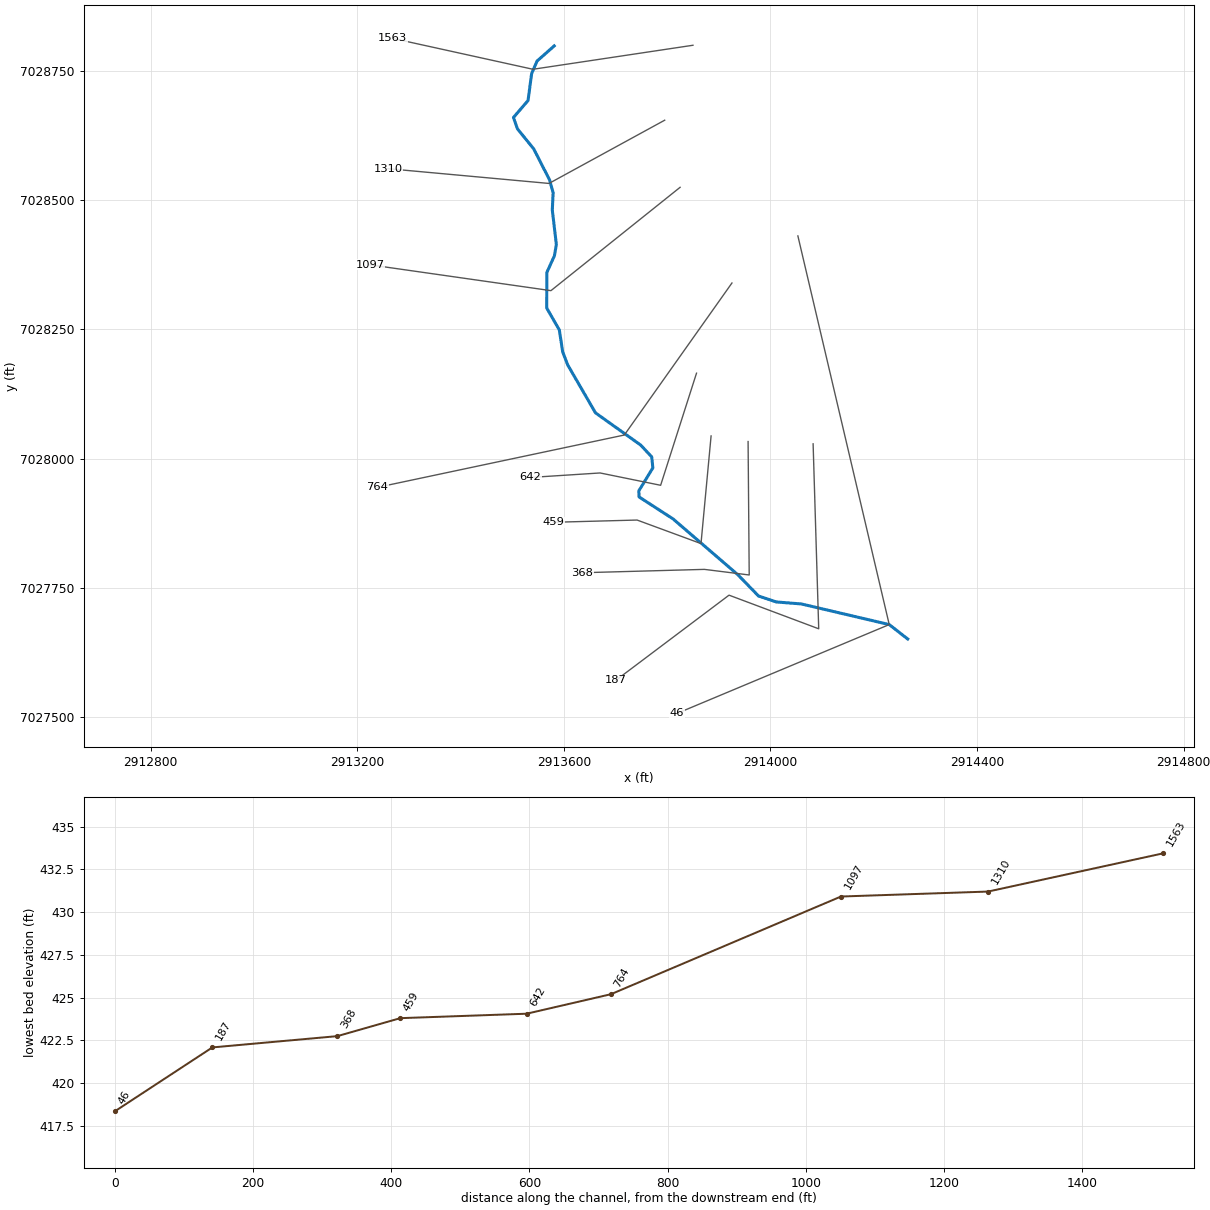
--- UNT 038 IN DRY CR WATERSHED.prj (project) ---

Proj Title=UNT 038 IN DRY CR WATERSHED Base Level Engineering
Current Plan=p01
Default Exp/Contr=0.3,0.1
English Units
Geom File=g01
Flow File=f01
Plan File=p01
Y Axis Title=Elevation
X Axis Title(PF)=Main Channel Distance
X Axis Title(XS)=Station
BEGIN DESCRIPTION:
UNT 038 IN DRY CR WATERSHED
END DESCRIPTION:
DSS Export Rating Curves= 0
DSS Export Rating Curve Sorted= 0
DSS Export Volume Flow Curves= 0
DXF OffsetX= 0
DXF OffsetY= 0
DXF ScaleX= 1
DXF ScaleY= 10

--- UNT 038 IN DRY CR WATERSHED.p01 (plan) ---

Plan Title=Multiple Run
Short Identifier=Multiple
Geom File=g01
Flow File=f01
Subcritical Flow
K Sum by GR= 0
Std Step Tol= 0.01
Critical Tol= 0.01
Num of Std Step Trials= 20
Max Error Tol= 0.3
Flow Tol Ratio= 0.001
Split Flow NTrial= 30
Split Flow Tol= 0.02
Split Flow Ratio= 0.02
Log Output Level= 0
Friction Slope Method= 1
Unsteady Friction Slope Method= 2
Unsteady Bridges Friction Slope Method= 1
Parabolic Critical Depth
Global Vel Dist=  1 , 1 , 1
Global Log Level= 0
CheckData=True
Encroach Param= -1, 0, 0, 0
BEGIN DESCRIPTION:
Multiple Run
END DESCRIPTION:

--- UNT 038 IN DRY CR WATERSHED.f01 (steady flow) ---

Flow Title=Multiple
Number of Profiles=7
Profile Names=10-year,25-year,50-year,1pct_min,100-year,1pct_plu,500-year
River Rch & RM= UNT 038 IN DRY C,Reach-1,1563
     229     291     338     197     392     783     527
Boundary for River Rch & Prof#=UNT 038 IN DRY C,Reach-1,1
Up Type=0
Dn Type=3
Dn Slope=0.005
Boundary for River Rch & Prof#=UNT 038 IN DRY C,Reach-1,2
Up Type=0
Dn Type=3
Dn Slope=0.005
Boundary for River Rch & Prof#=UNT 038 IN DRY C,Reach-1,3
Up Type=0
Dn Type=3
Dn Slope=0.005
Boundary for River Rch & Prof#=UNT 038 IN DRY C,Reach-1,4
Up Type=0
Dn Type=3
Dn Slope=0.005
Boundary for River Rch & Prof#=UNT 038 IN DRY C,Reach-1,5
Up Type=0
Dn Type=3
Dn Slope=0.005
Boundary for River Rch & Prof#=UNT 038 IN DRY C,Reach-1,6
Up Type=0
Dn Type=3
Dn Slope=0.005
Boundary for River Rch & Prof#=UNT 038 IN DRY C,Reach-1,7
Up Type=0
Dn Type=3
Dn Slope=0.005

--- UNT 038 IN DRY CR WATERSHED.g01 (geometry) ---

Geom Title=Existing Conditions
Program Version=5.07

River Reach=UNT 038 IN DRY C,Reach-1
Reach XY= 30
      2913581.43      7028798.77      2913548.25       7028769.5
      2913537.66      7028745.22      2913530.73      7028693.08
      2913502.46      7028660.19      2913510.19      7028638.22
      2913541.79      7028599.26      2913572.35      7028539.34
      2913579.29      7028514.54      2913577.66      7028481.14
       2913585.5      7028414.21      2913581.72      7028392.38
      2913567.01      7028360.02      2913566.88      7028291.34
      2913591.25      7028248.92      2913597.74       7028206.6
      2913607.37      7028181.44      2913661.25      7028088.44
      2913748.99      7028025.88      2913770.16      7028003.13
      2913772.28      7027981.91      2913745.14      7027937.42
      2913745.65      7027925.68      2913811.64      7027882.96
      2913936.97      7027774.96      2913976.85      7027733.91
      2914011.25      7027722.42       2914059.7      7027718.58
      2914229.85      7027678.63      2914265.59      7027650.71

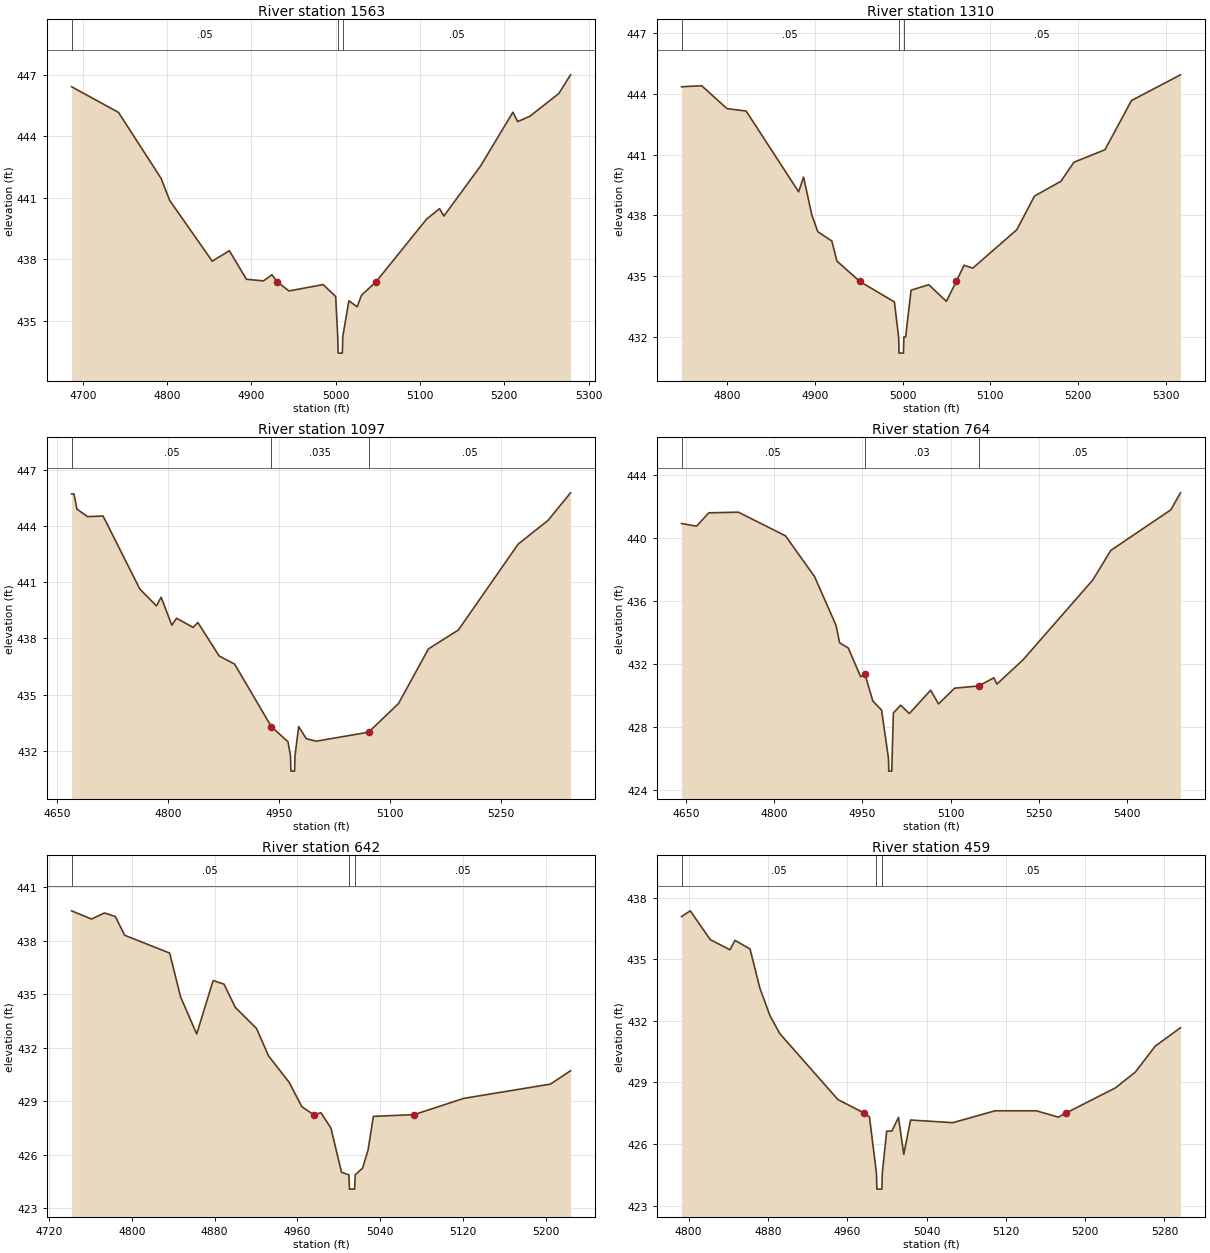
Type RM Length L Ch R = 1 ,1563    ,253,253,253
BEGIN DESCRIPTION:
UNT 038 IN DRY CR WATERSHED 3.0
END DESCRIPTION:
XS GIS Cut Line= 3
      2913849.98        7028800.      2913540.25       7028753.5
      2913268.26      7028813.39
#Sta/Elev= 30
  4686.8  446.41  4742.4  445.16    4793  441.94  4803.1  440.87  4853.6  437.91
  4873.9  438.42  4894.1  437.03  4914.3  436.95  4924.4  437.25  4930.3  436.92
  4944.6  436.46  4985.1  436.77    5000  436.19  5002.4  434.23  5002.9  433.43
  5007.9  433.43  5008.4  434.23  5015.6  435.98  5025.5  435.69  5030.6  436.25
  5048.1  436.92  5107.8  439.96  5123.2  440.47  5128.3  440.11    5172  442.56
  5210.2  445.17  5215.8  444.71  5230.6  444.98  5264.6  446.08  5278.5  446.99
#Mann= 3 ,-1 , 0
  4686.8     .05       0  5002.4    .035       0  5008.4     .05       0
Bank Sta=4930.3,5048.1
XS Rating Curve= 0 ,0
Exp/Cntr=0.3,0.1

Type RM Length L Ch R = 1 ,1310    ,213,213,213
BEGIN DESCRIPTION:
Mapping XS b6ac6908
END DESCRIPTION:
XS GIS Cut Line= 3
      2913795.22      7028654.93      2913571.24      7028532.52
       2913259.4      7028561.11
#Sta/Elev= 30
  4748.2  444.36  4771.2  444.41    4800  443.28  4821.8  443.16  4881.6  439.17
  4887.2   439.9  4896.6  438.03  4903.4   437.2  4919.4  436.74  4925.2  435.75
  4951.3  434.74  4990.7  433.73  4995.5     432    4996   431.2    5001   431.2
  5001.5     432  5003.5     432  5009.7  434.31  5029.8  434.58  5049.9  433.76
  5061.2  434.74    5070  435.54    5080   435.4  5130.2   437.3  5150.3  438.96
  5180.4  439.69  5195.2  440.63  5230.6  441.25  5260.8  443.68  5316.6  444.95
#Mann= 3 ,-1 , 0
  4748.2     .05       0  4995.5    .035       0  5001.5     .05       0
Bank Sta=4951.3,5061.2
XS Rating Curve= 0 ,0
Exp/Cntr=0.3,0.1

Type RM Length L Ch R = 1 ,1097    ,333,333,333
BEGIN DESCRIPTION:
UNT 038 IN DRY CR WATERSHED 2.0
END DESCRIPTION:
XS GIS Cut Line= 3
      2913825.03      7028525.02        2913575.        7028325.
      2913225.04      7028374.99
#Sta/Elev= 30
  4669.7  445.72  4672.9  445.72  4676.9  444.91  4691.3  444.51  4712.2  444.54
  4761.8  440.64  4784.2  439.74  4790.6   440.2    4805  438.71  4811.4  439.08
  4833.8  438.59  4840.2  438.85    4869  437.06  4889.8  436.63  4939.5  433.28
  4961.9  432.48  4965.3  431.71  4965.8  430.91  4970.8  430.91  4971.3  431.71
  4976.3  433.29  4986.7  432.64    5000  432.51  5070.7  432.99  5111.1  434.52
  5151.5  437.44  5191.9  438.45  5272.7  443.04  5313.1  444.31  5343.4  445.78
#Mann= 3 , 0 , 0
  4669.7     .05       0  4939.5    .035       0  5070.7     .05       0
Bank Sta=4939.5,5070.7
XS Rating Curve= 0 ,0
Exp/Cntr=0.3,0.1

Type RM Length L Ch R = 1 ,764     ,122,122,122
BEGIN DESCRIPTION:
Mapping XS ee8d6bb2
END DESCRIPTION:
XS GIS Cut Line= 3
      2913925.41      7028339.82      2913717.07      7028045.54
      2913238.95       7027944.2
#Sta/Elev= 30
    4642  440.93  4667.5  440.76  4688.4  441.61  4738.8  441.65  4818.9  440.15
  4868.4  437.56    4905  434.46  4911.1  433.35  4925.9  433.02  4946.8   431.2
  4954.2  431.35  4967.7  429.65  4982.5  429.08  4994.3     426  4994.8   425.2
  4999.8   425.2  5002.6  428.89  5014.9  429.39  5029.8  428.86    5066  430.34
  5079.4  429.47  5106.9  430.47  5147.8  430.61  5173.7  431.13  5178.8  430.73
  5223.3  432.27    5342  437.34  5372.7  439.22  5474.9   441.8  5491.3  442.88
#Mann= 3 , 0 , 0
    4642     .05       0  4954.2     .03       0  5147.8     .05       0
Bank Sta=4954.2,5147.8
XS Rating Curve= 0 ,0
Exp/Cntr=0.3,0.1

Type RM Length L Ch R = 1 ,642     ,183,183,183
BEGIN DESCRIPTION:
Mapping XS 60513204
END DESCRIPTION:
XS GIS Cut Line= 4
       2913856.8      7028165.25      2913787.36      7027948.24
      2913670.17      7027972.11       2913535.6      7027963.43
#Sta/Elev= 30
  4741.8  439.67    4761  439.21  4773.6  439.55  4784.1  439.35  4793.1   438.3
  4836.6   437.3  4847.1  434.85  4862.7  432.76  4878.6  435.76  4889.1  435.56
  4900.1  434.25  4920.6  433.07  4932.2  431.53  4952.1  430.05  4964.4  428.68
  4975.7  428.24  4982.9  428.34  4992.5  427.48  5002.7  425.01  5009.9  424.86
  5010.4  424.06  5015.4  424.06  5015.9  424.86  5023.1  425.24  5028.4  426.26
  5033.5  428.14  5073.1  428.24  5120.8  429.15  5204.7  429.95  5224.1   430.7
#Mann= 3 ,-1 , 0
  4741.8     .05       0  5009.9     .03       0  5015.9     .05       0
Bank Sta=4975.7,5073.1
XS Rating Curve= 0 ,0
Exp/Cntr=0.3,0.1

Type RM Length L Ch R = 1 ,459     ,91,91,91
BEGIN DESCRIPTION:
Mapping XS f752cb34
END DESCRIPTION:
XS GIS Cut Line= 4
      2913885.02      7028043.77      2913865.48      7027835.39
      2913741.78      7027880.97      2913579.55      7027876.64
#Sta/Elev= 30
  4792.8  437.09  4801.6  437.37  4821.7  435.97  4841.7  435.47  4846.7  435.93
  4861.9  435.51  4871.9  433.59    4882  432.26    4892  431.38  4950.5  428.17
  4976.5  427.52  4982.4  427.32  4989.4   424.6  4989.9   423.8  4994.9   423.8
  4995.4   424.6  4999.8  426.63    5005  426.63  5011.7   427.3    5017   425.5
  5023.9  427.17  5066.5  427.04  5109.2  427.62  5150.7  427.62    5173  427.31
  5181.1  427.52  5230.7  428.74  5250.7  429.51  5270.7  430.77  5296.2  431.67
#Mann= 3 ,-1 , 0
  4792.8     .05       0  4989.4     .03       0  4995.4     .05       0
Bank Sta=4976.5,5181.1
XS Rating Curve= 0 ,0
Exp/Cntr=0.3,0.1

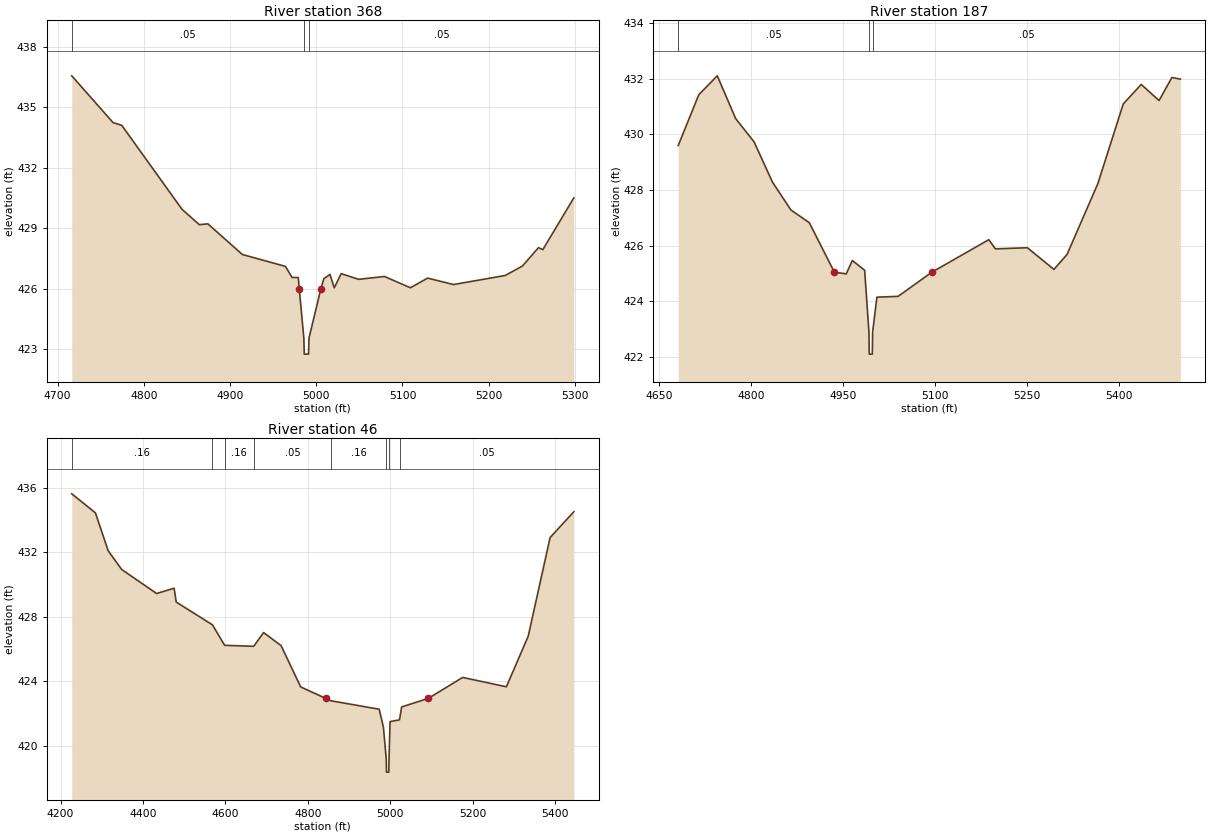
Type RM Length L Ch R = 1 ,368     ,181,181,181
BEGIN DESCRIPTION:
Mapping XS a2474bcc
END DESCRIPTION:
XS GIS Cut Line= 4
      2913956.63      7028032.92       2913958.8      7027774.63
      2913871.99      7027785.48      2913635.46      7027778.97
#Sta/Elev= 30
  4716.4  436.55  4764.3  434.23  4774.3   434.1  4844.3  429.93  4864.3  429.17
  4874.3  429.21  4914.3  427.69  4964.3   427.1    4972  426.55  4979.1  426.55
  4980.3  425.98  4985.6  423.55  4986.1  422.75  4991.1  422.75  4991.6  423.55
  5005.3  425.98  5008.8  426.49  5015.9   426.7  5020.9  426.04  5028.9  426.74
  5049.1  426.46  5079.2   426.6  5109.2  426.04  5129.2  426.52  5159.2   426.2
  5219.2  426.65  5239.2  427.12  5257.8  428.03  5262.8  427.93  5298.8   430.5
#Mann= 3 ,-1 , 0
  4716.4     .05       0  4985.6     .03       0  4991.6     .05       0
Bank Sta=4980.3,5005.3
XS Rating Curve= 0 ,0
Exp/Cntr=0.3,0.1

Type RM Length L Ch R = 1 ,187     ,141,141,141
BEGIN DESCRIPTION:
Mapping XS 0b2e0ad1
END DESCRIPTION:
XS GIS Cut Line= 4
       2914082.5      7028028.53      2914093.35      7027670.46
      2913919.74      7027735.57      2913700.51      7027570.61
#Sta/Elev= 30
  4681.8   429.6  4715.3  431.43  4745.4  432.11  4775.4  430.57  4805.4  429.73
  4835.4  428.28  4865.4  427.28  4895.4  426.82  4936.2  425.04  4955.5  424.98
  4965.5  425.46  4985.5  425.11  4992.5  422.89    4993  422.09    4998  422.09
  4998.5  422.89  5005.5  424.14    5040  424.17    5095  425.04  5187.8  426.21
  5198.5  425.88  5250.7  425.92  5293.9  425.14  5315.3  425.68  5365.3  428.22
  5406.9   431.1  5436.1   431.8  5465.2  431.22  5486.1  432.05  5499.8  431.99
#Mann= 3 ,-1 , 0
  4681.8     .05       0  4992.5     .03       0  4998.5     .05       0
Bank Sta=4936.2,5095
XS Rating Curve= 0 ,0
Exp/Cntr=0.3,0.1

Type RM Length L Ch R = 1 ,46      ,0,0,0
BEGIN DESCRIPTION:
UNT 038 IN DRY CR WATERSHED 1.0
END DESCRIPTION:
XS GIS Cut Line= 3
      2914053.02      7028430.92      2914229.85      7027678.63
      2913819.28      7027506.75
#Sta/Elev= 30
  4227.2  435.61  4284.6  434.43  4315.5  432.08  4348.3  430.92  4433.1  429.43
  4475.5  429.76  4480.6   428.9  4568.5  427.49    4598  426.22  4668.5  426.16
  4692.6  427.01    4735   426.2  4782.5  423.64  4843.2  422.93  4856.4  422.78
  4972.9  422.26  4983.2  421.14  4990.1  419.16  4990.6  418.36  4996.3  418.36
  4996.8  419.16  4999.3  421.49  5022.2   421.6  5027.4   422.4  5092.1  422.93
  5175.5  424.23  5281.5  423.65  5334.5  426.79  5387.5   432.9  5445.1   434.5
#Mann= 8 ,-1 , 0
  4227.2     .16       0  4568.5     .05       0    4598     .16       0
  4668.5     .05       0  4856.4     .16       0  4990.1     .07       0
  4996.8     .16       0  5022.2     .05       0
Bank Sta=4843.2,5092.1
XS Rating Curve= 0 ,0
Exp/Cntr=0.3,0.1
LCMann Table=0

Chan Stop Cuts=-1
Use User Specified Reach Order=0
Composite Channel Slope=5