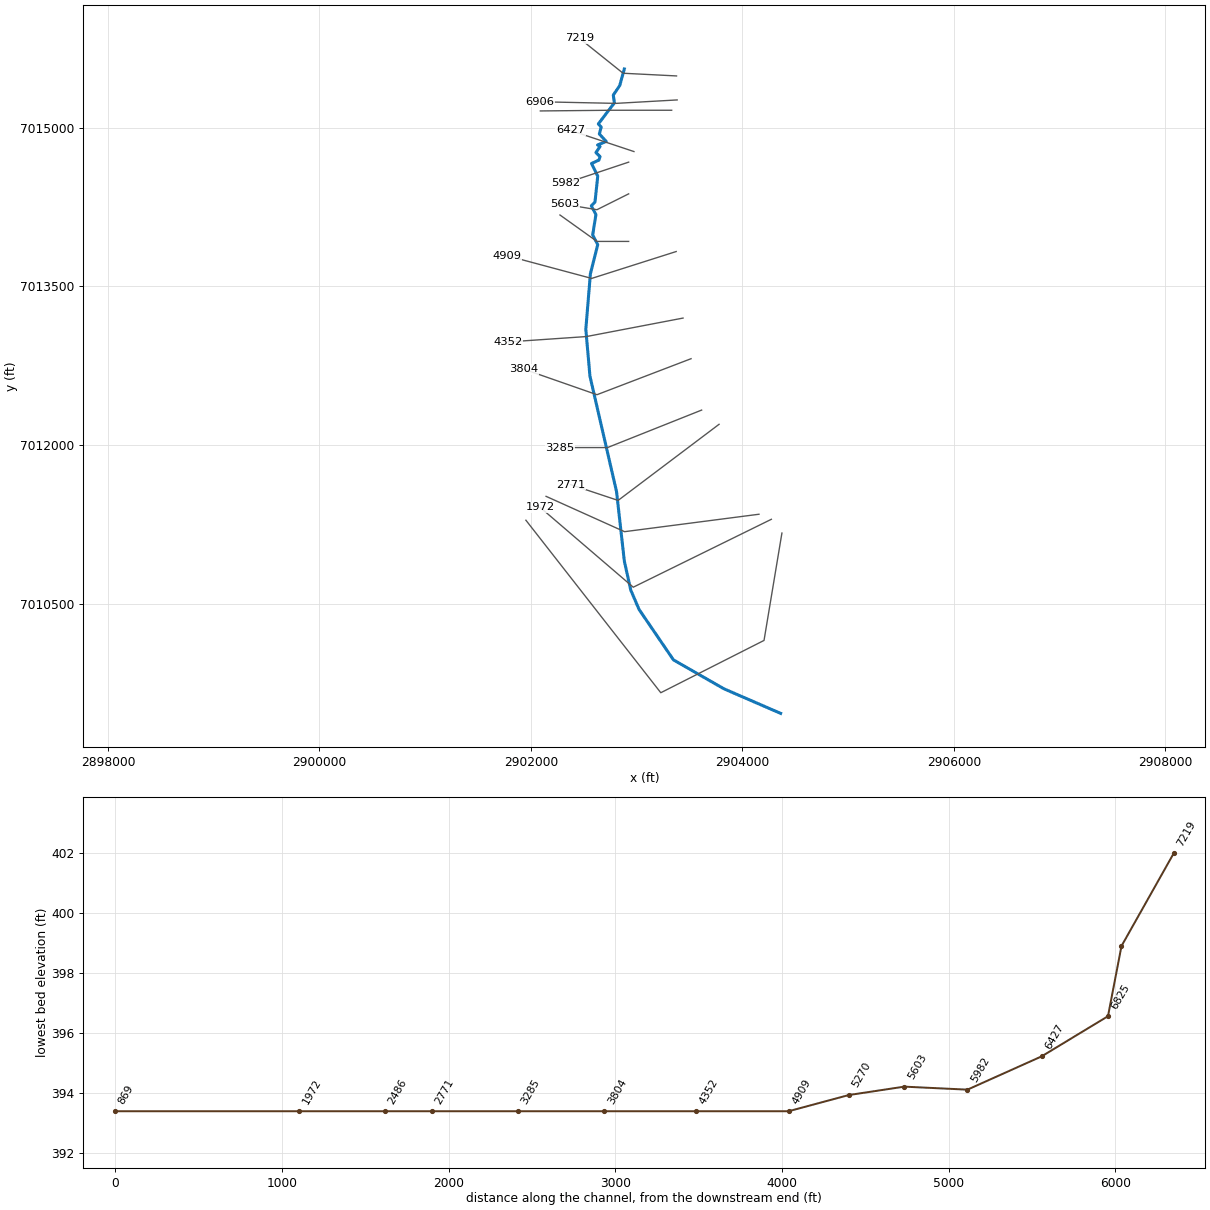
--- UNT 039 IN DRY CR WATERSHED.prj (project) ---

Proj Title=UNT 039 IN DRY CR WATERSHED Base Level Engineering
Current Plan=p01
Default Exp/Contr=0.3,0.1
English Units
Geom File=g01
Flow File=f01
Plan File=p01
BEGIN DESCRIPTION:
UNT 039 IN DRY CR WATERSHED
END DESCRIPTION:

--- UNT 039 IN DRY CR WATERSHED.p01 (plan) ---

Plan Title=Multiple Run
Short Identifier=Multiple
Geom File=g01
Flow File=f01
Subcritical Flow
K Sum by GR= 0
Std Step Tol= 0.01
Critical Tol= 0.01
Num of Std Step Trials= 20
Max Error Tol= 0.3
Flow Tol Ratio= 0.001
Split Flow NTrial= 30
Split Flow Tol= 0.02
Split Flow Ratio= 0.02
Log Output Level= 0
Friction Slope Method= 1
Unsteady Friction Slope Method= 2
Unsteady Bridges Friction Slope Method= 1
Parabolic Critical Depth
Global Vel Dist=  1 , 1 , 1
Global Log Level= 0
CheckData=True
Encroach Param= -1, 0, 0, 0
BEGIN DESCRIPTION:
Multiple Run
END DESCRIPTION:

--- UNT 039 IN DRY CR WATERSHED.f01 (steady flow) ---

Flow Title=Multiple
Number of Profiles=7
Profile Names=10-year,25-year,50-year,1pct_min,100-year,1pct_plu,500-year
River Rch & RM= UNT 039 IN DRY C,Reach-1,7219
     488     648     777     463     924    1844    1311
River Rch & RM= UNT 039 IN DRY C,Reach-1,5982
     588     784     942     562    1122    2239    1594
Boundary for River Rch & Prof#=UNT 039 IN DRY C,Reach-1,1
Up Type=0
Dn Type=3
Dn Slope=0.005
Boundary for River Rch & Prof#=UNT 039 IN DRY C,Reach-1,2
Up Type=0
Dn Type=3
Dn Slope=0.005
Boundary for River Rch & Prof#=UNT 039 IN DRY C,Reach-1,3
Up Type=0
Dn Type=3
Dn Slope=0.005
Boundary for River Rch & Prof#=UNT 039 IN DRY C,Reach-1,4
Up Type=0
Dn Type=3
Dn Slope=0.005
Boundary for River Rch & Prof#=UNT 039 IN DRY C,Reach-1,5
Up Type=0
Dn Type=3
Dn Slope=0.005
Boundary for River Rch & Prof#=UNT 039 IN DRY C,Reach-1,6
Up Type=0
Dn Type=3
Dn Slope=0.005
Boundary for River Rch & Prof#=UNT 039 IN DRY C,Reach-1,7
Up Type=0
Dn Type=3
Dn Slope=0.005

--- UNT 039 IN DRY CR WATERSHED.g01 (geometry) ---

Geom Title=Existing Conditions

River Reach=UNT 039 IN DRY C,Reach-1
Reach XY= 30
      2902883.67      7015556.17      2902840.70      7015399.92
      2902779.50      7015308.78      2902789.92      7015235.86
      2902637.69      7015036.01      2902664.97      7015006.82
      2902647.61      7014941.72      2902712.71      7014870.10
      2902630.25      7014837.55      2902654.12      7014822.36
      2902615.06      7014765.93      2902654.12      7014726.87
      2902643.27      7014694.32      2902573.82      7014661.77
      2902632.42      7014542.41      2902606.38      7014297.18
      2902571.65      7014261.38      2902615.06      7014178.91
      2902584.67      7013985.77      2902632.42      7013894.62
      2902562.97      7013619.02      2902519.57      7013093.84
      2902558.63      7012651.13      2902810.37      7011557.38
      2902884.15      7010899.83      2902944.92      7010626.39
      2903023.04      7010444.10      2903348.56      7009966.67
      2903825.99      7009693.23      2904362.50      7009460.67

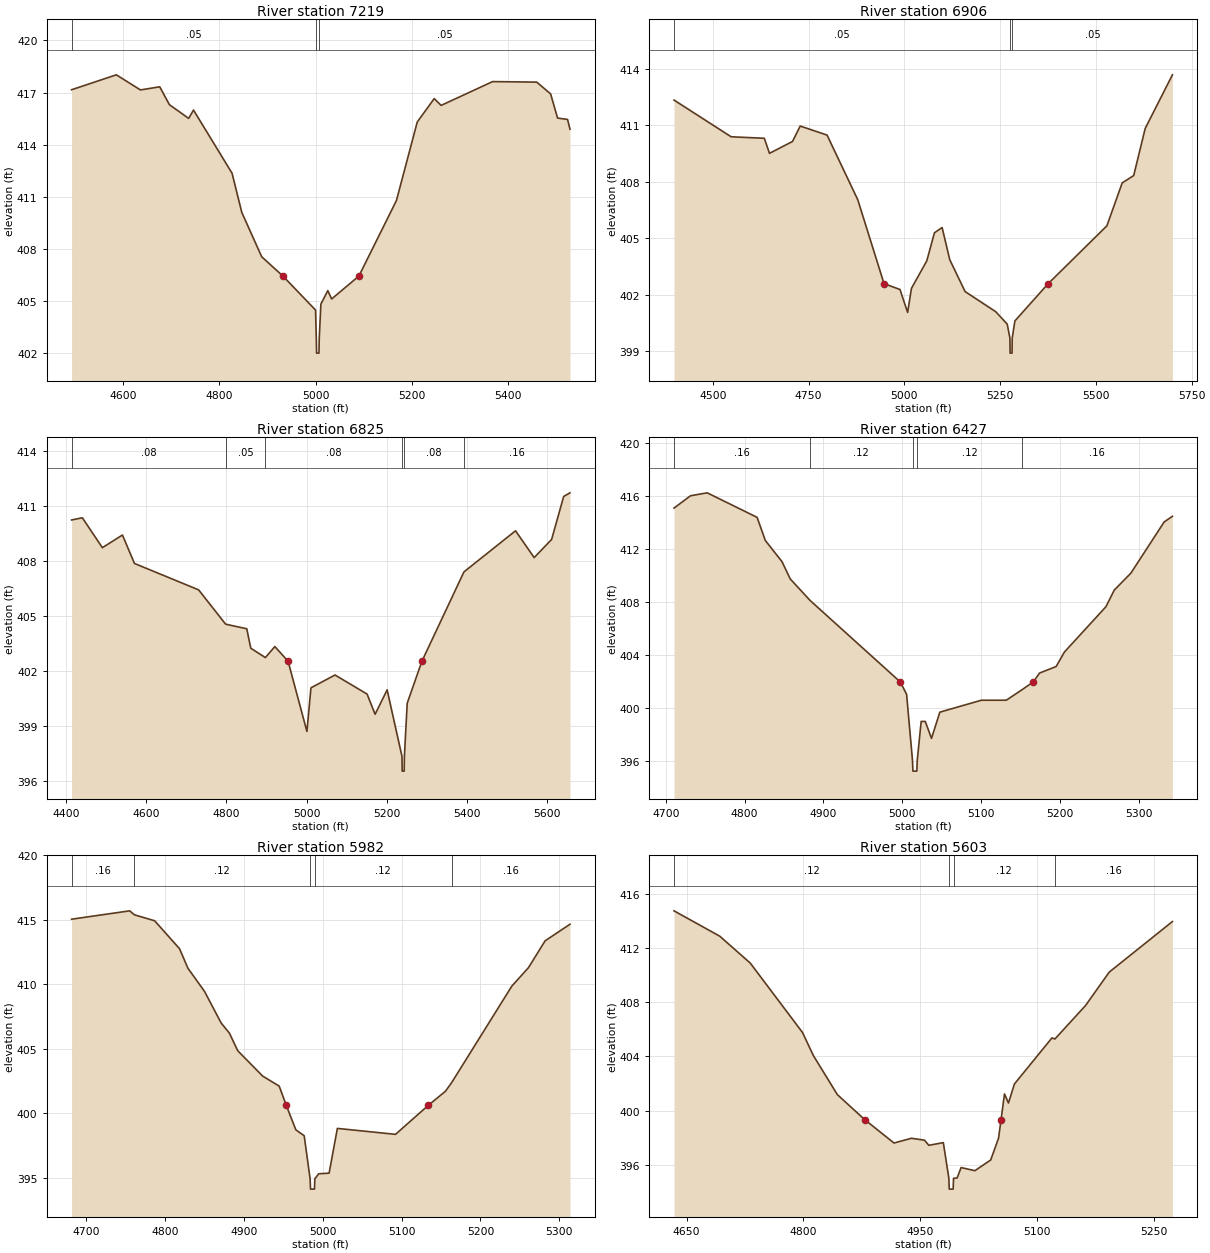
Type RM Length L Ch R = 1,7219,313,313,313
BEGIN DESCRIPTION:
UNT 039 IN DRY CR WATERSHED 11.0
END DESCRIPTION:
XS GIS Cut Line= 3
      2903377.80      7015490.30      2902871.95      7015515.81
      2902459.66      7015845.98
#Sta/Elev= 30
  4493.5  417.16  4586.4  418.02  4636.5  417.15  4676.5  417.33  4696.6  416.30
  4736.6  415.51  4746.6  415.99  4826.7  412.35  4846.8  410.10  4888.2  407.54
  4932.2  406.43  5000.0  404.47  5001.6  402.79  5002.1  401.99  5007.1  401.99
  5007.6  402.79  5011.0  404.81  5025.4  405.59  5033.4  405.11  5090.0  406.43
  5167.9  410.78  5211.1  415.30  5246.3  416.65  5260.7  416.26  5367.6  417.63
  5459.2  417.60  5488.0  416.92  5502.4  415.53  5523.2  415.45  5528.2  414.89
#Mann=3,-1,0
  4493.5    0.05       0  5001.6    0.03       0  5007.6    0.05       0
Bank Sta=4932.2,5090
Exp/Cntr=0.3,0.1

Type RM Length L Ch R = 1,6906,81,81,81
BEGIN DESCRIPTION:
Mapping XS 955cd847
END DESCRIPTION:
XS GIS Cut Line= 3
      2903383.84      7015263.30      2902804.44      7015230.75
      2902083.91      7015245.95
#Sta/Elev= 30
  4398.8  412.34  4547.9  410.39  4634.5  410.31  4648.0  409.51  4708.1  410.14
  4728.2  410.96  4798.3  410.48  4878.4  407.05  4947.0  402.59  4988.6  402.28
  5008.6  401.06  5018.6  402.34  5058.6  403.80  5078.6  405.29  5098.6  405.57
  5118.6  403.86  5158.6  402.17  5238.6  401.10  5268.6  400.44  5275.6  399.70
  5276.1  398.90  5281.1  398.90  5281.6  399.70  5288.6  400.61  5375.5  402.59
  5528.7  405.66  5568.7  407.94  5598.7  408.33  5628.7  410.83  5699.8  413.68
#Mann=3,-1,0
  4398.8    0.05       0  5275.6    0.03       0  5281.6    0.05       0
Bank Sta=4947,5375.5
Exp/Cntr=0.3,0.1

Type RM Length L Ch R = 1,6825,398,398,398
BEGIN DESCRIPTION:
Mapping XS 94c9417d
END DESCRIPTION:
XS GIS Cut Line= 3
      2903331.83      7015165.65      2902758.87      7015165.65
      2902089.16      7015159.15
#Sta/Elev= 30
  4414.2  410.25  4441.0  410.37  4491.0  408.74  4541.0  409.43  4571.0  407.88
  4731.0  406.44  4798.3  404.57  4851.0  404.32  4861.0  403.26  4897.4  402.75
  4921.0  403.35  4954.0  402.55  5001.0  398.72  5011.0  401.10  5071.0  401.80
  5151.0  400.76  5171.0  399.66  5201.0  400.99  5238.0  397.36  5238.5  396.56
  5243.5  396.56  5244.0  397.36  5251.0  400.26  5287.7  402.55  5392.5  407.42
  5521.1  409.66  5567.6  408.20  5611.1  409.19  5641.1  411.53  5656.9  411.73
#Mann=6,-1,0
  4414.2    0.08       0  4798.3    0.05       0  4897.4    0.08       0
  5238.0    0.07       0  5244.0    0.08       0  5392.5    0.16       0
Bank Sta=4954,5287.7
Exp/Cntr=0.3,0.1

Type RM Length L Ch R = 1,6427,445,445,445
BEGIN DESCRIPTION:
UNT 039 IN DRY CR WATERSHED 10.0
END DESCRIPTION:
XS GIS Cut Line= 3
      2902974.96      7014775.01      2902675.00      7014875.00
      2902375.02      7014974.99
#Sta/Elev= 30
  4710.5  415.07  4731.5  416.00  4752.6  416.22  4815.9  414.37  4826.4  412.62
  4847.5  411.03  4858.0  409.72  4883.3  408.09  4997.6  401.95  5005.6  401.02
  5013.1  396.02  5013.6  395.22  5018.6  395.22  5019.1  396.02  5024.1  398.97
  5029.3  398.97  5037.2  397.69  5047.8  399.67  5100.5  400.57  5132.1  400.57
  5151.5  401.34  5166.4  401.95  5174.3  402.62  5195.3  403.11  5205.9  404.21
  5258.6  407.63  5269.1  408.88  5290.2  410.16  5332.4  414.02  5342.9  414.45
#Mann=5,-1,0
  4710.5    0.16       0  4883.3    0.12       0  5013.1    0.07       0
  5019.1    0.12       0  5151.5    0.16       0
Bank Sta=4997.6,5166.4
Exp/Cntr=0.3,0.1

Type RM Length L Ch R = 1,5982,379,379,379
BEGIN DESCRIPTION:
UNT 039 IN DRY CR WATERSHED 9.0
END DESCRIPTION:
XS GIS Cut Line= 3
      2902925.02      7014675.01      2902625.00      7014575.00
      2902324.97      7014474.99
#Sta/Elev= 30
  4681.1  415.05  4754.9  415.70  4760.8  415.39  4786.5  414.93  4818.1  412.76
  4828.7  411.25  4849.8  409.45  4870.9  407.00  4881.4  406.21  4891.9  404.85
  4923.6  402.88  4944.6  402.10  4953.6  400.60  4965.7  398.71  4976.3  398.25
  4983.8  394.91  4984.3  394.11  4989.3  394.11  4989.8  394.91  4994.7  395.30
  5007.9  395.35  5018.4  398.82  5092.2  398.36  5133.6  400.60  5155.5  401.70
  5163.5  402.38  5239.8  409.86  5260.9  411.29  5282.0  413.37  5313.6  414.66
#Mann=5,-1,0
  4681.1    0.16       0  4760.8    0.12       0  4983.8    0.07       0
  4989.8    0.12       0  5163.5    0.16       0
Bank Sta=4953.6,5133.6
Exp/Cntr=0.3,0.1

Type RM Length L Ch R = 1,5603,333,333,333
BEGIN DESCRIPTION:
UNT 039 IN DRY CR WATERSHED 8.0
END DESCRIPTION:
XS GIS Cut Line= 3
      2902925.01      7014375.01      2902625.00      7014225.00
      2902324.96      7014275.01
#Sta/Elev= 30
  4633.9  414.73  4692.6  412.86  4731.7  410.88  4798.8  405.76  4812.8  404.05
  4843.5  401.18  4878.5  399.34  4916.2  397.61  4938.6  397.96  4955.3  397.82
  4960.9  397.44  4979.5  397.64  4986.6  395.01  4987.1  394.21  4992.1  394.21
  4992.6  395.01  4997.2  395.03  5002.3  395.80  5020.0  395.57  5040.3  396.36
  5050.4  397.97  5053.6  399.34  5058.0  401.23  5063.1  400.56  5070.7  401.96
  5118.9  405.36  5122.7  405.28  5161.9  407.74  5192.4  410.21  5273.5  413.94
#Mann=4,-1,0
  4633.9    0.12       0  4986.6    0.07       0  4992.6    0.12       0
  5122.7    0.16       0
Bank Sta=4878.5,5053.6
Exp/Cntr=0.3,0.1

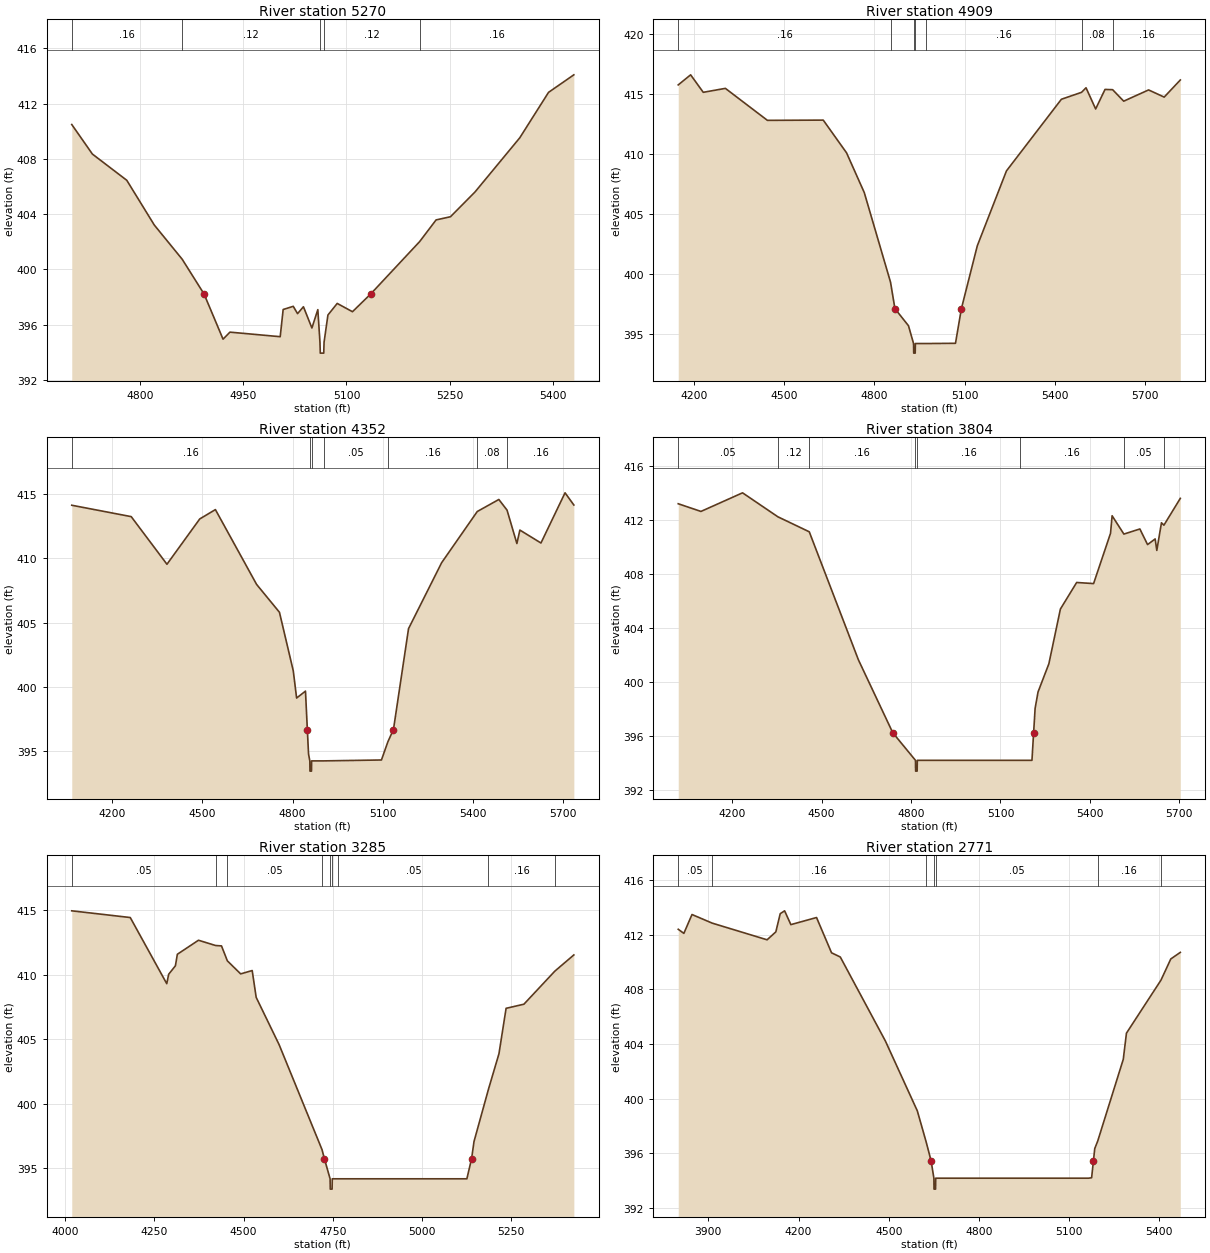
Type RM Length L Ch R = 1,5270,361,361,361
BEGIN DESCRIPTION:
UNT 039 IN DRY CR WATERSHED 7.0
END DESCRIPTION:
XS GIS Cut Line= 3
      2902925.01      7013925.00      2902625.00      7013925.00
      2902275.02      7014174.98
#Sta/Elev= 30
  4700.5  410.49  4730.5  408.35  4780.5  406.45  4820.5  403.21  4861.1  400.73
  4892.9  398.21  4920.5  394.94  4930.5  395.45  5003.6  395.12  5007.9  397.09
  5022.6  397.32  5028.8  396.79  5037.4  397.29  5049.7  395.75  5058.3  397.08
  5061.4  394.73  5061.9  393.93  5066.9  393.93  5067.4  394.73  5073.0  396.69
  5086.5  397.53  5108.7  396.93  5135.1  398.21  5206.4  402.01  5230.3  403.58
  5251.2  403.81  5286.8  405.60  5352.0  409.53  5393.8  412.82  5430.6  414.09
#Mann=5,-1,0
  4700.5    0.16       0  4861.1    0.12       0  5061.4    0.07       0
  5067.4    0.12       0  5206.4    0.16       0
Bank Sta=4892.9,5135.1
Exp/Cntr=0.3,0.1

Type RM Length L Ch R = 1,4909,557,557,557
BEGIN DESCRIPTION:
UNT 039 IN DRY CR WATERSHED 6.0
END DESCRIPTION:
XS GIS Cut Line= 3
      2903374.29      7013829.27      2902575.00      7013575.00
      2901773.21      7013790.09
#Sta/Elev= 30
  4148.0  415.78  4189.2  416.62  4231.2  415.16  4304.7  415.49  4444.4  412.82
  4630.0  412.84  4707.5  410.11  4766.4  406.79  4853.7  399.31  4868.3  397.10
  4913.3  395.68  4930.2  394.19  4930.7  393.39  4935.7  393.39  4936.2  394.19
  4972.8  394.19  5069.6  394.21  5089.2  397.10  5142.1  402.35  5239.0  408.60
  5421.6  414.58  5488.7  415.16  5503.5  415.54  5535.5  413.77  5566.6  415.40
  5591.9  415.38  5628.7  414.42  5711.5  415.36  5763.3  414.76  5816.9  416.19
#Mann=7,-1,0
  4148.0    0.16       0  4853.7    0.12       0  4930.2    0.07       0
  4936.2    0.12       0  4972.8    0.16       0  5488.7    0.08       0
  5591.9    0.16       0
Bank Sta=4868.3,5089.2
Exp/Cntr=0.3,0.1

Type RM Length L Ch R = 1,4352,548,548,548
BEGIN DESCRIPTION:
UNT 039 IN DRY CR WATERSHED 5.0
END DESCRIPTION:
XS GIS Cut Line= 3
      2903439.43      7013199.94      2902525.00      7013025.00
      2901785.76      7012974.24
#Sta/Elev= 30
  4064.9  414.16  4262.9  413.27  4381.9  409.55  4491.1  413.09  4543.2  413.82
  4680.3  407.98  4756.5  405.80  4802.5  401.23  4813.7  399.10  4843.2  399.64
  4849.4  396.64  4853.4  394.72  4857.7  394.19  4858.2  393.39  4863.2  393.39
  4863.7  394.19  4904.7  394.19  5096.2  394.26  5117.9  395.70  5136.2  396.64
  5186.4  404.52  5296.6  409.67  5415.3  413.67  5487.1  414.61  5514.4  413.78
  5547.2  411.17  5557.2  412.22  5627.4  411.21  5707.6  415.13  5736.9  414.18
#Mann=7,-1,0
  4064.9    0.16       0  4857.7   0.033       0  4863.7    0.16       0
  4904.7    0.05       0  5117.9    0.16       0  5415.3    0.08       0
  5514.4    0.16       0
Bank Sta=4849.4,5136.2
Exp/Cntr=0.3,0.1

Type RM Length L Ch R = 1,3804,519,519,519
BEGIN DESCRIPTION:
UNT 039 IN DRY CR WATERSHED 4.0
END DESCRIPTION:
XS GIS Cut Line= 3
      2903515.23      7012815.68      2902625.00      7012475.00
      2901935.35      7012715.86
#Sta/Elev= 30
  4019.5  413.22  4095.7  412.65  4235.2  414.03  4353.8  412.25  4458.9  411.14
  4623.8  401.64  4738.9  396.24  4815.1  394.19  4815.6  393.39  4820.7  393.39
  4821.2  394.19  5165.6  394.19  5205.7  394.19  5211.3  396.24  5216.3  398.05
  5226.1  399.26  5262.4  401.35  5301.1  405.41  5355.6  407.38  5412.4  407.30
  5469.2  411.03  5474.5  412.33  5514.0  410.97  5567.6  411.35  5593.4  410.19
  5618.8  410.61  5624.4  409.76  5640.0  411.81  5648.2  411.63  5703.2  413.62
#Mann=8,-1,0
  4019.5    0.05       0  4353.8    0.12       0  4458.9    0.16       0
  4815.1   0.033       0  4821.2    0.16       0  5165.6    0.16       0
  5514.0    0.05       0  5648.2    0.16       0
Bank Sta=4738.9,5211.3
Exp/Cntr=0.3,0.1

Type RM Length L Ch R = 1,3285,514,514,514
BEGIN DESCRIPTION:
UNT 039 IN DRY CR WATERSHED 3.0
END DESCRIPTION:
XS GIS Cut Line= 3
      2903615.09      7012329.58      2902725.00      7011975.00
      2902275.01      7011975.00
#Sta/Elev= 30
  4018.1  414.97  4182.1  414.45  4284.5  409.32  4289.9  410.05  4308.8  410.71
  4314.2  411.60  4373.5  412.69  4421.5  412.28  4438.0  412.25  4454.5  411.09
  4491.8  410.08  4524.1  410.34  4535.3  408.26  4599.5  404.60  4720.0  396.45
  4726.5  395.76  4742.6  394.19  4743.1  393.39  4748.2  393.39  4748.7  394.19
  4765.4  394.19  5126.2  394.19  5139.5  395.76  5146.2  397.08  5186.8  401.14
  5216.2  403.89  5236.2  407.41  5286.2  407.73  5372.8  410.29  5426.2  411.55
#Mann=9,-1,0
  4018.1    0.05       0  4421.5    0.16       0  4454.5    0.05       0
  4720.0    0.16       0  4742.6   0.033       0  4748.7    0.16       0
  4765.4    0.05       0  5186.8    0.16       0  5372.8    0.08       0
Bank Sta=4726.5,5139.5
Exp/Cntr=0.3,0.1

Type RM Length L Ch R = 1,2771,285,285,285
BEGIN DESCRIPTION:
UNT 039 IN DRY CR WATERSHED 2.0
END DESCRIPTION:
XS GIS Cut Line= 3
      2903779.97      7012195.00      2902825.00      7011475.00
      2902375.02      7011624.99
#Sta/Elev= 30
  3799.8  412.40  3818.5  412.10  3845.6  413.48  3912.8  412.85  4095.4  411.63
  4124.5  412.21  4139.1  413.54  4153.7  413.75  4174.5  412.74  4259.9  413.26
  4309.8  410.68  4339.0  410.37  4488.9  404.23  4595.1  399.12  4624.5  396.85
  4641.0  395.46  4650.3  394.19  4650.8  393.39  4655.9  393.39  4656.4  394.19
  5164.4  394.19  5175.0  394.22  5181.1  395.46  5185.5  396.36  5195.4  396.91
  5280.4  402.89  5290.9  404.80  5405.8  408.68  5438.5  410.23  5470.1  410.71
#Mann=7,-1,0
  3799.8    0.05       0  3912.8    0.16       0  4624.5    0.05       0
  4650.3   0.033       0  4656.4    0.05       0  5195.4    0.16       0
  5405.8    0.05       0
Bank Sta=4641,5181.1
Exp/Cntr=0.3,0.1

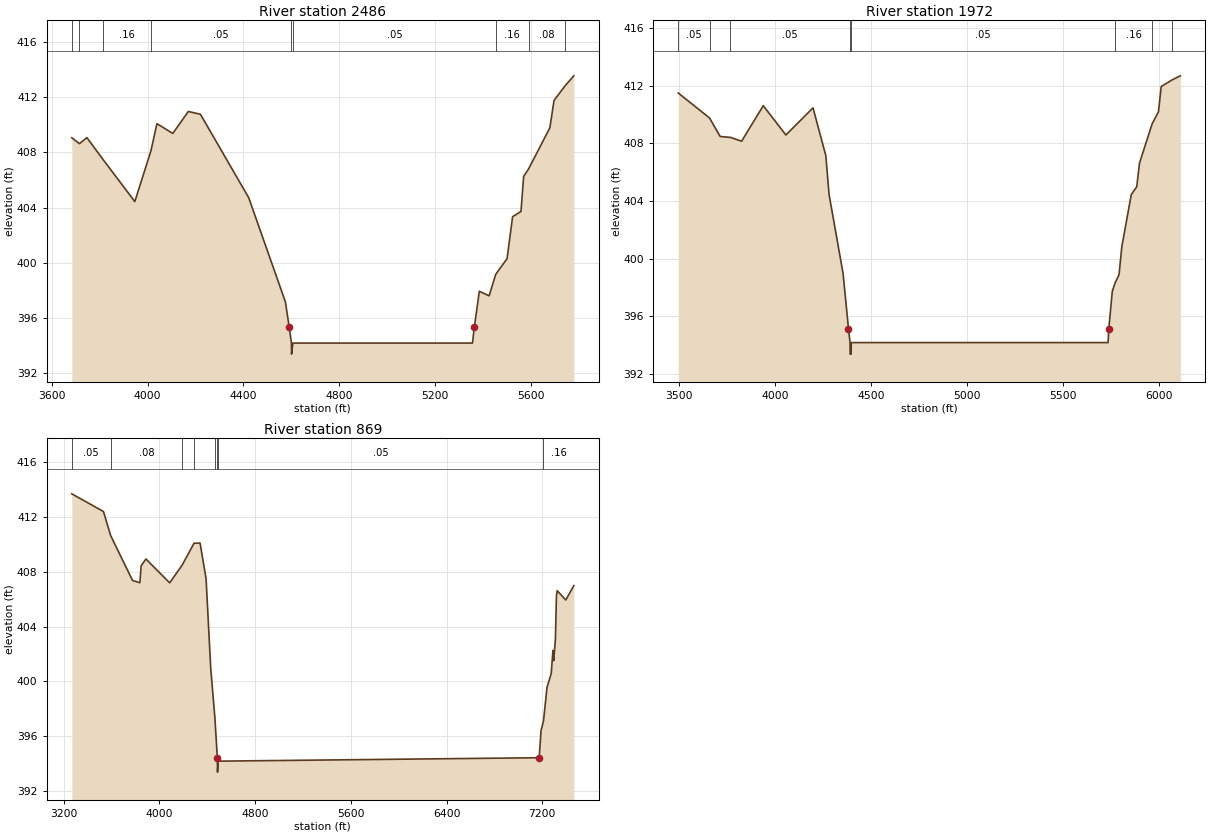
Type RM Length L Ch R = 1,2486,514,514,514
BEGIN DESCRIPTION:
Mapping XS 3fb7070a
END DESCRIPTION:
XS GIS Cut Line= 3
      2904157.63      7011344.33      2902885.89      7011179.39
      2902143.75      7011513.58
#Sta/Elev= 30
  3683.7  409.05  3715.8  408.62  3746.9  409.06  3815.3  407.45  3947.0  404.43
  4014.5  408.12  4039.3  410.07  4105.5  409.36  4170.4  410.95  4220.8  410.75
  4422.5  404.71  4575.7  397.17  4591.8  395.32  4600.9  394.19  4601.4  393.39
  4607.0  394.19  5356.8  394.19  5364.4  395.32  5385.4  397.94  5426.3  397.61
  5453.8  399.16  5501.2  400.30  5524.3  403.34  5559.3  403.71  5570.3  406.24
  5590.9  406.79  5679.9  409.77  5697.3  411.75  5743.4  412.81  5780.0  413.53
#Mann=9,-1,0
  3683.7    0.05       0  3715.8    0.08       0  3815.3    0.16       0
  4014.5    0.05       0  4600.9   0.033       0  4607.0    0.05       0
  5453.8    0.16       0  5590.9    0.08       0  5743.4    0.16       0
Bank Sta=4591.8,5364.4
Exp/Cntr=0.3,0.1

Type RM Length L Ch R = 1,1972,1103,1103,1103
BEGIN DESCRIPTION:
Mapping XS eb7a7b4b
END DESCRIPTION:
XS GIS Cut Line= 3
      2904274.78      7011296.58      2902968.36      7010654.22
      2902088.61      7011408.29
#Sta/Elev= 30
  3496.0  411.49  3659.0  409.76  3714.0  408.48  3768.1  408.41  3826.3  408.15
  3938.7  410.61  4056.7  408.58  4197.8  410.46  4264.7  407.14  4281.4  404.46
  4354.4  398.98  4382.6  395.16  4390.7  394.19  4391.2  393.39  4396.4  393.39
  4396.9  394.19  5734.4  394.19  5738.1  395.16  5756.4  397.75  5770.7  398.32
  5791.5  398.90  5805.8  400.83  5855.2  404.45  5883.7  404.99  5898.0  406.63
  5963.8  409.35  5996.8  410.19  6011.0  411.94  6069.6  412.41  6110.5  412.68
#Mann=8,-1,0
  3496.0    0.05       0  3659.0    0.08       0  3768.1    0.05       0
  4390.7   0.033       0  4396.9    0.05       0  5770.7    0.16       0
  5963.8    0.08       0  6069.6    0.16       0
Bank Sta=4382.6,5738.1
Exp/Cntr=0.3,0.1

Type RM Length L Ch R = 1,869,0,0,0
BEGIN DESCRIPTION:
UNT 039 IN DRY CR WATERSHED 1.0
END DESCRIPTION:
XS GIS Cut Line= 4
      2904374.60      7011166.32      2904205.34      7010150.75
      2903228.77      7009655.96      2901952.76      7011287.87
#Sta/Elev= 30
  3267.5  413.68  3532.4  412.39  3592.3  410.64  3775.7  407.36  3836.6  407.20
  3847.3  408.43  3887.3  408.93  4085.6  407.19  4189.8  408.48  4289.4  410.08
  4339.8  410.09  4390.0  407.48  4428.9  400.96  4463.5  397.37  4484.0  394.44
  4484.9  394.19  4485.4  393.39  4491.1  394.19  7173.6  394.44  7189.4  396.43
  7209.5  397.10  7239.1  399.56  7274.4  400.59  7288.8  402.26  7295.2  401.52
  7309.7  403.13  7317.8  406.22  7324.1  406.62  7396.3  405.94  7463.4  406.99
#Mann=8,-1,0
  3267.5    0.05       0  3592.3    0.08       0  4189.8    0.05       0
  4289.4    0.16       0  4463.5    0.05       0  4484.9   0.033       0
  4491.1    0.05       0  7209.5    0.16       0
Bank Sta=4484,7173.6
Exp/Cntr=0.3,0.1

Chan Stop Cuts=-1