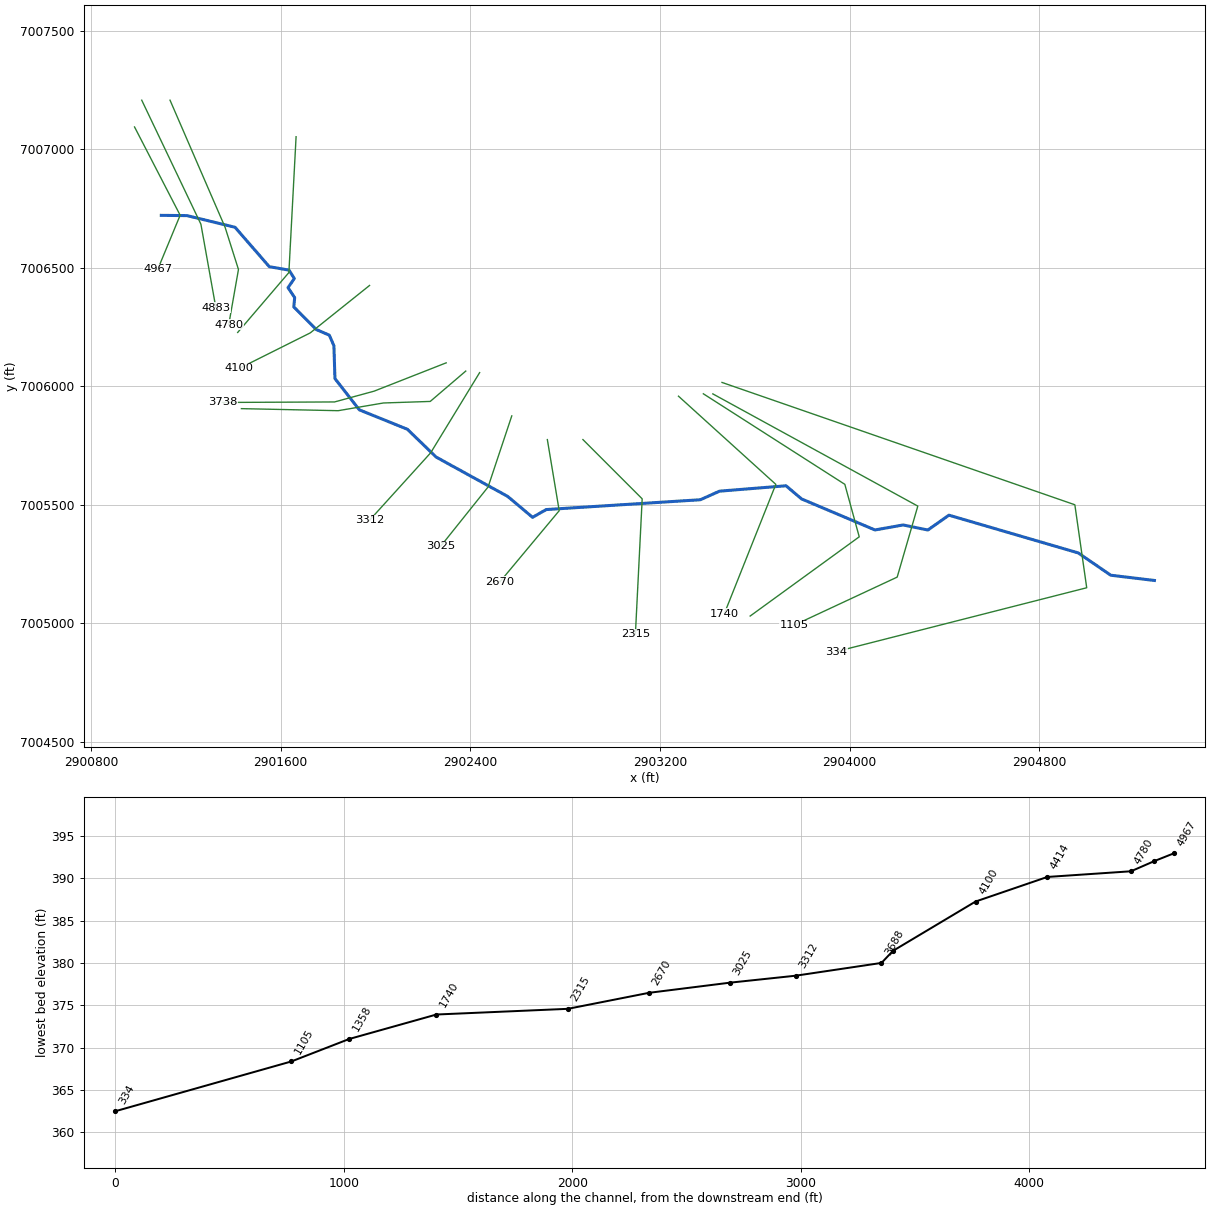
--- UNT 040 IN DRY CR WATERSHED.prj (project) ---

Proj Title=UNT 040 IN DRY CR WATERSHED Base Level Engineering
Current Plan=p01
Default Exp/Contr=0.3,0.1
English Units
Geom File=g01
Flow File=f01
Plan File=p01
BEGIN DESCRIPTION:
UNT 040 IN DRY CR WATERSHED
END DESCRIPTION:

--- UNT 040 IN DRY CR WATERSHED.p01 (plan) ---

Plan Title=Multiple Run
Short Identifier=Multiple
Geom File=g01
Flow File=f01
Subcritical Flow
K Sum by GR= 0
Std Step Tol= 0.01
Critical Tol= 0.01
Num of Std Step Trials= 20
Max Error Tol= 0.3
Flow Tol Ratio= 0.001
Split Flow NTrial= 30
Split Flow Tol= 0.02
Split Flow Ratio= 0.02
Log Output Level= 0
Friction Slope Method= 1
Unsteady Friction Slope Method= 2
Unsteady Bridges Friction Slope Method= 1
Parabolic Critical Depth
Global Vel Dist=  1 , 1 , 1
Global Log Level= 0
CheckData=True
Encroach Param= -1, 0, 0, 0
BEGIN DESCRIPTION:
Multiple Run
END DESCRIPTION:

--- UNT 040 IN DRY CR WATERSHED.f01 (steady flow) ---

Flow Title=Multiple
Number of Profiles=7
Profile Names=10-year,25-year,50-year,1pct_min,100-year,1pct_plu,500-year
River Rch & RM= UNT 040 IN DRY C,Reach-1,4967
     449     593     708     421     840    1676    1182
Boundary for River Rch & Prof#=UNT 040 IN DRY C,Reach-1,1
Up Type=0
Dn Type=3
Dn Slope=0.005
Boundary for River Rch & Prof#=UNT 040 IN DRY C,Reach-1,2
Up Type=0
Dn Type=3
Dn Slope=0.005
Boundary for River Rch & Prof#=UNT 040 IN DRY C,Reach-1,3
Up Type=0
Dn Type=3
Dn Slope=0.005
Boundary for River Rch & Prof#=UNT 040 IN DRY C,Reach-1,4
Up Type=0
Dn Type=3
Dn Slope=0.005
Boundary for River Rch & Prof#=UNT 040 IN DRY C,Reach-1,5
Up Type=0
Dn Type=3
Dn Slope=0.005
Boundary for River Rch & Prof#=UNT 040 IN DRY C,Reach-1,6
Up Type=0
Dn Type=3
Dn Slope=0.005
Boundary for River Rch & Prof#=UNT 040 IN DRY C,Reach-1,7
Up Type=0
Dn Type=3
Dn Slope=0.005

--- UNT 040 IN DRY CR WATERSHED.g01 (geometry) ---

Geom Title=Existing Conditions

River Reach=UNT 040 IN DRY C,Reach-1
Reach XY= 30
      2901096.82      7006720.74      2901205.25      7006719.64
      2901407.64      7006670.52      2901552.18      7006504.26
      2901635.27      7006489.82      2901657.73      7006454.49
      2901631.18      7006415.78      2901659.26      7006373.74
      2901655.55      7006334.48      2901750.20      7006239.24
      2901805.45      7006215.35      2901824.69      7006170.81
      2901829.14      7006032.18      2901931.95      7005900.41
      2902134.66      7005818.45      2902255.82      7005701.26
      2902557.97      7005535.07      2902662.58      7005447.05
      2902720.25      7005479.82      2903370.39      7005521.23
      2903451.29      7005557.43      2903731.71      7005580.11
      2903797.17      7005524.70      2904106.88      7005393.77
      2904225.64      7005414.82      2904329.97      7005393.51
      2904418.78      7005456.13      2904964.03      7005296.96
      2905101.47      7005202.83      2905285.59      7005180.71

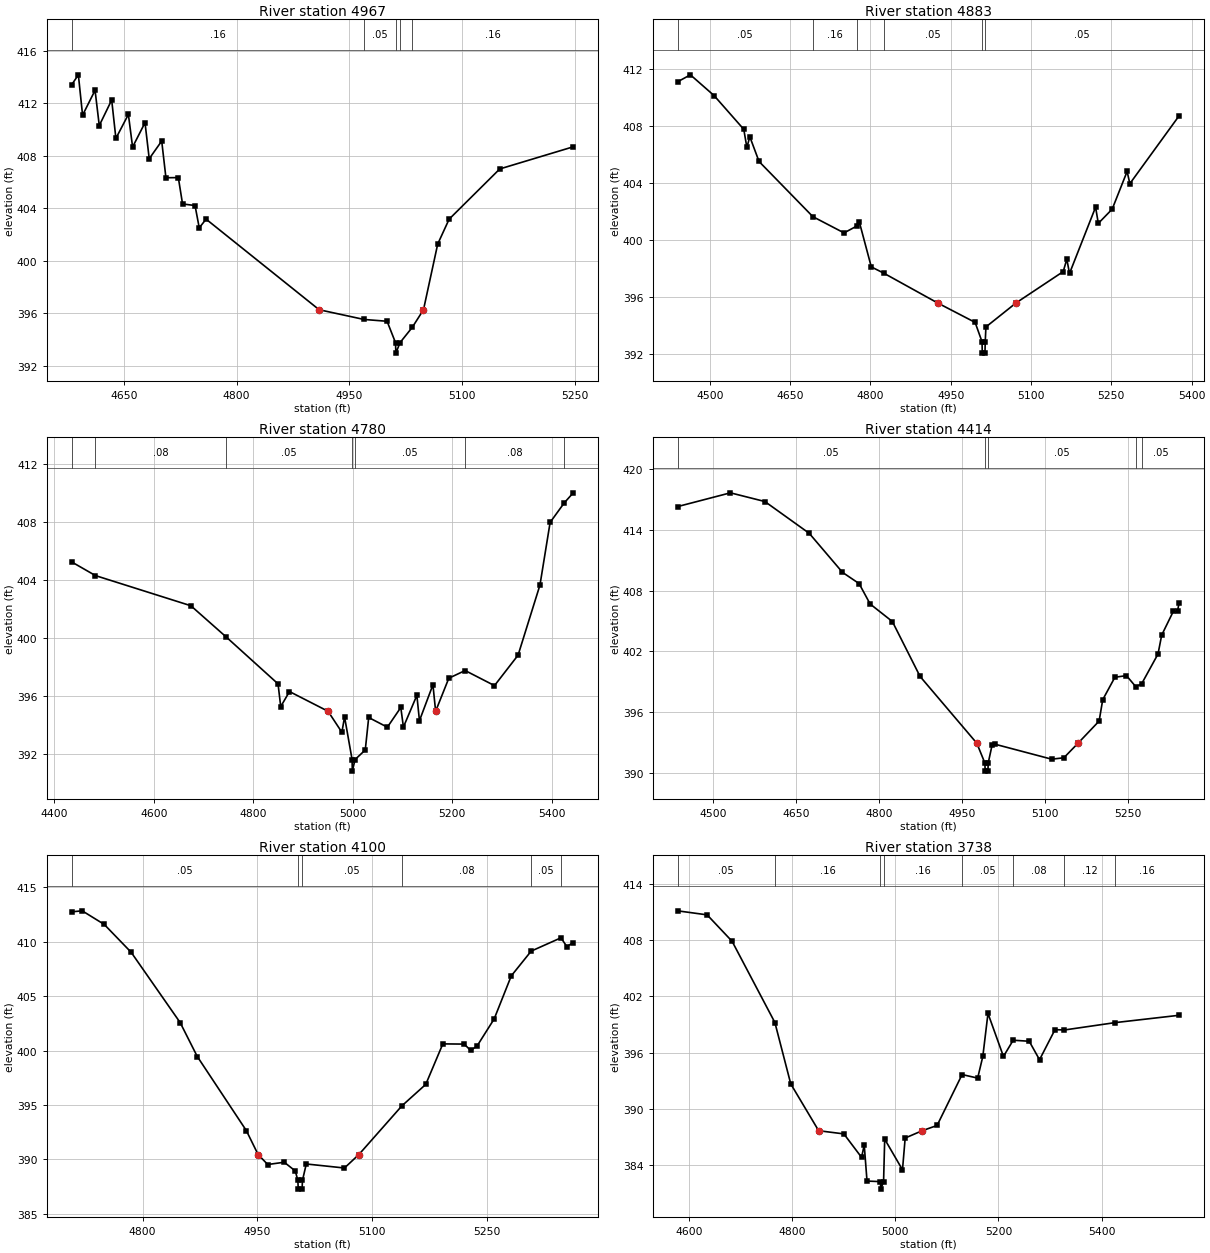
Type RM Length L Ch R = 1,4967,84,84,84
BEGIN DESCRIPTION:
UNT 040 IN DRY CR WATERSHED 8.0
END DESCRIPTION:
XS GIS Cut Line= 3
      2900983.79      7007093.64      2901176.20      7006721.21
      2901081.45      7006492.56
#Sta/Elev= 30
  4580.8  413.43  4589.6  414.18  4595.2  411.10  4611.8  413.00  4617.4  410.31
  4633.9  412.26  4639.5  409.33  4656.1  411.16  4661.7  408.67  4678.2  410.53
  4683.8  407.78  4700.4  409.13  4706.0  406.33  4722.5  406.34  4728.1  404.33
  4744.7  404.21  4750.3  402.51  4759.4  403.17  4909.7  396.26  4969.2  395.52
  5000.0  395.38  5011.2  393.75  5011.7  392.95  5017.2  393.75  5033.4  394.91
  5048.4  396.26  5067.3  401.27  5082.5  403.17  5149.8  407.00  5247.5  408.69
#Mann=5,-1,0
  4580.8    0.16       0  4969.2    0.05       0  5011.2    0.03       0
  5017.2    0.05       0  5033.4    0.16       0
Bank Sta=4909.7,5048.4
Exp/Cntr=0.3,0.1

Type RM Length L Ch R = 1,4883,103,103,103
BEGIN DESCRIPTION:
Mapping XS ea3fe4a8
END DESCRIPTION:
XS GIS Cut Line= 3
      2901014.15      7007206.53      2901263.73      7006683.50
      2901326.66      7006331.91
#Sta/Elev= 30
  4439.9  411.12  4463.8  411.61  4508.1  410.15  4563.5  407.78  4569.3  406.51
  4574.8  407.26  4592.0  405.52  4692.6  401.64  4750.8  400.50  4775.0  400.99
  4779.1  401.30  4801.7  398.11  4825.0  397.67  4925.4  395.58  4995.6  394.21
  5008.5  392.85  5009.0  392.05  5014.0  392.05  5014.5  392.85  5015.8  393.89
  5072.1  395.58  5160.1  397.78  5166.9  398.65  5171.9  397.65  5220.6  402.31
  5225.7  401.17  5251.6  402.17  5279.5  404.82  5284.6  403.96  5376.6  408.73
#Mann=6,-1,0
  4439.9    0.05       0  4692.6    0.16       0  4775.0    0.08       0
  4825.0    0.05       0  5008.5    0.03       0  5014.5    0.05       0
Bank Sta=4925.4,5072.1
Exp/Cntr=0.3,0.1

Type RM Length L Ch R = 1,4780,366,366,366
BEGIN DESCRIPTION:
Mapping XS e39dd9b3
END DESCRIPTION:
XS GIS Cut Line= 4
      2901133.51      7007206.53      2901365.72      7006670.48
      2901422.15      7006492.53      2901381.08      7006259.09
#Sta/Elev= 30
  4435.2  405.27  4482.9  404.33  4674.6  402.25  4746.1  400.08  4849.8  396.86
  4855.2  395.29  4872.8  396.33  4950.3  394.97  4978.1  393.52  4983.5  394.58
  4998.6  391.64  4999.1  390.84  5004.6  391.64  5025.1  392.30  5032.0  394.54
  5069.5  393.87  5096.5  395.23  5101.8  393.88  5128.8  396.07  5134.0  394.32
  5161.1  396.80  5166.5  394.97  5193.0  397.25  5225.8  397.78  5284.8  396.74
  5332.2  398.84  5376.2  403.68  5396.6  408.00  5425.3  409.36  5443.1  410.04
#Mann=7,-1,0
  4435.2    0.05       0  4482.9    0.08       0  4746.1    0.05       0
  4998.6    0.04       0  5004.6    0.05       0  5225.8    0.08       0
  5425.3    0.05       0
Bank Sta=4950.3,5166.5
Exp/Cntr=0.3,0.1

Type RM Length L Ch R = 1,4414,314,314,314
BEGIN DESCRIPTION:
Mapping XS 203a9ee6
END DESCRIPTION:
XS GIS Cut Line= 3
      2901665.20      7007052.44      2901634.82      7006479.51
      2901418.88      7006226.86
#Sta/Elev= 30
  4436.5  416.32  4531.9  417.68  4594.2  416.82  4674.3  413.68  4734.4  409.82
  4764.4  408.71  4784.4  406.69  4824.5  404.96  4874.6  399.53  4977.1  392.93
  4991.7  390.97  4992.2  390.17  4997.2  390.17  4997.7  390.97  5004.7  392.74
  5010.0  392.83  5112.4  391.35  5134.4  391.49  5160.0  392.93  5198.1  395.12
  5204.6  397.23  5226.6  399.45  5247.5  399.61  5264.1  398.53  5274.7  398.78
  5304.5  401.75  5311.1  403.61  5332.0  405.95  5339.7  405.97  5342.6  406.82
#Mann=5,-1,0
  4436.5    0.05       0  4991.7    0.03       0  4997.7    0.05       0
  5264.1    0.08       0  5274.7    0.05       0
Bank Sta=4977.1,5160
Exp/Cntr=0.3,0.1

Type RM Length L Ch R = 1,4100,362,362,362
BEGIN DESCRIPTION:
UNT 040 IN DRY CR WATERSHED 7.0
END DESCRIPTION:
XS GIS Cut Line= 3
      2901975.04      7006425.03      2901725.00      7006225.00
      2901425.01      7006075.01
#Sta/Elev= 30
  4707.4  412.74  4721.1  412.83  4749.9  411.58  4785.1  409.02  4849.1  402.57
  4871.5  399.45  4935.6  392.65  4951.0  390.45  4963.6  389.53  4985.2  389.74
  4999.6  388.94  5003.0  388.07  5003.5  387.27  5008.5  387.27  5009.0  388.07
  5014.0  389.58  5063.9  389.21  5082.8  390.45  5139.0  394.92  5170.2  396.89
  5192.5  400.61  5220.5  400.59  5228.8  400.01  5237.2  400.41  5259.6  402.90
  5282.0  406.86  5308.0  409.13  5346.9  410.35  5354.6  409.55  5363.0  409.92
#Mann=6,-1,0
  4707.4    0.05       0  5003.0    0.03       0  5009.0    0.05       0
  5139.0    0.08       0  5308.0    0.05       0  5346.9    0.16       0
Bank Sta=4951,5082.8
Exp/Cntr=0.3,0.1

Type RM Length L Ch R = 1,3738,50,50,50
BEGIN DESCRIPTION:
Mapping XS 1697d7b7
END DESCRIPTION:
XS GIS Cut Line= 4
      2902298.33      7006098.65      2901994.52      7005979.29
      2901827.42      7005933.72      2901354.34      7005931.55
#Sta/Elev= 30
  4577.8  411.12  4635.1  410.69  4683.5  407.87  4766.5  399.21  4797.3  392.66
  4851.4  387.67  4900.3  387.33  4934.6  384.83  4939.8  386.14  4945.2  382.30
  4971.3  382.24  4971.8  381.44  4977.3  382.24  4979.5  386.77  5014.0  383.50
  5019.2  386.89  5052.2  387.67  5081.1  388.23  5129.6  393.66  5159.8  393.28
  5169.8  395.59  5179.8  400.18  5209.8  395.59  5228.7  397.32  5259.8  397.21
  5279.8  395.24  5309.8  398.45  5327.7  398.41  5426.7  399.20  5550.5  399.98
#Mann=8,-1,0
  4577.8    0.05       0  4766.5    0.16       0  4971.3    0.07       0
  4977.3    0.16       0  5129.6    0.05       0  5228.7    0.08       0
  5327.7    0.12       0  5426.7    0.16       0
Bank Sta=4851.4,5052.2
Exp/Cntr=0.3,0.1

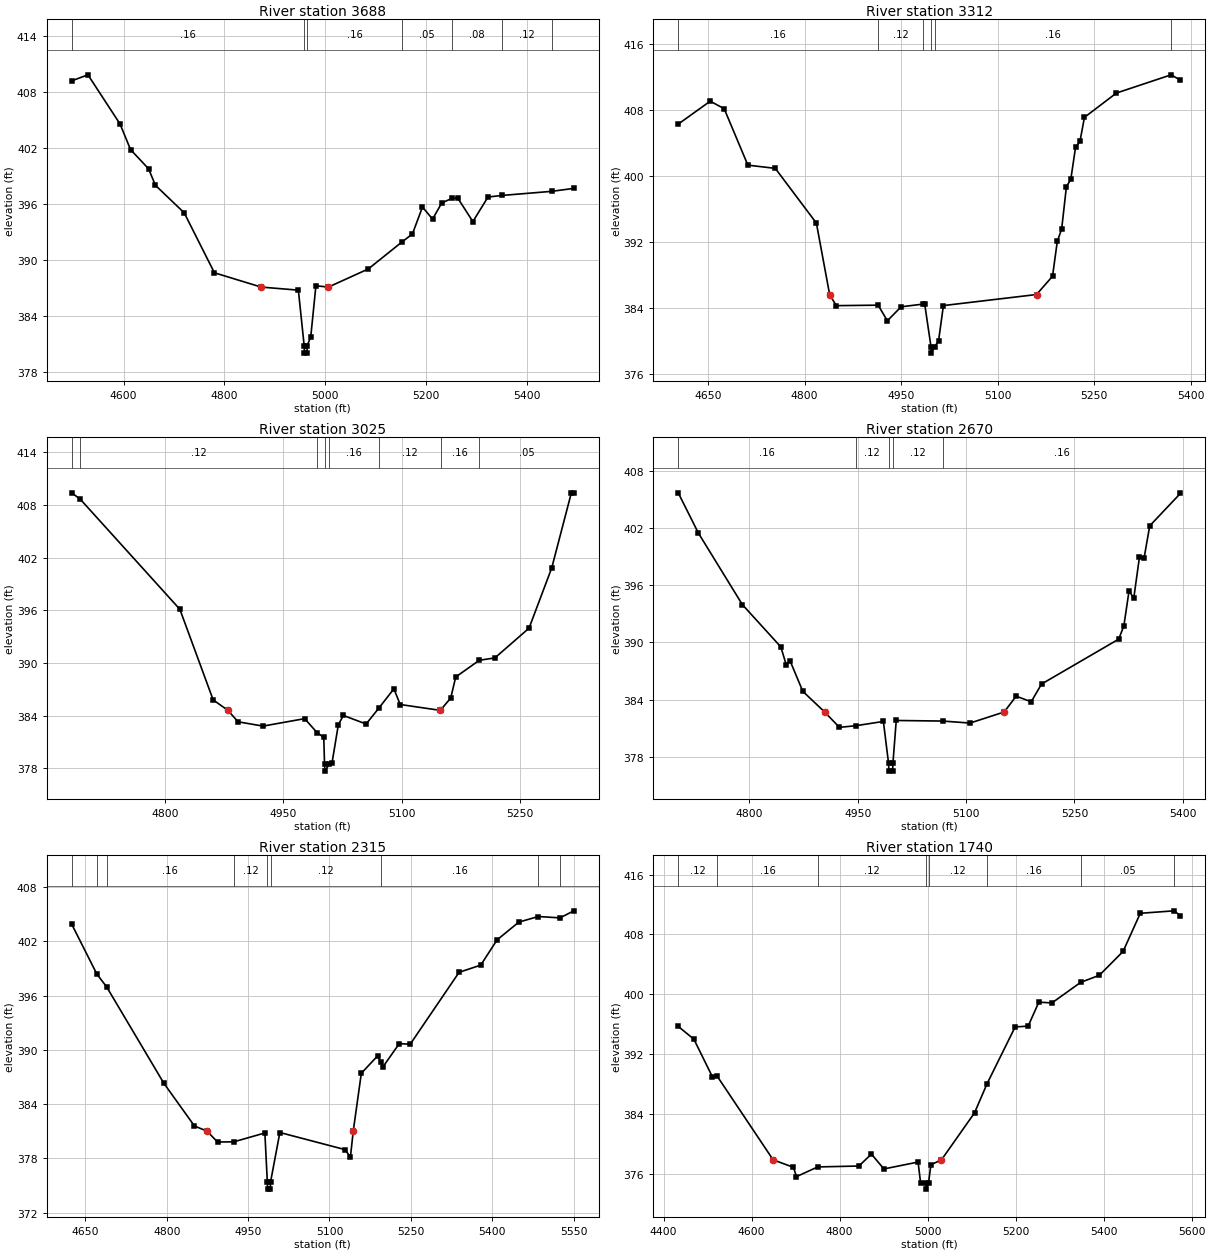
Type RM Length L Ch R = 1,3688,376,376,376
BEGIN DESCRIPTION:
Mapping XS 841ad3e9
END DESCRIPTION:
XS GIS Cut Line= 5
      2902380.82      7006063.94      2902231.06      7005935.89
      2902033.58      7005929.38      2901842.61      7005896.83
      2901434.66      7005905.51
#Sta/Elev= 30
  4497.0  409.21  4529.1  409.85  4592.8  404.58  4613.6  401.84  4649.4  399.78
  4663.0  398.01  4720.1  395.06  4780.1  388.63  4872.9  387.10  4946.7  386.77
  4958.2  380.82  4958.7  380.02  4963.7  380.02  4964.2  380.82  4971.3  381.78
  4981.5  387.24  5006.3  387.10  5085.4  389.04  5152.0  391.92  5173.0  392.79
  5193.0  395.68  5213.0  394.38  5231.3  396.12  5251.1  396.60  5263.0  396.64
  5293.0  394.12  5323.0  396.75  5350.2  396.92  5449.3  397.36  5493.4  397.68
#Mann=7,-1,0
  4497.0    0.16       0  4958.2    0.07       0  4964.2    0.16       0
  5152.0    0.05       0  5251.1    0.08       0  5350.2    0.12       0
  5449.3    0.16       0
Bank Sta=4872.9,5006.3
Exp/Cntr=0.3,0.1

Type RM Length L Ch R = 1,3312,287,287,287
BEGIN DESCRIPTION:
UNT 040 IN DRY CR WATERSHED 5.0
END DESCRIPTION:
XS GIS Cut Line= 3
      2902439.39      7006057.40      2902232.85      7005719.17
      2901975.01      7005434.61
#Sta/Elev= 30
  4603.7  406.30  4653.4  409.08  4675.1  408.17  4711.9  401.32  4754.5  400.93
  4818.4  394.29  4839.0  385.62  4849.3  384.27  4914.4  384.33  4928.7  382.43
  4950.0  384.13  4984.2  384.46  4986.8  384.43  4996.5  379.31  4997.0  378.51
  5002.5  379.31  5008.3  380.01  5015.8  384.28  5160.5  385.62  5185.4  387.84
  5192.8  392.06  5199.6  393.57  5207.0  398.72  5213.8  399.59  5221.2  403.50
  5228.0  404.19  5235.0  407.12  5284.7  410.07  5369.7  412.28  5384.0  411.64
#Mann=6,-1,0
  4603.7    0.16       0  4914.4    0.12       0  4984.2    0.16       0
  4996.5    0.07       0  5002.5    0.16       0  5369.7    0.05       0
Bank Sta=4839,5160.5
Exp/Cntr=0.3,0.1

Type RM Length L Ch R = 1,3025,355,355,355
BEGIN DESCRIPTION:
UNT 040 IN DRY CR WATERSHED 4.0
END DESCRIPTION:
XS GIS Cut Line= 3
      2902575.00      7005875.01      2902475.00      7005575.00
      2902275.00      7005325.00
#Sta/Elev= 30
  4681.9  409.40  4692.9  408.65  4818.9  396.13  4861.1  385.81  4879.7  384.62
  4892.7  383.31  4924.4  382.82  4977.1  383.67  4992.9  382.07  5001.3  381.54
  5002.3  378.49  5002.8  377.69  5008.3  378.49  5011.7  378.57  5019.8  382.99
  5026.2  384.03  5055.0  383.06  5070.8  384.83  5090.2  387.07  5098.2  385.28
  5148.6  384.62  5149.5  384.67  5162.2  386.01  5168.6  388.42  5198.5  390.32
  5218.2  390.59  5261.5  393.98  5290.3  400.85  5315.1  409.39  5318.3  409.39
#Mann=8,-1,0
  4681.9    0.16       0  4692.9    0.12       0  4992.9    0.16       0
  5002.3    0.07       0  5008.3    0.16       0  5070.8    0.12       0
  5149.5    0.16       0  5198.5    0.05       0
Bank Sta=4879.7,5148.6
Exp/Cntr=0.3,0.1

Type RM Length L Ch R = 1,2670,355,355,355
BEGIN DESCRIPTION:
UNT 040 IN DRY CR WATERSHED 3.0
END DESCRIPTION:
XS GIS Cut Line= 3
      2902725.01      7005774.97      2902775.00      7005475.00
      2902525.01      7005175.02
#Sta/Elev= 30
  4701.8  405.67  4729.6  401.46  4790.5  393.95  4843.7  389.52  4851.3  387.62
  4856.4  388.08  4874.1  384.86  4904.3  382.69  4924.8  381.08  4947.5  381.25
  4985.6  381.70  4992.8  377.29  4993.3  376.49  4998.3  376.49  4998.8  377.29
  5003.4  381.80  5067.7  381.74  5105.5  381.53  5152.7  382.69  5169.3  384.35
  5190.1  383.76  5204.4  385.62  5311.2  390.33  5318.3  391.72  5325.5  395.40
  5332.0  394.62  5339.8  398.89  5346.3  398.84  5354.1  402.21  5396.4  405.60
#Mann=5,-1,0
  4701.8    0.16       0  4947.5    0.12       0  4992.8    0.07       0
  4998.8    0.12       0  5067.7    0.16       0
Bank Sta=4904.3,5152.7
Exp/Cntr=0.3,0.1

Type RM Length L Ch R = 1,2315,575,575,575
BEGIN DESCRIPTION:
UNT 040 IN DRY CR WATERSHED 2.0
END DESCRIPTION:
XS GIS Cut Line= 3
      2902875.02      7005774.98      2903125.00      7005525.00
      2903096.37      7004953.64
#Sta/Elev= 30
  4624.9  403.88  4671.3  398.36  4689.1  396.97  4794.6  386.31  4851.1  381.58
  4874.3  381.01  4893.6  379.81  4923.7  379.83  4980.9  380.81  4985.4  375.40
  4985.9  374.60  4990.9  374.60  4991.4  375.40  5008.5  380.86  5128.6  378.97
  5138.6  378.14  5143.8  381.01  5158.7  387.41  5188.7  389.33  5194.5  388.63
  5198.7  388.13  5228.7  390.69  5248.8  390.62  5338.9  398.57  5378.9  399.37
  5409.0  402.16  5449.0  404.12  5484.9  404.74  5524.9  404.59  5550.5  405.37
#Mann=9,-1,0
  4624.9    0.16       0  4671.3    0.12       0  4689.1    0.16       0
  4923.7    0.12       0  4985.4    0.07       0  4991.4    0.12       0
  5194.5    0.16       0  5484.9    0.05       0  5524.9    0.16       0
Bank Sta=4874.3,5143.8
Exp/Cntr=0.3,0.1

Type RM Length L Ch R = 1,1740,382,382,382
BEGIN DESCRIPTION:
Mapping XS 0481dfab
END DESCRIPTION:
XS GIS Cut Line= 3
      2903278.17      7005958.01      2903688.67      7005586.14
      2903471.35      7005040.42
#Sta/Elev= 30
  4433.1  395.69  4468.7  393.98  4510.6  388.97  4521.9  389.01  4648.8  377.85
  4695.1  376.84  4701.8  375.60  4750.2  376.90  4843.8  377.02  4872.2  378.62
  4900.6  376.63  4978.3  377.55  4984.1  374.73  4996.0  374.73  4996.5  373.93
  5002.0  374.73  5007.4  377.19  5031.5  377.85  5106.6  384.13  5135.2  388.04
  5198.9  395.62  5228.5  395.73  5252.8  398.94  5282.5  398.83  5347.8  401.58
  5390.4  402.53  5444.3  405.72  5483.4  410.82  5560.4  411.15  5574.4  410.50
#Mann=8,-1,0
  4433.1    0.12       0  4521.9    0.16       0  4750.2    0.12       0
  4996.0    0.07       0  5002.0    0.12       0  5135.2    0.16       0
  5347.8    0.05       0  5560.4    0.16       0
Bank Sta=4648.8,5031.5
Exp/Cntr=0.3,0.1

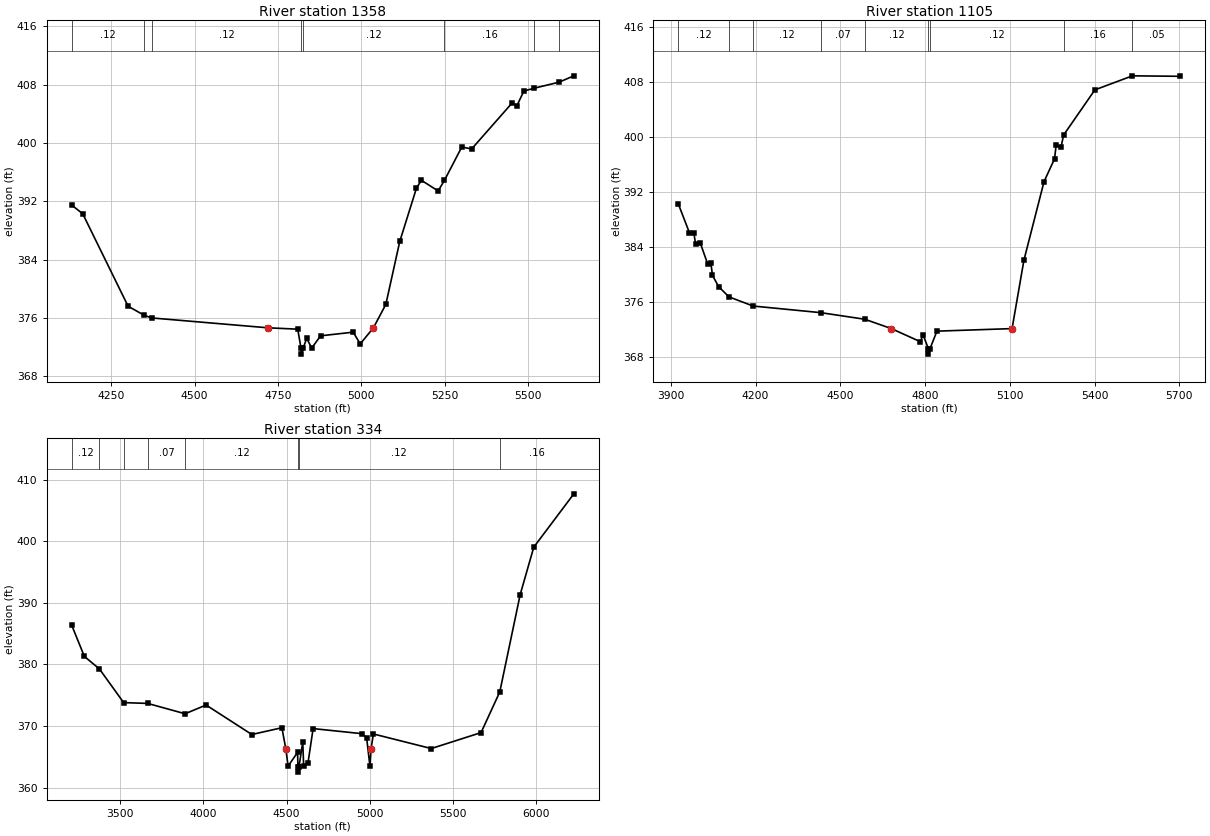
Type RM Length L Ch R = 1,1358,253,253,253
BEGIN DESCRIPTION:
Mapping XS 97cb4e93
END DESCRIPTION:
XS GIS Cut Line= 4
      2903382.96      7005968.15      2903979.74      7005586.21
      2904040.51      7005364.85      2903580.45      7005030.66
#Sta/Elev= 30
  4131.2  391.46  4164.1  390.28  4300.2  377.61  4348.7  376.36  4371.3  376.00
  4719.5  374.65  4809.3  374.46  4819.2  371.84  4819.7  371.04  4825.2  371.84
  4836.2  373.19  4851.4  371.88  4877.9  373.55  4975.8  374.05  4996.8  372.44
  5036.5  374.65  5073.7  377.86  5115.5  386.49  5165.7  393.81  5180.4  394.87
  5230.6  393.41  5249.6  394.86  5301.7  399.44  5331.1  399.16  5452.5  405.46
  5467.2  405.11  5488.0  407.11  5519.5  407.50  5593.6  408.32  5637.9  409.19
#Mann=8,-1,0
  4131.2    0.12       0  4348.7    0.16       0  4371.3    0.12       0
  4819.2    0.07       0  4825.2    0.12       0  5249.6    0.16       0
  5519.5    0.05       0  5593.6    0.16       0
Bank Sta=4719.5,5036.5
Exp/Cntr=0.3,0.1

Type RM Length L Ch R = 1,1105,771,771,771
BEGIN DESCRIPTION:
Mapping XS 78905e77
END DESCRIPTION:
XS GIS Cut Line= 4
      2903423.02      7005967.70      2904287.57      7005494.38
      2904200.63      7005194.93      2903765.99      7004992.09
#Sta/Elev= 30
  3926.4  390.26  3965.9  386.04  3982.0  385.93  3987.7  384.41  4003.8  384.61
  4031.3  381.42  4041.8  381.70  4047.5  379.85  4069.3  378.20  4106.1  376.71
  4191.5  375.38  4430.3  374.42  4586.6  373.46  4680.7  372.10  4783.7  370.19
  4792.8  371.22  4811.6  369.19  4812.1  368.39  4817.6  369.19  4842.1  371.73
  5108.0  372.10  5150.0  382.05  5221.2  393.47  5258.4  396.78  5263.9  398.74
  5281.3  398.49  5290.4  400.23  5401.1  406.80  5534.0  408.84  5703.5  408.77
#Mann=9,-1,0
  3926.4    0.12       0  4106.1    0.16       0  4191.5    0.12       0
  4430.3    0.07       0  4586.6    0.12       0  4811.6    0.07       0
  4817.6    0.12       0  5290.4    0.16       0  5534.0    0.05       0
Bank Sta=4680.7,5108
Exp/Cntr=0.3,0.1

Type RM Length L Ch R = 1,334,0,0,0
BEGIN DESCRIPTION:
UNT 040 IN DRY CR WATERSHED 1.0
END DESCRIPTION:
XS GIS Cut Line= 4
      2903461.71      7006015.98      2904950.00      7005500.00
      2905000.00      7005150.00      2903944.70      7004881.00
#Sta/Elev= 30
  3208.5  386.34  3284.3  381.30  3374.6  379.27  3520.4  373.80  3664.5  373.67
  3889.7  371.99  4015.8  373.41  4290.8  368.62  4471.5  369.72  4495.2  366.26
  4508.7  363.49  4565.7  365.71  4568.0  363.31  4568.5  362.51  4574.0  363.31
  4596.9  367.40  4602.2  363.57  4628.0  363.93  4659.1  369.58  4950.4  368.76
  4980.7  368.11  5000.9  363.43  5007.4  366.26  5021.1  368.71  5369.4  366.34
  5668.7  368.93  5781.1  375.54  5903.7  391.34  5985.5  399.05  6226.3  407.71
#Mann=8,-1,0
  3208.5    0.12       0  3374.6    0.16       0  3520.4    0.12       0
  3664.5    0.07       0  3889.7    0.12       0  4568.0    0.07       0
  4574.0    0.12       0  5781.1    0.16       0
Bank Sta=4495.2,5007.4
Exp/Cntr=0.3,0.1

Chan Stop Cuts=-1