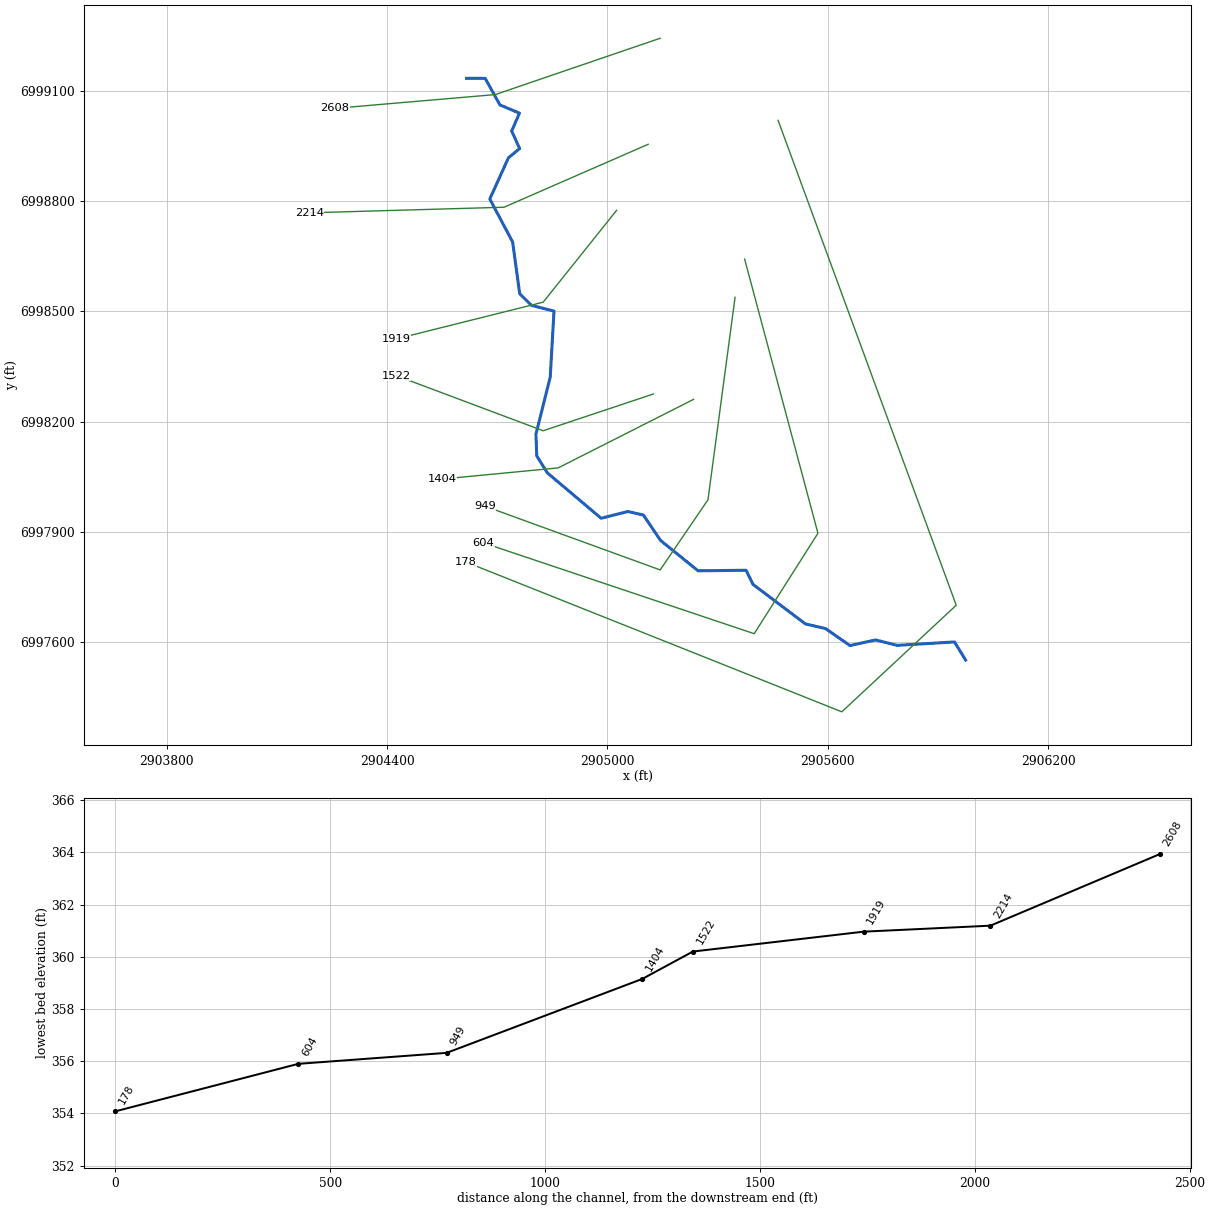
--- UNT 041 IN DRY CR WATERSHED.prj (project) ---

Proj Title=UNT 041 IN DRY CR WATERSHED Base Level Engineering
Current Plan=p01
Default Exp/Contr=0.3,0.1
English Units
Geom File=g01
Flow File=f01
Plan File=p01
BEGIN DESCRIPTION:
UNT 041 IN DRY CR WATERSHED
END DESCRIPTION:

--- UNT 041 IN DRY CR WATERSHED.p01 (plan) ---

Plan Title=Multiple Run
Short Identifier=Multiple
Geom File=g01
Flow File=f01
Subcritical Flow
K Sum by GR= 0
Std Step Tol= 0.01
Critical Tol= 0.01
Num of Std Step Trials= 20
Max Error Tol= 0.3
Flow Tol Ratio= 0.001
Split Flow NTrial= 30
Split Flow Tol= 0.02
Split Flow Ratio= 0.02
Log Output Level= 0
Friction Slope Method= 1
Unsteady Friction Slope Method= 2
Unsteady Bridges Friction Slope Method= 1
Parabolic Critical Depth
Global Vel Dist=  1 , 1 , 1
Global Log Level= 0
CheckData=True
Encroach Param= -1, 0, 0, 0
BEGIN DESCRIPTION:
Multiple Run
END DESCRIPTION:

--- UNT 041 IN DRY CR WATERSHED.f01 (steady flow) ---

Flow Title=Multiple
Number of Profiles=7
Profile Names=10-year,25-year,50-year,1pct_min,100-year,1pct_plu,500-year
River Rch & RM= UNT 041 IN DRY C,Reach-1,2608
     360     467     551     324     646    1290     890
Boundary for River Rch & Prof#=UNT 041 IN DRY C,Reach-1,1
Up Type=0
Dn Type=3
Dn Slope=0.005
Boundary for River Rch & Prof#=UNT 041 IN DRY C,Reach-1,2
Up Type=0
Dn Type=3
Dn Slope=0.005
Boundary for River Rch & Prof#=UNT 041 IN DRY C,Reach-1,3
Up Type=0
Dn Type=3
Dn Slope=0.005
Boundary for River Rch & Prof#=UNT 041 IN DRY C,Reach-1,4
Up Type=0
Dn Type=3
Dn Slope=0.005
Boundary for River Rch & Prof#=UNT 041 IN DRY C,Reach-1,5
Up Type=0
Dn Type=3
Dn Slope=0.005
Boundary for River Rch & Prof#=UNT 041 IN DRY C,Reach-1,6
Up Type=0
Dn Type=3
Dn Slope=0.005
Boundary for River Rch & Prof#=UNT 041 IN DRY C,Reach-1,7
Up Type=0
Dn Type=3
Dn Slope=0.005

--- UNT 041 IN DRY CR WATERSHED.g01 (geometry) ---

Geom Title=Existing Conditions

River Reach=UNT 041 IN DRY C,Reach-1
Reach XY= 30
      2904616.62      6999134.47      2904667.12      6999134.37
      2904707.21      6999062.11      2904760.39      6999039.66
      2904739.25      6998991.03      2904760.90      6998943.21
      2904730.42      6998918.14      2904679.62      6998805.87
      2904741.81      6998689.15      2904761.08      6998547.89
      2904793.13      6998516.41      2904854.49      6998500.71
      2904844.28      6998321.25      2904805.33      6998165.60
      2904807.54      6998106.59      2904836.18      6998060.51
      2904982.84      6997936.74      2905055.74      6997955.12
      2905098.11      6997945.46      2905144.51      6997876.54
      2905246.97      6997793.65      2905377.66      6997795.18
      2905396.32      6997756.77      2905539.23      6997649.10
      2905593.86      6997636.50      2905660.64      6997590.16
      2905730.50      6997605.46      2905789.24      6997590.70
      2905945.27      6997599.98      2905975.59      6997550.71

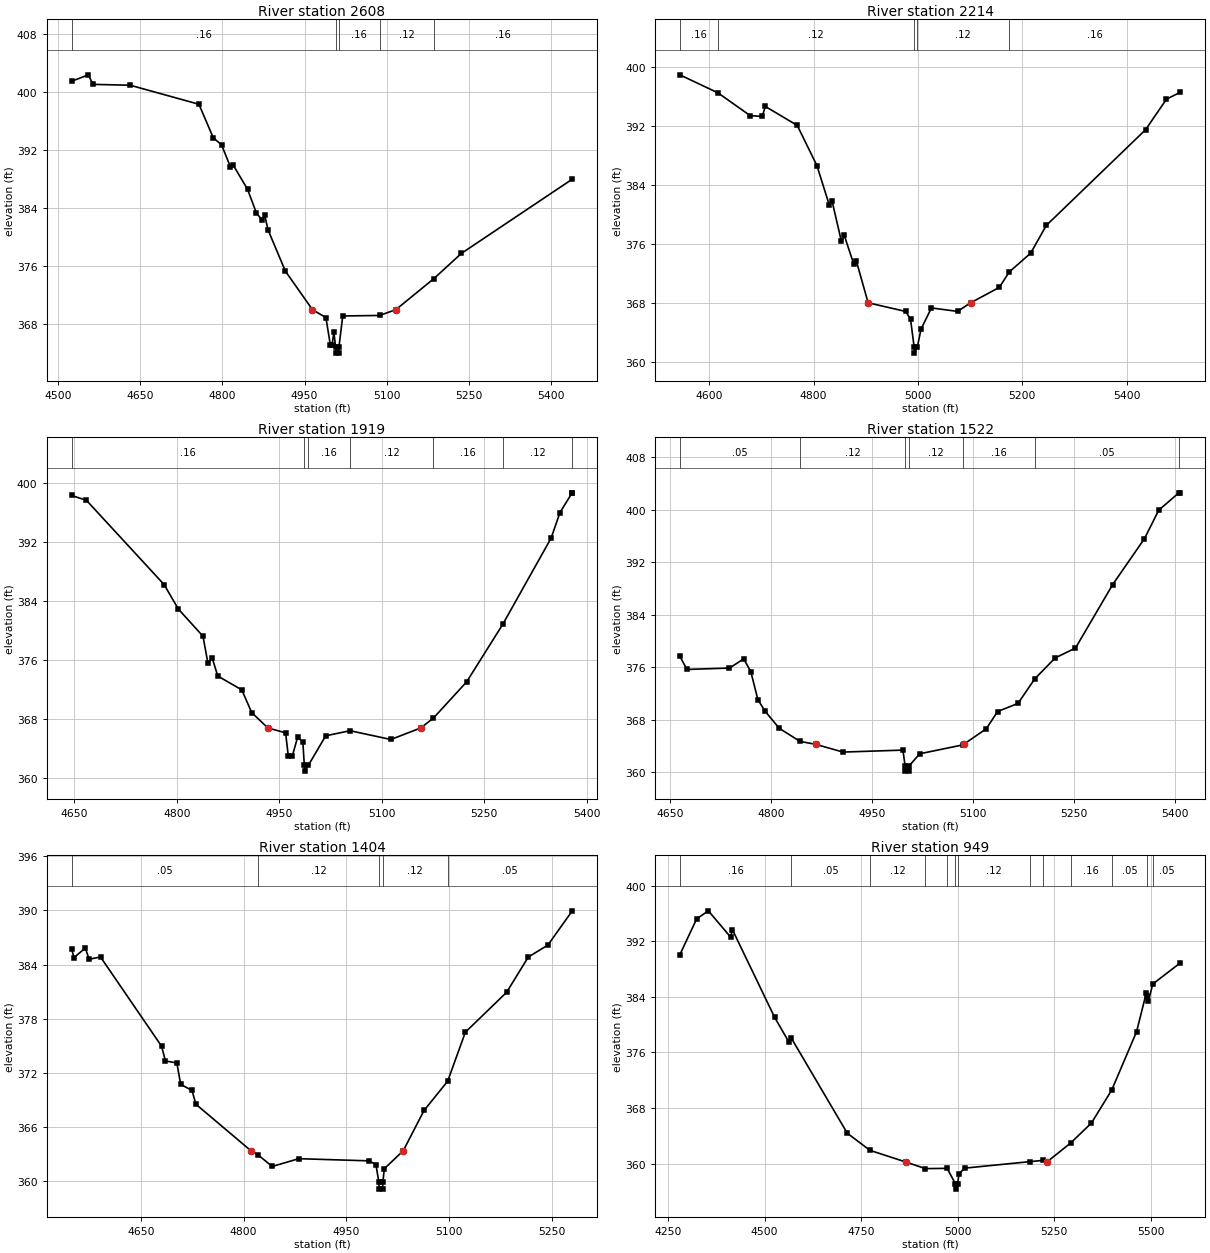
Type RM Length L Ch R = 1,2608,394,394,394
BEGIN DESCRIPTION:
UNT 041 IN DRY CR WATERSHED 4.0
END DESCRIPTION:
XS GIS Cut Line= 3
      2905143.68      6999243.56      2904694.54      6999090.21
      2904258.04      6999052.75
#Sta/Elev= 30
  4525.4  401.53  4555.7  402.42  4564.2  401.10  4632.1  400.98  4757.4  398.35
  4783.5  393.72  4798.7  392.73  4814.8  389.69  4820.1  389.91  4846.1  386.58
  4862.1  383.32  4872.1  382.38  4877.4  382.97  4883.3  380.99  4915.0  375.27
  4964.4  369.94  4988.9  368.85  4997.1  365.02  5000.0  365.02  5003.5  366.81
  5006.6  364.73  5007.1  363.93  5012.1  363.93  5012.6  364.73  5019.6  369.07
  5086.8  369.14  5116.4  369.94  5186.0  374.25  5235.9  377.72  5438.1  387.99
#Mann=5,-1,0
  4525.4    0.16       0  5006.6    0.07       0  5012.6    0.16       0
  5086.8    0.12       0  5186.0    0.16       0
Bank Sta=4964.4,5116.4
Exp/Cntr=0.3,0.1

Type RM Length L Ch R = 1,2214,295,295,295
BEGIN DESCRIPTION:
Mapping XS 5043b3e5
END DESCRIPTION:
XS GIS Cut Line= 3
      2905111.10      6998954.92      2904718.32      6998783.49
      2904188.30      6998768.34
#Sta/Elev= 30
  4543.9  399.00  4617.0  396.55  4678.6  393.46  4702.0  393.34  4707.5  394.71
  4768.8  392.13  4806.6  386.66  4830.0  381.35  4835.4  381.90  4853.4  376.37
  4858.8  377.21  4876.8  373.35  4882.3  373.64  4904.6  368.03  4976.6  366.85
  4985.8  365.80  4992.8  361.99  4993.3  361.19  4998.8  361.99  5005.8  364.43
  5025.8  367.33  5075.8  366.86  5101.0  368.03  5155.9  370.12  5174.8  372.21
  5215.9  374.77  5245.9  378.54  5436.0  391.54  5476.0  395.69  5502.7  396.64
#Mann=5,-1,0
  4543.9    0.16       0  4617.0    0.12       0  4992.8    0.07       0
  4998.8    0.12       0  5174.8    0.16       0
Bank Sta=4904.6,5101
Exp/Cntr=0.3,0.1

Type RM Length L Ch R = 1,1919,397,397,397
BEGIN DESCRIPTION:
UNT 041 IN DRY CR WATERSHED 3.0
END DESCRIPTION:
XS GIS Cut Line= 3
      2905025.01      6998775.02      2904825.00      6998525.00
      2904424.99      6998425.00
#Sta/Elev= 30
  4646.2  398.34  4667.8  397.68  4781.5  386.25  4802.3  382.93  4838.3  379.26
  4845.5  375.62  4851.9  376.28  4859.9  373.86  4895.1  371.98  4909.6  368.90
  4933.2  366.82  4959.2  366.15  4963.2  362.99  4969.0  362.99  4976.7  365.53
  4984.4  364.95  4986.6  361.76  4987.1  360.96  4992.6  361.76  5017.9  365.75
  5053.5  366.44  5113.3  365.25  5157.1  366.82  5175.5  368.15  5224.1  373.06
  5277.0  380.87  5347.8  392.57  5360.7  396.03  5378.5  398.70  5378.7  398.70
#Mann=7,-1,0
  4646.2    0.16       0  4986.6    0.07       0  4992.6    0.16       0
  5053.5    0.12       0  5175.5    0.16       0  5277.0    0.12       0
  5378.5    0.16       0
Bank Sta=4933.2,5157.1
Exp/Cntr=0.3,0.1

Type RM Length L Ch R = 1,1522,118,118,118
BEGIN DESCRIPTION:
UNT 041 IN DRY CR WATERSHED 2.0
END DESCRIPTION:
XS GIS Cut Line= 3
      2905125.03      6998275.01      2904825.00      6998175.00
      2904424.96      6998325.01
#Sta/Elev= 30
  4664.4  377.70  4675.0  375.68  4738.2  375.89  4759.3  377.29  4769.8  375.36
  4780.4  371.07  4790.9  369.35  4812.0  366.73  4842.8  364.73  4866.1  364.28
  4906.9  363.10  4995.8  363.40  4999.0  361.00  4999.5  360.20  5004.5  360.20
  5005.0  361.00  5020.7  362.84  5085.0  364.20  5086.0  364.28  5119.5  366.64
  5136.4  369.27  5166.7  370.51  5191.7  374.26  5221.9  377.43  5252.1  378.94
  5307.3  388.60  5354.5  395.59  5375.8  399.93  5405.6  402.57  5407.9  402.57
#Mann=7,-1,0
  4664.4    0.05       0  4842.8    0.12       0  4999.0    0.07       0
  5005.0    0.12       0  5085.0    0.16       0  5191.7    0.05       0
  5405.6    0.16       0
Bank Sta=4866.1,5086
Exp/Cntr=0.3,0.1

Type RM Length L Ch R = 1,1404,455,455,455
BEGIN DESCRIPTION:
Mapping XS ae8c0c22
END DESCRIPTION:
XS GIS Cut Line= 3
      2905234.77      6998260.46      2904865.89      6998073.85
      2904549.54      6998043.52
#Sta/Elev= 30
  4549.0  385.76  4552.2  384.77  4568.9  385.84  4574.5  384.60  4591.1  384.85
  4680.3  374.97  4685.9  373.34  4702.6  373.12  4708.2  370.75  4724.8  370.07
  4730.4  368.55  4810.8  363.40  4821.7  362.91  4841.9  361.66  4880.8  362.52
  4983.4  362.28  4993.4  361.87  4997.6  359.95  4998.1  359.15  5003.1  359.15
  5003.6  359.95  5005.6  361.41  5033.3  363.40  5063.7  367.86  5098.2  371.10
  5124.0  376.52  5184.3  380.94  5215.9  384.84  5244.6  386.17  5280.2  389.96
#Mann=5,-1,0
  4549.0    0.05       0  4821.7    0.12       0  4997.6    0.07       0
  5003.6    0.12       0  5098.2    0.05       0
Bank Sta=4810.8,5033.3
Exp/Cntr=0.3,0.1

Type RM Length L Ch R = 1,949,345,345,345
BEGIN DESCRIPTION:
Mapping XS 80e5e22d
END DESCRIPTION:
XS GIS Cut Line= 4
      2905347.66      6998538.27      2905273.88      6997987.05
      2905143.67      6997796.07      2904666.23      6997969.69
#Sta/Elev= 30
  4280.8  390.04  4324.5  395.21  4354.7  396.36  4412.1  392.59  4417.1  393.63
  4526.2  381.03  4563.1  377.48  4569.1  378.07  4714.1  364.37  4772.8  361.90
  4867.3  360.19  4916.3  359.27  4972.3  359.31  4993.8  357.12  4994.3  356.32
  4999.8  357.12  5003.2  358.53  5018.1  359.34  5185.8  360.27  5221.0  360.46
  5229.9  360.19  5292.0  362.95  5345.8  365.82  5398.3  370.56  5462.8  378.98
  5488.1  384.60  5490.1  384.13  5493.4  383.36  5504.6  385.83  5576.1  388.88
#Mann=13,-1,0
  4280.8    0.16       0  4569.1    0.05       0  4772.8    0.12       0
  4916.3    0.05       0  4972.3    0.12       0  4993.8    0.07       0
  4999.8    0.12       0  5185.8    0.16       0  5221.0    0.12       0
  5292.0    0.16       0  5398.3    0.05       0  5490.1    0.16       0
  5504.6    0.05       0
Bank Sta=4867.3,5229.9
Exp/Cntr=0.3,0.1

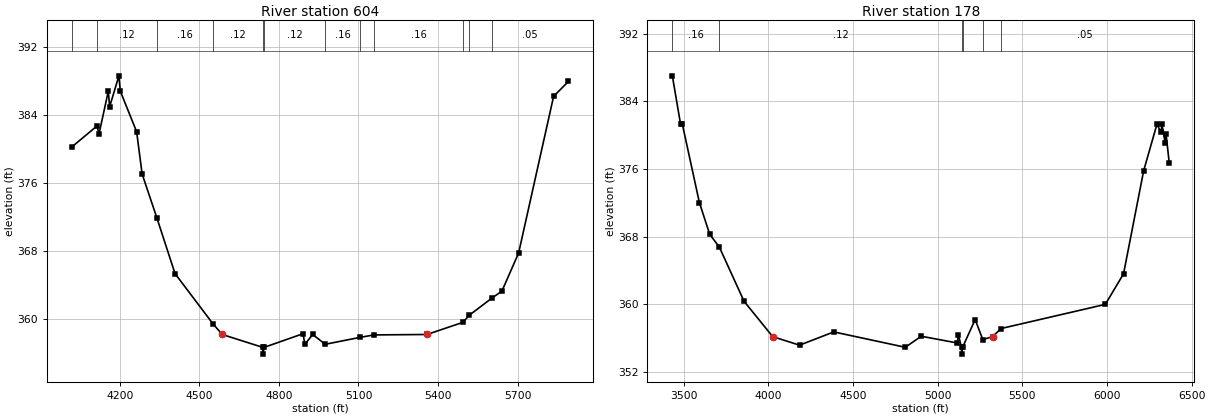
Type RM Length L Ch R = 1,604,426,426,426
BEGIN DESCRIPTION:
Mapping XS 202e9246
END DESCRIPTION:
XS GIS Cut Line= 4
      2905373.71      6998642.38      2905573.35      6997895.90
      2905399.74      6997622.46      2904661.93      6997869.85
#Sta/Elev= 30
  4017.4  380.24  4113.5  382.74  4121.3  381.82  4156.1  386.82  4161.3  385.02
  4196.2  388.64  4201.4  386.84  4263.1  382.06  4283.8  377.09  4339.4  371.93
  4408.0  365.37  4551.4  359.45  4586.1  358.21  4738.4  356.70  4738.9  355.90
  4744.4  356.70  4890.8  358.30  4897.8  357.05  4927.2  358.21  4974.8  357.06
  5107.5  357.88  5159.0  358.16  5358.3  358.21  5494.1  359.64  5518.0  360.48
  5603.8  362.50  5641.1  363.31  5704.2  367.80  5836.2  386.23  5892.2  387.98
#Mann=12,-1,0
  4017.4    0.16       0  4113.5    0.12       0  4339.4    0.16       0
  4551.4    0.12       0  4738.4    0.07       0  4744.4    0.12       0
  4974.8    0.16       0  5107.5    0.05       0  5159.0    0.16       0
  5494.1    0.05       0  5518.0    0.16       0  5603.8    0.05       0
Bank Sta=4586.1,5358.3
Exp/Cntr=0.3,0.1

Type RM Length L Ch R = 1,178,0,0,0
BEGIN DESCRIPTION:
UNT 041 IN DRY CR WATERSHED 1.0
END DESCRIPTION:
XS GIS Cut Line= 4
      2905464.86      6999019.99      2905950.00      6997700.00
      2905638.46      6997409.79      2904614.11      6997817.79
#Sta/Elev= 30
  3433.1  387.03  3481.7  381.31  3491.7  381.35  3592.9  372.02  3653.9  368.26
  3710.6  366.76  3856.5  360.34  4025.9  356.15  4184.2  355.14  4386.6  356.71
  4808.9  354.89  4902.9  356.20  5115.5  355.40  5122.3  356.37  5140.8  354.88
  5141.3  354.08  5146.8  354.88  5221.5  358.17  5266.6  355.80  5324.4  356.15
  5374.2  357.11  5990.1  359.97  6097.7  363.59  6216.6  375.80  6294.8  381.29
  6319.1  380.33  6324.4  381.29  6343.3  379.11  6348.7  380.16  6367.8  376.66
#Mann=6,-1,0
  3433.1    0.16       0  3710.6    0.12       0  5140.8    0.07       0
  5146.8    0.12       0  5266.6    0.07       0  5374.2    0.05       0
Bank Sta=4025.9,5324.4
Exp/Cntr=0.3,0.1

Chan Stop Cuts=-1