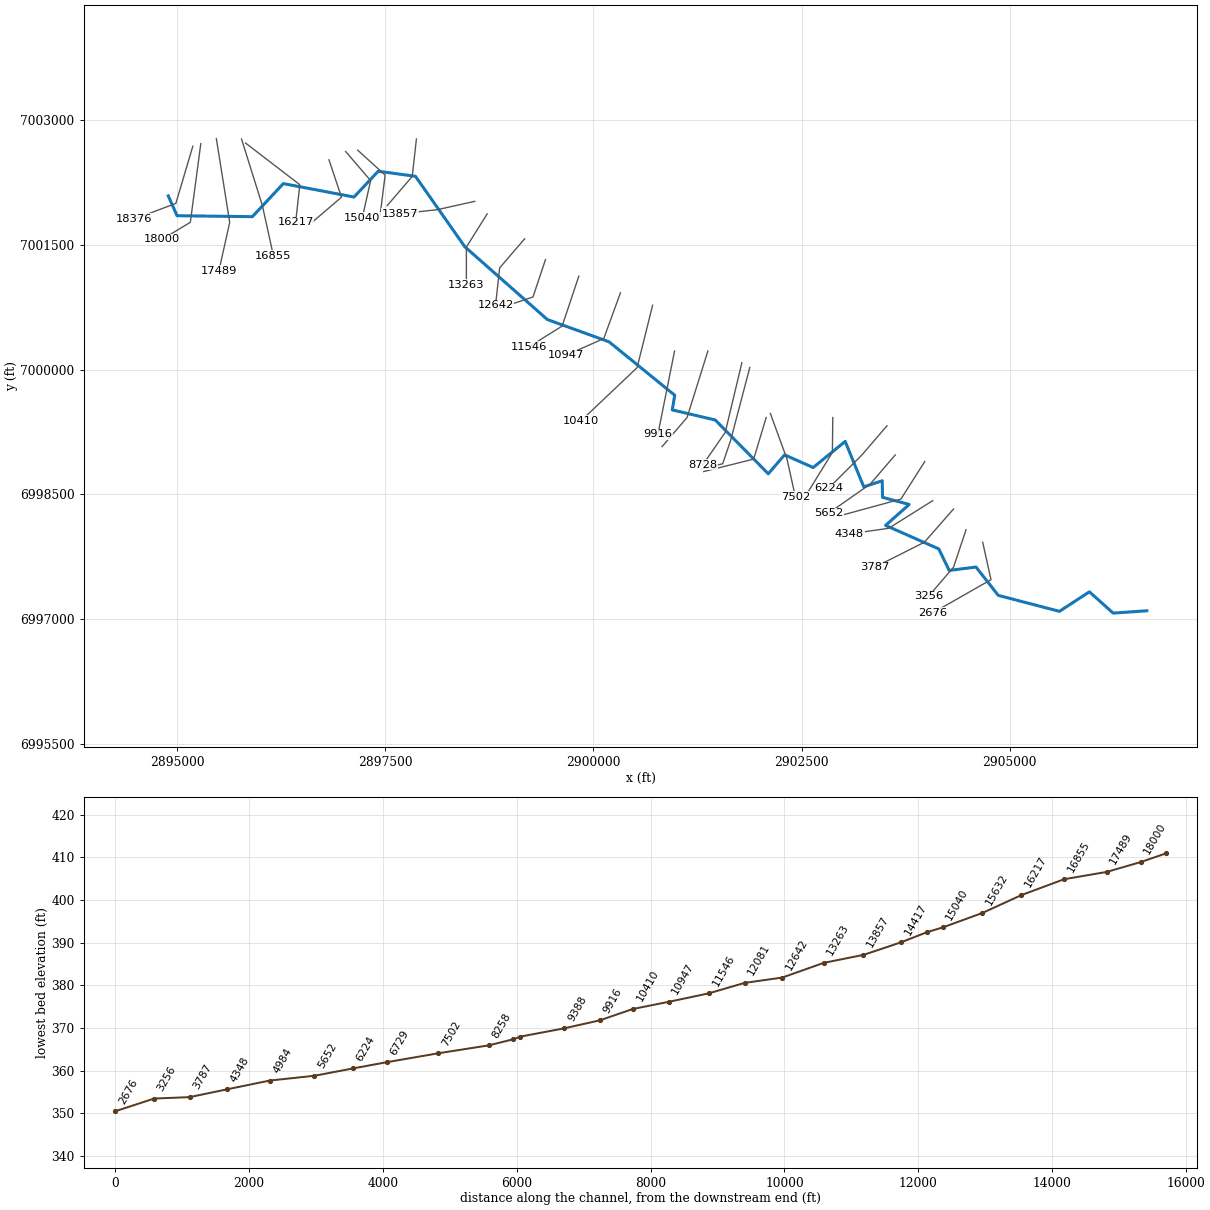
--- UNT 042 IN DRY CR WATERSHED.prj (project) ---

Proj Title=UNT 042 IN DRY CR WATERSHED Base Level Engineering
Current Plan=p01
Default Exp/Contr=0.3,0.1
English Units
Geom File=g01
Flow File=f01
Plan File=p01
BEGIN DESCRIPTION:
UNT 042 IN DRY CR WATERSHED
END DESCRIPTION:

--- UNT 042 IN DRY CR WATERSHED.p01 (plan) ---

Plan Title=Multiple Run
Short Identifier=Multiple
Geom File=g01
Flow File=f01
Subcritical Flow
K Sum by GR= 0
Std Step Tol= 0.01
Critical Tol= 0.01
Num of Std Step Trials= 20
Max Error Tol= 0.3
Flow Tol Ratio= 0.001
Split Flow NTrial= 30
Split Flow Tol= 0.02
Split Flow Ratio= 0.02
Log Output Level= 0
Friction Slope Method= 1
Unsteady Friction Slope Method= 2
Unsteady Bridges Friction Slope Method= 1
Parabolic Critical Depth
Global Vel Dist=  1 , 1 , 1
Global Log Level= 0
CheckData=True
Encroach Param= -1, 0, 0, 0
BEGIN DESCRIPTION:
Multiple Run
END DESCRIPTION:

--- UNT 042 IN DRY CR WATERSHED.f01 (steady flow) ---

Flow Title=Multiple
Number of Profiles=7
Profile Names=10-year,25-year,50-year,1pct_min,100-year,1pct_plu,500-year
River Rch & RM= UNT 042 IN DRY C,Reach-1,18376
     608     822     999     604    1204    2403    1753
River Rch & RM= UNT 042 IN DRY C,Reach-1,16855
     927    1281    1579     966    1927    3845    2879
River Rch & RM= UNT 042 IN DRY C,Reach-1,12642
    1158    1615    2001    1230    2454    4896    3701
River Rch & RM= UNT 042 IN DRY C,Reach-1,7502
    1217    1696    2100    1289    2572    5131    3869
Boundary for River Rch & Prof#=UNT 042 IN DRY C,Reach-1,1
Up Type=0
Dn Type=3
Dn Slope=0.005
Boundary for River Rch & Prof#=UNT 042 IN DRY C,Reach-1,2
Up Type=0
Dn Type=3
Dn Slope=0.005
Boundary for River Rch & Prof#=UNT 042 IN DRY C,Reach-1,3
Up Type=0
Dn Type=3
Dn Slope=0.005
Boundary for River Rch & Prof#=UNT 042 IN DRY C,Reach-1,4
Up Type=0
Dn Type=3
Dn Slope=0.005
Boundary for River Rch & Prof#=UNT 042 IN DRY C,Reach-1,5
Up Type=0
Dn Type=3
Dn Slope=0.005
Boundary for River Rch & Prof#=UNT 042 IN DRY C,Reach-1,6
Up Type=0
Dn Type=3
Dn Slope=0.005
Boundary for River Rch & Prof#=UNT 042 IN DRY C,Reach-1,7
Up Type=0
Dn Type=3
Dn Slope=0.005

--- UNT 042 IN DRY CR WATERSHED.g01 (geometry) ---

Geom Title=Existing Conditions

River Reach=UNT 042 IN DRY C,Reach-1
Reach XY= 30
      2894895.59      7002090.71      2895000.30      7001852.43
      2895904.65      7001840.75      2896277.02      7002238.73
      2897125.37      7002076.97      2897416.29      7002387.31
      2897863.33      7002326.62      2898456.22      7001479.38
      2899447.02      7000603.72      2900188.44      7000335.62
      2900977.41      6999692.65      2900947.03      6999516.87
      2901463.52      6999395.34      2902100.30      6998748.45
      2902296.29      6998976.18      2902639.30      6998823.58
      2903023.81      6999137.61      2903247.07      6998591.10
      2903468.89      6998664.51      2903472.31      6998465.40
      2903792.55      6998379.24      2903508.49      6998127.44
      2904147.69      6997844.88      2904272.72      6997585.68
      2904594.24      6997626.98      2904862.39      6997285.94
      2905596.72      6997093.79      2905956.36      6997328.68
      2906241.65      6997072.65      2906645.59      6997100.71

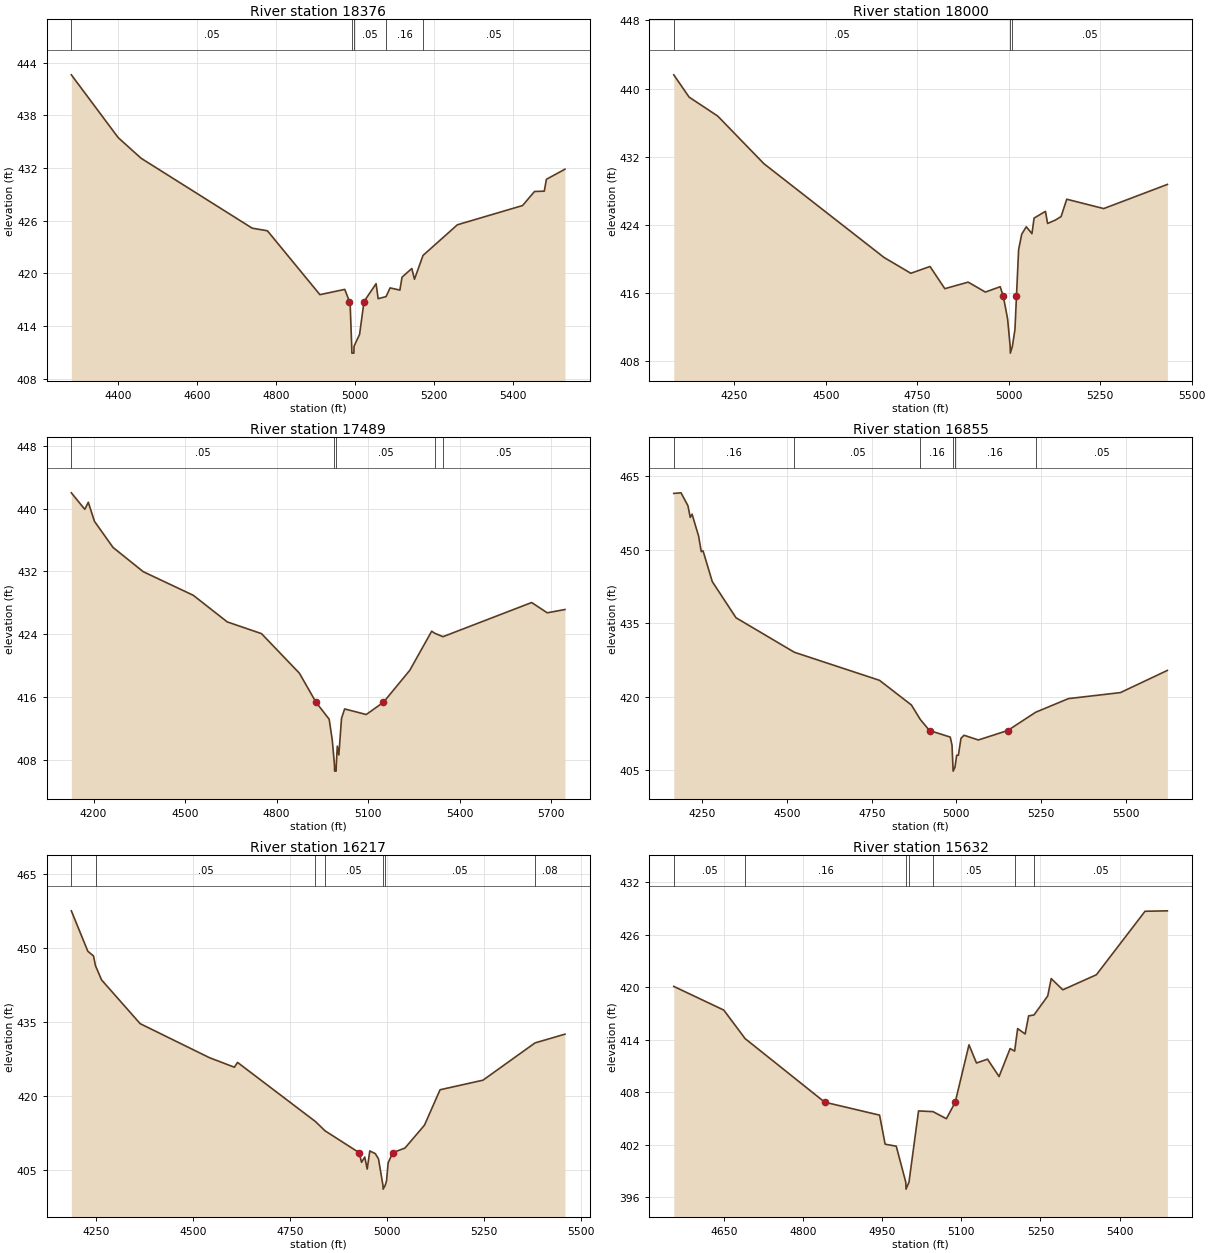
Type RM Length L Ch R = 1,18376,376,376,376
BEGIN DESCRIPTION:
UNT 042 IN DRY CR WATERSHED 26.0
END DESCRIPTION:
XS GIS Cut Line= 3
      2895190.35      7002688.72      2894986.23      7002000.56
      2894488.58      7001812.47
#Sta/Elev= 30
  4282.2  442.61  4400.8  435.46  4458.7  433.11  4740.2  425.14  4778.6  424.85
  4911.6  417.57  4974.5  418.17  4986.4  416.79  4988.4  416.20  4992.1  411.71
  4992.6  410.91  4997.6  410.91  4998.1  411.71  5012.0  413.04  5023.3  416.79
  5053.8  418.82  5059.1  417.11  5079.1  417.35  5089.3  418.34  5114.1  418.09
  5119.5  419.56  5144.3  420.55  5151.0  419.33  5172.7  422.04  5259.7  425.53
  5424.7  427.72  5454.9  429.32  5479.7  429.36  5485.1  430.71  5532.0  431.86
#Mann=5,-1,0
  4282.2    0.05       0  4992.1    0.03       0  4998.1    0.05       0
  5079.1    0.16       0  5172.7    0.05       0
Bank Sta=4986.4,5023.3
Exp/Cntr=0.3,0.1

Type RM Length L Ch R = 1,18000,511,511,511
BEGIN DESCRIPTION:
Mapping XS 78ac5510
END DESCRIPTION:
XS GIS Cut Line= 3
      2895285.84      7002719.11      2895159.96      7001772.89
      2894822.37      7001569.47
#Sta/Elev= 30
  4084.9  441.61  4126.8  438.99  4205.0  436.76  4331.2  431.16  4659.5  420.13
  4732.7  418.27  4785.1  419.07  4825.5  416.46  4889.3  417.23  4936.4  416.06
  4976.8  416.69  4985.4  415.55  4997.0  412.93  5004.1  409.68  5004.6  408.88
  5010.1  409.68  5017.2  411.67  5021.3  415.55  5027.2  421.06  5035.7  422.87
  5048.1  423.74  5063.6  422.93  5069.4  424.76  5100.5  425.55  5106.3  424.13
  5127.7  424.53  5143.2  424.94  5158.7  426.98  5259.7  425.88  5433.6  428.72
#Mann=3,-1,0
  4084.9    0.05       0  5004.1    0.03       0  5010.1    0.05       0
Bank Sta=4985.4,5021.3
Exp/Cntr=0.3,0.1

Type RM Length L Ch R = 1,17489,634,634,634
BEGIN DESCRIPTION:
Mapping XS f0558840
END DESCRIPTION:
XS GIS Cut Line= 3
      2895472.46      7002779.87      2895633.05      7001772.89
      2895503.18      7001188.46
#Sta/Elev= 30
  4127.2  442.00  4171.3  439.90  4182.8  440.80  4203.0  438.37  4263.8  435.05
  4362.8  431.96  4527.1  428.95  4638.5  425.56  4750.7  424.07  4875.0  419.03
  4929.4  415.33  4972.6  413.17  4982.8  410.49  4989.9  407.36  4990.4  406.56
  4995.4  406.56  4995.9  407.36  4999.2  409.74  5004.3  408.62  5013.1  413.29
  5023.3  414.48  5094.1  413.77  5150.6  415.33  5236.9  419.40  5308.7  424.38
  5318.5  424.12  5345.7  423.68  5636.5  428.03  5687.7  426.72  5745.6  427.14
#Mann=5,-1,0
  4127.2    0.05       0  4989.9    0.03       0  4995.9    0.05       0
  5318.5    0.08       0  5345.7    0.05       0
Bank Sta=4929.4,5150.6
Exp/Cntr=0.3,0.1

Type RM Length L Ch R = 1,16855,638,638,638
BEGIN DESCRIPTION:
UNT 042 IN DRY CR WATERSHED 25.0
END DESCRIPTION:
XS GIS Cut Line= 3
      2895774.99      7002775.02      2896025.00      7001975.00
      2896158.14      7001369.65
#Sta/Elev= 30
  4165.3  461.47  4186.8  461.59  4207.2  458.95  4214.0  456.58  4219.3  457.24
  4238.7  452.76  4246.5  449.60  4251.8  449.76  4279.0  443.50  4349.2  436.12
  4521.5  429.09  4773.0  423.37  4867.3  418.34  4893.4  415.40  4920.7  413.14
  4982.0  411.80  4987.2  410.15  4990.0  405.66  4990.5  404.86  4996.0  405.66
  5000.9  408.10  5006.0  408.10  5013.7  411.56  5022.8  412.17  5064.9  411.21
  5151.7  413.14  5234.2  416.86  5331.1  419.64  5484.7  420.87  5623.3  425.39
#Mann=6,-1,0
  4165.3    0.16       0  4521.5    0.05       0  4893.4    0.16       0
  4990.0    0.07       0  4996.0    0.16       0  5234.2    0.05       0
Bank Sta=4920.7,5151.7
Exp/Cntr=0.3,0.1

Type RM Length L Ch R = 1,16217,585,585,585
BEGIN DESCRIPTION:
UNT 042 IN DRY CR WATERSHED 24.0
END DESCRIPTION:
XS GIS Cut Line= 3
      2895825.02      7002724.98      2896475.00      7002225.00
      2896425.00      7001775.00
#Sta/Elev= 30
  4185.4  457.52  4228.0  449.32  4242.5  448.39  4247.7  446.39  4263.3  443.53
  4362.9  434.66  4541.5  427.77  4605.8  425.84  4614.0  426.81  4814.9  414.83
  4839.5  412.96  4927.5  408.53  4933.8  406.56  4942.0  407.64  4948.3  405.20
  4955.0  408.88  4969.2  408.33  4977.4  407.27  4988.9  401.94  4989.4  401.14
  4994.9  401.94  4998.2  402.83  5002.3  406.47  5014.3  408.53  5045.7  409.46
  5096.0  414.10  5136.2  421.27  5246.9  423.21  5381.0  430.76  5458.2  432.53
#Mann=7,-1,0
  4185.4    0.16       0  4247.7    0.05       0  4814.9    0.16       0
  4839.5    0.05       0  4988.9    0.03       0  4994.9    0.05       0
  5381.0    0.08       0
Bank Sta=4927.5,5014.3
Exp/Cntr=0.3,0.1

Type RM Length L Ch R = 1,15632,592,592,592
BEGIN DESCRIPTION:
UNT 042 IN DRY CR WATERSHED 23.0
END DESCRIPTION:
XS GIS Cut Line= 3
      2896825.01      7002524.97      2896975.00      7002075.00
      2896624.99      7001774.99
#Sta/Elev= 30
  4555.2  420.12  4650.0  417.41  4690.4  414.15  4841.3  406.88  4945.2  405.40
  4955.7  402.08  4976.8  401.85  4994.8  397.74  4995.3  396.94  5000.9  397.74
  5019.0  405.88  5046.5  405.80  5071.8  404.99  5088.5  406.88  5114.6  413.44
  5128.8  411.36  5149.7  411.80  5171.6  409.81  5192.5  413.01  5201.1  412.72
  5206.8  415.30  5221.0  414.68  5227.6  416.75  5237.7  416.85  5263.8  419.02
  5270.4  421.01  5292.4  419.73  5356.0  421.45  5448.2  428.71  5490.5  428.76
#Mann=7,-1,0
  4555.2    0.05       0  4690.4    0.16       0  4994.8    0.07       0
  5000.9    0.16       0  5046.5    0.05       0  5201.1    0.16       0
  5237.7    0.05       0
Bank Sta=4841.3,5088.5
Exp/Cntr=0.3,0.1

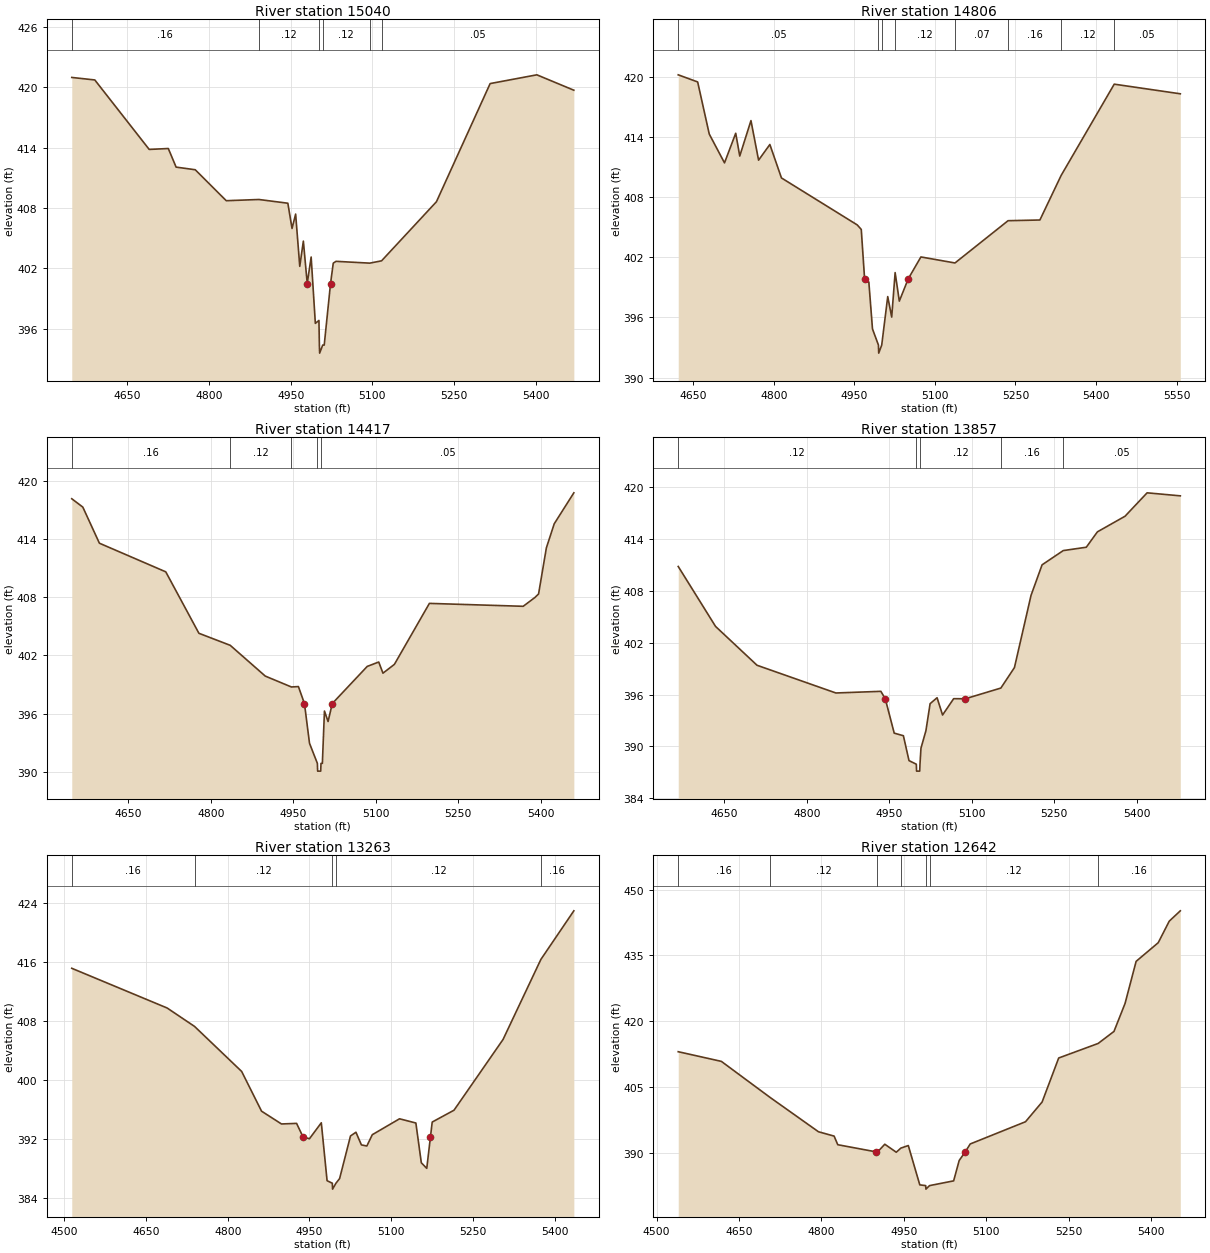
Type RM Length L Ch R = 1,15040,234,234,234
BEGIN DESCRIPTION:
UNT 042 IN DRY CR WATERSHED 22.0
END DESCRIPTION:
XS GIS Cut Line= 3
      2897024.98      7002625.02      2897325.00      7002275.00
      2897225.00      7001824.98
#Sta/Elev= 30
  4548.0  420.98  4590.3  420.73  4690.2  413.82  4725.3  413.91  4739.6  412.06
  4774.7  411.80  4831.7  408.72  4891.6  408.84  4944.8  408.47  4952.5  405.96
  4959.1  407.39  4966.7  402.19  4973.3  404.70  4980.4  400.48  4987.6  403.12
  4995.3  396.52  5001.9  396.81  5002.7  394.36  5003.2  393.56  5008.8  394.36
  5011.6  394.36  5023.2  400.48  5028.2  402.51  5033.3  402.69  5095.2  402.51
  5116.9  402.74  5217.7  408.62  5316.3  420.37  5402.1  421.24  5470.0  419.71
#Mann=6,-1,0
  4548.0    0.16       0  4891.6    0.12       0  5002.7    0.07       0
  5008.8    0.12       0  5095.2    0.16       0  5116.9    0.05       0
Bank Sta=4980.4,5023.2
Exp/Cntr=0.3,0.1

Type RM Length L Ch R = 1,14806,389,389,389
BEGIN DESCRIPTION:
Mapping XS 2b10e189
END DESCRIPTION:
XS GIS Cut Line= 3
      2897169.51      7002640.95      2897499.37      7002341.47
      2897438.61      7001855.38
#Sta/Elev= 30
  4621.7  420.17  4657.9  419.46  4679.5  414.27  4707.9  411.40  4728.8  414.35
  4736.3  412.08  4757.2  415.61  4771.4  411.67  4792.4  413.23  4814.0  409.90
  4955.2  405.22  4962.7  404.77  4968.9  399.85  4976.8  399.54  4983.6  394.86
  4994.7  393.25  4995.2  392.45  5000.8  393.25  5012.0  398.08  5019.4  396.04
  5025.8  400.47  5033.6  397.63  5050.2  399.85  5073.8  402.03  5137.3  401.43
  5236.2  405.64  5295.5  405.71  5335.1  410.15  5434.0  419.24  5557.1  418.28
#Mann=8,-1,0
  4621.7    0.05       0  4994.7    0.03       0  5000.8    0.05       0
  5025.8    0.12       0  5137.3    0.07       0  5236.2    0.16       0
  5335.1    0.12       0  5434.0    0.05       0
Bank Sta=4968.9,5050.2
Exp/Cntr=0.3,0.1

Type RM Length L Ch R = 1,14417,560,560,560
BEGIN DESCRIPTION:
UNT 042 IN DRY CR WATERSHED 21.0
END DESCRIPTION:
XS GIS Cut Line= 3
      2897875.00      7002775.01      2897825.00      7002325.00
      2897524.97      7001974.97
#Sta/Elev= 30
  4546.8  418.13  4566.9  417.27  4597.1  413.55  4717.9  410.60  4778.2  404.27
  4835.2  403.03  4899.0  399.86  4946.5  398.74  4959.3  398.78  4970.3  397.03
  4979.5  392.94  4993.8  390.87  4994.3  390.07  4999.9  390.07  5000.4  390.87
  5002.9  390.87  5006.7  396.26  5013.3  395.18  5020.9  397.03  5084.6  400.86
  5105.5  401.31  5113.2  400.16  5134.0  401.07  5197.7  407.35  5368.4  407.05
  5389.8  407.96  5396.4  408.32  5410.6  413.07  5424.9  415.55  5460.6  418.74
#Mann=5,-1,0
  4546.8    0.16       0  4835.2    0.12       0  4946.5    0.16       0
  4993.8    0.03       0  5000.4    0.05       0
Bank Sta=4970.3,5020.9
Exp/Cntr=0.3,0.1

Type RM Length L Ch R = 1,13857,594,594,594
BEGIN DESCRIPTION:
UNT 042 IN DRY CR WATERSHED 20.0
END DESCRIPTION:
XS GIS Cut Line= 3
      2898575.03      7002025.01      2898125.00      7001925.00
      2897674.98      7001875.00
#Sta/Elev= 30
  4565.9  410.83  4633.8  403.89  4709.3  399.39  4852.8  396.18  4934.7  396.37
  4942.7  395.51  4959.0  391.53  4975.7  391.23  4985.9  388.35  4999.2  387.93
  4999.7  387.13  5005.4  387.13  5005.9  387.93  5007.7  389.79  5016.7  391.81
  5024.3  394.94  5037.0  395.63  5047.0  393.63  5067.2  395.52  5088.4  395.51
  5153.1  396.75  5177.8  399.12  5208.0  407.48  5228.1  411.02  5266.6  412.67
  5308.6  413.06  5328.8  414.84  5379.1  416.65  5419.3  419.36  5479.7  419.01
#Mann=5,-1,0
  4565.9    0.12       0  4999.2    0.07       0  5005.9    0.12       0
  5153.1    0.16       0  5266.6    0.05       0
Bank Sta=4942.7,5088.4
Exp/Cntr=0.3,0.1

Type RM Length L Ch R = 1,13263,621,621,621
BEGIN DESCRIPTION:
UNT 042 IN DRY CR WATERSHED 19.0
END DESCRIPTION:
XS GIS Cut Line= 3
      2898724.98      7001874.97      2898475.00      7001475.00
      2898475.00      7001024.97
#Sta/Elev= 30
  4513.7  415.12  4688.8  409.75  4739.1  407.26  4825.6  401.17  4862.1  395.80
  4898.7  394.07  4926.4  394.15  4938.1  392.34  4950.0  392.07  4971.8  394.23
  4982.4  386.40  4992.0  386.06  4992.5  385.26  4998.7  386.06  5005.4  386.69
  5025.4  392.45  5035.4  392.95  5045.4  391.24  5055.4  391.09  5065.4  392.62
  5115.4  394.77  5145.4  394.20  5155.4  388.82  5165.4  388.07  5172.2  392.34
  5175.4  394.33  5215.4  395.93  5305.4  405.49  5374.9  416.32  5435.4  422.89
#Mann=5,-1,0
  4513.7    0.16       0  4739.1    0.12       0  4992.0    0.07       0
  4998.7    0.12       0  5374.9    0.16       0
Bank Sta=4938.1,5172.2
Exp/Cntr=0.3,0.1

Type RM Length L Ch R = 1,12642,561,561,561
BEGIN DESCRIPTION:
UNT 042 IN DRY CR WATERSHED 18.0
END DESCRIPTION:
XS GIS Cut Line= 3
      2899175.00      7001575.00      2898875.00      7001225.00
      2898825.00      7000775.04
#Sta/Elev= 30
  4539.4  413.09  4617.9  410.89  4706.6  402.68  4794.6  394.87  4823.1  393.88
  4829.7  391.92  4898.7  390.31  4902.0  390.25  4915.3  392.03  4936.2  390.21
  4944.6  391.15  4958.1  391.73  4979.0  382.78  4989.7  382.61  4990.2  381.81
  4996.7  382.61  5040.6  383.69  5050.7  388.33  5061.8  390.31  5070.8  392.09
  5171.4  397.15  5201.6  401.64  5231.8  411.66  5303.6  414.97  5332.4  417.71
  5352.5  424.06  5372.7  433.66  5412.9  437.90  5433.0  442.81  5453.1  445.16
#Mann=7,-1,0
  4539.4    0.16       0  4706.6    0.12       0  4902.0    0.16       0
  4944.6    0.12       0  4989.7    0.07       0  4996.7    0.12       0
  5303.6    0.16       0
Bank Sta=4898.7,5061.8
Exp/Cntr=0.3,0.1

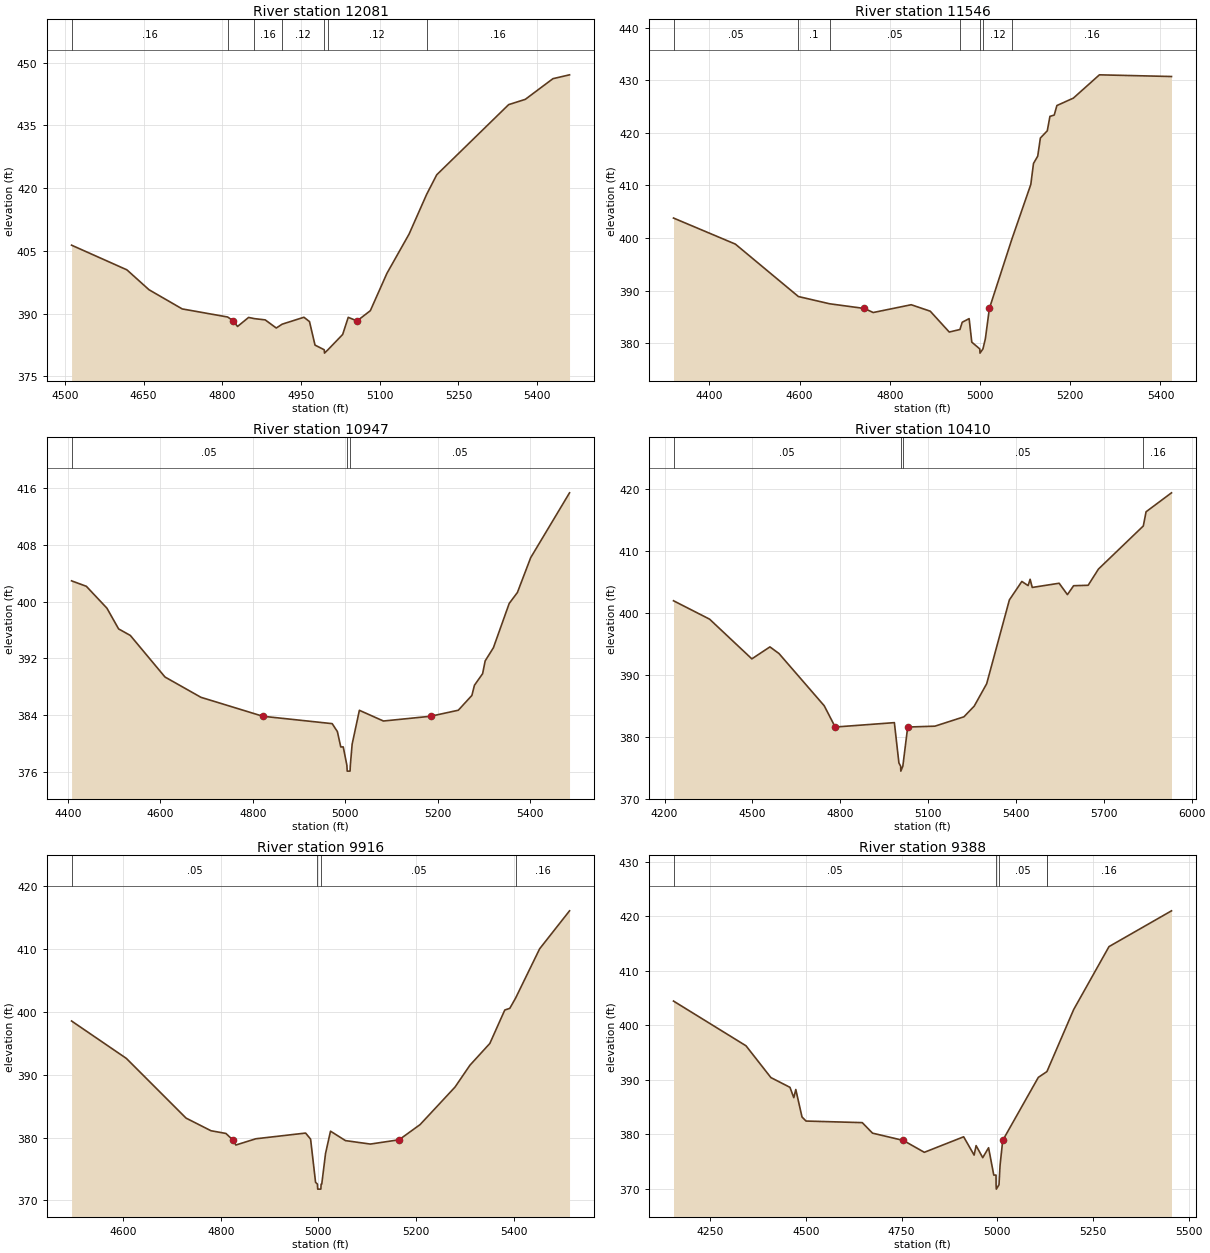
Type RM Length L Ch R = 1,12081,535,535,535
BEGIN DESCRIPTION:
UNT 042 IN DRY CR WATERSHED 17.0
END DESCRIPTION:
XS GIS Cut Line= 3
      2899425.00      7001325.01      2899275.00      7000875.00
      2898824.99      7000725.00
#Sta/Elev= 30
  4512.9  406.36  4618.3  400.47  4660.5  395.71  4723.7  391.13  4810.3  389.20
  4821.0  388.26  4829.1  386.94  4850.2  389.10  4861.4  388.81  4881.8  388.51
  4902.9  386.57  4914.2  387.49  4955.6  389.14  4966.2  388.10  4976.7  382.49
  4994.3  381.37  4994.8  380.57  5001.3  381.37  5029.4  385.03  5040.0  389.12
  5056.8  388.26  5082.1  390.71  5113.7  399.63  5155.9  409.01  5189.4  418.51
  5208.6  423.18  5345.6  439.94  5377.3  441.20  5430.0  446.14  5461.6  447.06
#Mann=7,-1,0
  4512.9    0.16       0  4810.3    0.12       0  4861.4    0.16       0
  4914.2    0.12       0  4994.3    0.07       0  5001.3    0.12       0
  5189.4    0.16       0
Bank Sta=4821,5056.8
Exp/Cntr=0.3,0.1

Type RM Length L Ch R = 1,11546,599,599,599
BEGIN DESCRIPTION:
UNT 042 IN DRY CR WATERSHED 16.0
END DESCRIPTION:
XS GIS Cut Line= 3
      2899825.01      7001125.04      2899625.00      7000525.00
      2899225.00      7000275.00
#Sta/Elev= 30
  4320.3  403.80  4457.4  398.85  4597.2  388.88  4666.5  387.50  4743.6  386.61
  4763.1  385.84  4847.4  387.32  4889.6  386.09  4931.7  382.13  4955.4  382.61
  4960.5  383.99  4975.8  384.68  4981.7  380.21  4999.4  378.92  4999.9  378.12
  5006.4  378.92  5011.8  380.84  5020.7  386.61  5070.5  399.77  5112.6  410.20
  5118.5  414.18  5127.9  415.57  5133.8  419.02  5149.1  420.39  5155.0  423.13
  5164.5  423.38  5170.4  425.19  5206.9  426.60  5264.7  431.03  5424.5  430.71
#Mann=7,-1,0
  4320.3    0.05       0  4597.2     0.1       0  4666.5    0.05       0
  4955.4    0.12       0  4999.4    0.07       0  5006.4    0.12       0
  5070.5    0.16       0
Bank Sta=4743.6,5020.7
Exp/Cntr=0.3,0.1

Type RM Length L Ch R = 1,10947,537,537,537
BEGIN DESCRIPTION:
UNT 042 IN DRY CR WATERSHED 15.0
END DESCRIPTION:
XS GIS Cut Line= 3
      2900325.02      7000925.05      2900125.00      7000375.00
      2899675.02      7000175.01
#Sta/Elev= 30
  4408.0  402.94  4440.0  402.17  4484.5  399.09  4509.8  396.17  4535.1  395.25
  4610.2  389.39  4688.0  386.53  4822.0  383.86  4972.0  382.82  4983.3  381.70
  4990.6  379.54  4996.0  379.54  5003.9  376.93  5004.5  376.13  5010.7  376.13
  5011.3  376.93  5015.2  379.92  5030.9  384.70  5082.9  383.19  5185.0  383.86
  5245.0  384.71  5274.4  386.80  5279.9  388.23  5297.6  389.86  5303.1  391.66
  5320.9  393.51  5355.1  399.75  5372.9  401.30  5401.6  406.20  5485.7  415.34
#Mann=3,-1,0
  4408.0    0.05       0  5003.9    0.03       0  5011.3    0.05       0
Bank Sta=4822,5185
Exp/Cntr=0.3,0.1

Type RM Length L Ch R = 1,10410,494,494,494
BEGIN DESCRIPTION:
UNT 042 IN DRY CR WATERSHED 14.0
END DESCRIPTION:
XS GIS Cut Line= 3
      2900711.17      7000774.59      2900525.00      7000025.00
      2899851.82      6999385.76
#Sta/Elev= 30
  4230.4  401.96  4353.6  398.99  4497.9  392.58  4559.7  394.51  4590.6  393.44
  4745.2  385.00  4782.6  381.57  4984.7  382.28  5000.2  375.77  5006.1  375.25
  5006.7  374.45  5013.6  375.25  5030.2  381.57  5123.1  381.71  5222.2  383.22
  5257.4  384.95  5299.9  388.56  5377.5  402.10  5420.0  405.08  5441.4  404.41
  5448.3  405.43  5455.6  404.11  5547.4  404.79  5575.7  402.95  5596.8  404.39
  5646.5  404.46  5681.7  407.08  5834.9  414.04  5844.3  416.33  5931.1  419.39
#Mann=4,-1,0
  4230.4    0.05       0  5006.1    0.03       0  5013.6    0.05       0
  5834.9    0.16       0
Bank Sta=4782.6,5030.2
Exp/Cntr=0.3,0.1

Type RM Length L Ch R = 1,9916,528,528,528
BEGIN DESCRIPTION:
UNT 042 IN DRY CR WATERSHED 13.0
END DESCRIPTION:
XS GIS Cut Line= 3
      2900974.99      7000224.97      2900875.00      6999725.00
      2900775.00      6999224.98
#Sta/Elev= 30
  4494.6  398.54  4606.8  392.59  4729.1  383.09  4780.1  381.08  4810.7  380.65
  4824.5  379.64  4831.1  378.81  4871.9  379.80  4973.9  380.71  4984.1  379.75
  4994.3  372.87  4998.1  372.59  4998.7  371.79  5005.1  371.79  5005.7  372.59
  5007.0  372.59  5014.7  377.45  5024.9  381.01  5055.5  379.51  5106.5  378.96
  5165.3  379.64  5208.4  382.06  5279.8  388.02  5310.4  391.50  5351.2  394.97
  5381.8  400.29  5392.0  400.55  5403.9  402.18  5453.2  410.03  5514.4  416.07
#Mann=4,-1,0
  4494.6    0.05       0  4998.1    0.03       0  5005.7    0.05       0
  5403.9    0.16       0
Bank Sta=4824.5,5165.3
Exp/Cntr=0.3,0.1

Type RM Length L Ch R = 1,9388,660,660,660
BEGIN DESCRIPTION:
UNT 042 IN DRY CR WATERSHED 12.0
END DESCRIPTION:
XS GIS Cut Line= 3
      2901375.00      7000224.99      2901125.00      6999425.00
      2900825.01      6999075.01
#Sta/Elev= 30
  4155.1  404.46  4344.2  396.25  4409.2  390.41  4458.9  388.62  4468.9  386.72
  4474.1  388.22  4490.3  383.18  4500.8  382.43  4647.5  382.14  4674.2  380.21
  4754.7  378.87  4809.4  376.69  4912.0  379.54  4939.3  376.18  4944.5  377.92
  4961.8  375.71  4977.0  377.53  4990.6  372.51  4996.5  372.51  4996.6  370.73
  4997.2  369.93  5004.2  370.73  5007.0  374.31  5013.9  378.87  5106.8  390.45
  5128.6  391.48  5129.6  391.57  5199.0  402.90  5291.2  414.46  5454.2  421.03
#Mann=5,-1,0
  4155.1    0.05       0  4996.6    0.03       0  5004.2    0.05       0
  5128.6    0.08       0  5129.6    0.16       0
Bank Sta=4754.7,5013.9
Exp/Cntr=0.3,0.1

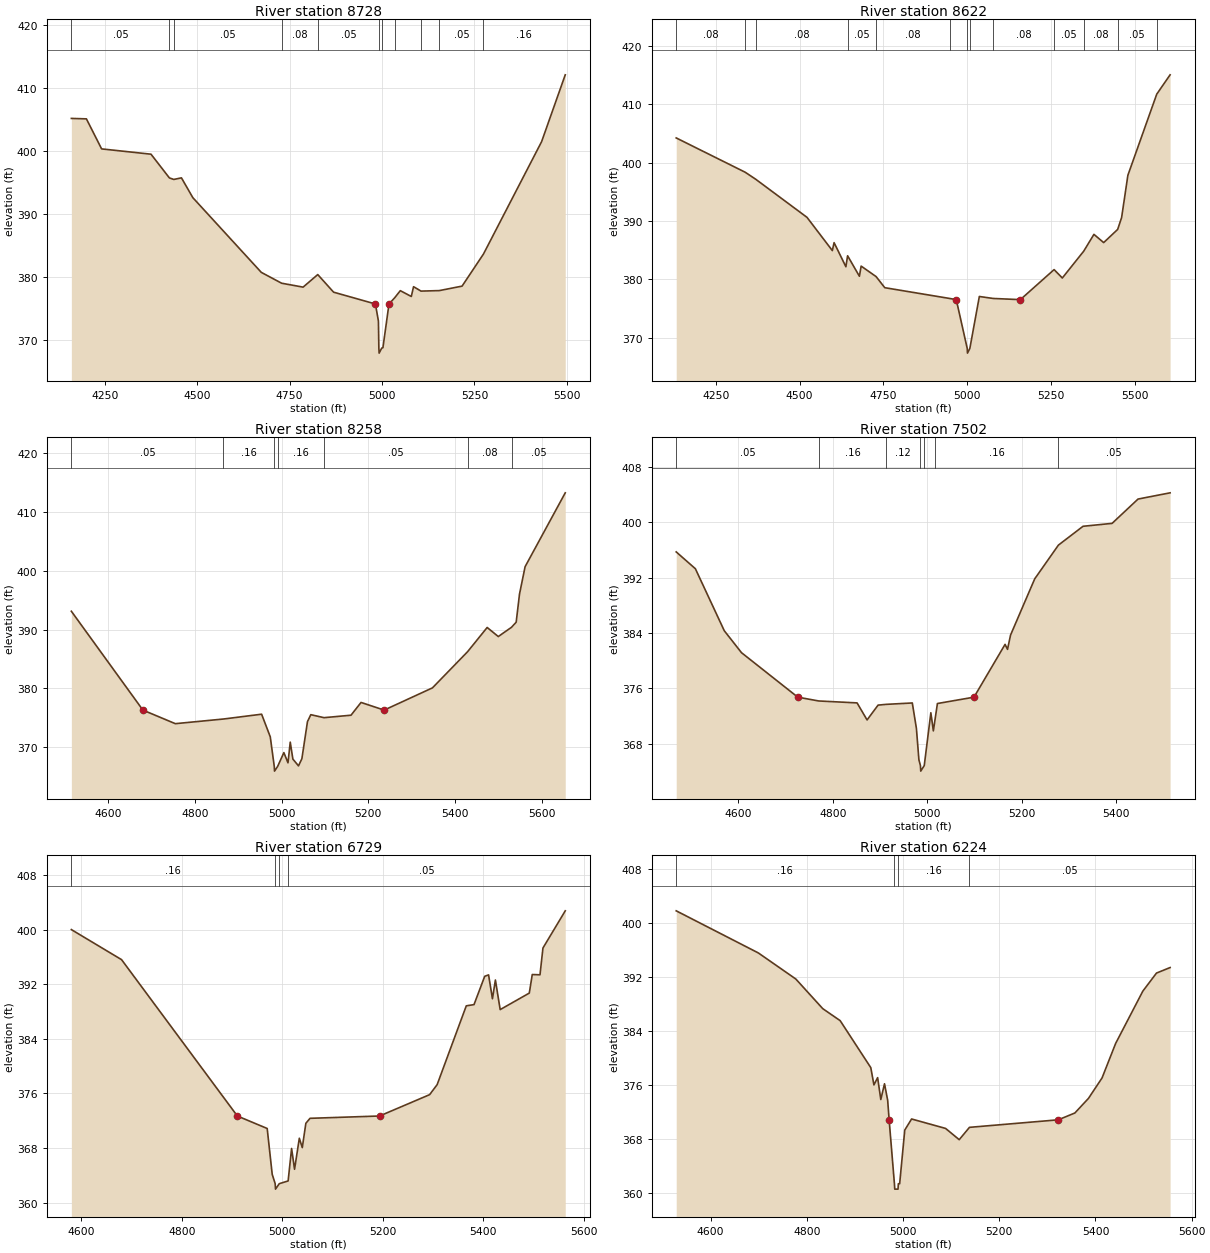
Type RM Length L Ch R = 1,8728,106,106,106
BEGIN DESCRIPTION:
Mapping XS ad13cb71
END DESCRIPTION:
XS GIS Cut Line= 3
      2901783.24      7000084.57      2901583.57      6999246.85
      2901314.49      6998856.25
#Sta/Elev= 30
  4160.0  405.17  4200.7  405.10  4241.8  400.34  4375.4  399.50  4425.1  395.74
  4437.0  395.50  4457.7  395.75  4488.5  392.61  4673.6  380.77  4728.6  379.05
  4786.6  378.43  4826.3  380.42  4869.1  377.63  4982.2  375.76  4990.3  373.05
  4991.5  368.77  4992.2  367.97  4999.3  368.77  5002.5  368.83  5018.9  375.76
  5034.1  376.73  5049.5  377.87  5079.2  376.95  5085.3  378.50  5105.5  377.80
  5154.9  377.88  5216.5  378.59  5274.4  383.68  5431.6  401.49  5495.5  412.08
#Mann=11,-1,0
  4160.0    0.05       0  4425.1    0.08       0  4437.0    0.05       0
  4728.6    0.08       0  4826.3    0.05       0  4991.5    0.03       0
  4999.3    0.05       0  5034.1    0.08       0  5105.5    0.16       0
  5154.9    0.05       0  5274.4    0.16       0
Bank Sta=4982.2,5018.9
Exp/Cntr=0.3,0.1

Type RM Length L Ch R = 1,8622,364,364,364
BEGIN DESCRIPTION:
Mapping XS 98739d4a
END DESCRIPTION:
XS GIS Cut Line= 4
      2901878.70      7000028.07      2901648.68      6999151.37
      2901553.19      6998869.25      2901292.82      6998804.16
#Sta/Elev= 30
  4132.4  404.24  4338.1  398.36  4369.9  397.14  4522.3  390.63  4597.9  384.93
  4603.1  386.29  4638.3  382.16  4643.4  384.04  4678.6  380.53  4683.8  382.27
  4728.4  380.47  4754.2  378.57  4948.8  376.71  4967.4  376.52  5000.1  368.15
  5000.8  367.35  5007.9  368.15  5036.2  377.06  5077.6  376.72  5158.5  376.52
  5259.1  381.67  5283.6  380.23  5347.2  384.81  5377.9  387.71  5406.9  386.30
  5448.7  388.56  5460.4  390.59  5479.1  397.84  5565.1  411.74  5605.0  415.06
#Mann=13,-1,0
  4132.4    0.08       0  4338.1    0.05       0  4369.9    0.08       0
  4643.4    0.05       0  4728.4    0.08       0  4948.8    0.05       0
  5000.1    0.04       0  5007.9    0.05       0  5077.6    0.08       0
  5259.1    0.05       0  5347.2    0.08       0  5448.7    0.05       0
  5565.1    0.16       0
Bank Sta=4967.4,5158.5
Exp/Cntr=0.3,0.1

Type RM Length L Ch R = 1,8258,756,756,756
BEGIN DESCRIPTION:
UNT 042 IN DRY CR WATERSHED 10.0
END DESCRIPTION:
XS GIS Cut Line= 3
      2902074.99      6999424.96      2901925.00      6998925.00
      2901325.04      6998775.01
#Sta/Elev= 30
  4514.4  393.12  4679.6  376.31  4754.5  374.00  4865.4  374.79  4953.7  375.61
  4973.7  371.76  4982.9  366.73  4983.5  365.93  4990.7  366.73  5005.1  369.08
  5014.6  367.34  5019.8  370.86  5025.9  367.98  5038.9  366.82  5046.7  368.05
  5059.6  374.35  5067.3  375.53  5097.8  375.02  5160.1  375.44  5183.3  377.61
  5236.7  376.31  5348.2  380.09  5429.3  386.24  5474.5  390.36  5500.2  388.82
  5530.8  390.40  5541.5  391.26  5549.2  396.05  5562.1  400.70  5654.8  413.26
#Mann=7,-1,0
  4514.4    0.05       0  4865.4    0.16       0  4982.9    0.07       0
  4990.7    0.16       0  5097.8    0.05       0  5429.3    0.08       0
  5530.8    0.05       0
Bank Sta=4679.6,5236.7
Exp/Cntr=0.3,0.1

Type RM Length L Ch R = 1,7502,773,773,773
BEGIN DESCRIPTION:
UNT 042 IN DRY CR WATERSHED 9.0
END DESCRIPTION:
XS GIS Cut Line= 3
      2902125.00      6999475.00      2902325.00      6998925.00
      2902425.00      6998475.01
#Sta/Elev= 30
  4468.4  395.72  4509.0  393.29  4570.2  384.34  4606.7  381.17  4725.9  374.75
  4770.1  374.20  4851.5  373.92  4872.7  371.46  4896.0  373.60  4913.3  373.71
  4968.5  373.91  4977.2  370.24  4982.5  365.70  4985.7  364.87  4986.4  364.07
  4993.8  364.87  5007.8  372.50  5013.1  369.88  5016.6  371.49  5021.7  373.83
  5099.2  374.75  5165.0  382.37  5170.2  381.65  5176.6  383.71  5227.8  391.83
  5278.0  396.70  5330.2  399.42  5391.7  399.84  5446.7  403.35  5514.6  404.25
#Mann=7,-1,0
  4468.4    0.05       0  4770.1    0.16       0  4913.3    0.12       0
  4985.7    0.07       0  4993.8    0.12       0  5016.6    0.16       0
  5278.0    0.05       0
Bank Sta=4725.9,5099.2
Exp/Cntr=0.3,0.1

Type RM Length L Ch R = 1,6729,505,505,505
BEGIN DESCRIPTION:
UNT 042 IN DRY CR WATERSHED 8.0
END DESCRIPTION:
XS GIS Cut Line= 3
      2902875.00      6999424.99      2902870.24      6999004.92
      2902574.98      6998524.96
#Sta/Elev= 30
  4579.9  400.02  4679.9  395.61  4910.5  372.69  4969.9  370.86  4979.9  364.14
  4985.8  362.77  4986.5  361.97  4994.0  362.77  5011.6  363.17  5018.5  367.93
  5024.4  364.88  5033.9  369.43  5039.8  368.06  5046.9  371.62  5055.2  372.35
  5193.7  372.69  5293.4  375.82  5308.4  377.29  5366.4  388.84  5381.8  389.02
  5403.1  393.17  5410.8  393.38  5418.5  389.88  5424.4  392.63  5433.9  388.29
  5491.9  390.71  5497.8  393.43  5513.2  393.39  5519.1  397.32  5563.5  402.77
#Mann=4,-1,0
  4579.9    0.16       0  4985.8    0.07       0  4994.0    0.16       0
  5011.6    0.05       0
Bank Sta=4910.5,5193.7
Exp/Cntr=0.3,0.1

Type RM Length L Ch R = 1,6224,572,572,572
BEGIN DESCRIPTION:
UNT 042 IN DRY CR WATERSHED 7.0
END DESCRIPTION:
XS GIS Cut Line= 3
      2903525.00      6999325.00      2903225.00      6998975.00
      2902824.98      6998574.98
#Sta/Elev= 30
  4528.5  401.82  4699.2  395.57  4777.1  391.70  4833.1  387.30  4869.3  385.52
  4933.0  378.54  4939.5  375.98  4947.2  377.06  4953.8  373.81  4961.5  376.15
  4968.1  373.69  4971.1  370.80  4982.1  361.31  4982.8  360.51  4989.6  360.51
  4990.3  361.31  4993.0  361.31  5003.6  369.28  5017.8  370.92  5088.5  369.52
  5116.8  367.85  5138.1  369.68  5322.8  370.80  5357.2  371.81  5385.5  373.98
  5413.7  377.01  5442.0  382.14  5498.6  389.91  5526.9  392.58  5555.2  393.40
#Mann=4,-1,0
  4528.5    0.16       0  4982.1    0.07       0  4990.3    0.16       0
  5138.1    0.05       0
Bank Sta=4971.1,5322.8
Exp/Cntr=0.3,0.1

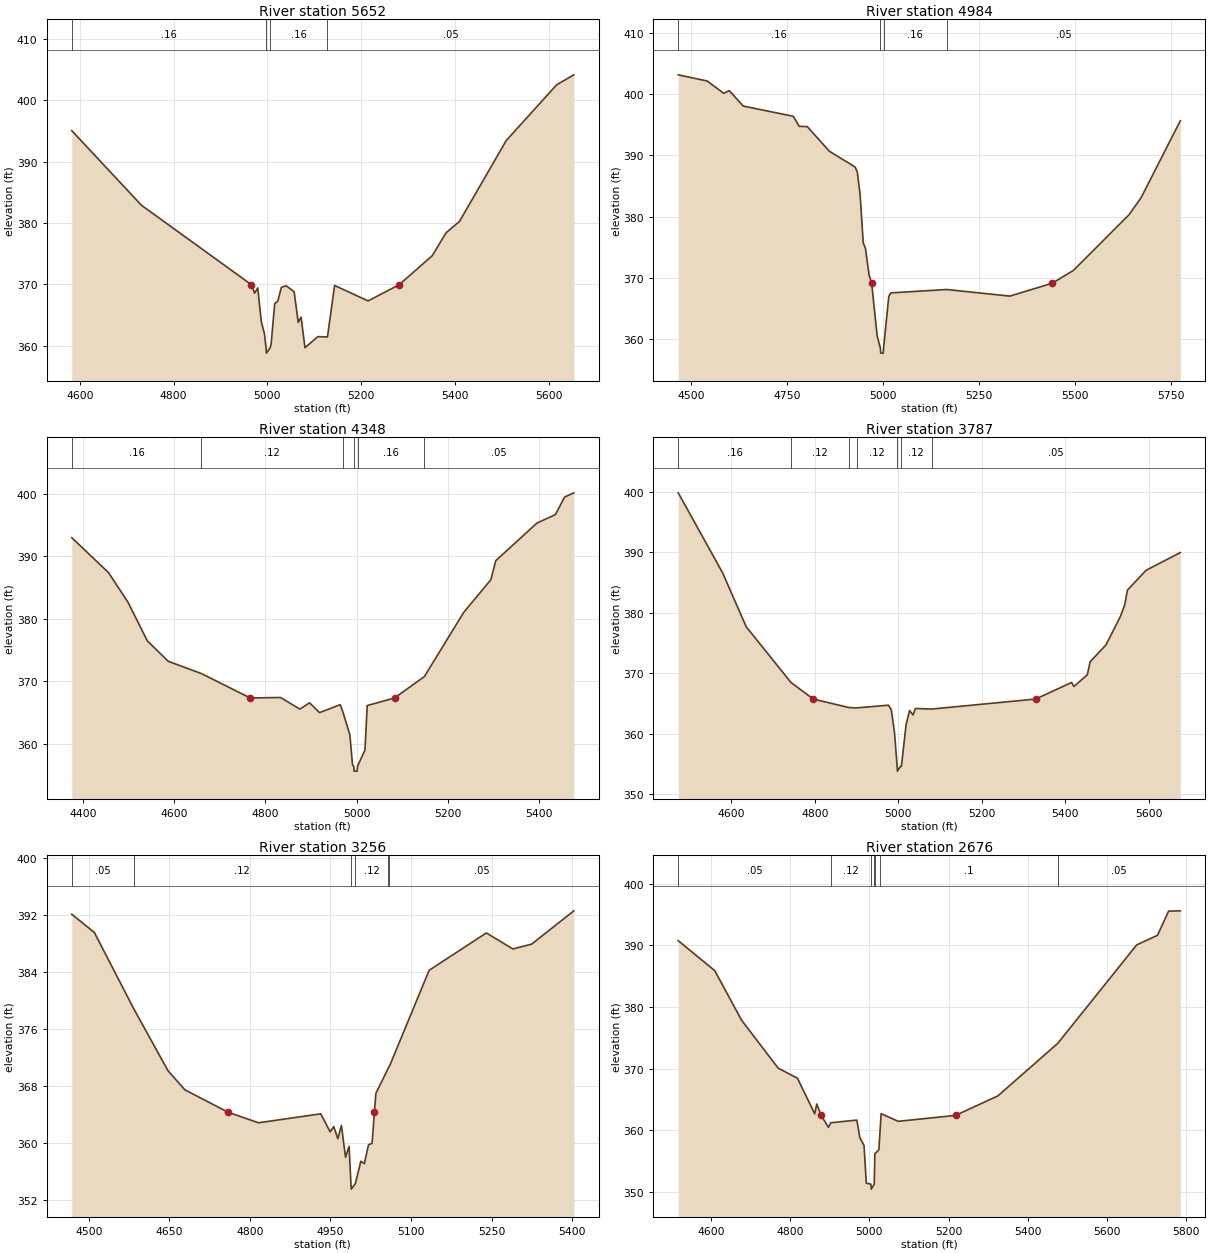
Type RM Length L Ch R = 1,5652,668,668,668
BEGIN DESCRIPTION:
UNT 042 IN DRY CR WATERSHED 6.0
END DESCRIPTION:
XS GIS Cut Line= 3
      2903625.02      6998975.02      2903325.00      6998625.00
      2902825.02      6998275.02
#Sta/Elev= 30
  4582.6  395.07  4731.3  382.91  4965.6  369.97  4972.8  368.58  4979.4  369.43
  4987.1  363.91  4993.7  361.96  4997.2  359.60  4997.9  358.80  5005.4  359.60
  5007.9  360.19  5015.6  366.85  5022.2  367.27  5029.9  369.53  5040.3  369.77
  5057.1  368.80  5065.8  363.82  5071.9  364.67  5080.2  359.68  5107.7  361.49
  5128.2  361.44  5143.4  369.83  5214.9  367.31  5281.5  369.97  5351.8  374.69
  5381.5  378.44  5409.8  380.26  5509.6  393.45  5617.3  402.55  5653.9  404.17
#Mann=4,-1,0
  4582.6    0.16       0  4997.2    0.07       0  5005.4    0.16       0
  5128.2    0.05       0
Bank Sta=4965.6,5281.5
Exp/Cntr=0.3,0.1

Type RM Length L Ch R = 1,4984,636,636,636
BEGIN DESCRIPTION:
Mapping XS fe5bd0cd
END DESCRIPTION:
XS GIS Cut Line= 3
      2903979.40      6998895.28      2903692.95      6998443.90
      2902946.42      6998239.91
#Sta/Elev= 30
  4466.4  403.18  4541.8  402.17  4585.2  400.15  4599.4  400.60  4635.9  398.07
  4766.3  396.40  4781.6  394.76  4802.7  394.71  4860.4  390.68  4927.3  388.11
  4933.2  387.26  4940.5  383.51  4948.5  375.74  4954.4  374.80  4963.7  370.46
  4970.5  369.11  4984.9  360.48  4993.3  358.48  4994.0  357.68  5000.8  357.68
  5001.5  358.48  5015.1  366.92  5020.3  367.53  5165.7  368.08  5330.6  367.00
  5441.2  369.11  5496.5  371.21  5641.6  380.33  5672.7  383.09  5774.9  395.67
#Mann=4,-1,0
  4466.4    0.16       0  4993.3    0.07       0  5001.5    0.16       0
  5165.7    0.05       0
Bank Sta=4970.5,5441.2
Exp/Cntr=0.3,0.1

Type RM Length L Ch R = 1,4348,561,561,561
BEGIN DESCRIPTION:
UNT 042 IN DRY CR WATERSHED 5.0
END DESCRIPTION:
XS GIS Cut Line= 3
      2904074.96      6998424.97      2903546.11      6998092.83
      2903074.97      6998025.00
#Sta/Elev= 30
  4375.5  392.98  4456.1  387.38  4498.6  382.67  4541.0  376.48  4586.9  373.20
  4659.5  371.24  4766.7  367.33  4833.1  367.41  4875.5  365.55  4896.7  366.56
  4918.6  364.99  4963.9  366.26  4970.4  364.95  4985.1  361.41  4991.0  356.56
  4993.6  356.43  4994.3  355.63  5001.1  355.63  5001.9  356.43  5018.1  358.98
  5023.1  366.12  5082.9  367.33  5148.3  370.75  5234.5  381.01  5294.1  386.25
  5304.9  389.30  5395.1  395.31  5435.6  396.67  5455.8  399.47  5476.0  400.15
#Mann=6,-1,0
  4375.5    0.16       0  4659.5    0.12       0  4970.4    0.16       0
  4993.6    0.07       0  5001.9    0.16       0  5148.3    0.05       0
Bank Sta=4766.7,5082.9
Exp/Cntr=0.3,0.1

Type RM Length L Ch R = 1,3787,531,531,531
BEGIN DESCRIPTION:
UNT 042 IN DRY CR WATERSHED 4.0
END DESCRIPTION:
XS GIS Cut Line= 3
      2904325.01      6998325.01      2903975.00      6997925.00
      2903376.09      6997623.58
#Sta/Elev= 30
  4473.2  399.79  4579.5  386.56  4636.0  377.65  4743.0  368.46  4796.5  365.71
  4882.2  364.30  4900.0  364.25  4976.7  364.70  4983.4  363.90  4991.0  360.15
  4997.2  354.60  4997.9  353.80  5005.5  354.60  5007.5  354.60  5018.7  361.47
  5027.1  363.81  5035.4  363.08  5041.0  364.15  5080.3  364.06  5328.9  365.71
  5414.8  368.45  5420.4  367.79  5452.5  369.71  5459.4  371.88  5497.3  374.66
  5532.0  379.39  5542.1  381.27  5548.7  383.72  5593.3  386.99  5675.2  389.92
#Mann=7,-1,0
  4473.2    0.16       0  4743.0    0.12       0  4882.2    0.16       0
  4900.0    0.12       0  4997.2    0.07       0  5005.5    0.12       0
  5080.3    0.05       0
Bank Sta=4796.5,5328.9
Exp/Cntr=0.3,0.1

Type RM Length L Ch R = 1,3256,580,580,580
BEGIN DESCRIPTION:
UNT 042 IN DRY CR WATERSHED 3.0
END DESCRIPTION:
XS GIS Cut Line= 3
      2904474.99      6998074.97      2904325.00      6997625.00
      2904024.99      6997274.99
#Sta/Elev= 30
  4468.1  392.12  4510.2  389.55  4583.6  378.82  4647.3  370.12  4678.9  367.42
  4759.2  364.28  4815.9  362.79  4931.9  364.05  4949.5  361.51  4956.1  362.26
  4963.8  360.56  4970.4  362.42  4978.1  357.94  4984.7  359.48  4988.1  354.26
  4988.9  353.46  4996.5  354.26  5006.6  357.38  5013.2  357.05  5020.9  359.70
  5027.5  359.90  5031.9  364.28  5034.6  366.92  5057.9  370.50  5059.9  370.74
  5133.9  384.24  5240.4  389.49  5289.8  387.24  5324.9  387.92  5403.4  392.60
#Mann=6,-1,0
  4468.1    0.05       0  4583.6    0.12       0  4988.1    0.07       0
  4996.5    0.12       0  5057.9     0.1       0  5059.9    0.05       0
Bank Sta=4759.2,5031.9
Exp/Cntr=0.3,0.1

Type RM Length L Ch R = 1,2676,616,616,616
BEGIN DESCRIPTION:
UNT 042 IN DRY CR WATERSHED 2.0
END DESCRIPTION:
XS GIS Cut Line= 3
      2904674.99      6997925.03      2904775.00      6997475.00
      2904075.03      6997075.02
#Sta/Elev= 30
  4517.7  390.76  4609.9  385.90  4677.8  377.85  4770.0  370.10  4818.7  368.46
  4862.2  362.69  4867.3  364.29  4878.3  362.44  4896.8  360.51  4902.7  361.25
  4968.5  361.68  4976.2  358.81  4986.6  357.57  4992.4  351.46  5004.0  351.29
  5004.8  350.49  5012.4  351.29  5013.6  355.00  5014.0  356.23  5024.1  356.85
  5027.7  360.56  5029.8  362.72  5073.0  361.48  5217.5  362.44  5324.2  365.59
  5475.5  374.11  5674.8  390.08  5727.3  391.63  5755.4  395.55  5784.9  395.60
#Mann=7,-1,0
  4517.7    0.05       0  4902.7    0.12       0  5004.0    0.07       0
  5012.4    0.12       0  5013.6    0.16       0  5027.7     0.1       0
  5475.5    0.05       0
Bank Sta=4878.3,5217.5
Exp/Cntr=0.3,0.1