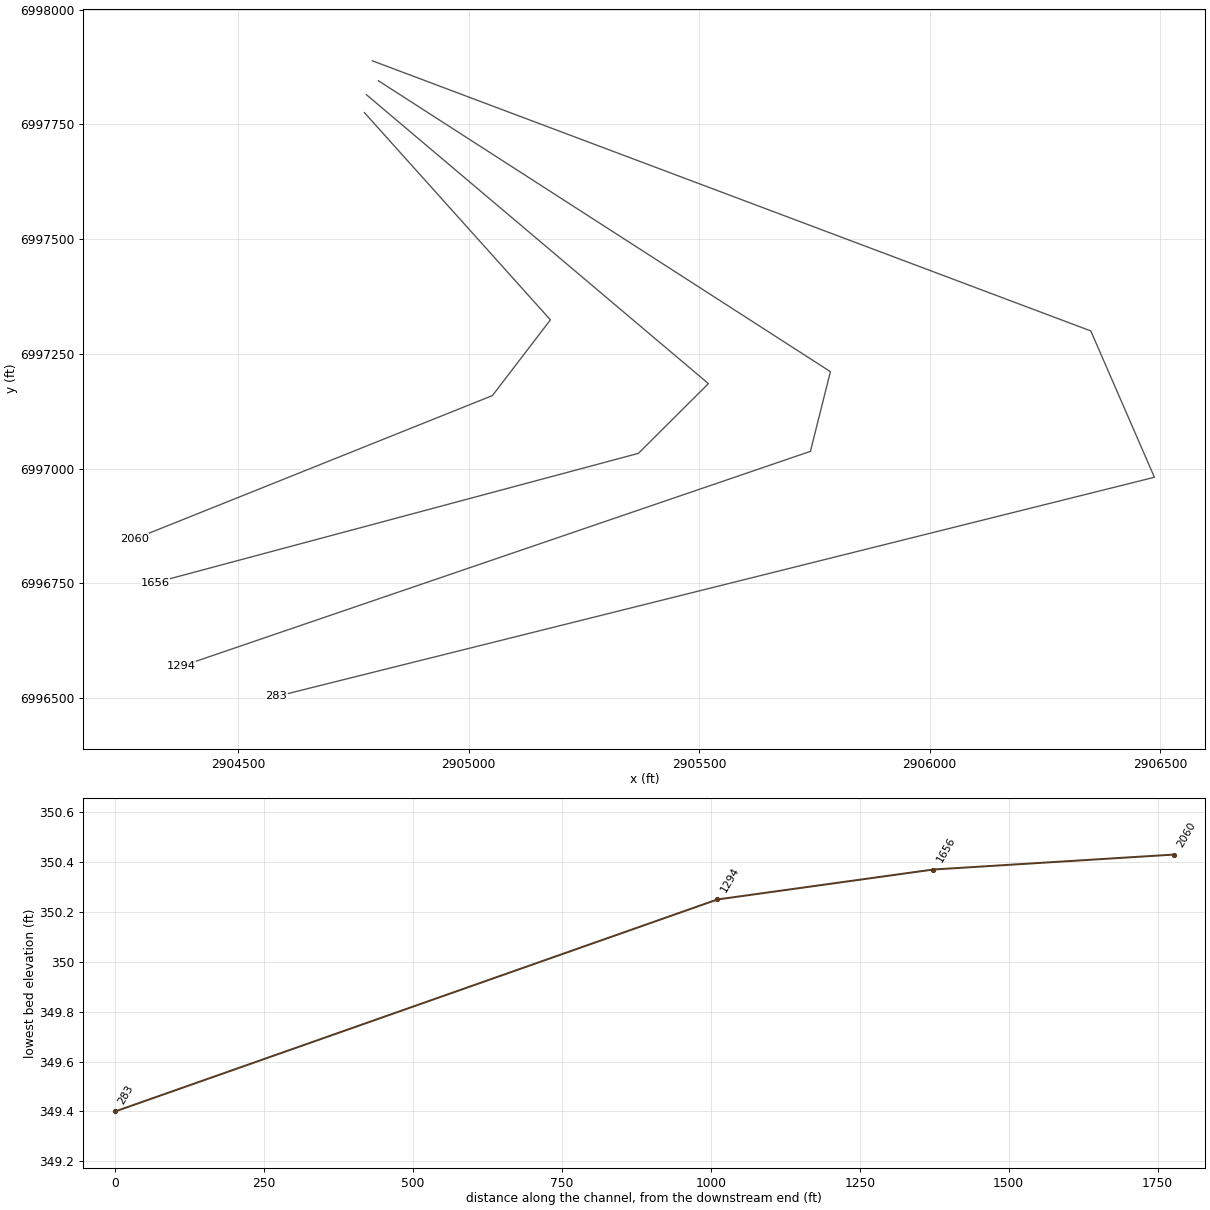
HEC-RAS study UNT 042 IN DRY CR WATERSHED.prj: UNT 042 IN DRY CR WATERSHED Base Level Engineering

--- UNT 042 IN DRY CR WATERSHED.g01 (geometry) --- (continued)

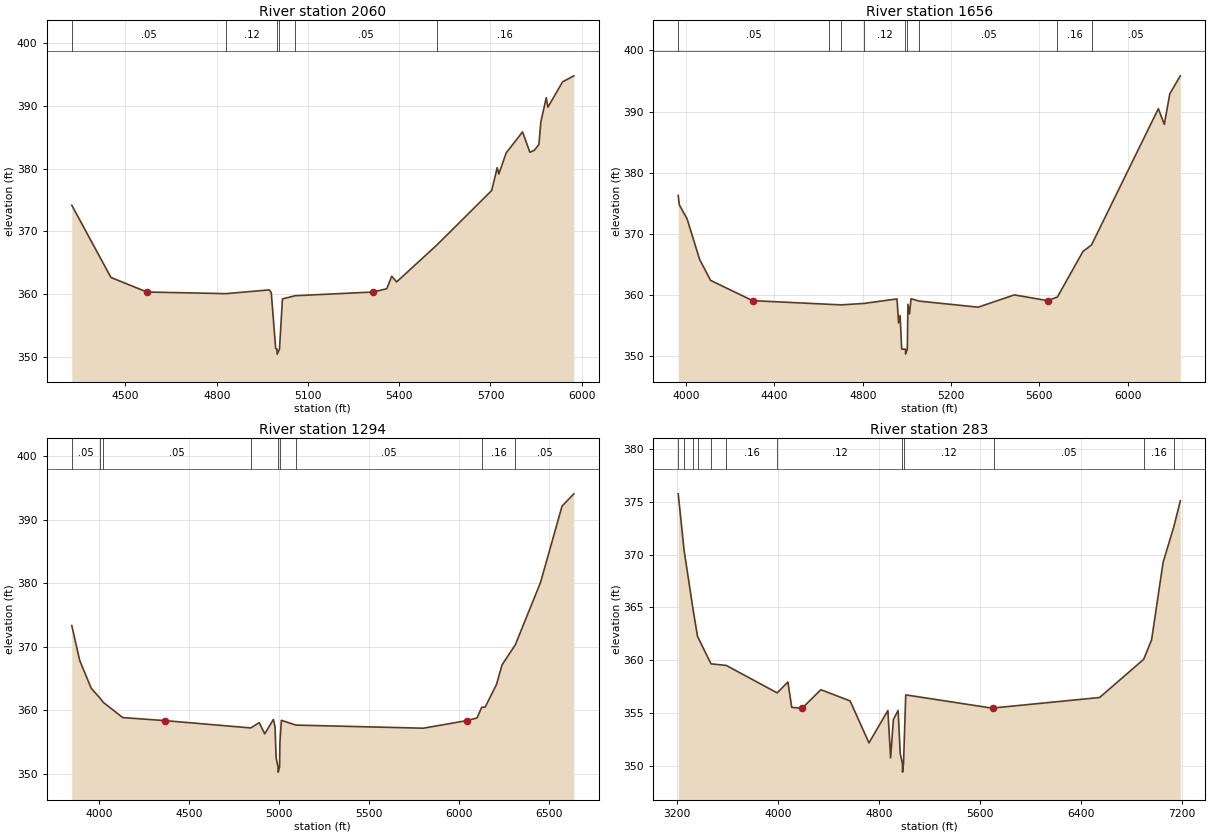
Type RM Length L Ch R = 1,2060,404,404,404
BEGIN DESCRIPTION:
Mapping XS 9abaf1ae
END DESCRIPTION:
XS GIS Cut Line= 4
      2904773.70      6997775.48      2905177.32      6997324.11
      2905051.46      6997159.18      2904274.54      6996846.68
#Sta/Elev= 30
  4323.6  374.17  4452.4  362.65  4570.8  360.33  4831.0  360.07  4973.1  360.67
  4979.4  360.21  4993.9  351.33  4998.0  351.23  4998.7  350.43  5006.4  351.23
  5016.1  359.23  5058.0  359.74  5313.8  360.33  5359.1  360.85  5375.4  362.85
  5391.5  361.94  5523.4  367.81  5704.0  376.51  5722.1  380.15  5727.5  379.14
  5751.6  382.51  5805.4  385.85  5829.5  382.61  5844.2  382.92  5859.1  383.85
  5865.7  387.47  5883.3  391.30  5888.7  389.79  5937.0  393.83  5974.0  394.79
#Mann=6,-1,0
  4323.6    0.05       0  4831.0    0.12       0  4998.0    0.07       0
  5006.4    0.12       0  5058.0    0.05       0  5523.4    0.16       0
Bank Sta=4570.8,5313.8
Exp/Cntr=0.3,0.1

Type RM Length L Ch R = 1,1656,362,362,362
BEGIN DESCRIPTION:
Mapping XS 2191e370
END DESCRIPTION:
XS GIS Cut Line= 4
      2904778.01      6997814.57      2905520.21      6997185.22
      2905368.30      6997033.31      2904318.93      6996751.46
#Sta/Elev= 30
  3964.1  376.31  3968.9  374.76  4004.1  372.49  4061.2  365.82  4110.6  362.42
  4300.9  359.11  4647.5  358.51  4703.2  358.42  4804.5  358.65  4955.2  359.39
  4962.3  355.47  4969.3  356.68  4976.4  351.19  4993.4  351.17  4994.2  350.37
  5001.8  351.17  5004.7  358.52  5011.8  356.93  5018.8  359.42  5056.7  359.03
  5322.7  358.04  5486.8  360.05  5637.7  359.11  5681.7  359.70  5797.4  367.13
  5836.5  368.22  6139.1  390.47  6166.1  387.91  6190.9  392.89  6238.6  395.84
#Mann=9,-1,0
  3964.1    0.05       0  4647.5    0.12       0  4703.2    0.07       0
  4804.5    0.12       0  4993.4    0.07       0  5001.8    0.12       0
  5056.7    0.05       0  5681.7    0.16       0  5836.5    0.05       0
Bank Sta=4300.9,5637.7
Exp/Cntr=0.3,0.1

Type RM Length L Ch R = 1,1294,1011,1011,1011
BEGIN DESCRIPTION:
Mapping XS e043c9c1
END DESCRIPTION:
XS GIS Cut Line= 4
      2904804.09      6997844.93      2905784.96      6997211.26
      2905741.56      6997037.65      2904376.00      6996569.46
#Sta/Elev= 30
  3846.8  373.34  3891.1  367.82  3955.0  363.46  4003.6  361.91  4022.9  361.22
  4130.0  358.84  4367.4  358.36  4841.5  357.21  4888.7  358.05  4919.1  356.28
  4967.3  358.55  4976.5  357.40  4982.4  352.50  4993.4  351.05  4994.1  350.25
  5001.8  351.05  5003.5  354.84  5011.6  358.41  5092.4  357.66  5800.3  357.17
  6041.3  358.36  6099.0  358.78  6124.9  360.46  6144.3  360.49  6206.9  364.04
  6238.2  367.15  6312.0  370.32  6451.8  380.12  6571.6  392.16  6637.1  394.09
#Mann=9,-1,0
  3846.8    0.05       0  4003.6    0.16       0  4022.9    0.05       0
  4841.5    0.12       0  4993.4    0.07       0  5001.8    0.12       0
  5092.4    0.05       0  6124.9    0.16       0  6312.0    0.05       0
Bank Sta=4367.4,6041.3
Exp/Cntr=0.3,0.1

Type RM Length L Ch R = 1,283,0,0,0
BEGIN DESCRIPTION:
UNT 042 IN DRY CR WATERSHED 1.0
END DESCRIPTION:
XS GIS Cut Line= 4
      2904791.02      6997888.35      2906350.00      6997300.00
      2906488.09      6996981.23      2904582.70      6996503.79
#Sta/Elev= 30
  3207.6  375.77  3253.7  370.45  3327.3  364.64  3360.5  362.26  3467.3  359.66
  3588.3  359.51  3991.4  356.91  4076.6  357.94  4106.8  355.54  4188.8  355.45
  4337.6  357.21  4569.3  356.15  4718.9  352.17  4868.6  355.24  4890.3  350.75
  4912.1  354.38  4949.8  355.25  4966.5  351.16  4984.1  350.20  4984.9  349.40
  4992.5  350.20  5010.1  356.72  5700.8  355.45  5705.6  355.48  6546.1  356.47
  6895.3  360.09  6958.0  361.93  7049.2  369.27  7133.8  372.64  7185.6  375.11
#Mann=12,-1,0
  3207.6    0.05       0  3253.7    0.16       0  3327.3    0.05       0
  3360.5    0.16       0  3467.3    0.12       0  3588.3    0.16       0
  3991.4    0.12       0  4984.1    0.07       0  4992.5    0.12       0
  5705.6    0.05       0  6895.3    0.16       0  7133.8    0.05       0
Bank Sta=4188.8,5700.8
Exp/Cntr=0.3,0.1

Chan Stop Cuts=-1