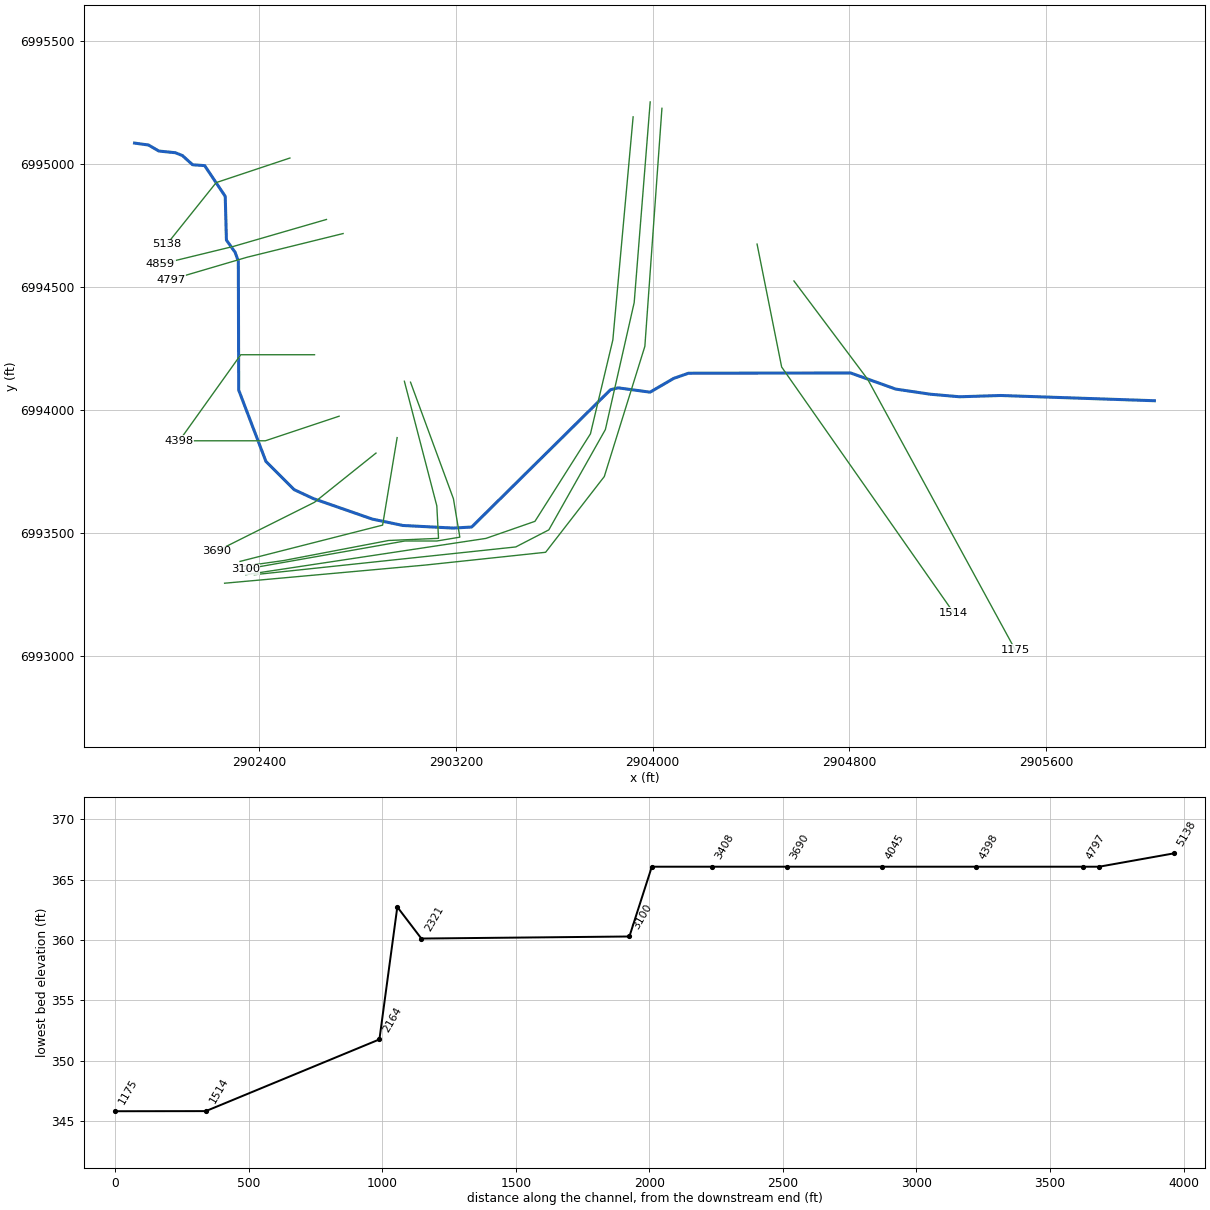
--- UNT 043 IN DRY CR WATERSHED.prj (project) ---

Proj Title=UNT 043 IN DRY CR WATERSHED Base Level Engineering
Current Plan=p01
Default Exp/Contr=0.3,0.1
English Units
Geom File=g01
Flow File=f01
Plan File=p01
BEGIN DESCRIPTION:
UNT 043 IN DRY CR WATERSHED
END DESCRIPTION:

--- UNT 043 IN DRY CR WATERSHED.p01 (plan) ---

Plan Title=Multiple Run
Short Identifier=Multiple
Geom File=g01
Flow File=f01
Subcritical Flow
K Sum by GR= 0
Std Step Tol= 0.01
Critical Tol= 0.01
Num of Std Step Trials= 20
Max Error Tol= 0.3
Flow Tol Ratio= 0.001
Split Flow NTrial= 30
Split Flow Tol= 0.02
Split Flow Ratio= 0.02
Log Output Level= 0
Friction Slope Method= 1
Unsteady Friction Slope Method= 2
Unsteady Bridges Friction Slope Method= 1
Parabolic Critical Depth
Global Vel Dist=  1 , 1 , 1
Global Log Level= 0
CheckData=True
Encroach Param= -1, 0, 0, 0
BEGIN DESCRIPTION:
Multiple Run
END DESCRIPTION:

--- UNT 043 IN DRY CR WATERSHED.f01 (steady flow) ---

Flow Title=Multiple
Number of Profiles=7
Profile Names=10-year,25-year,50-year,1pct_min,100-year,1pct_plu,500-year
River Rch & RM= UNT 043 IN DRY C,Reach-1,5138
     557     749     906     546    1089    2173    1573
Boundary for River Rch & Prof#=UNT 043 IN DRY C,Reach-1,1
Up Type=0
Dn Type=3
Dn Slope=0.005
Boundary for River Rch & Prof#=UNT 043 IN DRY C,Reach-1,2
Up Type=0
Dn Type=3
Dn Slope=0.005
Boundary for River Rch & Prof#=UNT 043 IN DRY C,Reach-1,3
Up Type=0
Dn Type=3
Dn Slope=0.005
Boundary for River Rch & Prof#=UNT 043 IN DRY C,Reach-1,4
Up Type=0
Dn Type=3
Dn Slope=0.005
Boundary for River Rch & Prof#=UNT 043 IN DRY C,Reach-1,5
Up Type=0
Dn Type=3
Dn Slope=0.005
Boundary for River Rch & Prof#=UNT 043 IN DRY C,Reach-1,6
Up Type=0
Dn Type=3
Dn Slope=0.005
Boundary for River Rch & Prof#=UNT 043 IN DRY C,Reach-1,7
Up Type=0
Dn Type=3
Dn Slope=0.005

--- UNT 043 IN DRY CR WATERSHED.g01 (geometry) ---

Geom Title=Existing Conditions

River Reach=UNT 043 IN DRY C,Reach-1
Reach XY= 30
      2901892.93      6995085.71      2901949.79      6995077.86
      2901991.70      6995053.38      2902058.67      6995046.56
      2902087.77      6995034.98      2902129.08      6994997.56
      2902178.13      6994994.04      2902261.83      6994869.15
      2902266.64      6994691.14      2902302.01      6994641.52
      2902315.10      6994605.50      2902316.64      6994081.14
      2902427.36      6993790.98      2902541.94      6993676.40
      2902620.07      6993639.94      2902859.65      6993556.60
      2902984.65      6993530.56      2903188.96      6993520.04
      2903264.10      6993524.19      2903829.05      6994082.77
      2903860.17      6994090.28      2903989.62      6994072.73
      2904086.32      6994128.94      2904146.00      6994149.71
      2904805.64      6994150.77      2904988.82      6994085.25
      2905129.44      6994064.42      2905249.23      6994054.00
      2905415.90      6994059.21      2906041.19      6994037.89

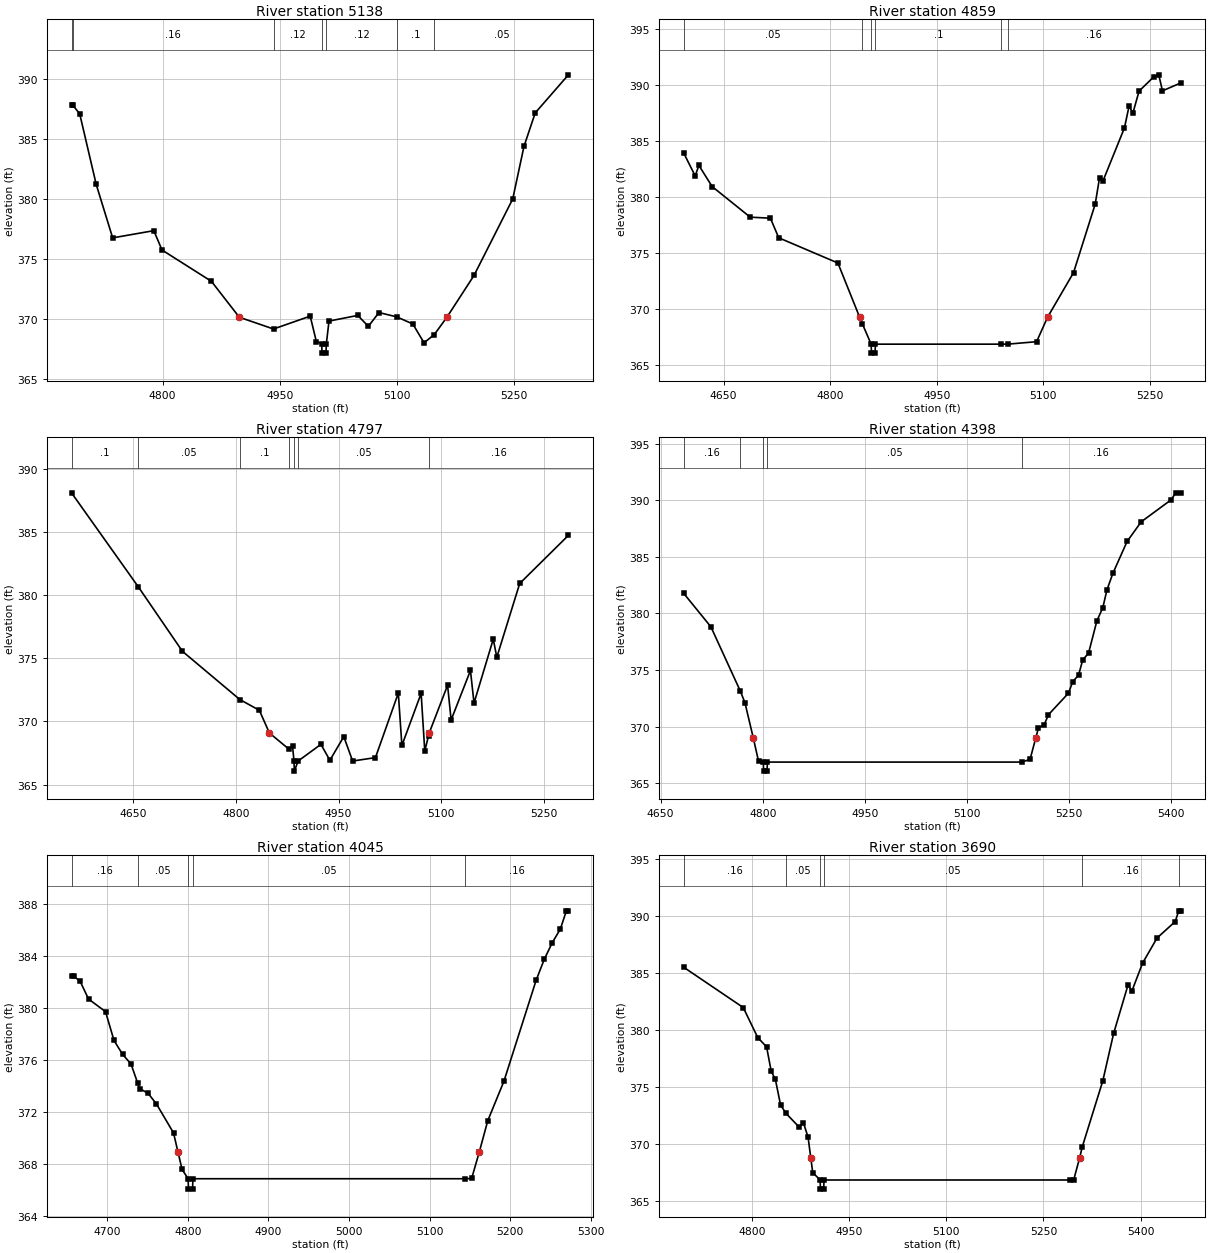
Type RM Length L Ch R = 1,5138,279,279,279
BEGIN DESCRIPTION:
UNT 043 IN DRY CR WATERSHED 7.0
END DESCRIPTION:
XS GIS Cut Line= 3
      2902524.97      6995024.99      2902225.00      6994925.00
      2902024.97      6994674.97
#Sta/Elev= 30
  4683.4  387.81  4685.1  387.81  4693.9  387.09  4715.0  381.22  4736.1  376.76
  4788.8  377.36  4799.3  375.75  4862.6  373.14  4898.3  370.15  4942.1  369.17
  4989.1  370.24  4997.0  368.12  5003.8  367.96  5004.3  367.16  5009.3  367.16
  5009.8  367.96  5013.2  369.83  5050.0  370.30  5063.6  369.39  5077.2  370.54
  5099.9  370.18  5120.5  369.59  5134.9  368.02  5148.1  368.71  5164.2  370.15
  5198.9  373.63  5248.5  380.00  5262.9  384.38  5277.3  387.17  5319.8  390.34
#Mann=7,-1,0
  4683.4    0.05       0  4685.1    0.16       0  4942.1    0.12       0
  5003.8    0.07       0  5009.8    0.12       0  5099.9     0.1       0
  5148.1    0.05       0
Bank Sta=4898.3,5164.2
Exp/Cntr=0.3,0.1

Type RM Length L Ch R = 1,4859,62,62,62
BEGIN DESCRIPTION:
Mapping XS 3c9e1813
END DESCRIPTION:
XS GIS Cut Line= 3
      2902673.49      6994775.08      2902295.87      6994665.70
      2901998.21      6994593.23
#Sta/Elev= 30
  4593.9  383.92  4610.1  381.87  4615.3  382.81  4634.0  380.92  4687.6  378.19
  4716.0  378.10  4727.7  376.35  4811.0  374.10  4841.5  369.28  4845.6  368.65
  4857.8  366.86  4858.3  366.06  4863.3  366.06  4863.8  366.86  5041.2  366.86
  5049.8  366.86  5090.7  367.08  5106.3  369.28  5142.7  373.24  5173.2  379.35
  5179.3  381.69  5184.4  381.46  5214.4  386.16  5221.0  388.13  5226.2  387.46
  5235.0  389.44  5255.5  390.70  5262.7  390.89  5267.9  389.46  5293.4  390.16
#Mann=6,-1,0
  4593.9    0.05       0  4845.6     0.1       0  4857.8    0.07       0
  4863.8     0.1       0  5041.2    0.05       0  5049.8    0.16       0
Bank Sta=4841.5,5106.3
Exp/Cntr=0.3,0.1

Type RM Length L Ch R = 1,4797,399,399,399
BEGIN DESCRIPTION:
Mapping XS 651780b2
END DESCRIPTION:
XS GIS Cut Line= 3
      2902741.18      6994717.79      2902350.56      6994621.43
      2902040.62      6994530.27
#Sta/Elev= 30
  4560.1  388.10  4657.8  380.64  4722.0  375.55  4805.8  371.73  4834.3  370.88
  4849.0  369.08  4877.3  367.81  4882.8  368.04  4884.9  366.86  4885.4  366.06
  4890.9  366.86  4924.2  368.18  4937.3  366.92  4957.6  368.79  4970.5  366.86
  5003.8  367.13  5037.2  372.24  5042.4  368.09  5070.5  372.22  5075.8  367.66
  5081.4  368.88  5082.3  369.08  5109.1  372.86  5114.3  370.11  5142.5  374.03
  5147.7  371.45  5175.8  376.51  5181.0  375.08  5214.4  380.92  5285.5  384.73
#Mann=7,-1,0
  4560.1     0.1       0  4657.8    0.05       0  4805.8     0.1       0
  4877.3    0.05       0  4884.9   0.033       0  4890.9    0.05       0
  5081.4    0.16       0
Bank Sta=4849,5082.3
Exp/Cntr=0.3,0.1

Type RM Length L Ch R = 1,4398,353,353,353
BEGIN DESCRIPTION:
UNT 043 IN DRY CR WATERSHED 5.0
END DESCRIPTION:
XS GIS Cut Line= 3
      2902624.99      6994225.00      2902325.00      6994225.00
      2902075.00      6993875.00
#Sta/Elev= 30
  4683.8  381.77  4723.8  378.81  4766.9  373.15  4773.8  372.11  4786.2  368.96
  4793.8  366.93  4800.8  366.86  4801.3  366.06  4806.3  366.06  4806.8  366.86
  5180.4  366.86  5192.7  367.09  5201.0  368.96  5205.0  369.86  5213.6  370.17
  5219.7  371.04  5249.2  372.95  5255.4  373.96  5264.0  374.54  5270.1  375.88
  5278.7  376.49  5291.0  379.35  5299.6  380.49  5305.8  382.09  5314.4  383.53
  5335.3  386.35  5356.1  388.09  5400.4  390.05  5406.5  390.64  5413.9  390.65
#Mann=5,-1,0
  4683.8    0.16       0  4766.9    0.05       0  4800.8   0.033       0
  4806.8    0.05       0  5180.4    0.16       0
Bank Sta=4786.2,5201
Exp/Cntr=0.3,0.1

Type RM Length L Ch R = 1,4045,355,355,355
BEGIN DESCRIPTION:
UNT 043 IN DRY CR WATERSHED 4.0
END DESCRIPTION:
XS GIS Cut Line= 3
      2902725.03      6993975.01      2902425.00      6993875.00
      2902124.96      6993875.00
#Sta/Elev= 30
  4655.8  382.44  4658.5  382.44  4666.4  382.07  4676.9  380.69  4698.0  379.72
  4708.5  377.50  4719.1  376.44  4729.6  375.69  4737.7  374.25  4740.2  373.80
  4750.7  373.44  4761.2  372.61  4782.3  370.39  4788.0  368.88  4792.9  367.58
  4800.4  366.86  4800.9  366.06  4805.9  366.06  4806.4  366.86  5144.1  366.86
  5152.1  366.88  5161.4  368.88  5172.1  371.33  5192.1  374.36  5232.1  382.14
  5242.1  383.74  5252.1  385.03  5262.1  386.08  5269.6  387.48  5272.1  387.48
#Mann=5,-1,0
  4655.8    0.16       0  4737.7    0.05       0  4800.4   0.033       0
  4806.4    0.05       0  5144.1    0.16       0
Bank Sta=4788,5161.4
Exp/Cntr=0.3,0.1

Type RM Length L Ch R = 1,3690,282,282,282
BEGIN DESCRIPTION:
UNT 043 IN DRY CR WATERSHED 3.0
END DESCRIPTION:
XS GIS Cut Line= 3
      2902874.98      6993824.98      2902625.00      6993625.00
      2902225.04      6993425.02
#Sta/Elev= 30
  4694.4  385.49  4786.4  381.96  4808.8  379.33  4822.4  378.52  4829.6  376.38
  4836.0  375.67  4844.0  373.43  4852.5  372.69  4872.9  371.48  4879.3  371.88
  4886.5  370.60  4890.7  368.79  4893.7  367.51  4905.1  366.86  4905.6  366.06
  4910.6  366.06  4911.1  366.86  5291.2  366.86  5296.8  366.90  5305.8  368.79
  5309.9  369.76  5341.6  375.54  5358.3  379.69  5380.7  383.97  5386.3  383.37
  5403.0  385.85  5425.4  388.05  5453.4  389.49  5458.9  390.43  5461.7  390.43
#Mann=6,-1,0
  4694.4    0.16       0  4852.5    0.05       0  4905.1   0.033       0
  4911.1    0.05       0  5309.9    0.16       0  5458.9    0.05       0
Bank Sta=4890.7,5305.8
Exp/Cntr=0.3,0.1

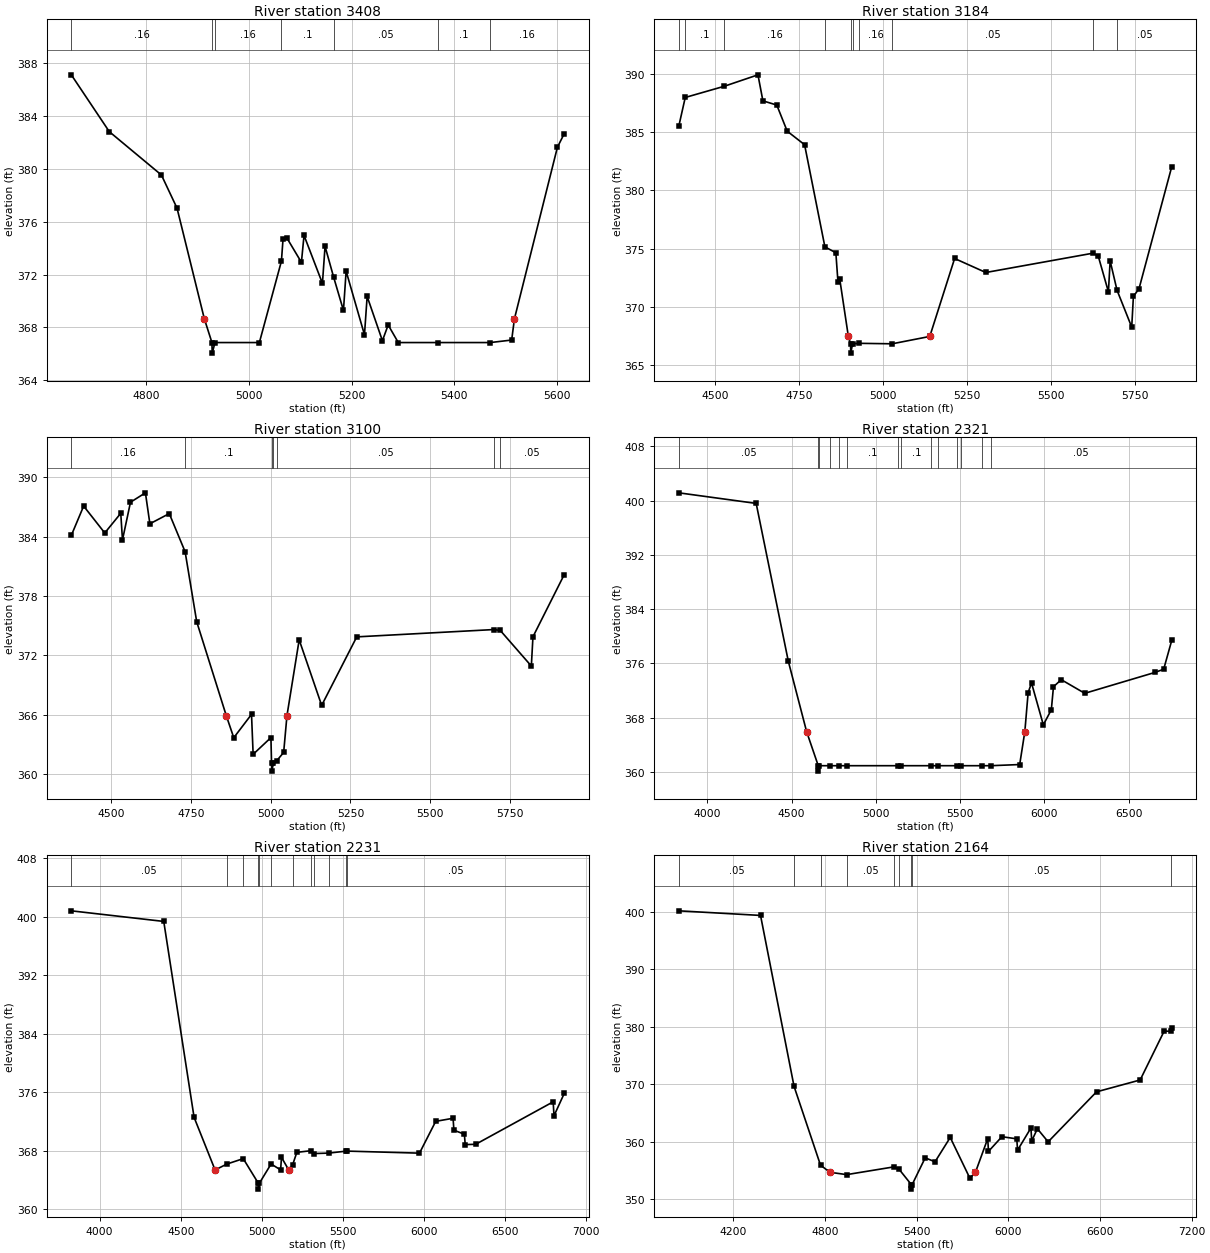
Type RM Length L Ch R = 1,3408,224,224,224
BEGIN DESCRIPTION:
Mapping XS 75ad1a7a
END DESCRIPTION:
XS GIS Cut Line= 3
      2902960.97      6993887.91      2902901.95      6993532.02
      2902322.08      6993384.45
#Sta/Elev= 30
  4654.7  387.12  4728.6  382.82  4830.0  379.54  4860.4  377.03  4913.5  368.66
  4928.3  366.86  4928.8  366.06  4934.3  366.86  5020.6  366.86  5063.5  373.02
  5066.6  374.67  5074.2  374.77  5102.4  372.93  5107.5  374.97  5143.3  371.34
  5148.4  374.14  5165.1  371.81  5184.2  369.29  5189.4  372.26  5225.1  367.45
  5230.3  370.35  5260.0  367.00  5271.2  368.19  5290.9  366.86  5368.3  366.86
  5469.9  366.86  5511.5  367.05  5516.9  368.66  5600.5  381.64  5613.8  382.67
#Mann=7,-1,0
  4654.7    0.16       0  4928.3    0.07       0  4934.3    0.16       0
  5063.5     0.1       0  5165.1    0.05       0  5368.3     0.1       0
  5469.9    0.16       0
Bank Sta=4913.5,5516.9
Exp/Cntr=0.3,0.1

Type RM Length L Ch R = 1,3184,84,84,84
BEGIN DESCRIPTION:
Mapping XS d3605fe7
END DESCRIPTION:
XS GIS Cut Line= 6
      2902990.48      6994117.14      2903122.43      6993610.15
      2903129.38      6993478.20      2902926.25      6993469.52
      2902499.17      6993387.93      2902328.69      6993363.82
#Sta/Elev= 30
  4392.8  385.51  4412.0  387.97  4528.1  388.93  4628.3  389.91  4643.0  387.68
  4684.3  387.32  4715.3  385.08  4767.0  383.92  4827.4  375.17  4860.0  374.66
  4866.2  372.19  4871.4  372.44  4897.2  367.49  4903.8  366.86  4904.3  366.06
  4909.8  366.86  4929.8  366.90  5027.6  366.86  5139.4  367.49  5213.3  374.17
  5306.1  372.97  5623.9  374.62  5640.3  374.40  5670.8  371.31  5675.9  373.97
  5696.4  371.45  5740.1  368.29  5745.1  370.92  5761.8  371.58  5859.1  382.03
#Mann=10,-1,0
  4392.8    0.16       0  4412.0     0.1       0  4528.1    0.16       0
  4827.4     0.1       0  4903.8    0.07       0  4909.8     0.1       0
  4929.8    0.16       0  5027.6    0.05       0  5623.9     0.1       0
  5696.4    0.05       0
Bank Sta=4897.2,5139.4
Exp/Cntr=0.3,0.1

Type RM Length L Ch R = 1,3100,779,779,779
BEGIN DESCRIPTION:
Mapping XS 4c188775
END DESCRIPTION:
XS GIS Cut Line= 6
      2903015.48      6994113.29      2903189.97      6993639.31
      2903216.01      6993483.06      2903122.26      6993467.44
      2902992.05      6993467.44      2902343.63      6993352.86
#Sta/Elev= 30
  4373.9  384.13  4412.6  387.10  4478.9  384.38  4529.1  386.37  4534.5  383.68
  4559.6  387.49  4606.5  388.44  4620.5  385.31  4681.4  386.34  4731.1  382.48
  4767.5  375.40  4860.2  365.91  4883.8  363.67  4939.5  366.03  4944.6  361.99
  5000.4  363.68  5002.4  361.09  5002.9  360.29  5008.4  361.09  5018.9  361.35
  5040.4  362.18  5050.8  365.91  5089.1  373.57  5159.7  366.94  5269.8  373.87
  5700.1  374.61  5720.3  374.52  5817.8  370.92  5822.9  373.88  5921.1  380.17
#Mann=7,-1,0
  4373.9    0.16       0  4731.1     0.1       0  5002.4    0.07       0
  5008.4     0.1       0  5018.9    0.05       0  5700.1     0.1       0
  5720.3    0.05       0
Bank Sta=4860.2,5050.8
Exp/Cntr=0.3,0.1

Type RM Length L Ch R = 1,2321,90,90,90
BEGIN DESCRIPTION:
Mapping XS 0697a5bd
END DESCRIPTION:
XS GIS Cut Line= 6
      2903920.87      6995192.37      2903838.41      6994285.26
      2903747.26      6993903.31      2903521.57      6993547.41
      2903321.91      6993477.96      2902345.37      6993330.40
#Sta/Elev= 30
  3830.6  401.14  4289.9  399.58  4480.6  376.33  4589.4  365.93  4658.4  360.92
  4658.9  360.12  4664.4  360.92  4727.9  360.92  4782.6  360.92  4828.7  360.92
  5132.2  360.92  5151.2  360.92  5329.6  360.92  5367.1  360.92  5484.7  360.92
  5508.0  360.92  5631.9  360.92  5682.5  360.92  5854.0  361.09  5884.5  365.93
  5904.1  371.68  5924.2  373.12  5994.3  366.94  6041.8  369.17  6054.5  372.56
  6100.7  373.60  6240.3  371.59  6657.2  374.67  6708.7  375.14  6756.4  379.38
#Mann=14,-1,0
  3830.6    0.05       0  4658.4    0.07       0  4664.4    0.05       0
  4727.9     0.1       0  4782.6    0.08       0  4828.7     0.1       0
  5132.2    0.08       0  5151.2     0.1       0  5329.6    0.05       0
  5367.1     0.1       0  5484.7    0.05       0  5508.0     0.1       0
  5631.9    0.08       0  5682.5    0.05       0
Bank Sta=4589.4,5884.5
Exp/Cntr=0.3,0.1

Type RM Length L Ch R = 1,2231,67,67,67
BEGIN DESCRIPTION:
Mapping XS a82a7f56
END DESCRIPTION:
XS GIS Cut Line= 6
      2903990.32      6995253.16      2903925.21      6994437.17
      2903808.02      6993920.67      2903577.99      6993512.69
      2903443.44      6993443.24      2902380.10      6993330.40
#Sta/Elev= 30
  3825.1  400.79  4395.1  399.34  4582.1  372.55  4711.6  365.35  4784.3  366.16
  4885.2  366.90  4978.4  363.53  4978.9  362.73  4984.4  363.53  5057.0  366.17
  5115.8  365.36  5121.0  367.08  5165.7  365.35  5189.4  366.03  5215.7  367.76
  5301.2  367.98  5319.1  367.59  5413.1  367.66  5517.8  367.92  5527.3  367.93
  5972.0  367.65  6072.0  372.00  6179.1  372.42  6184.2  370.79  6248.8  370.24
  6253.9  368.82  6318.5  368.86  6796.3  374.67  6801.4  372.76  6864.6  375.82
#Mann=12,-1,0
  3825.1    0.05       0  4784.3     0.1       0  4885.2    0.05       0
  4978.4    0.03       0  4984.4    0.05       0  5057.0     0.1       0
  5189.4    0.08       0  5301.2    0.05       0  5319.1     0.1       0
  5413.1    0.05       0  5517.8     0.1       0  5527.3    0.05       0
Bank Sta=4711.6,5165.7
Exp/Cntr=0.3,0.1

Type RM Length L Ch R = 1,2164,650,650,650
BEGIN DESCRIPTION:
Mapping XS fb424da8
END DESCRIPTION:
XS GIS Cut Line= 6
      2904038.06      6995227.11      2903968.61      6994259.21
      2903803.68      6993729.70      2903564.97      6993421.54
      2903074.52      6993369.46      2902259.24      6993295.74
#Sta/Elev= 30
  3842.5  400.15  4377.6  399.35  4597.0  369.64  4770.2  355.94  4832.1  354.71
  4941.3  354.30  5251.3  355.65  5284.2  355.24  5364.3  352.58  5364.8  351.78
  5370.3  352.58  5455.4  357.22  5519.7  356.53  5619.3  360.76  5747.8  353.68
  5784.4  354.71  5864.7  360.56  5869.7  358.34  5957.3  360.89  6054.9  360.52
  6060.0  358.55  6147.5  362.41  6152.6  360.16  6189.7  362.27  6260.1  360.00
  6577.0  368.69  6862.5  370.75  7019.9  379.26  7062.0  379.20  7069.1  379.75
#Mann=9,-1,0
  3842.5    0.05       0  4597.0     0.1       0  4770.2    0.12       0
  4941.3    0.05       0  5251.3    0.08       0  5284.2    0.05       0
  5364.3    0.03       0  5370.3    0.05       0  7062.0    0.16       0
Bank Sta=4832.1,5784.4
Exp/Cntr=0.3,0.1

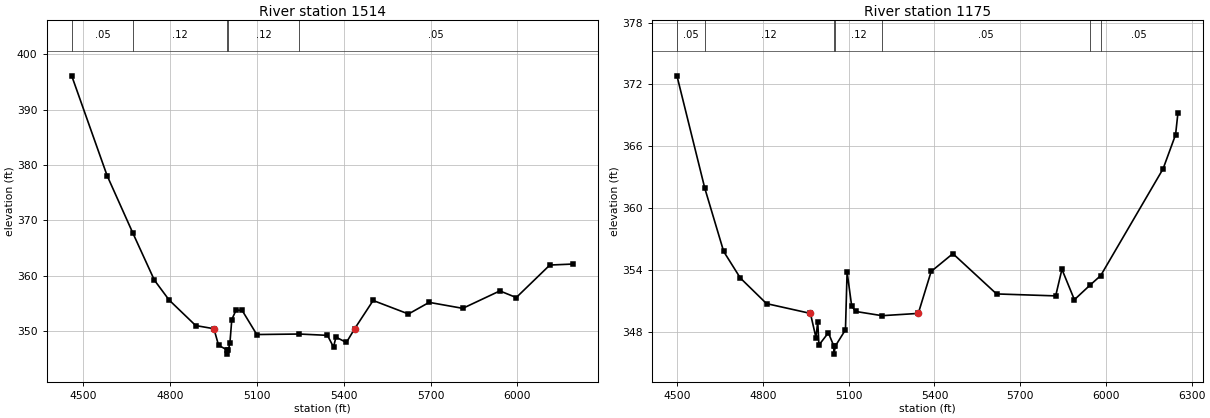
Type RM Length L Ch R = 1,1514,339,339,339
BEGIN DESCRIPTION:
UNT 043 IN DRY CR WATERSHED 2.0
END DESCRIPTION:
XS GIS Cut Line= 3
      2904425.01      6994674.96      2904525.00      6994175.00
      2905224.99      6993175.01
#Sta/Elev= 30
  4460.5  396.12  4582.8  378.09  4672.1  367.67  4746.0  359.22  4797.0  355.62
  4888.8  351.01  4951.7  350.44  4967.8  347.45  4995.7  346.65  4996.2  345.85
  5001.7  346.65  5007.0  347.87  5013.5  352.10  5028.3  353.81  5049.3  353.74
  5099.8  349.39  5247.1  349.48  5344.0  349.24  5364.9  347.12  5373.2  348.92
  5409.4  347.96  5437.9  350.44  5501.8  355.54  5623.8  353.10  5695.3  355.20
  5811.3  354.12  5939.5  357.27  5996.1  356.07  6112.1  361.94  6191.0  362.12
#Mann=5,-1,0
  4460.5    0.05       0  4672.1    0.12       0  4995.7    0.07       0
  5001.7    0.12       0  5247.1    0.05       0
Bank Sta=4951.7,5437.9
Exp/Cntr=0.3,0.1

Type RM Length L Ch R = 1,1175,0,0,0
BEGIN DESCRIPTION:
UNT 043 IN DRY CR WATERSHED 1.0
END DESCRIPTION:
XS GIS Cut Line= 3
      2904575.01      6994524.99      2904875.00      6994125.00
      2905475.01      6993024.98
#Sta/Elev= 30
  4498.9  372.84  4596.3  361.94  4662.4  355.80  4720.8  353.22  4812.4  350.74
  4966.0  349.79  4985.3  347.45  4991.6  349.00  4995.8  346.72  5028.8  347.91
  5047.6  346.64  5048.1  345.84  5053.6  346.64  5088.6  348.20  5094.3  353.81
  5110.4  350.50  5124.2  349.98  5216.6  349.57  5343.4  349.79  5388.5  353.86
  5464.5  355.59  5617.3  351.68  5824.2  351.49  5846.1  354.07  5889.7  351.12
  5944.3  352.53  5981.8  353.46  6200.1  363.82  6243.8  367.13  6251.9  369.21
#Mann=7,-1,0
  4498.9    0.05       0  4596.3    0.12       0  5047.6    0.07       0
  5053.6    0.12       0  5216.6    0.05       0  5944.3    0.12       0
  5981.8    0.05       0
Bank Sta=4966,5343.4
Exp/Cntr=0.3,0.1

Chan Stop Cuts=-1