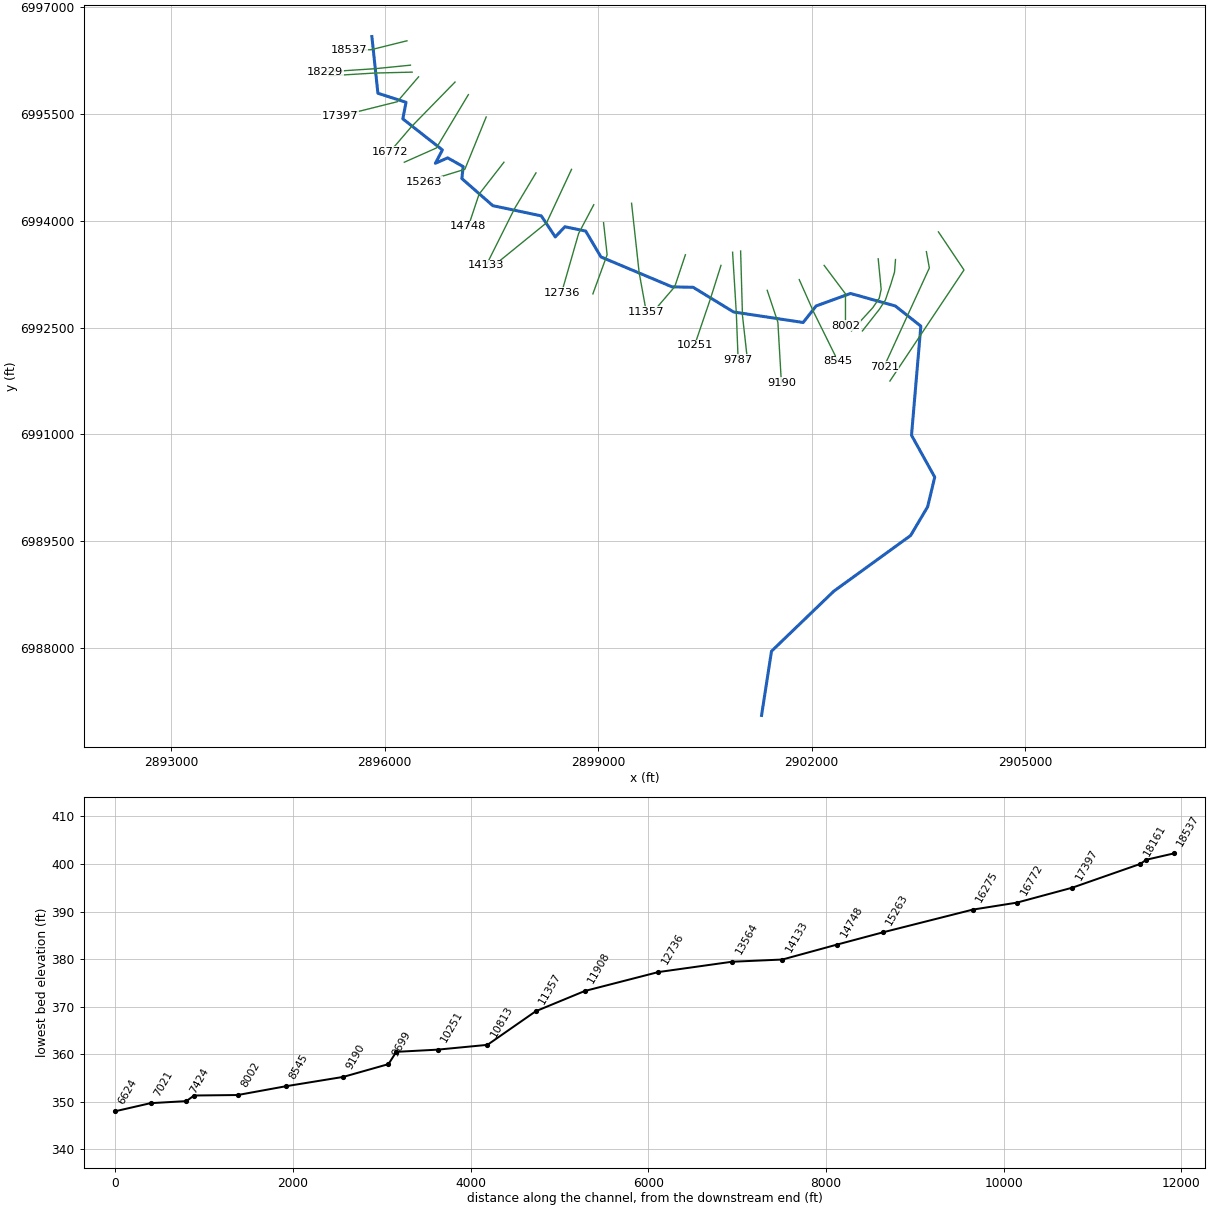
--- UNT 044 IN DRY CR WATERSHED.prj (project) ---

Proj Title=UNT 044 IN DRY CR WATERSHED Base Level Engineering
Current Plan=p01
Default Exp/Contr=0.3,0.1
English Units
Geom File=g01
Flow File=f01
Plan File=p01
BEGIN DESCRIPTION:
UNT 044 IN DRY CR WATERSHED
END DESCRIPTION:

--- UNT 044 IN DRY CR WATERSHED.p01 (plan) ---

Plan Title=Multiple Run
Short Identifier=Multiple
Geom File=g01
Flow File=f01
Subcritical Flow
K Sum by GR= 0
Std Step Tol= 0.01
Critical Tol= 0.01
Num of Std Step Trials= 20
Max Error Tol= 0.3
Flow Tol Ratio= 0.001
Split Flow NTrial= 30
Split Flow Tol= 0.02
Split Flow Ratio= 0.02
Log Output Level= 0
Friction Slope Method= 1
Unsteady Friction Slope Method= 2
Unsteady Bridges Friction Slope Method= 1
Parabolic Critical Depth
Global Vel Dist=  1 , 1 , 1
Global Log Level= 0
CheckData=True
Encroach Param= -1, 0, 0, 0
BEGIN DESCRIPTION:
Multiple Run
END DESCRIPTION:

--- UNT 044 IN DRY CR WATERSHED.f01 (steady flow) ---

Flow Title=Multiple
Number of Profiles=7
Profile Names=10-year,25-year,50-year,1pct_min,100-year,1pct_plu,500-year
River Rch & RM= UNT 044 IN DRY C,Reach-1,18537
     485     644     772     461     919    1834    1303
River Rch & RM= UNT 044 IN DRY C,Reach-1,18161
     714     968    1176     710    1417    2827    2060
River Rch & RM= UNT 044 IN DRY C,Reach-1,12736
     952    1309    1605     977    1950    3891    2884
River Rch & RM= UNT 044 IN DRY C,Reach-1,7021
    1101    1517    1863    1134    2263    4514    3348
Boundary for River Rch & Prof#=UNT 044 IN DRY C,Reach-1,1
Up Type=0
Dn Type=3
Dn Slope=0.005
Boundary for River Rch & Prof#=UNT 044 IN DRY C,Reach-1,2
Up Type=0
Dn Type=3
Dn Slope=0.005
Boundary for River Rch & Prof#=UNT 044 IN DRY C,Reach-1,3
Up Type=0
Dn Type=3
Dn Slope=0.005
Boundary for River Rch & Prof#=UNT 044 IN DRY C,Reach-1,4
Up Type=0
Dn Type=3
Dn Slope=0.005
Boundary for River Rch & Prof#=UNT 044 IN DRY C,Reach-1,5
Up Type=0
Dn Type=3
Dn Slope=0.005
Boundary for River Rch & Prof#=UNT 044 IN DRY C,Reach-1,6
Up Type=0
Dn Type=3
Dn Slope=0.005
Boundary for River Rch & Prof#=UNT 044 IN DRY C,Reach-1,7
Up Type=0
Dn Type=3
Dn Slope=0.005

--- UNT 044 IN DRY CR WATERSHED.g01 (geometry) ---

Geom Title=Existing Conditions

River Reach=UNT 044 IN DRY C,Reach-1
Reach XY= 30
      2895818.66      6996591.09      2895903.57      6995794.51
      2896298.97      6995667.28      2896253.28      6995434.80
      2896810.05      6994997.84      2896711.24      6994810.05
      2896884.33      6994886.34      2897102.07      6994763.29
      2897083.44      6994595.32      2897517.98      6994214.73
      2898199.92      6994070.98      2898396.39      6993775.11
      2898531.32      6993918.33      2898823.58      6993857.55
      2899038.04      6993494.04      2900036.85      6993073.74
      2900334.10      6993067.11      2900902.12      6992720.61
      2901879.77      6992572.65      2902062.94      6992805.10
      2902545.45      6992980.69      2903175.27      6992805.08
      2903533.85      6992521.40      2903402.95      6990987.75
      2903729.41      6990399.27      2903629.59      6989982.60
      2903390.87      6989578.96      2902310.14      6988795.54
      2901435.00      6987952.77      2901295.59      6987050.71

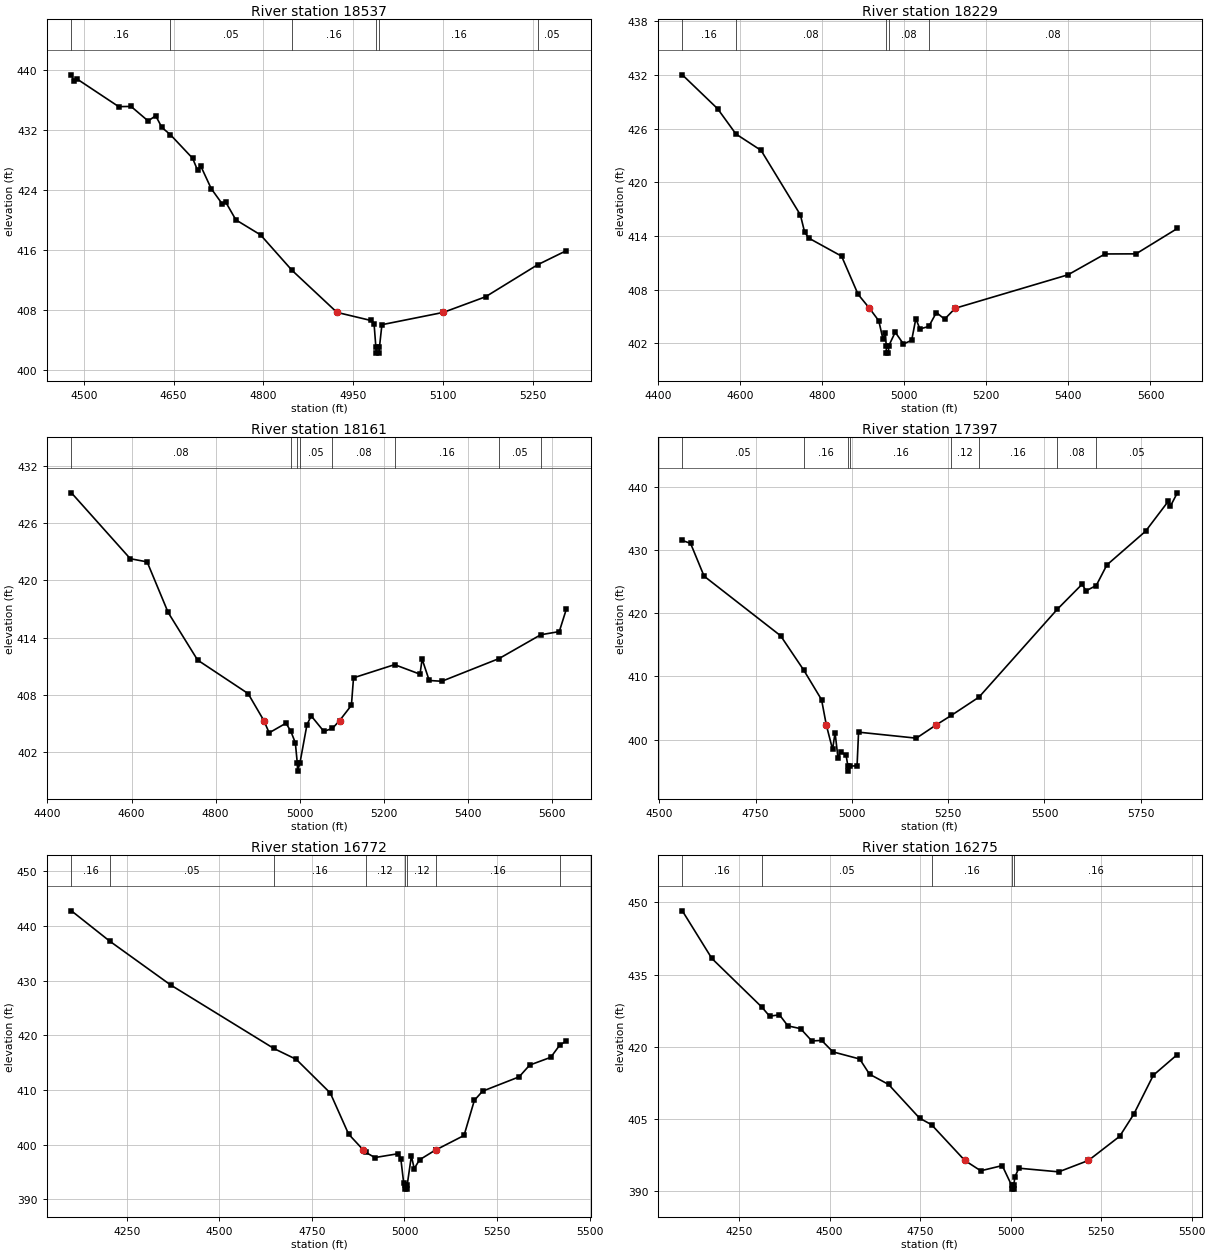
Type RM Length L Ch R = 1,18537,308,308,308
BEGIN DESCRIPTION:
UNT 044 IN DRY CR WATERSHED 19.0
END DESCRIPTION:
XS GIS Cut Line= 3
      2896311.68      6996531.56      2895806.31      6996406.15
      2895499.97      6996400.00
#Sta/Elev= 30
  4479.3  439.31  4483.4  438.50  4488.6  438.76  4558.3  435.07  4578.9  435.10
  4607.5  433.16  4620.1  433.86  4630.4  432.30  4644.7  431.33  4681.9  428.18
  4690.2  426.56  4695.4  427.16  4712.9  424.14  4731.6  422.07  4736.8  422.39
  4754.1  419.98  4795.3  417.98  4847.7  413.27  4923.0  407.65  4979.8  406.57
  4985.0  406.12  4988.0  403.02  4988.5  402.22  4993.5  402.22  4994.0  403.02
  4998.1  406.01  5100.8  407.65  5171.3  409.73  5258.1  413.99  5306.4  415.88
#Mann=6,-1,0
  4479.3    0.16       0  4644.7    0.05       0  4847.7    0.16       0
  4988.0    0.07       0  4994.0    0.16       0  5258.1    0.05       0
Bank Sta=4923,5100.8
Exp/Cntr=0.3,0.1

Type RM Length L Ch R = 1,18229,68,68,68
BEGIN DESCRIPTION:
Mapping XS 047d3623
END DESCRIPTION:
XS GIS Cut Line= 3
      2896361.05      6996188.90      2895857.56      6996138.99
      2895159.40      6996093.46
#Sta/Elev= 30
  4459.8  432.02  4545.7  428.23  4590.4  425.40  4651.6  423.57  4747.3  416.36
  4757.6  414.44  4767.4  413.77  4847.7  411.74  4887.9  407.47  4915.5  405.92
  4938.2  404.52  4948.2  402.51  4954.4  403.12  4956.4  401.70  4956.9  400.90
  4961.9  400.90  4962.4  401.70  4978.3  403.24  4998.4  401.92  5018.4  402.34
  5028.5  404.75  5038.5  403.60  5060.2  403.89  5078.6  405.44  5098.6  404.70
  5124.5  405.92  5399.2  409.66  5489.4  411.99  5564.7  412.00  5665.4  414.84
#Mann=5,-1,0
  4459.8    0.16       0  4590.4    0.08       0  4956.4    0.04       0
  4962.4    0.08       0  5060.2    0.08       0
Bank Sta=4915.5,5124.5
Exp/Cntr=0.3,0.1

Type RM Length L Ch R = 1,18161,764,764,764
BEGIN DESCRIPTION:
Mapping XS 48682359
END DESCRIPTION:
XS GIS Cut Line= 3
      2896384.92      6996091.25      2895855.39      6996078.22
      2895209.36      6996039.20
#Sta/Elev= 30
  4457.0  429.16  4597.0  422.26  4637.0  421.93  4687.0  416.63  4757.0  411.65
  4877.1  408.14  4914.7  405.30  4927.1  404.03  4967.1  405.04  4978.5  404.21
  4989.4  402.98  4994.1  400.82  4994.6  400.02  5000.1  400.82  5017.1  404.90
  5027.2  405.80  5057.2  404.18  5077.6  404.50  5094.4  405.30  5122.7  406.91
  5127.7  409.79  5225.3  411.17  5285.8  410.17  5290.8  411.75  5307.7  409.51
  5337.7  409.43  5473.9  411.81  5572.9  414.30  5616.9  414.63  5633.9  417.01
#Mann=8,-1,0
  4457.0    0.08       0  4978.5    0.05       0  4994.1    0.04       0
  5000.1    0.05       0  5077.6    0.08       0  5225.3    0.16       0
  5473.9    0.05       0  5572.9    0.08       0
Bank Sta=4914.7,5094.4
Exp/Cntr=0.3,0.1

Type RM Length L Ch R = 1,17397,625,625,625
BEGIN DESCRIPTION:
UNT 044 IN DRY CR WATERSHED 18.0
END DESCRIPTION:
XS GIS Cut Line= 3
      2896474.98      6996024.98      2896175.00      6995675.00
      2895374.97      6995474.99
#Sta/Elev= 30
  4559.5  431.49  4580.9  431.03  4616.0  425.85  4814.7  416.43  4874.9  410.99
  4921.1  406.32  4933.5  402.31  4949.7  398.46  4956.2  401.10  4963.9  397.05
  4970.5  398.11  4984.8  397.54  4989.5  395.83  4990.0  395.03  4995.5  395.83
  5013.3  395.87  5017.2  401.19  5167.3  400.24  5218.2  402.31  5257.9  403.83
  5330.0  406.73  5533.0  420.59  5597.7  424.57  5608.0  423.53  5634.5  424.37
  5662.1  427.62  5762.6  432.95  5821.9  437.71  5827.0  436.90  5845.1  439.02
#Mann=8,-1,0
  4559.5    0.05       0  4874.9    0.16       0  4989.5    0.07       0
  4995.5    0.16       0  5257.9    0.12       0  5330.0    0.16       0
  5533.0    0.08       0  5634.5    0.05       0
Bank Sta=4933.5,5218.2
Exp/Cntr=0.3,0.1

Type RM Length L Ch R = 1,16772,497,497,497
BEGIN DESCRIPTION:
UNT 044 IN DRY CR WATERSHED 17.0
END DESCRIPTION:
XS GIS Cut Line= 3
      2896987.11      6995951.48      2896375.00      6995325.00
      2896075.03      6994975.03
#Sta/Elev= 30
  4100.5  442.75  4203.9  437.21  4368.2  429.21  4647.2  417.59  4707.7  415.60
  4799.6  409.45  4849.1  401.93  4887.9  399.10  4894.8  398.63  4919.9  397.65
  4983.5  398.36  4990.1  397.41  4997.8  393.01  5001.3  392.68  5001.8  391.88
  5006.9  391.88  5007.4  392.68  5018.6  397.94  5026.3  395.63  5040.6  397.24
  5084.4  399.06  5086.2  399.10  5160.8  401.69  5188.7  408.11  5210.7  409.78
  5309.5  412.40  5338.0  414.55  5395.1  415.98  5419.0  418.18  5437.3  418.98
#Mann=8,-1,0
  4100.5    0.16       0  4203.9    0.05       0  4647.2    0.16       0
  4894.8    0.12       0  5001.3    0.07       0  5007.4    0.12       0
  5084.4    0.16       0  5419.0    0.08       0
Bank Sta=4887.9,5086.2
Exp/Cntr=0.3,0.1

Type RM Length L Ch R = 1,16275,1012,1012,1012
BEGIN DESCRIPTION:
UNT 044 IN DRY CR WATERSHED 16.0
END DESCRIPTION:
XS GIS Cut Line= 3
      2897174.98      6995774.96      2896725.00      6995025.00
      2896275.04      6994825.02
#Sta/Elev= 30
  4093.5  448.24  4175.1  438.34  4313.0  428.24  4334.5  426.35  4361.7  426.63
  4385.0  424.33  4420.0  423.76  4451.1  421.20  4478.3  421.31  4509.4  418.93
  4583.3  417.45  4610.5  414.29  4662.9  412.17  4748.5  405.17  4781.8  403.79
  4873.5  396.37  4917.6  394.22  4977.0  395.30  5002.7  391.21  5003.2  390.41
  5008.3  390.41  5008.8  391.21  5011.9  392.96  5022.8  394.76  5132.9  394.00
  5215.0  396.37  5301.2  401.38  5340.2  405.98  5394.2  414.08  5460.5  418.38
#Mann=5,-1,0
  4093.5    0.16       0  4313.0    0.05       0  4781.8    0.16       0
  5002.7    0.07       0  5008.8    0.16       0
Bank Sta=4873.5,5215
Exp/Cntr=0.3,0.1

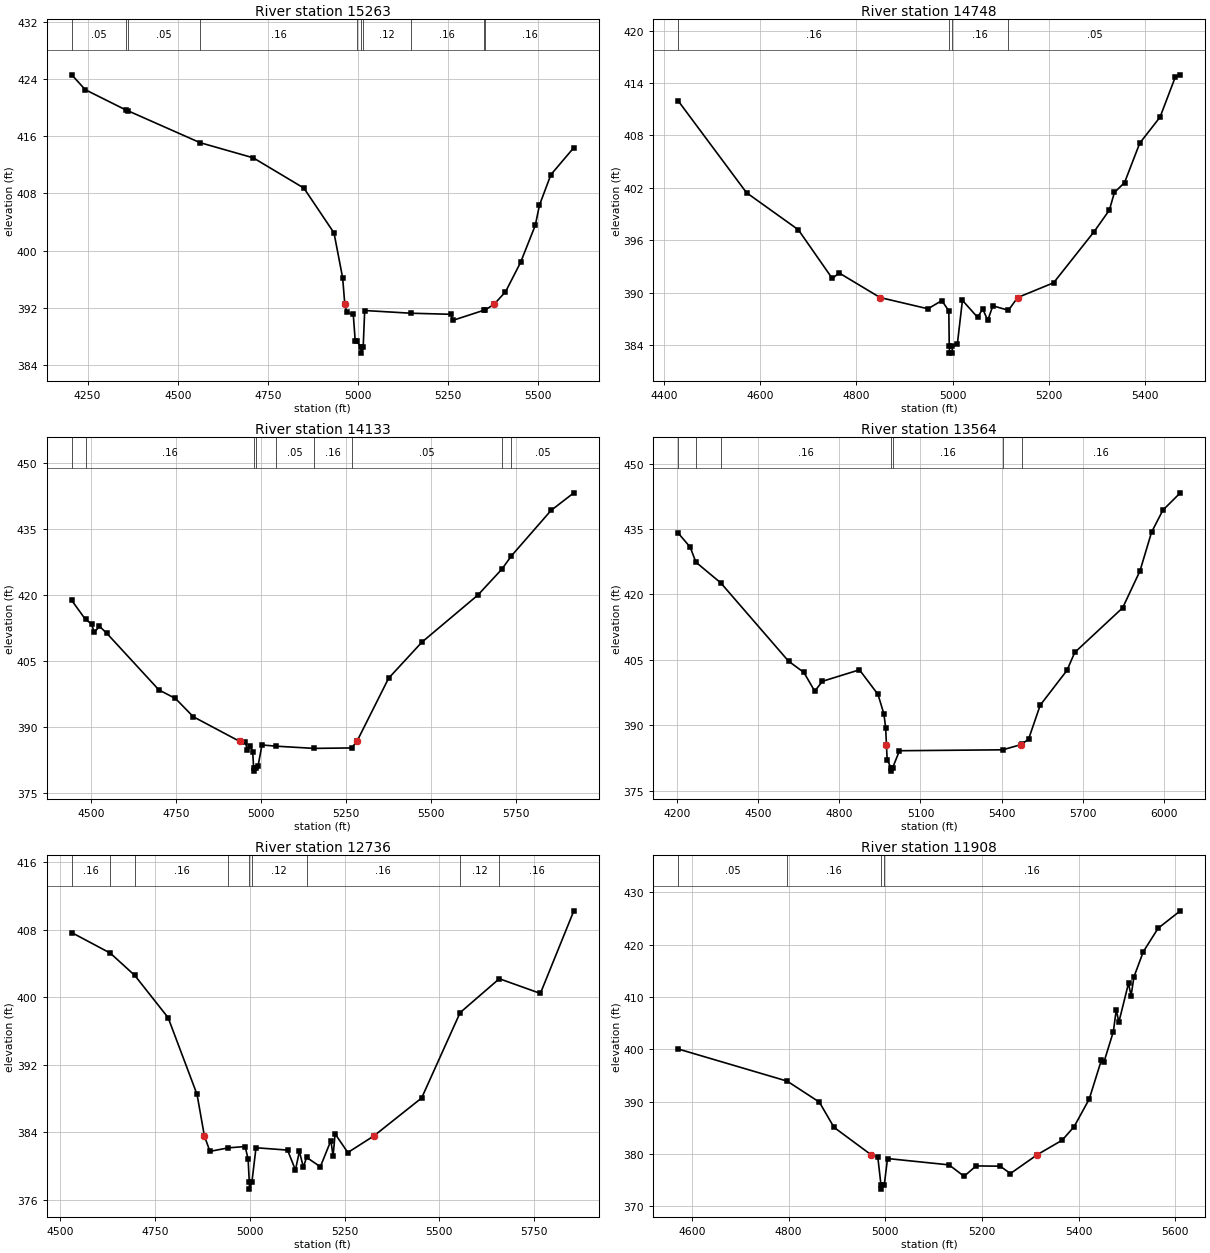
Type RM Length L Ch R = 1,15263,515,515,515
BEGIN DESCRIPTION:
UNT 044 IN DRY CR WATERSHED 15.0
END DESCRIPTION:
XS GIS Cut Line= 3
      2897425.50      6995461.08      2897125.74      6994726.05
      2896553.79      6994549.79
#Sta/Elev= 30
  4206.2  424.62  4243.5  422.54  4356.5  419.69  4361.7  419.59  4561.7  415.12
  4709.5  412.99  4849.9  408.75  4933.4  402.47  4957.4  396.17  4963.3  392.48
  4968.7  391.33  4986.8  391.06  4992.2  387.38  4996.6  387.32  5008.2  386.43
  5008.7  385.63  5014.3  386.43  5018.5  391.60  5146.9  391.22  5257.7  391.07
  5262.9  390.22  5348.0  391.62  5352.7  391.68  5377.4  392.48  5408.9  394.21
  5450.7  398.33  5491.6  403.54  5503.1  406.35  5534.8  410.63  5598.5  414.42
#Mann=10,-1,0
  4206.2    0.05       0  4356.5    0.16       0  4361.7    0.05       0
  4561.7    0.16       0  4996.6    0.12       0  5008.2    0.07       0
  5014.3    0.12       0  5146.9    0.16       0  5348.0    0.12       0
  5352.7    0.16       0
Bank Sta=4963.3,5377.4
Exp/Cntr=0.3,0.1

Type RM Length L Ch R = 1,14748,615,615,615
BEGIN DESCRIPTION:
UNT 044 IN DRY CR WATERSHED 14.0
END DESCRIPTION:
XS GIS Cut Line= 3
      2897675.03      6994825.03      2897325.00      6994375.00
      2897174.99      6993924.97
#Sta/Elev= 30
  4429.2  411.96  4571.3  401.44  4679.0  397.20  4749.6  391.62  4764.1  392.24
  4849.1  389.43  4948.7  388.14  4977.6  389.08  4992.1  387.90  4993.0  383.86
  4993.5  383.06  4998.9  383.06  4999.4  383.86  5009.9  384.11  5020.4  389.11
  5052.0  387.16  5062.6  388.13  5073.1  386.81  5083.7  388.48  5116.1  387.97
  5135.3  389.43  5210.1  391.12  5294.5  396.99  5326.1  399.45  5336.6  401.47
  5357.7  402.60  5389.3  407.12  5431.5  410.10  5463.1  414.67  5473.7  414.95
#Mann=4,-1,0
  4429.2    0.16       0  4993.0    0.07       0  4999.4    0.16       0
  5116.1    0.05       0
Bank Sta=4849.1,5135.3
Exp/Cntr=0.3,0.1

Type RM Length L Ch R = 1,14133,569,569,569
BEGIN DESCRIPTION:
UNT 044 IN DRY CR WATERSHED 13.0
END DESCRIPTION:
XS GIS Cut Line= 3
      2898124.98      6994674.96      2897825.00      6994175.00
      2897424.99      6993374.98
#Sta/Elev= 30
  4444.0  418.79  4484.5  414.46  4502.3  413.45  4510.0  411.52  4525.6  412.90
  4547.0  411.32  4700.5  398.41  4749.1  396.47  4801.6  392.31  4938.7  386.67
  4955.1  386.47  4961.0  384.62  4968.7  385.70  4976.5  384.27  4979.1  380.72
  4979.6  379.92  4985.5  380.72  4992.1  381.04  5003.7  385.88  5045.8  385.60
  5156.5  385.10  5267.2  385.20  5283.0  386.67  5376.4  401.08  5474.3  409.29
  5639.2  420.03  5710.0  425.95  5737.9  428.96  5854.4  439.30  5921.5  443.31
#Mann=9,-1,0
  4444.0    0.05       0  4484.5    0.16       0  4979.1    0.07       0
  4985.5    0.16       0  5045.8    0.05       0  5156.5    0.16       0
  5267.2    0.05       0  5710.0    0.16       0  5737.9    0.05       0
Bank Sta=4938.7,5283
Exp/Cntr=0.3,0.1

Type RM Length L Ch R = 1,13564,828,828,828
BEGIN DESCRIPTION:
UNT 044 IN DRY CR WATERSHED 12.0
END DESCRIPTION:
XS GIS Cut Line= 3
      2898625.02      6994725.03      2898275.00      6993975.00
      2897474.97      6993324.98
#Sta/Elev= 30
  4203.3  434.05  4247.5  430.84  4268.8  427.38  4360.7  422.64  4611.6  404.68
  4668.4  402.09  4708.6  397.80  4737.0  400.06  4874.1  402.69  4942.7  397.05
  4964.8  392.53  4971.1  389.38  4974.0  385.55  4976.6  382.10  4990.7  380.25
  4991.2  379.45  4997.1  380.25  5022.3  384.13  5404.3  384.34  5473.0  385.55
  5476.3  385.71  5500.0  386.77  5543.2  394.58  5642.3  402.57  5671.0  406.68
  5848.4  416.92  5912.3  425.35  5955.5  434.29  5997.3  439.32  6061.8  443.30
#Mann=7,-1,0
  4203.3    0.08       0  4268.8    0.05       0  4360.7    0.16       0
  4990.7    0.07       0  4997.1    0.16       0  5404.3    0.05       0
  5476.3    0.16       0
Bank Sta=4974,5473
Exp/Cntr=0.3,0.1

Type RM Length L Ch R = 1,12736,828,828,828
BEGIN DESCRIPTION:
UNT 044 IN DRY CR WATERSHED 11.0
END DESCRIPTION:
XS GIS Cut Line= 3
      2898937.34      6994227.43      2898725.00      6993825.00
      2898484.52      6992988.91
#Sta/Elev= 30
  4529.9  407.65  4631.6  405.22  4696.2  402.58  4784.2  397.58  4860.5  388.49
  4879.9  383.58  4894.5  381.75  4943.3  382.17  4987.5  382.32  4995.3  380.82
  4998.4  378.08  4998.9  377.28  5005.2  378.08  5016.1  382.18  5099.4  381.90
  5120.2  379.54  5130.6  381.75  5141.0  379.88  5149.6  381.04  5185.9  379.93
  5213.8  383.03  5219.5  381.17  5224.8  383.83  5258.4  381.61  5327.2  383.58
  5453.2  388.07  5554.8  398.18  5658.2  402.19  5766.6  400.45  5854.9  410.23
#Mann=9,-1,0
  4529.9    0.16       0  4631.6    0.05       0  4696.2    0.16       0
  4943.3    0.12       0  4998.4    0.07       0  5005.2    0.12       0
  5149.6    0.16       0  5554.8    0.12       0  5658.2    0.16       0
Bank Sta=4879.9,5327.2
Exp/Cntr=0.3,0.1

Type RM Length L Ch R = 1,11908,551,551,551
BEGIN DESCRIPTION:
UNT 044 IN DRY CR WATERSHED 10.0
END DESCRIPTION:
XS GIS Cut Line= 3
      2899074.99      6993975.05      2899125.00      6993525.00
      2898924.98      6992974.95
#Sta/Elev= 30
  4572.0  400.05  4797.2  393.92  4863.8  389.91  4894.0  385.10  4970.2  379.90
  4984.6  379.45  4991.2  374.10  4991.7  373.30  4998.0  374.10  5004.7  379.14
  5131.9  377.93  5163.1  375.75  5187.8  377.73  5237.6  377.68  5258.9  376.28
  5314.8  379.90  5366.0  382.65  5390.6  385.24  5421.8  390.50  5447.1  397.99
  5452.4  397.61  5471.7  403.39  5477.7  407.57  5483.0  405.16  5503.0  412.60
  5508.3  410.21  5514.3  413.84  5533.6  418.63  5564.2  423.10  5610.1  426.43
#Mann=4,-1,0
  4572.0    0.05       0  4797.2    0.16       0  4991.2    0.07       0
  4998.0    0.16       0
Bank Sta=4970.2,5314.8
Exp/Cntr=0.3,0.1

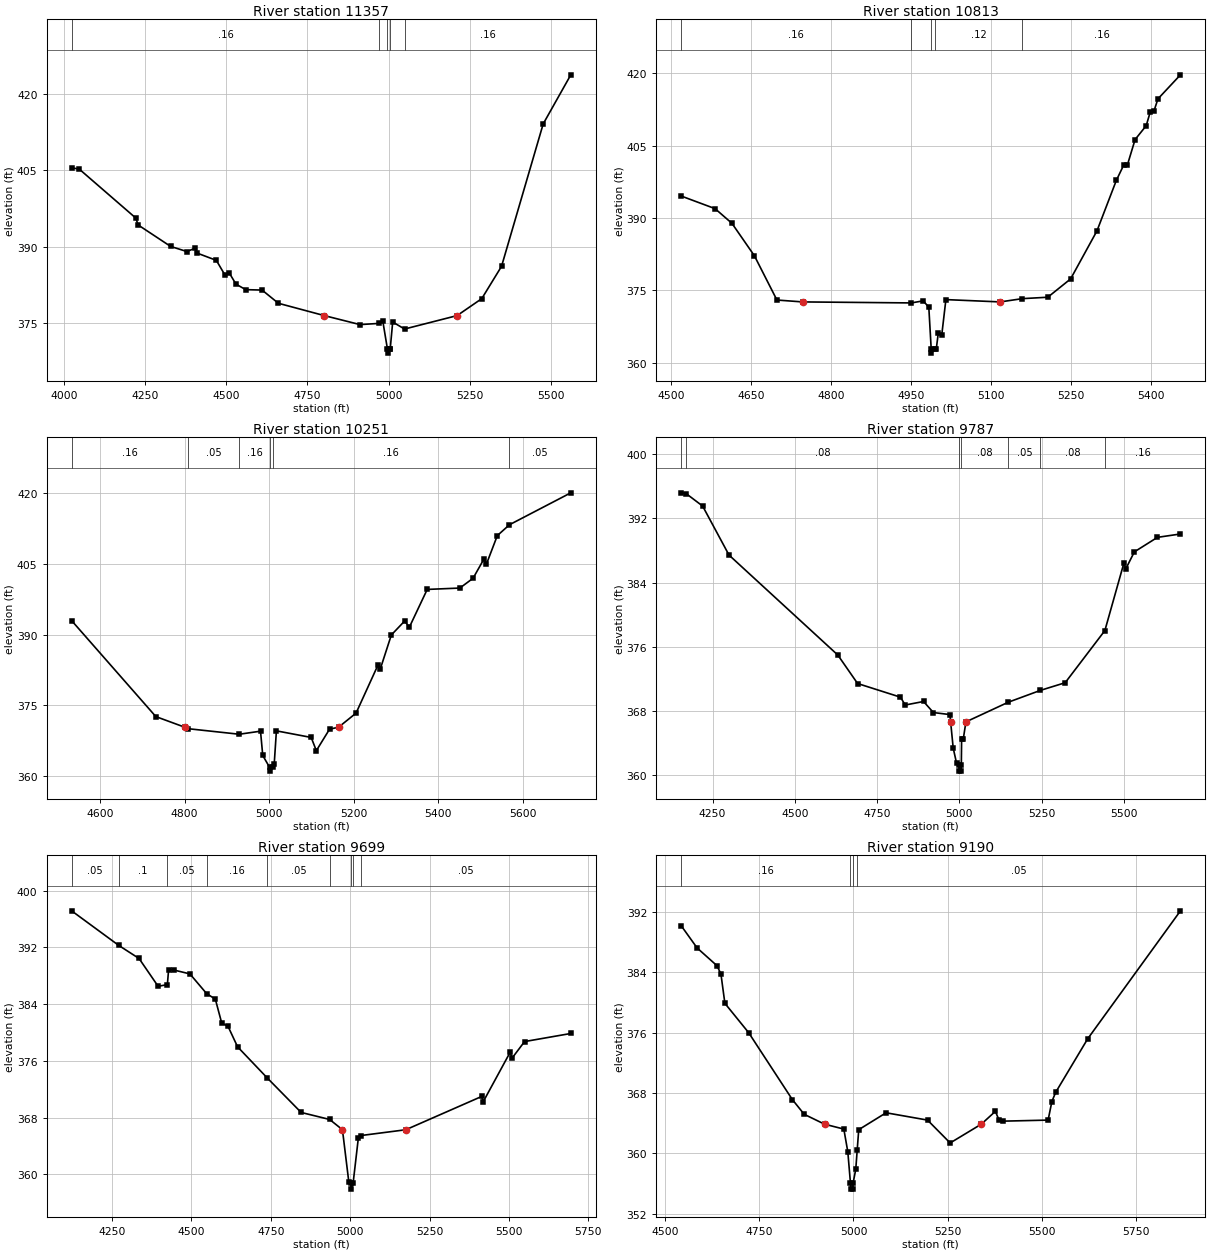
Type RM Length L Ch R = 1,11357,544,544,544
BEGIN DESCRIPTION:
UNT 044 IN DRY CR WATERSHED 9.0
END DESCRIPTION:
XS GIS Cut Line= 3
      2899468.60      6994248.30      2899575.00      6993275.00
      2899675.00      6992725.01
#Sta/Elev= 30
  4023.5  405.48  4046.9  405.24  4221.7  395.58  4228.0  394.27  4328.6  390.03
  4378.9  389.02  4404.3  389.70  4409.3  388.74  4469.4  387.29  4495.5  384.45
  4509.7  384.77  4529.8  382.62  4560.0  381.53  4610.3  381.45  4660.6  378.85
  4802.0  376.43  4912.1  374.66  4972.1  374.90  4982.5  375.28  4996.6  369.85
  4997.1  369.05  5003.5  369.85  5005.1  369.85  5012.8  375.17  5049.3  373.79
  5211.3  376.43  5287.2  379.76  5348.2  386.12  5476.5  414.12  5561.6  423.77
#Mann=5,-1,0
  4023.5    0.16       0  4972.1    0.12       0  4996.6    0.07       0
  5003.5    0.12       0  5049.3    0.16       0
Bank Sta=4802,5211.3
Exp/Cntr=0.3,0.1

Type RM Length L Ch R = 1,10813,562,562,562
BEGIN DESCRIPTION:
UNT 044 IN DRY CR WATERSHED 8.0
END DESCRIPTION:
XS GIS Cut Line= 3
      2900225.01      6993525.02      2900075.00      6993075.00
      2899775.02      6992725.03
#Sta/Elev= 30
  4519.7  394.55  4583.0  391.94  4614.6  388.90  4656.7  382.17  4698.9  372.99
  4746.9  372.60  4950.7  372.39  4973.0  372.82  4983.5  371.50  4988.0  362.78
  4988.5  361.98  4994.9  362.78  4997.4  362.78  5001.2  366.08  5007.8  365.78
  5015.5  373.08  5117.3  372.60  5158.9  373.28  5206.4  373.57  5249.2  377.37
  5298.6  387.34  5334.9  397.81  5349.1  401.08  5355.7  401.04  5370.0  406.27
  5390.8  409.14  5398.5  412.02  5405.1  412.10  5412.8  414.70  5455.0  419.69
#Mann=5,-1,0
  4519.7    0.16       0  4950.7    0.12       0  4988.0    0.07       0
  4994.9    0.12       0  5158.9    0.16       0
Bank Sta=4746.9,5117.3
Exp/Cntr=0.3,0.1

Type RM Length L Ch R = 1,10251,464,464,464
BEGIN DESCRIPTION:
UNT 044 IN DRY CR WATERSHED 7.0
END DESCRIPTION:
XS GIS Cut Line= 3
      2900725.01      6993375.05      2900576.13      6992903.59
      2900354.61      6992253.40
#Sta/Elev= 30
  4532.7  392.96  4732.0  372.56  4800.5  370.30  4808.1  369.99  4929.4  368.81
  4979.7  369.46  4985.0  364.30  5001.2  361.77  5001.7  360.97  5008.2  361.77
  5012.1  362.44  5017.3  369.53  5099.6  368.13  5111.8  365.32  5143.1  369.89
  5164.4  370.30  5205.8  373.30  5258.0  383.58  5263.2  382.69  5289.3  389.91
  5320.7  392.87  5332.0  391.57  5374.2  399.59  5451.4  399.88  5482.7  401.96
  5508.8  406.11  5514.1  404.91  5540.1  411.03  5568.9  413.34  5714.0  420.12
#Mann=6,-1,0
  4532.7    0.16       0  4808.1    0.05       0  4929.4    0.16       0
  5001.2    0.07       0  5008.2    0.16       0  5568.9    0.05       0
Bank Sta=4800.5,5164.4
Exp/Cntr=0.3,0.1

Type RM Length L Ch R = 1,9787,88,88,88
BEGIN DESCRIPTION:
Mapping XS 65808f20
END DESCRIPTION:
XS GIS Cut Line= 3
      2900888.45      6993559.80      2900940.53      6992709.08
      2900966.58      6992045.01
#Sta/Elev= 30
  4155.1  395.20  4170.0  395.10  4220.0  393.55  4300.2  387.44  4630.8  374.98
  4690.9  371.43  4821.1  369.73  4835.6  368.75  4891.3  369.19  4921.3  367.81
  4971.4  367.56  4973.6  366.65  4981.4  363.39  4991.5  361.52  4999.1  361.31
  4999.6  360.51  5005.6  360.51  5006.1  361.31  5007.0  364.51  5012.0  364.51
  5020.1  366.65  5148.8  369.10  5246.7  370.58  5321.7  371.53  5442.3  378.03
  5500.5  386.50  5505.5  385.69  5531.9  387.84  5602.0  389.65  5672.0  390.07
#Mann=7,-1,0
  4155.1    0.05       0  4170.0    0.08       0  4999.1    0.07       0
  5006.1    0.08       0  5148.8    0.05       0  5246.7    0.08       0
  5442.3    0.16       0
Bank Sta=4973.6,5020.1
Exp/Cntr=0.3,0.1

Type RM Length L Ch R = 1,9699,509,509,509
BEGIN DESCRIPTION:
Mapping XS c14e1d00
END DESCRIPTION:
XS GIS Cut Line= 3
      2901001.30      6993577.18      2901027.34      6992670.02
      2901101.13      6992010.27
#Sta/Elev= 30
  4123.3  397.16  4271.8  392.28  4335.6  390.44  4395.6  386.52  4424.7  386.76
  4428.6  388.87  4445.6  388.81  4495.6  388.27  4548.1  385.50  4575.7  384.71
  4595.7  381.35  4615.7  380.87  4645.7  377.99  4739.8  373.57  4845.8  368.74
  4935.5  367.75  4975.8  366.31  4995.8  358.97  5002.3  358.73  5002.8  357.93
  5009.3  358.73  5025.8  365.11  5033.3  365.48  5175.2  366.30  5413.9  370.99
  5419.0  370.25  5504.2  377.26  5509.2  376.36  5549.1  378.73  5694.7  379.87
#Mann=9,-1,0
  4123.3    0.05       0  4271.8     0.1       0  4424.7    0.05       0
  4548.1    0.16       0  4739.8    0.05       0  4935.5     0.1       0
  5002.3    0.07       0  5009.3     0.1       0  5033.3    0.05       0
Bank Sta=4975.8,5175.2
Exp/Cntr=0.3,0.1

Type RM Length L Ch R = 1,9190,645,645,645
BEGIN DESCRIPTION:
UNT 044 IN DRY CR WATERSHED 5.0
END DESCRIPTION:
XS GIS Cut Line= 3
      2901375.02      6993024.95      2901525.00      6992575.00
      2901574.22      6991723.81
#Sta/Elev= 30
  4542.3  390.14  4584.4  387.21  4637.1  384.86  4647.7  383.76  4658.2  379.87
  4721.4  375.98  4837.4  367.12  4869.0  365.16  4923.1  363.85  4974.4  363.20
  4985.0  360.18  4992.0  356.04  4992.5  355.24  4998.5  355.24  4999.0  356.04
  5006.1  357.86  5010.0  360.46  5014.0  363.12  5086.7  365.36  5196.9  364.39
  5257.0  361.36  5339.8  363.85  5377.2  365.55  5387.2  364.37  5397.2  364.25
  5517.4  364.39  5527.4  366.85  5537.5  368.07  5622.8  375.18  5869.2  392.13
#Mann=4,-1,0
  4542.3    0.16       0  4992.0    0.07       0  4999.0    0.16       0
  5010.0    0.05       0
Bank Sta=4923.1,5339.8
Exp/Cntr=0.3,0.1

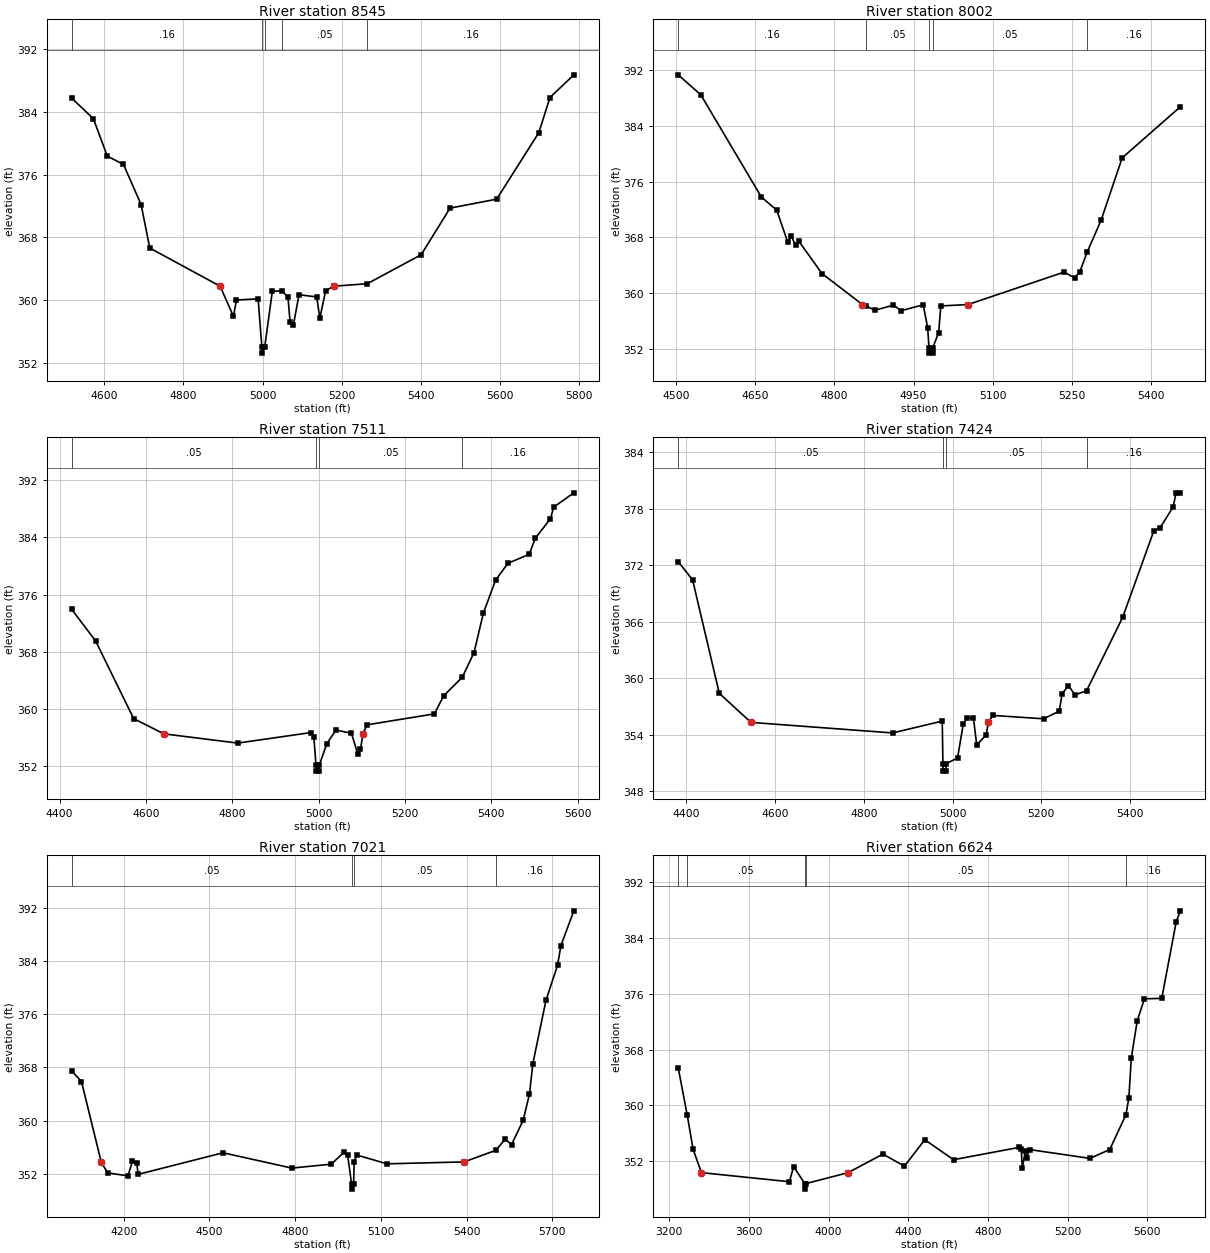
Type RM Length L Ch R = 1,8545,543,543,543
BEGIN DESCRIPTION:
UNT 044 IN DRY CR WATERSHED 4.0
END DESCRIPTION:
XS GIS Cut Line= 3
      2901825.01      6993174.97      2902025.00      6992725.00
      2902368.94      6992030.28
#Sta/Elev= 30
  4518.4  385.73  4573.1  383.09  4608.0  378.35  4649.0  377.29  4693.5  372.17
  4715.3  366.65  4892.8  361.80  4926.7  357.96  4934.2  360.04  4988.9  360.19
  4998.3  354.08  4998.9  353.28  5005.5  354.08  5024.8  361.14  5048.5  361.21
  5064.1  360.46  5069.7  357.21  5077.8  356.81  5092.1  360.71  5136.9  360.43
  5144.7  357.73  5159.4  361.24  5180.4  361.80  5264.4  362.11  5400.5  365.80
  5473.4  371.73  5591.1  372.87  5697.6  381.33  5725.6  385.80  5786.0  388.69
#Mann=5,-1,0
  4518.4    0.16       0  4998.3    0.07       0  5005.5    0.16       0
  5048.5    0.05       0  5264.4    0.16       0
Bank Sta=4892.8,5180.4
Exp/Cntr=0.3,0.1

Type RM Length L Ch R = 1,8002,491,491,491
BEGIN DESCRIPTION:
UNT 044 IN DRY CR WATERSHED 3.0
END DESCRIPTION:
XS GIS Cut Line= 3
      2902175.01      6993374.98      2902475.00      6992975.00
      2902475.00      6992524.98
#Sta/Elev= 30
  4504.7  391.28  4547.4  388.42  4662.0  373.78  4691.1  371.90  4712.0  367.29
  4718.2  368.26  4726.6  366.89  4732.8  367.47  4776.6  362.83  4853.3  358.38
  4860.1  358.19  4876.6  357.57  4912.0  358.30  4926.6  357.51  4968.2  358.35
  4976.6  355.09  4979.2  352.23  4979.7  351.43  4985.9  351.43  4986.4  352.23
  4997.4  354.35  5001.6  358.19  5052.8  358.38  5234.7  363.03  5254.7  362.21
  5264.7  363.11  5278.4  365.89  5304.7  370.44  5344.7  379.39  5454.7  386.70
#Mann=5,-1,0
  4504.7    0.16       0  4860.1    0.05       0  4979.2   0.035       0
  4986.4    0.05       0  5278.4    0.16       0
Bank Sta=4853.3,5052.8
Exp/Cntr=0.3,0.1

Type RM Length L Ch R = 1,7511,87,87,87
BEGIN DESCRIPTION:
Mapping XS 8ff08071
END DESCRIPTION:
XS GIS Cut Line= 5
      2902934.92      6993467.73      2902976.59      6993037.21
      2902948.81      6992912.21      2902858.53      6992780.26
      2902559.94      6992453.90
#Sta/Elev= 30
  4428.4  373.93  4483.8  369.51  4571.8  358.66  4641.9  356.54  4812.9  355.25
  4982.3  356.72  4989.0  356.14  4994.1  352.13  4994.6  351.33  5000.8  351.33
  5001.4  352.13  5019.1  355.16  5040.1  357.07  5076.0  356.63  5090.9  353.74
  5096.9  354.36  5103.0  356.54  5111.8  357.80  5268.2  359.33  5289.8  361.87
  5333.0  364.46  5360.1  367.91  5381.7  373.43  5410.0  378.03  5438.4  380.37
  5487.7  381.64  5501.9  383.86  5537.1  386.63  5544.5  388.23  5591.2  390.23
#Mann=4,-1,0
  4428.4    0.05       0  4994.1    0.03       0  5001.4    0.05       0
  5333.0    0.16       0
Bank Sta=4641.9,5103
Exp/Cntr=0.3,0.1

Type RM Length L Ch R = 1,7424,403,403,403
BEGIN DESCRIPTION:
Mapping XS 63f57f0c
END DESCRIPTION:
XS GIS Cut Line= 6
      2903177.97      6993457.31      2903164.09      6993280.26
      2903112.00      6993110.13      2903035.62      6992887.90
      2902952.28      6992759.43      2902712.71      6992453.89
#Sta/Elev= 30
  4381.5  372.37  4413.9  370.43  4474.1  358.40  4545.4  355.32  4865.1  354.20
  4976.7  355.46  4978.2  350.95  4978.8  350.15  4985.0  350.15  4985.5  350.95
  5011.2  351.54  5024.1  355.16  5033.3  355.83  5047.0  355.80  5054.4  352.93
  5075.5  353.98  5080.8  355.32  5090.6  356.06  5205.3  355.70  5240.5  356.51
  5246.9  358.36  5261.3  359.23  5275.8  358.24  5302.0  358.67  5383.4  366.46
  5453.9  375.66  5468.3  375.99  5497.3  378.18  5503.6  379.62  5513.4  379.67
#Mann=4,-1,0
  4381.5    0.05       0  4978.2    0.03       0  4985.5    0.05       0
  5302.0    0.16       0
Bank Sta=4545.4,5080.8
Exp/Cntr=0.3,0.1

Type RM Length L Ch R = 1,7021,397,397,397
BEGIN DESCRIPTION:
Mapping XS ba6e8d14
END DESCRIPTION:
XS GIS Cut Line= 3
      2903612.01      6993568.43      2903653.67      6993339.29
      2903018.24      6991953.85
#Sta/Elev= 30
  4018.4  367.46  4052.4  365.88  4121.3  353.81  4143.8  352.16  4215.0  351.71
  4230.5  353.89  4245.5  353.69  4250.9  351.94  4547.7  355.18  4788.7  352.88
  4926.7  353.47  4971.1  355.27  4983.7  354.91  4997.5  350.52  4998.1  349.72
  5004.8  350.52  5006.7  353.75  5015.1  354.85  5121.6  353.52  5391.3  353.81
  5503.3  355.56  5534.6  357.22  5557.6  356.42  5598.0  360.04  5620.2  364.00
  5632.0  368.56  5678.0  378.09  5718.5  383.35  5730.2  386.30  5775.5  391.52
#Mann=4,-1,0
  4018.4    0.05       0  4997.5    0.03       0  5004.8    0.05       0
  5503.3    0.16       0
Bank Sta=4121.3,5391.3
Exp/Cntr=0.3,0.1

Type RM Length L Ch R = 1,6624,0,0,0
BEGIN DESCRIPTION:
UNT 044 IN DRY CR WATERSHED 1.0
END DESCRIPTION:
XS GIS Cut Line= 3
      2903781.28      6993846.23      2904140.65      6993310.72
      2903099.84      6991750.31
#Sta/Elev= 30
  3245.0  365.38  3290.2  358.59  3319.6  353.74  3361.2  350.38  3802.8  349.08
  3824.6  351.23  3880.1  348.82  3880.7  348.02  3887.4  348.82  4097.6  350.38
  4272.5  353.03  4380.6  351.31  4482.8  355.09  4627.0  352.23  4957.5  354.00
  4966.5  353.81  4972.5  351.02  4987.5  353.53  4993.5  352.44  5008.6  353.68
  5312.0  352.42  5411.4  353.69  5492.7  358.67  5507.3  361.10  5519.5  366.78
  5549.3  372.11  5585.4  375.26  5672.5  375.32  5744.6  386.22  5765.6  387.85
#Mann=5,-1,0
  3245.0    0.08       0  3290.2    0.05       0  3880.1    0.03       0
  3887.4    0.05       0  5492.7    0.16       0
Bank Sta=3361.2,4097.6
Exp/Cntr=0.3,0.1

Chan Stop Cuts=-1