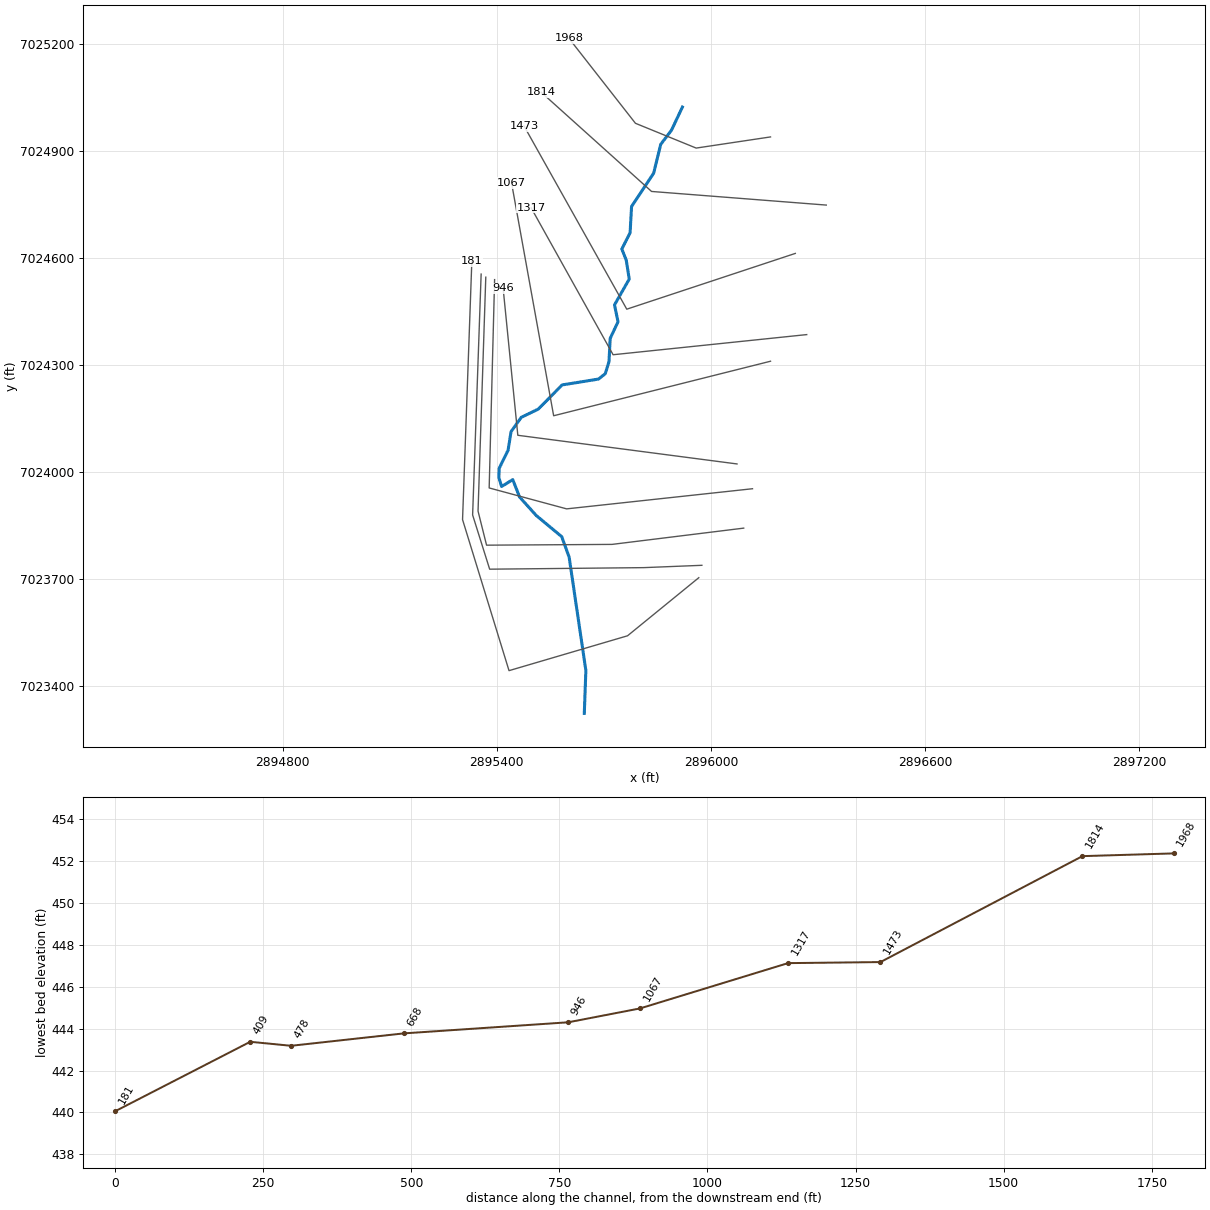
--- UNT 045 IN DRY CR WATERSHED.prj (project) ---

Proj Title=UNT 045 IN DRY CR WATERSHED Base Level Engineering
Current Plan=p01
Default Exp/Contr=0.3,0.1
English Units
Geom File=g01
Flow File=f01
Plan File=p01
BEGIN DESCRIPTION:
UNT 045 IN DRY CR WATERSHED
END DESCRIPTION:

--- UNT 045 IN DRY CR WATERSHED.p01 (plan) ---

Plan Title=Multiple Run
Short Identifier=Multiple
Geom File=g01
Flow File=f01
Subcritical Flow
K Sum by GR= 0
Std Step Tol= 0.01
Critical Tol= 0.01
Num of Std Step Trials= 20
Max Error Tol= 0.3
Flow Tol Ratio= 0.001
Split Flow NTrial= 30
Split Flow Tol= 0.02
Split Flow Ratio= 0.02
Log Output Level= 0
Friction Slope Method= 1
Unsteady Friction Slope Method= 2
Unsteady Bridges Friction Slope Method= 1
Parabolic Critical Depth
Global Vel Dist=  1 , 1 , 1
Global Log Level= 0
CheckData=True
Encroach Param= -1, 0, 0, 0
BEGIN DESCRIPTION:
Multiple Run
END DESCRIPTION:

--- UNT 045 IN DRY CR WATERSHED.f01 (steady flow) ---

Flow Title=Multiple
Number of Profiles=7
Profile Names=10-year,25-year,50-year,1pct_min,100-year,1pct_plu,500-year
River Rch & RM= UNT 045 IN DRY C,Reach-1,1968
     235     298     346     201     401     800     537
Boundary for River Rch & Prof#=UNT 045 IN DRY C,Reach-1,1
Up Type=0
Dn Type=3
Dn Slope=0.005
Boundary for River Rch & Prof#=UNT 045 IN DRY C,Reach-1,2
Up Type=0
Dn Type=3
Dn Slope=0.005
Boundary for River Rch & Prof#=UNT 045 IN DRY C,Reach-1,3
Up Type=0
Dn Type=3
Dn Slope=0.005
Boundary for River Rch & Prof#=UNT 045 IN DRY C,Reach-1,4
Up Type=0
Dn Type=3
Dn Slope=0.005
Boundary for River Rch & Prof#=UNT 045 IN DRY C,Reach-1,5
Up Type=0
Dn Type=3
Dn Slope=0.005
Boundary for River Rch & Prof#=UNT 045 IN DRY C,Reach-1,6
Up Type=0
Dn Type=3
Dn Slope=0.005
Boundary for River Rch & Prof#=UNT 045 IN DRY C,Reach-1,7
Up Type=0
Dn Type=3
Dn Slope=0.005

--- UNT 045 IN DRY CR WATERSHED.g01 (geometry) ---

Geom Title=Existing Conditions

River Reach=UNT 045 IN DRY C,Reach-1
Reach XY= 30
      2895920.37      7025023.44      2895889.67      7024958.44
      2895859.60      7024919.05      2895839.82      7024838.38
      2895777.84      7024744.77      2895773.76      7024671.29
      2895750.60      7024625.66      2895762.90      7024594.68
      2895771.42      7024541.48      2895730.11      7024469.21
      2895739.89      7024421.79      2895717.94      7024375.16
      2895714.66      7024310.26      2895704.22      7024276.42
      2895685.43      7024261.33      2895583.45      7024244.91
      2895516.63      7024177.28      2895468.75      7024153.99
      2895440.11      7024113.67      2895431.95      7024062.18
      2895406.78      7024010.84      2895406.21      7023984.85
      2895413.73      7023960.35      2895444.96      7023979.55
      2895464.06      7023930.93      2895510.94      7023878.85
      2895582.12      7023819.82      2895602.95      7023762.53
      2895649.83      7023444.82      2895645.45      7023324.63

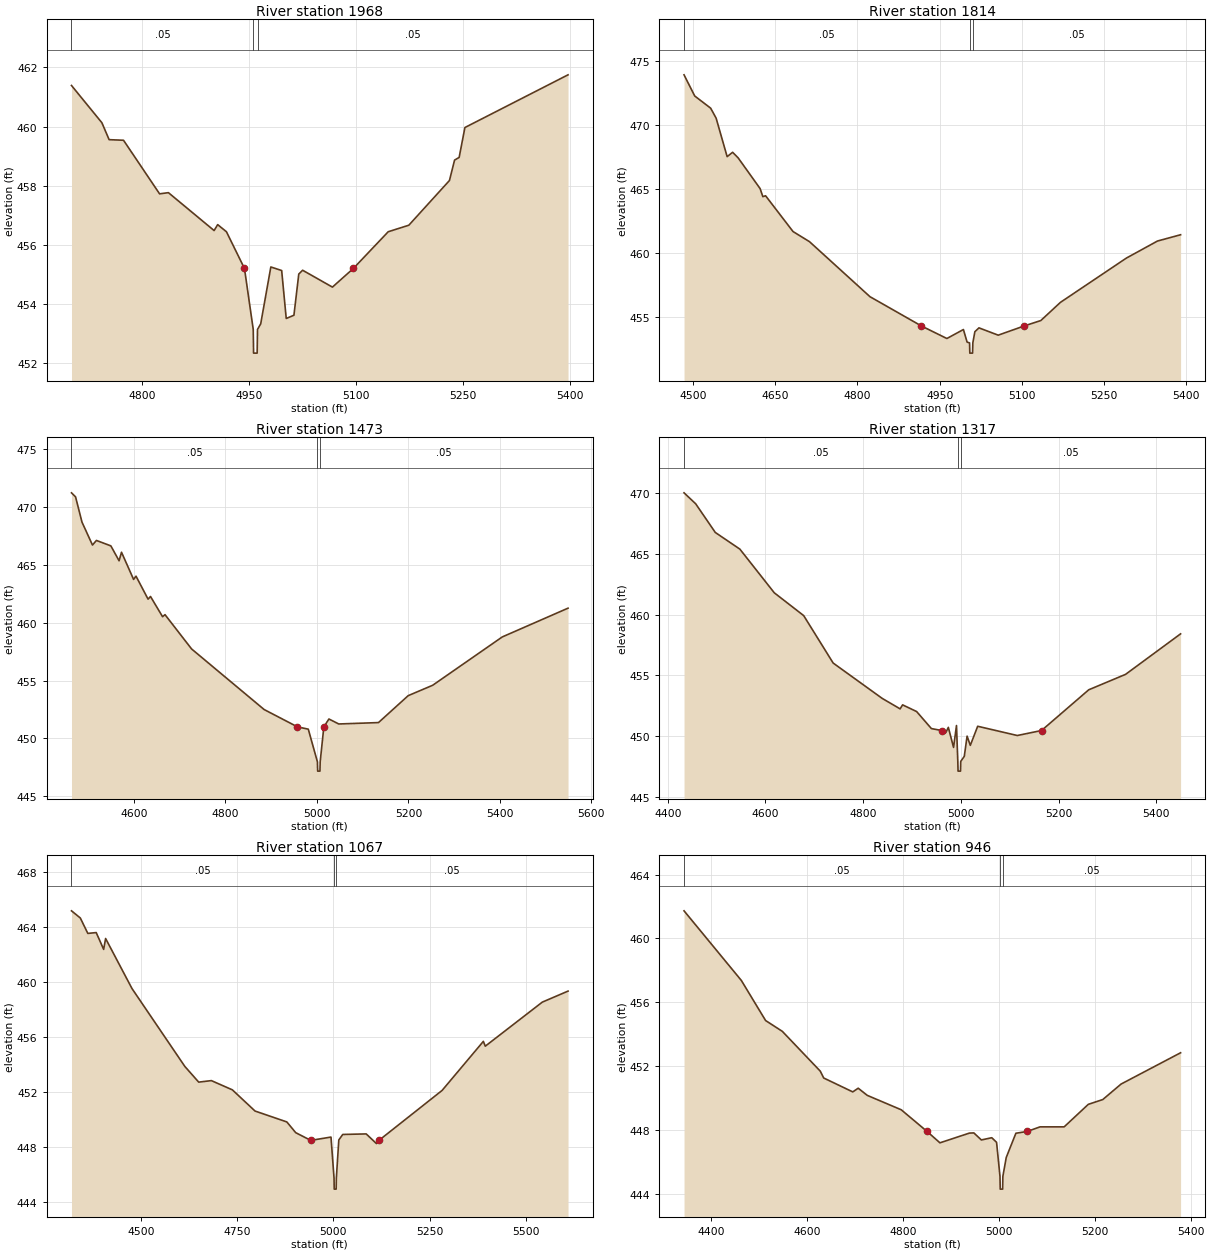
Type RM Length L Ch R = 1,1968,154,154,154
BEGIN DESCRIPTION:
UNT045 38.0
END DESCRIPTION:
XS GIS Cut Line= 4
      2896167.20      7024939.77      2895958.88      7024908.52
      2895788.74      7024977.97      2895602.43      7025216.00
#Sta/Elev= 30
  4700.5  461.39  4743.2  460.13  4753.3  459.56  4773.5  459.54  4824.1  457.73
  4836.5  457.77  4900.6  456.49  4905.6  456.69  4917.9  456.45  4943.2  455.21
  4955.5  453.15  4956.0  452.35  4961.0  452.35  4961.5  453.15  4966.0  453.34
  4980.2  455.26  4995.4  455.14  5001.8  453.52  5012.6  453.63  5019.4  455.02
  5024.8  455.15  5066.6  454.58  5096.0  455.21  5144.9  456.45  5173.8  456.67
  5230.8  458.18  5238.0  458.87  5244.4  458.96  5252.5  459.97  5397.2  461.75
#Mann=3,-1,0
  4700.5    0.05       0  4955.5    0.03       0  4961.5    0.05       0
Bank Sta=4943.2,5096
Exp/Cntr=0.3,0.1

Type RM Length L Ch R = 1,1814,341,341,341
BEGIN DESCRIPTION:
Mapping XS ee3b1b38
END DESCRIPTION:
XS GIS Cut Line= 3
      2896323.44      7024748.80      2895833.88      7024786.99
      2895524.83      7025064.79
#Sta/Elev= 30
  4483.3  473.92  4502.8  472.27  4531.9  471.32  4541.9  470.54  4562.0  467.54
  4572.0  467.88  4582.0  467.45  4622.2  465.05  4627.2  464.42  4632.2  464.49
  4682.3  461.70  4712.4  460.91  4822.8  456.62  4916.6  454.34  4963.2  453.36
  4993.4  454.06  5000.1  453.08  5004.6  453.02  5005.1  452.22  5010.1  452.22
  5010.6  453.02  5014.3  453.89  5021.8  454.19  5056.9  453.62  5104.4  454.34
  5134.7  454.76  5170.6  456.18  5290.9  459.63  5347.7  460.96  5389.9  461.45
#Mann=3,-1,0
  4483.3    0.05       0  5004.6    0.03       0  5010.6    0.05       0
Bank Sta=4916.6,5104.4
Exp/Cntr=0.3,0.1

Type RM Length L Ch R = 1,1473,156,156,156
BEGIN DESCRIPTION:
Mapping XS 499c6d31
END DESCRIPTION:
XS GIS Cut Line= 3
      2896236.70      7024613.40      2895764.43      7024457.13
      2895476.55      7024970.47
#Sta/Elev= 30
  4463.2  471.25  4472.1  470.90  4486.1  468.72  4509.1  466.73  4517.7  467.13
  4549.3  466.66  4567.3  465.37  4572.6  466.11  4599.0  463.76  4604.3  464.04
  4630.7  462.05  4636.0  462.28  4662.4  460.53  4667.7  460.71  4725.9  457.74
  4884.5  452.50  4957.4  451.00  4981.1  450.80  5001.1  447.97  5001.6  447.17
  5006.6  447.17  5007.1  447.97  5015.1  451.00  5026.2  451.68  5047.8  451.25
  5134.6  451.37  5199.6  453.70  5253.2  454.60  5405.3  458.78  5549.2  461.27
#Mann=3,-1,0
  4463.2    0.05       0  5001.1    0.03       0  5007.1    0.05       0
Bank Sta=4957.4,5015.1
Exp/Cntr=0.3,0.1

Type RM Length L Ch R = 1,1317,250,250,250
BEGIN DESCRIPTION:
Mapping XS 57742cd9
END DESCRIPTION:
XS GIS Cut Line= 3
      2896268.66      7024385.91      2895726.13      7024329.49
      2895496.59      7024740.93
#Sta/Elev= 30
  4433.3  470.01  4457.1  469.11  4497.3  466.75  4547.6  465.38  4618.0  461.79
  4678.3  459.91  4738.6  456.01  4839.1  453.10  4875.7  452.24  4880.8  452.57
  4909.5  452.02  4939.7  450.62  4960.8  450.46  4969.3  450.29  4974.4  450.72
  4985.1  449.07  4991.1  450.87  4993.8  447.92  4994.3  447.12  4999.3  447.12
  4999.8  447.92  5007.1  448.34  5012.8  450.00  5019.4  449.24  5034.5  450.81
  5115.6  450.05  5165.2  450.46  5261.9  453.81  5337.3  455.08  5449.9  458.41
#Mann=3,-1,0
  4433.3    0.05       0  4993.8    0.03       0  4999.8    0.05       0
Bank Sta=4960.8,5165.2
Exp/Cntr=0.3,0.1

Type RM Length L Ch R = 1,1067,121,121,121
BEGIN DESCRIPTION:
Mapping XS 4c674260
END DESCRIPTION:
XS GIS Cut Line= 3
      2896167.22      7024311.30      2895559.57      7024158.52
      2895441.63      7024810.69
#Sta/Elev= 30
  4320.1  465.17  4343.0  464.65  4362.5  463.53  4384.3  463.59  4403.6  462.37
  4408.7  463.16  4477.1  459.53  4614.4  453.87  4650.4  452.73  4683.3  452.84
  4737.8  452.17  4796.7  450.63  4879.2  449.84  4902.3  449.06  4941.3  448.50
  4993.9  448.74  5001.8  445.76  5002.3  444.96  5007.3  444.96  5007.8  445.76
  5014.2  448.53  5024.4  448.93  5085.3  448.97  5111.8  448.27  5118.4  448.50
  5282.5  452.13  5389.5  455.69  5394.5  455.34  5542.6  458.54  5609.4  459.34
#Mann=3,-1,0
  4320.1    0.05       0  5001.8    0.03       0  5007.8    0.05       0
Bank Sta=4941.3,5118.4
Exp/Cntr=0.3,0.1

Type RM Length L Ch R = 1,946,278,278,278
BEGIN DESCRIPTION:
Mapping XS 61e7ecf3
END DESCRIPTION:
XS GIS Cut Line= 3
      2896073.34      7024023.50      2895459.20      7024103.80
      2895417.96      7024516.17
#Sta/Elev= 30
  4343.8  461.73  4463.1  457.37  4513.6  454.86  4548.5  454.18  4627.4  451.69
  4634.6  451.26  4695.1  450.39  4706.4  450.62  4725.4  450.17  4796.0  449.27
  4849.9  447.91  4876.6  447.20  4938.0  447.81  4947.2  447.82  4962.8  447.38
  4984.5  447.52  4994.5  447.23  5001.6  445.10  5002.1  444.30  5007.1  444.30
  5007.6  445.10  5014.6  446.28  5034.7  447.80  5058.0  447.91  5085.0  448.20
  5135.2  448.20  5185.5  449.61  5215.6  449.91  5253.7  450.88  5377.6  452.84
#Mann=3,-1,0
  4343.8    0.05       0  5001.6    0.03       0  5007.6    0.05       0
Bank Sta=4849.9,5058
Exp/Cntr=0.3,0.1

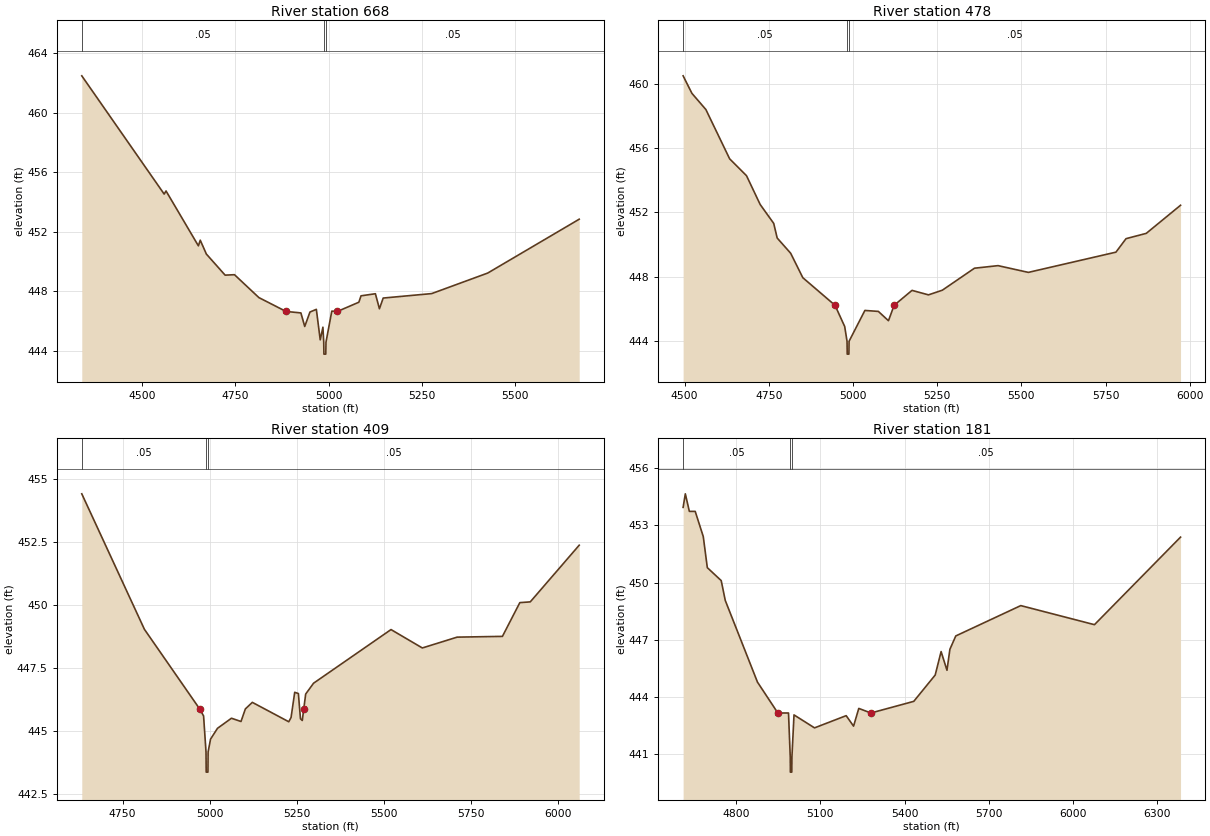
Type RM Length L Ch R = 1,668,190,190,190
BEGIN DESCRIPTION:
Mapping XS a558a203
END DESCRIPTION:
XS GIS Cut Line= 4
      2896116.75      7023954.06      2895595.92      7023897.63
      2895378.91      7023956.23      2895394.10      7024539.97
#Sta/Elev= 30
  4338.5  462.48  4559.2  454.53  4564.2  454.74  4650.9  451.05  4655.9  451.43
  4672.2  450.50  4722.5  449.08  4747.6  449.11  4813.0  447.57  4885.6  446.64
  4925.5  446.54  4935.8  445.63  4949.8  446.60  4966.9  446.78  4977.3  444.73
  4984.5  445.58  4986.7  444.57  4987.2  443.77  4992.2  443.77  4992.7  444.57
  5008.3  446.66  5023.4  446.64  5080.8  447.26  5086.6  447.69  5125.1  447.83
  5135.9  446.82  5146.0  447.54  5276.0  447.84  5426.0  449.22  5671.1  452.84
#Mann=3,-1,0
  4338.5    0.05       0  4986.7    0.03       0  4992.7    0.05       0
Bank Sta=4885.6,5023.4
Exp/Cntr=0.3,0.1

Type RM Length L Ch R = 1,478,69,69,69
BEGIN DESCRIPTION:
Mapping XS cdab3d7c
END DESCRIPTION:
XS GIS Cut Line= 5
      2896092.11      7023843.67      2895723.15      7023798.09
      2895371.59      7023795.92      2895347.72      7023891.40
      2895369.42      7024546.79
#Sta/Elev= 30
  4495.4  460.51  4521.5  459.42  4563.0  458.41  4633.6  455.34  4683.7  454.29
  4724.2  452.50  4764.5  451.32  4774.8  450.41  4814.9  449.46  4850.9  447.94
  4946.6  446.22  4975.3  444.90  4982.3  443.98  4982.8  443.18  4987.8  443.18
  4988.3  443.98  5035.3  445.90  5075.3  445.84  5105.3  445.26  5122.2  446.22
  5175.3  447.15  5224.1  446.87  5265.3  447.16  5360.8  448.53  5430.8  448.69
  5520.9  448.27  5781.0  449.53  5811.0  450.37  5871.1  450.70  5972.9  452.45
#Mann=3,-1,0
  4495.4    0.05       0  4982.3    0.03       0  4988.3    0.05       0
Bank Sta=4946.6,5122.2
Exp/Cntr=0.3,0.1

Type RM Length L Ch R = 1,409,228,228,228
BEGIN DESCRIPTION:
Mapping XS 48dbf57f
END DESCRIPTION:
XS GIS Cut Line= 5
      2895974.91      7023739.50      2895812.13      7023732.98
      2895380.27      7023728.64      2895332.53      7023880.55
      2895356.40      7024555.51
#Sta/Elev= 30
  4632.6  454.42  4812.6  449.04  4971.8  445.87  4982.6  445.60  4989.6  444.17
  4990.1  443.37  4995.1  443.37  4995.6  444.17  5002.6  444.68  5022.6  445.11
  5062.7  445.51  5090.1  445.38  5102.7  445.88  5122.7  446.14  5227.4  445.37
  5234.0  445.54  5244.5  446.54  5255.0  446.49  5261.0  445.49  5266.2  445.42
  5270.4  445.87  5276.0  446.47  5298.6  446.90  5521.2  449.03  5611.2  448.30
  5711.3  448.73  5841.4  448.76  5891.4  450.10  5921.4  450.13  6062.0  452.38
#Mann=3,-1,0
  4632.6    0.05       0  4989.6    0.03       0  4995.6    0.05       0
Bank Sta=4971.8,5270.4
Exp/Cntr=0.3,0.1

Type RM Length L Ch R = 1,181,0,0,0
BEGIN DESCRIPTION:
UNT045 39.0
END DESCRIPTION:
XS GIS Cut Line= 5
      2895966.22      7023704.78      2895766.56      7023542.01
      2895434.53      7023444.36      2895304.32      7023867.53
      2895330.32      7024591.21
#Sta/Elev= 30
  4611.5  453.94  4619.3  454.65  4633.7  453.73  4654.5  453.73  4683.2  452.41
  4697.6  450.78  4747.1  450.10  4761.5  449.06  4876.1  444.78  4948.7  443.16
  4986.6  443.16  4992.8  440.86  4993.3  440.06  4998.3  440.06  4998.8  440.86
  5006.2  443.06  5079.2  442.38  5191.9  443.02  5218.2  442.47  5236.8  443.40
  5280.0  443.16  5432.5  443.77  5508.8  445.15  5529.8  446.38  5550.7  445.40
  5561.1  446.50  5582.1  447.20  5813.4  448.79  6075.7  447.79  6382.1  452.38
#Mann=3,-1,0
  4611.5    0.05       0  4992.8    0.03       0  4998.8    0.05       0
Bank Sta=4948.7,5280
Exp/Cntr=0.3,0.1

Chan Stop Cuts=-1