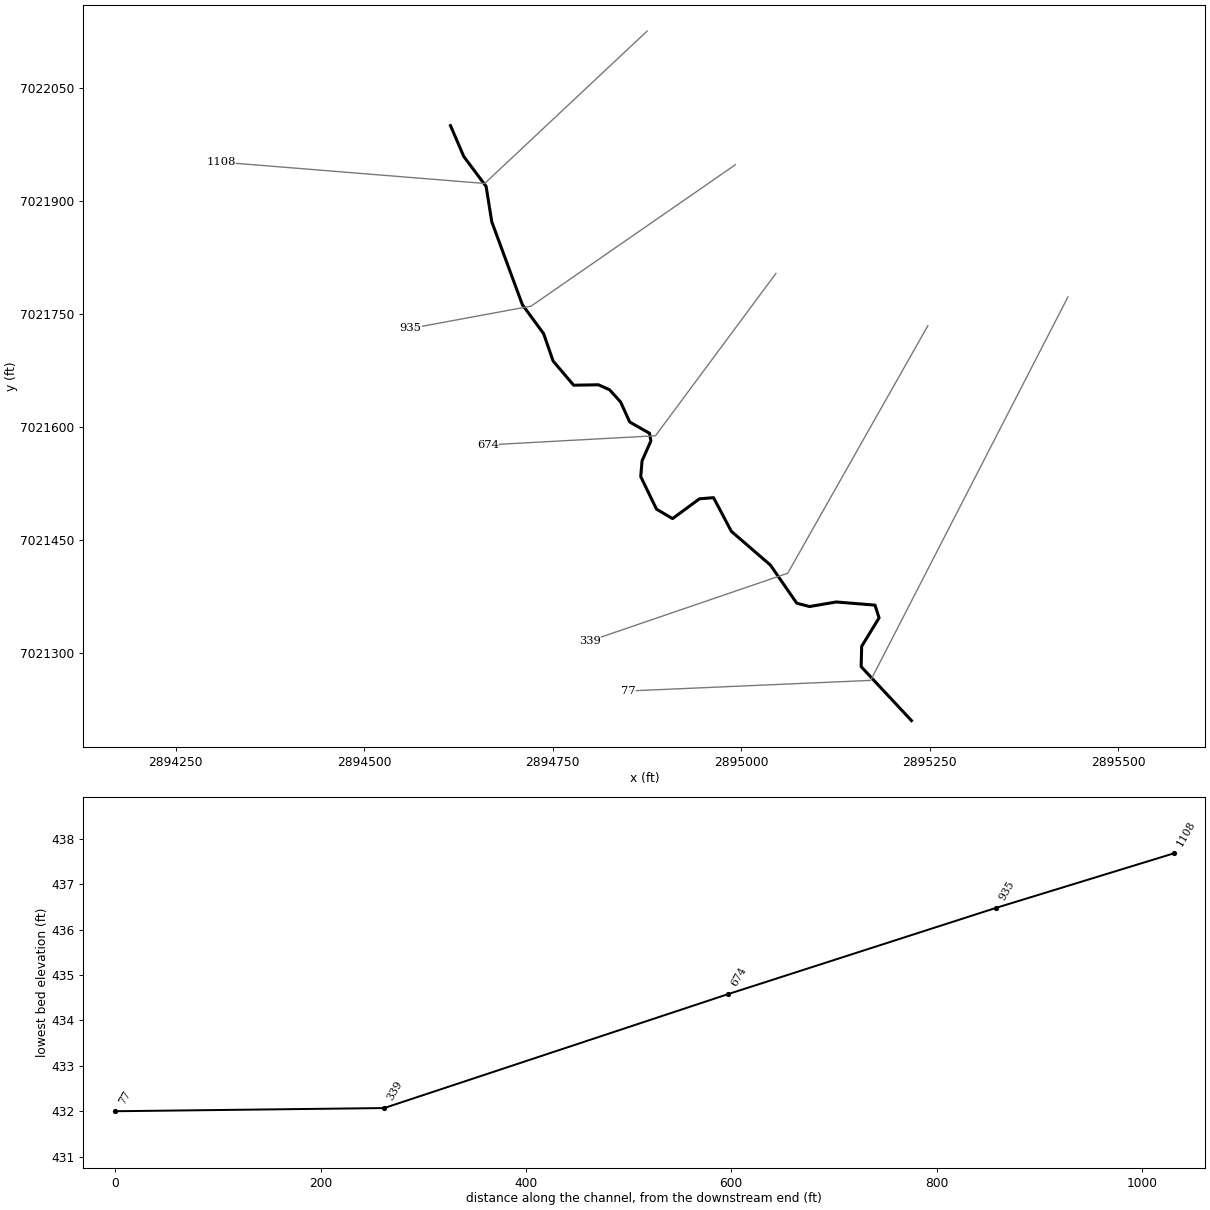
--- UNT 046 IN DRY CR WATERSHED.prj (project) ---

Proj Title=UNT 046 IN DRY CR WATERSHED Base Level Engineering
Current Plan=p01
Default Exp/Contr=0.3,0.1
English Units
Geom File=g01
Flow File=f01
Plan File=p01
BEGIN DESCRIPTION:
UNT 046 IN DRY CR WATERSHED
END DESCRIPTION:

--- UNT 046 IN DRY CR WATERSHED.p01 (plan) ---

Plan Title=Multiple Run
Short Identifier=Multiple
Geom File=g01
Flow File=f01
Subcritical Flow
K Sum by GR= 0
Std Step Tol= 0.01
Critical Tol= 0.01
Num of Std Step Trials= 20
Max Error Tol= 0.3
Flow Tol Ratio= 0.001
Split Flow NTrial= 30
Split Flow Tol= 0.02
Split Flow Ratio= 0.02
Log Output Level= 0
Friction Slope Method= 1
Unsteady Friction Slope Method= 2
Unsteady Bridges Friction Slope Method= 1
Parabolic Critical Depth
Global Vel Dist=  1 , 1 , 1
Global Log Level= 0
CheckData=True
Encroach Param= -1, 0, 0, 0
BEGIN DESCRIPTION:
Multiple Run
END DESCRIPTION:

--- UNT 046 IN DRY CR WATERSHED.f01 (steady flow) ---

Flow Title=Multiple
Program Version=5.07
Number of Profiles= 7
Profile Names=10-year,25-year,50-year,1pct_min,100-year,1pct_plu,500-year
River Rch & RM=UNT 046 IN DRY C,Reach-1         ,1108
     214     268     309     178     356     709     469
Boundary for River Rch & Prof#=UNT 046 IN DRY C,Reach-1         , 1
Up Type= 0
Dn Type= 3
Dn Slope=0.00138
Boundary for River Rch & Prof#=UNT 046 IN DRY C,Reach-1         , 2
Up Type= 0
Dn Type= 3
Dn Slope=0.00138
Boundary for River Rch & Prof#=UNT 046 IN DRY C,Reach-1         , 3
Up Type= 0
Dn Type= 3
Dn Slope=0.00138
Boundary for River Rch & Prof#=UNT 046 IN DRY C,Reach-1         , 4
Up Type= 0
Dn Type= 3
Dn Slope=0.00138
Boundary for River Rch & Prof#=UNT 046 IN DRY C,Reach-1         , 5
Up Type= 0
Dn Type= 3
Dn Slope=0.00138
Boundary for River Rch & Prof#=UNT 046 IN DRY C,Reach-1         , 6
Up Type= 0
Dn Type= 3
Dn Slope=0.00138
Boundary for River Rch & Prof#=UNT 046 IN DRY C,Reach-1         , 7
Up Type= 0
Dn Type= 3
Dn Slope=0.00138
DSS Import GetInterval= 0
DSS Import GetPeak= 0
DSS Import FillOption= 0

--- UNT 046 IN DRY CR WATERSHED.g01 (geometry) ---

Geom Title=Existing Conditions

River Reach=UNT 046 IN DRY C,Reach-1
Reach XY= 30
      2894614.33      7021999.66      2894631.95      7021958.72
      2894661.56      7021919.05      2894669.06      7021872.15
      2894709.61      7021762.26      2894737.79      7021723.83
      2894750.40      7021687.50      2894777.63      7021655.45
      2894810.46      7021656.04      2894825.28      7021649.39
      2894839.87      7021633.26      2894851.94      7021606.67
      2894878.17      7021591.77      2894880.07      7021581.56
      2894868.34      7021555.27      2894866.59      7021534.21
      2894887.52      7021491.06      2894908.77      7021478.57
      2894944.39      7021504.80      2894963.14      7021506.36
      2894986.69      7021461.73      2895038.49      7021416.98
      2895073.51      7021366.36      2895090.44      7021361.97
      2895125.81      7021368.04      2895177.26      7021363.82
      2895182.60      7021346.94      2895159.55      7021309.23
      2895158.82      7021282.29      2895225.59      7021210.71

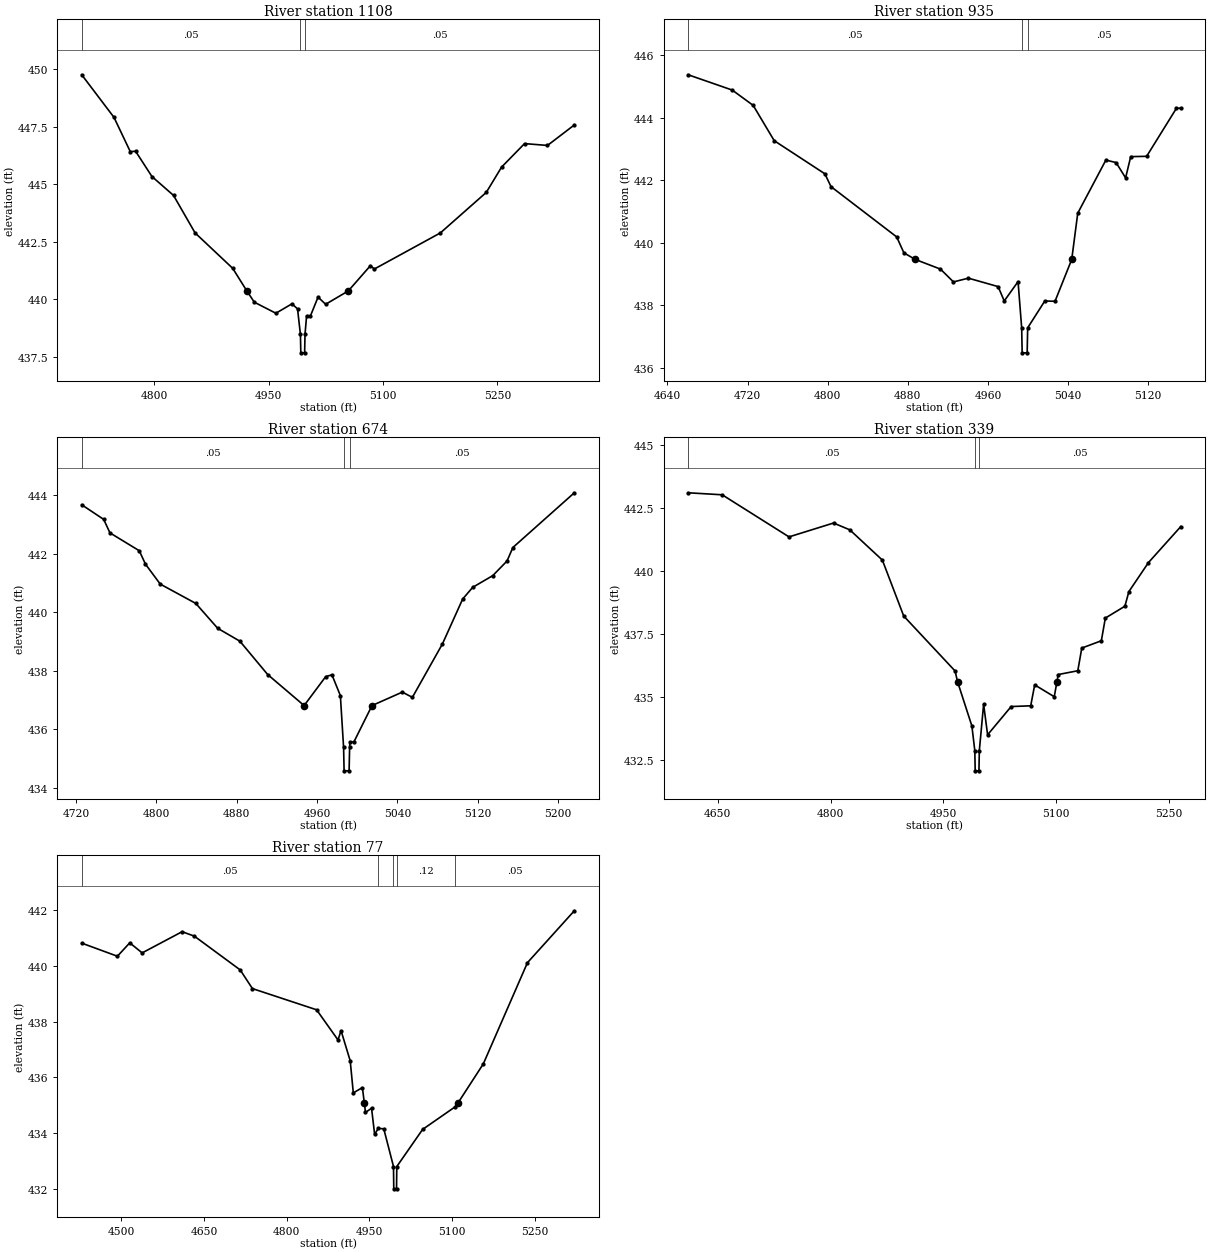
Type RM Length L Ch R = 1,1108,173,173,173
BEGIN DESCRIPTION:
UNT 046 IN DRY CR WATERSHED 2.0
END DESCRIPTION:
XS GIS Cut Line= 3
      2894875.01      7022125.01      2894659.63      7021922.97
      2894309.88      7021951.28
#Sta/Elev= 30
  4704.7  449.76  4747.0  447.91  4768.4  446.42  4775.3  446.44  4796.8  445.34
  4825.1  444.52  4853.4  442.89  4902.8  441.35  4921.3  440.37  4931.1  439.88
  4959.4  439.40  4980.5  439.81  4987.8  439.59  4991.6  438.48  4992.1  437.68
  4997.1  437.68  4997.6  438.48  4999.7  439.29  5004.8  439.29  5014.7  440.10
  5024.7  439.79  5054.4  440.37  5083.5  441.47  5088.5  441.32  5175.2  442.89
  5235.4  444.65  5255.5  445.75  5285.6  446.77  5315.7  446.69  5350.9  447.58
#Mann=3,-1,0
  4704.7    0.05       0  4991.6    0.03       0  4997.6    0.05       0
Bank Sta=4921.3,5054.4
Exp/Cntr=0.3,0.1

Type RM Length L Ch R = 1,935,261,261,261
BEGIN DESCRIPTION:
Mapping XS e4f5cb6f
END DESCRIPTION:
XS GIS Cut Line= 3
      2894992.10      7021947.84      2894721.23      7021760.32
      2894561.48      7021730.80
#Sta/Elev= 30
  4660.7  445.38  4704.7  444.89  4725.6  444.40  4746.6  443.27  4797.2  442.21
  4803.3  441.80  4868.9  440.19  4876.1  439.68  4887.4  439.47  4912.6  439.16
  4925.6  438.75  4940.5  438.87  4970.2  438.60  4976.3  438.14  4990.1  438.76
  4993.7  437.28  4994.2  436.48  4999.2  436.48  4999.7  437.28  5016.8  438.14
  5027.0  438.13  5043.7  439.47  5049.7  440.95  5077.8  442.65  5088.0  442.57
  5097.5  442.08  5102.6  442.76  5118.5  442.77  5148.3  444.31  5152.6  444.31
#Mann=3,-1,0
  4660.7    0.05       0  4993.7    0.03       0  4999.7    0.05       0
Bank Sta=4887.4,5043.7
Exp/Cntr=0.3,0.1

Type RM Length L Ch R = 1,674,335,335,335
BEGIN DESCRIPTION:
Mapping XS d3cdd713
END DESCRIPTION:
XS GIS Cut Line= 3
      2895045.87      7021803.71      2894886.16      7021588.44
      2894663.93      7021576.29
#Sta/Elev= 30
  4725.6  443.67  4747.5  443.17  4753.7  442.71  4782.9  442.10  4789.1  441.64
  4803.8  440.96  4839.2  440.30  4861.0  439.45  4883.1  439.01  4910.8  437.87
  4947.1  436.81  4968.6  437.80  4974.8  437.86  4983.2  437.15  4986.4  435.38
  4986.9  434.58  4991.9  434.58  4992.4  435.38  4992.7  435.57  4996.7  435.57
  5014.7  436.81  5044.9  437.27  5054.9  437.09  5084.9  438.92  5105.0  440.45
  5115.0  440.85  5135.0  441.25  5149.2  441.75  5155.0  442.21  5216.2  444.08
#Mann=3,-1,0
  4725.6    0.05       0  4986.4    0.03       0  4992.4    0.05       0
Bank Sta=4947.1,5014.7
Exp/Cntr=0.3,0.1

Type RM Length L Ch R = 1,339,262,262,262
BEGIN DESCRIPTION:
Mapping XS faef1533
END DESCRIPTION:
XS GIS Cut Line= 3
      2895247.29      7021734.32      2895061.50      7021406.15
      2894798.76      7021316.27
#Sta/Elev= 30
  4610.7  443.10  4655.9  443.02  4744.7  441.35  4803.9  441.90  4825.5  441.63
  4868.8  440.43  4897.2  438.21  4965.5  436.03  4968.7  435.61  4987.8  433.85
  4991.7  432.87  4992.2  432.07  4997.2  432.07  4997.7  432.87  5003.4  434.71
  5008.7  433.50  5040.0  434.62  5066.0  434.65  5071.3  435.48  5097.3  435.01
  5100.9  435.61  5102.6  435.89  5128.6  436.04  5133.9  436.94  5159.9  437.23
  5165.2  438.13  5191.2  438.60  5196.5  439.18  5222.5  440.33  5265.5  441.76
#Mann=3,-1,0
  4610.7    0.05       0  4991.7    0.03       0  4997.7    0.05       0
Bank Sta=4968.7,5100.9
Exp/Cntr=0.3,0.1

Type RM Length L Ch R = 1,77,0,0,0
BEGIN DESCRIPTION:
UNT 046 IN DRY CR WATERSHED 1.0
END DESCRIPTION:
XS GIS Cut Line= 3
      2895433.04      7021772.49      2895171.44      7021264.04
      2894850.05      7021250.00
#Sta/Elev= 30
  4428.2  440.81  4492.9  440.34  4515.3  440.82  4537.8  440.46  4610.3  441.22
  4632.5  441.06  4715.6  439.85  4737.8  439.18  4854.2  438.42  4893.0  437.34
  4898.6  437.67  4915.2  436.59  4920.8  435.44  4937.3  435.63  4940.8  435.08
  4942.9  434.74  4953.9  434.89  4959.5  433.95  4966.1  434.17  4976.1  434.15
  4993.7  432.80  4994.2  432.00  4999.2  432.00  4999.7  432.80  5046.5  434.13
  5105.5  434.94  5110.7  435.08  5156.6  436.48  5236.7  440.11  5321.7  441.97
#Mann=5,-1,0
  4428.2    0.05       0  4966.1    0.12       0  4993.7    0.07       0
  4999.7    0.12       0  5105.5    0.05       0
Bank Sta=4940.8,5110.7
Exp/Cntr=0.3,0.1

Chan Stop Cuts=-1