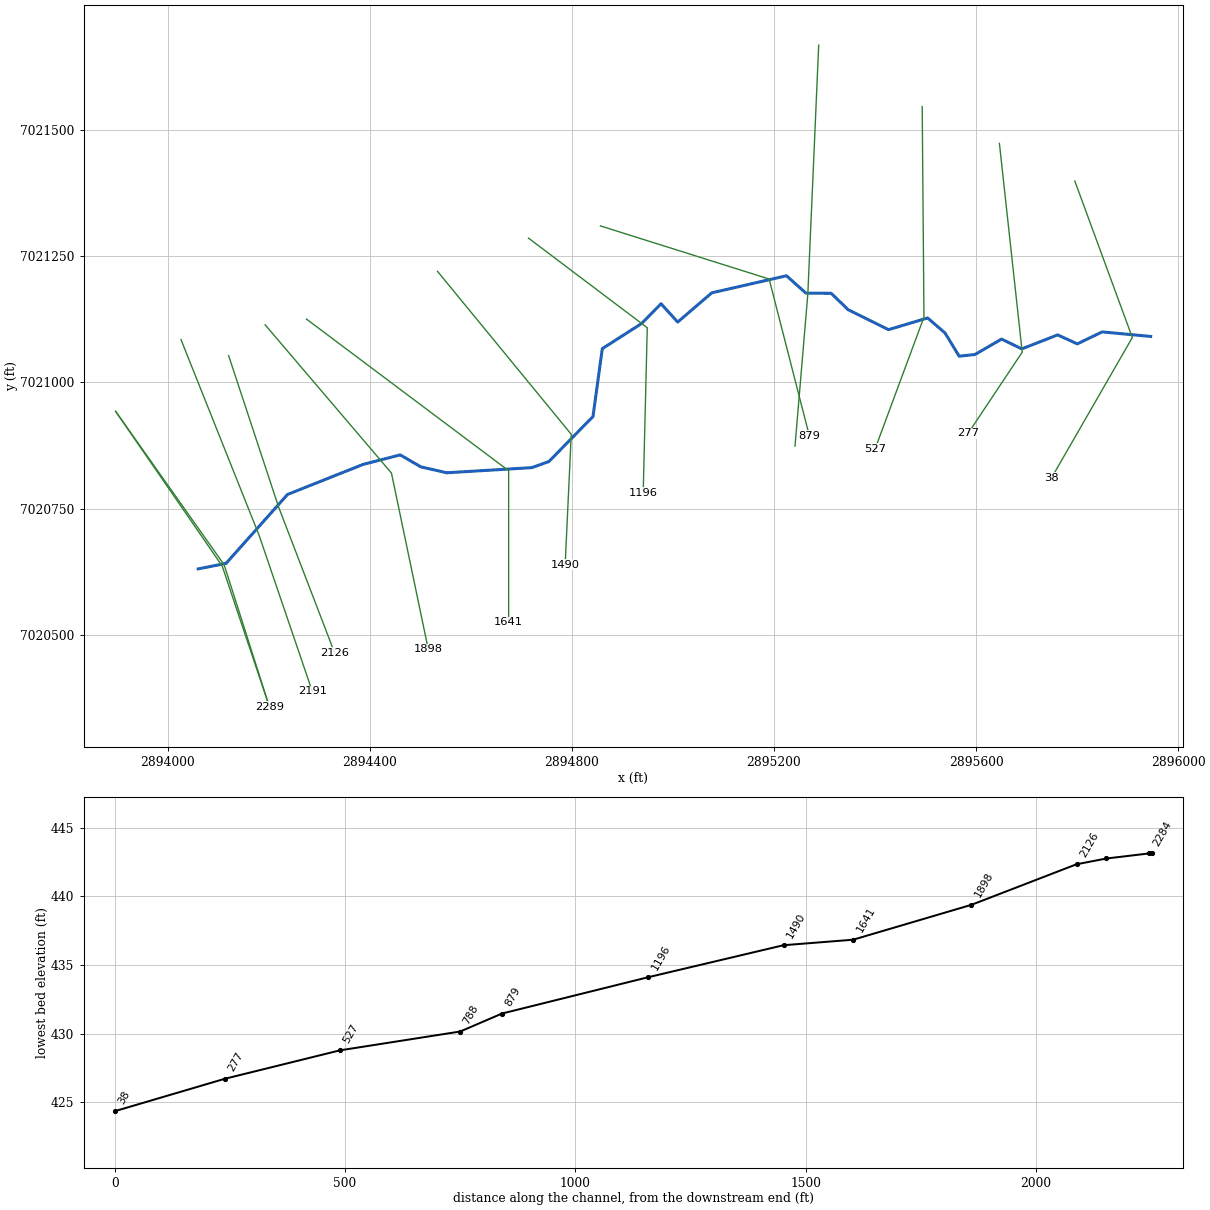
--- UNT 047 IN DRY CR WATERSHED.prj (project) ---

Proj Title=UNT 047 IN DRY CR WATERSHED Base Level Engineering
Current Plan=p01
Default Exp/Contr=0.3,0.1
English Units
Geom File=g01
Flow File=f01
Plan File=p01
BEGIN DESCRIPTION:
UNT 047 IN DRY CR WATERSHED
END DESCRIPTION:

--- UNT 047 IN DRY CR WATERSHED.p01 (plan) ---

Plan Title=Multiple Run
Short Identifier=Multiple
Geom File=g01
Flow File=f01
Subcritical Flow
K Sum by GR= 0
Std Step Tol= 0.01
Critical Tol= 0.01
Num of Std Step Trials= 20
Max Error Tol= 0.3
Flow Tol Ratio= 0.001
Split Flow NTrial= 30
Split Flow Tol= 0.02
Split Flow Ratio= 0.02
Log Output Level= 0
Friction Slope Method= 1
Unsteady Friction Slope Method= 2
Unsteady Bridges Friction Slope Method= 1
Parabolic Critical Depth
Global Vel Dist=  1 , 1 , 1
Global Log Level= 0
CheckData=True
Encroach Param= -1, 0, 0, 0
BEGIN DESCRIPTION:
Multiple Run
END DESCRIPTION:

--- UNT 047 IN DRY CR WATERSHED.f01 (steady flow) ---

Flow Title=Multiple
Number of Profiles=7
Profile Names=10-year,25-year,50-year,1pct_min,100-year,1pct_plu,500-year
River Rch & RM= UNT 047 IN DRY C,Reach-1,2289
     159     196     223     127     254     507     327
River Rch & RM= UNT 047 IN DRY C,Reach-1,788
     322     415     488     286     571    1139     780
Boundary for River Rch & Prof#=UNT 047 IN DRY C,Reach-1,1
Up Type=0
Dn Type=3
Dn Slope=0.005
Boundary for River Rch & Prof#=UNT 047 IN DRY C,Reach-1,2
Up Type=0
Dn Type=3
Dn Slope=0.005
Boundary for River Rch & Prof#=UNT 047 IN DRY C,Reach-1,3
Up Type=0
Dn Type=3
Dn Slope=0.005
Boundary for River Rch & Prof#=UNT 047 IN DRY C,Reach-1,4
Up Type=0
Dn Type=3
Dn Slope=0.005
Boundary for River Rch & Prof#=UNT 047 IN DRY C,Reach-1,5
Up Type=0
Dn Type=3
Dn Slope=0.005
Boundary for River Rch & Prof#=UNT 047 IN DRY C,Reach-1,6
Up Type=0
Dn Type=3
Dn Slope=0.005
Boundary for River Rch & Prof#=UNT 047 IN DRY C,Reach-1,7
Up Type=0
Dn Type=3
Dn Slope=0.005

--- UNT 047 IN DRY CR WATERSHED.g01 (geometry) ---

Geom Title=Existing Conditions

River Reach=UNT 047 IN DRY C,Reach-1
Reach XY= 30
      2894060.59      7020630.71      2894115.70      7020641.52
      2894237.32      7020777.91      2894387.02      7020837.48
      2894460.43      7020856.28      2894501.25      7020832.57
      2894552.67      7020820.90      2894721.00      7020831.06
      2894754.54      7020843.07      2894841.92      7020932.16
      2894860.35      7021066.54      2894938.05      7021116.23
      2894976.62      7021155.39      2895009.53      7021119.17
      2895077.02      7021177.01      2895224.84      7021210.82
      2895263.25      7021176.48      2895313.38      7021176.07
      2895346.86      7021143.71      2895426.77      7021104.13
      2895504.21      7021127.27      2895538.73      7021097.51
      2895566.60      7021051.57      2895597.95      7021055.01
      2895650.61      7021085.46      2895690.53      7021066.06
      2895761.53      7021093.77      2895800.52      7021075.98
      2895849.63      7021099.72      2895945.59      7021090.71

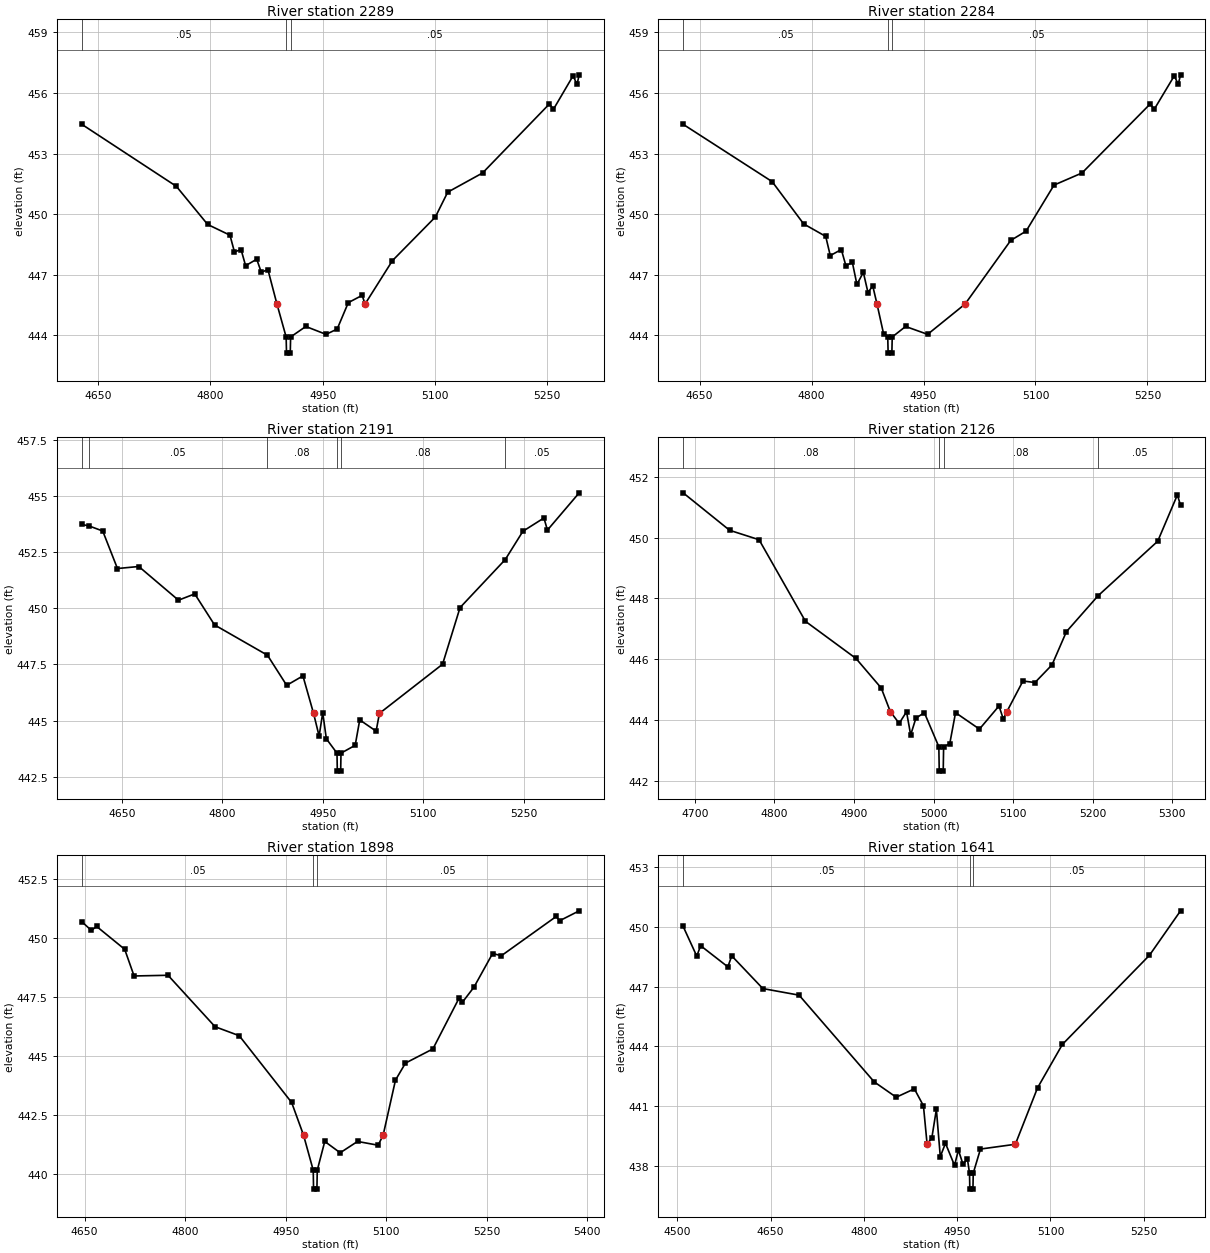
Type RM Length L Ch R = 1,2289,5,5,5
BEGIN DESCRIPTION:
UNT 047 IN DRY CR WATERSHED 6.0
END DESCRIPTION:
XS GIS Cut Line= 3
      2893897.18      7020942.44      2894108.22      7020636.10
      2894201.29      7020358.27
#Sta/Elev= 30
  4628.0  454.45  4754.4  451.38  4796.3  449.49  4826.1  448.96  4832.1  448.13
  4840.9  448.25  4847.0  447.45  4861.9  447.77  4868.0  447.12  4876.8  447.26
  4888.9  445.55  4901.2  443.92  4901.7  443.12  4906.7  443.12  4907.2  443.92
  4927.5  444.44  4954.5  444.05  4969.4  444.31  4984.3  445.62  5002.8  445.98
  5006.7  445.55  5043.3  447.70  5100.7  449.86  5117.2  451.09  5163.8  452.04
  5253.2  455.46  5258.5  455.19  5284.8  456.85  5290.1  456.43  5293.0  456.90
#Mann=3,-1,0
  4628.0    0.05       0  4901.2    0.03       0  4907.2    0.05       0
Bank Sta=4888.9,5006.7
Exp/Cntr=0.3,0.1

Type RM Length L Ch R = 1,2284,93,93,93
BEGIN DESCRIPTION:
Mapping XS 10fba5de
END DESCRIPTION:
XS GIS Cut Line= 3
      2893897.23      7020942.37      2894112.03      7020638.65
      2894201.33      7020358.23
#Sta/Elev= 30
  4628.0  454.45  4747.3  451.61  4789.4  449.52  4819.0  448.90  4825.1  447.95
  4839.9  448.25  4846.0  447.45  4854.7  447.61  4860.8  446.52  4869.4  447.12
  4875.6  446.12  4882.0  446.45  4887.7  445.55  4896.5  444.08  4902.1  443.92
  4902.6  443.12  4907.6  443.12  4908.1  443.92  4926.0  444.44  4955.5  444.05
  5005.7  445.55  5066.8  448.70  5087.4  449.16  5124.8  451.44  5162.3  452.04
  5253.7  455.46  5259.0  455.19  5285.9  456.85  5291.2  456.43  5294.3  456.90
#Mann=3,-1,0
  4628.0    0.05       0  4902.1    0.03       0  4908.1    0.05       0
Bank Sta=4887.7,5005.7
Exp/Cntr=0.3,0.1

Type RM Length L Ch R = 1,2191,65,65,65
BEGIN DESCRIPTION:
Mapping XS f0cfbac3
END DESCRIPTION:
XS GIS Cut Line= 3
      2894026.54      7021084.50      2894181.07      7020697.31
      2894286.39      7020388.25
#Sta/Elev= 30
  4589.8  453.73  4600.3  453.67  4621.1  453.44  4643.1  451.77  4675.0  451.86
  4734.3  450.36  4758.6  450.64  4788.2  449.26  4867.3  447.91  4896.0  446.57
  4920.3  446.99  4936.2  445.32  4944.5  444.31  4949.9  445.35  4955.3  444.19
  4971.2  443.55  4971.7  442.75  4976.7  442.75  4977.2  443.55  4998.4  443.90
  5005.2  445.03  5029.7  444.53  5034.6  445.32  5129.0  447.51  5155.1  450.03
  5222.7  452.17  5249.1  453.43  5280.5  454.02  5285.7  453.48  5333.2  455.14
#Mann=6,-1,0
  4589.8    0.08       0  4600.3    0.05       0  4867.3    0.08       0
  4971.2    0.07       0  4977.2    0.08       0  5222.7    0.05       0
Bank Sta=4936.2,5034.6
Exp/Cntr=0.3,0.1

Type RM Length L Ch R = 1,2126,228,228,228
BEGIN DESCRIPTION:
UNT 047 IN DRY CR WATERSHED 5.0
END DESCRIPTION:
XS GIS Cut Line= 3
      2894120.83      7021052.80      2894219.39      7020754.04
      2894330.66      7020464.27
#Sta/Elev= 30
  4685.4  451.47  4743.8  450.24  4780.8  449.93  4839.1  447.25  4902.6  446.03
  4934.3  445.06  4945.8  444.28  4956.9  443.90  4966.1  444.28  4971.3  443.52
  4977.9  444.07  4988.5  444.25  5006.7  443.13  5007.2  442.33  5012.2  442.33
  5012.7  443.13  5020.4  443.23  5027.7  444.25  5057.7  443.71  5082.3  444.47
  5087.7  444.04  5092.1  444.28  5112.4  445.29  5127.5  445.24  5148.9  445.82
  5167.0  446.91  5206.8  448.09  5281.7  449.88  5306.4  451.40  5310.4  451.06
#Mann=4,-1,0
  4685.4    0.08       0  5006.7    0.07       0  5012.7    0.08       0
  5206.8    0.05       0
Bank Sta=4945.8,5092.1
Exp/Cntr=0.3,0.1

Type RM Length L Ch R = 1,1898,257,257,257
BEGIN DESCRIPTION:
Mapping XS 074e8340
END DESCRIPTION:
XS GIS Cut Line= 3
      2894193.09      7021113.72      2894443.08      7020820.33
      2894515.98      7020471.42
#Sta/Elev= 30
  4645.9  450.71  4660.2  450.34  4668.0  450.51  4709.9  449.54  4723.9  448.41
  4774.5  448.44  4844.7  446.26  4880.7  445.88  4958.9  443.05  4976.6  441.67
  4991.1  440.18  4991.6  439.38  4996.6  439.38  4997.1  440.18  5008.3  441.40
  5031.3  440.92  5057.2  441.40  5087.9  441.24  5095.4  441.67  5113.8  444.00
  5128.7  444.72  5169.6  445.32  5208.6  447.47  5213.7  447.30  5230.9  447.94
  5258.6  449.36  5271.8  449.27  5353.5  450.93  5358.6  450.75  5387.8  451.17
#Mann=3,-1,0
  4645.9    0.05       0  4991.1    0.03       0  4997.1    0.05       0
Bank Sta=4976.6,5095.4
Exp/Cntr=0.3,0.1

Type RM Length L Ch R = 1,1641,151,151,151
BEGIN DESCRIPTION:
UNT 047 IN DRY CR WATERSHED 4.0
END DESCRIPTION:
XS GIS Cut Line= 3
      2894274.97      7021125.02      2894675.00      7020825.00
      2894675.00      7020525.04
#Sta/Elev= 30
  4509.2  450.02  4531.1  448.53  4537.4  449.05  4581.1  447.99  4587.4  448.54
  4637.4  446.90  4695.7  446.57  4816.5  442.22  4851.9  441.45  4881.1  441.87
  4895.7  441.02  4901.6  439.09  4909.2  439.41  4916.5  440.84  4922.8  438.47
  4931.1  439.14  4945.7  438.03  4951.9  438.80  4959.2  438.10  4966.5  438.34
  4969.8  437.64  4970.3  436.84  4975.3  436.84  4975.8  437.64  4987.4  438.85
  5043.5  439.09  5079.2  441.92  5119.2  444.10  5259.2  448.57  5309.2  450.80
#Mann=3,-1,0
  4509.2    0.05       0  4969.8    0.03       0  4975.8    0.05       0
Bank Sta=4901.6,5043.5
Exp/Cntr=0.3,0.1

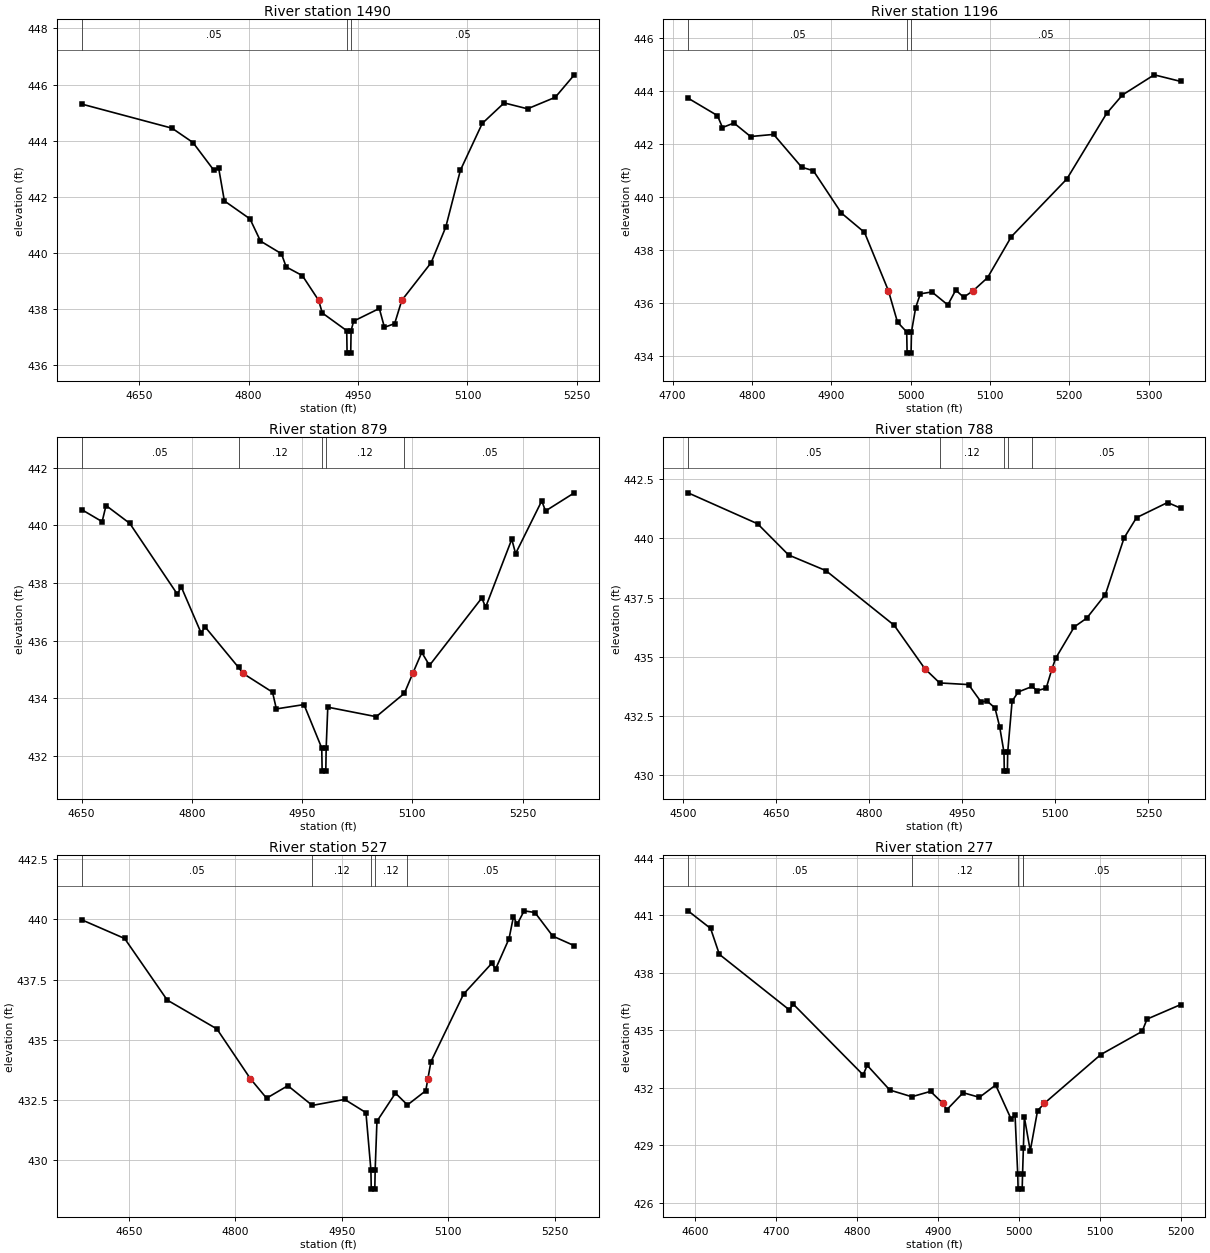
Type RM Length L Ch R = 1,1490,294,294,294
BEGIN DESCRIPTION:
Mapping XS eb0fde52
END DESCRIPTION:
XS GIS Cut Line= 3
      2894534.27      7021219.47      2894798.91      7020897.07
      2894786.87      7020638.95
#Sta/Elev= 30
  4571.0  445.31  4695.0  444.45  4723.7  443.94  4752.4  442.95  4758.9  443.04
  4766.8  441.86  4801.9  441.22  4816.3  440.43  4845.0  439.98  4851.5  439.51
  4873.7  439.20  4896.0  438.32  4901.0  437.87  4934.5  437.24  4935.0  436.44
  4940.0  436.44  4940.5  437.24  4944.0  437.58  4979.2  438.03  4986.2  437.36
  5000.2  437.49  5010.0  438.32  5050.2  439.66  5070.3  440.93  5090.3  442.95
  5120.3  444.62  5150.3  445.35  5182.4  445.14  5220.4  445.55  5246.5  446.35
#Mann=3,-1,0
  4571.0    0.05       0  4934.5    0.03       0  4940.5    0.05       0
Bank Sta=4896,5010
Exp/Cntr=0.3,0.1

Type RM Length L Ch R = 1,1196,317,317,317
BEGIN DESCRIPTION:
Mapping XS 0f2ca6b2
END DESCRIPTION:
XS GIS Cut Line= 3
      2894714.27      7021285.29      2894949.36      7021107.97
      2894941.30      7020781.53
#Sta/Elev= 30
  4719.5  443.74  4756.6  443.08  4762.9  442.63  4777.4  442.80  4798.3  442.29
  4827.4  442.37  4862.8  441.13  4877.4  441.00  4912.8  439.40  4941.9  438.67
  4972.0  436.47  4983.5  435.28  4995.1  434.91  4995.6  434.11  5000.6  434.11
  5001.1  434.91  5006.4  435.83  5012.3  436.35  5026.9  436.42  5046.9  435.93
  5056.9  436.49  5066.9  436.22  5079.0  436.47  5097.0  436.96  5127.0  438.51
  5197.0  440.69  5247.0  443.16  5267.0  443.86  5307.0  444.62  5340.5  444.37
#Mann=3,-1,0
  4719.5    0.05       0  4995.1    0.03       0  5001.1    0.05       0
Bank Sta=4972,5079
Exp/Cntr=0.3,0.1

Type RM Length L Ch R = 1,879,91,91,91
BEGIN DESCRIPTION:
UNT 047 IN DRY CR WATERSHED 3.0
END DESCRIPTION:
XS GIS Cut Line= 3
      2894856.63      7021309.47      2895190.57      7021204.32
      2895270.19      7020893.87
#Sta/Elev= 30
  4649.9  440.55  4677.9  440.13  4683.2  440.69  4715.5  440.07  4780.3  437.61
  4785.5  437.87  4812.7  436.26  4817.9  436.48  4863.5  435.07  4869.8  434.86
  4909.8  434.21  4915.0  433.63  4952.6  433.78  4976.8  432.27  4977.3  431.47
  4982.3  431.47  4982.8  432.27  4985.0  433.69  5050.9  433.36  5089.2  434.17
  5100.6  434.86  5112.9  435.59  5123.4  435.14  5194.6  437.48  5199.8  437.16
  5235.4  439.52  5240.6  439.02  5276.2  440.85  5281.3  440.50  5320.5  441.13
#Mann=5,-1,0
  4649.9    0.05       0  4863.5    0.12       0  4976.8    0.07       0
  4982.8    0.12       0  5089.2    0.05       0
Bank Sta=4869.8,5100.6
Exp/Cntr=0.3,0.1

Type RM Length L Ch R = 1,788,261,261,261
BEGIN DESCRIPTION:
UNT 047 IN DRY CR WATERSHED 2.0
END DESCRIPTION:
XS GIS Cut Line= 3
      2895288.64      7021667.19      2895267.14      7021174.95
      2895241.76      7020873.82
#Sta/Elev= 30
  4507.3  441.93  4619.6  440.62  4669.6  439.30  4729.7  438.64  4839.8  436.33
  4889.4  434.49  4913.2  433.89  4959.9  433.82  4979.9  433.09  4989.9  433.12
  5002.5  432.83  5010.0  432.04  5017.0  430.96  5017.5  430.16  5022.5  430.16
  5023.0  430.96  5030.1  433.12  5040.1  433.51  5062.5  433.74  5070.2  433.56
  5085.1  433.67  5094.5  434.49  5100.3  434.93  5130.4  436.26  5150.5  436.63
  5180.6  437.63  5210.7  440.02  5230.8  440.88  5280.9  441.52  5302.2  441.28
#Mann=5,-1,0
  4507.3    0.05       0  4913.2    0.12       0  5017.0    0.07       0
  5023.0    0.12       0  5062.5    0.05       0
Bank Sta=4889.4,5094.5
Exp/Cntr=0.3,0.1

Type RM Length L Ch R = 1,527,250,250,250
BEGIN DESCRIPTION:
Mapping XS 5b4717dc
END DESCRIPTION:
XS GIS Cut Line= 3
      2895493.50      7021545.69      2895496.97      7021128.99
      2895400.45      7020868.72
#Sta/Elev= 30
  4583.3  439.99  4644.0  439.21  4704.0  436.65  4774.0  435.45  4821.2  433.38
  4844.0  432.57  4874.0  433.09  4908.4  432.27  4954.0  432.52  4984.0  431.97
  4991.0  429.59  4991.5  428.79  4996.5  428.79  4997.0  429.59  4999.5  431.61
  5025.6  432.78  5042.5  432.29  5068.3  432.88  5071.3  433.38  5075.6  434.09
  5121.6  436.90  5161.4  438.18  5166.7  437.94  5185.6  439.20  5191.8  440.11
  5197.1  439.80  5206.9  440.36  5222.1  440.29  5247.2  439.31  5277.6  438.91
#Mann=5,-1,0
  4583.3    0.05       0  4908.4    0.12       0  4991.0    0.07       0
  4997.0    0.12       0  5042.5    0.05       0
Bank Sta=4821.2,5071.3
Exp/Cntr=0.3,0.1

Type RM Length L Ch R = 1,277,239,239,239
BEGIN DESCRIPTION:
Mapping XS fe447c3d
END DESCRIPTION:
XS GIS Cut Line= 3
      2895646.27      7021472.76      2895691.41      7021059.54
      2895584.40      7020899.02
#Sta/Elev= 30
  4590.9  441.24  4618.8  440.32  4629.6  438.97  4715.8  436.08  4720.9  436.37
  4807.2  432.68  4812.2  433.18  4840.1  431.89  4867.3  431.54  4890.4  431.82
  4905.6  431.20  4910.5  430.86  4930.7  431.75  4950.8  431.51  4970.9  432.15
  4989.8  430.39  4994.8  430.58  4998.1  427.52  4998.6  426.72  5003.6  426.72
  5004.1  427.52  5005.1  428.86  5006.3  430.47  5013.6  428.72  5022.6  430.81
  5031.1  431.20  5100.7  433.74  5151.8  434.95  5157.8  435.59  5199.5  436.35
#Mann=5,-1,0
  4590.9    0.05       0  4867.3    0.12       0  4998.1    0.07       0
  5004.1    0.12       0  5005.1    0.05       0
Bank Sta=4905.6,5031.1
Exp/Cntr=0.3,0.1

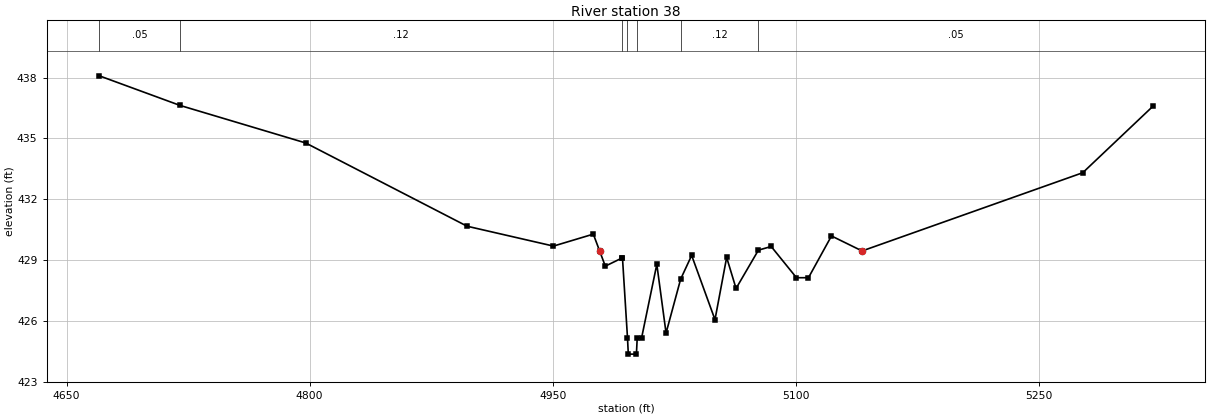
Type RM Length L Ch R = 1,38,0,0,0
BEGIN DESCRIPTION:
UNT 047 IN DRY CR WATERSHED 1.0
END DESCRIPTION:
XS GIS Cut Line= 3
      2895795.57      7021398.10      2895909.32      7021088.54
      2895749.46      7020810.86
#Sta/Elev= 30
  4670.2  438.09  4720.0  436.63  4797.5  434.78  4897.2  430.67  4950.5  429.69
  4975.1  430.28  4979.0  429.45  4982.5  428.70  4992.5  429.09  4993.1  429.11
  4996.2  425.16  4996.7  424.36  5001.7  424.36  5002.2  425.16  5004.9  425.16
  5014.3  428.79  5020.0  425.40  5029.0  428.06  5035.8  429.23  5050.2  426.06
  5057.4  429.13  5063.2  427.60  5077.0  429.49  5084.9  429.67  5100.5  428.13
  5107.9  428.13  5122.1  430.19  5141.0  429.45  5277.2  433.31  5320.4  436.58
#Mann=7,-1,0
  4670.2    0.05       0  4720.0    0.12       0  4992.5    0.16       0
  4996.2    0.07       0  5002.2    0.16       0  5029.0    0.12       0
  5077.0    0.05       0
Bank Sta=4979,5141
Exp/Cntr=0.3,0.1

Chan Stop Cuts=-1