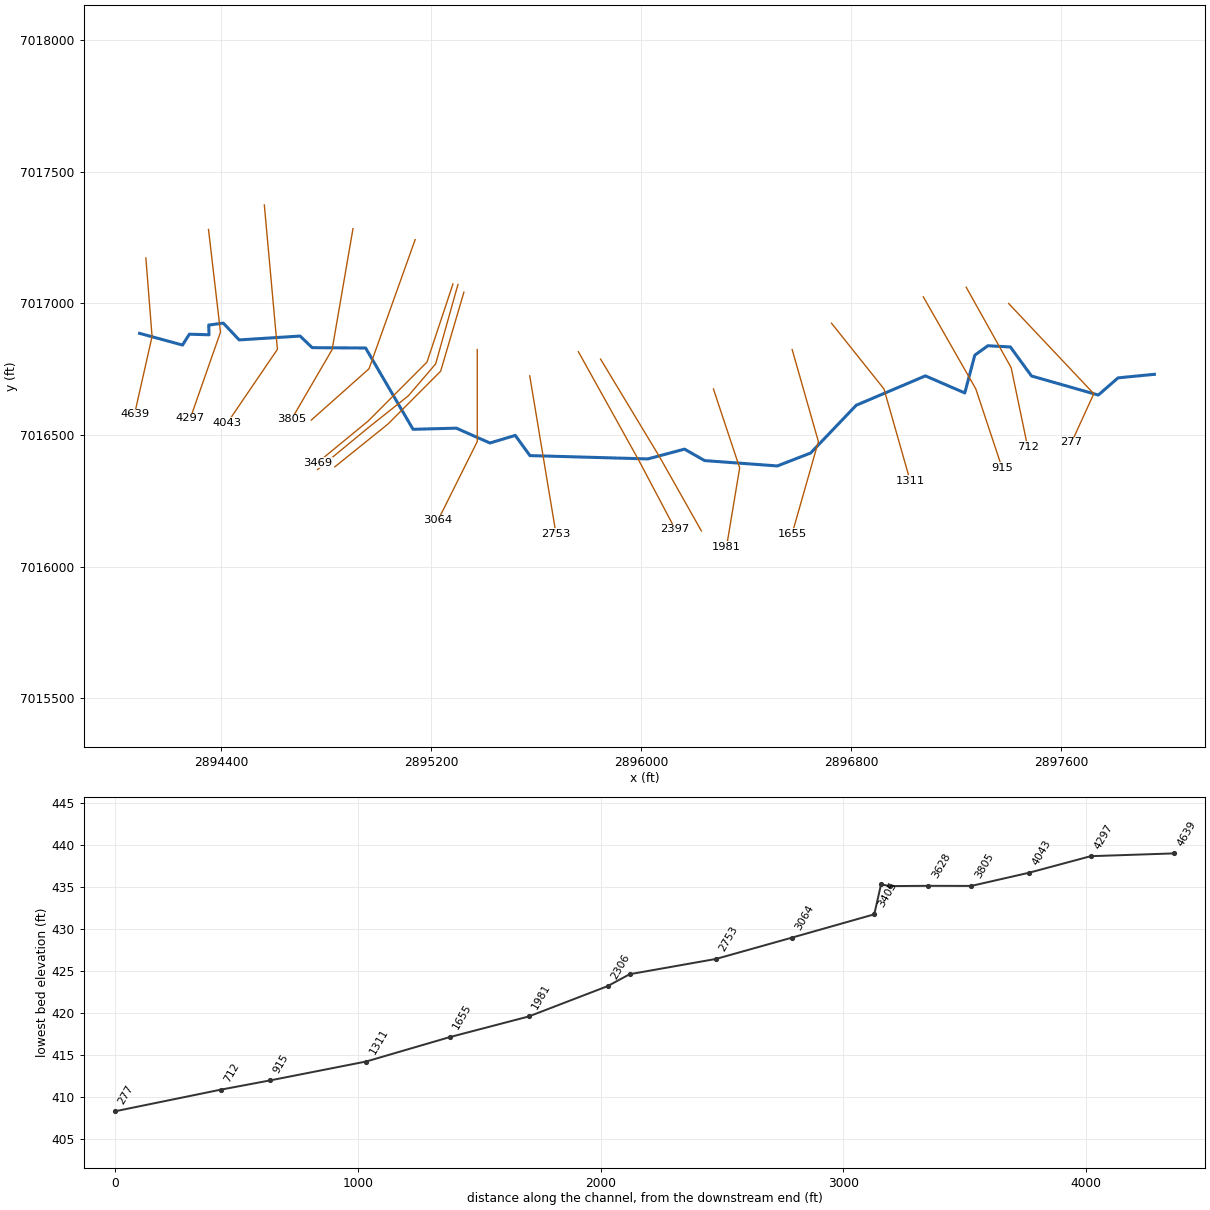
--- UNT 048 IN DRY CR WATERSHED.prj (project) ---

Proj Title=UNT 048 IN DRY CR WATERSHED Base Level Engineering
Current Plan=p01
Default Exp/Contr=0.3,0.1
English Units
Geom File=g01
Flow File=f01
Plan File=p01
Y Axis Title=Elevation
X Axis Title(PF)=Main Channel Distance
X Axis Title(XS)=Station
BEGIN DESCRIPTION:
UNT 048 IN DRY CR WATERSHED
END DESCRIPTION:
DSS Export Rating Curves= 0
DSS Export Rating Curve Sorted= 0
DSS Export Volume Flow Curves= 0
DXF OffsetX= 0
DXF OffsetY= 0
DXF ScaleX= 1
DXF ScaleY= 10

--- UNT 048 IN DRY CR WATERSHED.p01 (plan) ---

Plan Title=Multiple Run
Short Identifier=Multiple
Geom File=g01
Flow File=f01
Subcritical Flow
K Sum by GR= 0
Std Step Tol= 0.01
Critical Tol= 0.01
Num of Std Step Trials= 20
Max Error Tol= 0.3
Flow Tol Ratio= 0.001
Split Flow NTrial= 30
Split Flow Tol= 0.02
Split Flow Ratio= 0.02
Log Output Level= 0
Friction Slope Method= 1
Unsteady Friction Slope Method= 2
Unsteady Bridges Friction Slope Method= 1
Parabolic Critical Depth
Global Vel Dist=  1 , 1 , 1
Global Log Level= 0
CheckData=True
Encroach Param= -1, 0, 0, 0
BEGIN DESCRIPTION:
Multiple Run
END DESCRIPTION:

--- UNT 048 IN DRY CR WATERSHED.f01 (steady flow) ---

Flow Title=Multiple
Number of Profiles=7
Profile Names=10-year,25-year,50-year,1pct_min,100-year,1pct_plu,500-year
River Rch & RM= UNT 048 IN DRY C,Reach-1,4639
     291     373     436     254     508    1013     688
Boundary for River Rch & Prof#=UNT 048 IN DRY C,Reach-1,1
Up Type=0
Dn Type=3
Dn Slope=0.005
Boundary for River Rch & Prof#=UNT 048 IN DRY C,Reach-1,2
Up Type=0
Dn Type=3
Dn Slope=0.005
Boundary for River Rch & Prof#=UNT 048 IN DRY C,Reach-1,3
Up Type=0
Dn Type=3
Dn Slope=0.005
Boundary for River Rch & Prof#=UNT 048 IN DRY C,Reach-1,4
Up Type=0
Dn Type=3
Dn Slope=0.005
Boundary for River Rch & Prof#=UNT 048 IN DRY C,Reach-1,5
Up Type=0
Dn Type=3
Dn Slope=0.005
Boundary for River Rch & Prof#=UNT 048 IN DRY C,Reach-1,6
Up Type=0
Dn Type=3
Dn Slope=0.005
Boundary for River Rch & Prof#=UNT 048 IN DRY C,Reach-1,7
Up Type=0
Dn Type=3
Dn Slope=0.005

--- UNT 048 IN DRY CR WATERSHED.g01 (geometry) ---

Geom Title=Existing Conditions
Program Version=5.07

River Reach=UNT 048 IN DRY C,Reach-1
Reach XY= 30
      2894088.21      7016886.44      2894251.84      7016841.96
      2894277.88      7016883.19      2894352.75      7016881.02
      2894351.67      7016917.91      2894407.01      7016925.51
      2894467.77      7016861.49      2894699.92      7016876.19
      2894745.93      7016832.04      2894949.59      7016830.69
      2895130.29      7016521.65      2895295.22      7016525.99
      2895423.26      7016469.56      2895519.82      7016498.45
      2895575.73      7016421.68      2896024.87      7016409.09
      2896164.94      7016446.24      2896241.36      7016402.69
      2896518.65      7016382.37      2896645.37      7016431.41
      2896819.26      7016613.13      2897082.89      7016724.76
      2897232.96       7016659.9      2897271.04      7016803.46
      2897320.91      7016839.29      2897406.57      7016834.73
      2897487.02      7016724.46       2897741.8      7016651.95
      2897816.96      7016717.28      2897955.59      7016730.71

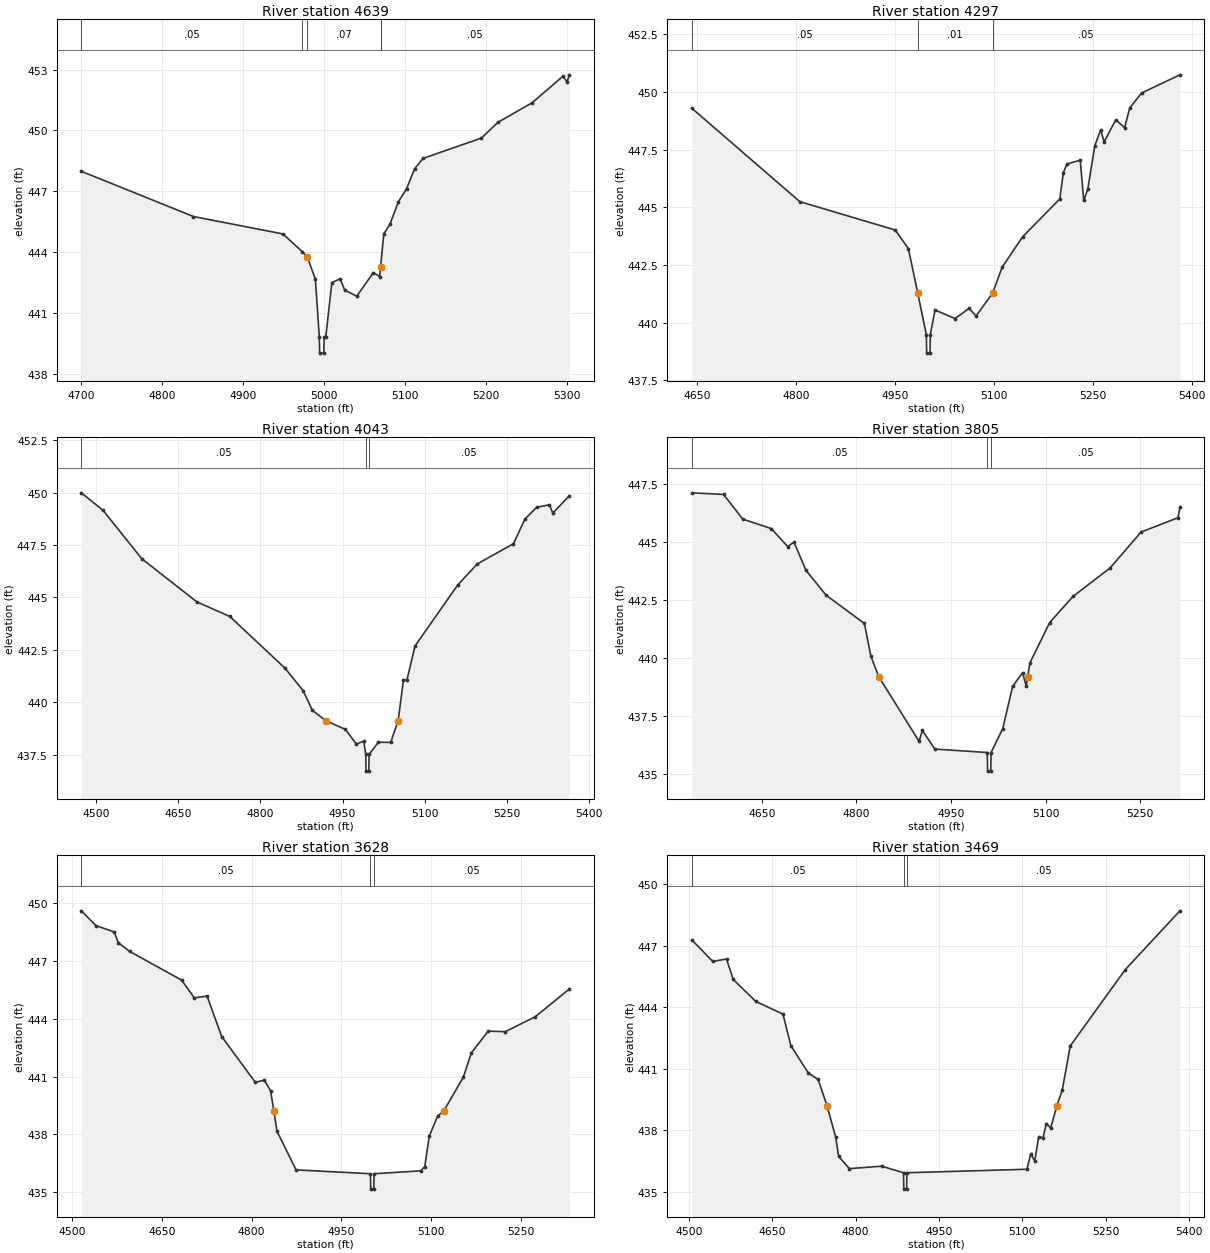
Type RM Length L Ch R = 1 ,4639    ,342,342,342
BEGIN DESCRIPTION:
UNT 048 IN DRY CR WATERSHED 10.0
END DESCRIPTION:
XS GIS Cut Line= 3
      2894112.14      7017172.89      2894135.74      7016874.53
      2894068.94      7016579.19
#Sta/Elev= 30
  4700.7  447.98    4839  445.75  4949.4  444.89  4973.2  444.02  4979.5  443.76
  4989.5  442.65  4994.3  439.81  4994.8  439.01  4999.8  439.01  5000.3  439.81
  5002.3  439.81  5009.8  442.49    5020  442.68  5025.6  442.12  5040.5  441.82
    5061  442.98  5068.8  442.79  5069.9  443.25  5073.9   444.9  5081.5  445.37
  5091.8  446.47    5102  447.12  5111.9  448.11  5122.5  448.62  5194.3  449.62
  5214.8   450.4  5256.8  451.36  5294.9  452.67    5300  452.39  5302.8  452.74
#Mann= 5 ,-1 , 0
  4700.7     .05       0  4973.2     .16       0  4979.5     .07       0
  5069.9     .16       0  5069.9     .05       0
Bank Sta=4979.5,5069.9
XS Rating Curve= 0 ,0
Exp/Cntr=0.3,0.1

Type RM Length L Ch R = 1 ,4297    ,254,254,254
BEGIN DESCRIPTION:
Mapping XS 23cdbbe1
END DESCRIPTION:
XS GIS Cut Line= 3
      2894350.86      7017281.39      2894396.43      7016890.78
      2894281.43      7016563.14
#Sta/Elev= 30
  4641.7   449.3  4805.5  445.25  4950.2  444.02  4970.3  443.21  4984.4  441.29
  4997.5  439.48    4998  438.68    5003  438.68  5003.5  439.48  5010.6  440.55
  5041.1  440.18  5062.3  440.62  5072.9  440.29  5098.2  441.29  5112.4   442.4
  5143.4  443.72    5200  445.37  5205.3   446.5  5210.7  446.88    5231  447.05
  5236.3   445.3  5242.5   445.8  5253.1  447.68    5262  448.36  5267.3  447.84
  5284.8   448.8  5298.3  448.46    5306  449.31    5324  449.96  5382.2  450.75
#Mann= 3 , 0 , 0
  4641.7     .05       0  4984.4     .01       0  5098.2     .05       0
Bank Sta=4984.4,5098.2
XS Rating Curve= 0 ,0
Exp/Cntr=0.3,0.1

Type RM Length L Ch R = 1 ,4043    ,238,238,238
BEGIN DESCRIPTION:
Mapping XS e23ae089
END DESCRIPTION:
XS GIS Cut Line= 3
      2894563.53      7017374.68      2894613.44      7016825.68
      2894422.49      7016545.77
#Sta/Elev= 30
  4473.6  449.99  4513.4  449.15  4583.7  446.85  4684.1  444.79  4744.4  444.09
  4844.8  441.63  4878.2  440.55    4895  439.61  4919.4  439.12  4955.3   438.7
  4975.3     438  4988.6  438.14  4992.4  437.51  4992.9  436.71  4997.9  436.71
  4998.4  437.51  5015.5  438.09  5037.8  438.08  5051.5  439.12  5061.2  441.08
  5067.3  441.04  5082.2  442.68    5160  445.59  5195.9   446.6  5261.7  447.56
  5282.7  448.74  5304.1   449.3  5327.4  449.42  5333.5  449.02  5363.7  449.85
#Mann= 3 ,-1 , 0
  4473.6     .05       0  4992.4     .03       0  4998.4     .05       0
Bank Sta=4919.4,5051.5
XS Rating Curve= 0 ,0
Exp/Cntr=0.3,0.1

Type RM Length L Ch R = 1 ,3805    ,177,177,177
BEGIN DESCRIPTION:
Mapping XS c3bf3ba7
END DESCRIPTION:
XS GIS Cut Line= 3
      2894901.42      7017284.55      2894821.98      7016824.87
      2894667.24      7016559.59
#Sta/Elev= 30
  4539.3  447.11  4589.6  447.04    4620  445.98  4665.4  445.57  4691.1   444.8
  4701.2  444.99  4720.1  443.78    4752  442.71  4812.8  441.49    4823  440.09
  4835.4  439.21  4899.5  436.42  4904.6  436.89  4924.5  436.09  5007.6  435.94
  5008.1  435.14  5013.1  435.14  5013.6  435.94  5032.1  436.97  5047.8  438.79
  5063.5  439.37  5069.3  438.81  5071.7  439.21  5075.1  439.79  5106.5  441.53
  5143.7  442.66  5202.4  443.88  5251.2  445.42  5309.9  446.04  5312.9  446.49
#Mann= 3 ,-1 , 0
  4539.3     .05       0  5007.6    .035       0  5013.6     .05       0
Bank Sta=4835.4,5071.7
XS Rating Curve= 0 ,0
Exp/Cntr=0.3,0.1

Type RM Length L Ch R = 1 ,3628    ,159,159,159
BEGIN DESCRIPTION:
Mapping XS 243510c4
END DESCRIPTION:
XS GIS Cut Line= 3
      2895138.39      7017242.86      2894962.61      7016751.96
      2894742.52      7016556.61
#Sta/Elev= 30
  4515.4  449.61    4540  448.84  4570.8  448.51  4576.9  447.96  4596.2   447.5
  4683.1  446.01  4704.3  445.09  4725.6  445.18    4750  443.08  4806.2   440.7
  4821.2  440.81  4831.7  440.27  4837.3   439.2  4842.4  438.16  4874.3  436.15
  4998.7  435.95  4999.2  435.15  5004.2  435.15  5004.7  435.95  5082.7   436.1
  5089.4  436.32  5096.9   437.9  5111.1  438.96  5120.9   439.2  5153.8  440.96
  5167.3  442.23  5195.6  443.36    5224  443.33  5274.2  444.11  5331.1  445.55
#Mann= 3 ,-1 , 0
  4515.4     .05       0  4998.7    .033       0  5004.7     .05       0
Bank Sta=4837.3,5120.9
XS Rating Curve= 0 ,0
Exp/Cntr=0.3,0.1

Type RM Length L Ch R = 1 ,3469    ,36,36,36
BEGIN DESCRIPTION:
Mapping XS a0b8c984
END DESCRIPTION:
XS GIS Cut Line= 4
      2895282.42      7017074.16      2895183.46      7016777.28
       2894959.5      7016553.32      2894766.76      7016395.31
#Sta/Elev= 30
    4505  447.28  4542.6  446.23  4567.4  446.35  4579.5  445.35  4620.1  444.28
  4669.1  443.66  4683.3  442.12  4714.9  440.78  4732.4  440.47  4748.3   439.2
    4764  437.66  4769.3  436.72  4788.7  436.12  4846.7  436.24  4886.2  435.92
  4886.7  435.12  4891.7  435.12  4892.2  435.92  5108.4  436.09  5115.4  436.85
  5122.5  436.49  5129.6  437.68  5137.3  437.62  5143.4  438.32  5151.3  438.11
  5162.5   439.2  5172.1  439.96  5186.5  442.11  5285.5  445.83  5383.9   448.7
#Mann= 3 ,-1 , 0
    4505     .05       0  4886.2    .033       0  4892.2     .05       0
Bank Sta=4748.3,5162.5
XS Rating Curve= 0 ,0
Exp/Cntr=0.3,0.1

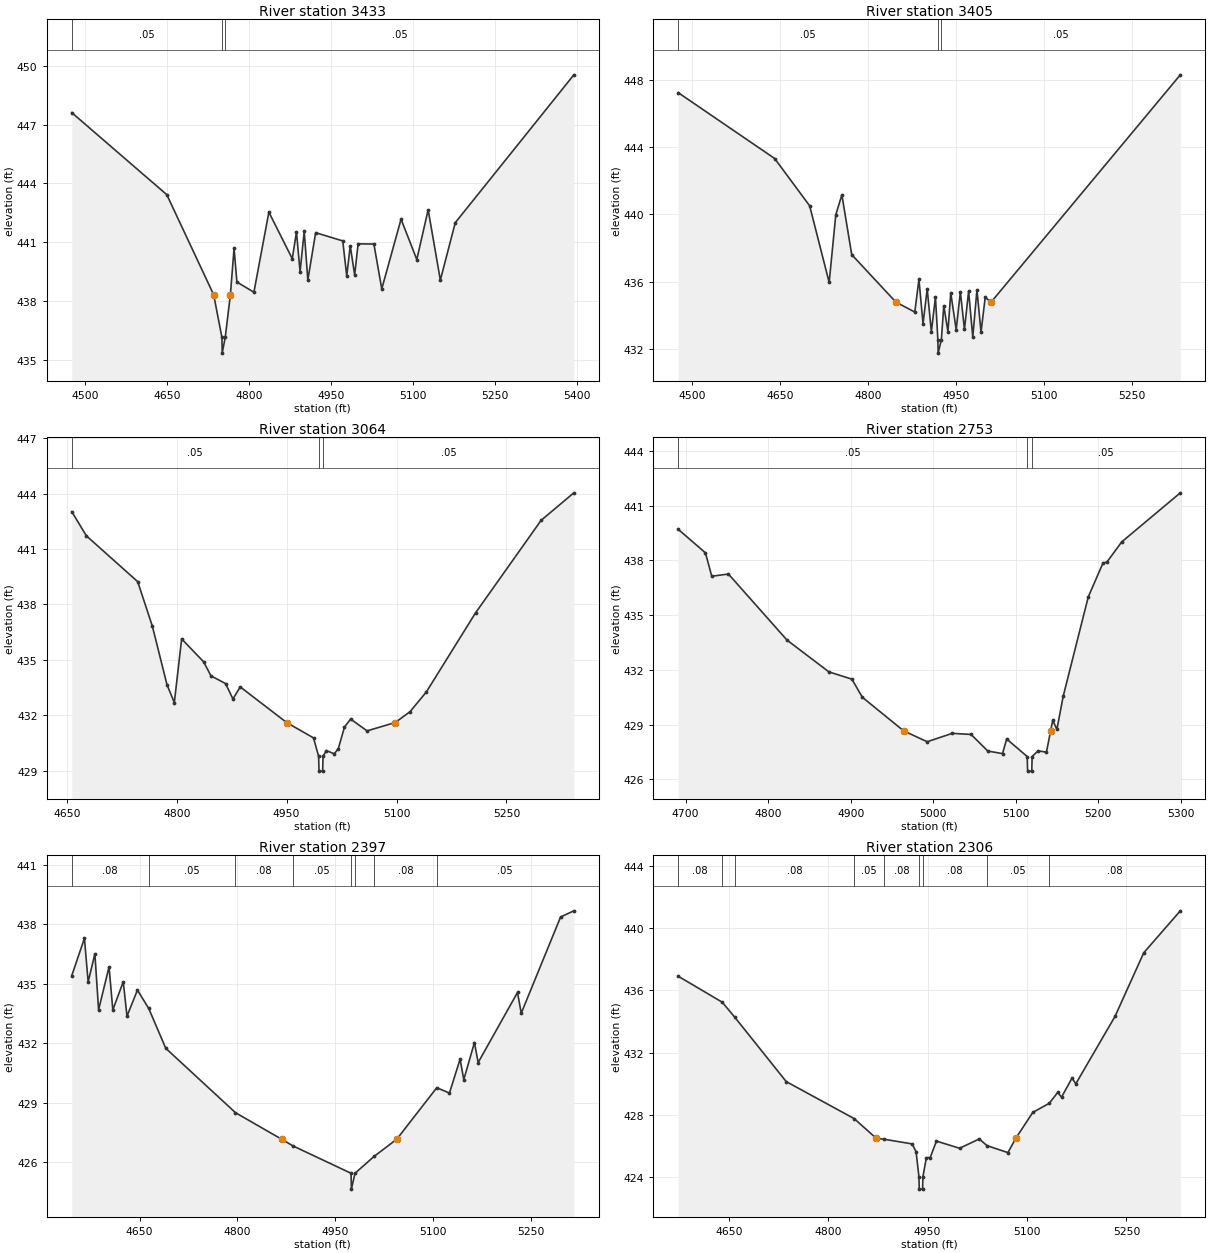
Type RM Length L Ch R = 1 ,3433    ,28,28,28
BEGIN DESCRIPTION:
Mapping XS cac0702e
END DESCRIPTION:
XS GIS Cut Line= 5
      2895301.51       7017072.4      2895216.44      7016770.33
      2895112.28       7016648.8      2894961.23      7016529.01
      2894766.55      7016368.78
#Sta/Elev= 30
  4475.6  447.61  4649.5  443.42  4735.3  438.31  4750.4  436.13  4750.9  435.33
  4756.4  436.13  4765.9  438.31  4772.6  440.68  4777.8  438.96  4808.9  438.44
  4836.3  442.53  4879.1  440.15  4886.8  441.51  4893.4  439.49    4901  441.55
  4907.6  439.06  4921.9  441.48  4971.5  441.06  4978.8  439.27  4985.2  440.81
  4993.3  439.32  4999.6  440.91  5028.5   440.9  5042.9  438.61  5078.2  442.17
    5107  440.11  5127.8  442.65  5150.1  439.06  5177.4  441.99  5394.4  449.54
#Mann= 3 ,-1 , 0
  4475.6     .05       0  4750.4    .033       0  4756.4     .05       0
Bank Sta=4735.3,4765.9
XS Rating Curve= 0 ,0
Exp/Cntr=0.3,0.1

Type RM Length L Ch R = 1 ,3405    ,341,341,341
BEGIN DESCRIPTION:
Mapping XS 85409fff
END DESCRIPTION:
XS GIS Cut Line= 5
      2895324.08      7017042.89      2895235.54      7016742.55
      2895126.16      7016633.18      2895034.15      7016541.16
      2894832.26      7016378.96
#Sta/Elev= 30
  4476.1  447.23  4640.7  443.32  4700.4  440.51  4733.7  435.96    4745  439.98
  4755.4  441.16  4772.2  437.61  4847.6  434.79  4879.8   434.2  4886.9  436.14
  4893.9  433.51    4901  435.58  4908.1  433.03  4915.1  435.09  4919.2  432.56
  4919.7  431.76  4925.2  432.56  4929.3  434.58  4936.4  433.04  4941.2  435.34
  4950.5  433.15  4957.6   435.4  4964.6  433.17  4971.7  435.44  4978.8  432.72
  4985.9  435.51  4992.9  433.01    5000  435.07  5010.1  434.79    5333  448.29
#Mann= 3 ,-1 , 0
  4476.1     .05       0  4919.2     .03       0  4925.2     .05       0
Bank Sta=4847.6,5010.1
XS Rating Curve= 0 ,0
Exp/Cntr=0.3,0.1

Type RM Length L Ch R = 1 ,3064    ,311,311,311
BEGIN DESCRIPTION:
UNT 048 IN DRY CR WATERSHED 8.0
END DESCRIPTION:
XS GIS Cut Line= 3
        2895375.      7016824.97        2895375.        7016475.
      2895224.99      7016174.98
#Sta/Elev= 30
  4656.7  443.02  4676.7  441.71  4746.7  439.23  4766.7  436.82  4786.7  433.65
  4796.7  432.68  4806.7  436.13  4836.7  434.89  4846.7  434.13  4866.7  433.71
  4876.7  432.88  4886.7  433.53  4950.1   431.6  4986.7  430.77  4993.7  429.77
  4994.2  428.97  4999.2  428.97  4999.7  429.77  5004.2  430.08  5015.1  429.91
  5020.6  430.19    5029  431.36  5037.4  431.79  5059.8  431.15  5098.2   431.6
  5118.5  432.19  5140.8  433.26  5207.9  437.54  5297.4  442.55  5342.1  444.04
#Mann= 3 ,-1 , 0
  4656.7     .05       0  4993.7     .03       0  4999.7     .05       0
Bank Sta=4950.1,5098.2
XS Rating Curve= 0 ,0
Exp/Cntr=0.3,0.1

Type RM Length L Ch R = 1 ,2753    ,356,356,356
BEGIN DESCRIPTION:
UNT 048 IN DRY CR WATERSHED 7.0
END DESCRIPTION:
XS GIS Cut Line= 3
        2895575.      7016725.01        2895625.        7016425.
        2895675.      7016124.99
#Sta/Elev= 30
  4691.1   439.7  4724.1  438.41  4731.7  437.13  4751.9  437.25  4822.9  433.63
  4873.6  431.89  4901.5  431.49  4914.1   430.5  4964.1  428.66  4992.7  428.06
  5023.1  428.52  5045.9  428.46  5066.2  427.55    5084  427.41    5089  428.21
  5113.9  427.25  5114.4  426.45  5119.4  426.45  5119.9  427.25    5127  427.56
  5137.2  427.49  5142.3  428.66  5144.8  429.23  5149.9  428.74  5157.5  430.55
  5187.9     436  5205.6  437.84  5210.7  437.92  5228.4  439.01  5299.4   441.7
#Mann= 3 ,-1 , 0
  4691.1     .05       0  5113.9     .03       0  5119.9     .05       0
Bank Sta=4964.1,5142.3
XS Rating Curve= 0 ,0
Exp/Cntr=0.3,0.1

Type RM Length L Ch R = 1 ,2397    ,91,91,91
BEGIN DESCRIPTION:
Mapping XS 21602b1a
END DESCRIPTION:
XS GIS Cut Line= 3
      2895760.38      7016816.66      2895992.57      7016400.02
       2896129.3      7016141.75
#Sta/Elev= 30
  4546.2  435.41  4565.6  437.29  4571.3  435.09  4581.6  436.51  4587.3  433.68
  4603.3  435.85  4609.1  433.68  4625.1   435.1  4630.8  433.36  4646.8  434.68
  4664.1  433.75  4690.2  431.74    4797  428.49  4867.7  427.15  4885.2  426.81
  4974.1  425.43  4974.6  424.63  4980.1  425.43  5009.3  426.28  5044.1  427.15
  5105.4  429.75  5124.8  429.48  5141.1  431.19  5146.8  430.16  5163.1  432.03
  5168.8  431.02  5229.1  434.56  5234.8  433.51  5295.1  438.37  5315.4  438.68
#Mann= 8 ,-1 , 0
  4546.2     .08       0  4664.1     .05       0    4797     .08       0
  4885.2     .05       0  4974.1     .03       0  4980.1     .05       0
  5009.3     .08       0  5105.4     .05       0
Bank Sta=4867.7,5044.1
XS Rating Curve= 0 ,0
Exp/Cntr=0.3,0.1

Type RM Length L Ch R = 1 ,2306    ,325,325,325
BEGIN DESCRIPTION:
Mapping XS 0f0b8033
END DESCRIPTION:
XS GIS Cut Line= 3
      2895845.01      7016788.45       2896070.7      7016415.21
       2896229.1      7016135.29
#Sta/Elev= 30
  4573.6  436.91    4640  435.24    4659  434.27  4736.6  430.13  4839.1  427.75
  4872.2  426.49  4884.5  426.42  4926.7  426.12  4932.6  425.61  4936.9  424.01
  4937.4  423.21  4942.4  423.21  4942.9  424.01  4948.1  425.23  4953.9  425.24
  4963.3   426.3  4998.3  425.84    5028  426.44  5039.6  426.01  5071.2  425.56
  5083.2  426.49  5108.8  428.15  5133.5  428.73  5146.3  429.43  5152.1  429.13
    5168  430.36  5173.7  429.99  5232.9  434.33  5276.2  438.42  5331.4  441.12
#Mann= 9 ,-1 , 0
  4573.6     .08       0    4640     .05       0    4659     .08       0
  4839.1     .05       0  4884.5     .08       0  4936.9     .07       0
  4942.9     .08       0  5039.6     .05       0  5133.5     .08       0
Bank Sta=4872.2,5083.2
XS Rating Curve= 0 ,0
Exp/Cntr=0.3,0.1

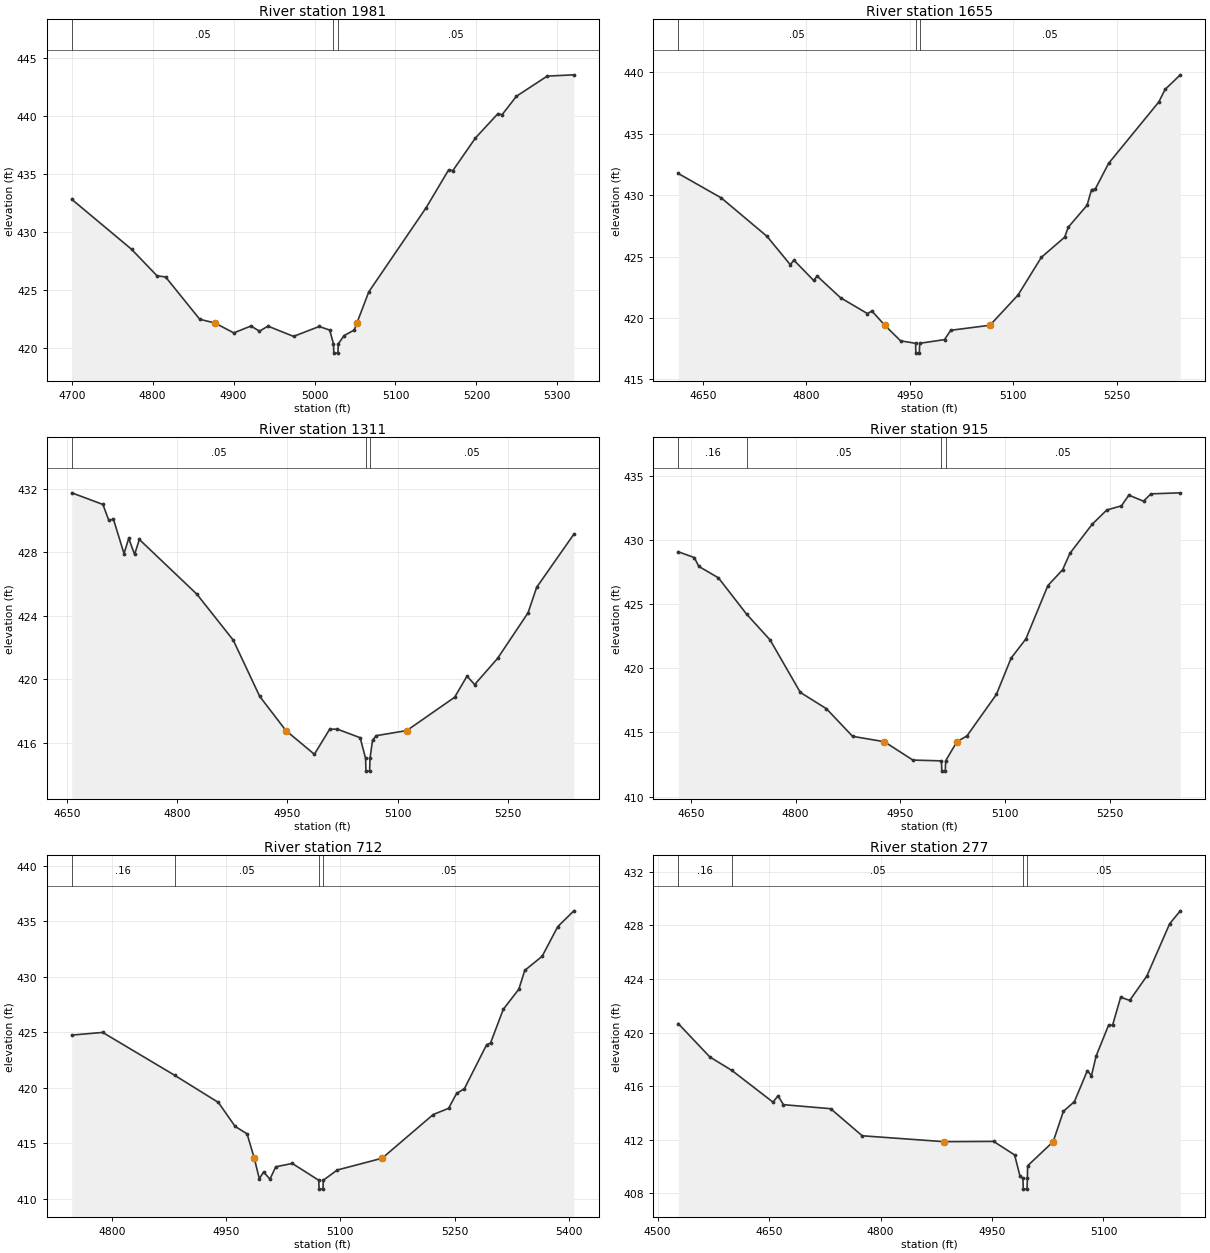
Type RM Length L Ch R = 1 ,1981    ,326,326,326
BEGIN DESCRIPTION:
UNT 048 IN DRY CR WATERSHED 5.0
END DESCRIPTION:
XS GIS Cut Line= 3
      2896275.01      7016674.97        2896375.        7016375.
      2896325.01      7016075.03
#Sta/Elev= 30
  4700.1  432.82  4773.9  428.53  4805.5  426.24    4816  426.15  4858.2  422.51
  4876.9  422.19  4900.3  421.34  4921.4  421.93    4932  421.49  4942.5  421.92
  4974.1  421.04  5005.8  421.89  5018.8  421.58  5023.4   420.4  5023.9   419.6
  5028.9   419.6  5029.4   420.4  5036.6  421.11  5049.2  421.59  5052.4  422.19
    5067  424.86  5137.9   432.1  5165.8  435.36  5170.9  435.29  5198.8  438.09
  5226.7  440.19  5231.7  440.09  5249.5  441.68  5287.5  443.41  5320.4  443.52
#Mann= 3 ,-1 , 0
  4700.1     .05       0  5023.4     .03       0  5029.4     .05       0
Bank Sta=4876.9,5052.4
XS Rating Curve= 0 ,0
Exp/Cntr=0.3,0.1

Type RM Length L Ch R = 1 ,1655    ,344,344,344
BEGIN DESCRIPTION:
UNT 048 IN DRY CR WATERSHED 4.0
END DESCRIPTION:
XS GIS Cut Line= 3
        2896575.      7016825.01        2896675.        7016475.
      2896575.01      7016125.02
#Sta/Elev= 30
  4614.3  431.77  4676.7  429.78    4743  426.65  4776.8  424.34    4782  424.71
  4810.6  423.06  4815.8  423.41  4849.6  421.65  4888.6  420.36  4895.1  420.57
  4913.8  419.41  4936.7  418.14  4958.4  417.94  4958.9  417.14  4963.9  417.14
  4964.4  417.94  5000.4  418.24  5009.5     419  5066.3  419.41    5107  421.87
  5140.8  424.94  5174.6  426.58  5179.8  427.39  5207.1  429.18  5213.6  430.46
  5218.8  430.48  5238.3  432.59  5311.1  437.59  5320.2  438.61  5342.3   439.8
#Mann= 3 ,-1 , 0
  4614.3     .05       0  4958.4     .03       0  4964.4     .05       0
Bank Sta=4913.8,5066.3
XS Rating Curve= 0 ,0
Exp/Cntr=0.3,0.1

Type RM Length L Ch R = 1 ,1311    ,396,396,396
BEGIN DESCRIPTION:
UNT 048 IN DRY CR WATERSHED 3.0
END DESCRIPTION:
XS GIS Cut Line= 3
        2896725.      7016925.01        2896925.        7016675.
      2897025.01      7016324.97
#Sta/Elev= 30
  4656.1  431.73  4698.5     431  4706.5  430.01  4712.9  430.07  4727.3  427.91
  4733.7  428.87  4741.7  427.86  4748.2   428.8  4826.6  425.36  4876.2  422.47
  4912.2  418.94  4947.9  416.79  4986.7   415.3  5007.5  416.87  5017.9  416.88
  5049.1  416.34  5056.5  415.04    5057  414.24    5062  414.24  5062.5  415.04
    5066  416.19  5071.2  416.47  5112.7  416.79  5177.8  418.88  5194.7  420.21
  5205.1  419.68  5236.3  421.32  5277.9  424.19  5289.6  425.79  5340.3  429.13
#Mann= 3 ,-1 , 0
  4656.1     .05       0  5056.5     .03       0  5062.5     .05       0
Bank Sta=4947.9,5112.7
XS Rating Curve= 0 ,0
Exp/Cntr=0.3,0.1

Type RM Length L Ch R = 1 ,915     ,203,203,203
BEGIN DESCRIPTION:
UNT 048 IN DRY CR WATERSHED 2.0
END DESCRIPTION:
XS GIS Cut Line= 3
      2897075.01      7017024.99        2897275.        7016675.
      2897374.99      7016375.02
#Sta/Elev= 30
    4632  429.07    4655  428.62  4661.5  427.93  4689.6  427.04    4730  424.21
  4763.7   422.2  4806.9  418.12  4844.3  416.85  4881.8   414.7  4927.3  414.28
  4968.2  412.85  5009.1  412.79  5009.6  411.99  5014.6  411.99  5015.1  412.79
  5031.2  414.28  5045.6  414.73  5087.8  417.96  5108.9  420.79    5130  422.28
  5161.6  426.44  5182.7  427.67  5193.2  428.95  5224.8   431.2  5245.9  432.32
    5267  432.65  5277.5  433.48  5298.6  433.01  5309.2  433.58  5351.3  433.66
#Mann= 4 ,-1 , 0
    4632     .16       0    4730     .05       0  5009.1     .03       0
  5015.1     .05       0
Bank Sta=4927.3,5031.2
XS Rating Curve= 0 ,0
Exp/Cntr=0.3,0.1

Type RM Length L Ch R = 1 ,712     ,435,435,435
BEGIN DESCRIPTION:
Mapping XS 7e9c9996
END DESCRIPTION:
XS GIS Cut Line= 3
      2897238.21      7017061.95      2897409.67      7016755.92
       2897472.6       7016454.3
#Sta/Elev= 30
  4747.5  424.75  4788.1  424.99  4882.6  421.13  4939.9  418.69  4961.8  416.54
  4977.6  415.86    4987  413.67  4993.6  411.83  4999.3  412.43  5007.6  411.79
  5015.2   412.9  5036.9   413.2  5071.6  411.69  5072.1  410.89  5077.1  410.89
  5077.6  411.69  5095.9  412.61  5154.8  413.67  5221.8   417.6    5242  418.16
  5252.5   419.5  5262.7  419.92    5292  423.89  5297.1  424.04  5313.8  427.07
  5334.2  428.88    5342  430.57  5364.8  431.84  5385.3  434.51  5406.4  435.93
#Mann= 4 ,-1 , 0
  4747.5     .16       0  4882.6     .05       0  5071.6     .03       0
  5077.6     .05       0
Bank Sta=4987,5154.8
XS Rating Curve= 0 ,0
Exp/Cntr=0.3,0.1

Type RM Length L Ch R = 1 ,277     ,0,0,0
BEGIN DESCRIPTION:
UNT 048 IN DRY CR WATERSHED 1.0
END DESCRIPTION:
XS GIS Cut Line= 3
      2897399.98      7017000.02      2897724.56      7016656.93
      2897639.87        7016472.
#Sta/Elev= 30
  4527.7  420.67  4570.2  418.18    4600  417.17  4655.2  414.81    4662  415.28
  4669.3  414.62  4732.8  414.32  4775.3   412.3  4885.3  411.86  4952.1  411.88
  4980.4  410.87  4987.7  409.28  4991.6  409.12  4992.1  408.32  4997.1  408.32
  4997.6  409.12  4997.9  410.06  5032.3  411.86  5046.1  414.13  5060.8  414.84
  5078.3  417.16  5083.8  416.78  5090.1  418.25  5106.8  420.54  5112.3  420.56
  5123.1  422.63  5135.3   422.4  5158.3  424.21  5189.1  428.12  5203.4  429.08
#Mann= 4 ,-1 , 0
  4527.7     .16       0    4600     .05       0  4991.6     .03       0
  4997.6     .05       0
Bank Sta=4885.3,5032.3
XS Rating Curve= 0 ,0
Exp/Cntr=0.3,0.1
LCMann Table=0

Chan Stop Cuts=-1
Use User Specified Reach Order=0
Composite Channel Slope=5