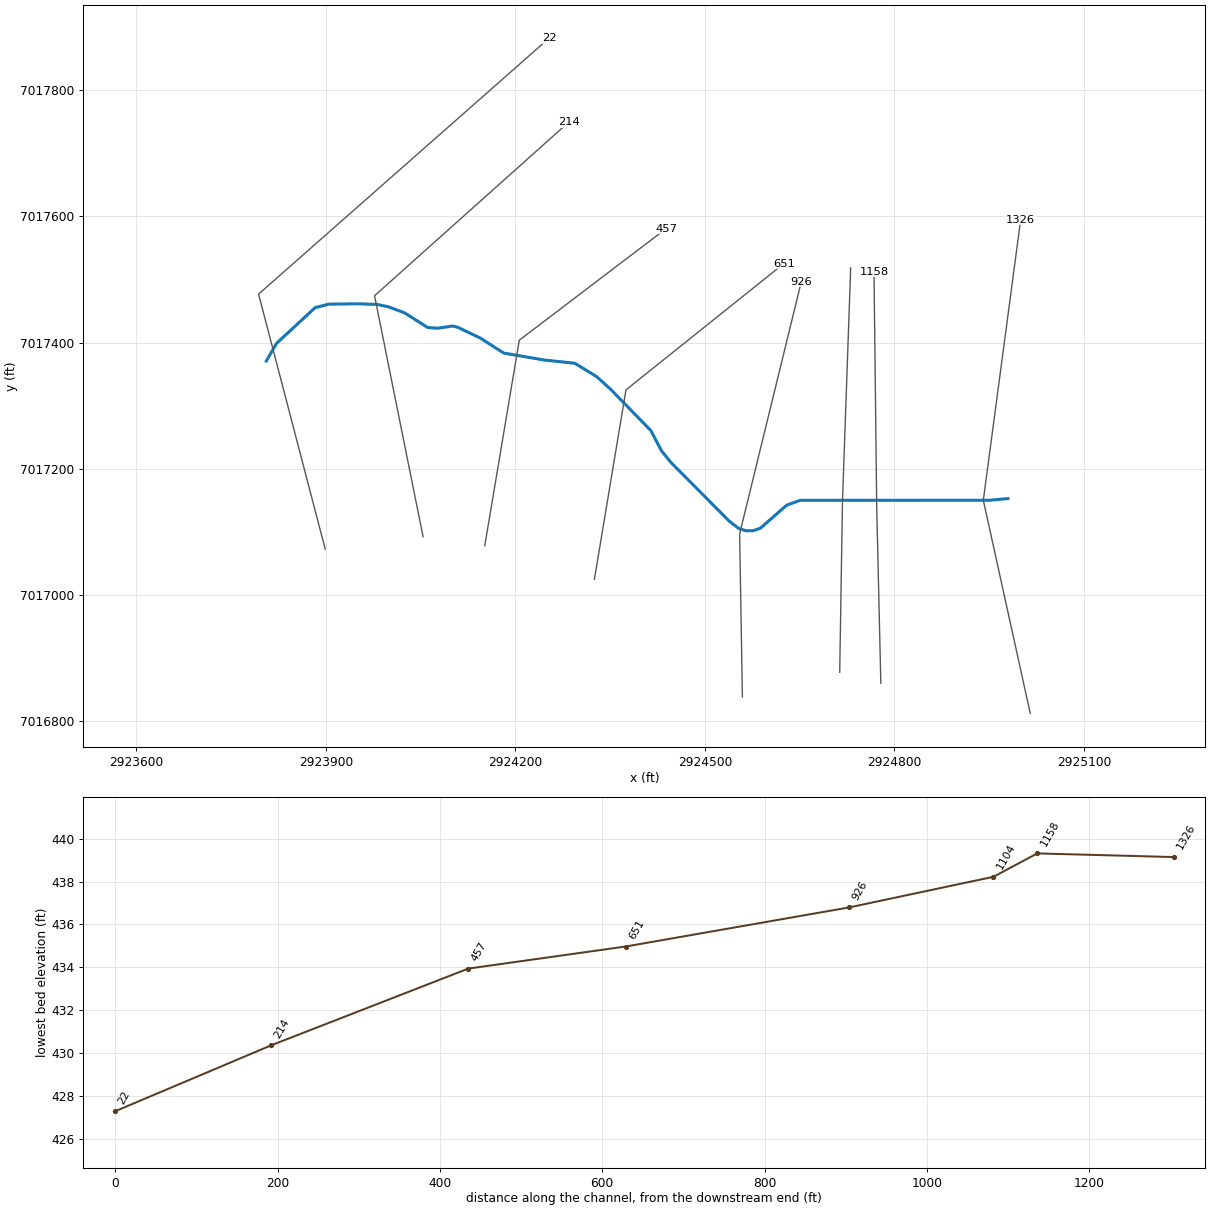
--- UNT 049 IN DRY CR WATERSHED.prj (project) ---

Proj Title=UNT 049 IN DRY CR WATERSHED Base Level Engineering
Current Plan=p01
Default Exp/Contr=0.3,0.1
English Units
Geom File=g01
Flow File=f01
Plan File=p01
BEGIN DESCRIPTION:
UNT 049 IN DRY CR WATERSHED
END DESCRIPTION:

--- UNT 049 IN DRY CR WATERSHED.p01 (plan) ---

Plan Title=Multiple Run
Short Identifier=Multiple
Geom File=g01
Flow File=f01
Subcritical Flow
K Sum by GR= 0
Std Step Tol= 0.01
Critical Tol= 0.01
Num of Std Step Trials= 20
Max Error Tol= 0.3
Flow Tol Ratio= 0.001
Split Flow NTrial= 30
Split Flow Tol= 0.02
Split Flow Ratio= 0.02
Log Output Level= 0
Friction Slope Method= 1
Unsteady Friction Slope Method= 2
Unsteady Bridges Friction Slope Method= 1
Parabolic Critical Depth
Global Vel Dist=  1 , 1 , 1
Global Log Level= 0
CheckData=True
Encroach Param= -1, 0, 0, 0
BEGIN DESCRIPTION:
Multiple Run
END DESCRIPTION:

--- UNT 049 IN DRY CR WATERSHED.f01 (steady flow) ---

Flow Title=Multiple
Number of Profiles=7
Profile Names=10-year,25-year,50-year,1pct_min,100-year,1pct_plu,500-year
River Rch & RM= UNT 049 IN DRY C,Reach-1,1326
     277     357     420     246     491     981     673
Boundary for River Rch & Prof#=UNT 049 IN DRY C,Reach-1,1
Up Type=0
Dn Type=3
Dn Slope=0.005
Boundary for River Rch & Prof#=UNT 049 IN DRY C,Reach-1,2
Up Type=0
Dn Type=3
Dn Slope=0.005
Boundary for River Rch & Prof#=UNT 049 IN DRY C,Reach-1,3
Up Type=0
Dn Type=3
Dn Slope=0.005
Boundary for River Rch & Prof#=UNT 049 IN DRY C,Reach-1,4
Up Type=0
Dn Type=3
Dn Slope=0.005
Boundary for River Rch & Prof#=UNT 049 IN DRY C,Reach-1,5
Up Type=0
Dn Type=3
Dn Slope=0.005
Boundary for River Rch & Prof#=UNT 049 IN DRY C,Reach-1,6
Up Type=0
Dn Type=3
Dn Slope=0.005
Boundary for River Rch & Prof#=UNT 049 IN DRY C,Reach-1,7
Up Type=0
Dn Type=3
Dn Slope=0.005

--- UNT 049 IN DRY CR WATERSHED.g01 (geometry) ---

Geom Title=Existing Conditions

River Reach=UNT 049 IN DRY C,Reach-1
Reach XY= 30
      2924979.69      7017152.88      2924950.78      7017150.25
      2924650.79      7017150.15      2924629.49      7017142.45
      2924587.72      7017105.97      2924576.35      7017102.06
      2924564.70      7017101.98      2924553.11      7017105.86
      2924538.05      7017117.62      2924446.68      7017209.63
      2924431.46      7017228.17      2924414.34      7017260.69
      2924349.85      7017326.81      2924328.53      7017346.03
      2924294.11      7017367.13      2924245.48      7017372.29
      2924181.61      7017383.23      2924144.03      7017407.21
      2924108.31      7017424.25      2924100.37      7017426.10
      2924076.56      7017422.59      2924061.01      7017423.81
      2924024.17      7017447.11      2923998.60      7017456.61
      2923981.00      7017460.28      2923952.55      7017461.26
      2923904.74      7017460.77      2923882.86      7017455.21
      2923821.66      7017398.51      2923805.59      7017370.71

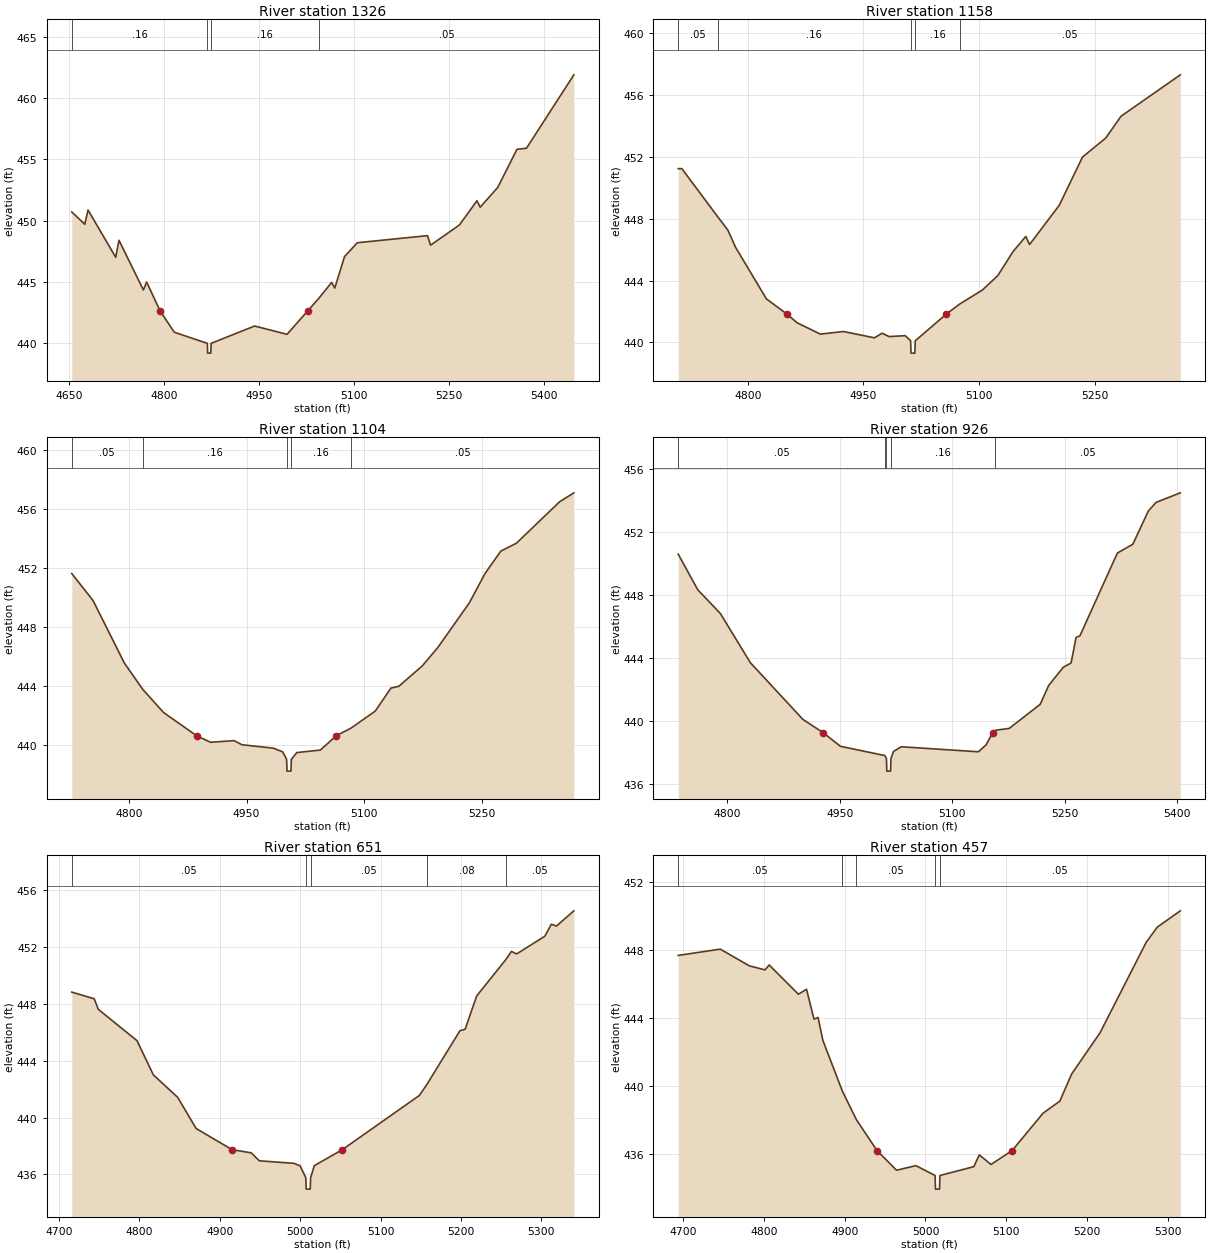
Type RM Length L Ch R = 1,1326,168,168,168
BEGIN DESCRIPTION:
UNT 049 IN DRY CR WATERSHED 3.0
END DESCRIPTION:
XS GIS Cut Line= 3
      2925015.08      7016812.83      2924940.78      7017150.25
      2924999.89      7017594.13
#Sta/Elev= 30
  4654.5  450.70  4675.1  449.69  4680.2  450.86  4723.9  446.99  4729.1  448.38
  4767.7  444.31  4772.8  444.96  4794.1  442.59  4816.5  440.85  4868.7  439.94
  4869.2  439.14  4874.2  439.14  4874.7  439.94  4943.4  441.36  4994.6  440.68
  5027.2  442.59  5045.2  443.65  5065.1  444.93  5070.1  444.47  5085.5  447.05
  5105.7  448.18  5216.5  448.76  5221.5  447.98  5267.1  449.64  5294.7  451.62
  5299.8  451.09  5327.6  452.71  5357.9  455.83  5373.0  455.92  5447.8  461.93
#Mann=4,-1,0
  4654.5    0.16       0  4868.7    0.07       0  4874.7    0.16       0
  5045.2    0.05       0
Bank Sta=4794.1,5027.2
Exp/Cntr=0.3,0.1

Type RM Length L Ch R = 1,1158,54,54,54
BEGIN DESCRIPTION:
Mapping XS beff5e84
END DESCRIPTION:
XS GIS Cut Line= 3
      2924778.53      7016860.62      2924772.02      7017138.37
      2924767.70      7017511.92
#Sta/Elev= 30
  4709.8  451.25  4714.5  451.25  4761.4  448.11  4774.2  447.27  4784.2  446.16
  4824.2  442.82  4851.0  441.83  4864.2  441.27  4894.2  440.54  4924.2  440.71
  4964.3  440.30  4974.3  440.60  4983.4  440.38  5004.3  440.44  5011.3  440.11
  5011.8  439.31  5016.8  439.31  5017.3  440.11  5057.5  441.83  5074.8  442.48
  5104.3  443.39  5124.3  444.32  5144.3  445.89  5160.7  446.86  5165.7  446.34
  5204.3  448.89  5234.3  452.00  5264.3  453.22  5284.3  454.64  5361.2  457.32
#Mann=5,-1,0
  4709.8    0.05       0  4761.4    0.16       0  5011.3    0.07       0
  5017.3    0.16       0  5074.8    0.05       0
Bank Sta=4851,5057.5
Exp/Cntr=0.3,0.1

Type RM Length L Ch R = 1,1104,178,178,178
BEGIN DESCRIPTION:
Mapping XS 57c4aa75
END DESCRIPTION:
XS GIS Cut Line= 3
      2924713.42      7016877.94      2924717.76      7017147.05
      2924730.79      7017518.17
#Sta/Elev= 30
  4727.0  451.64  4754.1  449.81  4794.1  445.56  4817.6  443.77  4844.1  442.20
  4886.4  440.62  4904.1  440.18  4934.1  440.29  4944.1  440.01  4984.1  439.78
  4996.1  439.53  5001.1  439.02  5001.6  438.22  5006.6  438.22  5007.1  439.02
  5014.1  439.48  5044.1  439.65  5064.4  440.62  5083.5  441.15  5114.2  442.30
  5134.2  443.86  5144.2  443.98  5174.2  445.37  5194.2  446.63  5234.2  449.65
  5254.3  451.65  5274.3  453.16  5294.3  453.70  5349.3  456.51  5367.5  457.12
#Mann=5,-1,0
  4727.0    0.05       0  4817.6    0.16       0  5001.1    0.07       0
  5007.1    0.16       0  5083.5    0.05       0
Bank Sta=4886.4,5064.4
Exp/Cntr=0.3,0.1

Type RM Length L Ch R = 1,926,275,275,275
BEGIN DESCRIPTION:
Mapping XS 4badec03
END DESCRIPTION:
XS GIS Cut Line= 3
      2924559.35      7016838.86      2924555.00      7017097.14
      2924652.66      7017496.46
#Sta/Elev= 30
  4734.5  450.59  4760.6  448.32  4790.6  446.82  4830.6  443.69  4900.7  440.08
  4927.9  439.23  4950.7  438.37  5010.0  437.78  5012.1  437.59  5012.6  436.79
  5017.6  436.79  5018.1  437.59  5021.5  438.04  5031.8  438.34  5134.7  438.02
  5145.1  438.47  5153.7  439.23  5156.8  439.38  5175.9  439.51  5217.1  441.04
  5228.4  442.24  5248.0  443.40  5258.3  443.67  5264.9  445.29  5270.1  445.40
  5320.0  450.66  5340.6  451.22  5361.2  453.33  5371.5  453.88  5403.9  454.49
#Mann=5,-1,0
  4734.5    0.05       0  5010.0    0.16       0  5012.1    0.03       0
  5018.1    0.16       0  5156.8    0.05       0
Bank Sta=4927.9,5153.7
Exp/Cntr=0.3,0.1

Type RM Length L Ch R = 1,651,194,194,194
BEGIN DESCRIPTION:
UNT 049 IN DRY CR WATERSHED 2.0
END DESCRIPTION:
XS GIS Cut Line= 3
      2924324.99      7017024.95      2924375.00      7017325.00
      2924624.97      7017524.97
#Sta/Elev= 30
  4716.1  448.81  4744.0  448.34  4749.1  447.60  4797.2  445.40  4817.5  443.00
  4847.9  441.41  4870.7  439.23  4915.5  437.74  4939.2  437.52  4949.3  436.96
  4992.4  436.78  5000.0  436.61  5007.1  435.77  5007.6  434.97  5012.6  434.97
  5013.1  435.77  5017.7  436.62  5052.5  437.74  5148.3  441.55  5157.2  442.28
  5198.8  446.10  5205.2  446.20  5219.6  448.54  5256.2  451.12  5262.8  451.67
  5269.2  451.49  5304.4  452.74  5312.4  453.58  5318.8  453.45  5340.4  454.52
#Mann=5,-1,0
  4716.1    0.05       0  5007.1    0.03       0  5013.1    0.05       0
  5157.2    0.08       0  5256.2    0.05       0
Bank Sta=4915.5,5052.5
Exp/Cntr=0.3,0.1

Type RM Length L Ch R = 1,457,243,243,243
BEGIN DESCRIPTION:
Mapping XS 1699c275
END DESCRIPTION:
XS GIS Cut Line= 3
      2924151.44      7017078.17      2924206.12      7017403.69
      2924438.72      7017580.42
#Sta/Elev= 30
  4693.6  447.67  4745.7  448.04  4781.6  447.06  4801.2  446.82  4806.3  447.11
  4842.5  445.39  4852.6  445.68  4861.8  443.93  4866.9  444.02  4872.9  442.67
  4896.9  439.71  4914.3  438.03  4940.0  436.20  4964.2  435.05  4988.1  435.32
  5011.9  434.74  5012.4  433.94  5017.4  433.94  5017.9  434.74  5059.9  435.26
  5066.7  435.95  5081.2  435.39  5107.3  436.20  5145.7  438.40  5166.5  439.11
  5181.1  440.70  5216.4  443.13  5273.4  448.43  5287.2  449.33  5315.8  450.29
#Mann=5,-1,0
  4693.6    0.05       0  4896.9    0.16       0  4914.3    0.05       0
  5011.9    0.03       0  5017.9    0.05       0
Bank Sta=4940,5107.3
Exp/Cntr=0.3,0.1

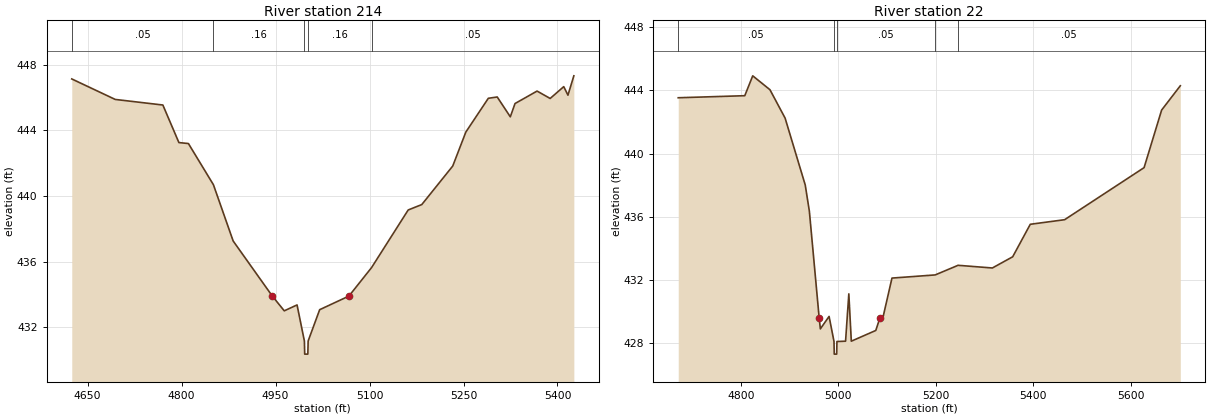
Type RM Length L Ch R = 1,214,192,192,192
BEGIN DESCRIPTION:
Mapping XS 7b8d2529
END DESCRIPTION:
XS GIS Cut Line= 3
      2924053.79      7017092.47      2923976.96      7017474.01
      2924284.25      7017748.75
#Sta/Elev= 30
  4624.7  447.14  4694.1  445.89  4770.1  445.55  4795.7  443.26  4810.9  443.20
  4850.8  440.69  4882.3  437.26  4944.8  433.90  4963.9  433.00  4984.3  433.36
  4996.0  431.16  4996.5  430.36  5001.5  430.36  5002.0  431.16  5020.4  433.07
  5067.1  433.90  5103.3  435.64  5161.7  439.15  5183.4  439.48  5232.8  441.83
  5253.7  443.90  5289.6  445.96  5303.8  446.04  5324.7  444.83  5332.2  445.64
  5367.4  446.40  5388.3  445.95  5410.0  446.67  5416.7  446.15  5426.1  447.33
#Mann=5,-1,0
  4624.7    0.05       0  4850.8    0.16       0  4996.0    0.07       0
  5002.0    0.16       0  5103.3    0.05       0
Bank Sta=4944.8,5067.1
Exp/Cntr=0.3,0.1

Type RM Length L Ch R = 1,22,0,0,0
BEGIN DESCRIPTION:
UNT 049 IN DRY CR WATERSHED 1.0
END DESCRIPTION:
XS GIS Cut Line= 3
      2923898.83      7017072.96      2923793.36      7017476.61
      2924253.02      7017881.58
#Sta/Elev= 30
  4671.9  443.54  4808.4  443.67  4824.7  444.93  4860.0  444.05  4891.1  442.25
  4932.4  438.01  4940.9  436.34  4961.0  429.58  4963.4  428.89  4981.3  429.68
  4991.4  428.09  4991.9  427.29  4996.9  427.29  4997.4  428.09  5015.1  428.11
  5021.8  431.11  5026.9  428.11  5077.1  428.79  5085.5  429.58  5091.7  429.60
  5110.3  432.11  5198.9  432.31  5245.9  432.92  5316.2  432.75  5357.9  433.46
  5394.0  435.52  5464.4  435.81  5627.4  439.11  5663.4  442.76  5701.7  444.30
#Mann=5,-1,0
  4671.9    0.05       0  4991.4    0.03       0  4997.4    0.05       0
  5198.9    0.16       0  5245.9    0.05       0
Bank Sta=4961,5085.5
Exp/Cntr=0.3,0.1

Chan Stop Cuts=-1