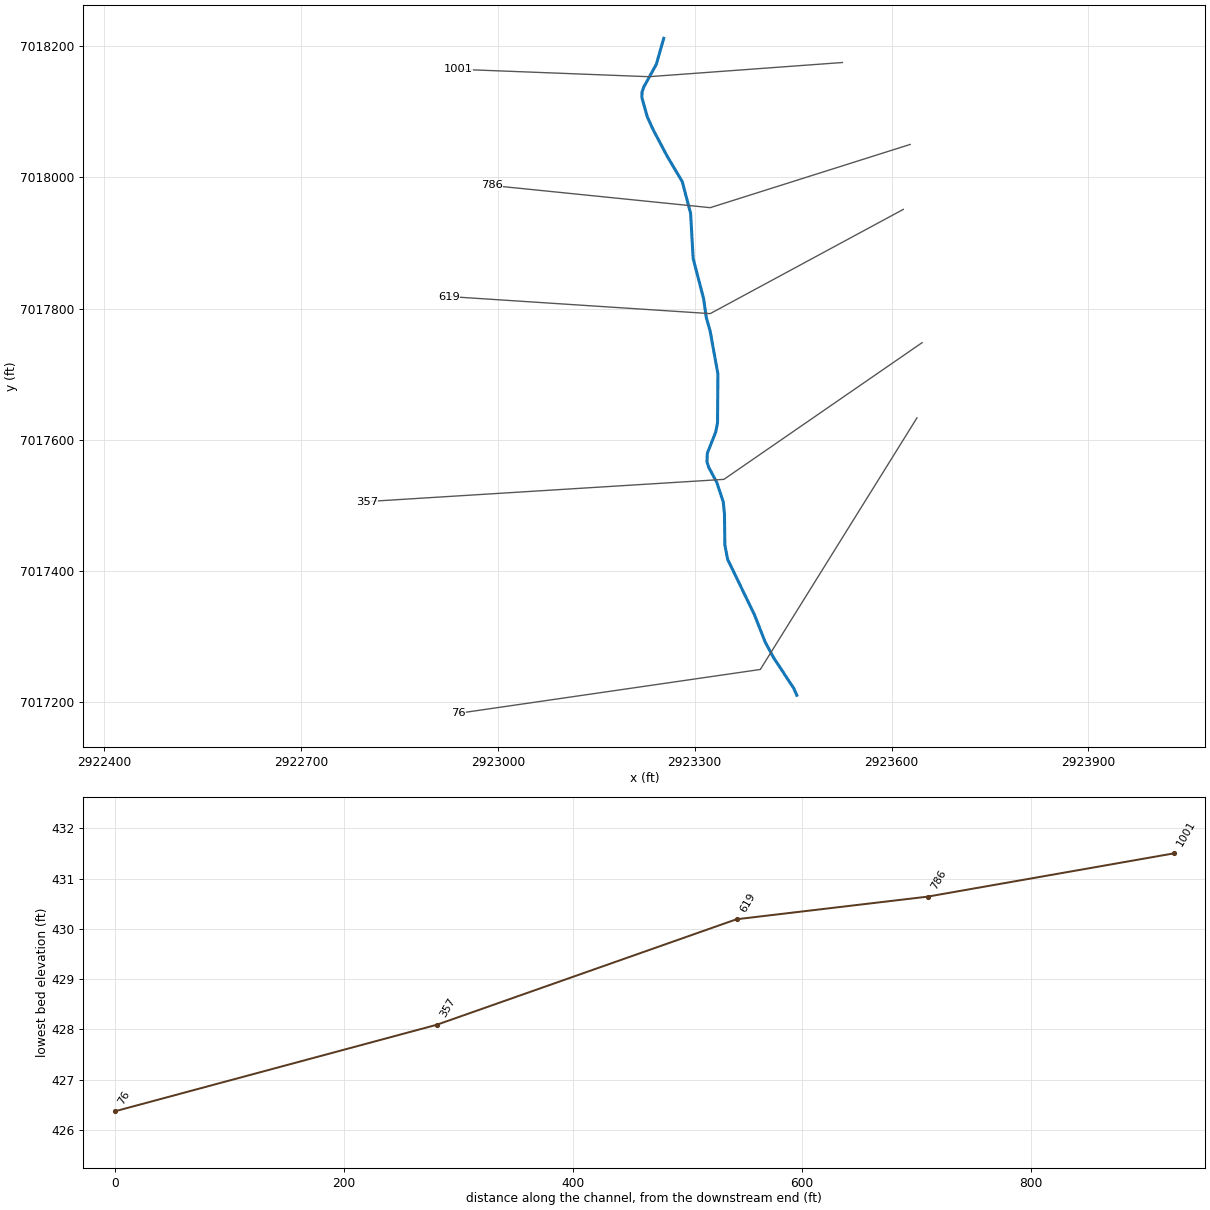
--- UNT 050 IN DRY CR WATERSHED.prj (project) ---

Proj Title=UNT 050 IN DRY CR WATERSHED Base Level Engineering
Current Plan=p01
Default Exp/Contr=0.3,0.1
English Units
Geom File=g01
Flow File=f01
Plan File=p01
BEGIN DESCRIPTION:
UNT 050 IN DRY CR WATERSHED
END DESCRIPTION:

--- UNT 050 IN DRY CR WATERSHED.p01 (plan) ---

Plan Title=Multiple Run
Short Identifier=Multiple
Geom File=g01
Flow File=f01
Subcritical Flow
K Sum by GR= 0
Std Step Tol= 0.01
Critical Tol= 0.01
Num of Std Step Trials= 20
Max Error Tol= 0.3
Flow Tol Ratio= 0.001
Split Flow NTrial= 30
Split Flow Tol= 0.02
Split Flow Ratio= 0.02
Log Output Level= 0
Friction Slope Method= 1
Unsteady Friction Slope Method= 2
Unsteady Bridges Friction Slope Method= 1
Parabolic Critical Depth
Global Vel Dist=  1 , 1 , 1
Global Log Level= 0
CheckData=True
Encroach Param= -1, 0, 0, 0
BEGIN DESCRIPTION:
Multiple Run
END DESCRIPTION:

--- UNT 050 IN DRY CR WATERSHED.f01 (steady flow) ---

Flow Title=Multiple
Number of Profiles=7
Profile Names=10-year,25-year,50-year,1pct_min,100-year,1pct_plu,500-year
River Rch & RM= UNT 050 IN DRY C,Reach-1,1001
     259     331     386     225     449     896     606
Boundary for River Rch & Prof#=UNT 050 IN DRY C,Reach-1,1
Up Type=0
Dn Type=3
Dn Slope=0.005
Boundary for River Rch & Prof#=UNT 050 IN DRY C,Reach-1,2
Up Type=0
Dn Type=3
Dn Slope=0.005
Boundary for River Rch & Prof#=UNT 050 IN DRY C,Reach-1,3
Up Type=0
Dn Type=3
Dn Slope=0.005
Boundary for River Rch & Prof#=UNT 050 IN DRY C,Reach-1,4
Up Type=0
Dn Type=3
Dn Slope=0.005
Boundary for River Rch & Prof#=UNT 050 IN DRY C,Reach-1,5
Up Type=0
Dn Type=3
Dn Slope=0.005
Boundary for River Rch & Prof#=UNT 050 IN DRY C,Reach-1,6
Up Type=0
Dn Type=3
Dn Slope=0.005
Boundary for River Rch & Prof#=UNT 050 IN DRY C,Reach-1,7
Up Type=0
Dn Type=3
Dn Slope=0.005

--- UNT 050 IN DRY CR WATERSHED.g01 (geometry) ---

Geom Title=Existing Conditions

River Reach=UNT 050 IN DRY C,Reach-1
Reach XY= 30
      2923252.75      7018211.85      2923241.49      7018172.25
      2923222.27      7018137.54      2923219.72      7018129.83
      2923219.46      7018121.41      2923227.82      7018091.89
      2923237.19      7018071.53      2923258.24      7018031.83
      2923281.00      7017993.52      2923293.71      7017945.23
      2923297.62      7017876.26      2923313.59      7017814.88
      2923317.62      7017786.55      2923323.56      7017765.42
      2923335.31      7017700.53      2923334.77      7017625.95
      2923332.06      7017611.98      2923319.20      7017579.47
      2923318.69      7017566.41      2923321.24      7017558.27
      2923333.61      7017535.07      2923343.55      7017505.19
      2923345.33      7017486.95      2923345.93      7017439.80
      2923350.14      7017417.88      2923390.97      7017333.51
      2923407.50      7017291.50      2923420.25      7017267.92
      2923451.07      7017221.00      2923455.59      7017210.71

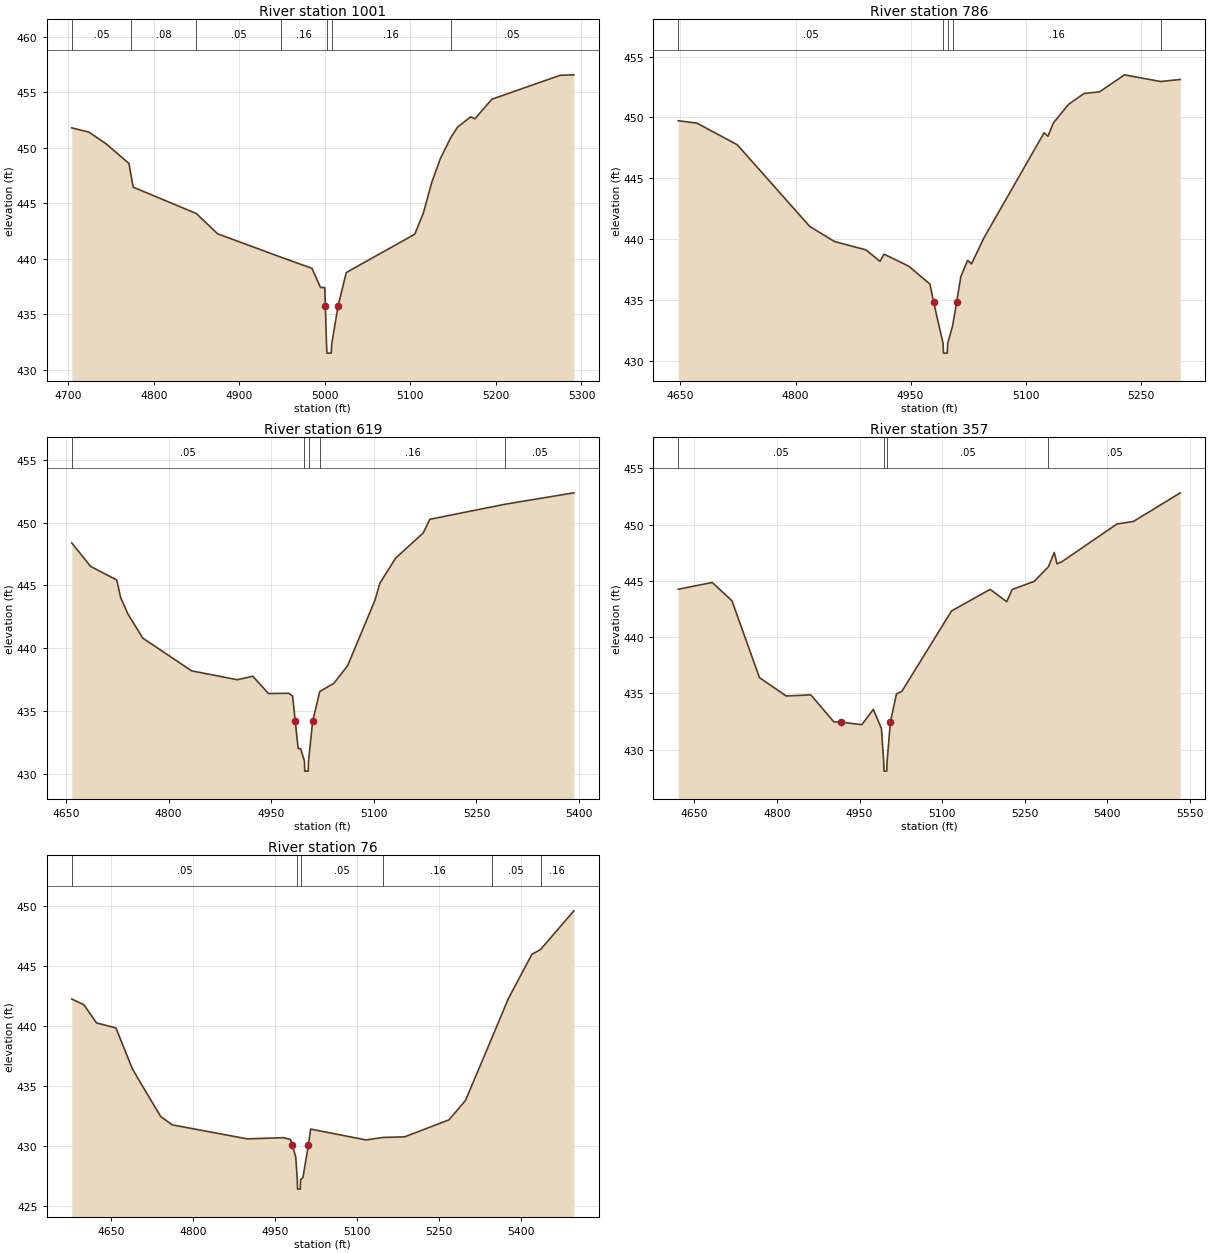
Type RM Length L Ch R = 1,1001,215,215,215
BEGIN DESCRIPTION:
UNT 050 IN DRY CR WATERSHED 2.0
END DESCRIPTION:
XS GIS Cut Line= 3
      2923525.04      7018175.00      2923230.03      7018153.38
      2922939.15      7018164.68
#Sta/Elev= 30
  4704.2  451.79  4724.3  451.41  4744.4  450.35  4771.0  448.59  4773.4  447.56
  4776.0  446.45  4849.7  444.08  4874.7  442.25  4948.8  440.14  4985.0  439.14
  4995.0  437.41  5000.0  437.41  5000.6  435.79  5002.0  432.30  5002.5  431.50
  5007.5  431.50  5008.0  432.30  5015.6  435.79  5025.1  438.76  5105.1  442.21
  5115.1  444.10  5125.1  446.90  5135.1  449.03  5147.2  450.91  5155.2  451.86
  5170.4  452.78  5175.4  452.61  5195.2  454.37  5275.2  456.53  5291.1  456.57
#Mann=7,-1,0
  4704.2    0.05       0  4773.4    0.08       0  4849.7    0.05       0
  4948.8    0.16       0  5002.0    0.07       0  5008.0    0.16       0
  5147.2    0.05       0
Bank Sta=5000.6,5015.6
Exp/Cntr=0.3,0.1

Type RM Length L Ch R = 1,786,167,167,167
BEGIN DESCRIPTION:
Mapping XS ecb8c28a
END DESCRIPTION:
XS GIS Cut Line= 3
      2923628.30      7018050.13      2923323.63      7017953.78
      2922990.29      7017987.63
#Sta/Elev= 30
  4647.1  449.73  4671.5  449.53  4724.0  447.76  4818.5  441.05  4850.8  439.81
  4891.8  439.12  4910.2  438.18  4915.4  438.77  4947.7  437.78  4975.3  436.31
  4980.1  434.82  4992.4  431.44  4992.9  430.64  4997.9  430.64  4998.4  431.44
  5004.8  432.87  5010.1  434.82  5015.5  436.92  5024.4  438.26  5029.4  437.97
  5045.7  440.11  5124.1  448.74  5129.2  448.46  5136.1  449.54  5156.2  451.09
  5176.3  451.97  5196.4  452.10  5228.9  453.50  5276.1  452.95  5301.7  453.12
#Mann=5,-1,0
  4647.1    0.05       0  4992.4    0.03       0  4998.4    0.05       0
  5004.8    0.16       0  5276.1    0.05       0
Bank Sta=4980.1,5010.1
Exp/Cntr=0.3,0.1

Type RM Length L Ch R = 1,619,262,262,262
BEGIN DESCRIPTION:
Mapping XS 1778f9f3
END DESCRIPTION:
XS GIS Cut Line= 3
      2923617.87      7017951.16      2923323.63      7017792.32
      2922925.16      7017818.36
#Sta/Elev= 30
  4658.6  448.39  4686.2  446.52  4724.3  445.44  4730.1  444.03  4740.5  442.74
  4762.4  440.80  4833.7  438.19  4900.5  437.48  4923.2  437.76  4946.0  436.38
  4975.6  436.40  4981.3  436.18  4985.2  434.17  4989.4  431.99  4993.0  431.99
  4998.6  430.99  4999.1  430.19  5004.1  430.19  5004.6  430.99  5010.6  434.17
  5021.0  436.54  5041.7  437.20  5061.8  438.61  5101.8  443.84  5108.8  445.18
  5131.9  447.18  5172.0  449.18  5182.0  450.28  5291.7  451.48  5392.3  452.39
#Mann=5,-1,0
  4658.6    0.05       0  4998.6    0.03       0  5004.6    0.05       0
  5021.0    0.16       0  5291.7    0.05       0
Bank Sta=4985.2,5010.6
Exp/Cntr=0.3,0.1

Type RM Length L Ch R = 1,357,281,281,281
BEGIN DESCRIPTION:
Mapping XS a6a899b4
END DESCRIPTION:
XS GIS Cut Line= 3
      2923646.53      7017748.03      2923344.47      7017539.71
      2922800.15      7017505.86
#Sta/Elev= 30
  4620.6  444.26  4682.4  444.86  4718.2  443.24  4768.2  436.40  4816.9  434.77
  4861.5  434.87  4903.4  432.47  4916.1  432.44  4954.2  432.22  4975.1  433.58
  4989.8  431.88  4994.0  428.89  4994.5  428.09  4999.5  428.09  5000.0  428.89
  5006.1  432.44  5017.1  434.95  5027.1  435.19  5117.2  442.33  5187.4  444.25
  5217.4  443.15  5227.5  444.24  5267.5  444.96  5293.3  446.26  5303.8  447.53
  5308.9  446.52  5317.6  446.70  5417.8  450.06  5447.9  450.29  5532.9  452.83
#Mann=4,-1,0
  4620.6    0.05       0  4994.0    0.07       0  5000.0    0.05       0
  5293.3    0.05       0
Bank Sta=4916.1,5006.1
Exp/Cntr=0.3,0.1

Type RM Length L Ch R = 1,76,0,0,0
BEGIN DESCRIPTION:
UNT 050 IN DRY CR WATERSHED 1.0
END DESCRIPTION:
XS GIS Cut Line= 3
      2923638.74      7017633.47      2923400.00      7017250.00
      2922939.15      7017183.08
#Sta/Elev= 30
  4578.4  442.26  4600.5  441.78  4623.7  440.26  4659.1  439.84  4689.0  436.44
  4704.4  435.23  4741.0  432.43  4762.2  431.74  4899.1  430.57  4965.3  430.67
  4978.2  430.52  4981.3  430.04  4987.6  429.08  4990.5  427.17  4991.0  426.37
  4996.0  426.37  4996.5  427.17  5000.7  427.32  5010.8  430.04  5014.8  431.39
  5116.0  430.48  5147.4  430.69  5186.7  430.74  5267.6  432.16  5297.9  433.79
  5345.8  438.98  5375.9  442.27  5419.2  446.00  5434.9  446.39  5495.8  449.63
#Mann=6,-1,0
  4578.4    0.05       0  4990.5    0.03       0  4996.5    0.05       0
  5147.4    0.16       0  5345.8    0.05       0  5434.9    0.16       0
Bank Sta=4981.3,5010.8
Exp/Cntr=0.3,0.1

Chan Stop Cuts=-1