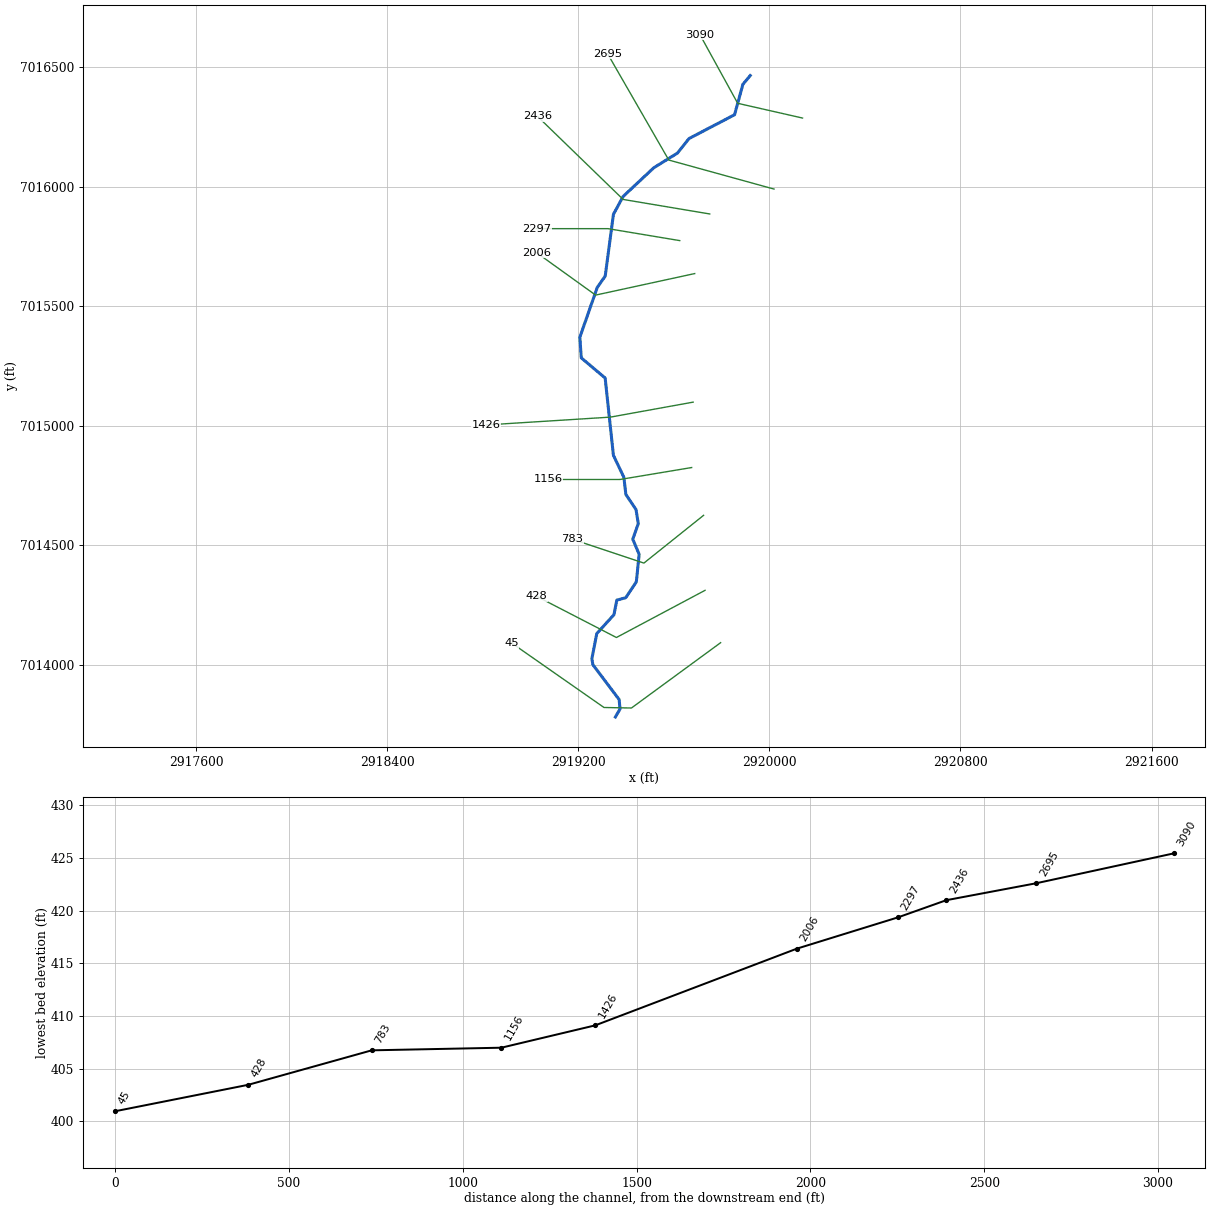
--- UNT 051 IN DRY CR WATERSHED.prj (project) ---

Proj Title=UNT 051 IN DRY CR WATERSHED Base Level Engineering
Current Plan=p01
Default Exp/Contr=0.3,0.1
English Units
Geom File=g01
Flow File=f01
Plan File=p01
BEGIN DESCRIPTION:
UNT 051 IN DRY CR WATERSHED
END DESCRIPTION:

--- UNT 051 IN DRY CR WATERSHED.p01 (plan) ---

Plan Title=Multiple Run
Short Identifier=Multiple
Geom File=g01
Flow File=f01
Subcritical Flow
K Sum by GR= 0
Std Step Tol= 0.01
Critical Tol= 0.01
Num of Std Step Trials= 20
Max Error Tol= 0.3
Flow Tol Ratio= 0.001
Split Flow NTrial= 30
Split Flow Tol= 0.02
Split Flow Ratio= 0.02
Log Output Level= 0
Friction Slope Method= 1
Unsteady Friction Slope Method= 2
Unsteady Bridges Friction Slope Method= 1
Parabolic Critical Depth
Global Vel Dist=  1 , 1 , 1
Global Log Level= 0
CheckData=True
Encroach Param= -1, 0, 0, 0
BEGIN DESCRIPTION:
Multiple Run
END DESCRIPTION:

--- UNT 051 IN DRY CR WATERSHED.f01 (steady flow) ---

Flow Title=Multiple
Number of Profiles=7
Profile Names=10-year,25-year,50-year,1pct_min,100-year,1pct_plu,500-year
River Rch & RM= UNT 051 IN DRY C,Reach-1,3090
     440     582     697     416     830    1655    1175
Boundary for River Rch & Prof#=UNT 051 IN DRY C,Reach-1,1
Up Type=0
Dn Type=3
Dn Slope=0.005
Boundary for River Rch & Prof#=UNT 051 IN DRY C,Reach-1,2
Up Type=0
Dn Type=3
Dn Slope=0.005
Boundary for River Rch & Prof#=UNT 051 IN DRY C,Reach-1,3
Up Type=0
Dn Type=3
Dn Slope=0.005
Boundary for River Rch & Prof#=UNT 051 IN DRY C,Reach-1,4
Up Type=0
Dn Type=3
Dn Slope=0.005
Boundary for River Rch & Prof#=UNT 051 IN DRY C,Reach-1,5
Up Type=0
Dn Type=3
Dn Slope=0.005
Boundary for River Rch & Prof#=UNT 051 IN DRY C,Reach-1,6
Up Type=0
Dn Type=3
Dn Slope=0.005
Boundary for River Rch & Prof#=UNT 051 IN DRY C,Reach-1,7
Up Type=0
Dn Type=3
Dn Slope=0.005

--- UNT 051 IN DRY CR WATERSHED.g01 (geometry) ---

Geom Title=Existing Conditions

River Reach=UNT 051 IN DRY C,Reach-1
Reach XY= 30
      2919920.21      7016465.86      2919889.40      7016429.12
      2919854.56      7016301.81      2919663.97      7016202.18
      2919615.50      7016141.38      2919516.14      7016079.59
      2919388.06      7015959.72      2919347.49      7015884.92
      2919313.13      7015626.46      2919279.80      7015578.97
      2919206.95      7015370.53      2919212.81      7015284.12
      2919312.81      7015199.74      2919347.39      7014876.46
      2919391.32      7014783.65      2919399.52      7014712.34
      2919441.99      7014649.10      2919451.55      7014589.99
      2919428.41      7014525.24      2919455.24      7014461.61
      2919443.35      7014346.56      2919399.02      7014280.14
      2919361.65      7014269.91      2919349.63      7014208.87
      2919277.75      7014129.85      2919257.25      7014024.73
      2919261.58      7013999.45      2919371.44      7013853.74
      2919375.09      7013814.08      2919355.59      7013780.71

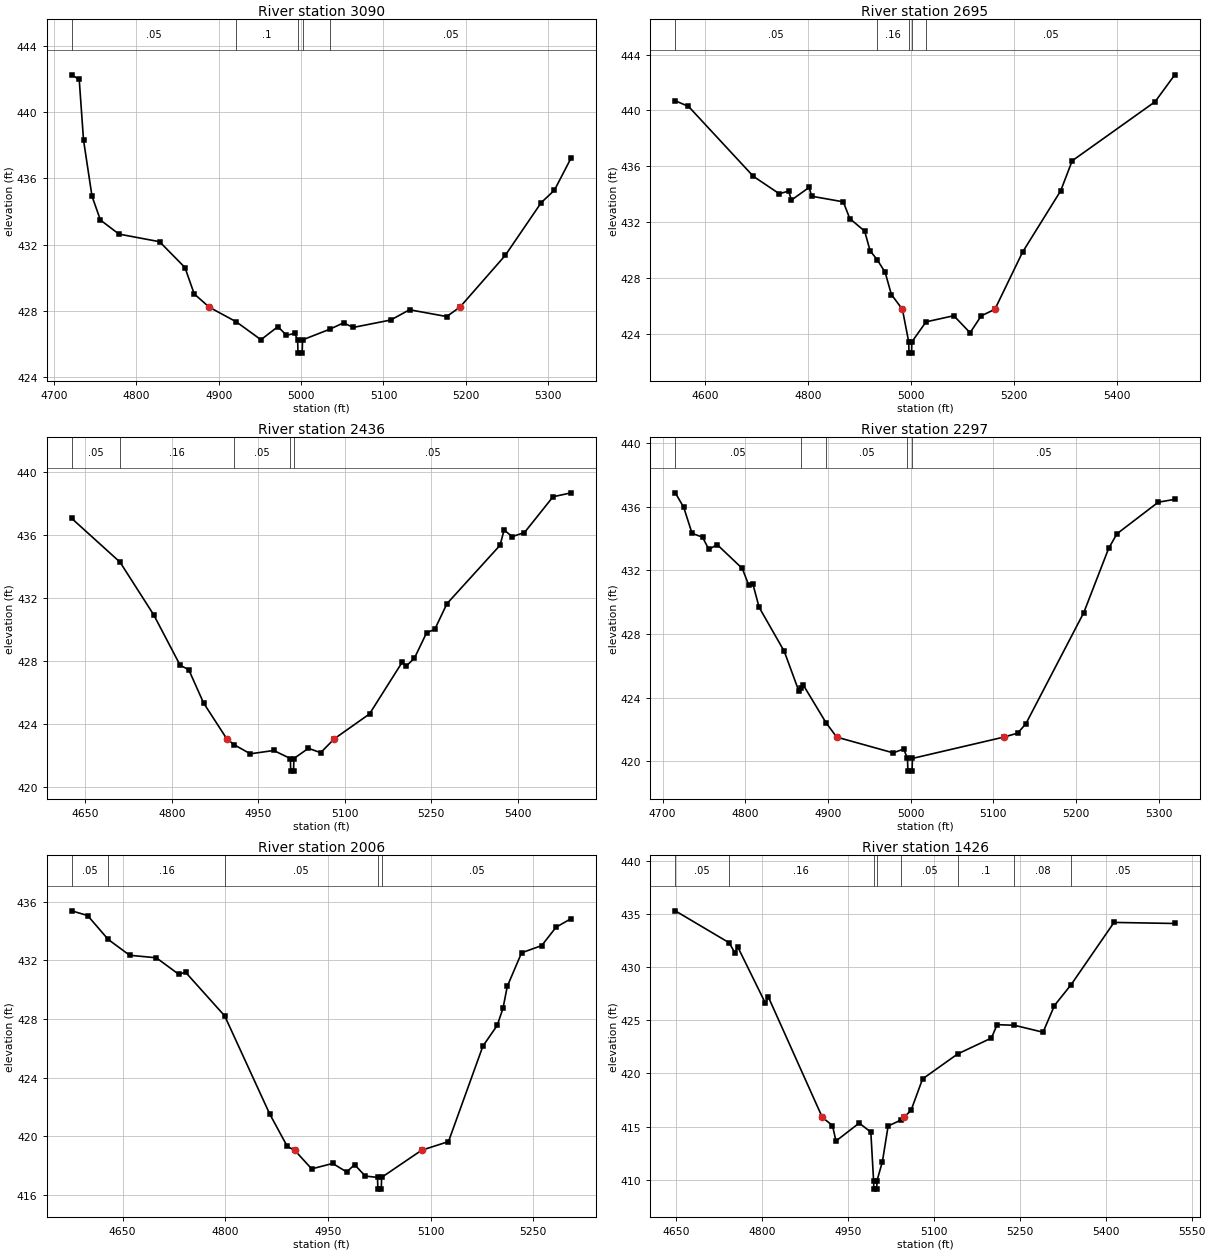
Type RM Length L Ch R = 1,3090,395,395,395
BEGIN DESCRIPTION:
UNT 051 IN DRY CR WATERSHED 7.0
END DESCRIPTION:
XS GIS Cut Line= 3
      2920139.07      7016287.97      2919867.60      7016349.70
      2919709.68      7016636.84
#Sta/Elev= 30
  4721.6  442.25  4730.8  441.97  4736.0  438.32  4746.3  434.92  4756.5  433.48
  4779.0  432.63  4828.3  432.17  4859.1  430.61  4870.3  429.02  4888.4  428.22
  4921.4  427.33  4951.3  426.25  4971.9  427.04  4982.2  426.52  4992.4  426.63
  4995.8  426.24  4996.3  425.44  5001.3  425.44  5001.8  426.24  5034.6  426.88
  5051.6  427.27  5063.1  426.99  5108.8  427.44  5131.6  428.06  5176.7  427.65
  5192.8  428.22  5247.7  431.34  5291.4  434.53  5307.4  435.28  5327.7  437.23
#Mann=5,-1,0
  4721.6    0.05       0  4921.4     0.1       0  4995.8    0.07       0
  5001.8     0.1       0  5034.6    0.05       0
Bank Sta=4888.4,5192.8
Exp/Cntr=0.3,0.1

Type RM Length L Ch R = 1,2695,259,259,259
BEGIN DESCRIPTION:
Mapping XS f5084f7e
END DESCRIPTION:
XS GIS Cut Line= 3
      2920019.68      7015990.67      2919579.19      7016112.18
      2919323.09      7016557.09
#Sta/Elev= 30
  4541.9  440.69  4567.5  440.29  4693.5  435.28  4743.9  434.03  4762.2  434.22
  4767.4  433.57  4801.8  434.48  4807.0  433.85  4868.3  433.45  4880.9  432.25
  4909.8  431.35  4920.4  429.94  4934.2  429.30  4949.6  428.40  4961.7  426.81
  4983.1  425.75  4995.4  423.41  4995.9  422.61  5000.9  422.61  5001.4  423.41
  5029.0  424.85  5083.0  425.29  5114.6  424.07  5136.2  425.28  5162.8  425.75
  5216.6  429.85  5290.6  434.24  5312.9  436.39  5473.9  440.62  5512.2  442.55
#Mann=5,-1,0
  4541.9    0.05       0  4934.2    0.16       0  4995.4    0.07       0
  5001.4    0.16       0  5029.0    0.05       0
Bank Sta=4983.1,5162.8
Exp/Cntr=0.3,0.1

Type RM Length L Ch R = 1,2436,139,139,139
BEGIN DESCRIPTION:
Mapping XS e5725a30
END DESCRIPTION:
XS GIS Cut Line= 3
      2919750.64      7015886.49      2919388.21      7015947.25
      2919030.11      7016294.50
#Sta/Elev= 30
  4626.1  437.05  4710.0  434.27  4768.5  430.92  4814.3  427.72  4829.2  427.44
  4854.9  425.33  4895.0  423.06  4907.7  422.68  4936.0  422.10  4976.6  422.31
  5005.5  421.80  5006.0  421.00  5011.0  421.00  5011.5  421.80  5036.8  422.45
  5057.9  422.17  5081.9  423.06  5142.7  424.63  5199.3  427.91  5206.5  427.67
  5220.7  428.18  5241.8  429.79  5255.9  430.00  5277.0  431.63  5369.1  435.34
  5376.1  436.31  5390.2  435.89  5411.5  436.15  5461.0  438.42  5492.4  438.67
#Mann=5,-1,0
  4626.1    0.05       0  4710.0    0.16       0  4907.7    0.05       0
  5005.5    0.03       0  5011.5    0.05       0
Bank Sta=4895,5081.9
Exp/Cntr=0.3,0.1

Type RM Length L Ch R = 1,2297,291,291,291
BEGIN DESCRIPTION:
UNT 051 IN DRY CR WATERSHED 6.0
END DESCRIPTION:
XS GIS Cut Line= 3
      2919625.03      7015774.99      2919325.00      7015825.00
      2919024.97      7015825.00
#Sta/Elev= 30
  4715.3  436.88  4725.5  435.97  4735.6  434.33  4748.3  434.09  4755.9  433.32
  4766.0  433.62  4796.4  432.12  4804.0  431.09  4809.1  431.16  4816.7  429.68
  4847.1  426.91  4864.9  424.39  4867.0  424.57  4869.9  424.81  4897.7  422.41
  4910.6  421.51  4978.9  420.52  4991.6  420.76  4996.2  420.17  4996.7  419.37
  5001.7  419.37  5002.2  420.17  5112.6  421.51  5129.5  421.76  5139.5  422.36
  5209.5  429.35  5239.5  433.38  5249.5  434.30  5299.5  436.29  5319.5  436.47
#Mann=5,-1,0
  4715.3    0.05       0  4867.0    0.16       0  4897.7    0.05       0
  4996.2    0.03       0  5002.2    0.05       0
Bank Sta=4910.6,5112.6
Exp/Cntr=0.3,0.1

Type RM Length L Ch R = 1,2006,580,580,580
BEGIN DESCRIPTION:
UNT 051 IN DRY CR WATERSHED 5.0
END DESCRIPTION:
XS GIS Cut Line= 3
      2919687.73      7015636.93      2919272.90      7015546.82
      2919024.99      7015725.01
#Sta/Elev= 30
  4575.5  435.37  4598.8  435.05  4628.9  433.42  4660.3  432.34  4699.2  432.17
  4731.8  431.05  4742.0  431.18  4799.1  428.21  4864.8  421.53  4890.6  419.31
  4901.4  419.05  4926.2  417.78  4956.9  418.15  4977.4  417.57  4988.9  418.07
  5004.5  417.29  5022.4  417.20  5022.9  416.40  5027.9  416.40  5028.4  417.20
  5086.8  419.05  5126.1  419.64  5176.4  426.15  5197.3  427.56  5205.8  428.74
  5212.0  430.22  5232.9  432.51  5262.3  433.00  5283.2  434.25  5305.3  434.84
#Mann=5,-1,0
  4575.5    0.05       0  4628.9    0.16       0  4799.1    0.05       0
  5022.4    0.03       0  5028.4    0.05       0
Bank Sta=4901.4,5086.8
Exp/Cntr=0.3,0.1

Type RM Length L Ch R = 1,1426,270,270,270
BEGIN DESCRIPTION:
UNT 051 IN DRY CR WATERSHED 4.0
END DESCRIPTION:
XS GIS Cut Line= 3
      2919681.17      7015098.73      2919334.80      7015036.03
      2918815.33      7015003.24
#Sta/Elev= 30
  4648.0  435.28  4742.1  432.28  4752.0  431.34  4757.1  431.89  4805.5  426.59
  4810.5  427.19  4904.9  415.86  4922.6  415.10  4928.7  413.64  4969.3  415.33
  4989.6  414.48  4994.4  409.92  4994.9  409.12  4999.9  409.12  5000.4  409.92
  5009.8  411.70  5019.8  415.05  5042.3  415.62  5047.2  415.86  5059.9  416.53
  5080.0  419.48  5141.4  421.83  5200.2  423.32  5210.2  424.58  5240.5  424.52
  5290.4  423.87  5310.4  426.38  5339.6  428.35  5414.4  434.19  5520.5  434.09
#Mann=8,-1,0
  4648.0    0.05       0  4742.1    0.16       0  4994.4    0.07       0
  5000.4    0.16       0  5042.3    0.05       0  5141.4     0.1       0
  5240.5    0.08       0  5339.6    0.05       0
Bank Sta=4904.9,5047.2
Exp/Cntr=0.3,0.1

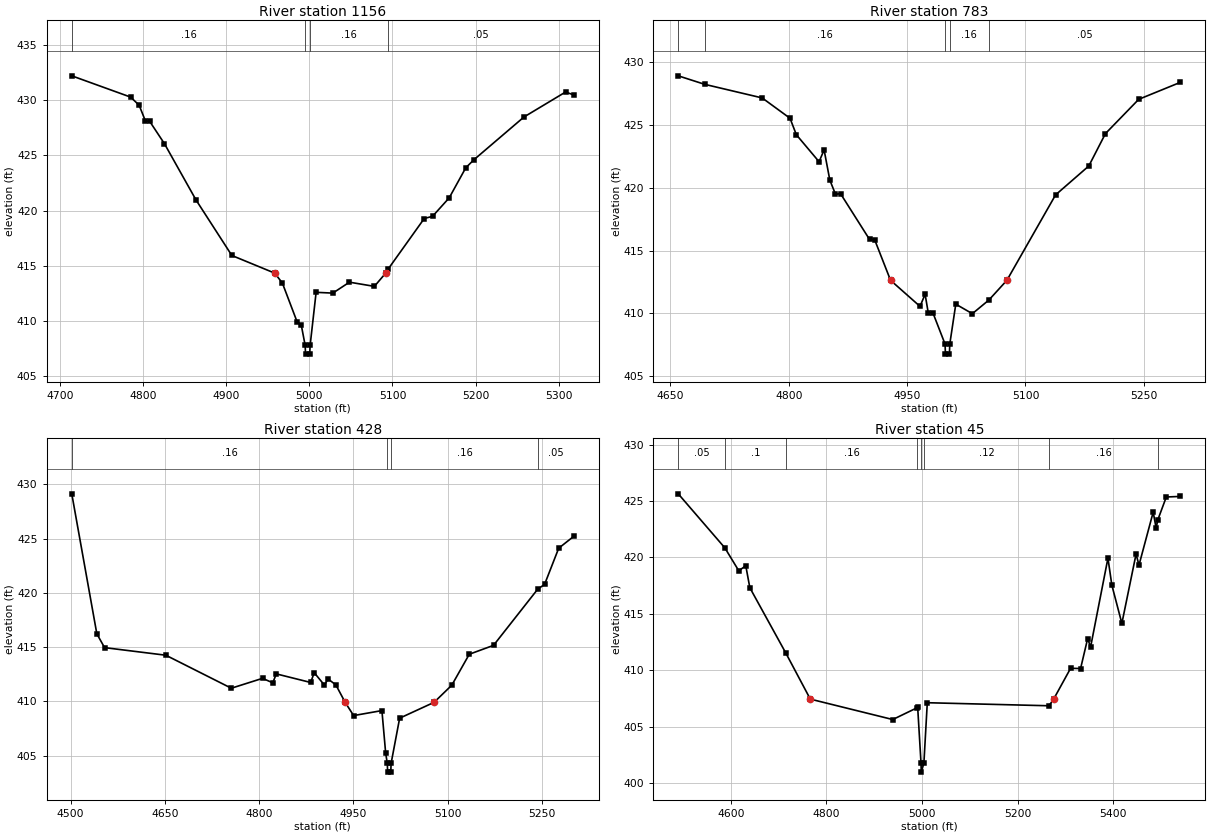
Type RM Length L Ch R = 1,1156,373,373,373
BEGIN DESCRIPTION:
UNT 051 IN DRY CR WATERSHED 3.0
END DESCRIPTION:
XS GIS Cut Line= 3
      2919674.97      7014825.00      2919375.00      7014775.00
      2919075.01      7014775.00
#Sta/Elev= 30
  4714.1  432.22  4785.0  430.29  4795.2  429.55  4802.8  428.11  4807.8  428.10
  4825.6  426.07  4863.6  420.97  4906.7  415.94  4958.3  414.34  4967.5  413.44
  4985.3  409.91  4990.3  409.61  4994.9  407.80  4995.4  407.00  5000.4  407.00
  5000.9  407.80  5008.1  412.60  5028.2  412.53  5048.2  413.52  5078.2  413.14
  5091.8  414.34  5094.7  414.70  5138.2  419.29  5148.2  419.49  5168.2  421.16
  5188.2  423.89  5198.2  424.63  5258.2  428.49  5308.2  430.75  5318.2  430.49
#Mann=4,-1,0
  4714.1    0.16       0  4994.9    0.07       0  5000.9    0.16       0
  5094.7    0.05       0
Bank Sta=4958.3,5091.8
Exp/Cntr=0.3,0.1

Type RM Length L Ch R = 1,783,355,355,355
BEGIN DESCRIPTION:
UNT 051 IN DRY CR WATERSHED 2.0
END DESCRIPTION:
XS GIS Cut Line= 3
      2919724.99      7014624.99      2919475.00      7014425.00
      2919174.97      7014525.01
#Sta/Elev= 30
  4659.9  428.91  4693.6  428.23  4766.3  427.15  4801.6  425.53  4809.6  424.22
  4838.4  422.07  4844.8  423.01  4852.0  420.62  4859.2  419.48  4865.6  419.53
  4902.4  415.88  4908.8  415.87  4929.0  412.63  4966.4  410.55  4972.8  411.52
  4976.8  410.04  4982.7  410.04  4998.1  407.55  4998.6  406.75  5003.6  406.75
  5004.1  407.55  5011.7  410.73  5032.7  409.97  5053.7  411.06  5076.5  412.63
  5138.2  419.43  5180.3  421.73  5201.4  424.31  5243.6  427.04  5296.3  428.39
#Mann=5,-1,0
  4659.9    0.05       0  4693.6    0.16       0  4998.1    0.07       0
  5004.1    0.16       0  5053.7    0.05       0
Bank Sta=4929,5076.5
Exp/Cntr=0.3,0.1

Type RM Length L Ch R = 1,428,383,383,383
BEGIN DESCRIPTION:
Mapping XS cea89e68
END DESCRIPTION:
XS GIS Cut Line= 3
      2919731.06      7014310.95      2919360.00      7014113.48
      2919023.59      7014287.12
#Sta/Elev= 30
  4502.0  429.12  4541.9  416.22  4554.2  414.95  4651.7  414.25  4755.9  411.21
  4805.5  412.12  4821.8  411.71  4827.5  412.53  4882.1  411.74  4887.8  412.64
  4904.1  411.49  4909.7  412.07  4922.3  411.51  4937.0  409.91  4950.5  408.69
  4995.5  409.15  5001.5  405.21  5004.1  404.28  5004.6  403.48  5009.6  403.48
  5010.1  404.28  5023.7  408.45  5078.5  409.91  5106.7  411.49  5134.5  414.34
  5173.1  415.16  5243.6  420.35  5254.3  420.77  5276.8  424.11  5300.9  425.21
#Mann=4,-1,0
  4502.0    0.16       0  5004.1    0.07       0  5010.1    0.16       0
  5243.6    0.05       0
Bank Sta=4937,5078.5
Exp/Cntr=0.3,0.1

Type RM Length L Ch R = 1,45,0,0,0
BEGIN DESCRIPTION:
UNT 051 IN DRY CR WATERSHED 1.0
END DESCRIPTION:
XS GIS Cut Line= 4
      2919796.20      7014091.78      2919422.94      7013818.35
      2919307.92      7013820.52      2918920.97      7014090.73
#Sta/Elev= 30
  4490.2  425.63  4587.7  420.84  4616.8  418.81  4631.4  419.26  4639.9  417.31
  4715.4  411.50  4766.3  407.44  4938.7  405.63  4989.4  406.67  4990.8  406.72
  4997.8  401.77  4998.3  400.97  5003.8  401.77  5010.9  407.12  5265.4  406.85
  5275.1  407.44  5310.5  410.17  5331.4  410.15  5346.2  412.81  5352.3  412.05
  5388.6  419.93  5396.8  417.53  5417.7  414.15  5447.4  420.29  5453.5  419.31
  5483.2  424.01  5489.3  422.60  5493.0  423.34  5510.6  425.35  5539.9  425.40
#Mann=8,-1,0
  4490.2    0.05       0  4587.7     0.1       0  4715.4    0.16       0
  4989.4    0.12       0  4997.8    0.07       0  5003.8    0.12       0
  5265.4    0.16       0  5493.0    0.05       0
Bank Sta=4766.3,5275.1
Exp/Cntr=0.3,0.1

Chan Stop Cuts=-1