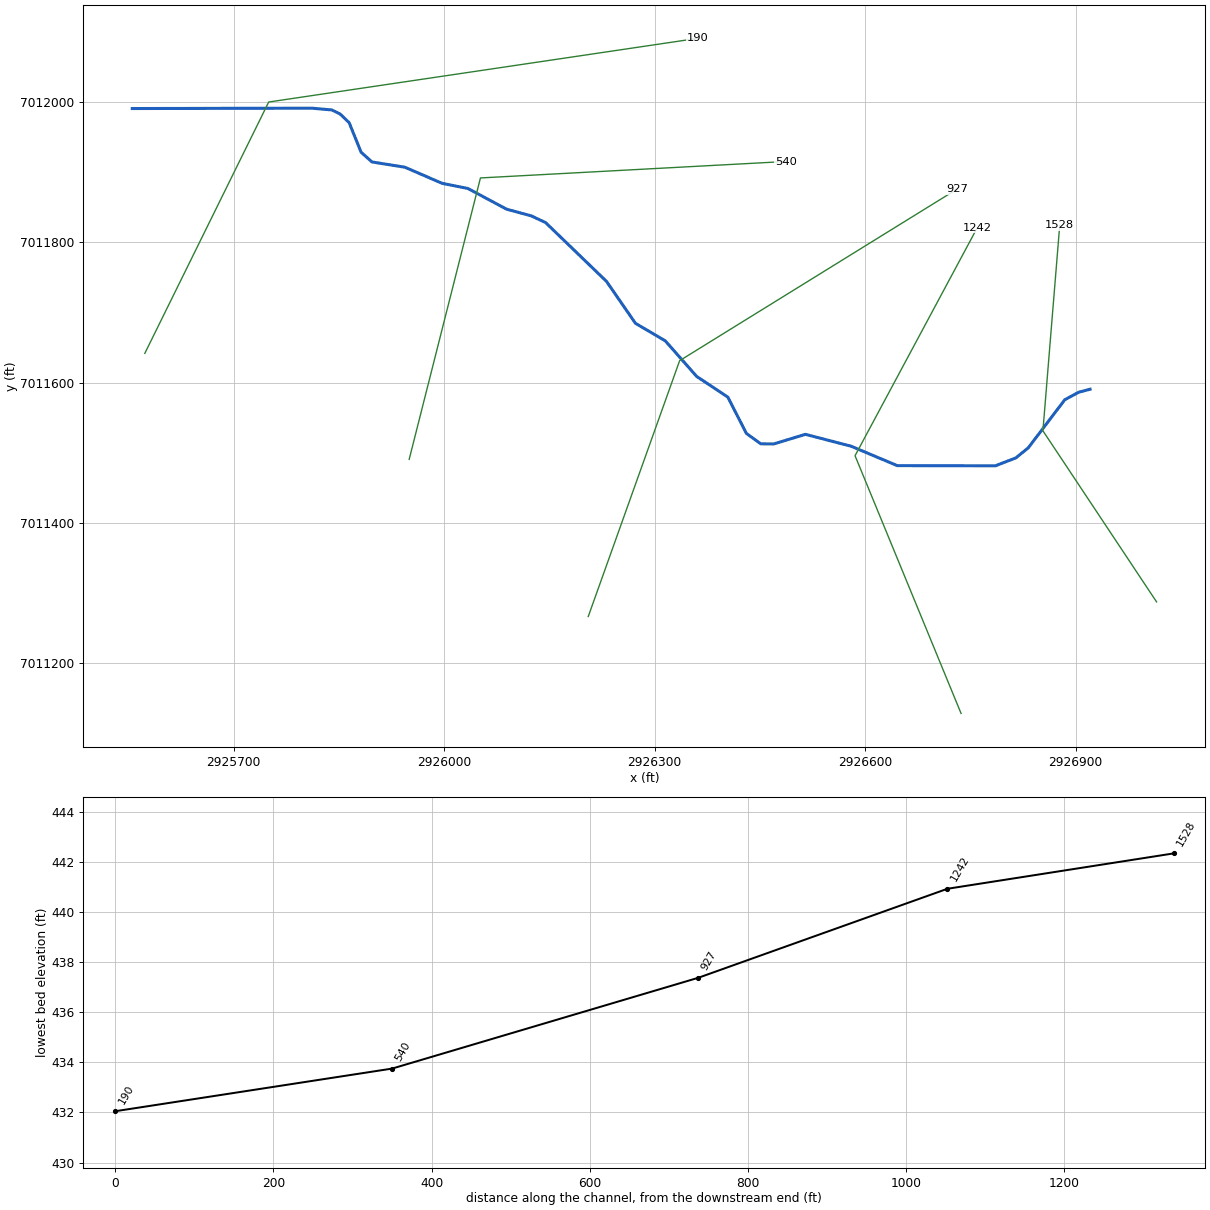
--- UNT 052 IN DRY CR WATERSHED.prj (project) ---

Proj Title=UNT 052 IN DRY CR WATERSHED Base Level Engineering
Current Plan=p01
Default Exp/Contr=0.3,0.1
English Units
Geom File=g01
Flow File=f01
Plan File=p01
BEGIN DESCRIPTION:
UNT 052 IN DRY CR WATERSHED
END DESCRIPTION:

--- UNT 052 IN DRY CR WATERSHED.p01 (plan) ---

Plan Title=Multiple Run
Short Identifier=Multiple
Geom File=g01
Flow File=f01
Subcritical Flow
K Sum by GR= 0
Std Step Tol= 0.01
Critical Tol= 0.01
Num of Std Step Trials= 20
Max Error Tol= 0.3
Flow Tol Ratio= 0.001
Split Flow NTrial= 30
Split Flow Tol= 0.02
Split Flow Ratio= 0.02
Log Output Level= 0
Friction Slope Method= 1
Unsteady Friction Slope Method= 2
Unsteady Bridges Friction Slope Method= 1
Parabolic Critical Depth
Global Vel Dist=  1 , 1 , 1
Global Log Level= 0
CheckData=True
Encroach Param= -1, 0, 0, 0
BEGIN DESCRIPTION:
Multiple Run
END DESCRIPTION:

--- UNT 052 IN DRY CR WATERSHED.f01 (steady flow) ---

Flow Title=Multiple
Number of Profiles=7
Profile Names=10-year,25-year,50-year,1pct_min,100-year,1pct_plu,500-year
River Rch & RM= UNT 052 IN DRY C,Reach-1,1528
     168     209     240     138     275     549     361
Boundary for River Rch & Prof#=UNT 052 IN DRY C,Reach-1,1
Up Type=0
Dn Type=3
Dn Slope=0.005
Boundary for River Rch & Prof#=UNT 052 IN DRY C,Reach-1,2
Up Type=0
Dn Type=3
Dn Slope=0.005
Boundary for River Rch & Prof#=UNT 052 IN DRY C,Reach-1,3
Up Type=0
Dn Type=3
Dn Slope=0.005
Boundary for River Rch & Prof#=UNT 052 IN DRY C,Reach-1,4
Up Type=0
Dn Type=3
Dn Slope=0.005
Boundary for River Rch & Prof#=UNT 052 IN DRY C,Reach-1,5
Up Type=0
Dn Type=3
Dn Slope=0.005
Boundary for River Rch & Prof#=UNT 052 IN DRY C,Reach-1,6
Up Type=0
Dn Type=3
Dn Slope=0.005
Boundary for River Rch & Prof#=UNT 052 IN DRY C,Reach-1,7
Up Type=0
Dn Type=3
Dn Slope=0.005

--- UNT 052 IN DRY CR WATERSHED.g01 (geometry) ---

Geom Title=Existing Conditions

River Reach=UNT 052 IN DRY C,Reach-1
Reach XY= 30
      2926920.59      7011590.71      2926904.27      7011586.39
      2926884.46      7011575.68      2926832.42      7011507.12
      2926814.80      7011492.87      2926785.58      7011481.55
      2926645.76      7011481.84      2926580.00      7011509.49
      2926514.84      7011526.42      2926469.47      7011512.64
      2926451.30      7011512.91      2926430.72      7011527.77
      2926404.33      7011579.48      2926360.02      7011608.84
      2926315.15      7011659.67      2926272.66      7011684.65
      2926231.45      7011744.33      2926144.56      7011828.22
      2926124.34      7011837.69      2926088.91      7011847.35
      2926033.95      7011876.75      2925997.02      7011884.18
      2925943.99      7011907.12      2925897.16      7011914.58
      2925881.58      7011928.56      2925864.71      7011970.50
      2925851.90      7011982.86      2925840.06      7011988.69
      2925811.52      7011991.24      2925555.59      7011990.71

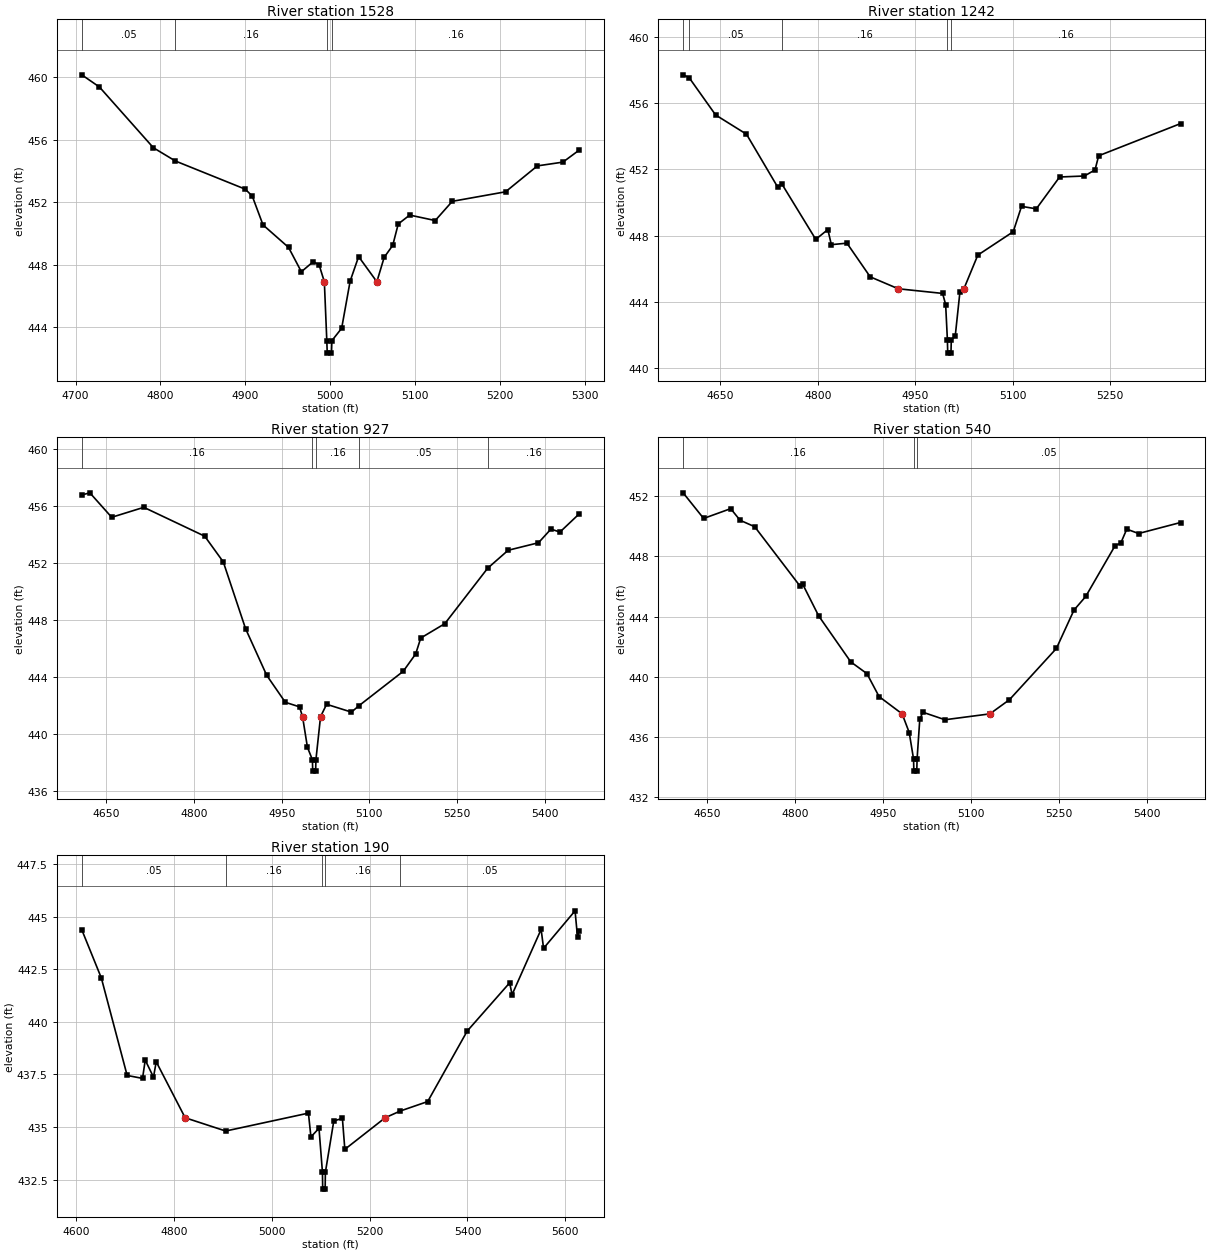
Type RM Length L Ch R = 1,1528,286,286,286
BEGIN DESCRIPTION:
UNT 052 IN DRY CR WATERSHED 2.0
END DESCRIPTION:
XS GIS Cut Line= 3
      2927015.29      7011287.65      2926853.34      7011531.46
      2926877.28      7011824.09
#Sta/Elev= 30
  4707.3  460.15  4728.1  459.37  4791.7  455.48  4817.7  454.63  4899.9  452.83
  4908.2  452.39  4920.9  450.54  4951.0  449.10  4966.1  447.54  4980.2  448.19
  4987.1  447.97  4993.2  446.90  4996.1  443.13  4996.6  442.33  5001.6  442.33
  5002.1  443.13  5013.6  443.92  5023.6  446.94  5033.6  448.51  5055.1  446.90
  5063.7  448.46  5073.8  449.23  5080.3  450.60  5093.8  451.17  5123.9  450.82
  5144.0  452.05  5206.8  452.66  5244.3  454.32  5274.4  454.56  5293.6  455.33
#Mann=4,-1,0
  4707.3    0.05       0  4817.7    0.16       0  4996.1    0.07       0
  5002.1    0.16       0
Bank Sta=4993.2,5055.1
Exp/Cntr=0.3,0.1

Type RM Length L Ch R = 1,1242,315,315,315
BEGIN DESCRIPTION:
Mapping XS b95a4bfe
END DESCRIPTION:
XS GIS Cut Line= 3
      2926736.66      7011128.76      2926585.61      7011495.96
      2926759.67      7011820.70
#Sta/Elev= 30
  4592.5  457.70  4601.7  457.53  4642.5  455.28  4690.0  454.12  4737.9  450.94
  4744.9  451.09  4796.6  447.78  4815.2  448.37  4820.6  447.46  4844.6  447.55
  4880.4  445.52  4923.6  444.80  4991.8  444.52  4996.5  443.85  4999.2  441.72
  4999.7  440.92  5004.7  440.92  5005.2  441.72  5011.2  441.93  5018.4  444.58
  5024.6  444.80  5046.0  446.83  5100.5  448.24  5113.3  449.77  5136.0  449.62
  5171.9  451.54  5210.1  451.60  5226.4  451.97  5232.0  452.82  5358.0  454.76
#Mann=5,-1,0
  4592.5     0.1       0  4601.7    0.05       0  4744.9    0.16       0
  4999.2    0.07       0  5005.2    0.16       0
Bank Sta=4923.6,5024.6
Exp/Cntr=0.3,0.1

Type RM Length L Ch R = 1,927,387,387,387
BEGIN DESCRIPTION:
Mapping XS 9b25e111
END DESCRIPTION:
XS GIS Cut Line= 3
      2926205.40      7011266.80      2926335.61      7011631.38
      2926730.72      7011875.73
#Sta/Elev= 30
  4607.7  456.79  4621.5  456.94  4658.9  455.22  4713.9  455.92  4818.2  453.89
  4850.0  452.08  4888.1  447.39  4924.3  444.11  4956.2  442.21  4980.5  441.89
  4985.7  441.20  4994.1  439.04  5002.6  438.17  5003.1  437.37  5008.1  437.37
  5008.6  438.17  5016.5  441.20  5026.9  442.07  5069.4  441.52  5082.6  441.98
  5158.1  444.39  5179.4  445.61  5188.1  446.73  5229.3  447.74  5302.7  451.64
  5337.7  452.90  5389.7  453.43  5411.0  454.39  5426.4  454.18  5459.4  455.46
#Mann=5,-1,0
  4607.7    0.16       0  5002.6    0.07       0  5008.6    0.16       0
  5082.6    0.05       0  5302.7    0.16       0
Bank Sta=4985.7,5016.5
Exp/Cntr=0.3,0.1

Type RM Length L Ch R = 1,540,350,350,350
BEGIN DESCRIPTION:
Mapping XS cc9f00ee
END DESCRIPTION:
XS GIS Cut Line= 3
      2925950.20      7011490.78      2926051.76      7011891.80
      2926486.64      7011915.23
#Sta/Elev= 30
  4608.9  452.22  4643.9  450.52  4690.1  451.17  4706.1  450.40  4731.1  449.97
  4807.9  446.06  4813.1  446.15  4840.2  444.06  4895.1  441.00  4922.7  440.22
  4943.4  438.70  4982.8  437.55  4994.9  436.31  5002.3  434.55  5002.8  433.75
  5007.8  433.75  5008.3  434.55  5012.9  437.18  5018.1  437.66  5055.9  437.16
  5132.6  437.55  5166.0  438.49  5246.1  441.89  5276.2  444.44  5296.2  445.34
  5346.3  448.71  5356.1  448.89  5366.3  449.81  5386.4  449.52  5458.1  450.25
#Mann=3,-1,0
  4608.9    0.16       0  5002.3    0.07       0  5008.3    0.05       0
Bank Sta=4982.8,5132.6
Exp/Cntr=0.3,0.1

Type RM Length L Ch R = 1,190,0,0,0
BEGIN DESCRIPTION:
UNT 052 IN DRY CR WATERSHED 1.0
END DESCRIPTION:
XS GIS Cut Line= 3
      2925573.45      7011641.79      2925750.00      7012000.00
      2926361.65      7012090.76
#Sta/Elev= 30
  4610.9  444.37  4650.9  442.08  4703.7  437.45  4735.2  437.31  4740.7  438.18
  4757.6  437.37  4763.2  438.10  4822.4  435.44  4905.3  434.81  5074.6  435.66
  5079.7  434.53  5096.2  434.94  5103.3  432.85  5103.8  432.05  5108.8  432.05
  5109.3  432.85  5126.5  435.29  5144.1  435.41  5149.1  433.94  5231.6  435.44
  5262.4  435.76  5318.6  436.21  5399.5  439.56  5486.3  441.85  5491.3  441.29
  5550.7  444.39  5555.7  443.49  5620.1  445.27  5625.2  444.01  5628.6  444.33
#Mann=5,-1,0
  4610.9    0.05       0  4905.3    0.16       0  5103.3    0.07       0
  5109.3    0.16       0  5262.4    0.05       0
Bank Sta=4822.4,5231.6
Exp/Cntr=0.3,0.1

Chan Stop Cuts=-1