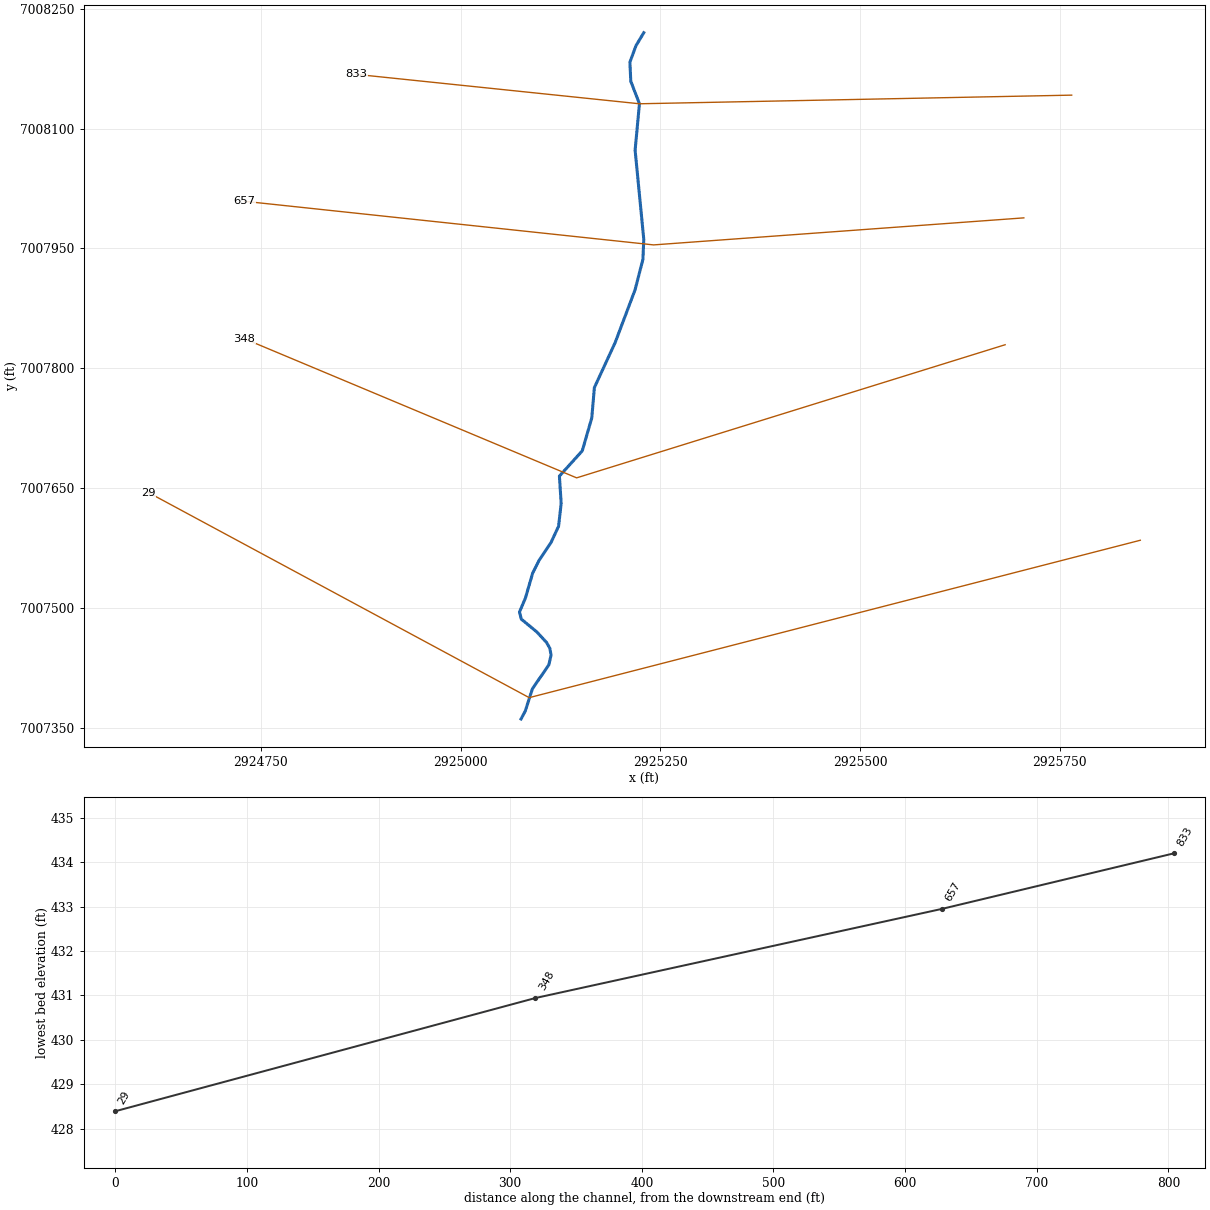
--- UNT 053 IN DRY CR WATERSHED.prj (project) ---

Proj Title=UNT 053 IN DRY CR WATERSHED Base Level Engineering
Current Plan=p01
Default Exp/Contr=0.3,0.1
English Units
Geom File=g01
Flow File=f01
Plan File=p01
BEGIN DESCRIPTION:
UNT 053 IN DRY CR WATERSHED
END DESCRIPTION:

--- UNT 053 IN DRY CR WATERSHED.p01 (plan) ---

Plan Title=Multiple Run
Short Identifier=Multiple
Geom File=g01
Flow File=f01
Subcritical Flow
K Sum by GR= 0
Std Step Tol= 0.01
Critical Tol= 0.01
Num of Std Step Trials= 20
Max Error Tol= 0.3
Flow Tol Ratio= 0.001
Split Flow NTrial= 30
Split Flow Tol= 0.02
Split Flow Ratio= 0.02
Log Output Level= 0
Friction Slope Method= 1
Unsteady Friction Slope Method= 2
Unsteady Bridges Friction Slope Method= 1
Parabolic Critical Depth
Global Vel Dist=  1 , 1 , 1
Global Log Level= 0
CheckData=True
Encroach Param= -1, 0, 0, 0
BEGIN DESCRIPTION:
Multiple Run
END DESCRIPTION:

--- UNT 053 IN DRY CR WATERSHED.f01 (steady flow) ---

Flow Title=Multiple
Number of Profiles=7
Profile Names=10-year,25-year,50-year,1pct_min,100-year,1pct_plu,500-year
River Rch & RM= UNT 053 IN DRY C,Reach-1,833
     321     416     490     288     575    1148     792
Boundary for River Rch & Prof#=UNT 053 IN DRY C,Reach-1,1
Up Type=0
Dn Type=3
Dn Slope=0.005
Boundary for River Rch & Prof#=UNT 053 IN DRY C,Reach-1,2
Up Type=0
Dn Type=3
Dn Slope=0.005
Boundary for River Rch & Prof#=UNT 053 IN DRY C,Reach-1,3
Up Type=0
Dn Type=3
Dn Slope=0.005
Boundary for River Rch & Prof#=UNT 053 IN DRY C,Reach-1,4
Up Type=0
Dn Type=3
Dn Slope=0.005
Boundary for River Rch & Prof#=UNT 053 IN DRY C,Reach-1,5
Up Type=0
Dn Type=3
Dn Slope=0.005
Boundary for River Rch & Prof#=UNT 053 IN DRY C,Reach-1,6
Up Type=0
Dn Type=3
Dn Slope=0.005
Boundary for River Rch & Prof#=UNT 053 IN DRY C,Reach-1,7
Up Type=0
Dn Type=3
Dn Slope=0.005

--- UNT 053 IN DRY CR WATERSHED.g01 (geometry) ---

Geom Title=Existing Conditions

River Reach=UNT 053 IN DRY C,Reach-1
Reach XY= 30
      2925229.27      7008219.98      2925219.50      7008203.70
      2925211.91      7008183.09      2925212.99      7008159.21
      2925223.84      7008131.00      2925218.42      7008072.95
      2925229.27      7007961.19      2925228.18      7007936.23
      2925218.42      7007898.25      2925193.46      7007832.07
      2925167.42      7007775.64      2925164.16      7007737.66
      2925152.23      7007696.43      2925123.64      7007664.83
      2925125.84      7007630.68      2925122.59      7007602.02
      2925113.14      7007581.71      2925098.22      7007559.47
      2925090.10      7007543.24      2925081.12      7007512.22
      2925073.62      7007494.56      2925076.03      7007485.70
      2925095.16      7007469.90      2925107.40      7007456.78
      2925111.55      7007449.41      2925113.20      7007440.95
      2925110.48      7007428.57      2925089.93      7007398.73
      2925080.80      7007370.47      2925075.59      7007360.71

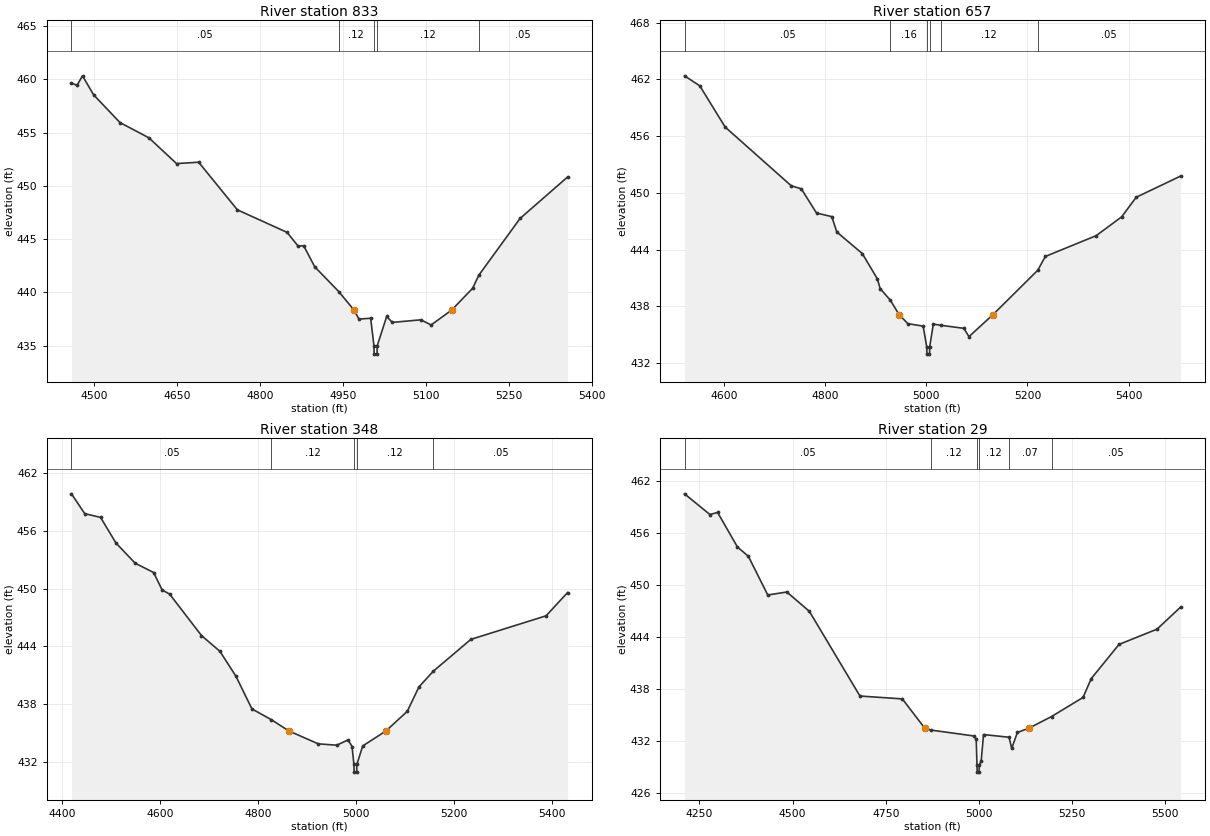
Type RM Length L Ch R = 1,833,176,176,176
BEGIN DESCRIPTION:
UNT 053 IN DRY CR WATERSHED 2.0
END DESCRIPTION:
XS GIS Cut Line= 3
      2925765.03      7008141.81      2925223.84      7008131.00
      2924869.55      7008167.81
#Sta/Elev= 30
  4458.7  459.65  4468.7  459.44  4478.7  460.33  4498.7  458.55  4546.5  455.94
  4598.8  454.51  4648.8  452.09  4688.8  452.22  4758.8  447.75  4848.8  445.63
  4868.8  444.34  4878.8  444.38  4898.8  442.40  4942.1  440.08  4969.8  438.34
  4978.8  437.49  5000.0  437.57  5005.9  435.00  5006.4  434.20  5011.4  434.20
  5011.9  435.00  5029.0  437.74  5039.1  437.18  5090.7  437.42  5109.4  436.94
  5146.6  438.34  5184.4  440.38  5195.5  441.60  5270.3  446.94  5356.2  450.83
#Mann=5,-1,0
  4458.7    0.05       0  4942.1    0.12       0  5005.9    0.07       0
  5011.9    0.12       0  5195.5    0.05       0
Bank Sta=4969.8,5146.6
Exp/Cntr=0.3,0.1

Type RM Length L Ch R = 1,657,309,309,309
BEGIN DESCRIPTION:
Mapping XS 521b7719
END DESCRIPTION:
XS GIS Cut Line= 3
      2925705.12      7007988.16      2925241.56      7007954.30
      2924729.26      7008008.92
#Sta/Elev= 30
  4522.6  462.38  4552.8  461.32  4602.9  456.96  4733.3  450.76  4753.3  450.43
  4783.4  447.87  4813.5  447.49  4823.5  445.86  4873.7  443.59  4903.7  440.90
  4909.0  439.89  4929.4  438.64  4946.7  437.11  4963.9  436.17  4994.0  435.91
  5001.0  433.75  5001.5  432.95  5006.5  432.95  5007.0  433.75  5014.1  436.13
  5028.8  436.00  5074.4  435.68  5084.5  434.80  5131.6  437.11  5220.4  441.82
  5235.4  443.28  5335.9  445.48  5386.2  447.47  5414.9  449.54  5502.6  451.78
#Mann=6,-1,0
  4522.6    0.05       0  4929.4    0.16       0  5001.0    0.07       0
  5007.0    0.16       0  5028.8    0.12       0  5220.4    0.05       0
Bank Sta=4946.7,5131.6
Exp/Cntr=0.3,0.1

Type RM Length L Ch R = 1,348,319,319,319
BEGIN DESCRIPTION:
Mapping XS 31823bc5
END DESCRIPTION:
XS GIS Cut Line= 3
      2925681.69      7007829.31      2925145.20      7007662.64
      2924729.28      7007836.80
#Sta/Elev= 30
  4419.7  459.87  4446.8  457.81  4479.1  457.42  4510.5  454.76  4549.7  452.66
  4587.5  451.69  4604.7  449.88  4620.0  449.45  4685.1  445.14  4722.9  443.49
  4755.5  440.90  4788.1  437.51  4827.8  436.39  4863.6  435.22  4923.5  433.88
  4961.3  433.74  4984.3  434.29  4992.5  433.60  4996.3  431.74  4996.8  430.94
  5001.8  430.94  5002.3  431.74  5014.2  433.66  5061.6  435.22  5105.2  437.26
  5129.0  439.80  5158.5  441.44  5235.0  444.74  5388.6  447.19  5432.4  449.61
#Mann=5,-1,0
  4419.7    0.05       0  4827.8    0.12       0  4996.3    0.07       0
  5002.3    0.12       0  5158.5    0.05       0
Bank Sta=4863.6,5061.6
Exp/Cntr=0.3,0.1

Type RM Length L Ch R = 1,29,0,0,0
BEGIN DESCRIPTION:
UNT 053 IN DRY CR WATERSHED 1.0
END DESCRIPTION:
XS GIS Cut Line= 3
      2925850.95      7007584.52      2925085.82      7007387.45
      2924609.34      7007644.09
#Sta/Elev= 30
  4209.9  460.54  4278.0  458.15  4298.7  458.39  4351.9  454.40  4381.3  453.32
  4433.3  448.85  4484.5  449.20  4545.0  446.96  4680.7  437.18  4794.4  436.85
  4854.6  433.47  4870.8  433.25  4987.6  432.56  4992.7  432.19  4994.8  429.19
  4995.3  428.39  5000.3  428.39  5000.8  429.19  5006.0  429.66  5012.3  432.73
  5080.8  432.42  5087.9  431.13  5103.2  432.97  5134.2  433.47  5194.8  434.81
  5279.4  437.02  5301.3  439.19  5375.8  443.14  5478.0  444.91  5541.2  447.46
#Mann=6,-1,0
  4209.9    0.05       0  4870.8    0.12       0  4994.8    0.07       0
  5000.8    0.12       0  5080.8    0.07       0  5194.8    0.05       0
Bank Sta=4854.6,5134.2
Exp/Cntr=0.3,0.1

Chan Stop Cuts=-1