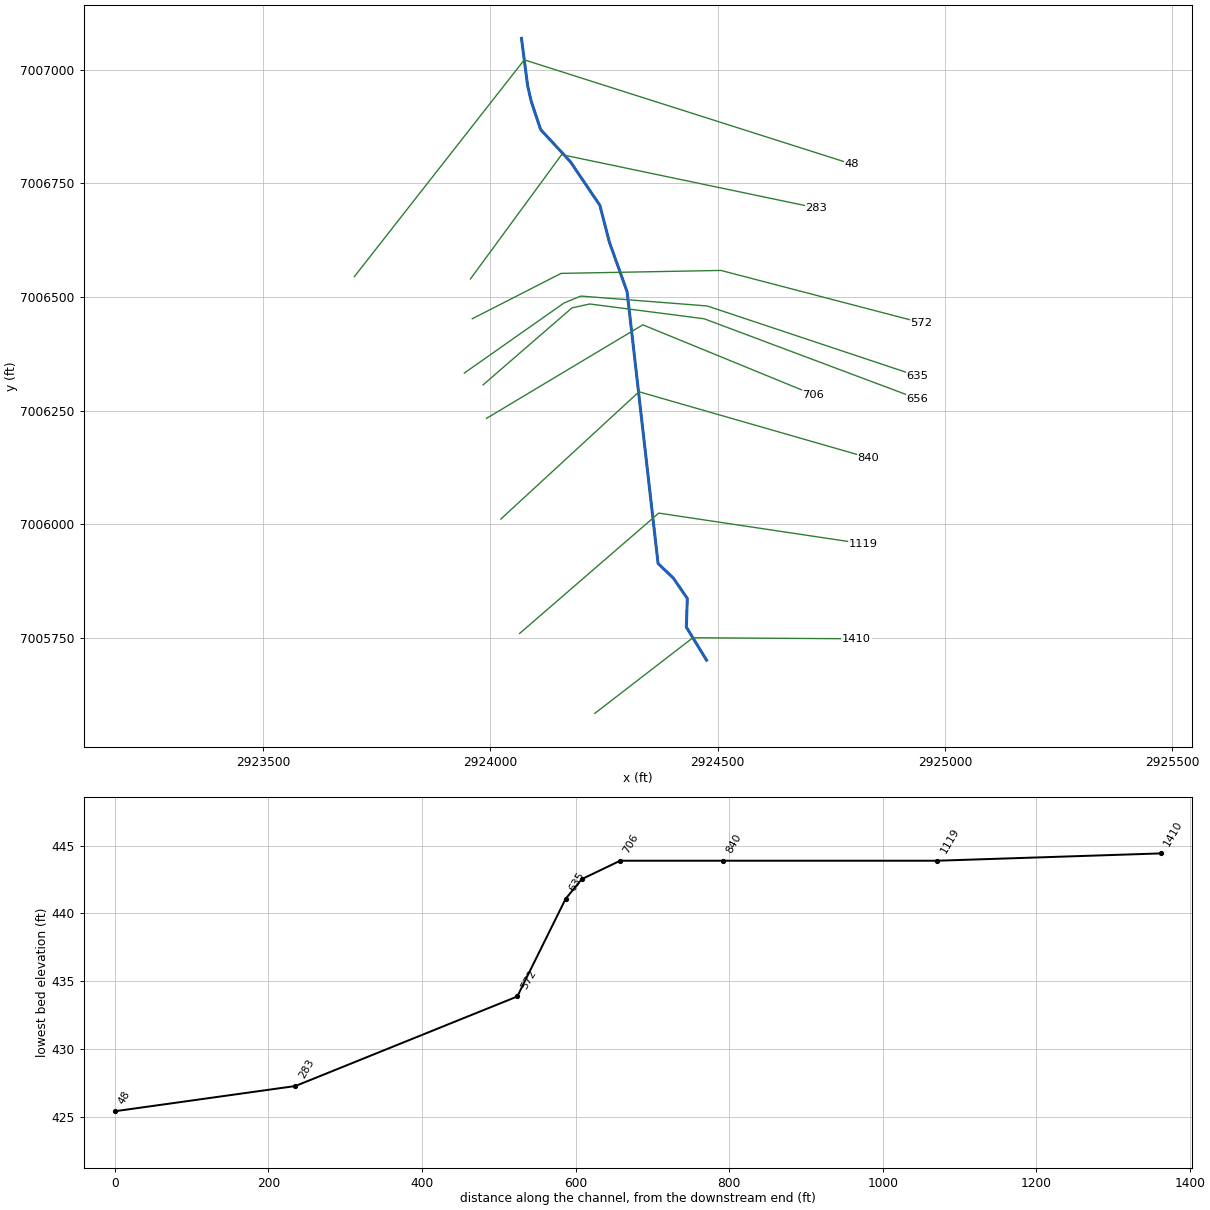
--- UNT 054 IN DRY CR WATERSHED.prj (project) ---

Proj Title=UNT 054 IN DRY CR WATERSHED Base Level Engineering
Current Plan=p01
Default Exp/Contr=0.3,0.1
English Units
Geom File=g01
Flow File=f01
Plan File=p01
BEGIN DESCRIPTION:
UNT 054 IN DRY CR WATERSHED
END DESCRIPTION:

--- UNT 054 IN DRY CR WATERSHED.p01 (plan) ---

Plan Title=Multiple Run
Short Identifier=Multiple
Geom File=g01
Flow File=f01
Subcritical Flow
K Sum by GR= 0
Std Step Tol= 0.01
Critical Tol= 0.01
Num of Std Step Trials= 20
Max Error Tol= 0.3
Flow Tol Ratio= 0.001
Split Flow NTrial= 30
Split Flow Tol= 0.02
Split Flow Ratio= 0.02
Log Output Level= 0
Friction Slope Method= 1
Unsteady Friction Slope Method= 2
Unsteady Bridges Friction Slope Method= 1
Parabolic Critical Depth
Global Vel Dist=  1 , 1 , 1
Global Log Level= 0
CheckData=True
Encroach Param= -1, 0, 0, 0
BEGIN DESCRIPTION:
Multiple Run
END DESCRIPTION:

--- UNT 054 IN DRY CR WATERSHED.f01 (steady flow) ---

Flow Title=Multiple
Number of Profiles=7
Profile Names=10-year,25-year,50-year,1pct_min,100-year,1pct_plu,500-year
River Rch & RM= UNT 054 IN DRY C,Reach-1,1410
     127     155     176     100     201     400     257
Boundary for River Rch & Prof#=UNT 054 IN DRY C,Reach-1,1
Up Type=0
Dn Type=3
Dn Slope=0.005
Boundary for River Rch & Prof#=UNT 054 IN DRY C,Reach-1,2
Up Type=0
Dn Type=3
Dn Slope=0.005
Boundary for River Rch & Prof#=UNT 054 IN DRY C,Reach-1,3
Up Type=0
Dn Type=3
Dn Slope=0.005
Boundary for River Rch & Prof#=UNT 054 IN DRY C,Reach-1,4
Up Type=0
Dn Type=3
Dn Slope=0.005
Boundary for River Rch & Prof#=UNT 054 IN DRY C,Reach-1,5
Up Type=0
Dn Type=3
Dn Slope=0.005
Boundary for River Rch & Prof#=UNT 054 IN DRY C,Reach-1,6
Up Type=0
Dn Type=3
Dn Slope=0.005
Boundary for River Rch & Prof#=UNT 054 IN DRY C,Reach-1,7
Up Type=0
Dn Type=3
Dn Slope=0.005

--- UNT 054 IN DRY CR WATERSHED.g01 (geometry) ---

Geom Title=Existing Conditions

River Reach=UNT 054 IN DRY C,Reach-1
Reach XY= 13
      2924475.58      7005701.22      2924431.10      7005773.92
      2924433.27      7005836.86      2924402.89      7005881.34
      2924368.96      7005913.99      2924300.87      7006511.66
      2924261.80      7006621.04      2924240.97      7006701.77
      2924175.87      7006798.12      2924110.76      7006868.43
      2924089.93      7006930.93      2924082.12      7006964.79
      2924068.56      7007069.16

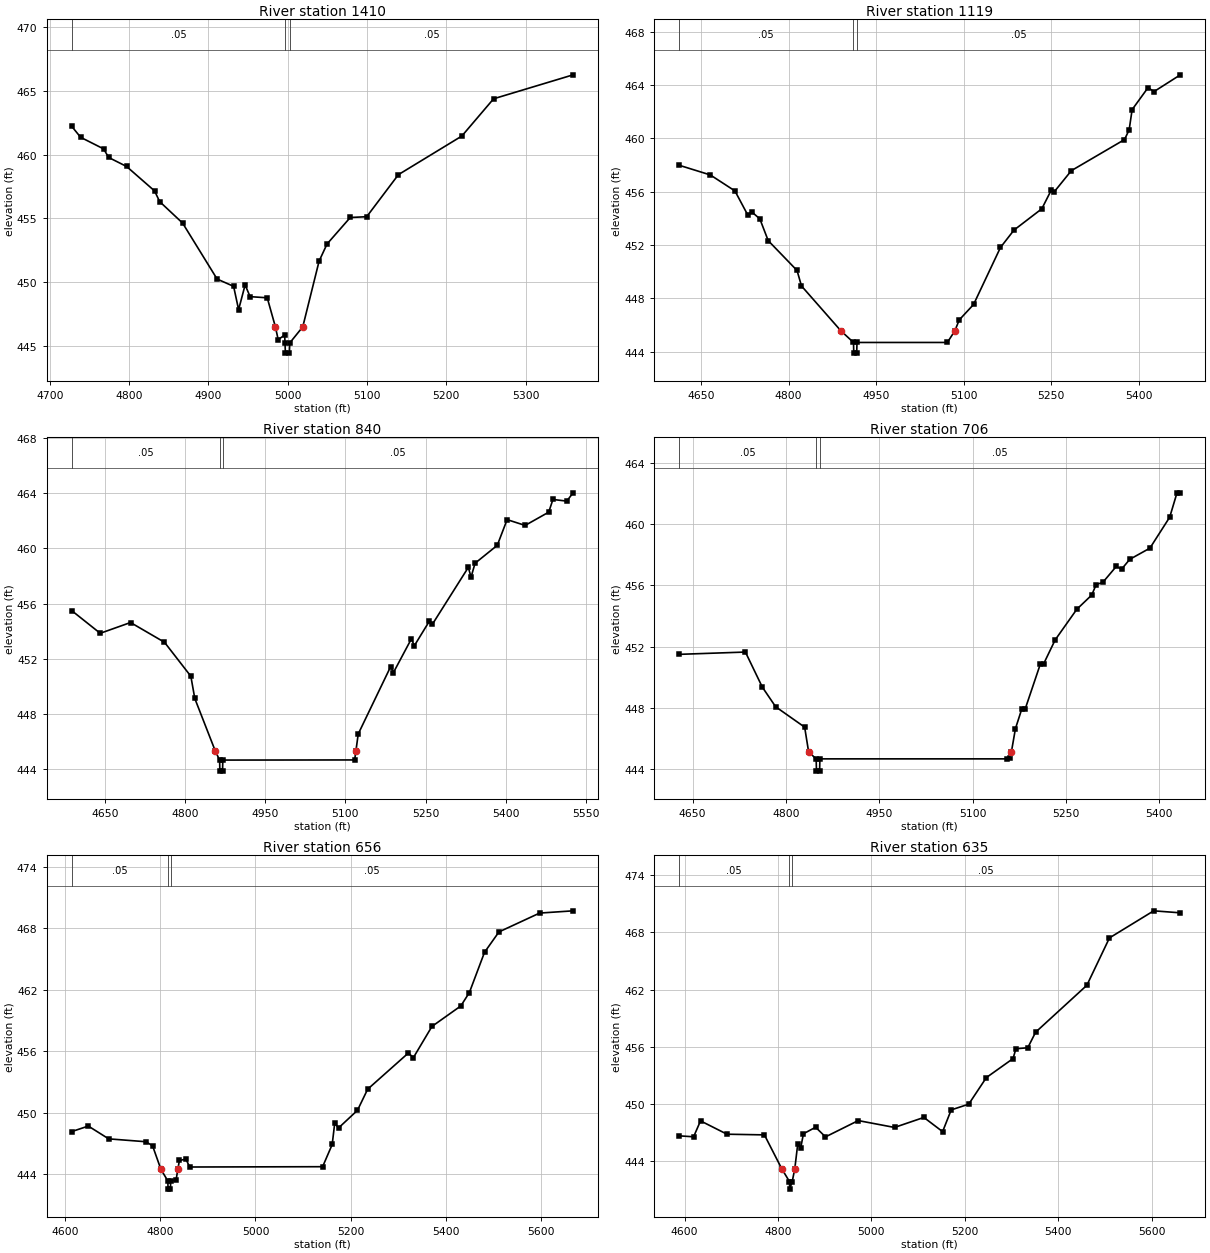
Type RM Length L Ch R = 1,1410,291,291,291
BEGIN DESCRIPTION:
UNT 054 IN DRY CR WATERSHED 3.0
END DESCRIPTION:
XS GIS Cut Line= 3
      2924229.82      7005584.19      2924445.42      7005750.52
      2924805.31      7005748.26
#Sta/Elev= 30
  4727.7  462.21  4738.9  461.35  4767.9  460.44  4774.2  459.77  4796.9  459.06
  4832.2  457.14  4838.5  456.31  4867.5  454.62  4911.0  450.23  4931.8  449.66
  4938.1  447.83  4946.3  449.77  4952.6  448.85  4974.2  448.76  4984.5  446.48
  4988.0  445.48  4996.2  445.84  4996.6  445.22  4997.1  444.42  5002.1  444.42
  5002.6  445.22  5019.0  446.48  5039.6  451.64  5049.6  452.98  5078.9  455.06
  5099.6  455.12  5139.6  458.42  5219.6  461.45  5259.6  464.37  5359.9  466.25
#Mann=3,-1,0
  4727.7    0.05       0  4996.6    0.03       0  5002.6    0.05       0
Bank Sta=4984.5,5019
Exp/Cntr=0.3,0.1

Type RM Length L Ch R = 1,1119,279,279,279
BEGIN DESCRIPTION:
Mapping XS a256347a
END DESCRIPTION:
XS GIS Cut Line= 3
      2924064.42      7005759.94      2924370.45      7006024.73
      2924819.66      7005957.46
#Sta/Elev= 30
  4612.3  457.98  4666.0  457.25  4708.2  456.05  4730.1  454.25  4736.7  454.49
  4750.9  453.95  4765.2  452.32  4814.6  450.08  4822.2  448.92  4889.6  445.56
  4911.3  444.68  4911.8  443.88  4916.8  443.88  4917.3  444.68  5072.1  444.68
  5085.0  445.56  5092.4  446.37  5117.0  447.53  5163.1  451.81  5186.2  453.11
  5233.9  454.71  5250.3  456.13  5255.3  455.99  5284.5  457.57  5375.5  459.90
  5383.5  460.63  5388.6  462.15  5415.9  463.80  5426.0  463.50  5471.2  464.76
#Mann=3,-1,0
  4612.3    0.05       0  4911.3   0.033       0  4917.3    0.05       0
Bank Sta=4889.6,5085
Exp/Cntr=0.3,0.1

Type RM Length L Ch R = 1,840,134,134,134
BEGIN DESCRIPTION:
Mapping XS 04ca93f7
END DESCRIPTION:
XS GIS Cut Line= 3
      2924023.20      7006011.69      2924327.04      7006291.66
      2924831.34      7006146.65
#Sta/Elev= 30
  4588.2  455.50  4641.5  453.86  4698.2  454.64  4761.7  453.21  4811.0  450.75
  4818.4  449.14  4856.9  445.32  4864.8  444.68  4865.3  443.88  4870.3  443.88
  4870.8  444.68  5117.4  444.69  5119.7  445.32  5124.1  446.57  5184.8  451.45
  5190.0  451.02  5223.7  453.47  5228.9  452.95  5257.4  454.75  5262.6  454.50
  5330.0  458.63  5335.2  457.93  5342.6  458.93  5384.2  460.23  5402.6  462.09
  5436.3  461.67  5480.4  462.63  5488.3  463.55  5514.1  463.43  5526.1  464.03
#Mann=3,-1,0
  4588.2    0.05       0  4864.8   0.033       0  4870.8    0.05       0
Bank Sta=4856.9,5119.7
Exp/Cntr=0.3,0.1

Type RM Length L Ch R = 1,706,50,50,50
BEGIN DESCRIPTION:
Mapping XS 5119f567
END DESCRIPTION:
XS GIS Cut Line= 3
      2923991.63      7006233.18      2924335.41      7006438.92
      2924710.22      7006285.36
#Sta/Elev= 30
  4628.0  451.50  4734.8  451.65  4762.0  449.36  4783.4  448.08  4830.0  446.75
  4836.4  445.13  4848.5  444.68  4849.0  443.88  4854.0  443.88  4854.5  444.68
  5155.1  444.68  5160.5  444.73  5162.2  445.13  5168.7  446.65  5179.1  447.96
  5184.5  447.95  5208.5  450.84  5213.9  450.87  5232.5  452.44  5267.3  454.44
  5291.3  455.37  5298.4  456.05  5309.2  456.20  5330.8  457.24  5339.3  457.06
  5352.4  457.70  5384.8  458.43  5416.6  460.45  5428.1  462.01  5433.7  462.04
#Mann=3,-1,0
  4628.0    0.05       0  4848.5   0.033       0  4854.5    0.05       0
Bank Sta=4836.4,5162.2
Exp/Cntr=0.3,0.1

Type RM Length L Ch R = 1,656,21,21,21
BEGIN DESCRIPTION:
Mapping XS 788f96b4
END DESCRIPTION:
XS GIS Cut Line= 5
      2923984.13      7006306.82      2924179.47      7006476.12
      2924218.54      7006484.80      2924470.27      7006452.25
      2924939.05      7006276.46
#Sta/Elev= 30
  4614.1  448.14  4648.9  448.68  4691.7  447.43  4769.5  447.15  4783.8  446.76
  4801.3  444.46  4815.9  443.32  4816.4  442.52  4821.4  442.52  4821.9  443.32
  4833.2  443.42  4837.0  444.46  4840.2  445.32  4854.0  445.45  4861.7  444.68
  5141.0  444.71  5161.1  446.88  5166.3  448.93  5174.8  448.51  5214.2  450.22
  5235.6  452.28  5321.0  455.81  5331.7  455.37  5370.6  458.41  5431.2  460.41
  5449.2  461.72  5481.0  465.65  5511.3  467.64  5596.7  469.48  5667.1  469.70
#Mann=3,-1,0
  4614.1    0.05       0  4815.9    0.03       0  4821.9    0.05       0
Bank Sta=4801.3,4837
Exp/Cntr=0.3,0.1

Type RM Length L Ch R = 1,635,63,63,63
BEGIN DESCRIPTION:
Mapping XS 6597dea7
END DESCRIPTION:
XS GIS Cut Line= 5
      2923942.93      7006332.90      2924162.11      7006486.97
      2924199.01      7006502.16      2924476.78      7006480.46
      2924939.04      7006326.38
#Sta/Elev= 30
  4588.0  446.66  4619.4  446.56  4634.2  448.23  4690.9  446.83  4771.0  446.76
  4808.0  443.22  4824.6  441.87  4825.1  441.07  4830.6  441.87  4836.1  443.22
  4842.5  445.85  4848.6  445.36  4854.6  446.88  4880.7  447.56  4901.8  446.55
  4972.0  448.26  5049.6  447.54  5112.5  448.59  5152.6  447.10  5171.0  449.38
  5208.5  449.98  5246.3  452.77  5303.4  454.76  5309.6  455.79  5335.0  455.90
  5351.8  457.53  5461.5  462.45  5509.9  467.42  5604.7  470.26  5661.7  470.05
#Mann=3,-1,0
  4588.0    0.05       0  4824.6    0.03       0  4830.6    0.05       0
Bank Sta=4808,4836.1
Exp/Cntr=0.3,0.1

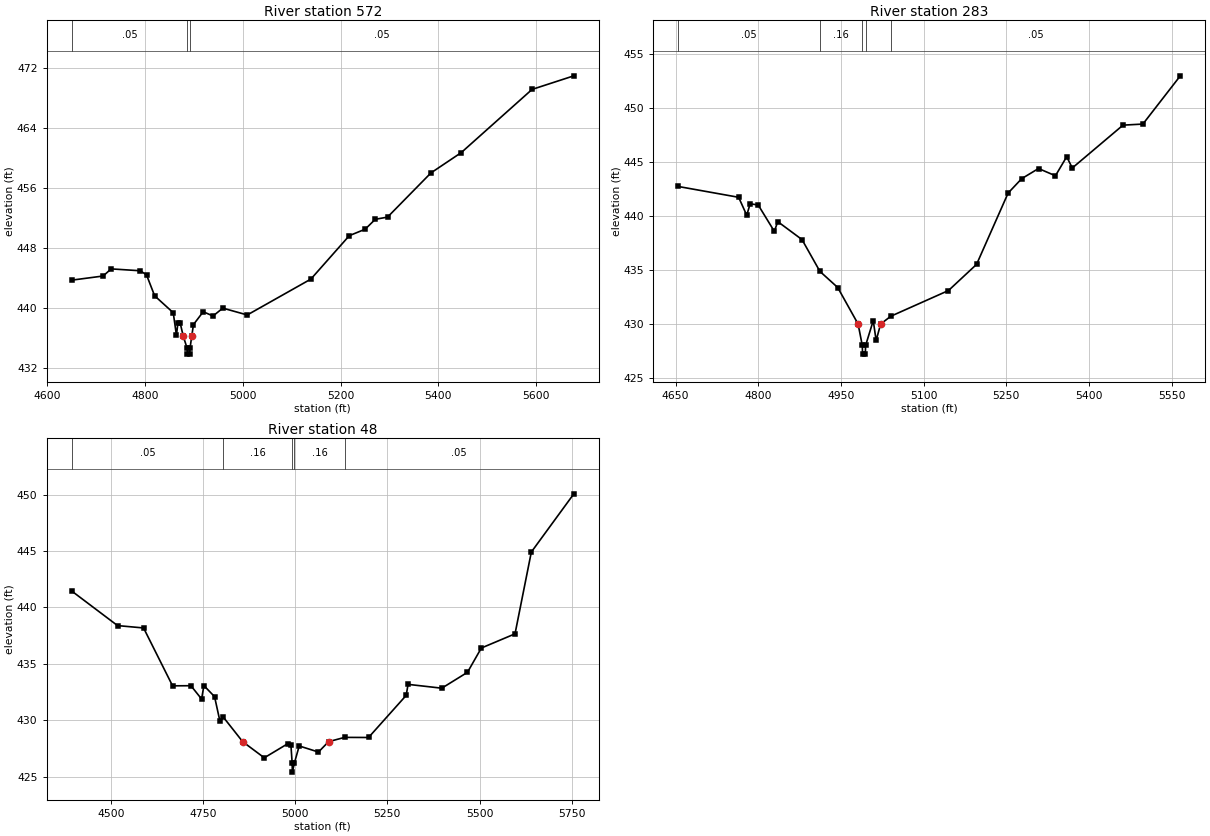
Type RM Length L Ch R = 1,572,289,289,289
BEGIN DESCRIPTION:
Mapping XS be2ccd97
END DESCRIPTION:
XS GIS Cut Line= 4
      2923960.32      7006452.27      2924155.60      7006552.08
      2924507.17      7006558.59      2924947.67      7006443.58
#Sta/Elev= 30
  4650.7  443.72  4714.7  444.27  4731.3  445.22  4790.7  444.97  4803.5  444.42
  4820.1  441.63  4858.1  439.38  4864.6  436.39  4867.7  438.03  4872.2  438.03
  4878.6  436.24  4886.4  434.66  4886.9  433.86  4891.9  433.86  4892.4  434.66
  4895.9  436.24  4899.4  437.80  4919.4  439.51  4939.4  438.94  4959.4  439.99
  5009.4  439.08  5139.4  443.86  5218.0  449.65  5250.4  450.51  5271.1  451.83
  5296.1  452.12  5384.8  458.01  5446.8  460.72  5591.5  469.14  5676.9  470.95
#Mann=3,-1,0
  4650.7    0.05       0  4886.4    0.03       0  4892.4    0.05       0
Bank Sta=4878.6,4895.9
Exp/Cntr=0.3,0.1

Type RM Length L Ch R = 1,283,235,235,235
BEGIN DESCRIPTION:
Mapping XS 9bc5bfbb
END DESCRIPTION:
XS GIS Cut Line= 3
      2923956.40      7006539.95      2924156.90      7006813.36
      2924716.82      7006696.17
#Sta/Elev= 30
  4654.8  442.75  4764.4  441.75  4779.1  440.09  4785.3  441.15  4799.9  441.04
  4829.2  438.60  4835.4  439.50  4879.4  437.84  4911.9  434.90  4944.2  433.41
  4981.2  430.03  4988.8  428.05  4989.3  427.25  4994.3  427.25  4994.8  428.05
  5008.7  430.35  5013.9  428.51  5022.1  430.03  5040.4  430.75  5145.2  433.13
  5196.2  435.55  5253.4  442.14  5278.0  443.47  5308.6  444.41  5339.3  443.74
  5359.7  445.50  5369.9  444.46  5461.9  448.42  5498.0  448.52  5565.9  452.98
#Mann=5,-1,0
  4654.8    0.05       0  4911.9    0.16       0  4988.8    0.07       0
  4994.8    0.16       0  5040.4    0.05       0
Bank Sta=4981.2,5022.1
Exp/Cntr=0.3,0.1

Type RM Length L Ch R = 1,48,0,0,0
BEGIN DESCRIPTION:
UNT 054 IN DRY CR WATERSHED 1.0
END DESCRIPTION:
XS GIS Cut Line= 3
      2923701.19      7006545.15      2924074.71      7007021.84
      2924794.88      7006792.54
#Sta/Elev= 30
  4394.4  441.44  4518.5  438.38  4589.1  438.17  4667.7  433.04  4717.5  433.05
  4746.4  431.87  4752.7  433.06  4781.6  432.08  4796.1  429.91  4805.2  430.27
  4857.8  428.09  4916.4  426.66  4980.6  427.92  4988.7  427.76  4992.0  426.19
  4992.5  425.39  4998.0  426.19  5011.1  427.71  5063.3  427.17  5090.7  428.09
  5134.3  428.47  5199.1  428.46  5301.1  432.19  5306.3  433.17  5397.7  432.83
  5467.4  434.24  5504.9  436.39  5596.3  437.65  5640.5  444.90  5755.8  450.06
#Mann=5,-1,0
  4394.4    0.05       0  4805.2    0.16       0  4992.0    0.07       0
  4998.0    0.16       0  5134.3    0.05       0
Bank Sta=4857.8,5090.7
Exp/Cntr=0.3,0.1

Chan Stop Cuts=-1