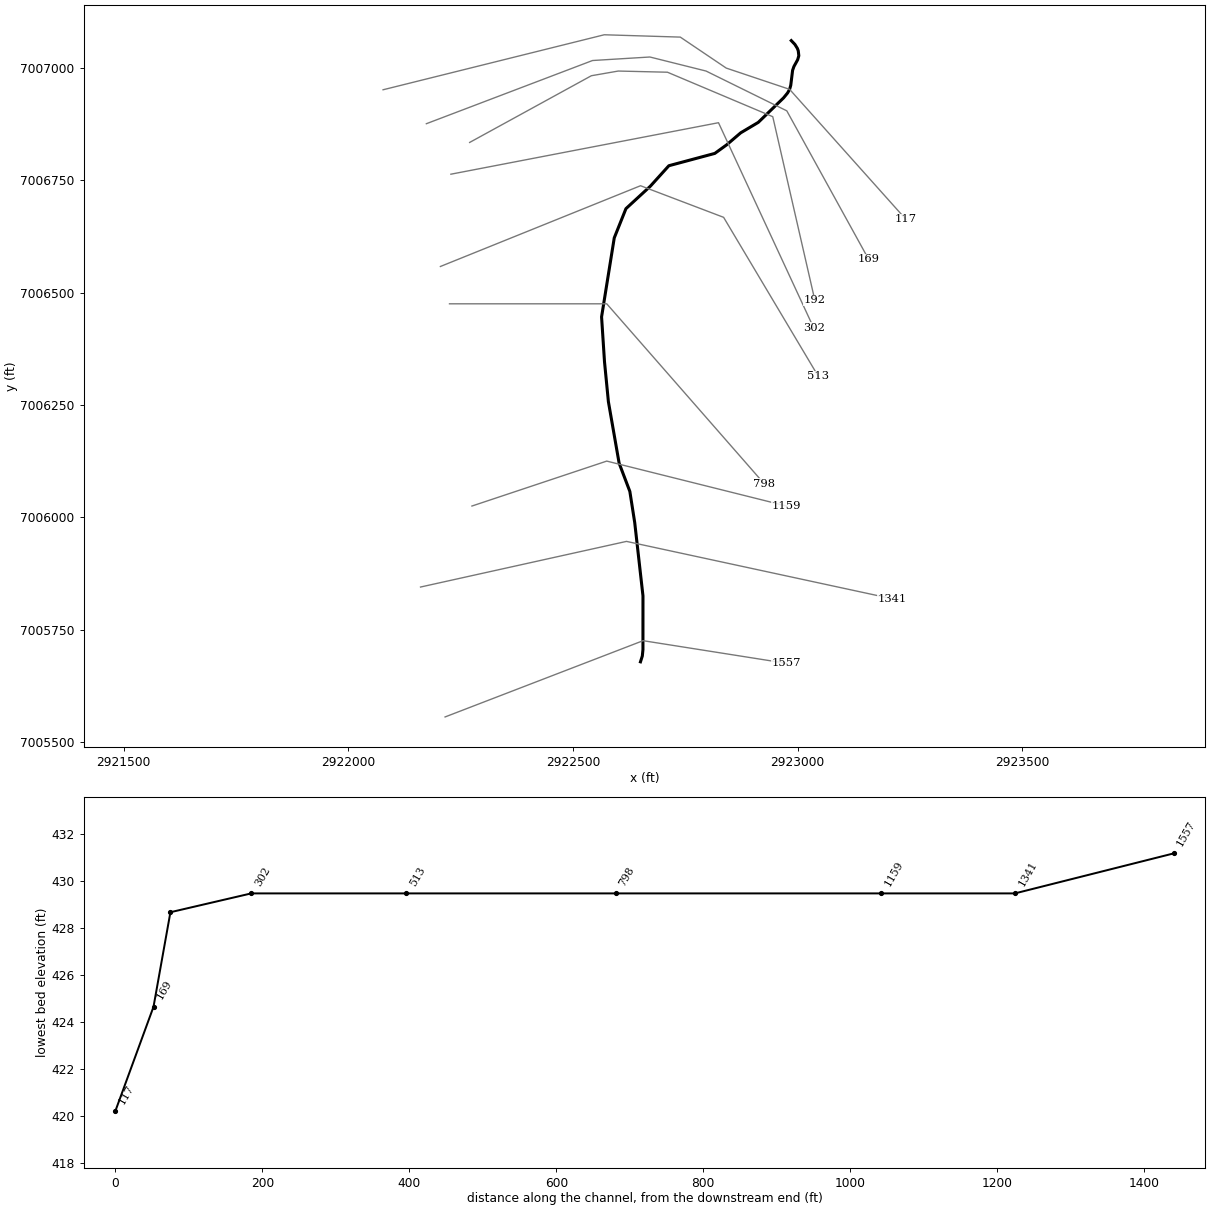
--- UNT 055 IN DRY CR WATERSHED.prj (project) ---

Proj Title=UNT 055 IN DRY CR WATERSHED Base Level Engineering
Current Plan=p01
Default Exp/Contr=0.3,0.1
English Units
Geom File=g01
Flow File=f01
Plan File=p01
BEGIN DESCRIPTION:
UNT 055 IN DRY CR WATERSHED
END DESCRIPTION:

--- UNT 055 IN DRY CR WATERSHED.p01 (plan) ---

Plan Title=Multiple Run
Short Identifier=Multiple
Geom File=g01
Flow File=f01
Subcritical Flow
K Sum by GR= 0
Std Step Tol= 0.01
Critical Tol= 0.01
Num of Std Step Trials= 20
Max Error Tol= 0.3
Flow Tol Ratio= 0.001
Split Flow NTrial= 30
Split Flow Tol= 0.02
Split Flow Ratio= 0.02
Log Output Level= 0
Friction Slope Method= 1
Unsteady Friction Slope Method= 2
Unsteady Bridges Friction Slope Method= 1
Parabolic Critical Depth
Global Vel Dist=  1 , 1 , 1
Global Log Level= 0
CheckData=True
Encroach Param= -1, 0, 0, 0
BEGIN DESCRIPTION:
Multiple Run
END DESCRIPTION:

--- UNT 055 IN DRY CR WATERSHED.f01 (steady flow) ---

Flow Title=Multiple
Number of Profiles=7
Profile Names=10-year,25-year,50-year,1pct_min,100-year,1pct_plu,500-year
River Rch & RM= UNT 055 IN DRY C,Reach-1,1557
     207     262     304     177     353     704     473
Boundary for River Rch & Prof#=UNT 055 IN DRY C,Reach-1,1
Up Type=0
Dn Type=3
Dn Slope=0.005
Boundary for River Rch & Prof#=UNT 055 IN DRY C,Reach-1,2
Up Type=0
Dn Type=3
Dn Slope=0.005
Boundary for River Rch & Prof#=UNT 055 IN DRY C,Reach-1,3
Up Type=0
Dn Type=3
Dn Slope=0.005
Boundary for River Rch & Prof#=UNT 055 IN DRY C,Reach-1,4
Up Type=0
Dn Type=3
Dn Slope=0.005
Boundary for River Rch & Prof#=UNT 055 IN DRY C,Reach-1,5
Up Type=0
Dn Type=3
Dn Slope=0.005
Boundary for River Rch & Prof#=UNT 055 IN DRY C,Reach-1,6
Up Type=0
Dn Type=3
Dn Slope=0.005
Boundary for River Rch & Prof#=UNT 055 IN DRY C,Reach-1,7
Up Type=0
Dn Type=3
Dn Slope=0.005

--- UNT 055 IN DRY CR WATERSHED.g01 (geometry) ---

Geom Title=Existing Conditions

River Reach=UNT 055 IN DRY C,Reach-1
Reach XY= 30
      2922650.03      7005678.30      2922654.14      7005691.26
      2922655.54      7005705.60      2922655.60      7005824.96
      2922637.25      7005987.99      2922626.40      7006057.43
      2922602.53      7006120.37      2922578.66      7006257.09
      2922569.98      7006346.06      2922563.47      7006445.89
      2922591.68      7006621.67      2922617.72      7006686.77
      2922671.98      7006736.69      2922713.21      7006782.26
      2922815.44      7006809.68      2922841.71      7006828.69
      2922873.05      7006855.47      2922912.16      7006878.72
      2922968.38      7006933.20      2922977.42      7006944.24
      2922981.91      7006952.24      2922984.45      7006961.21
      2922988.55      7006994.59      2922991.53      7007003.09
      2922999.89      7007018.31      2923002.39      7007027.07
      2923001.16      7007038.01      2922999.15      7007043.44
      2922993.60      7007052.33      2922985.59      7007060.71

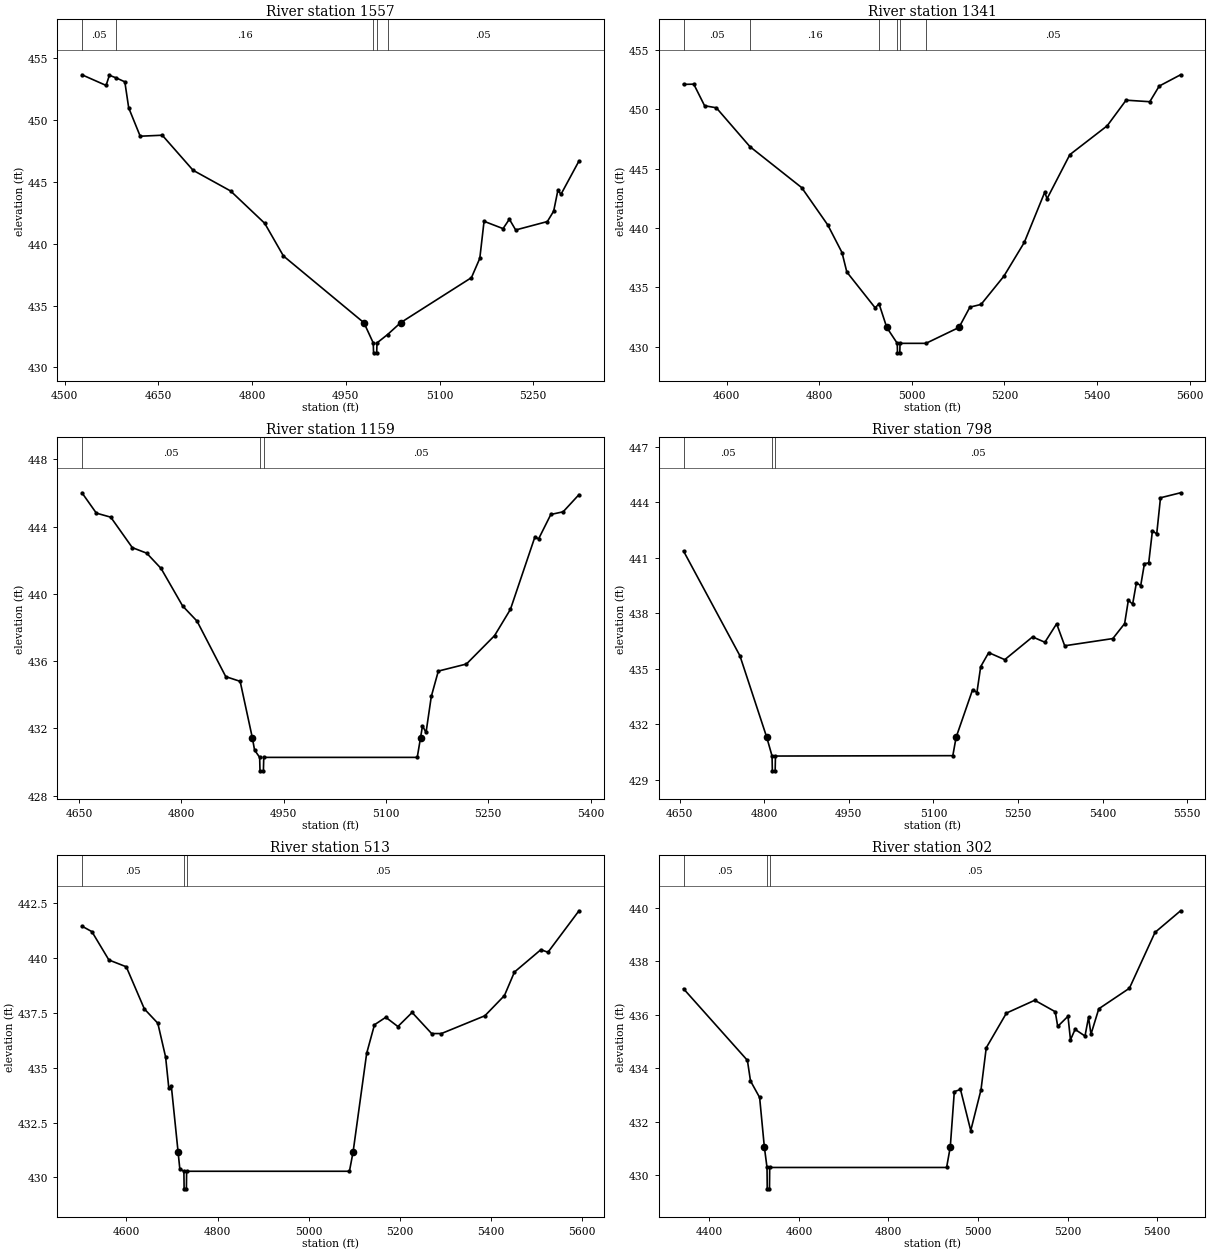
Type RM Length L Ch R = 1,1557,216,216,216
BEGIN DESCRIPTION:
UNT 055 IN DRY CR WATERSHED 4.0
END DESCRIPTION:
XS GIS Cut Line= 3
      2922215.22      7005555.66      2922655.87      7005725.36
      2922975.03      7005675.00
#Sta/Elev= 30
  4527.8  453.63  4566.4  452.77  4571.7  453.59  4583.0  453.37  4596.4  453.06
  4602.6  450.96  4621.0  448.67  4656.3  448.75  4705.6  445.92  4765.6  444.25
  4820.2  441.64  4850.2  439.00  4979.0  433.61  4993.9  431.98  4994.4  431.18
  4999.4  431.18  4999.9  431.98  5016.9  432.66  5037.6  433.61  5151.0  437.25
  5164.4  438.81  5171.2  441.80  5201.6  441.21  5211.7  441.97  5221.8  441.10
  5272.5  441.78  5282.6  442.62  5289.3  444.29  5294.4  443.99  5323.1  446.67
#Mann=5,-1,0
  4527.8    0.05       0  4583.0    0.16       0  4993.9    0.07       0
  4999.9    0.16       0  5016.9    0.05       0
Bank Sta=4979,5037.6
Exp/Cntr=0.3,0.1

Type RM Length L Ch R = 1,1341,182,182,182
BEGIN DESCRIPTION:
Mapping XS 27588632
END DESCRIPTION:
XS GIS Cut Line= 3
      2922160.58      7005844.74      2922618.89      7005946.30
      2923210.05      7005818.69
#Sta/Elev= 30
  4506.4  452.10  4528.5  452.12  4551.9  450.30  4577.2  450.13  4650.0  446.85
  4761.8  443.40  4818.2  440.25  4848.9  437.93  4859.3  436.29  4920.6  433.27
  4928.9  433.62  4945.6  431.62  4968.3  430.28  4968.8  429.48  4973.8  429.48
  4974.3  430.28  5030.3  430.28  5101.7  431.62  5125.3  433.33  5149.4  433.56
  5198.6  435.93  5242.8  438.78  5287.0  443.01  5292.1  442.47  5341.3  446.18
  5422.0  448.61  5462.9  450.77  5514.1  450.64  5534.5  451.96  5580.6  452.91
#Mann=6,-1,0
  4506.4    0.05       0  4650.0    0.16       0  4928.9     0.1       0
  4968.3    0.07       0  4974.3     0.1       0  5030.3    0.05       0
Bank Sta=4945.6,5101.7
Exp/Cntr=0.3,0.1

Type RM Length L Ch R = 1,1159,361,361,361
BEGIN DESCRIPTION:
UNT 055 IN DRY CR WATERSHED 3.0
END DESCRIPTION:
XS GIS Cut Line= 3
      2922274.98      7006024.99      2922575.00      7006125.00
      2922975.04      7006024.99
#Sta/Elev= 30
  4654.4  446.01  4675.5  444.80  4696.6  444.56  4728.2  442.75  4749.3  442.42
  4770.4  441.51  4802.0  439.28  4823.1  438.38  4865.2  435.08  4886.3  434.80
  4904.2  431.44  4907.4  430.72  4914.9  430.28  4915.4  429.48  4920.4  429.48
  4920.9  430.28  5145.9  430.28  5150.7  431.44  5153.6  432.15  5158.8  431.76
  5166.5  433.90  5176.8  435.41  5218.0  435.83  5259.3  437.52  5282.5  439.08
  5318.5  443.40  5323.7  443.26  5341.7  444.72  5359.8  444.88  5383.0  445.90
#Mann=3,-1,0
  4654.4    0.05       0  4914.9   0.033       0  4920.9    0.05       0
Bank Sta=4904.2,5150.7
Exp/Cntr=0.3,0.1

Type RM Length L Ch R = 1,798,285,285,285
BEGIN DESCRIPTION:
UNT 055 IN DRY CR WATERSHED 2.0
END DESCRIPTION:
XS GIS Cut Line= 3
      2922225.04      7006475.00      2922575.00      7006475.00
      2922925.02      7006074.97
#Sta/Elev= 30
  4656.9  441.36  4756.9  435.70  4804.5  431.29  4813.9  430.28  4814.4  429.48
  4819.4  429.48  4819.9  430.28  5134.5  430.30  5140.3  431.29  5169.6  433.87
  5177.2  433.71  5183.9  435.11  5198.1  435.87  5226.6  435.49  5275.9  436.72
  5297.8  436.43  5318.6  437.43  5332.9  436.24  5418.3  436.63  5439.2  437.44
  5445.8  438.70  5453.4  438.49  5460.1  439.65  5467.7  439.49  5474.3  440.68
  5481.9  440.72  5488.5  442.46  5496.1  442.28  5502.8  444.24  5538.4  444.51
#Mann=3,-1,0
  4656.9    0.05       0  4813.9   0.033       0  4819.9    0.05       0
Bank Sta=4804.5,5140.3
Exp/Cntr=0.3,0.1

Type RM Length L Ch R = 1,513,211,211,211
BEGIN DESCRIPTION:
Mapping XS 17f4069c
END DESCRIPTION:
XS GIS Cut Line= 4
      2922204.83      7006558.06      2922650.14      7006737.75
      2922835.04      7006667.44      2923045.96      7006313.30
#Sta/Elev= 30
  4502.4  441.44  4524.2  441.19  4561.5  439.90  4599.6  439.59  4639.3  437.67
  4668.8  437.02  4685.9  435.48  4693.0  434.05  4698.4  434.17  4713.2  431.17
  4717.1  430.38  4726.0  430.28  4726.5  429.48  4731.5  429.48  4732.0  430.28
  5089.1  430.28  5097.2  431.17  5126.9  435.65  5144.0  436.95  5168.8  437.29
  5195.4  436.87  5226.6  437.51  5269.4  436.55  5290.8  436.55  5386.2  437.36
  5429.1  438.28  5451.0  439.35  5509.1  440.37  5524.5  440.25  5592.6  442.14
#Mann=3,-1,0
  4502.4    0.05       0  4726.0   0.033       0  4732.0    0.05       0
Bank Sta=4713.2,5097.2
Exp/Cntr=0.3,0.1

Type RM Length L Ch R = 1,302,110,110,110
BEGIN DESCRIPTION:
Mapping XS 34b227db
END DESCRIPTION:
XS GIS Cut Line= 3
      2922228.16      7006763.42      2922823.67      7006878.01
      2923035.49      7006421.38
#Sta/Elev= 30
  4342.4  436.97  4485.0  434.29  4491.9  433.52  4512.3  432.90  4522.8  431.05
  4528.8  430.28  4529.3  429.48  4534.3  429.48  4534.8  430.28  4929.8  430.28
  4938.0  431.05  4947.0  433.12  4960.8  433.20  4983.7  431.66  5006.6  433.19
  5018.3  434.76  5063.4  436.06  5126.6  436.54  5172.4  436.11  5177.9  435.56
  5200.8  435.94  5206.4  435.06  5216.7  435.45  5238.8  435.20  5246.7  435.90
  5252.2  435.27  5269.6  436.22  5338.0  436.99  5395.1  439.08  5452.2  439.89
#Mann=3,-1,0
  4342.4    0.05       0  4528.8    0.03       0  4534.8    0.05       0
Bank Sta=4522.8,4938
Exp/Cntr=0.3,0.1

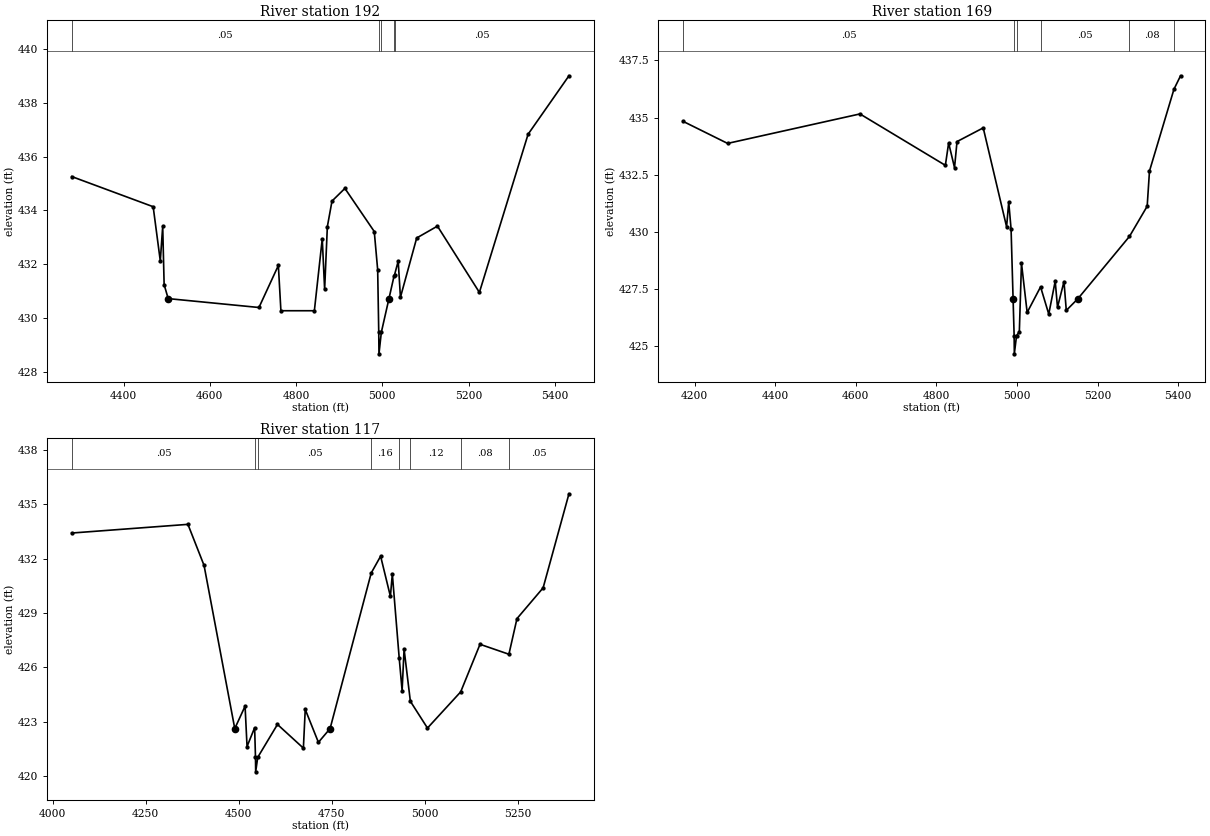
Type RM Length L Ch R = 1,192,23,23,23
BEGIN DESCRIPTION:
Mapping XS 33622507
END DESCRIPTION:
XS GIS Cut Line= 6
      2922269.89      7006834.08      2922540.77      7006982.54
      2922600.66      7006992.96      2922710.04      7006990.35
      2922944.41      7006891.39      2923038.15      7006482.58
#Sta/Elev= 30
  4279.8  435.26  4468.7  434.14  4485.2  432.13  4490.8  433.41  4494.1  431.25
  4503.5  430.73  4714.0  430.40  4759.0  431.96  4764.9  430.28  4842.5  430.28
  4860.8  432.95  4866.3  431.07  4872.6  433.40  4883.4  434.35  4913.3  434.82
  4981.4  433.22  4989.3  431.80  4991.8  429.48  4992.3  428.68  4997.8  429.48
  5015.5  430.73  5027.3  431.57  5028.4  431.61  5036.9  432.12  5042.1  430.78
  5079.8  432.98  5127.9  433.42  5225.2  430.96  5338.1  436.83  5432.9  439.00
#Mann=5,-1,0
  4279.8    0.05       0  4991.8    0.03       0  4997.8    0.05       0
  5027.3    0.12       0  5028.4    0.05       0
Bank Sta=4503.5,5015.5
Exp/Cntr=0.3,0.1

Type RM Length L Ch R = 1,169,52,52,52
BEGIN DESCRIPTION:
Mapping XS 570d674f
END DESCRIPTION:
XS GIS Cut Line= 6
      2922173.55      7006875.76      2922543.37      7007016.39
      2922670.97      7007024.21      2922795.97      7006992.96
      2922975.66      7006904.41      2923157.93      7006573.72
#Sta/Elev= 30
  4172.1  434.83  4282.0  433.87  4610.4  435.16  4822.3  432.91  4830.4  433.89
  4845.0  432.81  4851.2  433.95  4916.2  434.55  4974.2  430.22  4979.5  431.30
  4985.3  430.13  4990.3  427.07  4992.9  425.46  4993.4  424.66  4998.9  425.46
  5005.8  425.62  5011.1  428.63  5025.2  426.47  5058.5  427.59  5078.8  426.40
  5094.8  427.84  5100.5  426.70  5116.6  427.82  5122.3  426.56  5151.0  427.07
  5279.1  429.80  5323.0  431.12  5328.7  432.66  5389.4  436.24  5405.8  436.83
#Mann=6,-1,0
  4172.1    0.05       0  4992.9    0.07       0  4998.9    0.05       0
  5058.5    0.05       0  5279.1    0.08       0  5389.4    0.05       0
Bank Sta=4990.3,5151
Exp/Cntr=0.3,0.1

Type RM Length L Ch R = 1,117,0,0,0
BEGIN DESCRIPTION:
UNT 055 IN DRY CR WATERSHED 1.0
END DESCRIPTION:
XS GIS Cut Line= 6
      2922077.25      7006951.30      2922569.41      7007073.69
      2922738.68      7007068.48      2922840.92      7006999.52
      2922981.91      7006952.24      2923240.64      7006662.95
#Sta/Elev= 30
  4050.9  433.42  4363.4  433.90  4406.8  431.63  4489.4  422.61  4517.1  423.85
  4522.4  421.62  4542.8  422.66  4545.1  421.02  4545.6  420.22  4551.1  421.02
  4604.2  422.84  4673.9  421.53  4678.9  423.67  4714.3  421.85  4745.7  422.61
  4856.3  431.21  4881.6  432.14  4907.9  429.92  4913.1  431.15  4931.5  426.53
  4939.4  424.71  4944.7  427.00  4961.6  424.12  5007.6  422.64  5096.9  424.64
  5148.9  427.27  5226.6  426.72  5248.3  428.69  5318.6  430.39  5388.1  435.59
#Mann=8,-1,0
  4050.9    0.05       0  4545.1    0.07       0  4551.1    0.05       0
  4856.3    0.16       0  4931.5    0.05       0  4961.6    0.12       0
  5096.9    0.08       0  5226.6    0.05       0
Bank Sta=4489.4,4745.7
Exp/Cntr=0.3,0.1

Chan Stop Cuts=-1