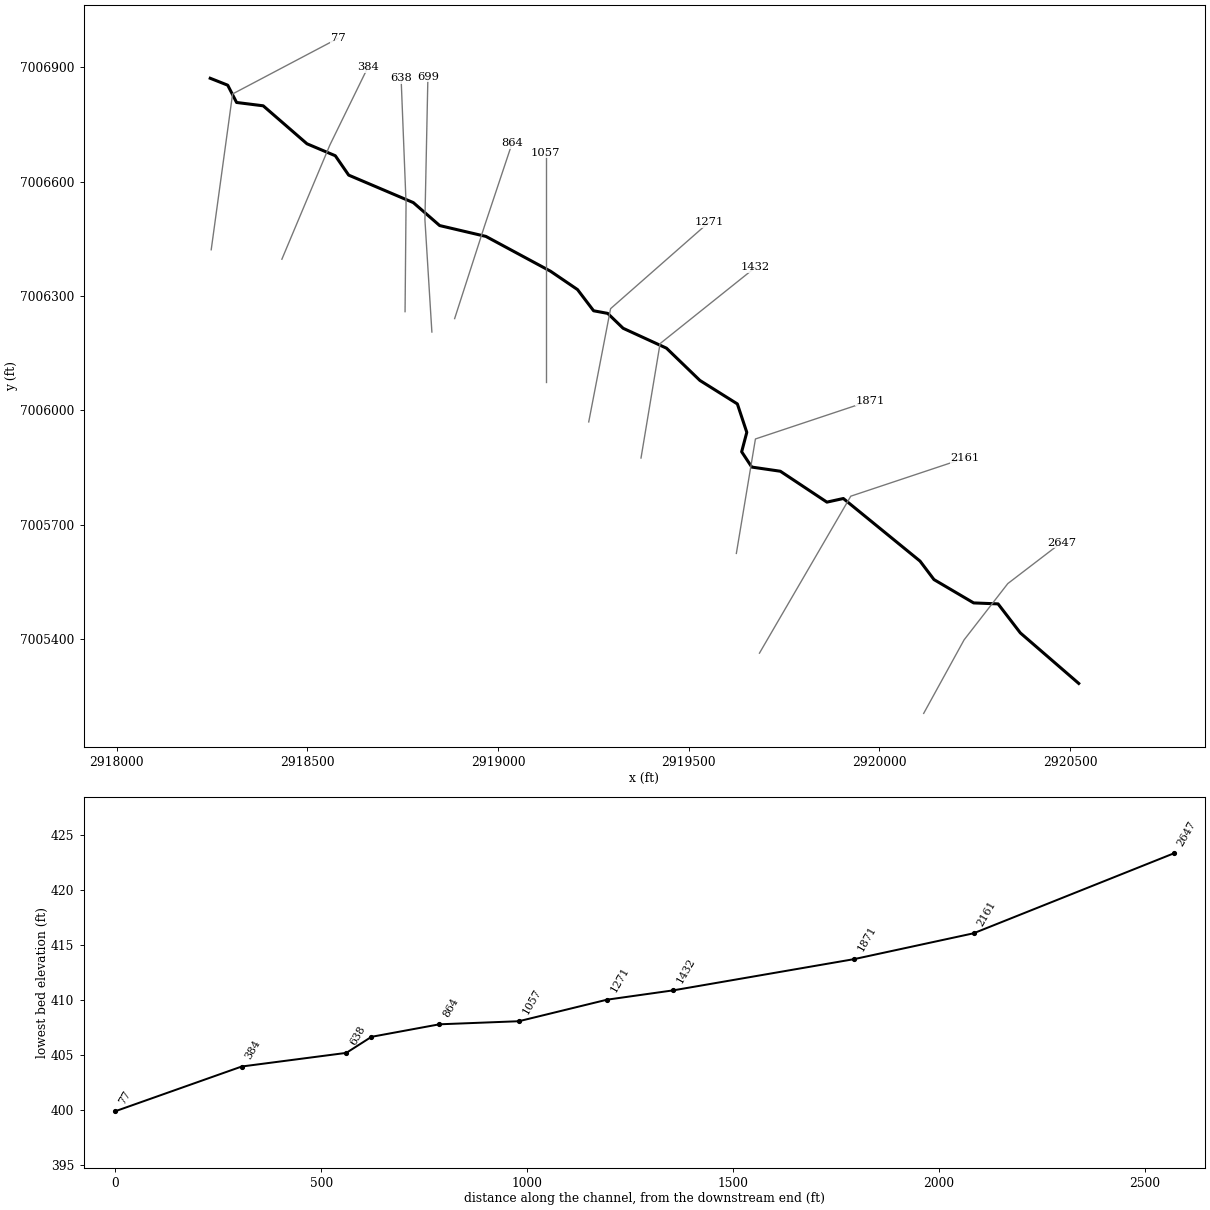
--- UNT 056 IN DRY CR WATERSHED.prj (project) ---

Proj Title=UNT 056 IN DRY CR WATERSHED Base Level Engineering
Current Plan=p01
Default Exp/Contr=0.3,0.1
English Units
Geom File=g01
Flow File=f01
Plan File=p01
BEGIN DESCRIPTION:
UNT 056 IN DRY CR WATERSHED
END DESCRIPTION:

--- UNT 056 IN DRY CR WATERSHED.p01 (plan) ---

Plan Title=Multiple Run
Short Identifier=Multiple
Geom File=g01
Flow File=f01
Subcritical Flow
K Sum by GR= 0
Std Step Tol= 0.01
Critical Tol= 0.01
Num of Std Step Trials= 20
Max Error Tol= 0.3
Flow Tol Ratio= 0.001
Split Flow NTrial= 30
Split Flow Tol= 0.02
Split Flow Ratio= 0.02
Log Output Level= 0
Friction Slope Method= 1
Unsteady Friction Slope Method= 2
Unsteady Bridges Friction Slope Method= 1
Parabolic Critical Depth
Global Vel Dist=  1 , 1 , 1
Global Log Level= 0
CheckData=True
Encroach Param= -1, 0, 0, 0
BEGIN DESCRIPTION:
Multiple Run
END DESCRIPTION:

--- UNT 056 IN DRY CR WATERSHED.f01 (steady flow) ---

Flow Title=Multiple
Number of Profiles=7
Profile Names=10-year,25-year,50-year,1pct_min,100-year,1pct_plu,500-year
River Rch & RM= UNT 056 IN DRY C,Reach-1,2647
     253     323     378     221     441     881     600
Boundary for River Rch & Prof#=UNT 056 IN DRY C,Reach-1,1
Up Type=0
Dn Type=3
Dn Slope=0.005
Boundary for River Rch & Prof#=UNT 056 IN DRY C,Reach-1,2
Up Type=0
Dn Type=3
Dn Slope=0.005
Boundary for River Rch & Prof#=UNT 056 IN DRY C,Reach-1,3
Up Type=0
Dn Type=3
Dn Slope=0.005
Boundary for River Rch & Prof#=UNT 056 IN DRY C,Reach-1,4
Up Type=0
Dn Type=3
Dn Slope=0.005
Boundary for River Rch & Prof#=UNT 056 IN DRY C,Reach-1,5
Up Type=0
Dn Type=3
Dn Slope=0.005
Boundary for River Rch & Prof#=UNT 056 IN DRY C,Reach-1,6
Up Type=0
Dn Type=3
Dn Slope=0.005
Boundary for River Rch & Prof#=UNT 056 IN DRY C,Reach-1,7
Up Type=0
Dn Type=3
Dn Slope=0.005

--- UNT 056 IN DRY CR WATERSHED.g01 (geometry) ---

Geom Title=Existing Conditions

River Reach=UNT 056 IN DRY C,Reach-1
Reach XY= 30
      2920522.64      7005284.08      2920369.57      7005416.49
      2920311.15      7005492.61      2920247.12      7005495.18
      2920143.11      7005556.37      2920106.56      7005604.82
      2919905.47      7005768.91      2919862.37      7005759.42
      2919740.36      7005840.39      2919665.44      7005851.31
      2919638.91      7005891.46      2919652.37      7005942.40
      2919627.63      7006016.90      2919529.40      7006078.47
      2919441.81      7006163.07      2919328.10      7006215.23
      2919287.73      7006254.24      2919250.72      7006261.10
      2919208.56      7006316.68      2919137.86      7006364.76
      2918968.38      7006456.07      2918847.16      7006484.50
      2918778.05      7006544.71      2918608.62      7006616.75
      2918573.50      7006667.59      2918499.25      7006698.94
      2918384.51      7006798.50      2918314.67      7006807.24
      2918291.47      7006852.53      2918245.59      7006870.71

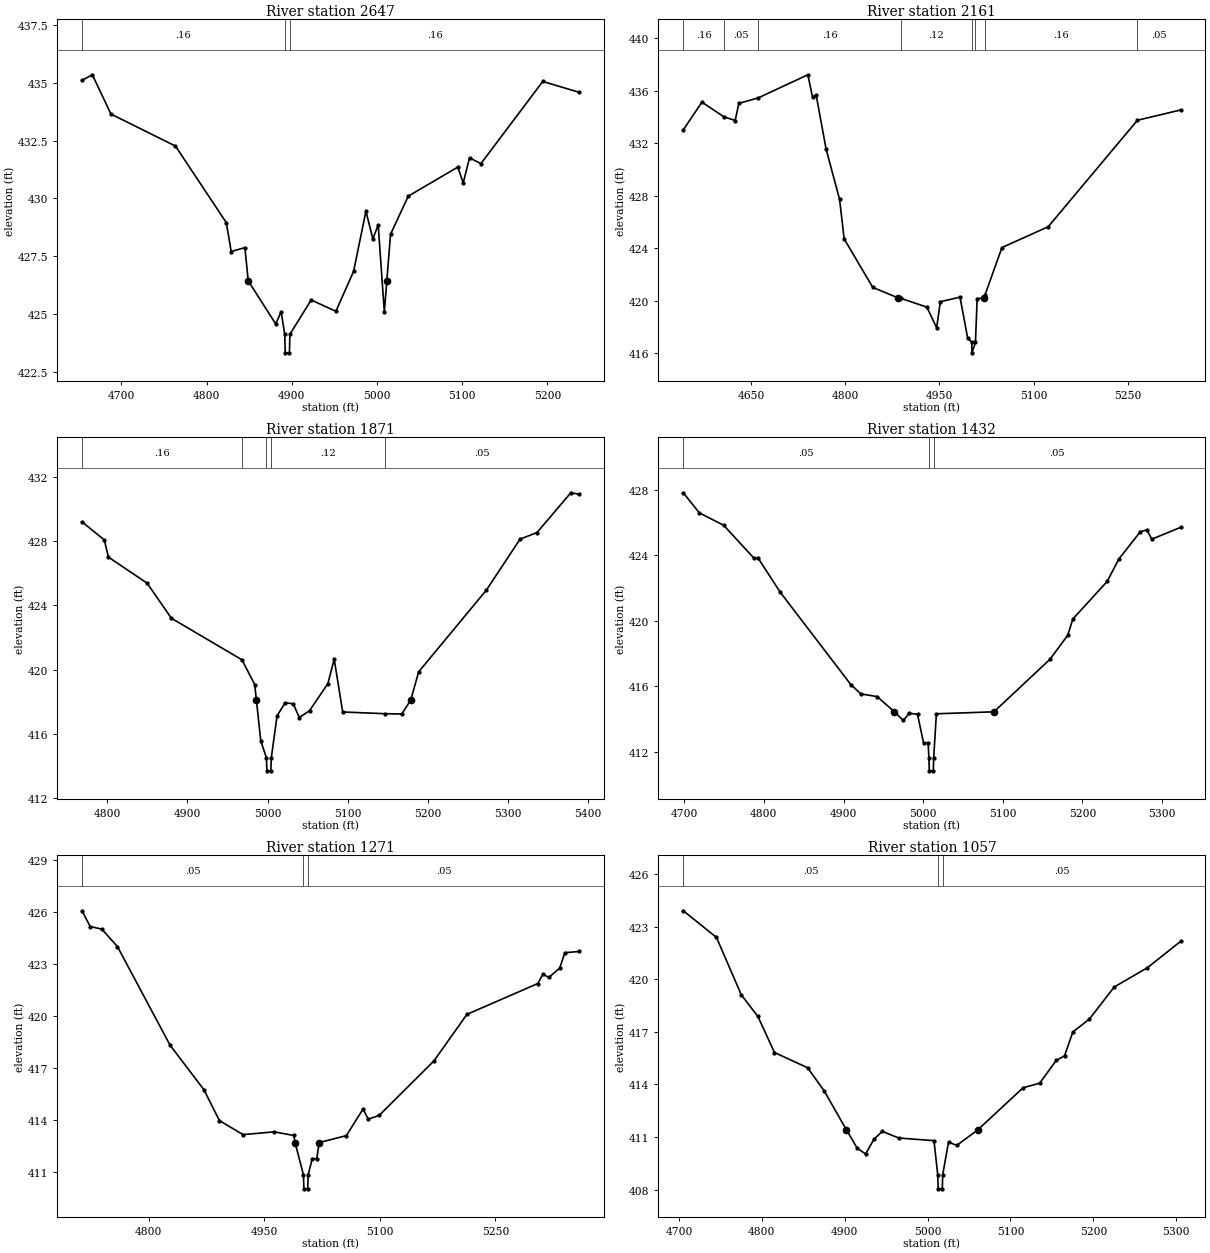
Type RM Length L Ch R = 1,2647,486,486,486
BEGIN DESCRIPTION:
Mapping XS f9d67462
END DESCRIPTION:
XS GIS Cut Line= 4
      2920116.15      7005205.57      2920222.04      7005398.25
      2920336.62      7005545.82      2920477.25      7005653.47
#Sta/Elev= 30
  4653.6  435.12  4665.8  435.36  4687.6  433.66  4763.4  432.27  4823.1  428.95
  4828.8  427.70  4844.9  427.87  4848.8  426.43  4881.1  424.56  4887.4  425.09
  4891.7  424.11  4892.2  423.31  4897.2  423.31  4897.7  424.11  4922.7  425.60
  4951.7  425.11  4972.5  426.84  4987.0  429.45  4995.1  428.25  5001.4  428.85
  5008.6  425.08  5011.5  426.43  5015.9  428.45  5036.7  430.10  5094.9  431.36
  5101.2  430.67  5108.6  431.76  5122.0  431.51  5194.6  435.07  5237.4  434.60
#Mann=3,-1,0
  4653.6    0.16       0  4891.7    0.07       0  4897.7    0.16       0
Bank Sta=4848.8,5011.5
Exp/Cntr=0.3,0.1

Type RM Length L Ch R = 1,2161,290,290,290
BEGIN DESCRIPTION:
UNT 056 IN DRY CR WATERSHED 5.0
END DESCRIPTION:
XS GIS Cut Line= 3
      2919685.56      7005363.49      2919925.00      7005775.00
      2920224.97      7005874.99
#Sta/Elev= 30
  4542.0  433.01  4571.7  435.12  4606.3  434.01  4624.7  433.72  4630.4  435.02
  4661.8  435.45  4740.4  437.20  4747.9  435.51  4753.7  435.66  4769.5  431.55
  4791.0  427.72  4798.3  424.71  4843.9  421.02  4884.3  420.22  4889.0  420.18
  4930.0  419.52  4945.7  417.95  4951.5  419.93  4982.9  420.28  4995.0  417.18
  5001.5  416.84  5002.0  416.04  5007.5  416.84  5010.2  420.16  5021.6  420.22
  5022.6  420.43  5049.7  424.05  5123.5  425.64  5265.6  433.74  5334.3  434.52
#Mann=8,-1,0
  4542.0    0.16       0  4606.3    0.05       0  4661.8    0.16       0
  4889.0    0.12       0  5001.5    0.07       0  5007.5    0.12       0
  5022.6    0.16       0  5265.6    0.05       0
Bank Sta=4884.3,5021.6
Exp/Cntr=0.3,0.1

Type RM Length L Ch R = 1,1871,439,439,439
BEGIN DESCRIPTION:
UNT 056 IN DRY CR WATERSHED 4.0
END DESCRIPTION:
XS GIS Cut Line= 3
      2919624.99      7005624.95      2919675.00      7005925.00
      2919974.99      7006025.00
#Sta/Elev= 30
  4768.5  429.21  4796.4  428.08  4801.5  427.01  4849.7  425.39  4880.1  423.20
  4968.1  420.61  4984.0  419.07  4986.1  418.12  4991.6  415.56  4998.7  414.49
  4999.2  413.69  5004.2  413.69  5004.7  414.49  5011.9  417.12  5022.0  417.93
  5032.1  417.87  5039.7  417.01  5052.4  417.44  5075.3  419.12  5083.2  420.65
  5093.8  417.36  5147.1  417.25  5167.6  417.23  5178.8  418.12  5188.6  419.86
  5273.0  424.95  5315.1  428.13  5336.2  428.54  5378.4  431.02  5388.9  430.93
#Mann=5,-1,0
  4768.5    0.16       0  4968.1    0.12       0  4998.7    0.07       0
  5004.7    0.12       0  5147.1    0.05       0
Bank Sta=4986.1,5178.8
Exp/Cntr=0.3,0.1

Type RM Length L Ch R = 1,1432,161,161,161
BEGIN DESCRIPTION:
UNT 056 IN DRY CR WATERSHED 3.0
END DESCRIPTION:
XS GIS Cut Line= 3
      2919375.01      7005875.05      2919425.00      7006175.00
      2919674.96      7006374.97
#Sta/Elev= 30
  4698.9  427.81  4719.1  426.58  4749.5  425.83  4787.6  423.82  4792.6  423.84
  4820.5  421.75  4909.2  416.11  4921.9  415.54  4942.2  415.38  4963.9  414.45
  4975.1  413.93  4982.7  414.36  4992.9  414.30  5000.5  412.55  5006.2  412.55
  5007.2  411.65  5007.7  410.85  5012.7  410.85  5013.2  411.65  5016.6  414.33
  5088.8  414.45  5159.1  417.65  5181.5  419.12  5187.9  420.11  5231.1  422.41
  5245.5  423.76  5272.7  425.44  5280.7  425.54  5287.1  424.98  5323.1  425.70
#Mann=3,-1,0
  4698.9    0.05       0  5007.2    0.03       0  5013.2    0.05       0
Bank Sta=4963.9,5088.8
Exp/Cntr=0.3,0.1

Type RM Length L Ch R = 1,1271,214,214,214
BEGIN DESCRIPTION:
Mapping XS bb7848f2
END DESCRIPTION:
XS GIS Cut Line= 3
      2919237.95      7005969.70      2919295.24      7006266.60
      2919553.06      7006493.17
#Sta/Elev= 30
  4713.2  426.05  4723.9  425.14  4739.0  424.99  4759.3  423.98  4827.6  418.29
  4871.4  415.73  4891.7  413.94  4922.3  413.13  4963.0  413.29  4988.2  413.08
  4989.9  412.67  5000.8  410.80  5001.3  410.00  5006.3  410.00  5006.8  410.80
  5012.2  411.74  5018.1  411.74  5021.1  412.67  5056.4  413.07  5078.2  414.61
  5084.9  414.02  5099.1  414.24  5170.3  417.39  5213.0  420.07  5305.0  421.85
  5311.7  422.39  5319.2  422.20  5333.5  422.74  5340.1  423.63  5358.8  423.70
#Mann=3,-1,0
  4713.2    0.05       0  5000.8    0.03       0  5006.8    0.05       0
Bank Sta=4989.9,5021.1
Exp/Cntr=0.3,0.1

Type RM Length L Ch R = 1,1057,193,193,193
BEGIN DESCRIPTION:
UNT 056 IN DRY CR WATERSHED 2.0
END DESCRIPTION:
XS GIS Cut Line= 3
      2919125.00      7006074.96      2919125.00      7006375.00
      2919125.00      7006674.96
#Sta/Elev= 30
  4705.2  423.91  4745.2  422.39  4775.2  419.11  4795.2  417.88  4815.2  415.82
  4855.2  414.95  4875.2  413.63  4902.1  411.40  4915.2  410.35  4925.2  410.03
  4935.2  410.87  4945.2  411.32  4965.2  410.94  5007.7  410.79  5012.2  408.84
  5012.7  408.04  5017.7  408.04  5018.2  408.84  5025.2  410.71  5035.2  410.52
  5060.4  411.40  5115.2  413.81  5135.2  414.07  5155.2  415.37  5165.2  415.63
  5175.2  416.99  5195.2  417.73  5225.2  419.56  5265.2  420.66  5305.2  422.16
#Mann=3,-1,0
  4705.2    0.05       0  5012.2    0.03       0  5018.2    0.05       0
Bank Sta=4902.1,5060.4
Exp/Cntr=0.3,0.1

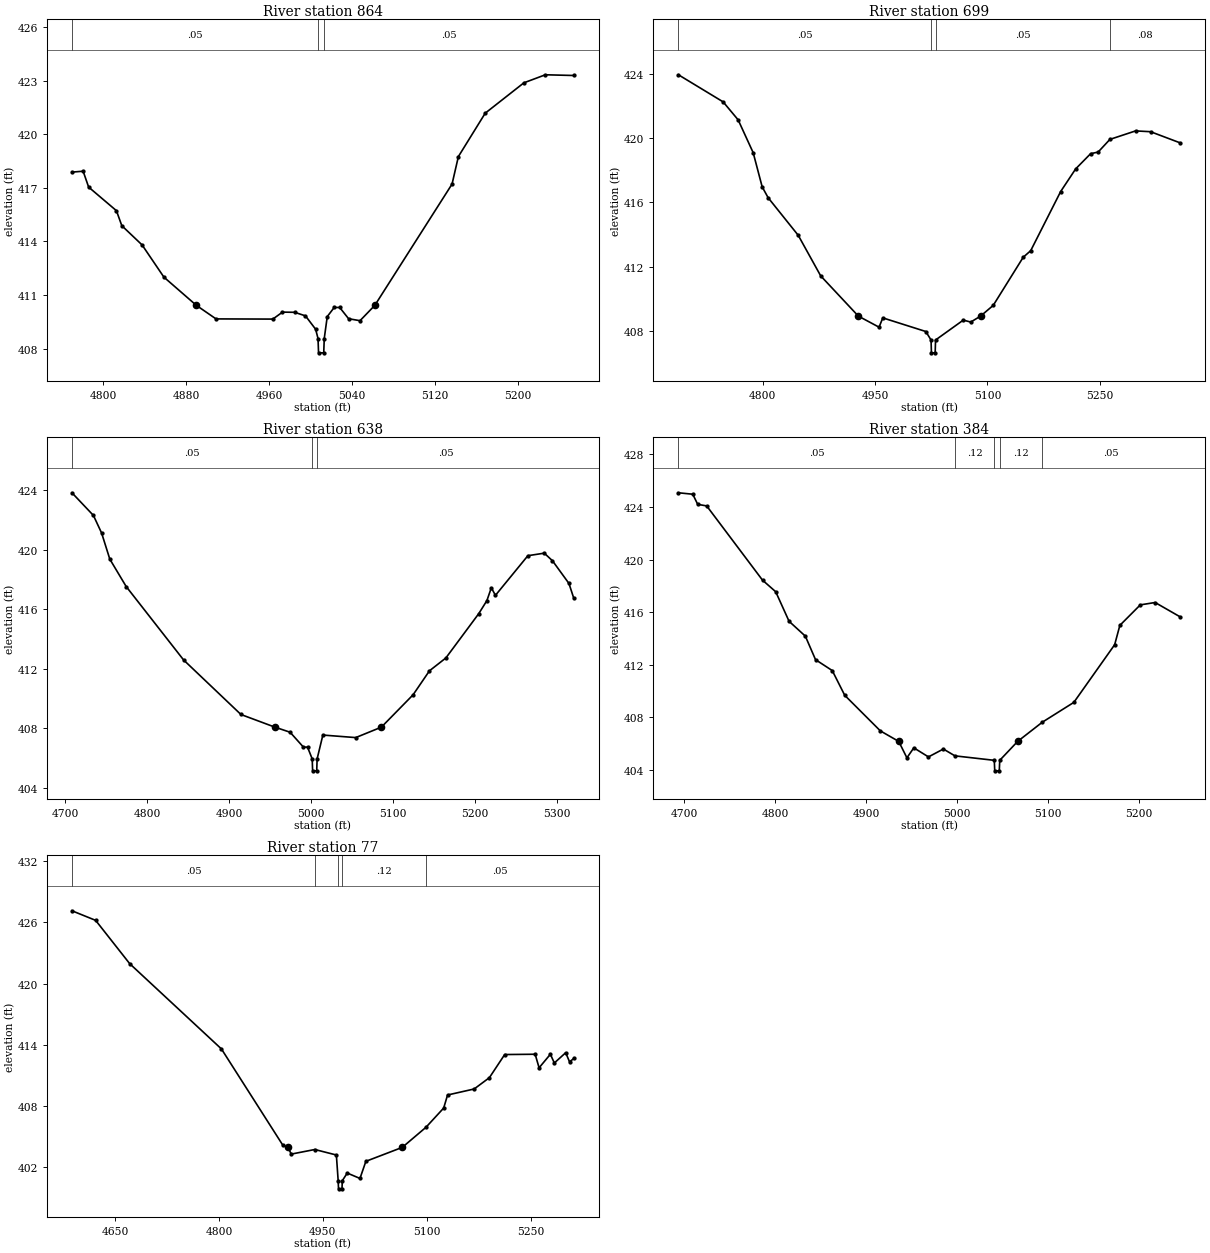
Type RM Length L Ch R = 1,864,165,165,165
BEGIN DESCRIPTION:
Mapping XS c15600fc
END DESCRIPTION:
XS GIS Cut Line= 3
      2918886.40      7006240.59      2918964.51      7006482.74
      2919037.17      7006700.71
#Sta/Elev= 30
  4769.7  417.88  4780.5  417.93  4785.8  417.04  4812.6  415.72  4817.8  414.88
  4837.4  413.80  4858.4  412.00  4889.7  410.42  4908.7  409.66  4963.5  409.65
  4972.8  410.04  4984.5  410.03  4995.0  409.83  5004.8  409.08  5007.1  408.56
  5007.6  407.76  5012.6  407.76  5013.1  408.56  5016.0  409.79  5022.7  410.30
  5028.0  410.30  5036.6  409.67  5047.6  409.56  5061.9  410.42  5136.4  417.21
  5142.5  418.75  5168.4  421.18  5205.7  422.88  5226.4  423.33  5253.9  423.29
#Mann=3,-1,0
  4769.7    0.05       0  5007.1    0.03       0  5013.1    0.05       0
Bank Sta=4889.7,5061.9
Exp/Cntr=0.3,0.1

Type RM Length L Ch R = 1,699,61,61,61
BEGIN DESCRIPTION:
Mapping XS 98120e79
END DESCRIPTION:
XS GIS Cut Line= 3
      2918826.72      7006205.42      2918808.49      7006499.67
      2918816.31      7006874.67
#Sta/Elev= 30
  4687.5  423.96  4747.2  422.27  4767.2  421.15  4787.3  419.10  4799.3  416.97
  4807.3  416.29  4847.4  413.95  4877.4  411.42  4927.7  408.91  4955.3  408.22
  4960.3  408.80  5017.7  407.95  5024.7  407.42  5025.2  406.62  5030.2  406.62
  5030.7  407.42  5067.7  408.66  5077.7  408.54  5090.8  408.91  5107.7  409.58
  5147.7  412.58  5157.7  412.99  5197.7  416.68  5217.7  418.09  5237.7  419.04
  5247.7  419.14  5263.4  419.93  5297.7  420.46  5317.7  420.41  5357.4  419.71
#Mann=4,-1,0
  4687.5    0.05       0  5024.7    0.03       0  5030.7    0.05       0
  5263.4    0.08       0
Bank Sta=4927.7,5090.8
Exp/Cntr=0.3,0.1

Type RM Length L Ch R = 1,638,254,254,254
BEGIN DESCRIPTION:
Mapping XS 7ddbaaea
END DESCRIPTION:
XS GIS Cut Line= 3
      2918756.41      7006258.80      2918759.02      7006542.64
      2918746.04      7006871.04
#Sta/Elev= 30
  4708.3  423.81  4734.5  422.29  4744.5  421.11  4754.5  419.36  4774.5  417.52
  4844.5  412.60  4914.5  408.94  4956.0  408.09  4974.5  407.75  4990.8  406.75
  4995.8  406.75  5001.5  405.96  5002.0  405.16  5007.0  405.16  5007.5  405.96
  5014.5  407.56  5054.6  407.39  5085.9  408.09  5124.6  410.26  5144.6  411.87
  5164.6  412.73  5204.7  415.70  5214.7  416.58  5220.1  417.44  5225.1  416.93
  5264.7  419.59  5284.7  419.76  5294.7  419.25  5314.8  417.73  5320.8  416.72
#Mann=3,-1,0
  4708.3    0.05       0  5001.5    0.03       0  5007.5    0.05       0
Bank Sta=4956,5085.9
Exp/Cntr=0.3,0.1

Type RM Length L Ch R = 1,384,307,307,307
BEGIN DESCRIPTION:
Mapping XS 470031e5
END DESCRIPTION:
XS GIS Cut Line= 3
      2918433.48      7006396.34      2918559.36      7006695.85
      2918659.19      7006899.85
#Sta/Elev= 30
  4693.6  425.08  4709.4  424.97  4714.8  424.20  4724.7  424.08  4786.1  418.43
  4800.6  417.55  4815.3  415.30  4833.2  414.17  4844.4  412.38  4862.8  411.55
  4876.5  409.67  4915.7  406.96  4935.9  406.16  4944.9  404.91  4952.5  405.67
  4968.6  404.98  4985.0  405.58  4997.7  405.06  5041.0  404.72  5041.5  403.92
  5046.5  403.92  5047.0  404.72  5066.7  406.16  5093.8  407.62  5128.5  409.13
  5173.4  413.52  5179.1  414.99  5201.6  416.55  5217.9  416.73  5245.6  415.63
#Mann=5,-1,0
  4693.6    0.05       0  4997.7    0.12       0  5041.0    0.07       0
  5047.0    0.12       0  5093.8    0.05       0
Bank Sta=4935.9,5066.7
Exp/Cntr=0.3,0.1

Type RM Length L Ch R = 1,77,0,0,0
BEGIN DESCRIPTION:
UNT 056 IN DRY CR WATERSHED 1.0
END DESCRIPTION:
XS GIS Cut Line= 3
      2918248.16      7006421.10      2918304.21      7006829.57
      2918580.72      7006975.39
#Sta/Elev= 30
  4587.7  427.14  4621.9  426.20  4671.1  421.95  4803.6  413.58  4892.4  404.12
  4899.6  403.92  4904.5  403.26  4938.5  403.71  4969.6  403.17  4972.2  400.65
  4972.7  399.85  4977.7  399.85  4978.2  400.65  4985.3  401.40  5003.7  400.87
  5012.2  402.55  5064.8  403.92  5099.0  405.89  5124.6  407.78  5130.2  409.06
  5168.6  409.65  5190.6  410.76  5212.7  413.03  5256.7  413.06  5262.4  411.73
  5278.7  413.06  5284.4  412.20  5300.8  413.21  5306.4  412.31  5312.6  412.65
#Mann=5,-1,0
  4587.7    0.05       0  4938.5    0.12       0  4972.2    0.07       0
  4978.2    0.12       0  5099.0    0.05       0
Bank Sta=4899.6,5064.8
Exp/Cntr=0.3,0.1

Chan Stop Cuts=-1