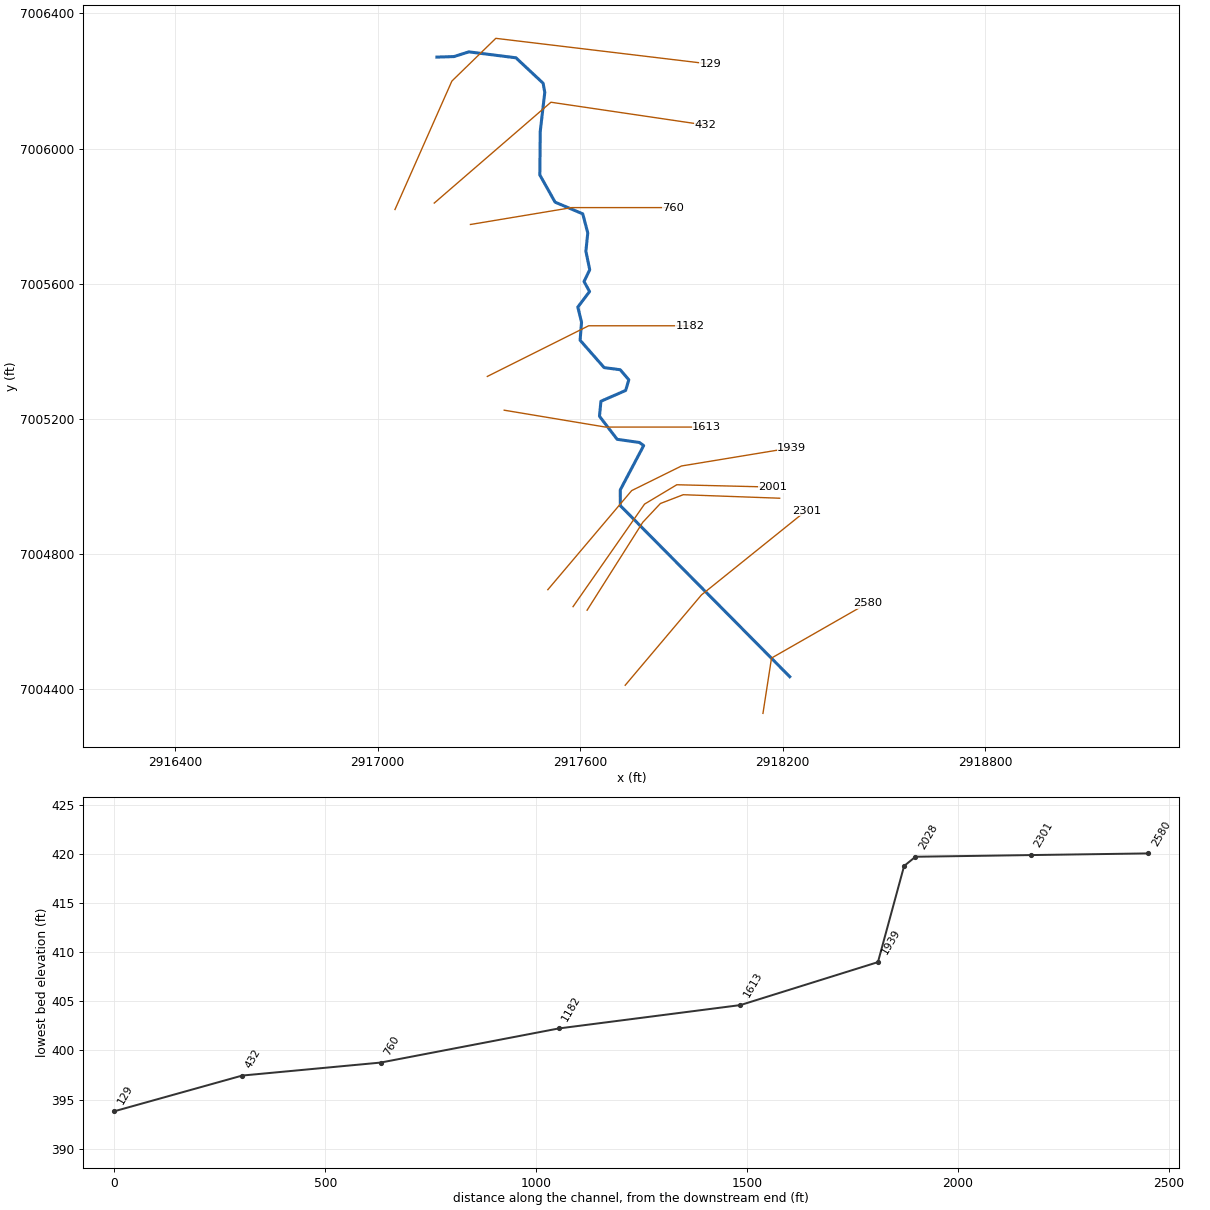
--- UNT 057 IN DRY CR WATERSHED.prj (project) ---

Proj Title=UNT 057 IN DRY CR WATERSHED Base Level Engineering
Current Plan=p01
Default Exp/Contr=0.3,0.1
English Units
Geom File=g01
Flow File=f01
Plan File=p01
BEGIN DESCRIPTION:
UNT 057 IN DRY CR WATERSHED
END DESCRIPTION:

--- UNT 057 IN DRY CR WATERSHED.p01 (plan) ---

Plan Title=Multiple Run
Short Identifier=Multiple
Geom File=g01
Flow File=f01
Subcritical Flow
K Sum by GR= 0
Std Step Tol= 0.01
Critical Tol= 0.01
Num of Std Step Trials= 20
Max Error Tol= 0.3
Flow Tol Ratio= 0.001
Split Flow NTrial= 30
Split Flow Tol= 0.02
Split Flow Ratio= 0.02
Log Output Level= 0
Friction Slope Method= 1
Unsteady Friction Slope Method= 2
Unsteady Bridges Friction Slope Method= 1
Parabolic Critical Depth
Global Vel Dist=  1 , 1 , 1
Global Log Level= 0
CheckData=True
Encroach Param= -1, 0, 0, 0
BEGIN DESCRIPTION:
Multiple Run
END DESCRIPTION:

--- UNT 057 IN DRY CR WATERSHED.f01 (steady flow) ---

Flow Title=Multiple
Number of Profiles=7
Profile Names=10-year,25-year,50-year,1pct_min,100-year,1pct_plu,500-year
River Rch & RM= UNT 057 IN DRY C,Reach-1,2580
     246     315     369     215     430     857     583
Boundary for River Rch & Prof#=UNT 057 IN DRY C,Reach-1,1
Up Type=0
Dn Type=3
Dn Slope=0.005
Boundary for River Rch & Prof#=UNT 057 IN DRY C,Reach-1,2
Up Type=0
Dn Type=3
Dn Slope=0.005
Boundary for River Rch & Prof#=UNT 057 IN DRY C,Reach-1,3
Up Type=0
Dn Type=3
Dn Slope=0.005
Boundary for River Rch & Prof#=UNT 057 IN DRY C,Reach-1,4
Up Type=0
Dn Type=3
Dn Slope=0.005
Boundary for River Rch & Prof#=UNT 057 IN DRY C,Reach-1,5
Up Type=0
Dn Type=3
Dn Slope=0.005
Boundary for River Rch & Prof#=UNT 057 IN DRY C,Reach-1,6
Up Type=0
Dn Type=3
Dn Slope=0.005
Boundary for River Rch & Prof#=UNT 057 IN DRY C,Reach-1,7
Up Type=0
Dn Type=3
Dn Slope=0.005

--- UNT 057 IN DRY CR WATERSHED.g01 (geometry) ---

Geom Title=Existing Conditions

River Reach=UNT 057 IN DRY C,Reach-1
Reach XY= 30
      2918220.59      7004435.71      2917718.80      7004942.31
      2917718.74      7004989.04      2917787.98      7005120.19
      2917775.32      7005129.38      2917709.52      7005138.66
      2917657.12      7005207.00      2917661.41      7005251.45
      2917734.61      7005283.45      2917743.98      7005314.95
      2917718.51      7005344.80      2917670.90      7005351.12
      2917599.77      7005432.17      2917603.94      7005485.53
      2917592.95      7005530.44      2917627.84      7005576.45
      2917611.39      7005606.03      2917628.25      7005640.90
      2917616.85      7005695.85      2917622.45      7005749.87
      2917607.55      7005806.49      2917525.64      7005841.10
      2917480.46      7005921.62      2917481.68      7006050.72
      2917495.11      7006166.16      2917490.19      7006193.32
      2917409.74      7006268.63      2917270.40      7006286.24
      2917226.01      7006272.28      2917175.59      7006270.71

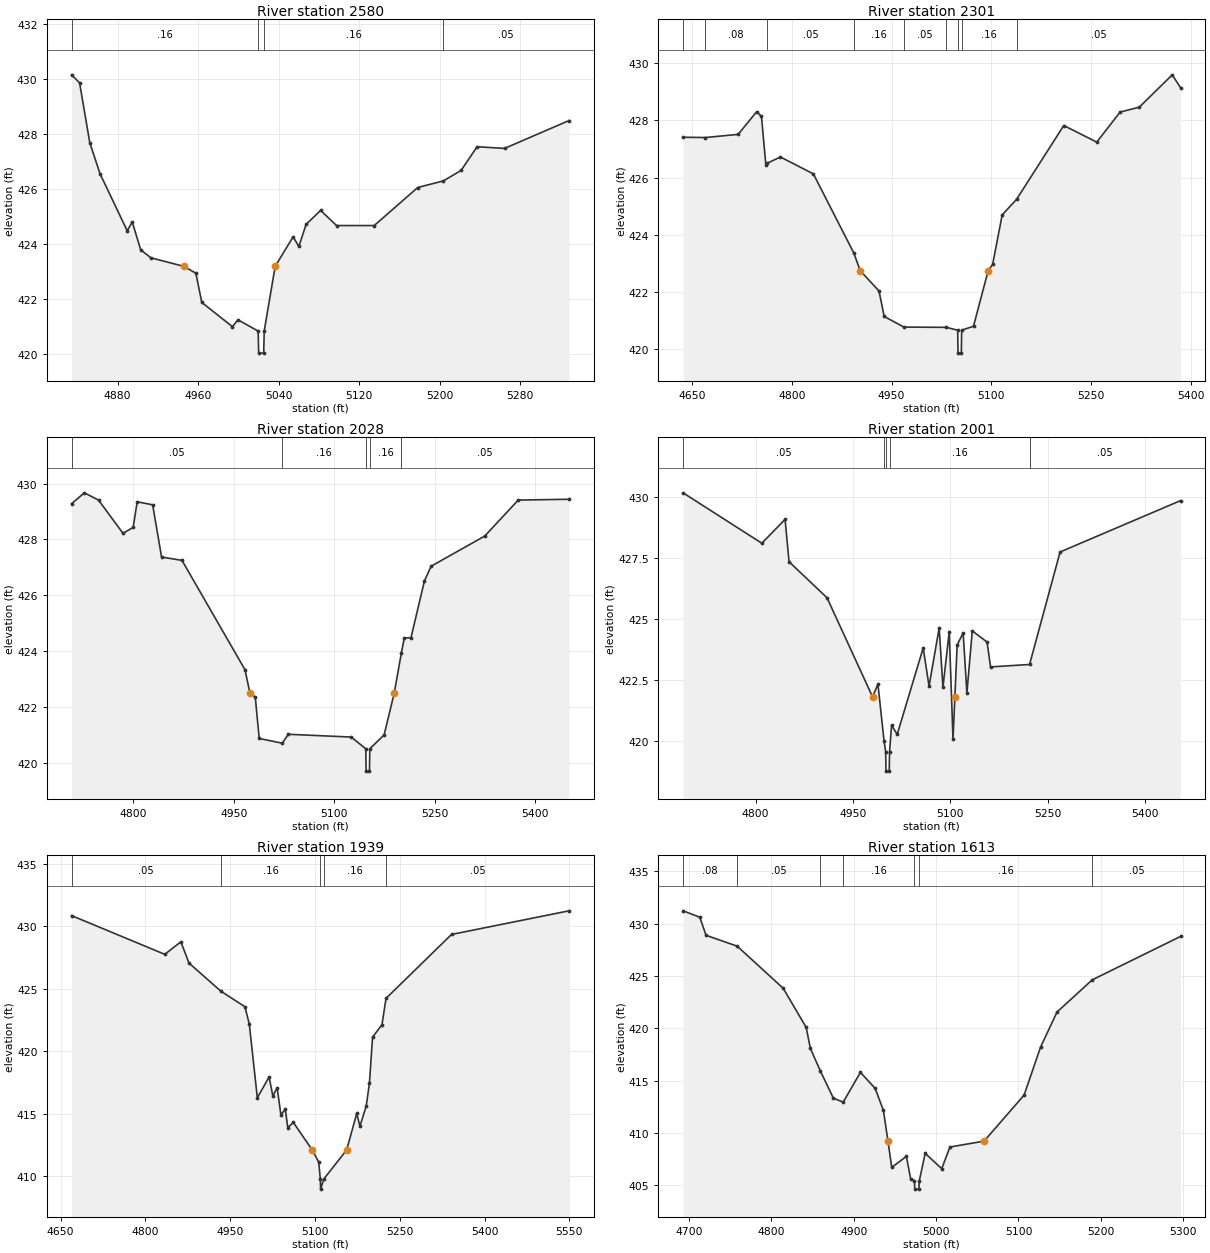
Type RM Length L Ch R = 1,2580,279,279,279
BEGIN DESCRIPTION:
UNT 057 IN DRY CR WATERSHED 6.0
END DESCRIPTION:
XS GIS Cut Line= 3
      2918141.30      7004327.08      2918166.58      7004490.84
      2918451.72      7004653.96
#Sta/Elev= 30
  4834.3  430.14  4842.3  429.85  4852.4  427.68  4862.6  426.55  4889.6  424.48
  4894.6  424.80  4903.0  423.79  4913.1  423.50  4945.8  423.19  4957.8  422.94
  4963.7  421.88  4994.1  421.00  4999.6  421.25  5019.7  420.84  5020.2  420.04
  5025.2  420.04  5025.7  420.84  5036.6  423.19  5054.4  424.26  5060.1  423.91
  5067.3  424.71  5081.7  425.22  5097.6  424.67  5135.0  424.67  5178.2  426.05
  5203.6  426.29  5221.3  426.67  5237.2  427.53  5264.5  427.47  5328.5  428.48
#Mann=4,-1,0
  4834.3    0.16       0  5019.7    0.07       0  5025.7    0.16       0
  5203.6    0.05       0
Bank Sta=4945.8,5036.6
Exp/Cntr=0.3,0.1

Type RM Length L Ch R = 1,2301,273,273,273
BEGIN DESCRIPTION:
Mapping XS 79becc5b
END DESCRIPTION:
XS GIS Cut Line= 3
      2917733.32      7004410.44      2917959.02      7004677.80
      2918269.76      7004927.78
#Sta/Elev= 30
  4636.3  427.41  4669.8  427.40  4719.2  427.51  4747.0  428.30  4754.3  428.14
  4760.9  426.44  4762.6  426.50  4782.9  426.72  4832.4  426.13  4893.2  423.37
  4902.9  422.75  4931.2  422.04  4939.0  421.15  4968.7  420.78  5032.5  420.77
  5049.6  420.67  5050.1  419.87  5055.1  419.87  5055.6  420.67  5073.4  420.81
  5095.5  422.75  5102.2  422.97  5116.6  424.70  5138.2  425.24  5209.3  427.82
  5258.9  427.24  5294.1  428.29  5322.9  428.46  5372.5  429.59  5385.0  429.14
#Mann=9,-1,0
  4636.3    0.05       0  4669.8    0.08       0  4762.6    0.05       0
  4893.2    0.16       0  4968.7    0.05       0  5032.5    0.16       0
  5049.6   0.033       0  5055.6    0.16       0  5138.2    0.05       0
Bank Sta=4902.9,5095.5
Exp/Cntr=0.3,0.1

Type RM Length L Ch R = 1,2028,27,27,27
BEGIN DESCRIPTION:
Mapping XS 983fc86f
END DESCRIPTION:
XS GIS Cut Line= 5
      2917620.49      7004632.68      2917785.41      7004893.08
      2917837.49      7004948.63      2917905.20      7004974.68
      2918190.78      7004964.29
#Sta/Elev= 30
  4708.0  429.28  4727.1  429.67  4748.3  429.41  4784.8  428.22  4800.0  428.43
  4806.0  429.35  4829.1  429.24  4842.4  427.37  4872.9  427.25  4967.0  423.33
  4974.3  422.50  4982.3  422.35  4988.2  420.87  5022.7  420.70  5031.6  421.02
  5125.6  420.92  5147.3  420.50  5147.8  419.70  5152.8  419.70  5153.3  420.50
  5174.7  421.00  5189.8  422.50  5200.4  423.93  5204.8  424.47  5214.8  424.48
  5234.8  426.51  5244.8  427.04  5324.8  428.12  5374.9  429.41  5450.7  429.44
#Mann=5,-1,0
  4708.0    0.05       0  5022.7    0.16       0  5147.3   0.033       0
  5153.3    0.16       0  5200.4    0.05       0
Bank Sta=4974.3,5189.8
Exp/Cntr=0.3,0.1

Type RM Length L Ch R = 1,2001,62,62,62
BEGIN DESCRIPTION:
Mapping XS 5f5d7188
END DESCRIPTION:
XS GIS Cut Line= 4
      2917578.83      7004643.11      2917790.61      7004946.90
      2917886.10      7005004.19      2918170.43      7004997.25
#Sta/Elev= 30
  4688.4  430.19  4809.7  428.12  4845.5  429.10  4851.6  427.36  4910.1  425.88
  4980.2  421.81  4988.5  422.33  4997.9  420.00  5000.4  419.56  5000.9  418.76
  5005.9  418.76  5006.4  419.56  5009.5  420.64  5018.2  420.27  5058.2  423.82
  5067.2  422.25  5082.8  424.64  5088.6  422.20  5098.3  424.49  5104.1  420.07
  5107.0  421.81  5110.5  423.94  5119.7  424.44  5125.5  421.97  5133.8  424.52
  5156.6  424.06  5161.9  423.04  5222.0  423.14  5269.0  427.76  5454.5  429.87
#Mann=5,-1,0
  4688.4    0.05       0  4997.9    0.16       0  5000.4    0.07       0
  5006.4    0.16       0  5222.0    0.05       0
Bank Sta=4980.2,5107
Exp/Cntr=0.3,0.1

Type RM Length L Ch R = 1,1939,326,326,326
BEGIN DESCRIPTION:
Mapping XS 39caac21
END DESCRIPTION:
XS GIS Cut Line= 4
      2917504.14      7004693.41      2917752.42      7004986.83
      2917899.99      7005059.75      2918226.41      7005113.57
#Sta/Elev= 30
  4669.5  430.86  4834.4  427.76  4862.9  428.76  4877.2  427.06  4933.7  424.81
  4976.1  423.57  4983.8  422.20  4998.1  416.29  5018.9  417.95  5025.5  416.43
  5033.2  417.08  5039.8  414.91  5047.5  415.38  5052.0  413.89  5061.7  414.32
  5095.2  412.11  5106.6  411.15  5109.5  409.78  5110.0  408.98  5115.5  409.78
  5156.0  412.11  5173.9  415.03  5179.5  414.01  5190.6  415.61  5196.3  417.43
  5201.9  421.14  5218.5  422.13  5225.7  424.24  5341.5  429.35  5549.3  431.24
#Mann=5,-1,0
  4669.5    0.05       0  4933.7    0.16       0  5109.5    0.07       0
  5115.5    0.16       0  5225.7    0.05       0
Bank Sta=5095.2,5156
Exp/Cntr=0.3,0.1

Type RM Length L Ch R = 1,1613,431,431,431
BEGIN DESCRIPTION:
UNT 057 IN DRY CR WATERSHED 4.0
END DESCRIPTION:
XS GIS Cut Line= 3
      2917375.01      7005225.00      2917675.00      7005175.00
      2917974.97      7005175.00
#Sta/Elev= 30
  4692.7  431.23  4713.0  430.62  4720.6  428.89  4758.4  427.85  4814.3  423.82
  4842.2  420.08  4847.3  418.07  4859.2  415.95  4875.2  413.31  4887.1  412.93
  4908.1  415.78  4925.9  414.25  4936.0  412.14  4941.5  409.20  4946.1  406.69
  4963.9  407.74  4969.0  405.62  4973.6  405.41  4974.1  404.61  4979.1  404.61
  4979.6  405.41  4986.7  408.03  5006.8  406.57  5016.8  408.64  5058.2  409.20
  5106.8  413.60  5126.8  418.19  5146.8  421.55  5189.6  424.63  5296.8  428.78
#Mann=7,-1,0
  4692.7    0.08       0  4758.4    0.05       0  4859.2    0.12       0
  4887.1    0.16       0  4973.6    0.07       0  4979.6    0.16       0
  5189.6    0.05       0
Bank Sta=4941.5,5058.2
Exp/Cntr=0.3,0.1

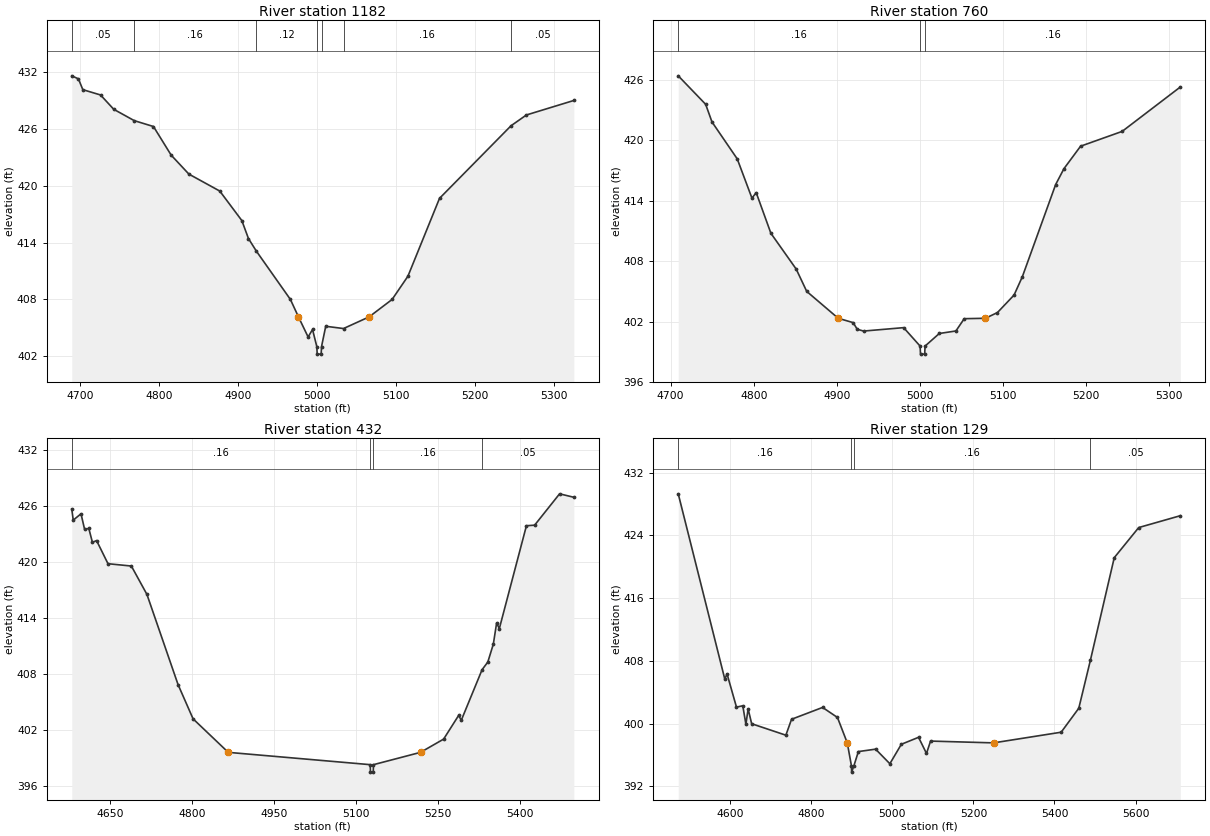
Type RM Length L Ch R = 1,1182,422,422,422
BEGIN DESCRIPTION:
UNT 057 IN DRY CR WATERSHED 3.0
END DESCRIPTION:
XS GIS Cut Line= 3
      2917324.99      7005324.99      2917625.00      7005475.00
      2917924.97      7005475.00
#Sta/Elev= 30
  4689.8  431.60  4698.2  431.28  4703.8  430.14  4726.2  429.58  4742.9  428.07
  4768.9  426.87  4793.2  426.25  4815.6  423.23  4838.0  421.23  4877.1  419.44
  4905.0  416.33  4913.4  414.43  4923.4  413.10  4966.5  408.00  4976.7  406.16
  4988.9  404.04  4994.5  404.83  4999.9  403.03  5000.4  402.23  5005.4  402.23
  5005.9  403.03  5011.2  405.17  5033.7  404.93  5066.1  406.16  5095.2  408.00
  5115.2  410.45  5155.2  418.67  5245.7  426.33  5265.2  427.47  5325.2  429.00
#Mann=7,-1,0
  4689.8    0.05       0  4768.9    0.16       0  4923.4    0.12       0
  4999.9    0.07       0  5005.9    0.12       0  5033.7    0.16       0
  5245.7    0.05       0
Bank Sta=4976.7,5066.1
Exp/Cntr=0.3,0.1

Type RM Length L Ch R = 1,760,328,328,328
BEGIN DESCRIPTION:
UNT 057 IN DRY CR WATERSHED 2.0
END DESCRIPTION:
XS GIS Cut Line= 3
      2917275.00      7005775.00      2917575.00      7005825.00
      2917874.96      7005825.00
#Sta/Elev= 30
  4709.1  426.40  4742.1  423.57  4749.7  421.82  4780.1  418.15  4797.8  414.25
  4802.9  414.80  4820.6  410.76  4851.0  407.21  4863.7  404.99  4901.6  402.32
  4919.5  401.89  4924.5  401.23  4932.1  401.05  4980.3  401.39  5000.1  399.56
  5000.6  398.76  5005.6  398.76  5006.1  399.56  5023.2  400.81  5043.2  401.06
  5053.2  402.28  5078.7  402.32  5093.2  402.89  5113.2  404.63  5123.2  406.46
  5163.2  415.60  5173.2  417.18  5193.2  419.41  5243.2  420.88  5313.2  425.29
#Mann=3,-1,0
  4709.1    0.16       0  5000.1    0.07       0  5006.1    0.16       0
Bank Sta=4901.6,5078.7
Exp/Cntr=0.3,0.1

Type RM Length L Ch R = 1,432,303,303,303
BEGIN DESCRIPTION:
Mapping XS 1fd0e141
END DESCRIPTION:
XS GIS Cut Line= 3
      2917167.79      7005838.43      2917513.30      7006137.06
      2917970.85      7006069.47
#Sta/Elev= 30
  4579.5  425.64  4582.2  424.45  4596.4  425.13  4603.0  423.46  4610.7  423.56
  4617.3  422.07  4624.9  422.26  4645.8  419.78  4688.6  419.53  4717.1  416.49
  4774.1  406.82  4801.6  403.15  4866.0  399.56  5125.9  398.24  5126.4  397.44
  5131.4  397.44  5131.9  398.24  5218.0  399.56  5260.3  400.98  5287.7  403.51
  5292.7  403.01  5330.7  408.42  5341.2  409.24  5351.3  411.16  5357.3  413.42
  5362.3  412.83  5411.9  423.85  5426.9  423.91  5472.6  427.27  5498.7  426.90
#Mann=4,-1,0
  4579.5    0.16       0  5125.9    0.07       0  5131.9    0.16       0
  5330.7    0.05       0
Bank Sta=4866,5218
Exp/Cntr=0.3,0.1

Type RM Length L Ch R = 1,129,0,0,0
BEGIN DESCRIPTION:
UNT 057 IN DRY CR WATERSHED 1.0
END DESCRIPTION:
XS GIS Cut Line= 4
      2917051.49      7005819.34      2917219.96      7006199.71
      2917350.10      7006326.30      2917986.88      7006249.95
#Sta/Elev= 30
  4471.6  429.30  4586.5  405.67  4592.0  406.34  4615.3  402.10  4630.9  402.27
  4638.6  399.90  4644.0  401.88  4652.8  399.98  4737.2  398.52  4751.2  400.55
  4827.8  402.06  4864.5  400.78  4888.7  397.54  4899.0  394.61  4899.5  393.81
  4905.0  394.61  4916.1  396.43  4958.6  396.74  4993.8  394.88  5022.1  397.36
  5064.6  398.25  5084.2  396.19  5094.2  397.77  5249.6  397.54  5416.5  398.90
  5460.0  401.96  5488.6  408.07  5547.5  421.16  5607.9  425.00  5710.5  426.51
#Mann=4,-1,0
  4471.6    0.16       0  4899.0    0.07       0  4905.0    0.16       0
  5488.6    0.05       0
Bank Sta=4888.7,5249.6
Exp/Cntr=0.3,0.1

Chan Stop Cuts=-1