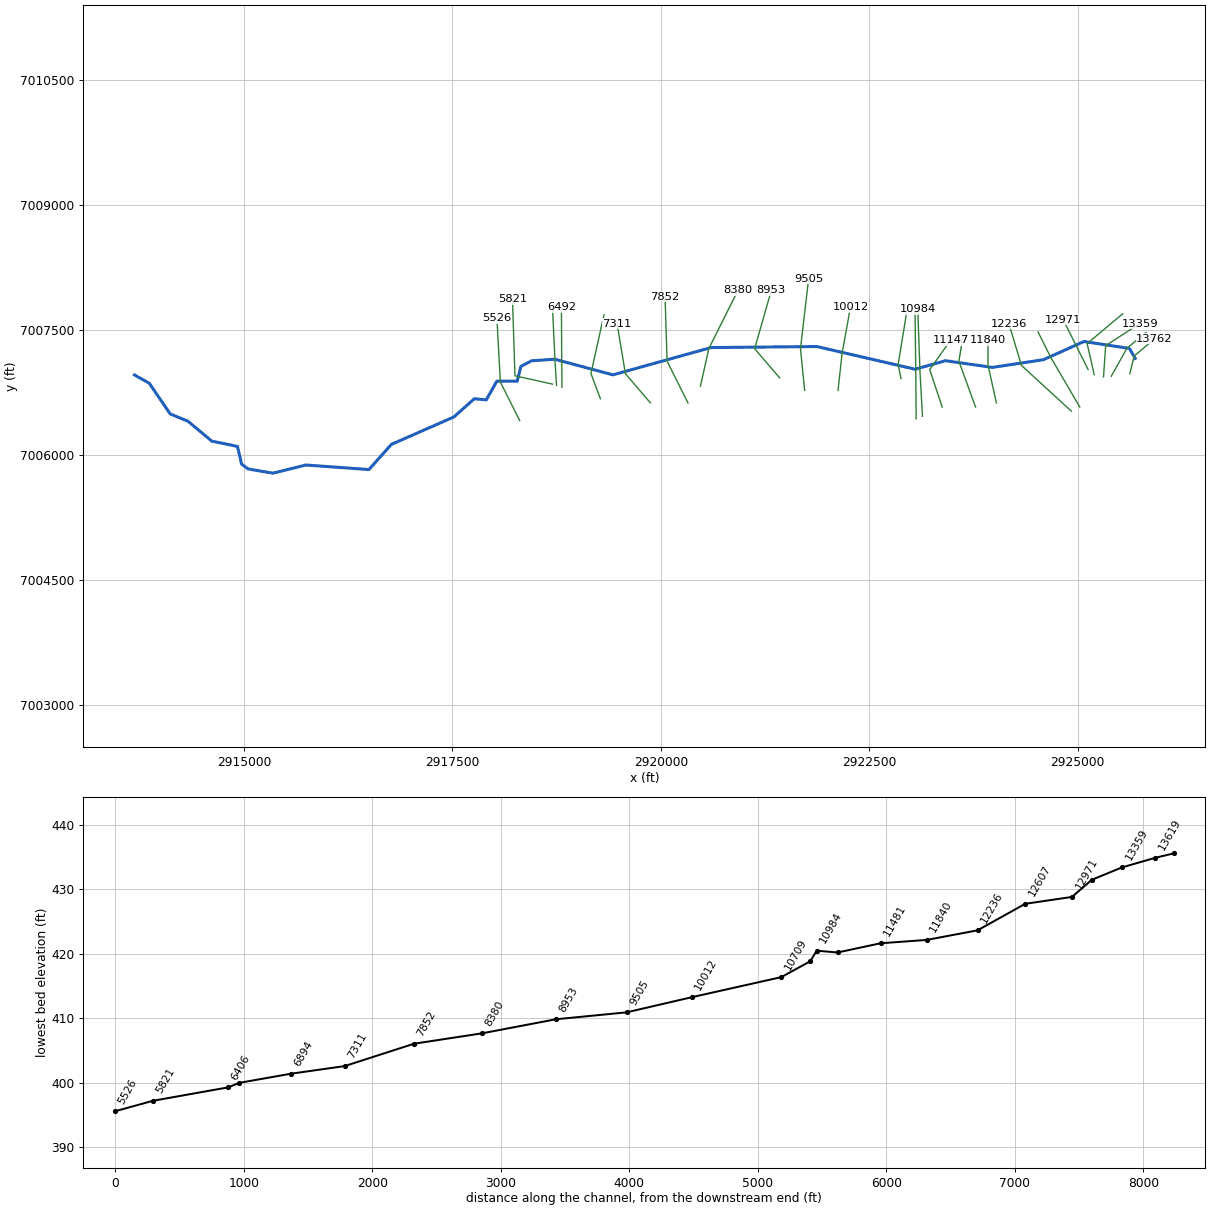
--- UNT 058 IN DRY CR WATERSHED.prj (project) ---

Proj Title=UNT 058 IN DRY CR WATERSHED Base Level Engineering
Current Plan=p01
Default Exp/Contr=0.3,0.1
English Units
Geom File=g01
Flow File=f01
Plan File=p01
Y Axis Title=Elevation
X Axis Title(PF)=Main Channel Distance
X Axis Title(XS)=Station
BEGIN DESCRIPTION:
UNT 058 IN DRY CR WATERSHED
END DESCRIPTION:
DSS File=dss
DSS Export Rating Curves= 0
DSS Export Rating Curve Sorted= 0
DSS Export Volume Flow Curves= 0
DXF OffsetX= 0
DXF OffsetY= 0
DXF ScaleX= 1
DXF ScaleY= 10

--- UNT 058 IN DRY CR WATERSHED.p01 (plan) ---

Plan Title=Multiple Run
Program Version=5.07
Short Identifier=Multiple Run
Geom File=g01
Flow File=f01
Subcritical Flow
K Sum by GR= 0
Std Step Tol= 0.01
Critical Tol= 0.01
Num of Std Step Trials= 20
Max Error Tol= 0.3
Flow Tol Ratio= 0.001
Split Flow NTrial= 30
Split Flow Tol= 0.02
Split Flow Ratio= 0.02
Log Output Level= 0
Friction Slope Method= 1
Unsteady Friction Slope Method= 2
Unsteady Bridges Friction Slope Method= 1
Parabolic Critical Depth
Global Vel Dist= 1 , 1 , 1
Global Log Level= 0
CheckData=True
Encroach Param=-1 ,0,0, 0
BEGIN DESCRIPTION:
Multiple Run
END DESCRIPTION:
Computation Interval=1MIN
Output Interval=1HOUR
Instantaneous Interval=1HOUR
Mapping Interval=1HOUR
Computation Time Step Use Courant=        0
Computation Time Step Use Time Series=    0
Computation Time Step Count To Double=0
Computation Time Step Max Doubling=0
Computation Time Step Max Halving=0
Computation Time Step Residence Courant=0
Run HTab= 0
Run UNet= 0
Run Sediment= 0
Run PostProcess= 0
Run WQNet= 0
Run RASMapper= 0
UNET Theta= 1
UNET Theta Warmup= 1
UNET ZTol= 0.02
UNET ZSATol= 0.02
UNET MxIter= 20
UNET Max Iter WO Improvement= 0
UNET MaxInSteps= 0
UNET DtIC= 0
UNET DtMin= 0
UNET MaxCRTS= 20
UNET WFStab= 2
UNET SFStab= 1
UNET WFX= 1
UNET SFX= 1
UNET 1D Methodology=Finite Difference
UNET DSS MLevel= 4
UNET Pardiso=0
UNET DZMax Abort= 100
UNET Use Existing IB Tables=-1
UNET Froude Reduction=False
UNET Froude Limit= 0.8
UNET Froude Power= 4
UNET D1 Cores= 0
UNET D2 Coriolis=0
UNET D2 Cores= 0
UNET D2 Theta= 1
UNET D2 Theta Warmup= 1
UNET D2 Z Tol= 0.01
UNET D2 Volume Tol= 0.01
UNET D2 Max Iterations= 20
UNET D2 Equation= 0
UNET D2 RampUpFraction=0.1
UNET D2 TimeSlices= 1
UNET D2 BCVolumeCheck=0
UNET D1D2 MaxIter= 0
UNET D1D2 ZTol=0.01
UNET D1D2 QTol=0.1
UNET D1D2 MinQTol=1
DSS File=dss
Write IC File= 0
Write IC File at Fixed DateTime=0
Write IC File at Sim End=0
Echo Input=False
Echo Parameters=False
Echo Output=False
Write Detailed= 0
HDF Write Warmup=0
HDF Write Time Slices=0
HDF Flush=0
HDF Face Node Velocities=0
HDF Compression= 1
HDF Chunk Size= 1
HDF Spatial Parts= 1
HDF Use Max Rows=0
HDF Fixed Rows= 1
Calibration Method= 0
Calibration Iterations= 20
Calibration Max Change=0.05
Calibration Tolerance=0.2
Calibration Maximum=1.5
Calibration Minimum=0.5
Calibration Optimization Method= 1
WQ AD Non Conservative
WQ ULTIMATE=-1
WQ Max Comp Step=1HOUR
WQ Output Interval=15MIN
WQ Output Selected Increments= 0
WQ Output face flow=0
WQ Output face velocity=0
WQ Output face area=0
WQ Output face dispersion=0
WQ Output cell volume=0
WQ Output cell surface area=0
WQ Output cell continuity=0
WQ Output cumulative cell continuity=0
WQ Output face conc=0
WQ Output face dconc_dx=0
WQ Output face courant=0
WQ Output face peclet=0
WQ Output face adv mass=0
WQ Output face disp mass=0
WQ Output cell mass=0
WQ Output cell source sink temp=0
WQ Output nsm pathways=0
WQ Output nsm derived pathways=0
WQ Output MaxMinRange=-1
WQ Daily Max Min Mean=-1
WQ Daily Range=0
WQ Daily Time=0
WQ Create Restart=0
WQ Fixed Restart=0
WQ System Summary=0
WQ Write To DSS=0
WQ Use Fixed Temperature=0
Sorting and Armoring Iterations= 10
XS Update Threshold= 0.02
Bed Roughness Predictor= 0
Hydraulics Update Threshold= 0.02
Energy Slope Method= 1
Volume Change Method= 1
Sediment Retention Method= 0
XS Weighting Method= 0
Number of US Weighted Cross Sections= 1
Number of DS Weighted Cross Sections= 1
Upstream XS Weight=0
Main XS Weight=1
Downstream XS Weight=0
Number of DS XS's Weighted with US Boundary= 1
Upstream Boundary Weight= 1
Weight of XSs Associated with US Boundary= 0
Number of US XS's Weighted with DS Boundary= 1
Downstream Boundary Weight= 0.5
Weight of XSs Associated with DS Boundary= 0.5
Percentile Method= 0
Sediment Output Level= 3
Mass or Volume Output= 0
Output Increment Type= 1
Profile and TS Output Increment= 1
XS Output Flag= 0
XS Output Increment= 10
Write Gradation File= 0
Read Gradation Hotstart= 0
Write HDF5 File= 1
Write Binary Output= 1
Write DSS Sediment File= 0
SV Curve= 0
Specific Gage Flag= 0

--- UNT 058 IN DRY CR WATERSHED.f01 (steady flow) ---

Flow Title=Multiple
Number of Profiles=7
Profile Names=10-year,25-year,50-year,1pct_min,100-year,1pct_plu,500-year
River Rch & RM= UNT 058 IN DRY C,Reach-1,13762
     174     215     245     140     279     557     361
River Rch & RM= UNT 058 IN DRY C,Reach-1,12971
     471     626     750     448     893    1782    1268
River Rch & RM= UNT 058 IN DRY C,Reach-1,11840
     542     725     873     524    1045    2084    1496
River Rch & RM= UNT 058 IN DRY C,Reach-1,10709
     799    1090    1330     806    1607    3207    2354
River Rch & RM= UNT 058 IN DRY C,Reach-1,5526
     918    1260    1545     940    1876    3744    2773
River Rch & RM= UNT 058 IN DRY C,Reach-1,3870
    1115    1546    1907    1167    2329    4646    3480
Boundary for River Rch & Prof#=UNT 058 IN DRY C,Reach-1,1
Up Type=0
Dn Type=3
Dn Slope=0.005
Boundary for River Rch & Prof#=UNT 058 IN DRY C,Reach-1,2
Up Type=0
Dn Type=3
Dn Slope=0.005
Boundary for River Rch & Prof#=UNT 058 IN DRY C,Reach-1,3
Up Type=0
Dn Type=3
Dn Slope=0.005
Boundary for River Rch & Prof#=UNT 058 IN DRY C,Reach-1,4
Up Type=0
Dn Type=3
Dn Slope=0.005
Boundary for River Rch & Prof#=UNT 058 IN DRY C,Reach-1,5
Up Type=0
Dn Type=3
Dn Slope=0.005
Boundary for River Rch & Prof#=UNT 058 IN DRY C,Reach-1,6
Up Type=0
Dn Type=3
Dn Slope=0.005
Boundary for River Rch & Prof#=UNT 058 IN DRY C,Reach-1,7
Up Type=0
Dn Type=3
Dn Slope=0.005

--- UNT 058 IN DRY CR WATERSHED.g01 (geometry) ---

Geom Title=Existing Conditions
Program Version=5.07

River Reach=UNT 058 IN DRY C,Reach-1
Reach XY= 30
      2925690.37      7007157.81      2925620.18      7007278.58
      2925075.09      7007360.89      2924589.92      7007143.22
      2923977.08      7007050.49      2923414.18      7007130.94
      2923050.67      7007028.57      2921870.63      7007300.82
       2920601.4      7007288.36      2919425.44      7006961.06
      2918728.38      7007148.38      2918449.79       7007130.1
       2918321.7       7007062.6      2918276.65      7006885.13
      2918032.87      7006885.24      2917905.89      7006661.06
       2917762.8      7006674.53      2917518.14      7006456.44
      2916767.66      7006127.05      2916498.55      7005825.22
      2915740.45      7005879.69      2915345.54      7005781.68
      2915046.58       7005833.3      2914970.63      7005892.34
       2914922.3      7006102.42      2914613.27       7006166.5
      2914327.99      7006405.27      2914115.13      7006492.14
      2913864.56      7006859.61      2913685.59      7006960.71

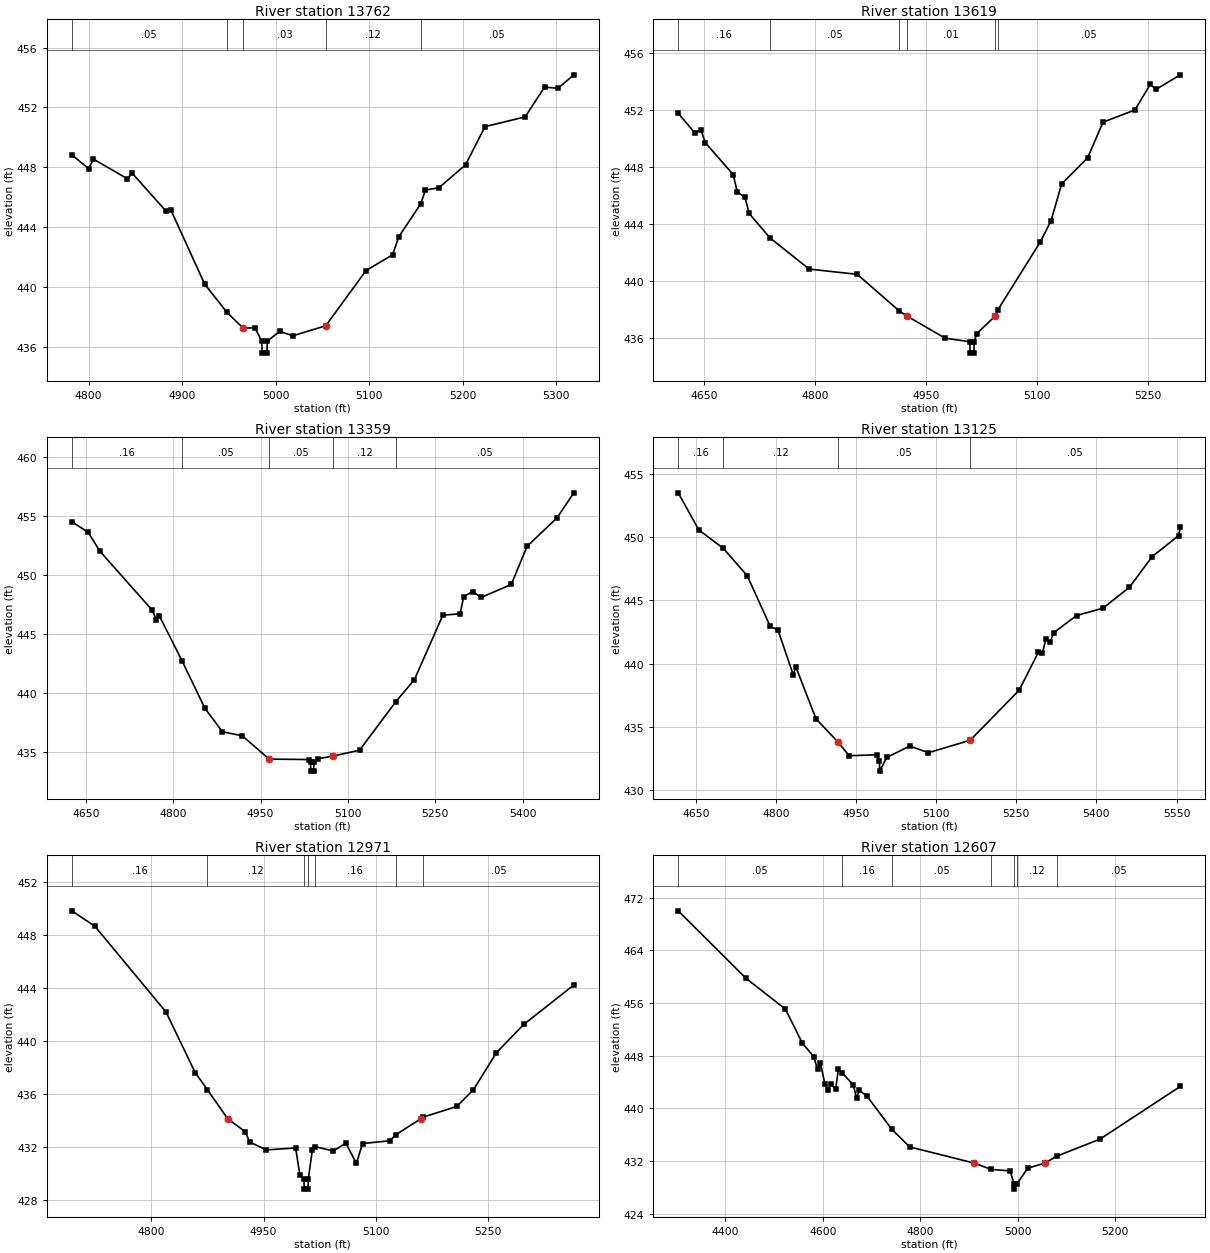
Type RM Length L Ch R = 1 ,13762   ,143,143,143
BEGIN DESCRIPTION:
UNT 058 IN DRY CR WATERSHED 27.0
END DESCRIPTION:
XS GIS Cut Line= 3
        2925625.      7006975.01      2925677.58      7007186.47
      2925920.43      7007393.17
#Sta/Elev= 30
  4782.1  448.84  4800.2  447.91  4805.3  448.55  4841.5  447.24  4846.7  447.61
  4882.8  445.08    4888  445.16  4924.2   440.2  4947.8  438.33  4965.5  437.25
  4977.9  437.29  4985.2  436.39  4985.7  435.59  4990.7  435.59  4991.2  436.39
  5004.3  437.04  5018.6  436.75  5053.7  437.42  5096.6   441.1  5125.1  442.16
  5131.7  443.36  5155.2  445.56  5160.2  446.49  5174.5  446.63  5203.1  448.17
  5223.9  450.72  5266.8  451.37  5287.6  453.36  5301.9  453.28  5318.9  454.18
#Mann= 5 ,-1 , 0
  4782.1     .05       0  4947.8     .12       0  4965.5     .03       0
  5053.7     .12       0  5155.2     .05       0
Bank Sta=4965.5,5053.7
XS Rating Curve= 0 ,0
Exp/Cntr=0.3,0.1

Type RM Length L Ch R = 1 ,13619   ,260,260,260
BEGIN DESCRIPTION:
Mapping XS a4067466
END DESCRIPTION:
XS GIS Cut Line= 3
      2925403.55      7006945.65      2925591.06      7007280.74
      2925818.46      7007468.21
#Sta/Elev= 30
  4615.5  451.77  4637.7  450.41  4646.3  450.61    4652  449.71  4689.7  447.47
  4695.4  446.23  4705.7  445.88  4711.4  444.73  4739.6  443.01  4792.5  440.82
  4857.5  440.45  4914.2  437.88  4925.3   437.5  4976.3  435.96  5009.6  435.71
  5010.1  434.91  5015.1  434.91  5015.6  435.71    5019  436.28  5043.6   437.5
  5047.4  437.94  5105.1  442.74  5119.4  444.21  5133.8  446.81  5168.9  448.64
  5189.7  451.15  5232.8  452.01  5253.6  453.81  5261.4  453.46  5294.2  454.48
#Mann= 6 ,-1 , 0
  4615.5     .16       0  4739.6     .05       0  4914.2     .12       0
  4925.3     .01       0  5043.6     .12       0  5047.4     .05       0
Bank Sta=4925.3,5043.6
XS Rating Curve= 0 ,0
Exp/Cntr=0.3,0.1

Type RM Length L Ch R = 1 ,13359   ,234,234,234
BEGIN DESCRIPTION:
Mapping XS c4ead67c
END DESCRIPTION:
XS GIS Cut Line= 3
      2925309.81      7006937.01      2925335.85      7007311.99
      2925743.86      7007575.89
#Sta/Elev= 30
  4625.9  454.52    4654  453.62    4674  452.03  4764.2  447.02  4771.1   446.2
  4776.1  446.56  4814.9  442.77  4854.4  438.73  4884.5  436.74  4918.5   436.4
  4964.7  434.43  5032.7  434.39  5035.7  434.21  5036.2  433.41  5041.2  433.41
  5041.7  434.21  5047.9  434.45    5075  434.69  5119.9  435.18  5181.6  439.25
  5214.1  441.16  5262.8   446.6  5292.6  446.73  5298.6  448.18  5313.8   448.6
  5328.9  448.11  5380.3  449.21  5407.4  452.43  5458.9  454.85  5487.7  456.96
#Mann= 5 ,-1 , 0
  4625.9     .16       0  4814.9     .05       0  4964.7     .05       0
    5075     .12       0  5181.6     .05       0
Bank Sta=4964.7,5075
XS Rating Curve= 0 ,0
Exp/Cntr=0.3,0.1

Type RM Length L Ch R = 1 ,13125   ,154,154,154
BEGIN DESCRIPTION:
UNT 058 IN DRY CR WATERSHED 26.0
END DESCRIPTION:
XS GIS Cut Line= 3
      2925198.69      7006963.05      2925113.13      7007336.07
      2925540.35      7007693.63
#Sta/Elev= 30
  4617.3  453.51  4655.7  450.58  4701.9  449.11  4746.6  446.94  4789.5  442.94
    4804  442.66  4832.4  439.13  4837.5  439.73  4875.2  435.63  4916.8  433.77
  4937.3  432.71  4988.6  432.78  4993.9  432.29  4994.4  431.49  5007.5  432.57
  5050.5  433.47  5085.6  432.95  5163.7  433.93  5255.4  437.89  5291.2  440.88
    5299  440.83  5305.5  441.96  5313.3  441.67  5319.8  442.43  5362.8   443.8
  5412.2  444.38  5461.7  446.03  5504.6  448.47  5554.1  450.13  5557.1  450.82
#Mann= 4 ,-1 , 0
  4617.3     .16       0  4701.9     .12       0  4916.8     .05       0
  5163.7     .05       0
Bank Sta=4916.8,5163.7
XS Rating Curve= 0 ,0
Exp/Cntr=0.3,0.1

Type RM Length L Ch R = 1 ,12971   ,364,364,364
BEGIN DESCRIPTION:
UNT 058 IN DRY CR WATERSHED 25.0
END DESCRIPTION:
XS GIS Cut Line= 3
      2925125.01      7007024.98        2924975.        7007325.
      2924825.02      7007624.96
#Sta/Elev= 30
  4693.8  449.84  4724.6  448.68  4819.6  442.21  4858.7  437.63  4875.1  436.33
  4902.3  434.13  4925.8  433.16  4931.4  432.39  4953.8  431.79  4992.9  431.94
  4998.5  429.92  5003.9  429.63  5004.4  428.83  5009.4  428.83  5009.9  429.63
  5015.3  431.81  5018.6  432.04  5043.2  431.71    5060   432.3    5074  430.77
  5082.3  432.27  5118.7  432.48  5126.8  432.94  5159.9  434.13    5163  434.26
  5208.1  435.07  5230.5  436.34  5261.2  439.13  5297.6  441.26  5364.6  444.24
#Mann= 7 ,-1 , 0
  4693.8     .16       0  4875.1     .12       0  5003.9     .07       0
  5009.9     .12       0  5018.6     .16       0  5126.8     .07       0
    5163     .05       0
Bank Sta=4902.3,5159.9
XS Rating Curve= 0 ,0
Exp/Cntr=0.3,0.1

Type RM Length L Ch R = 1 ,12607   ,371,371,371
BEGIN DESCRIPTION:
UNT 058 IN DRY CR WATERSHED 24.0
END DESCRIPTION:
XS GIS Cut Line= 3
      2925025.01      7006574.99        2924675.        7007175.
      2924525.02      7007474.96
#Sta/Elev= 30
  4303.4  469.98  4442.3  459.75  4523.4  455.06  4558.1   449.9  4581.3  447.86
  4589.1  445.96  4594.9  446.94  4604.4  443.68  4610.6  442.83  4616.4  443.71
  4626.3  442.94  4632.1  446.04  4639.8  445.41  4662.3  443.58  4669.3  441.64
  4675.1  442.73  4690.8  441.85  4741.1  436.88  4778.1  434.17  4910.9   431.7
  4945.4  430.75  4984.4  430.53  4992.1  428.56  4992.6  427.76  4998.1  428.56
  5020.4  430.93  5055.2   431.7  5080.2  432.77  5168.5  435.34  5333.4  443.34
#Mann= 7 ,-1 , 0
  4303.4     .05       0  4639.8     .16       0  4741.1     .05       0
  4945.4     .12       0  4992.1     .07       0  4998.1     .12       0
  5080.2     .05       0
Bank Sta=4910.9,5055.2
XS Rating Curve= 0 ,0
Exp/Cntr=0.3,0.1

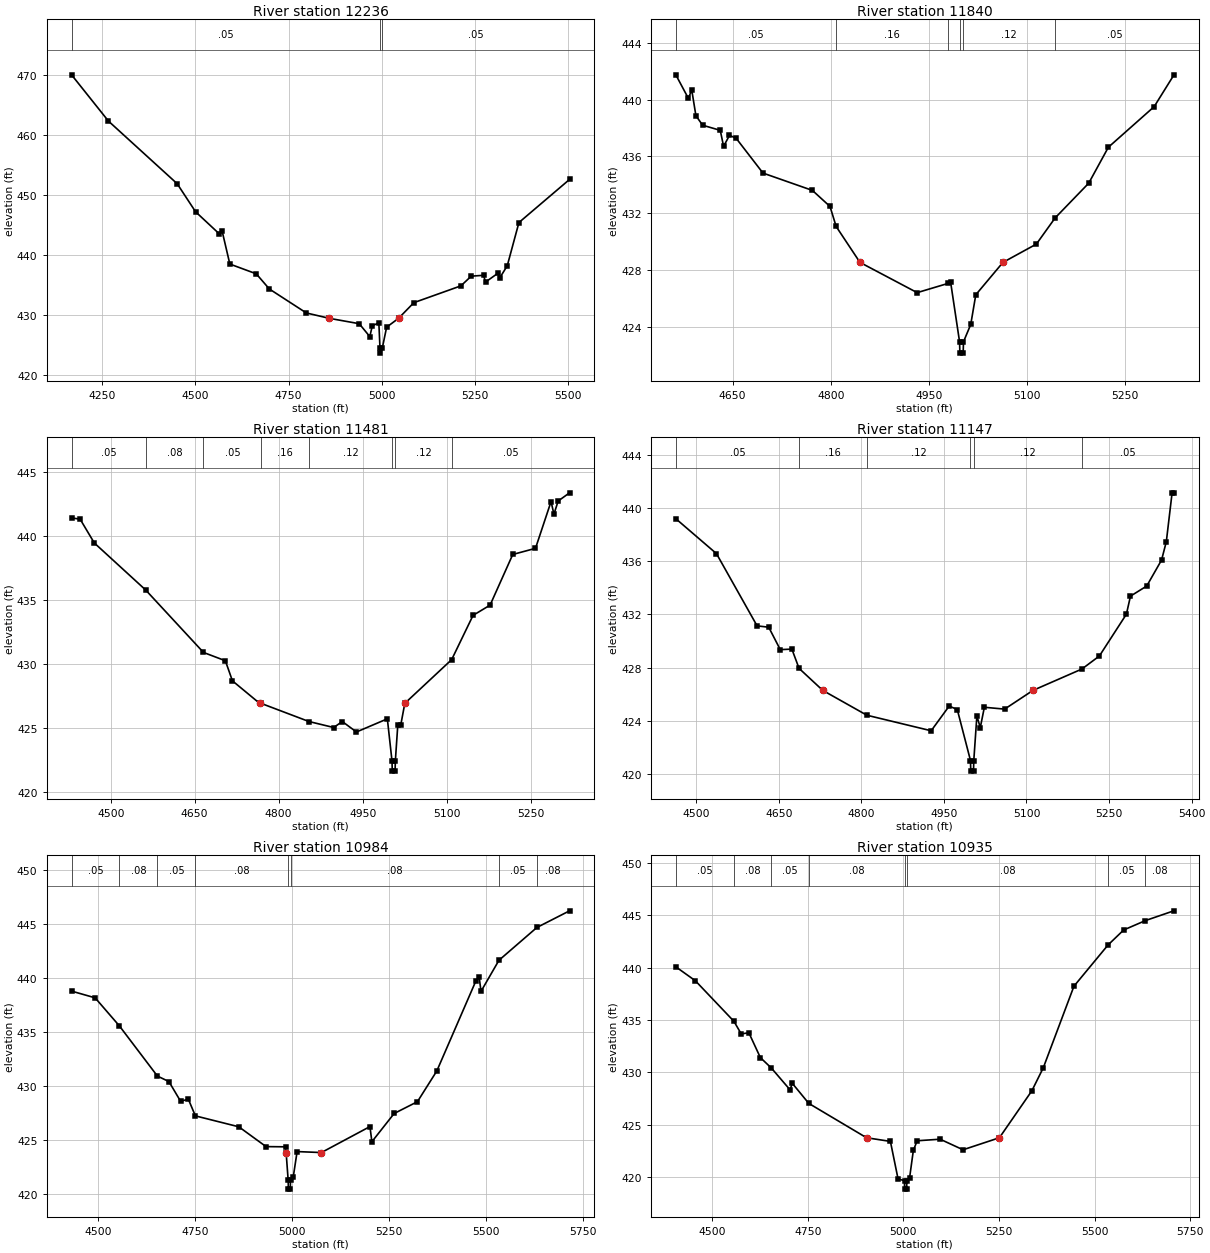
Type RM Length L Ch R = 1 ,12236   ,396,396,396
BEGIN DESCRIPTION:
UNT 058 IN DRY CR WATERSHED 23.0
END DESCRIPTION:
XS GIS Cut Line= 3
      2924925.01        7006525.        2924325.        7007075.
      2924174.99      7007575.04
#Sta/Elev= 30
  4167.5  470.06  4266.5  462.34  4450.8   451.9  4500.2  447.22  4563.7  443.54
  4571.1  444.09  4592.1   438.5    4663  436.87  4698.1  434.34  4797.4  430.34
  4859.3  429.44  4939.2  428.55  4967.6   426.4  4974.4   428.2  4991.9   428.7
    4995  424.44  4995.5  423.64    5001  424.44  5012.8  427.97  5044.7  429.44
  5085.9  432.06    5212  434.86  5239.8  436.48  5272.9  436.62  5278.1  435.49
  5311.2  436.96  5316.4   436.2  5336.4  438.21  5367.7  445.42  5503.5  452.61
#Mann= 3 ,-1 , 0
  4167.5     .05       0    4995     .03       0    5001     .05       0
Bank Sta=4859.3,5044.7
XS Rating Curve= 0 ,0
Exp/Cntr=0.3,0.1

Type RM Length L Ch R = 1 ,11840   ,359,359,359
BEGIN DESCRIPTION:
UNT 058 IN DRY CR WATERSHED 22.0
END DESCRIPTION:
XS GIS Cut Line= 3
        2924025.        7006625.        2923925.        7007075.
        2923925.      7007375.02
#Sta/Elev= 30
  4563.2  441.75  4582.4  440.09  4587.5  440.69  4593.9  438.87  4604.2   438.2
  4631.1  437.84  4636.2  436.71  4645.2  437.49  4655.4  437.28  4696.4  434.83
  4771.9  433.61  4798.8  432.48  4808.2  431.07  4844.6  428.54    4932  426.41
  4979.2  427.06  4983.2  427.13  4996.8  422.95  4997.3  422.15  5002.3  422.15
  5002.8  422.95  5013.9  424.17  5021.6  426.26  5063.1  428.54  5114.2  429.83
  5142.8  431.67  5194.2  434.12  5224.2  436.65  5294.2  439.51  5324.2  441.73
#Mann= 6 ,-1 , 0
  4563.2     .05       0  4808.2     .16       0  4979.2     .12       0
  4996.8     .07       0  5002.8     .12       0  5142.8     .05       0
Bank Sta=4844.6,5063.1
XS Rating Curve= 0 ,0
Exp/Cntr=0.3,0.1

Type RM Length L Ch R = 1 ,11481   ,334,334,334
BEGIN DESCRIPTION:
UNT 058 IN DRY CR WATERSHED 21.0
END DESCRIPTION:
XS GIS Cut Line= 3
      2923775.01      7006574.98        2923575.        7007125.
        2923625.        7007425.
#Sta/Elev= 30
  4430.1  441.43  4445.4  441.33  4470.7  439.47  4562.5  435.79  4665.7  430.91
  4704.8  430.26  4717.4  428.69    4766  426.93    4769  426.92    4854  425.51
  4898.3  425.04  4913.6  425.51  4938.9  424.69  4994.1  425.72  5002.4  422.43
  5002.9  421.63  5007.9  421.63  5008.4  422.43  5012.7   425.2  5017.9   425.2
  5025.3  426.93    5109  430.35  5147.2  433.81  5177.6  434.61  5218.1  438.57
  5258.7  439.05  5286.5  442.71  5291.6  441.72  5299.2  442.75  5319.5  443.39
#Mann= 8 ,-1 , 0
  4430.1     .05       0  4562.5     .08       0  4665.7     .05       0
    4769     .16       0    4854     .12       0  5002.4     .07       0
  5008.4     .12       0    5109     .05       0
Bank Sta=4766,5025.3
XS Rating Curve= 0 ,0
Exp/Cntr=0.3,0.1

Type RM Length L Ch R = 1 ,11147   ,163,163,163
BEGIN DESCRIPTION:
UNT 058 IN DRY CR WATERSHED 20.0
END DESCRIPTION:
XS GIS Cut Line= 3
        2923375.        7006575.        2923225.        7007025.
      2923475.03      7007375.04
#Sta/Elev= 30
  4463.1  439.21  4536.9  436.58  4610.7  431.14  4631.8  431.04  4652.8  429.35
  4673.9  429.39  4686.9  427.94    4730  426.28  4810.1  424.41  4926.9  423.24
  4959.6   425.1  4974.3  424.84  4998.3     421  4998.8   420.2  5003.8   420.2
  5004.3     421  5009.9  424.35  5016.1  423.48  5023.5  425.01  5060.3  424.87
  5111.8  426.28  5200.7  427.89  5232.4  428.87  5281.5  432.02  5288.9  433.38
  5318.4  434.14  5345.4   436.1    5354  437.48  5364.5  441.16  5367.6  441.16
#Mann= 6 ,-1 , 0
  4463.1     .05       0  4686.9     .16       0  4810.1     .12       0
  4998.3     .07       0  5004.3     .12       0  5200.7     .05       0
Bank Sta=4730,5111.8
XS Rating Curve= 0 ,0
Exp/Cntr=0.3,0.1

Type RM Length L Ch R = 1 ,10984   ,49,49,49
BEGIN DESCRIPTION:
Mapping XS 325681b2
END DESCRIPTION:
XS GIS Cut Line= 3
      2923138.32      7006464.37      2923107.93      7007011.24
      2923081.89      7007746.96
#Sta/Elev= 30
  4431.5  438.78  4492.2  438.16  4554.9  435.56  4652.8  430.93  4682.5  430.42
  4712.6   428.6  4732.6  428.79  4750.7  427.25  4862.8  426.24  4932.9  424.41
  4983.6  424.39  4984.7  423.86    4990  421.28  4990.5  420.48  4995.5  420.48
    4996  421.28    5003  421.59    5013  423.95  5075.6  423.86  5200.8  426.26
  5205.8  424.86  5263.2  427.47  5323.2  428.56  5373.2   431.4  5473.3  439.67
  5482.2  440.11  5487.2  438.76  5533.4  441.63  5631.2  444.66  5715.4   446.2
#Mann= 8 ,-1 , 0
  4431.5     .05       0  4554.9     .08       0  4652.8     .05       0
  4750.7     .08       0    4990     .07       0    4996     .08       0
  5533.4     .05       0  5631.2     .08       0
Bank Sta=4984.7,5075.6
XS Rating Curve= 0 ,0
Exp/Cntr=0.3,0.1

Type RM Length L Ch R = 1 ,10935   ,226,226,226
BEGIN DESCRIPTION:
Mapping XS 39f54bb5
END DESCRIPTION:
XS GIS Cut Line= 3
      2923062.36      7006433.97      2923058.02      7006989.54
      2923049.34       7007736.1
#Sta/Elev= 30
  4405.1  440.08  4456.1  438.75  4557.1  434.87  4576.1  433.67  4596.1  433.78
  4626.1  431.41  4654.9  430.41  4704.2  428.31  4709.2  428.97  4752.8  427.03
  4903.8  423.75  4966.2   423.4  4986.2  419.82  5003.2  419.64  5003.7  418.84
  5008.7  418.84  5009.2  419.64  5016.2  419.87  5026.2  422.54  5036.2  423.46
  5096.2  423.61  5156.2   422.6  5251.3  423.75  5336.2  428.24  5366.2  430.45
  5446.2  438.23  5535.4  442.17  5576.2   443.6  5633.2   444.5  5707.3  445.43
#Mann= 8 ,-1 , 0
  4405.1     .05       0  4557.1     .08       0  4654.9     .05       0
  4752.8     .08       0  5003.2     .07       0  5009.2     .08       0
  5535.4     .05       0  5633.2     .08       0
Bank Sta=4903.8,5251.3
XS Rating Curve= 0 ,0
Exp/Cntr=0.3,0.1

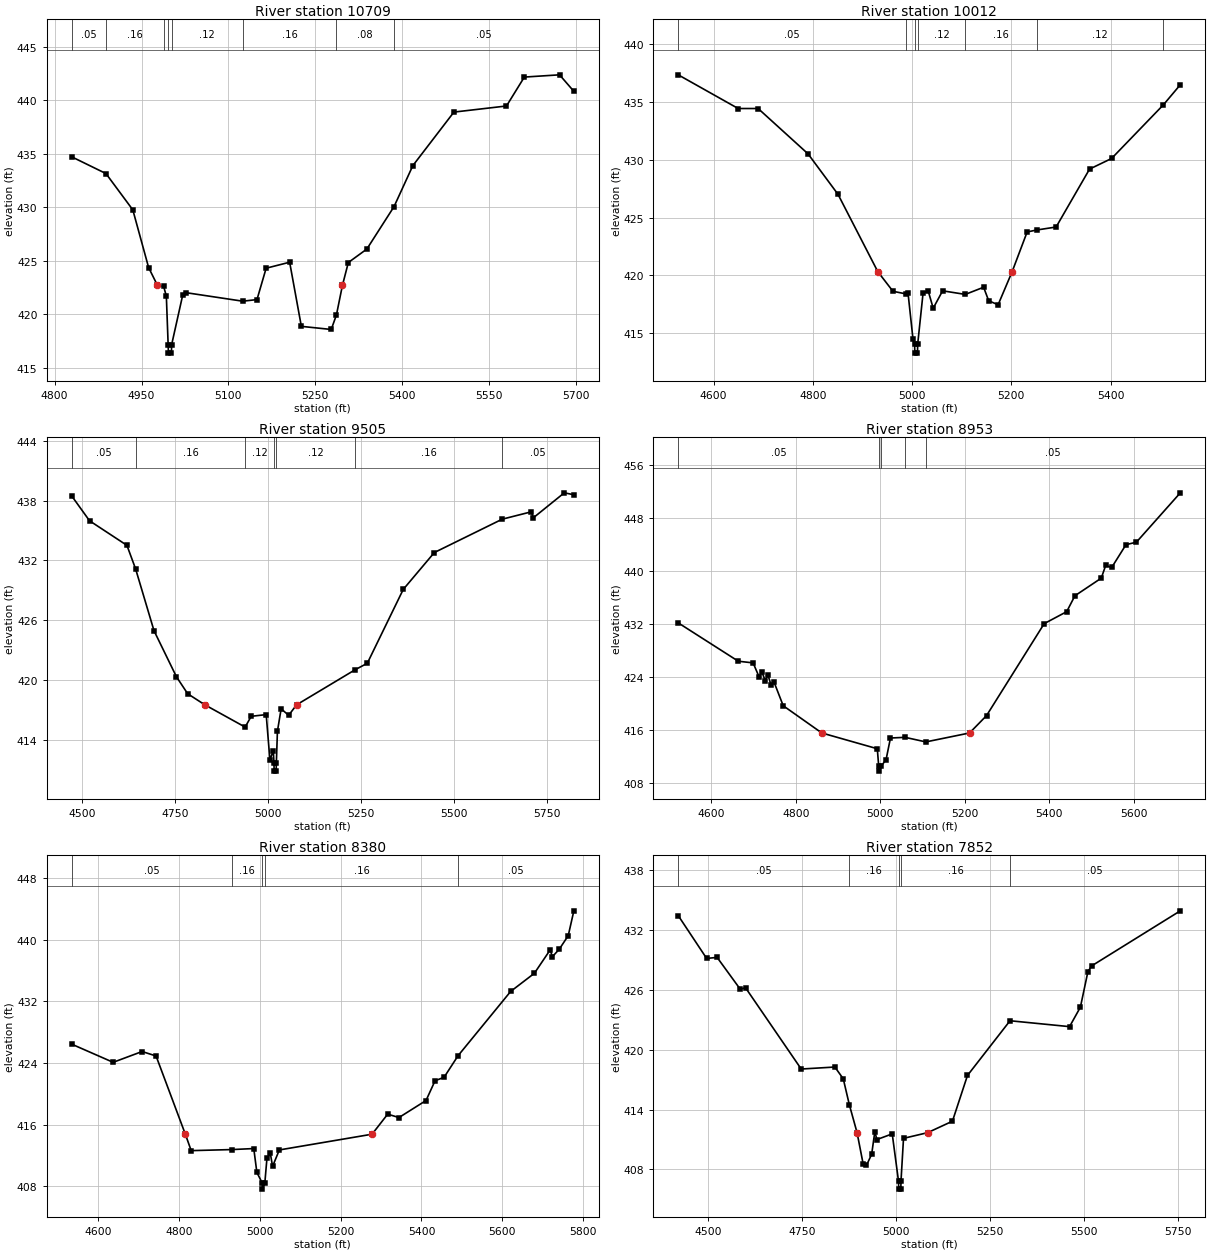
Type RM Length L Ch R = 1 ,10709   ,697,697,697
BEGIN DESCRIPTION:
UNT 058 IN DRY CR WATERSHED 19.0
END DESCRIPTION:
XS GIS Cut Line= 3
      2922881.51      7006915.22      2922846.13      7007082.01
      2922957.91      7007769.38
#Sta/Elev= 30
  4829.5   434.7  4888.5  433.14  4934.9  429.75  4962.2  424.36  4977.5  422.69
    4988  422.63  4992.8  421.69  4995.9  417.17  4996.4  416.37  5001.5  416.37
    5002  417.17  5021.2  421.83  5026.2  422.02  5124.7  421.22  5149.3  421.37
  5165.1   424.3  5205.7  424.86  5225.9  418.87  5277.5  418.58  5286.5  419.94
  5296.8  422.69    5307  424.83    5339  426.09    5386  430.06  5418.4  433.88
  5489.3  438.88  5580.1  439.45  5610.9  442.15  5671.7  442.36  5696.4  440.82
#Mann= 8 ,-1 , 0
  4829.5     .05       0  4888.5     .16       0    4988     .12       0
  4995.9     .07       0    5002     .12       0  5124.7     .16       0
  5286.5     .08       0    5386     .05       0
Bank Sta=4977.5,5296.8
XS Rating Curve= 0 ,0
Exp/Cntr=0.3,0.1

Type RM Length L Ch R = 1 ,10012   ,507,507,507
BEGIN DESCRIPTION:
UNT 058 IN DRY CR WATERSHED 18.0
END DESCRIPTION:
XS GIS Cut Line= 3
        2922125.      7006774.98        2922175.        7007225.
        2922275.      7007774.99
#Sta/Elev= 30
  4528.7  437.37  4649.5  434.45  4689.7  434.45  4790.3  430.52  4850.7  427.01
  4930.9  420.31  4961.4  418.61  4987.9  418.38  4991.7  418.49  5001.8  414.46
    5005  414.05  5005.5  413.25  5010.8  413.25  5011.3  414.05  5022.1  418.46
  5032.3  418.66  5042.5  417.14  5061.5  418.65  5107.2  418.34  5144.1  418.96
  5154.3  417.79  5173.3  417.44  5201.6  420.31  5231.8  423.75  5250.9  423.92
  5290.2  424.18  5357.6   429.2    5402  430.12  5506.6  434.78  5540.5  436.51
#Mann= 7 ,-1 , 0
  4528.7     .05       0  4987.9     .12       0    5005     .07       0
  5011.3     .12       0  5107.2     .16       0  5250.9     .12       0
  5506.6     .16       0
Bank Sta=4930.9,5201.6
XS Rating Curve= 0 ,0
Exp/Cntr=0.3,0.1

Type RM Length L Ch R = 1 ,9505    ,552,552,552
BEGIN DESCRIPTION:
UNT 058 IN DRY CR WATERSHED 17.0
END DESCRIPTION:
XS GIS Cut Line= 3
        2921725.      7006774.96        2921675.        7007275.
      2921772.84       7008116.6
#Sta/Elev= 30
  4471.6  438.45  4519.4  435.97  4619.9  433.51  4643.4  431.13  4692.7  424.96
    4753  420.35  4783.2  418.65  4829.4  417.54  4937.7  415.31    4954  416.39
  4994.3  416.56  5004.3  412.02  5013.4  412.95  5015.2   411.7  5015.7   410.9
  5021.1   410.9  5021.6   411.7  5024.5   414.9  5034.5  417.14  5054.7  416.49
    5076  417.54  5233.7  421.06  5266.1   421.7  5362.8   429.1  5446.3  432.79
  5628.8  436.13  5707.1  436.87  5712.2  436.26  5795.7  438.77  5821.4  438.58
#Mann= 7 ,-1 , 0
  4471.6     .05       0  4643.4     .16       0  4937.7     .12       0
  5015.2     .07       0  5021.6     .12       0  5233.7     .16       0
  5628.8     .05       0
Bank Sta=4829.4,5076
XS Rating Curve= 0 ,0
Exp/Cntr=0.3,0.1

Type RM Length L Ch R = 1 ,8953    ,573,573,573
BEGIN DESCRIPTION:
UNT 058 IN DRY CR WATERSHED 16.0
END DESCRIPTION:
XS GIS Cut Line= 3
      2921425.02      7006924.97        2921125.        7007275.
      2921324.99      7007974.98
#Sta/Elev= 30
  4521.7   432.2  4663.9  426.41    4699  426.16  4713.3  424.03  4719.8  424.81
  4727.5   423.5  4734.1  424.34  4741.8  422.75  4748.4  423.29  4770.3  419.69
  4861.7  415.58  4993.1   413.2  4996.4  410.62  4996.9  409.82  5002.8  410.62
  5013.9  411.56  5024.3  414.82    5059  414.92  5108.1  414.23  5211.6  415.58
  5251.8   418.2  5388.3  432.08  5441.6  433.89  5461.1  436.29  5523.5  438.95
  5533.9  440.86  5548.2  440.56    5582     444  5606.7  444.38  5710.7  451.83
#Mann= 5 ,-1 , 0
  4521.7     .05       0  4996.4     .03       0  5002.8     .05       0
    5059     .07       0  5108.1     .05       0
Bank Sta=4861.7,5211.6
XS Rating Curve= 0 ,0
Exp/Cntr=0.3,0.1

Type RM Length L Ch R = 1 ,8380    ,528,528,528
BEGIN DESCRIPTION:
UNT 058 IN DRY CR WATERSHED 15.0
END DESCRIPTION:
XS GIS Cut Line= 3
      2920474.99      7006824.96        2920575.        7007275.
      2920924.98      7007974.96
#Sta/Elev= 30
  4533.8  426.43  4636.3  424.08    4708  425.48  4742.6   424.9  4815.1  414.76
  4829.6  412.63    4931  412.77  4984.6   412.9  4992.3   409.8  5005.5  408.44
    5006  407.64    5012  408.44  5017.2  411.62  5025.6  412.28  5031.2  410.59
  5047.9  412.72  5277.6  414.76  5316.3  417.36  5344.2  416.92  5411.3  419.13
  5433.6  421.69    5456  422.14  5490.8  424.95  5620.9  433.27  5679.6  435.62
  5718.7  438.65  5724.3  437.78  5741.1  438.73  5763.5   440.5  5777.4  443.72
#Mann= 5 ,-1 , 0
  4533.8     .05       0    4931     .16       0  5005.5     .07       0
    5012     .16       0  5490.8     .05       0
Bank Sta=4815.1,5277.6
XS Rating Curve= 0 ,0
Exp/Cntr=0.3,0.1

Type RM Length L Ch R = 1 ,7852    ,541,541,541
BEGIN DESCRIPTION:
UNT 058 IN DRY CR WATERSHED 14.0
END DESCRIPTION:
XS GIS Cut Line= 3
      2920324.99      7006625.02        2920075.        7007125.
      2920050.63      7007900.62
#Sta/Elev= 30
  4420.7  433.45  4496.2  429.16  4524.1  429.26  4585.6  426.07  4599.6  426.22
  4747.7  418.07  4837.2  418.27  4859.5  417.09  4875.6   414.5  4896.2  411.69
  4912.6  408.51    4921   408.4    4935  409.52  4943.4  411.78    4949     411
  4989.7  411.57  5006.4  406.83  5006.9  406.03  5012.5  406.03    5013  406.83
  5019.7  411.12  5083.8  411.69  5149.8  412.84  5189.8  417.43  5302.9  422.91
  5461.2  422.32    5490  424.27    5510  427.83    5520  428.41  5755.7  433.93
#Mann= 5 ,-1 , 0
  4420.7     .05       0  4875.6     .16       0  5006.4     .07       0
    5013     .16       0  5302.9     .05       0
Bank Sta=4896.2,5083.8
XS Rating Curve= 0 ,0
Exp/Cntr=0.3,0.1

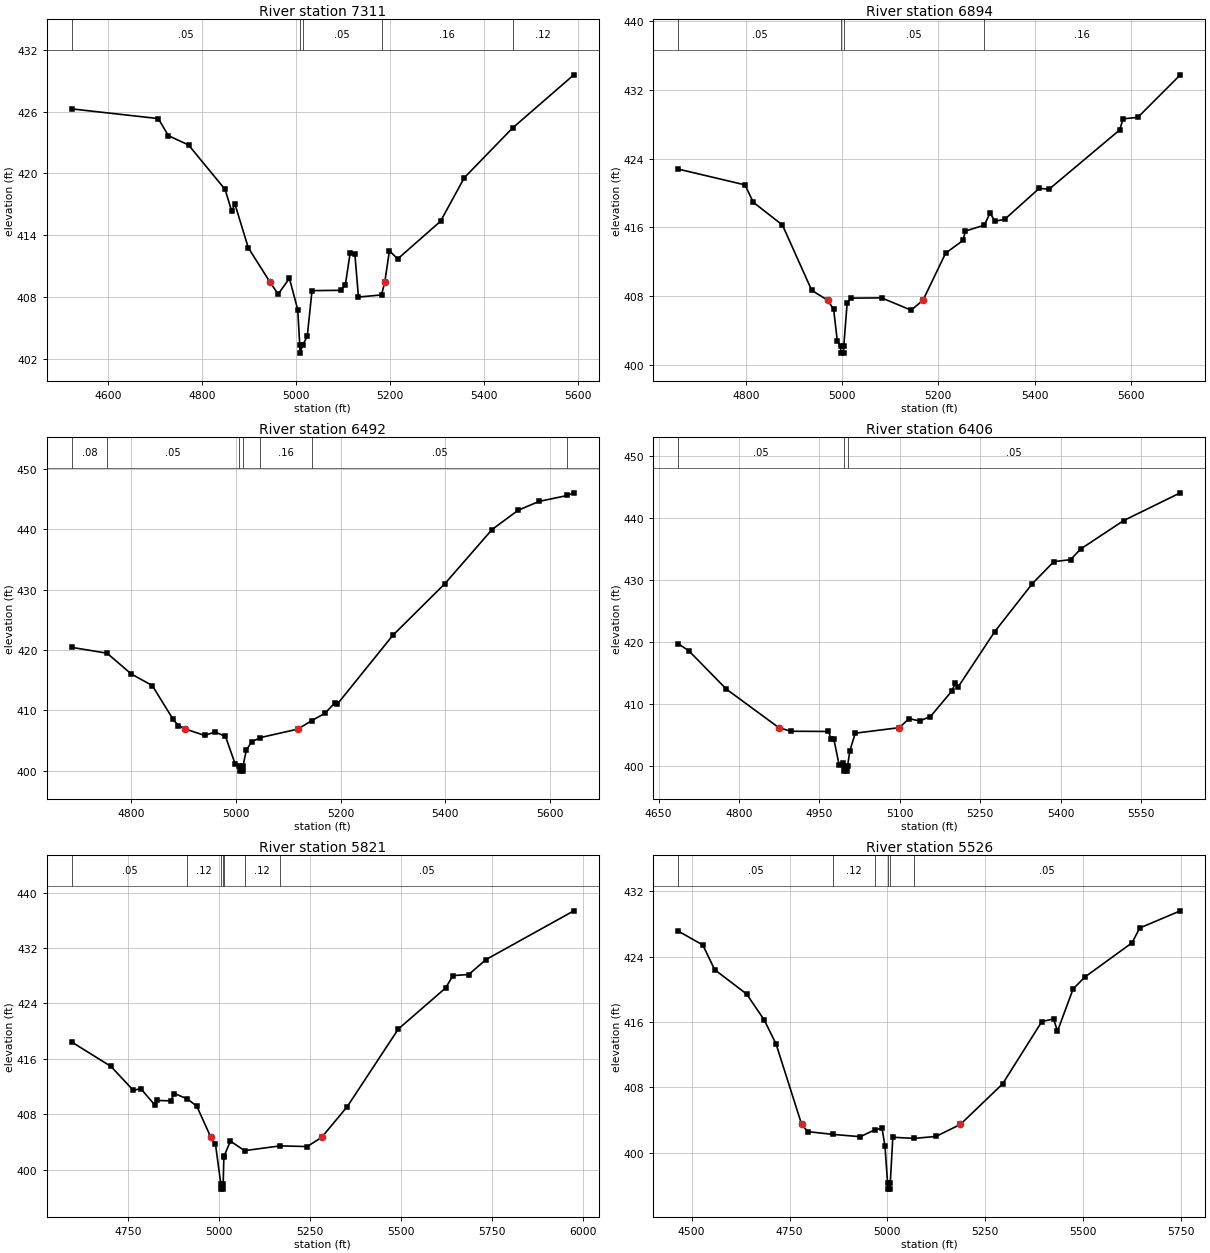
Type RM Length L Ch R = 1 ,7311    ,417,417,417
BEGIN DESCRIPTION:
UNT 058 IN DRY CR WATERSHED 13.0
END DESCRIPTION:
XS GIS Cut Line= 3
      2919874.97      7006625.04        2919575.        7006975.
        2919475.      7007574.99
#Sta/Elev= 30
    4523  426.27  4707.3  425.33  4728.7  423.67  4771.6  422.77  4849.5  418.45
  4863.7  416.31  4870.3  417.05  4898.9  412.78  4944.7  409.48  4962.5  408.28
  4986.5  409.81  5004.2  406.77  5008.5  403.35    5009  402.55  5015.1  403.35
  5024.5  404.19  5034.6  408.62  5095.4  408.65  5105.6  409.17  5115.7  412.24
  5125.9  412.15  5133.5     408  5182.6   408.2  5189.7  409.48  5199.4  412.49
  5217.1   411.7  5308.3  415.36    5359  419.59  5461.6  424.41  5592.2  429.58
#Mann= 5 ,-1 , 0
    4523     .05       0  5008.5     .03       0  5015.1     .05       0
  5182.6     .16       0  5461.6     .12       0
Bank Sta=4944.7,5189.7
XS Rating Curve= 0 ,0
Exp/Cntr=0.3,0.1

Type RM Length L Ch R = 1 ,6894    ,402,402,402
BEGIN DESCRIPTION:
UNT 058 IN DRY CR WATERSHED 12.0
END DESCRIPTION:
XS GIS Cut Line= 3
        2919275.      7006675.01      2919161.91      7006977.67
      2919317.68      7007681.23
#Sta/Elev= 30
  4659.4  422.79  4798.2  420.95  4815.4  418.93    4876  416.28  4936.9  408.68
  4970.1  407.52  4982.5  406.47    4990   402.8  4996.9  402.17  4997.4  401.37
    5003  401.37  5003.5  402.17  5010.5   407.2  5017.8  407.77  5082.2   407.8
  5143.6  406.37  5168.1  407.52  5215.3  413.01  5251.2  414.48  5256.3  415.58
  5295.7  416.26  5307.5  417.68  5317.8  416.72  5338.2  416.95  5409.9  420.55
  5430.4  420.45    5577  427.34  5584.1  428.64  5614.8  428.81  5703.1  433.76
#Mann= 4 ,-1 , 0
  4659.4     .05       0  4996.9     .03       0  5003.5     .05       0
  5295.7     .16       0
Bank Sta=4970.1,5168.1
XS Rating Curve= 0 ,0
Exp/Cntr=0.3,0.1

Type RM Length L Ch R = 1 ,6492    ,86,86,86
BEGIN DESCRIPTION:
Mapping XS 788b8da3
END DESCRIPTION:
XS GIS Cut Line= 3
       2918814.5      7006811.02      2918811.03      7007126.98
      2918807.56      7007771.39
#Sta/Elev= 30
  4685.8  420.46  4753.3  419.49  4799.8  416.04  4839.8  414.13  4879.8  408.51
  4889.8  407.48  4902.9  406.93  4939.8  405.87  4959.8  406.43  4979.8  405.71
  4998.3  401.15  5006.5  400.75    5007  399.95  5012.7  399.95  5013.2  400.75
  5019.8  403.44  5029.8   404.8  5046.8  405.51  5118.7  406.93  5144.6  408.31
  5169.8  409.52    5189  411.25    5194  411.08  5299.8  422.44  5399.8  431.04
  5489.8  439.99  5539.8  443.19  5579.8  444.65  5633.8  445.63  5646.2  446.07
#Mann= 7 ,-1 , 0
  4685.8     .08       0  4753.3     .05       0  5006.5     .04       0
  5013.2     .05       0  5046.8     .16       0  5144.6     .05       0
  5633.8     .08       0
Bank Sta=4902.9,5118.7
XS Rating Curve= 0 ,0
Exp/Cntr=0.3,0.1

Type RM Length L Ch R = 1 ,6406    ,585,585,585
BEGIN DESCRIPTION:
Mapping XS ee89ea0d
END DESCRIPTION:
XS GIS Cut Line= 3
      2918748.53      7006835.36      2918731.17      7007120.04
      2918700.02      7007770.59
#Sta/Elev= 30
  4686.7  419.76  4706.4  418.63  4776.5  412.45  4874.3  406.25  4896.7  405.67
  4966.9  405.64  4971.9  404.42  4976.9  404.42  4986.9   400.2  4994.1  400.52
  4995.8  400.05  4996.3  399.25    5002  399.25  5002.5  400.05  5006.9  402.56
  5016.9  405.36  5099.2  406.25    5117   407.7  5137.1  407.33  5157.1  408.04
  5197.1  412.14  5203.8  413.48  5208.8   412.8  5277.2  421.73  5347.3  429.45
  5387.3  432.98  5418.5   433.3  5437.4  435.02  5517.5  439.59  5623.2  444.06
#Mann= 3 ,-1 , 0
  4686.7     .05       0  4995.8     .03       0  5002.5     .05       0
Bank Sta=4874.3,5099.2
XS Rating Curve= 0 ,0
Exp/Cntr=0.3,0.1

Type RM Length L Ch R = 1 ,5821    ,295,295,295
BEGIN DESCRIPTION:
UNT 058 IN DRY CR WATERSHED 11.0
END DESCRIPTION:
XS GIS Cut Line= 3
      2918699.96      7006850.01        2918250.        7006950.
      2918220.75      7007866.59
#Sta/Elev= 30
  4595.7  418.42  4703.2   414.9  4764.7  411.44  4785.2  411.69  4823.6  409.32
  4828.7  409.99  4867.1  409.92  4877.4  410.98  4912.4  410.22  4938.8  409.16
  4977.6  404.64  4990.1  403.67  5004.6  397.97  5005.1  397.17  5010.8  397.17
  5011.3  397.97  5013.1  401.74  5014.4  402.01    5031  404.11  5069.9  402.73
  5167.7  403.42  5241.7  403.32  5281.4  404.64  5351.8  409.09  5491.9   420.3
  5621.9  426.24  5641.9  428.02  5685.3  428.18    5732  430.32  5973.7  437.38
#Mann= 7 ,-1 , 0
  4595.7     .05       0  4912.4     .12       0  5004.6     .07       0
  5011.3     .12       0  5014.4     .16       0  5069.9     .12       0
  5167.7     .05       0
Bank Sta=4977.6,5281.4
XS Rating Curve= 0 ,0
Exp/Cntr=0.3,0.1

Type RM Length L Ch R = 1 ,5526    ,593,593,593
BEGIN DESCRIPTION:
UNT 058 IN DRY CR WATERSHED 10.0
END DESCRIPTION:
XS GIS Cut Line= 3
      2918307.22      7006411.78        2918075.        7006875.
      2918033.78      7007638.32
#Sta/Elev= 30
  4465.7  427.13  4528.6  425.42  4558.8   422.4  4640.3  419.43    4685  416.28
  4715.4  413.34    4781  403.46  4796.7  402.58  4860.5  402.24  4930.8  401.96
  4968.7  402.82  4986.4  402.98  4993.9  400.76  5000.4  396.34  5000.9  395.54
  5006.9  395.54  5007.4  396.34  5013.9  401.89    5068  401.75  5124.1  401.99
  5186.4  403.46  5294.3  408.42  5394.5  416.05  5424.5  416.38  5434.5  414.88
  5474.6  420.06  5504.6  421.51  5624.8  425.69  5644.8  427.51  5748.3  429.61
#Mann= 6 ,-1 , 0
  4465.7     .05       0  4860.5     .12       0  4968.7     .16       0
  5000.4     .07       0  5007.4     .16       0    5068     .05       0
Bank Sta=4781,5186.4
XS Rating Curve= 0 ,0
Exp/Cntr=0.3,0.1