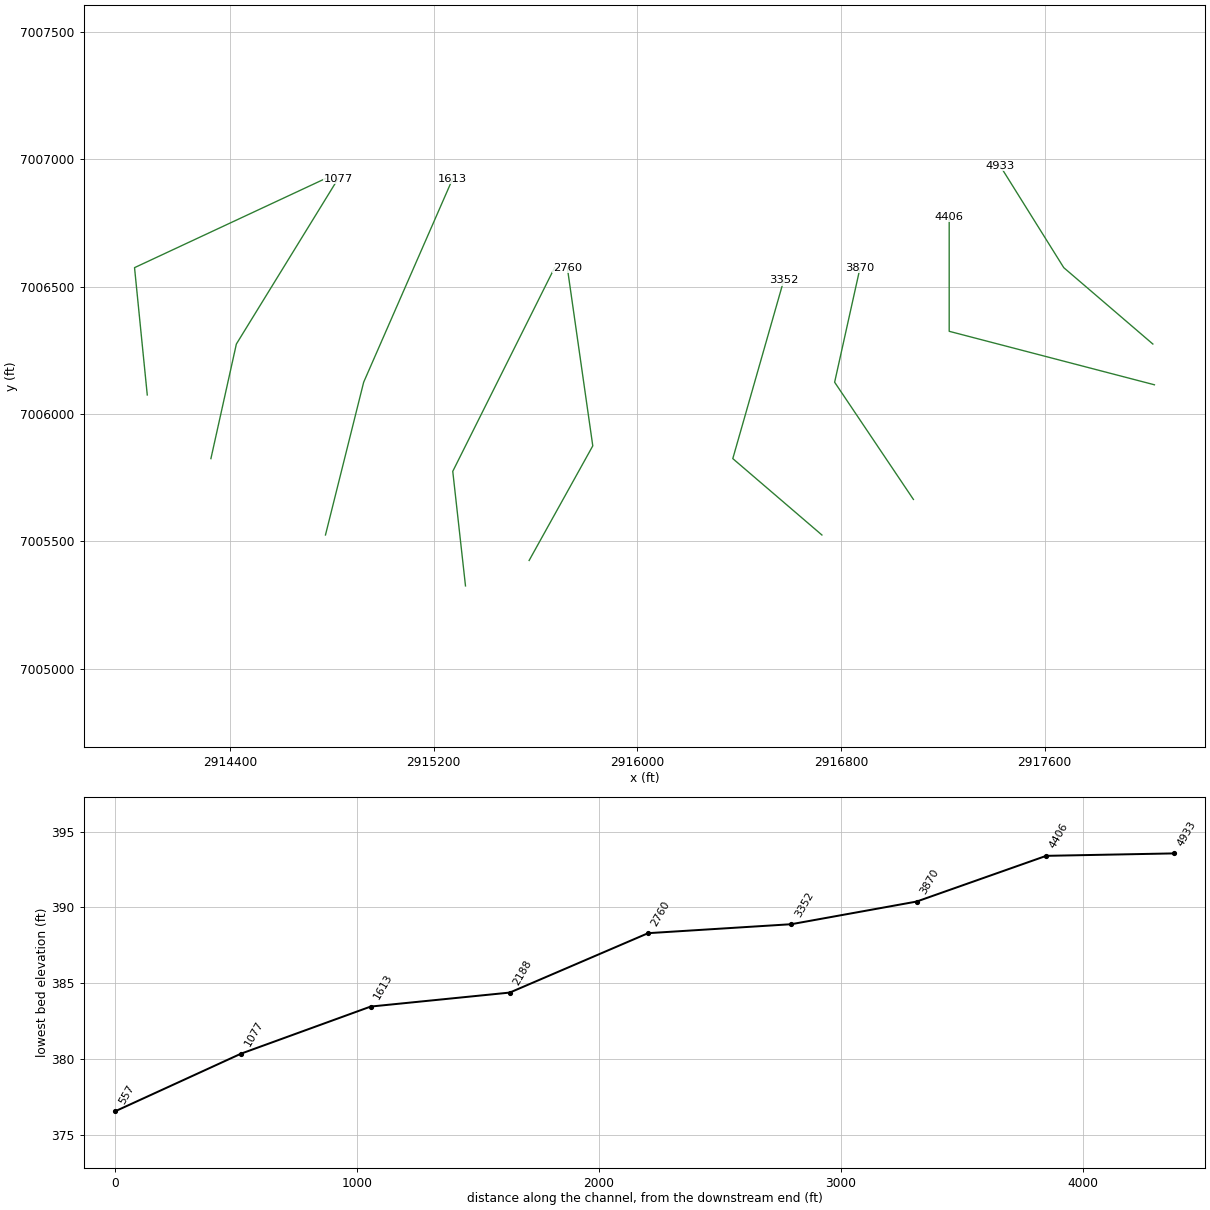
HEC-RAS study UNT 058 IN DRY CR WATERSHED.prj: UNT 058 IN DRY CR WATERSHED Base Level Engineering

--- UNT 058 IN DRY CR WATERSHED.g01 (geometry) --- (continued)

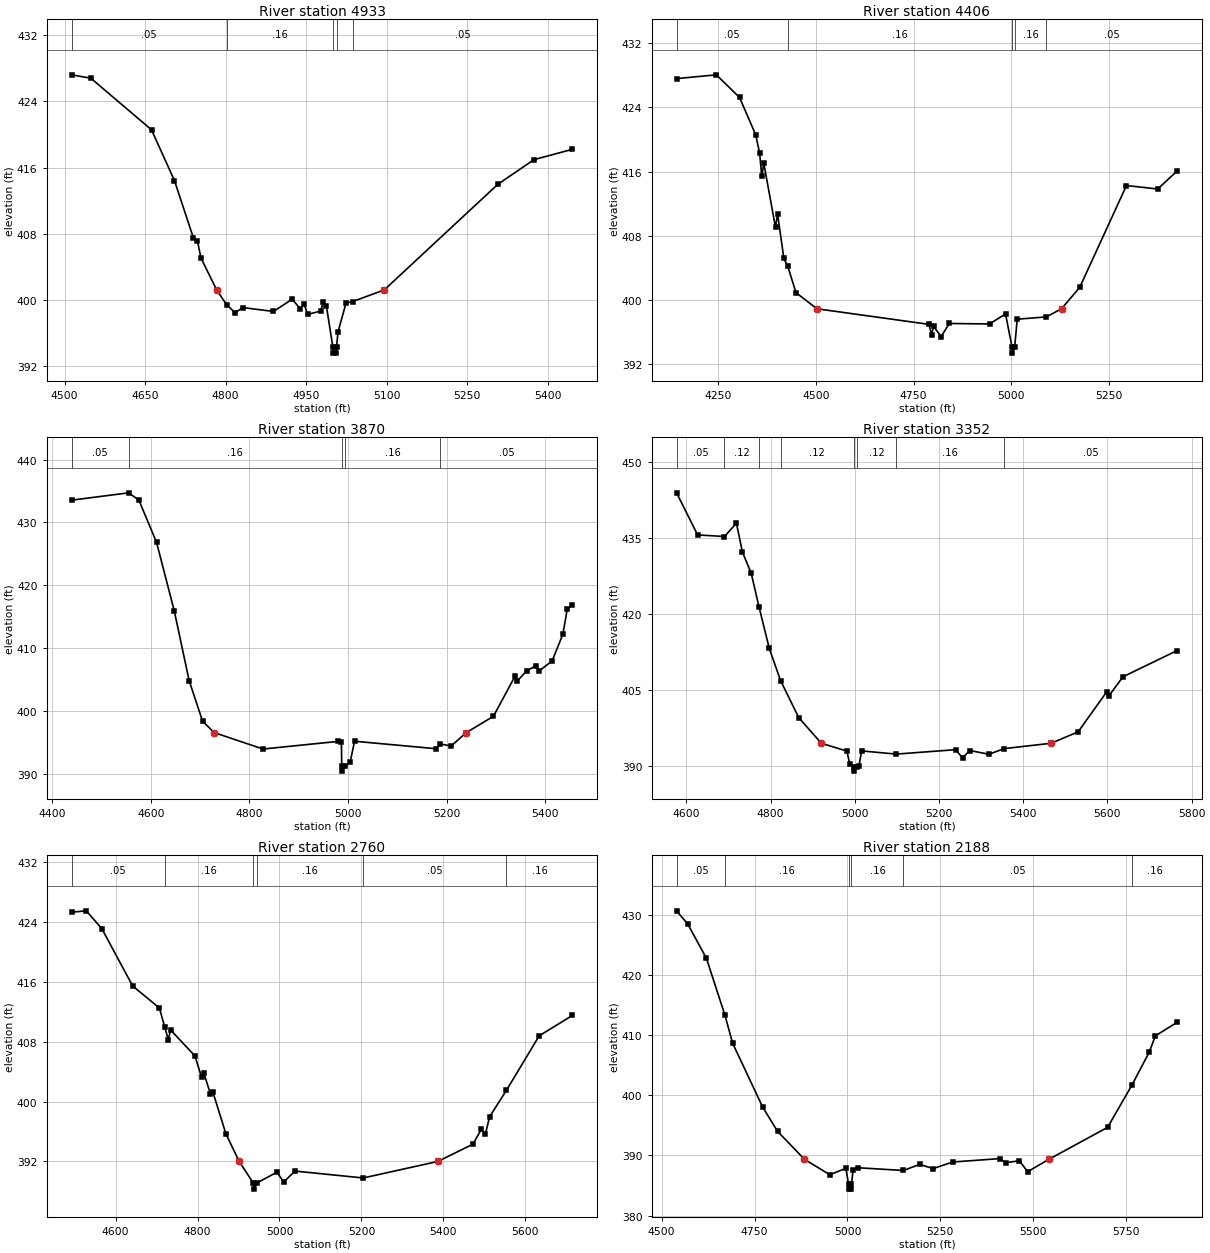
Type RM Length L Ch R = 1 ,4933    ,527,527,527
BEGIN DESCRIPTION:
UNT 058 IN DRY CR WATERSHED 9.0
END DESCRIPTION:
XS GIS Cut Line= 3
      2918024.99      7006275.01        2917675.        7006575.
      2917424.98      7006975.04
#Sta/Elev= 30
  4513.2  427.22  4548.9  426.81  4661.9  420.57  4704.7  414.42  4739.8  407.52
  4747.5  407.11  4754.1  405.06  4783.2  401.21    4802  399.39  4817.8  398.45
    4832  399.07  4889.1   398.6  4924.2  400.09  4938.5  398.94  4946.2  399.48
  4952.8  398.25  4977.1  398.64  4981.8  399.71  4987.7  399.25  4999.6  394.36
  5000.1  393.56  5006.1  393.56  5006.6  394.36  5009.5  396.16  5024.3  399.62
  5036.4  399.79  5095.6  401.21  5307.3  413.99  5374.5  416.96  5445.9  418.21
#Mann= 5 ,-1 , 0
  4513.2     .05       0    4802     .16       0  4999.6     .07       0
  5006.6     .16       0  5036.4     .05       0
Bank Sta=4783.2,5095.6
XS Rating Curve= 0 ,0
Exp/Cntr=0.3,0.1

Type RM Length L Ch R = 1 ,4406    ,536,536,536
BEGIN DESCRIPTION:
UNT 058 IN DRY CR WATERSHED 8.0
END DESCRIPTION:
XS GIS Cut Line= 3
      2918031.15      7006114.92        2917225.        7006325.
        2917225.      7006775.02
#Sta/Elev= 30
  4142.7  427.57  4244.7  428.04  4304.1  425.22  4345.4  420.59  4355.7  418.26
    4361  415.39  4366.2  417.04  4396.3  409.05  4401.5  410.73  4417.7  405.18
  4427.8  404.19  4448.7  400.93  4502.4  398.92  4789.8  396.98  4796.1  395.68
  4801.3  396.74  4820.8  395.46  4841.8  397.09  4944.8  397.03  4985.8  398.28
  5002.3   394.2  5002.8   393.4  5009.3   394.2  5015.8  397.62  5090.3  397.91
  5129.3  398.92  5175.8  401.57  5295.8  414.26  5375.8  413.83  5425.8  416.08
#Mann= 5 ,-1 , 0
  4142.7     .05       0  4427.8     .16       0  5002.3     .07       0
  5009.3     .16       0  5090.3     .05       0
Bank Sta=4502.4,5129.3
XS Rating Curve= 0 ,0
Exp/Cntr=0.3,0.1

Type RM Length L Ch R = 1 ,3870    ,518,518,518
BEGIN DESCRIPTION:
UNT 058 IN DRY CR WATERSHED 7.0
END DESCRIPTION:
XS GIS Cut Line= 3
      2917084.47      7005664.67        2916775.        7006125.
      2916875.01      7006575.04
#Sta/Elev= 30
  4439.3  433.54  4554.7  434.71  4575.5  433.56  4611.5  426.81  4647.5  415.88
  4677.5  404.82  4704.8  398.35  4728.3  396.53  4827.5  393.91  4980.5  395.13
  4986.5  394.97  4987.2  391.19  4987.8  390.39  4994.7  391.19  5004.2  391.81
  5013.2  395.15  5178.4  393.96  5187.5  394.71  5209.1  394.39    5240  396.53
  5294.9  399.12  5338.4  405.46  5343.6  404.77  5362.8  406.39    5382  407.19
  5387.1  406.31    5414  407.94  5435.8  412.19  5444.7  416.19    5455  416.88
#Mann= 5 ,-1 , 0
  4439.3     .05       0  4554.7     .16       0  4987.2     .07       0
  4994.7     .16       0  5187.5     .05       0
Bank Sta=4728.3,5240
XS Rating Curve= 0 ,0
Exp/Cntr=0.3,0.1

Type RM Length L Ch R = 1 ,3352    ,592,592,592
BEGIN DESCRIPTION:
UNT 058 IN DRY CR WATERSHED 6.0
END DESCRIPTION:
XS GIS Cut Line= 3
      2916725.03      7005524.97        2916375.        7005825.
      2916574.99      7006524.97
#Sta/Elev= 30
  4576.7  443.82  4626.7  435.51  4690.5   435.2  4718.9  437.83  4733.1  432.12
    4754  427.94  4772.3  421.38  4796.8  413.14  4823.6  406.78    4867  399.44
  4920.5   394.4  4981.2  392.85  4987.8  390.38  4998.3   389.7  4998.8   388.9
  5005.8   389.7  5009.7  389.88  5016.3  392.89  5098.3  392.26  5239.2  393.13
  5256.1  391.51    5273  392.97  5318.5  392.23  5354.6  393.34  5466.3   394.4
  5530.4  396.65    5598  404.51  5603.2  403.73    5637  407.52  5765.7   412.7
#Mann= 8 ,-1 , 0
  4576.7     .05       0  4690.5     .12       0  4772.3     .16       0
  4823.6     .12       0  4998.3     .07       0  5005.8     .12       0
  5098.3     .16       0  5354.6     .05       0
Bank Sta=4920.5,5466.3
XS Rating Curve= 0 ,0
Exp/Cntr=0.3,0.1

Type RM Length L Ch R = 1 ,2760    ,572,572,572
BEGIN DESCRIPTION:
UNT 058 IN DRY CR WATERSHED 5.0
END DESCRIPTION:
XS GIS Cut Line= 3
      2915574.98      7005424.96        2915825.        7005875.
        2915725.      7006574.97
#Sta/Elev= 30
  4492.9  425.28  4528.4  425.46  4566.2   423.1  4641.7  415.43  4706.9  412.49
    4720  409.94  4728.6  408.26  4734.3  409.56  4793.8  406.08  4809.8  403.26
  4815.5  403.79  4831.6  401.01  4837.3   401.3  4869.3  395.69  4901.7  392.01
  4936.3  389.11    4937  388.31  4944.1  389.11    4994  390.57  5010.2  389.26
    5038  390.72  5204.4   389.8  5386.9  392.01  5472.4  394.32  5492.6   396.3
  5502.7  395.67  5512.8  397.96    5554   401.5    5634  408.78  5714.8  411.49
#Mann= 6 ,-1 , 0
  4492.9     .05       0    4720     .16       0  4936.3     .07       0
  4944.1     .16       0  5204.4     .05       0    5554     .16       0
Bank Sta=4901.7,5386.9
XS Rating Curve= 0 ,0
Exp/Cntr=0.3,0.1

Type RM Length L Ch R = 1 ,2188    ,575,575,575
BEGIN DESCRIPTION:
UNT 058 IN DRY CR WATERSHED 4.0
END DESCRIPTION:
XS GIS Cut Line= 3
        2915325.      7005324.99        2915275.        7005775.
        2915675.      7006574.99
#Sta/Elev= 30
  4540.2  430.66  4570.4  428.46  4620.7  422.74  4670.2  413.34  4691.1  408.65
  4771.6  398.07  4811.9  394.01  4884.2  389.36  4952.7  386.79  4995.8  387.86
  5003.1   385.2  5003.7   384.4  5010.2   384.4  5010.9   385.2  5015.3  387.63
  5029.3  387.95  5150.6   387.5  5194.2  388.51  5230.6  387.82  5283.7  388.91
  5409.5  389.47  5426.2  388.79  5462.6  389.12  5484.9   387.3  5542.2  389.36
  5700.1  394.67  5765.1  401.64  5811.9  407.14  5828.7  409.88  5887.4  412.13
#Mann= 6 ,-1 , 0
  4540.2     .05       0  4670.2     .16       0  5003.1     .07       0
  5010.9     .16       0  5150.6     .05       0  5765.1     .16       0
Bank Sta=4884.2,5542.2
XS Rating Curve= 0 ,0
Exp/Cntr=0.3,0.1

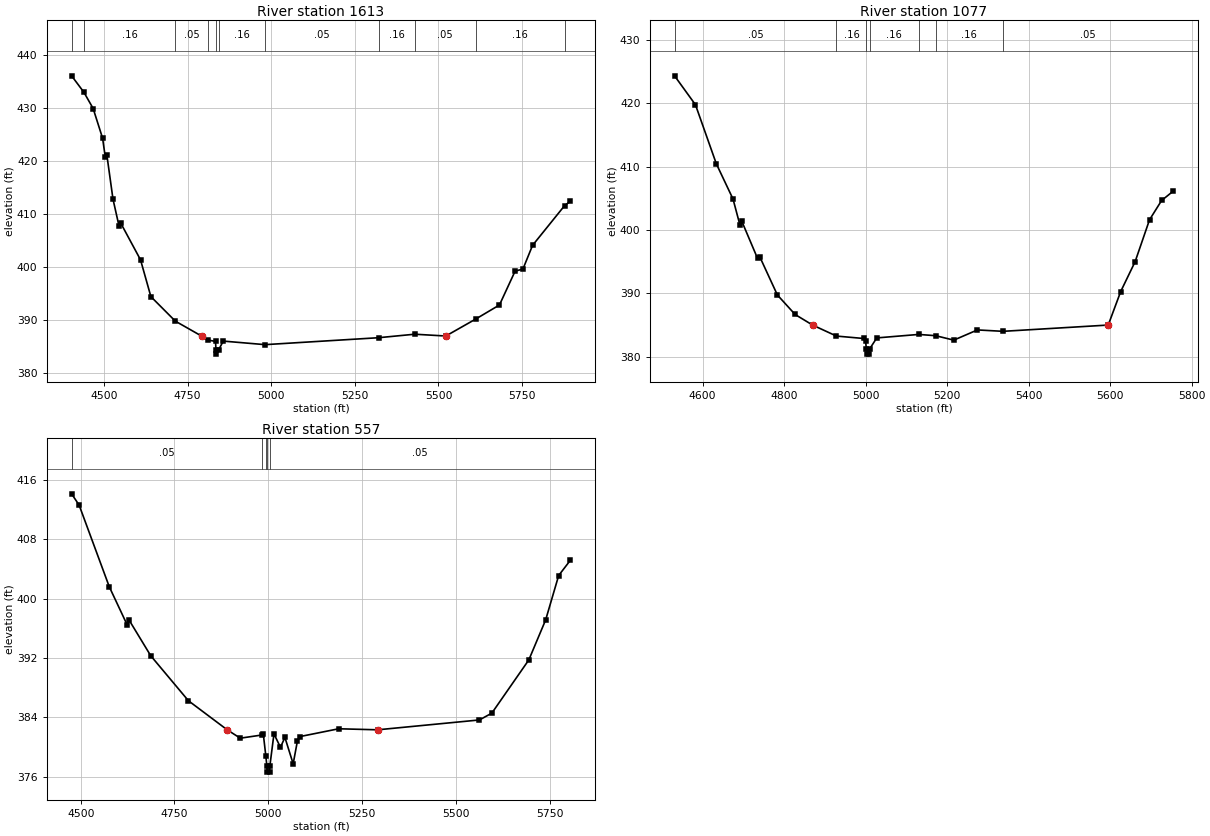
Type RM Length L Ch R = 1 ,1613    ,536,536,536
BEGIN DESCRIPTION:
UNT 058 IN DRY CR WATERSHED 3.0
END DESCRIPTION:
XS GIS Cut Line= 3
      2914775.01      7005525.04        2914925.        7006125.
      2915274.99      7006924.97
#Sta/Elev= 30
  4403.2  436.03  4439.9  432.93  4467.6  429.86  4495.9  424.23  4503.7  420.75
  4508.8     421  4526.9  412.75  4544.9  407.68    4550  408.23  4609.3  401.28
  4640.2  394.34  4713.3  389.71  4791.6   386.9  4810.6  386.14  4833.5  385.88
  4834.8  384.28  4835.4  383.48  4842.6  384.28  4856.7  385.94  4981.6  385.27
  5321.1  386.58    5429  387.24  5522.1   386.9  5610.8  390.08  5682.4  392.76
  5729.2  399.15  5752.6  399.54  5781.4  404.02  5877.3  411.53  5894.8  412.35
#Mann= 11 ,-1 , 0
  4403.2     .05       0  4439.9     .16       0  4713.3     .05       0
  4810.6     .16       0  4834.8     .03       0  4842.6     .16       0
  4981.6     .05       0  5321.1     .16       0    5429     .05       0
  5610.8     .16       0  5877.3     .05       0
Bank Sta=4791.6,5522.1
XS Rating Curve= 0 ,0
Exp/Cntr=0.3,0.1

Type RM Length L Ch R = 1 ,1077    ,520,520,520
BEGIN DESCRIPTION:
UNT 058 IN DRY CR WATERSHED 2.0
END DESCRIPTION:
XS GIS Cut Line= 3
      2914324.99      7005824.96        2914425.        7006275.
      2914824.98      7006924.97
#Sta/Elev= 30
  4531.1  424.32  4582.4  419.75  4633.6  410.43  4674.6  404.86  4691.2  400.84
  4696.3  401.33  4734.7   395.5  4739.9  395.79  4783.4  389.72  4826.9  386.64
  4869.8  384.97  4928.4  383.23  4995.1  382.85  4999.8  382.49  5001.7  381.18
  5002.4  380.38    5009  380.38  5009.6  381.18  5027.3  382.94  5130.4  383.49
  5171.7  383.29  5216.3  382.59  5274.3   384.2  5337.1  383.98  5595.3  384.97
  5625.8  390.25  5661.4     395  5696.6  401.59  5726.3  404.64  5755.3  406.14
#Mann= 7 ,-1 , 0
  4531.1     .05       0  4928.4     .16       0  5001.7     .07       0
  5009.6     .16       0  5130.4     .05       0  5171.7     .16       0
  5337.1     .05       0
Bank Sta=4869.8,5595.3
XS Rating Curve= 0 ,0
Exp/Cntr=0.3,0.1

Type RM Length L Ch R = 1 ,557     ,0,0,0
BEGIN DESCRIPTION:
UNT 058 IN DRY CR WATERSHED 1.0
END DESCRIPTION:
XS GIS Cut Line= 3
        2914075.      7006075.05        2914025.        7006575.
      2914775.01        7006925.
#Sta/Elev= 30
  4475.8  414.14  4495.9  412.61  4576.3  401.59    4624  396.45    4629  397.11
  4686.8  392.29  4787.3  386.22  4890.6   382.3  4925.5  381.17  4983.3   381.6
  4986.9  381.72  4993.6  378.78  4996.4  377.39    4997  376.59  5003.6  376.59
  5004.3  377.39  5015.3  381.75  5032.6  379.94  5044.5  381.27  5066.5  377.71
  5077.6  380.73  5083.9  381.38  5187.9  382.44  5291.7   382.3  5563.1  383.63
  5596.2  384.55  5694.8  391.73  5739.7  397.13  5774.4  403.12  5805.9   405.2
#Mann= 5 ,-1 , 0
  4475.8     .05       0  4983.3     .16       0  4993.6     .05       0
  4996.4     .03       0  5004.3     .05       0
Bank Sta=4890.6,5291.7
XS Rating Curve= 0 ,0
Exp/Cntr=0.3,0.1
LCMann Table=0

Chan Stop Cuts=-1
Use User Specified Reach Order=0
Composite Channel Slope=5