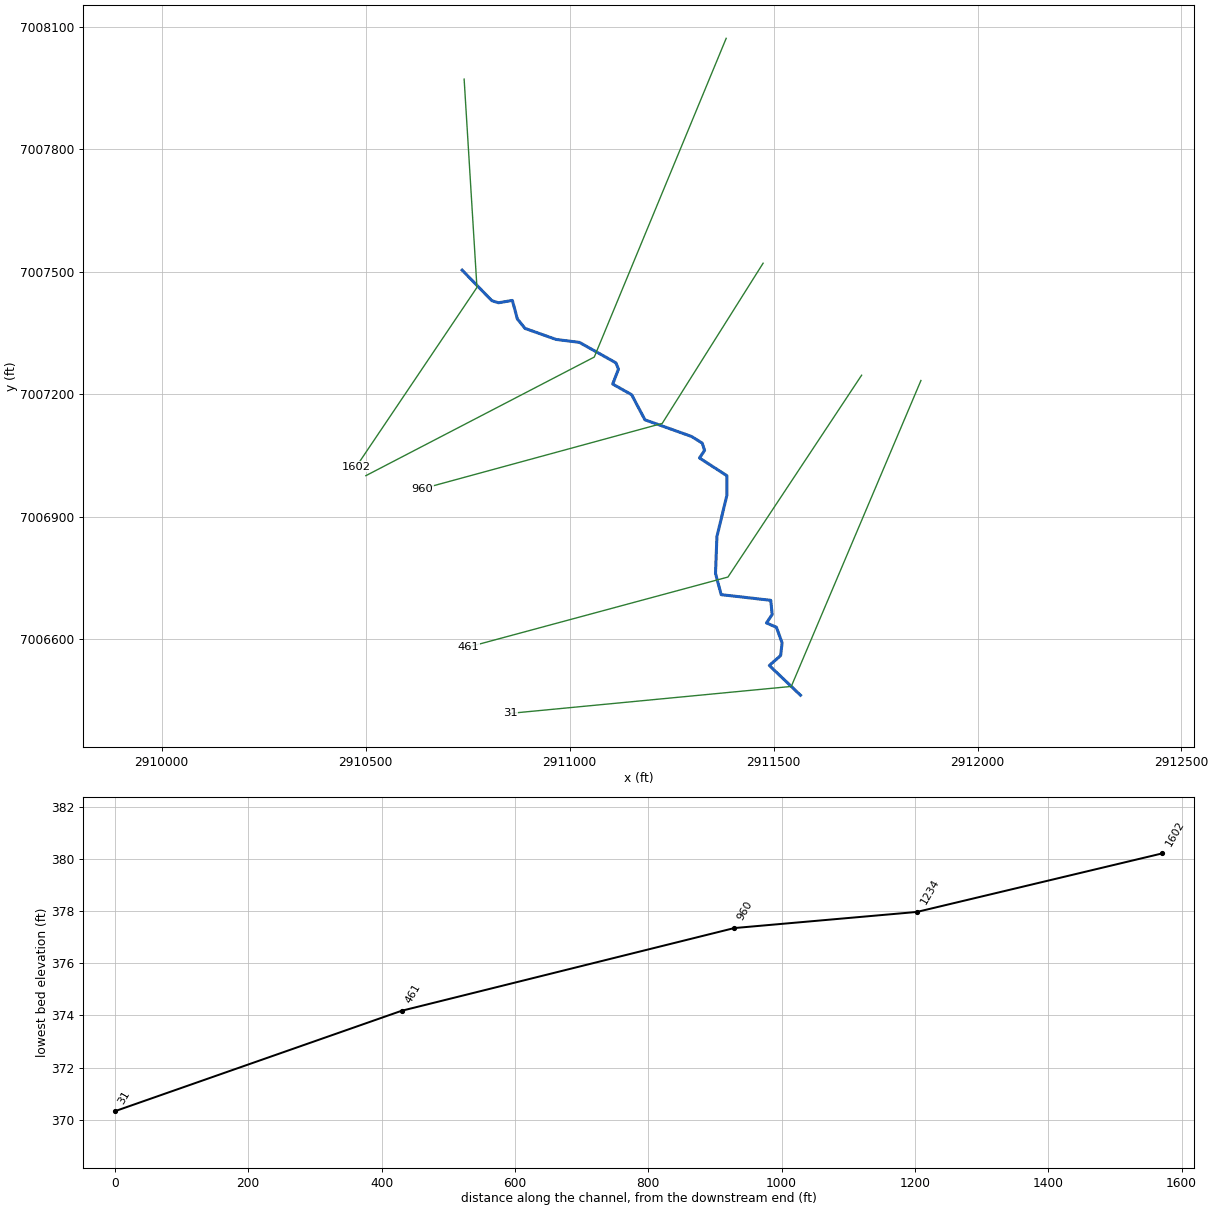
--- UNT 059 IN DRY CR WATERSHED.prj (project) ---

Proj Title=UNT 059 IN DRY CR WATERSHED Base Level Engineering
Current Plan=p01
Default Exp/Contr=0.3,0.1
English Units
Geom File=g01
Flow File=f01
Plan File=p01
BEGIN DESCRIPTION:
UNT 059 IN DRY CR WATERSHED
END DESCRIPTION:

--- UNT 059 IN DRY CR WATERSHED.p01 (plan) ---

Plan Title=Multiple Run
Short Identifier=Multiple
Geom File=g01
Flow File=f01
Subcritical Flow
K Sum by GR= 0
Std Step Tol= 0.01
Critical Tol= 0.01
Num of Std Step Trials= 20
Max Error Tol= 0.3
Flow Tol Ratio= 0.001
Split Flow NTrial= 30
Split Flow Tol= 0.02
Split Flow Ratio= 0.02
Log Output Level= 0
Friction Slope Method= 1
Unsteady Friction Slope Method= 2
Unsteady Bridges Friction Slope Method= 1
Parabolic Critical Depth
Global Vel Dist=  1 , 1 , 1
Global Log Level= 0
CheckData=True
Encroach Param= -1, 0, 0, 0
BEGIN DESCRIPTION:
Multiple Run
END DESCRIPTION:

--- UNT 059 IN DRY CR WATERSHED.f01 (steady flow) ---

Flow Title=Multiple
Number of Profiles=7
Profile Names=10-year,25-year,50-year,1pct_min,100-year,1pct_plu,500-year
River Rch & RM= UNT 059 IN DRY C,Reach-1,1602
     215     268     308     176     351     701     457
Boundary for River Rch & Prof#=UNT 059 IN DRY C,Reach-1,1
Up Type=0
Dn Type=3
Dn Slope=0.005
Boundary for River Rch & Prof#=UNT 059 IN DRY C,Reach-1,2
Up Type=0
Dn Type=3
Dn Slope=0.005
Boundary for River Rch & Prof#=UNT 059 IN DRY C,Reach-1,3
Up Type=0
Dn Type=3
Dn Slope=0.005
Boundary for River Rch & Prof#=UNT 059 IN DRY C,Reach-1,4
Up Type=0
Dn Type=3
Dn Slope=0.005
Boundary for River Rch & Prof#=UNT 059 IN DRY C,Reach-1,5
Up Type=0
Dn Type=3
Dn Slope=0.005
Boundary for River Rch & Prof#=UNT 059 IN DRY C,Reach-1,6
Up Type=0
Dn Type=3
Dn Slope=0.005
Boundary for River Rch & Prof#=UNT 059 IN DRY C,Reach-1,7
Up Type=0
Dn Type=3
Dn Slope=0.005

--- UNT 059 IN DRY CR WATERSHED.g01 (geometry) ---

Geom Title=Existing Conditions

River Reach=UNT 059 IN DRY C,Reach-1
Reach XY= 30
      2910736.57      7007504.03      2910809.64      7007428.96
      2910825.85      7007423.98      2910859.75      7007429.76
      2910872.06      7007384.23      2910890.80      7007361.14
      2910966.95      7007334.07      2911024.06      7007326.92
      2911113.36      7007276.88      2911119.94      7007261.50
      2911105.71      7007224.68      2911152.22      7007198.58
      2911184.67      7007137.09      2911299.21      7007096.18
      2911325.15      7007080.01      2911330.98      7007062.09
      2911318.46      7007043.48      2911385.52      7007000.14
      2911385.52      7006951.53      2911361.21      7006850.84
      2911357.74      7006760.56      2911371.63      7006708.48
      2911493.16      7006694.59      2911496.63      7006659.86
      2911482.74      7006639.03      2911507.05      7006628.61
      2911520.93      7006590.42      2911517.46      7006559.17
      2911489.68      7006534.86      2911566.07      7006461.95

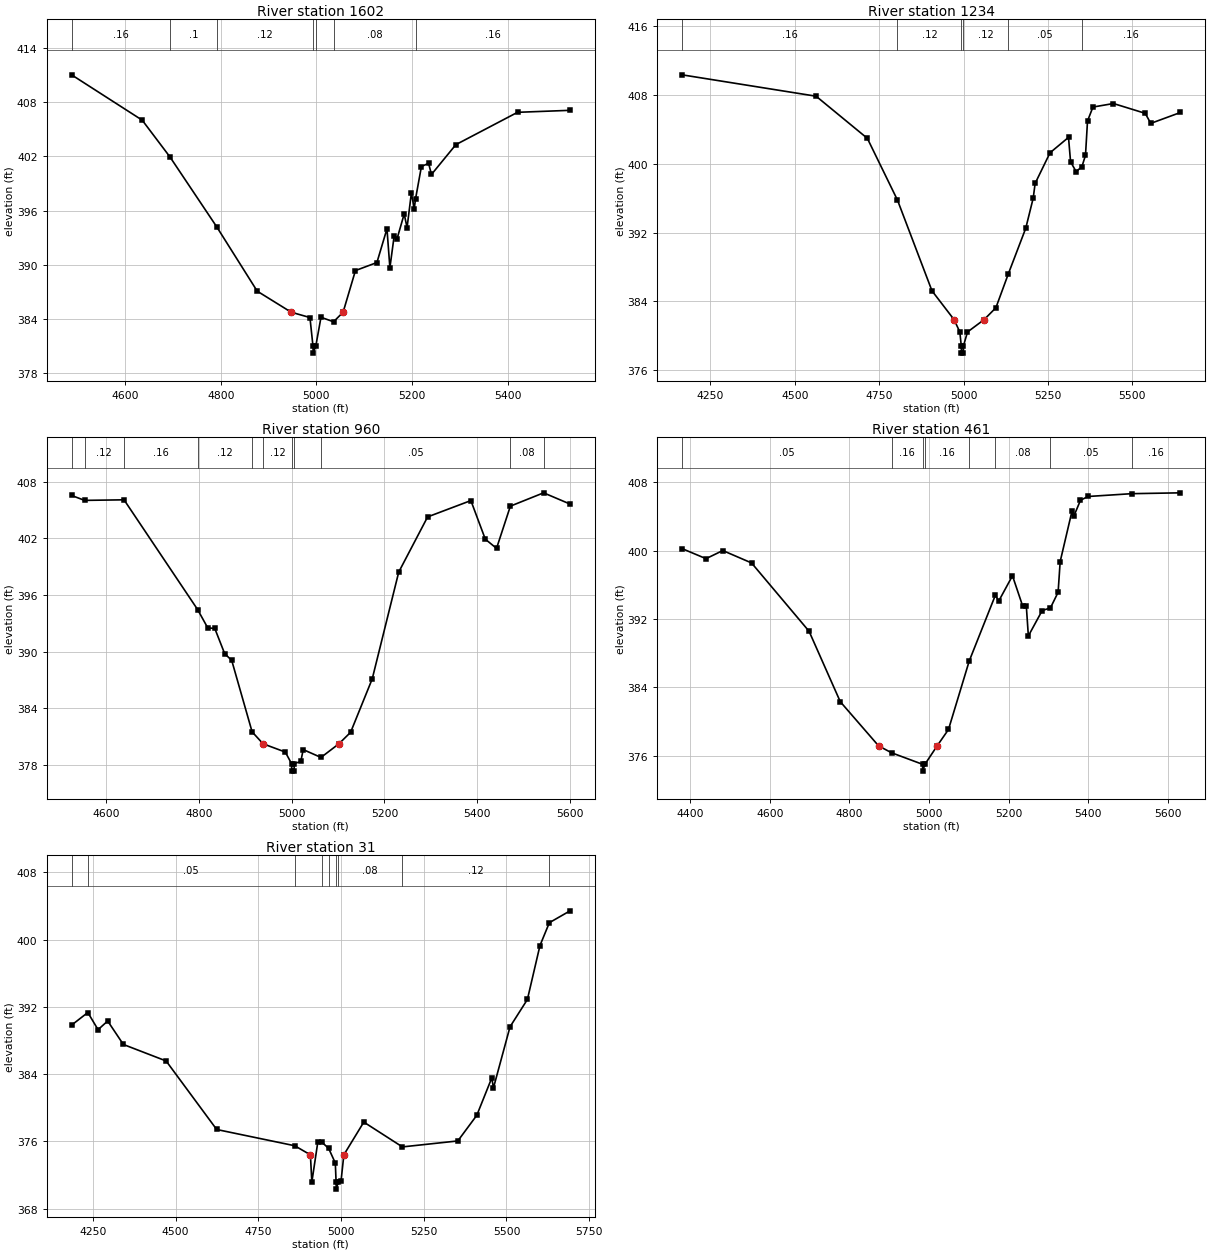
Type RM Length L Ch R = 1,1602,368,368,368
BEGIN DESCRIPTION:
UNT 059 IN DRY CR WATERSHED 2.0
END DESCRIPTION:
XS GIS Cut Line= 3
      2910741.54      7007972.30      2910772.96      7007461.56
      2910476.77      7007021.80
#Sta/Elev= 30
  4488.3  411.04  4635.9  406.02  4693.9  401.95  4791.8  394.20  4876.3  387.09
  4947.3  384.76  4986.5  384.17  4992.8  381.03  4993.3  380.23  4998.8  381.03
  5009.6  384.20  5035.8  383.70  5055.8  384.76  5081.6  389.37  5126.5  390.26
  5147.5  394.00  5153.6  389.68  5162.5  393.19  5168.5  392.87  5183.5  395.64
  5189.5  394.12  5198.5  397.95  5204.5  396.23  5207.2  397.30  5219.5  400.89
  5234.5  401.24  5240.5  400.01  5291.5  403.31  5420.4  406.89  5530.2  407.11
#Mann=7,-1,0
  4488.3    0.16       0  4693.9     0.1       0  4791.8    0.12       0
  4992.8    0.07       0  4998.8    0.12       0  5035.8    0.08       0
  5207.2    0.16       0
Bank Sta=4947.3,5055.8
Exp/Cntr=0.3,0.1

Type RM Length L Ch R = 1,1234,274,274,274
BEGIN DESCRIPTION:
Mapping XS 0fbc7cfe
END DESCRIPTION:
XS GIS Cut Line= 3
      2911383.92      7008072.21      2911060.55      7007290.91
      2910500.64      7007000.11
#Sta/Elev= 30
  4166.1  410.37  4563.3  407.88  4715.0  402.98  4804.3  395.79  4906.5  385.23
  4971.9  381.88  4989.0  380.44  4993.4  378.78  4993.9  377.98  4998.9  377.98
  4999.4  378.78  5011.7  380.44  5060.9  381.88  5095.8  383.26  5132.8  387.22
  5184.3  392.52  5206.4  396.03  5212.0  397.73  5256.2  401.30  5310.9  403.09
  5317.0  400.25  5333.4  399.11  5350.5  399.67  5361.2  401.00  5367.2  405.00
  5383.3  406.62  5444.0  407.03  5538.1  405.89  5554.6  404.72  5642.6  405.99
#Mann=6,-1,0
  4166.1    0.16       0  4804.3    0.12       0  4993.4    0.07       0
  4999.4    0.12       0  5132.8    0.05       0  5350.5    0.16       0
Bank Sta=4971.9,5060.9
Exp/Cntr=0.3,0.1

Type RM Length L Ch R = 1,960,499,499,499
BEGIN DESCRIPTION:
Mapping XS 2c3a63f5
END DESCRIPTION:
XS GIS Cut Line= 3
      2911474.46      7007521.02      2911227.04      7007128.18
      2910638.85      7006967.93
#Sta/Elev= 30
  4526.1  406.55  4554.2  406.03  4639.1  406.09  4797.6  394.47  4819.4  392.53
  4834.6  392.47  4855.8  389.81  4871.1  389.08  4915.0  381.52  4938.5  380.26
  4939.4  380.24  4986.5  379.38  4999.9  378.16  5000.4  377.36  5005.4  377.36
  5005.9  378.16  5019.9  378.38  5025.1  379.64  5063.4  378.81  5101.9  380.25
  5127.2  381.47  5173.8  387.13  5230.9  398.44  5293.1  404.28  5386.3  406.01
  5417.4  401.92  5441.6  400.95  5471.4  405.42  5543.0  406.83  5600.0  405.64
#Mann=11,-1,0
  4526.1    0.16       0  4554.2    0.12       0  4639.1    0.16       0
  4797.6    0.12       0  4915.0    0.16       0  4939.4    0.12       0
  4999.9    0.07       0  5005.9    0.12       0  5063.4    0.05       0
  5471.4    0.08       0  5543.0    0.16       0
Bank Sta=4938.5,5101.9
Exp/Cntr=0.3,0.1

Type RM Length L Ch R = 1,461,430,430,430
BEGIN DESCRIPTION:
Mapping XS 68b472c0
END DESCRIPTION:
XS GIS Cut Line= 3
      2911715.91      7007246.40      2911388.24      7006751.63
      2910752.38      7006580.19
#Sta/Elev= 30
  4379.4  400.24  4439.7  399.06  4481.8  400.01  4554.0  398.56  4698.5  390.56
  4776.9  382.31  4873.1  377.14  4905.6  376.33  4983.5  374.98  4984.0  374.18
  4989.5  374.98  5020.2  377.14  5048.7  379.06  5100.8  387.08  5166.6  394.80
  5174.7  394.08  5209.4  397.06  5235.1  393.50  5244.1  393.56  5249.3  390.01
  5284.1  392.99  5304.7  393.29  5324.0  395.12  5329.2  398.72  5358.7  404.59
  5363.9  404.08  5380.1  405.89  5398.7  406.34  5508.6  406.67  5631.4  406.77
#Mann=8,-1,0
  4379.4    0.05       0  4905.6    0.16       0  4983.5    0.07       0
  4989.5    0.16       0  5100.8    0.05       0  5166.6    0.08       0
  5304.7    0.05       0  5508.6    0.16       0
Bank Sta=4873.1,5020.2
Exp/Cntr=0.3,0.1

Type RM Length L Ch R = 1,31,0,0,0
BEGIN DESCRIPTION:
UNT 059 IN DRY CR WATERSHED 1.0
END DESCRIPTION:
XS GIS Cut Line= 3
      2911861.33      7007233.41      2911543.52      7006483.48
      2910854.37      7006417.43
#Sta/Elev= 30
  4185.5  389.82  4234.6  391.32  4265.5  389.28  4294.6  390.31  4342.0  387.52
  4471.2  385.56  4624.1  377.41  4859.8  375.48  4907.4  374.40  4911.7  371.15
  4929.9  375.95  4942.4  375.89  4962.6  375.16  4982.7  373.42  4985.1  371.12
  4985.6  370.32  4991.1  371.12  5000.0  371.28  5008.5  374.40  5068.8  378.29
  5185.5  375.34  5353.0  376.05  5410.4  379.10  5455.7  383.55  5460.7  382.35
  5510.8  389.62  5563.3  392.87  5601.3  399.28  5629.7  402.00  5692.3  403.41
#Mann=9,-1,0
  4185.5    0.12       0  4234.6    0.05       0  4859.8    0.12       0
  4942.4    0.16       0  4962.6    0.08       0  4985.1    0.07       0
  4991.1    0.08       0  5185.5    0.12       0  5629.7    0.16       0
Bank Sta=4907.4,5008.5
Exp/Cntr=0.3,0.1

Chan Stop Cuts=-1