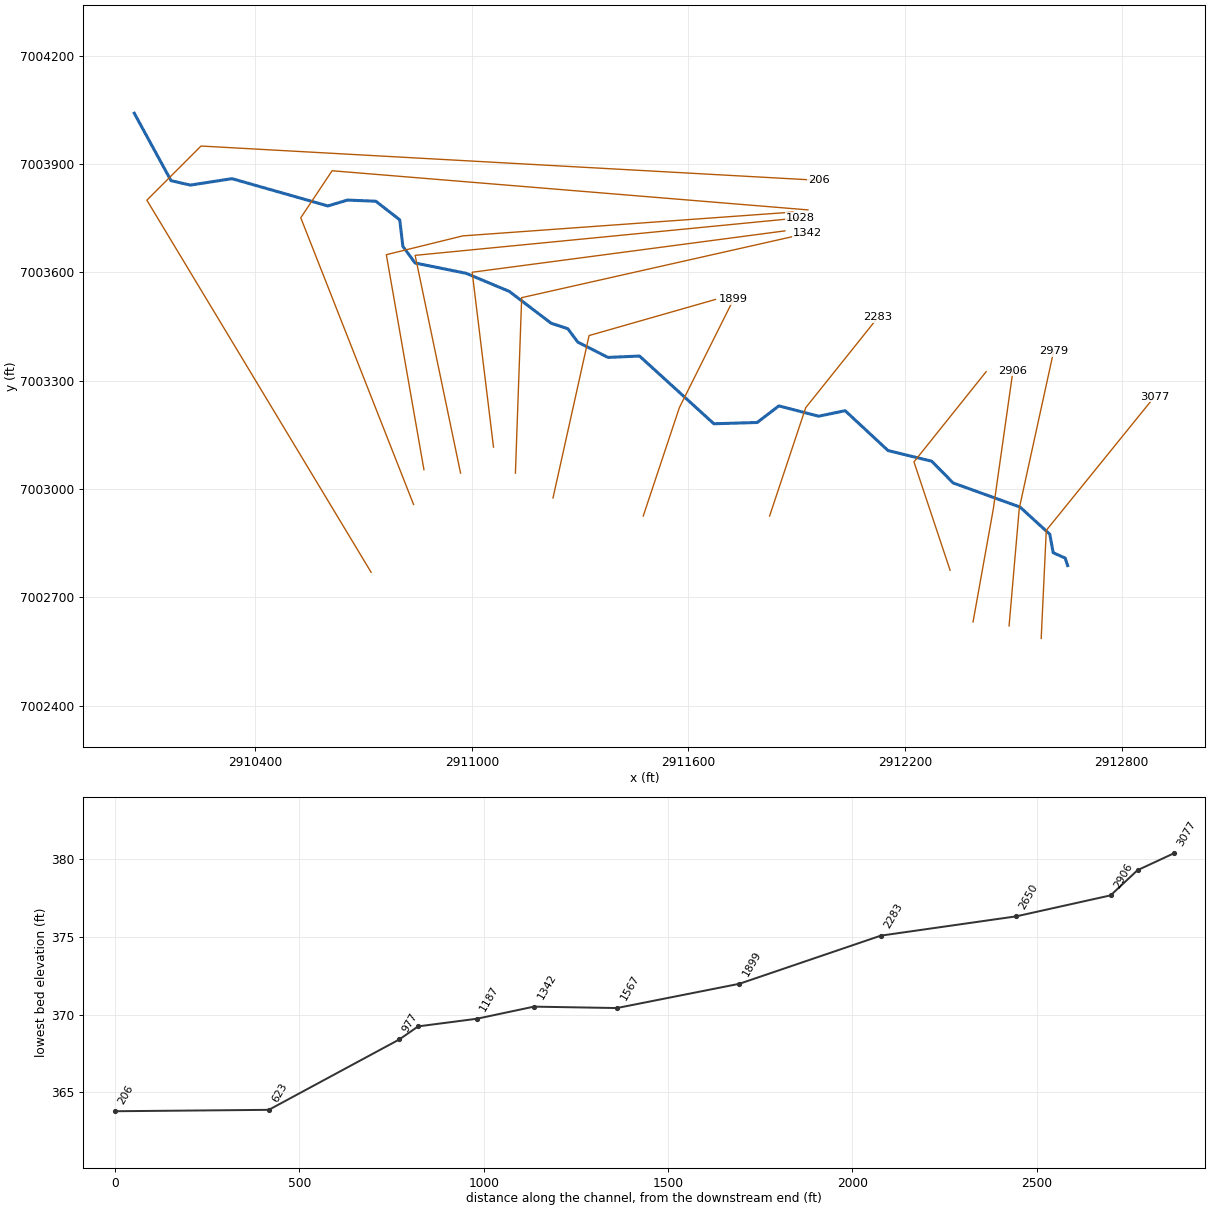
--- UNT 060 IN DRY CR WATERSHED.prj (project) ---

Proj Title=UNT 060 IN DRY CR WATERSHED Base Level Engineering
Current Plan=p01
Default Exp/Contr=0.3,0.1
English Units
Geom File=g01
Flow File=f01
Plan File=p01
BEGIN DESCRIPTION:
UNT 060 IN DRY CR WATERSHED
END DESCRIPTION:

--- UNT 060 IN DRY CR WATERSHED.p01 (plan) ---

Plan Title=Multiple Run
Short Identifier=Multiple
Geom File=g01
Flow File=f01
Subcritical Flow
K Sum by GR= 0
Std Step Tol= 0.01
Critical Tol= 0.01
Num of Std Step Trials= 20
Max Error Tol= 0.3
Flow Tol Ratio= 0.001
Split Flow NTrial= 30
Split Flow Tol= 0.02
Split Flow Ratio= 0.02
Log Output Level= 0
Friction Slope Method= 1
Unsteady Friction Slope Method= 2
Unsteady Bridges Friction Slope Method= 1
Parabolic Critical Depth
Global Vel Dist=  1 , 1 , 1
Global Log Level= 0
CheckData=True
Encroach Param= -1, 0, 0, 0
BEGIN DESCRIPTION:
Multiple Run
END DESCRIPTION:

--- UNT 060 IN DRY CR WATERSHED.f01 (steady flow) ---

Flow Title=Multiple
Number of Profiles=7
Profile Names=10-year,25-year,50-year,1pct_min,100-year,1pct_plu,500-year
River Rch & RM= UNT 060 IN DRY C,Reach-1,3077
     332     432     511     302     602    1201     833
Boundary for River Rch & Prof#=UNT 060 IN DRY C,Reach-1,1
Up Type=0
Dn Type=3
Dn Slope=0.005
Boundary for River Rch & Prof#=UNT 060 IN DRY C,Reach-1,2
Up Type=0
Dn Type=3
Dn Slope=0.005
Boundary for River Rch & Prof#=UNT 060 IN DRY C,Reach-1,3
Up Type=0
Dn Type=3
Dn Slope=0.005
Boundary for River Rch & Prof#=UNT 060 IN DRY C,Reach-1,4
Up Type=0
Dn Type=3
Dn Slope=0.005
Boundary for River Rch & Prof#=UNT 060 IN DRY C,Reach-1,5
Up Type=0
Dn Type=3
Dn Slope=0.005
Boundary for River Rch & Prof#=UNT 060 IN DRY C,Reach-1,6
Up Type=0
Dn Type=3
Dn Slope=0.005
Boundary for River Rch & Prof#=UNT 060 IN DRY C,Reach-1,7
Up Type=0
Dn Type=3
Dn Slope=0.005

--- UNT 060 IN DRY CR WATERSHED.g01 (geometry) ---

Geom Title=Existing Conditions

River Reach=UNT 060 IN DRY C,Reach-1
Reach XY= 30
      2912650.78      7002787.85      2912643.97      7002808.45
      2912610.65      7002823.46      2912601.27      7002874.53
      2912518.87      7002949.89      2912333.59      7003016.66
      2912274.08      7003076.87      2912153.22      7003106.42
      2912034.32      7003216.83      2911960.89      7003201.59
      2911850.70      7003230.11      2911790.72      7003184.19
      2911670.72      7003180.63      2911464.68      7003368.25
      2911377.30      7003364.44      2911293.64      7003406.87
      2911266.18      7003443.89      2911219.79      7003459.16
      2911104.15      7003547.23      2910984.26      7003597.49
      2910843.01      7003626.01      2910809.15      7003672.09
      2910800.46      7003745.71      2910734.16      7003797.14
      2910655.76      7003800.29      2910601.26      7003784.06
      2910335.76      7003859.63      2910220.43      7003841.80
      2910166.96      7003854.04      2910065.15      7004040.78

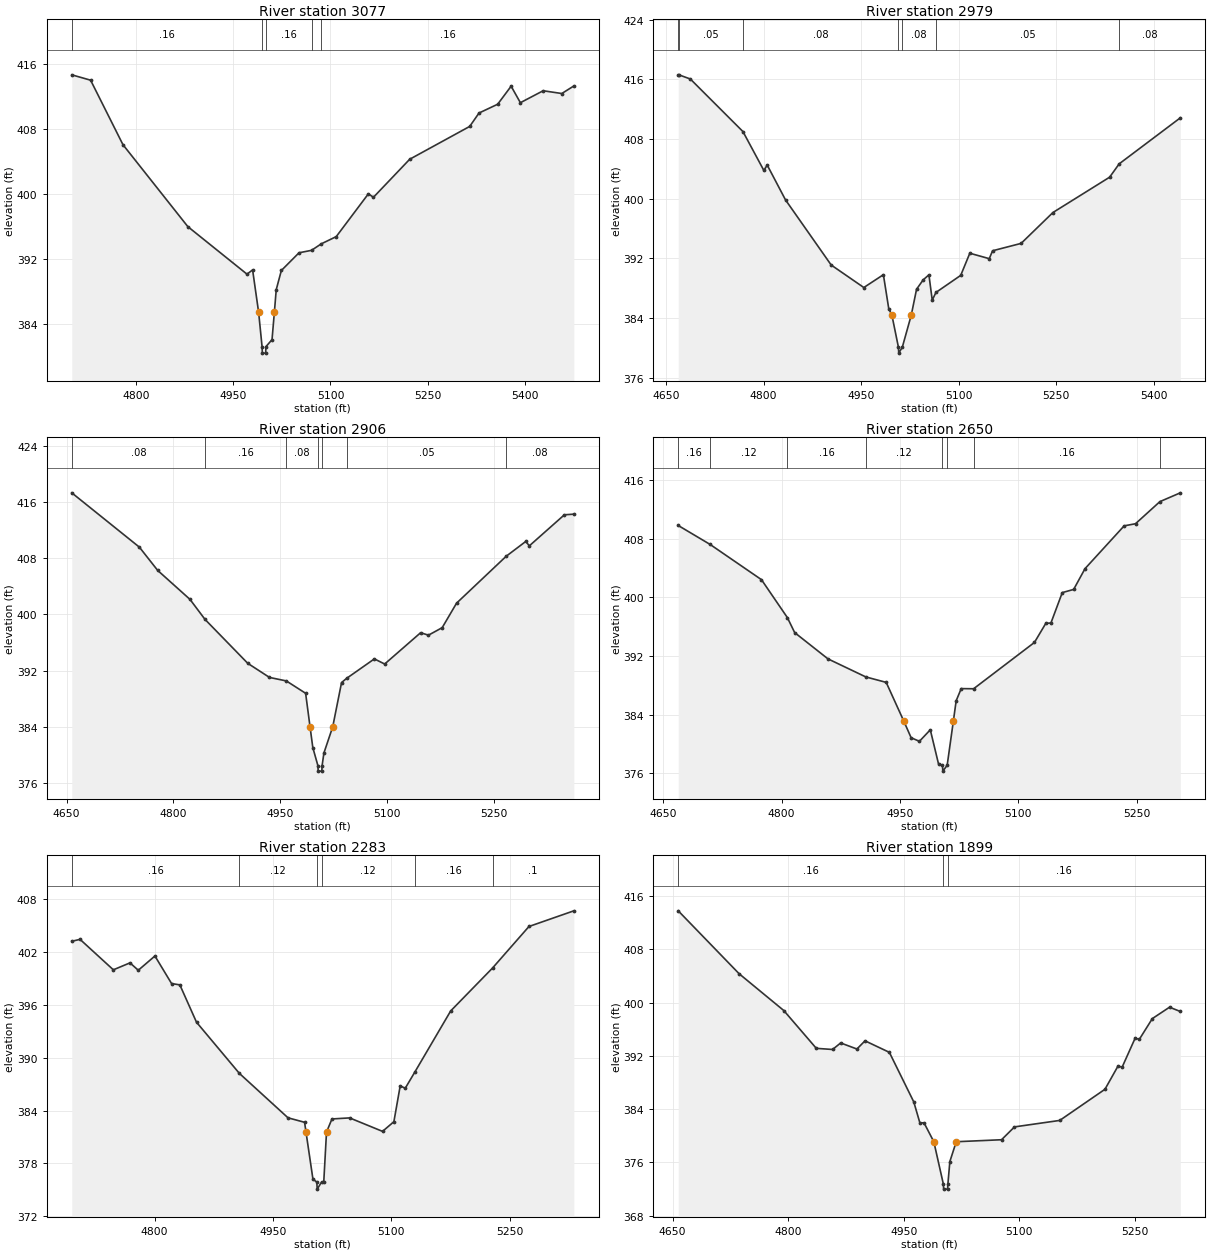
Type RM Length L Ch R = 1,3077,98,98,98
BEGIN DESCRIPTION:
UNT 060 IN DRY CR WATERSHED 6.0
END DESCRIPTION:
XS GIS Cut Line= 3
      2912577.44      7002585.94      2912591.53      7002885.31
      2912891.07      7003255.25
#Sta/Elev= 30
  4700.3  414.62  4729.4  413.96  4779.4  406.02  4879.6  395.94  4971.0  390.09
  4979.7  390.61  4989.0  385.39  4994.3  381.17  4994.8  380.37  4999.8  380.37
  5000.3  381.17  5009.7  382.03  5013.3  385.39  5016.2  388.18  5024.1  390.54
  5051.4  392.72  5070.7  393.02  5085.8  393.82  5108.9  394.71  5158.5  399.97
  5166.4  399.55  5222.4  404.23  5315.1  408.27  5329.5  409.92  5358.3  411.00
  5379.1  413.22  5393.4  411.19  5428.6  412.66  5457.4  412.32  5476.0  413.25
#Mann=5,-1,0
  4700.3    0.16       0  4994.3    0.07       0  5000.3    0.16       0
  5070.7    0.12       0  5085.8    0.16       0
Bank Sta=4989,5013.3
Exp/Cntr=0.3,0.1

Type RM Length L Ch R = 1,2979,73,73,73
BEGIN DESCRIPTION:
Mapping XS ff8ae6ad
END DESCRIPTION:
XS GIS Cut Line= 3
      2912488.46      7002620.65      2912516.67      7002946.20
      2912611.90      7003381.23
#Sta/Elev= 30
  4668.7  416.62  4669.7  416.62  4687.3  416.06  4768.2  409.01  4800.4  403.79
  4805.5  404.52  4833.7  399.84  4903.9  391.11  4954.1  388.09  4984.2  389.81
  4992.4  385.27  4997.3  384.37  5007.3  380.09  5007.8  379.29  5013.3  380.09
  5027.0  384.37  5035.2  387.86  5045.4  389.12  5054.2  389.79  5059.3  386.40
  5065.0  387.43  5103.1  389.72  5117.1  392.69  5147.0  391.96  5152.1  393.02
  5196.0  394.01  5244.9  398.15  5332.1  402.89  5346.8  404.68  5440.8  410.85
#Mann=7,-1,0
  4668.7    0.16       0  4669.7    0.05       0  4768.2    0.08       0
  5007.3    0.07       0  5013.3    0.08       0  5065.0    0.05       0
  5346.8    0.08       0
Bank Sta=4997.3,5027
Exp/Cntr=0.3,0.1

Type RM Length L Ch R = 1,2906,256,256,256
BEGIN DESCRIPTION:
Mapping XS 5f1c43a7
END DESCRIPTION:
XS GIS Cut Line= 3
      2912388.64      7002631.54      2912445.06      7002946.20
      2912499.32      7003328.18
#Sta/Elev= 30
  4657.2  417.32  4752.2  409.58  4777.9  406.27  4823.3  402.14  4844.4  399.29
  4904.5  393.03  4935.0  391.02  4958.7  390.52  4985.8  388.76  4992.0  383.99
  4995.9  381.03  5003.0  378.47  5003.5  377.67  5008.5  377.67  5009.0  378.47
  5011.5  380.25  5023.9  383.99  5036.3  390.29  5043.6  390.90  5082.4  393.66
  5096.9  392.93  5147.4  397.39  5158.4  397.04  5177.7  398.11  5197.9  401.60
  5267.6  408.28  5295.1  410.39  5300.2  409.77  5349.4  414.19  5362.7  414.28
#Mann=7,-1,0
  4657.2    0.08       0  4844.4    0.16       0  4958.7    0.08       0
  5003.0    0.07       0  5009.0    0.08       0  5043.6    0.05       0
  5267.6    0.08       0
Bank Sta=4992,5023.9
Exp/Cntr=0.3,0.1

Type RM Length L Ch R = 1,2650,367,367,367
BEGIN DESCRIPTION:
UNT 060 IN DRY CR WATERSHED 5.0
END DESCRIPTION:
XS GIS Cut Line= 3
      2912325.01      7002774.96      2912225.00      7003075.00
      2912424.98      7003324.98
#Sta/Elev= 30
  4669.1  409.78  4709.5  407.20  4774.6  402.40  4807.4  397.24  4816.7  395.19
  4858.9  391.61  4906.9  389.15  4932.7  388.41  4955.1  383.11  4964.3  380.87
  4974.8  380.38  4988.6  381.95  4999.0  377.31  5004.0  377.12  5004.5  376.32
  5010.0  377.12  5017.8  383.11  5021.4  385.91  5027.8  387.56  5043.5  387.54
  5120.6  393.85  5135.0  396.45  5141.5  396.50  5155.9  400.64  5170.3  401.07
  5184.7  403.90  5234.3  409.73  5248.7  410.02  5279.6  413.03  5305.5  414.23
#Mann=8,-1,0
  4669.1    0.16       0  4709.5    0.12       0  4807.4    0.16       0
  4906.9    0.12       0  5004.0    0.07       0  5010.0    0.12       0
  5043.5    0.16       0  5279.6    0.05       0
Bank Sta=4955.1,5017.8
Exp/Cntr=0.3,0.1

Type RM Length L Ch R = 1,2283,384,384,384
BEGIN DESCRIPTION:
UNT 060 IN DRY CR WATERSHED 4.0
END DESCRIPTION:
XS GIS Cut Line= 3
      2911825.00      7002925.01      2911925.00      7003225.00
      2912125.02      7003475.02
#Sta/Elev= 30
  4694.9  403.23  4705.4  403.45  4747.6  399.99  4768.7  400.78  4779.2  399.94
  4800.3  401.56  4821.4  398.43  4831.9  398.28  4853.0  394.04  4907.3  388.23
  4969.0  383.18  4990.0  382.67  4991.8  381.56  5000.6  376.21  5005.5  375.88
  5006.0  375.08  5011.5  375.88  5014.3  375.88  5017.8  381.56  5024.7  383.05
  5047.1  383.17  5088.8  381.64  5103.2  382.74  5111.2  386.81  5117.6  386.54
  5129.5  388.34  5175.2  395.32  5228.2  400.19  5274.4  404.91  5331.3  406.69
#Mann=6,-1,0
  4694.9    0.16       0  4907.3    0.12       0  5005.5    0.07       0
  5011.5    0.12       0  5129.5    0.16       0  5228.2     0.1       0
Bank Sta=4991.8,5017.8
Exp/Cntr=0.3,0.1

Type RM Length L Ch R = 1,1899,332,332,332
BEGIN DESCRIPTION:
UNT 060 IN DRY CR WATERSHED 3.0
END DESCRIPTION:
XS GIS Cut Line= 3
      2911475.01      7002925.02      2911575.00      7003225.00
      2911724.99      7003524.98
#Sta/Elev= 30
  4657.4  413.79  4736.4  404.34  4794.4  398.81  4836.6  393.13  4857.7  392.96
  4868.2  393.94  4889.3  393.03  4899.8  394.26  4931.4  392.53  4963.1  385.08
  4971.0  381.94  4976.4  381.94  4989.1  379.10  5001.4  372.78  5001.9  371.98
  5006.9  371.98  5007.4  372.78  5009.9  376.12  5018.2  379.10  5077.0  379.40
  5093.8  381.33  5152.5  382.30  5211.2  386.98  5228.0  390.44  5233.6  390.33
  5250.3  394.64  5255.9  394.50  5272.7  397.60  5295.0  399.31  5309.0  398.67
#Mann=3,-1,0
  4657.4    0.16       0  5001.4    0.07       0  5007.4    0.16       0
Bank Sta=4989.1,5018.2
Exp/Cntr=0.3,0.1

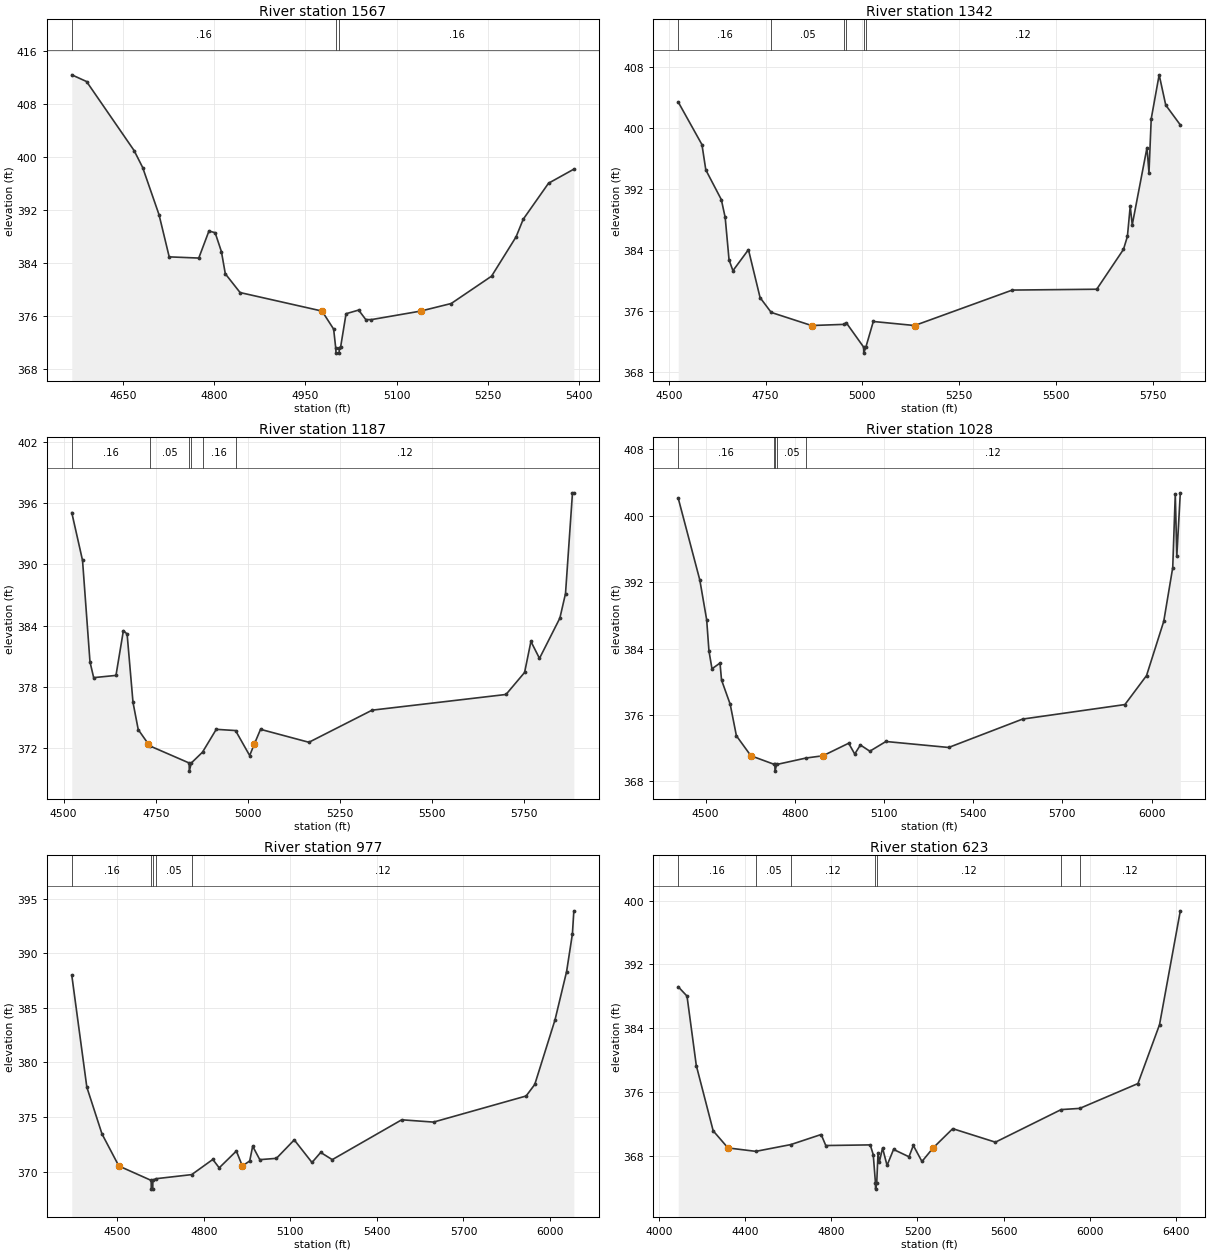
Type RM Length L Ch R = 1,1567,225,225,225
BEGIN DESCRIPTION:
UNT 060 IN DRY CR WATERSHED 2.0
END DESCRIPTION:
XS GIS Cut Line= 3
      2911225.00      7002974.99      2911325.00      7003425.00
      2911675.01      7003525.00
#Sta/Elev= 30
  4566.0  412.37  4590.3  411.36  4668.4  400.96  4682.5  398.40  4709.4  391.28
  4726.1  384.93  4774.7  384.75  4791.4  388.83  4801.6  388.57  4811.9  385.72
  4818.3  382.38  4842.6  379.55  4977.2  376.76  4996.3  374.04  4999.7  371.22
  5000.2  370.42  5005.2  370.42  5005.7  371.22  5007.8  371.35  5016.7  376.36
  5037.4  376.91  5049.1  375.48  5058.2  375.47  5139.4  376.76  5189.5  377.90
  5255.8  382.02  5296.1  387.95  5307.8  390.60  5349.4  396.03  5391.0  398.15
#Mann=3,-1,0
  4566.0    0.16       0  4999.7    0.07       0  5005.7    0.16       0
Bank Sta=4977.2,5139.4
Exp/Cntr=0.3,0.1

Type RM Length L Ch R = 1,1342,155,155,155
BEGIN DESCRIPTION:
Mapping XS e3036ed5
END DESCRIPTION:
XS GIS Cut Line= 3
      2911120.91      7003043.84      2911138.27      7003529.97
      2911928.24      7003707.93
#Sta/Elev= 30
  4524.6  403.44  4585.8  397.86  4595.8  394.54  4635.8  390.65  4645.8  388.31
  4655.8  382.74  4665.8  381.32  4705.9  384.08  4735.9  377.79  4764.6  375.85
  4868.8  374.13  4951.8  374.28  4959.0  374.45  5003.1  371.31  5003.6  370.51
  5009.1  371.31  5028.2  374.66  5134.9  374.13  5387.0  378.78  5605.0  378.89
  5674.0  384.11  5684.2  385.81  5691.5  389.79  5696.7  387.34  5734.8  397.46
  5739.9  394.16  5745.7  401.24  5766.2  407.01  5783.2  403.04  5820.8  400.44
#Mann=6,-1,0
  4524.6    0.16       0  4764.6    0.05       0  4951.8    0.16       0
  4959.0    0.12       0  5003.1    0.07       0  5009.1    0.12       0
Bank Sta=4868.8,5134.9
Exp/Cntr=0.3,0.1

Type RM Length L Ch R = 1,1187,159,159,159
BEGIN DESCRIPTION:
Mapping XS 71b3d77d
END DESCRIPTION:
XS GIS Cut Line= 3
      2911060.20      7003116.01      2911001.17      7003600.41
      2911867.44      7003714.99
#Sta/Elev= 30
  4522.3  395.09  4551.5  390.40  4571.7  380.45  4581.7  378.90  4642.2  379.12
  4662.3  383.51  4672.4  383.18  4688.4  376.47  4702.6  373.80  4730.4  372.37
  4735.5  372.18  4840.6  370.53  4841.1  369.73  4846.6  370.53  4876.9  371.59
  4914.2  373.83  4966.5  373.71  5004.8  371.26  5017.3  372.37  5034.3  373.83
  5165.5  372.56  5336.9  375.71  5700.1  377.25  5750.5  379.41  5767.7  382.45
  5790.9  380.79  5846.2  384.74  5861.5  387.15  5880.4  397.03  5884.1  397.03
#Mann=6,-1,0
  4522.3    0.16       0  4735.5    0.05       0  4840.6    0.07       0
  4846.6    0.05       0  4876.9    0.16       0  4966.5    0.12       0
Bank Sta=4730.4,5017.3
Exp/Cntr=0.3,0.1

Type RM Length L Ch R = 1,1028,51,51,51
BEGIN DESCRIPTION:
Mapping XS 2854de29
END DESCRIPTION:
XS GIS Cut Line= 3
      2910968.99      7003043.90      2910843.13      7003647.16
      2911910.42      7003751.28
#Sta/Elev= 30
  4408.2  402.12  4480.8  392.26  4503.8  387.48  4511.5  383.73  4521.7  381.57
  4548.7  382.26  4553.8  380.22  4583.0  377.29  4603.8  373.50  4652.6  371.09
  4730.0  370.07  4733.2  370.04  4733.7  369.24  4739.2  370.04  4838.2  370.82
  4894.9  371.09  4981.4  372.60  5001.8  371.30  5020.8  372.39  5052.6  371.64
  5106.7  372.81  5317.7  372.09  5566.3  375.51  5910.5  377.26  5983.2  380.75
  6041.1  387.29  6071.3  393.76  6079.9  402.65  6085.0  395.14  6096.8  402.77
#Mann=5,-1,0
  4408.2    0.16       0  4730.0    0.05       0  4733.2    0.07       0
  4739.2    0.05       0  4838.2    0.12       0
Bank Sta=4652.6,4894.9
Exp/Cntr=0.3,0.1

Type RM Length L Ch R = 1,977,354,354,354
BEGIN DESCRIPTION:
Mapping XS a2447844
END DESCRIPTION:
XS GIS Cut Line= 4
      2910867.49      7003053.53      2910763.32      7003649.02
      2910975.12      7003701.11      2911890.00      7003767.07
#Sta/Elev= 30
  4342.7  388.00  4394.9  377.74  4447.5  373.45  4505.8  370.52  4617.8  369.20
  4618.3  368.40  4623.3  368.40  4623.8  369.20  4633.2  369.35  4758.3  369.73
  4831.5  371.12  4853.6  370.35  4913.1  371.89  4933.8  370.52  4959.3  370.98
  4969.6  372.33  4994.3  371.10  5051.9  371.22  5113.7  372.91  5175.2  370.84
  5205.3  371.76  5245.4  371.10  5486.1  374.75  5596.3  374.54  5917.2  376.93
  5947.2  377.99  6017.4  383.91  6057.5  388.33  6077.6  391.77  6082.6  393.89
#Mann=5,-1,0
  4342.7    0.16       0  4617.8    0.07       0  4623.8    0.16       0
  4633.2    0.05       0  4758.3    0.12       0
Bank Sta=4505.8,4933.8
Exp/Cntr=0.3,0.1

Type RM Length L Ch R = 1,623,417,417,417
BEGIN DESCRIPTION:
Mapping XS 1220cc9e
END DESCRIPTION:
XS GIS Cut Line= 4
      2910838.79      7002957.08      2910526.29      7003751.33
      2910613.10      7003881.53      2911931.25      7003773.13
#Sta/Elev= 30
  4088.6  389.21  4129.4  388.04  4172.5  379.35  4251.0  371.17  4319.7  369.03
  4449.2  368.60  4611.8  369.45  4752.6  370.71  4774.1  369.33  4980.7  369.41
  4994.6  368.18  5004.8  364.67  5005.3  363.87  5010.8  364.67  5016.8  368.40
  5022.8  367.25  5037.8  369.02  5058.8  366.84  5088.9  368.84  5160.7  367.92
  5180.8  369.34  5220.9  367.33  5272.7  369.03  5363.9  371.44  5562.1  369.75
  5867.6  373.83  5954.0  373.98  6224.3  377.09  6324.6  384.46  6421.2  398.72
#Mann=7,-1,0
  4088.6    0.16       0  4449.2    0.05       0  4611.8    0.12       0
  5004.8    0.07       0  5010.8    0.12       0  5867.6    0.16       0
  5954.0    0.12       0
Bank Sta=4319.7,5272.7
Exp/Cntr=0.3,0.1

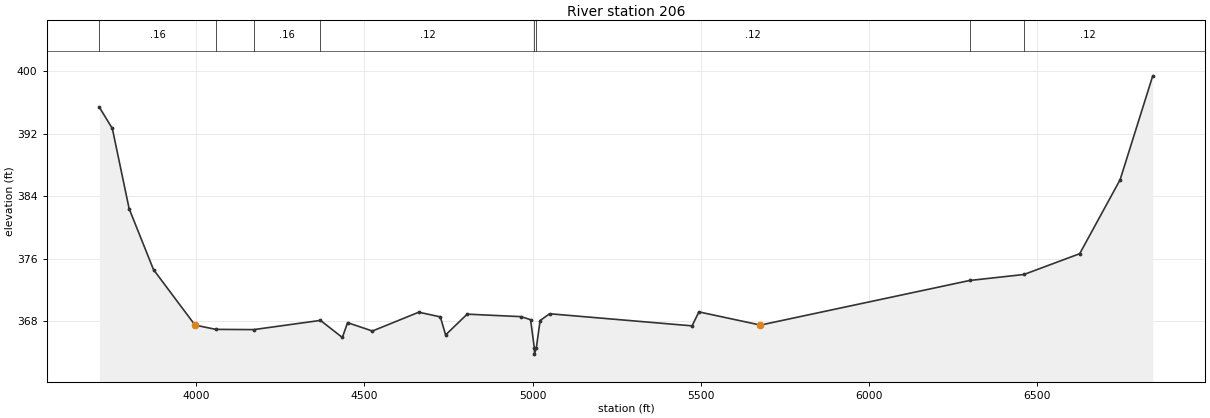
Type RM Length L Ch R = 1,206,0,0,0
BEGIN DESCRIPTION:
UNT 060 IN DRY CR WATERSHED 1.0
END DESCRIPTION:
XS GIS Cut Line= 4
      2910721.25      7002769.11      2910100.00      7003800.00
      2910250.00      7003950.00      2911961.72      7003855.00
#Sta/Elev= 30
  3712.8  395.40  3751.4  392.68  3801.4  382.40  3873.8  374.60  3997.1  367.50
  4058.9  366.95  4171.6  366.92  4369.9  368.10  4434.9  365.91  4450.4  367.81
  4524.2  366.74  4662.1  369.15  4726.1  368.55  4741.7  366.24  4805.8  368.90
  4965.9  368.58  4994.2  368.19  5005.3  364.58  5005.8  363.78  5011.3  364.58
  5022.5  368.08  5050.8  368.95  5474.1  367.40  5494.3  369.19  5677.2  367.50
  6298.7  373.21  6460.2  373.98  6625.8  376.64  6746.0  386.12  6842.9  399.42
#Mann=8,-1,0
  3712.8    0.16       0  4058.9    0.05       0  4171.6    0.16       0
  4369.9    0.12       0  5005.3    0.07       0  5011.3    0.12       0
  6298.7    0.16       0  6460.2    0.12       0
Bank Sta=3997.1,5677.2
Exp/Cntr=0.3,0.1

Chan Stop Cuts=-1