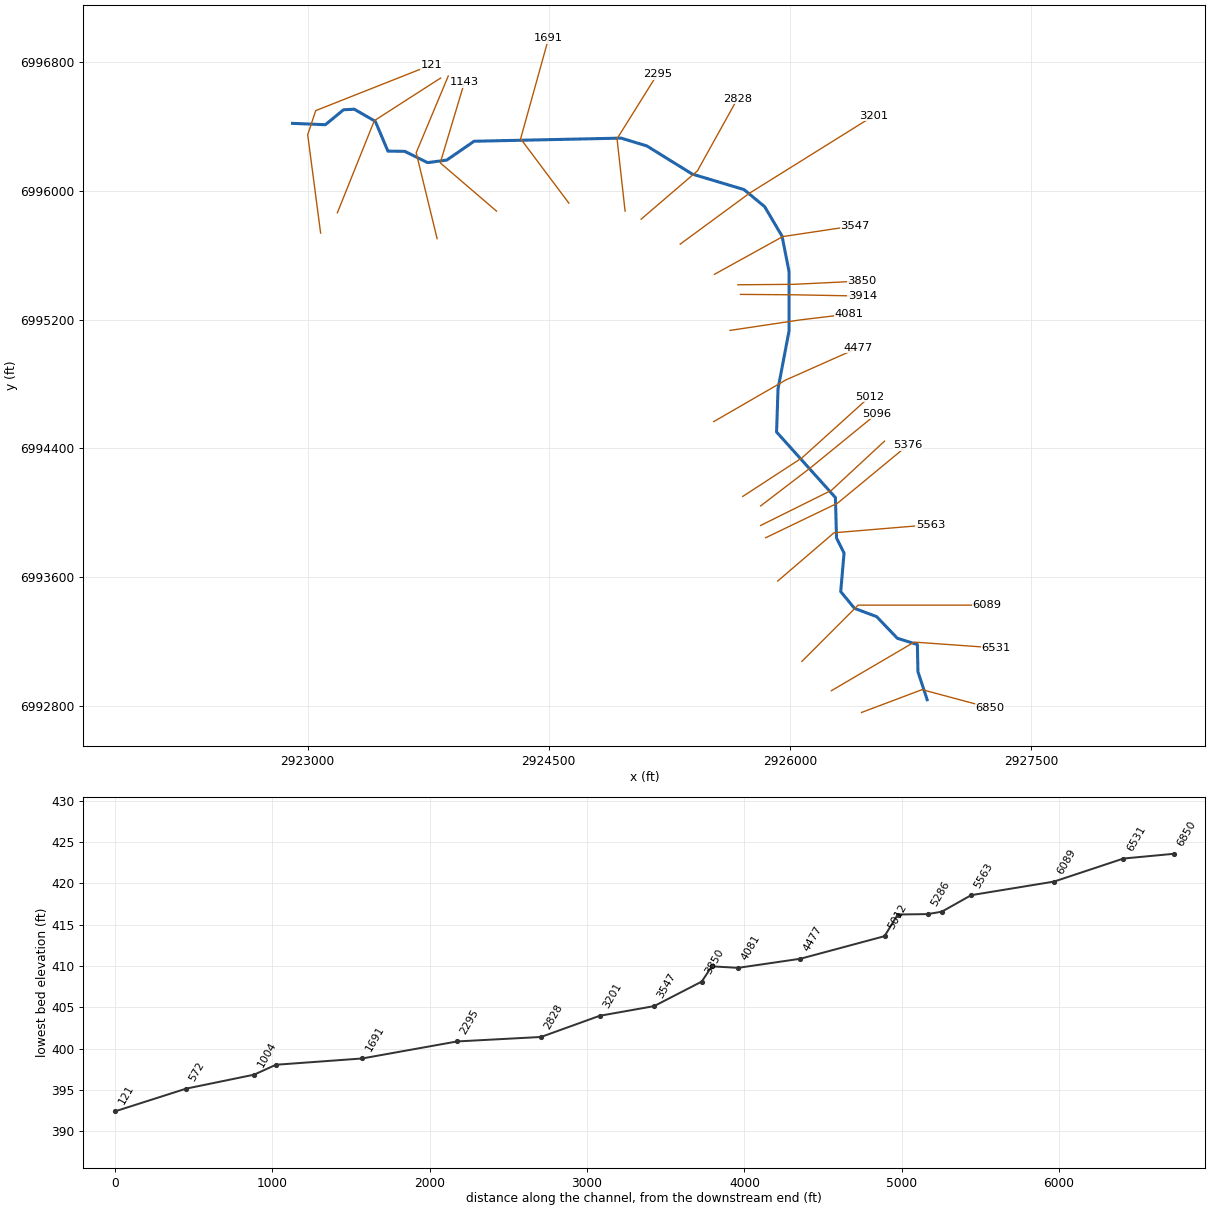
--- UNT 061 IN DRY CR WATERSHED.prj (project) ---

Proj Title=UNT 061 IN DRY CR WATERSHED Base Level Engineering
Current Plan=p01
Default Exp/Contr=0.3,0.1
English Units
Geom File=g01
Flow File=f01
Plan File=p01
BEGIN DESCRIPTION:
UNT 061 IN DRY CR WATERSHED
END DESCRIPTION:

--- UNT 061 IN DRY CR WATERSHED.p01 (plan) ---

Plan Title=Multiple Run
Short Identifier=Multiple
Geom File=g01
Flow File=f01
Subcritical Flow
K Sum by GR= 0
Std Step Tol= 0.01
Critical Tol= 0.01
Num of Std Step Trials= 20
Max Error Tol= 0.3
Flow Tol Ratio= 0.001
Split Flow NTrial= 30
Split Flow Tol= 0.02
Split Flow Ratio= 0.02
Log Output Level= 0
Friction Slope Method= 1
Unsteady Friction Slope Method= 2
Unsteady Bridges Friction Slope Method= 1
Parabolic Critical Depth
Global Vel Dist=  1 , 1 , 1
Global Log Level= 0
CheckData=True
Encroach Param= -1, 0, 0, 0
BEGIN DESCRIPTION:
Multiple Run
END DESCRIPTION:

--- UNT 061 IN DRY CR WATERSHED.f01 (steady flow) ---

Flow Title=Multiple
Number of Profiles=7
Profile Names=10-year,25-year,50-year,1pct_min,100-year,1pct_plu,500-year
River Rch & RM= UNT 061 IN DRY C,Reach-1,6850
     571     765     924     555    1107    2208    1590
River Rch & RM= UNT 061 IN DRY C,Reach-1,6089
     876    1199    1466     890    1776    3543    2610
Boundary for River Rch & Prof#=UNT 061 IN DRY C,Reach-1,1
Up Type=0
Dn Type=3
Dn Slope=0.005
Boundary for River Rch & Prof#=UNT 061 IN DRY C,Reach-1,2
Up Type=0
Dn Type=3
Dn Slope=0.005
Boundary for River Rch & Prof#=UNT 061 IN DRY C,Reach-1,3
Up Type=0
Dn Type=3
Dn Slope=0.005
Boundary for River Rch & Prof#=UNT 061 IN DRY C,Reach-1,4
Up Type=0
Dn Type=3
Dn Slope=0.005
Boundary for River Rch & Prof#=UNT 061 IN DRY C,Reach-1,5
Up Type=0
Dn Type=3
Dn Slope=0.005
Boundary for River Rch & Prof#=UNT 061 IN DRY C,Reach-1,6
Up Type=0
Dn Type=3
Dn Slope=0.005
Boundary for River Rch & Prof#=UNT 061 IN DRY C,Reach-1,7
Up Type=0
Dn Type=3
Dn Slope=0.005

--- UNT 061 IN DRY CR WATERSHED.g01 (geometry) ---

Geom Title=Existing Conditions

River Reach=UNT 061 IN DRY C,Reach-1
Reach XY= 30
      2926854.67      6992837.03      2926797.24      6993011.40
      2926793.86      6993180.15      2926669.07      6993218.94
      2926540.41      6993353.51      2926402.72      6993405.02
      2926316.78      6993509.19      2926337.62      6993748.77
      2926290.74      6993842.52      2926283.71      6994094.14
      2925917.63      6994501.63      2925926.69      6994770.25
      2925995.29      6995130.59      2925995.16      6995500.77
      2925951.76      6995719.12      2925843.40      6995902.97
      2925714.91      6996009.07      2925392.81      6996105.39
      2925110.45      6996280.38      2924950.03      6996328.89
      2924035.42      6996309.52      2923865.00      6996192.21
      2923745.52      6996176.56      2923604.26      6996246.64
      2923499.19      6996248.15      2923420.68      6996433.31
      2923289.83      6996508.65      2923223.07      6996505.31
      2923110.12      6996412.29      2922905.59      6996420.71

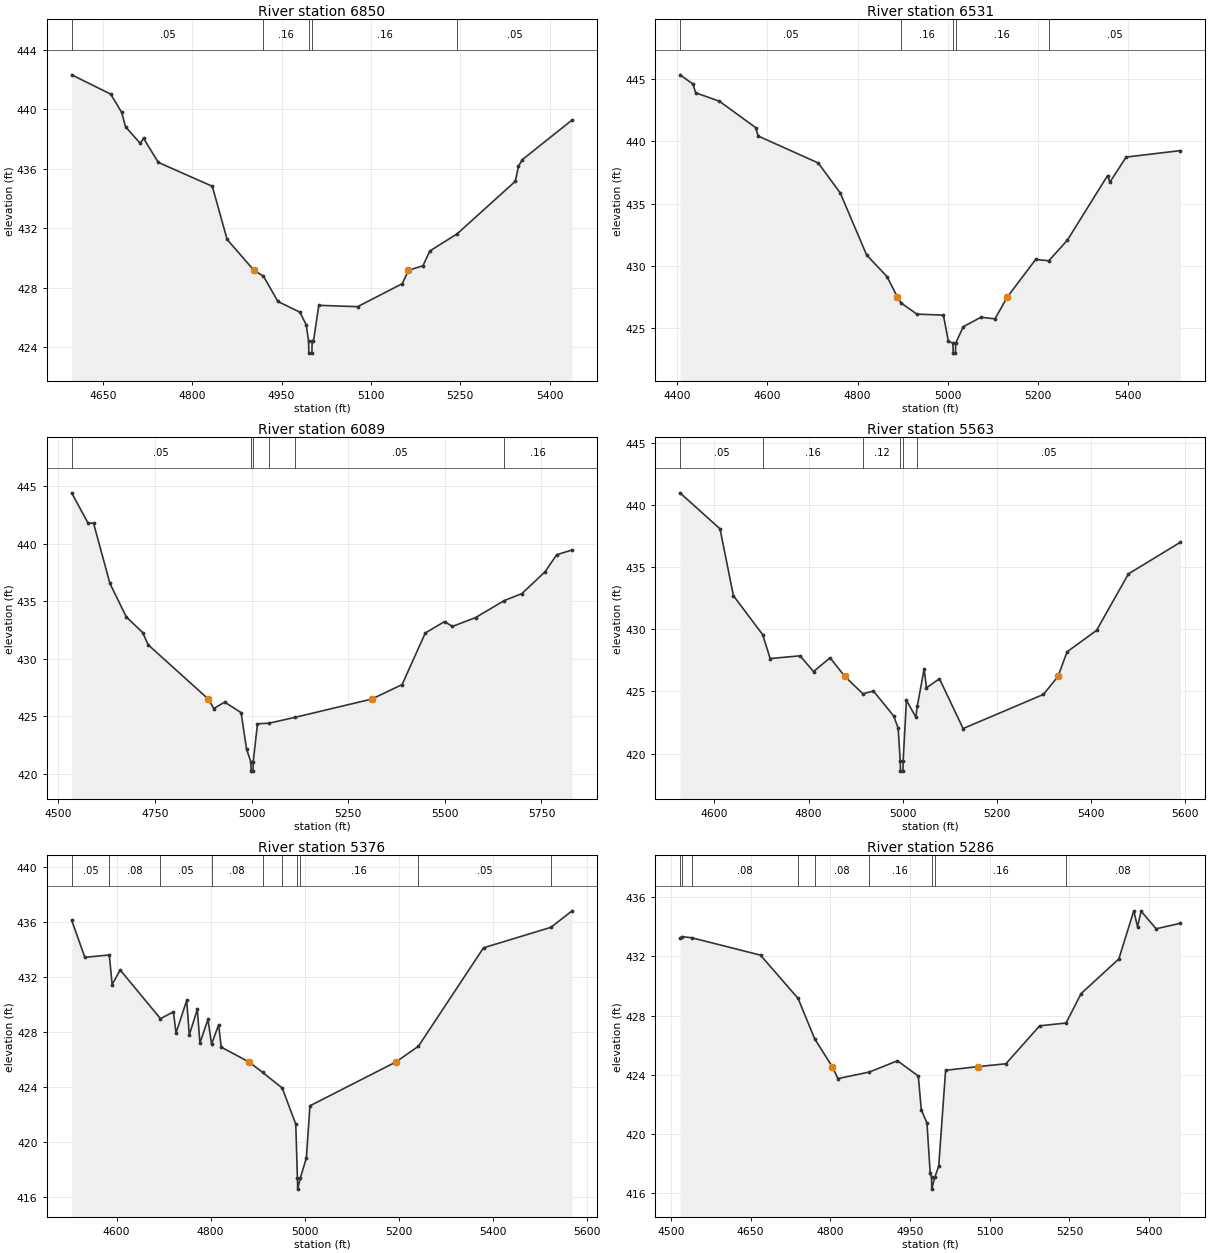
Type RM Length L Ch R = 1,6850,319,319,319
BEGIN DESCRIPTION:
UNT 061 IN DRY CR WATERSHED 12.0
END DESCRIPTION:
XS GIS Cut Line= 3
      2926446.49      6992757.75      2926822.96      6992899.58
      2927245.88      6992786.40
#Sta/Elev= 30
  4597.7  442.33  4663.2  441.03  4681.6  439.80  4688.1  438.83  4712.9  437.71
  4718.3  438.06  4743.1  436.43  4833.8  434.82  4858.6  431.24  4903.7  429.16
  4919.7  428.76  4943.9  427.06  4980.8  426.34  4991.5  425.48  4995.4  424.38
  4995.9  423.58  5000.9  423.58  5001.4  424.38  5003.6  424.38  5012.5  426.80
  5077.7  426.71  5152.7  428.26  5163.1  429.16  5187.5  429.47  5198.8  430.46
  5244.6  431.61  5342.5  435.16  5347.7  436.17  5354.1  436.61  5437.8  439.29
#Mann=5,-1,0
  4597.7    0.05       0  4919.7    0.16       0  4995.4    0.07       0
  5001.4    0.16       0  5244.6    0.05       0
Bank Sta=4903.7,5163.1
Exp/Cntr=0.3,0.1

Type RM Length L Ch R = 1,6531,442,442,442
BEGIN DESCRIPTION:
Mapping XS 1874d53a
END DESCRIPTION:
XS GIS Cut Line= 3
      2926258.94      6992893.15      2926774.57      6993195.24
      2927284.97      6993158.78
#Sta/Elev= 30
  4406.3  445.34  4435.2  444.60  4441.0  443.90  4493.8  443.22  4573.9  441.11
  4579.7  440.43  4712.7  438.27  4761.5  435.87  4820.1  430.88  4865.3  429.15
  4888.1  427.53  4896.2  427.04  4931.6  426.14  4990.3  426.06  5001.3  423.96
  5011.4  423.81  5011.9  423.01  5016.9  423.01  5017.4  423.81  5034.4  425.13
  5073.5  425.89  5104.6  425.76  5132.3  427.53  5194.8  430.53  5223.9  430.42
  5265.0  432.07  5354.2  437.26  5359.2  436.72  5395.3  438.74  5515.6  439.26
#Mann=5,-1,0
  4406.3    0.05       0  4896.2    0.16       0  5011.4    0.07       0
  5017.4    0.16       0  5223.9    0.05       0
Bank Sta=4888.1,5132.3
Exp/Cntr=0.3,0.1

Type RM Length L Ch R = 1,6089,526,526,526
BEGIN DESCRIPTION:
UNT 061 IN DRY CR WATERSHED 11.0
END DESCRIPTION:
XS GIS Cut Line= 3
      2926074.99      6993074.99      2926425.00      6993425.00
      2927225.02      6993425.00
#Sta/Elev= 30
  4534.4  444.44  4576.8  441.80  4591.0  441.80  4633.4  436.55  4675.8  433.64
  4718.3  432.27  4732.4  431.21  4888.1  426.49  4902.1  425.67  4930.4  426.23
  4972.8  425.31  4987.0  422.12  4998.1  421.02  4998.6  420.22  5003.6  420.22
  5004.1  421.02  5015.2  424.34  5044.7  424.39  5112.1  424.90  5310.7  426.49
  5389.4  427.75  5449.4  432.24  5499.4  433.24  5519.4  432.81  5579.4  433.58
  5653.6  435.06  5699.4  435.67  5759.4  437.57  5789.4  439.05  5829.4  439.47
#Mann=6,-1,0
  4534.4    0.05       0  4998.1    0.03       0  5004.1    0.05       0
  5044.7    0.16       0  5112.1    0.05       0  5653.6    0.16       0
Bank Sta=4888.1,5310.7
Exp/Cntr=0.3,0.1

Type RM Length L Ch R = 1,5563,187,187,187
BEGIN DESCRIPTION:
UNT 061 IN DRY CR WATERSHED 10.0
END DESCRIPTION:
XS GIS Cut Line= 3
      2925924.98      6993574.98      2926275.00      6993875.00
      2926875.02      6993925.00
#Sta/Elev= 30
  4526.8  441.00  4611.9  438.10  4640.4  432.71  4702.6  429.57  4718.4  427.65
  4782.0  427.87  4810.5  426.60  4845.7  427.71  4877.0  426.21  4915.5  424.81
  4937.9  425.03  4980.7  423.03  4990.3  422.05  4994.8  419.38  4995.3  418.58
  5000.4  418.58  5000.9  419.38  5007.9  424.29  5027.9  422.93  5030.9  423.80
  5045.5  426.81  5050.5  425.30  5078.1  426.02  5128.3  422.01  5298.9  424.76
  5329.9  426.21  5349.1  428.19  5411.8  429.92  5479.5  434.47  5589.9  437.02
#Mann=6,-1,0
  4526.8    0.05       0  4702.6    0.16       0  4915.5    0.12       0
  4994.8    0.07       0  5000.9    0.12       0  5030.9    0.05       0
Bank Sta=4877,5329.9
Exp/Cntr=0.3,0.1

Type RM Length L Ch R = 1,5376,90,90,90
BEGIN DESCRIPTION:
Mapping XS 5fa638ce
END DESCRIPTION:
XS GIS Cut Line= 3
      2925849.73      6993844.07      2926297.66      6994059.36
      2926734.88      6994420.24
#Sta/Elev= 30
  4504.5  436.13  4532.5  433.44  4584.5  433.61  4590.5  431.46  4607.6  432.52
  4693.2  428.98  4720.8  429.47  4726.3  427.94  4749.0  430.30  4754.5  427.79
  4771.6  429.65  4777.1  427.21  4794.2  428.92  4801.9  427.13  4816.9  428.53
  4822.4  426.91  4881.9  425.82  4910.5  425.07  4952.1  423.93  4980.9  421.31
  4984.4  417.38  4984.9  416.58  4990.5  417.38  5003.5  418.86  5011.0  422.64
  5193.4  425.82  5241.6  426.97  5380.0  434.13  5523.4  435.62  5568.4  436.82
#Mann=10,-1,0
  4504.5    0.05       0  4584.5    0.08       0  4693.2    0.05       0
  4801.9    0.08       0  4910.5    0.12       0  4952.1    0.16       0
  4984.4    0.07       0  4990.5    0.16       0  5241.6    0.05       0
  5523.4    0.08       0
Bank Sta=4881.9,5193.4
Exp/Cntr=0.3,0.1

Type RM Length L Ch R = 1,5286,190,190,190
BEGIN DESCRIPTION:
Mapping XS 27152c34
END DESCRIPTION:
XS GIS Cut Line= 3
      2925818.49      6993920.47      2926259.47      6994139.22
      2926589.34      6994444.78
#Sta/Elev= 30
  4517.0  433.21  4520.7  433.33  4539.5  433.25  4668.6  432.08  4739.3  429.16
  4770.5  426.44  4803.5  424.56  4814.5  423.75  4873.2  424.19  4926.4  424.95
  4965.6  423.92  4971.2  421.65  4981.9  420.75  4988.0  417.37  4990.5  417.09
  4991.0  416.29  4996.6  417.09  5004.0  417.84  5017.0  424.31  5078.7  424.56
  5130.4  424.75  5194.0  427.31  5243.7  427.50  5272.1  429.49  5343.0  431.82
  5371.2  435.07  5378.2  434.00  5385.0  435.04  5413.3  433.86  5458.9  434.23
#Mann=9,-1,0
  4517.0    0.08       0  4520.7    0.05       0  4539.5    0.08       0
  4739.3    0.05       0  4770.5    0.08       0  4873.2    0.16       0
  4990.5    0.07       0  4996.6    0.16       0  5243.7    0.08       0
Bank Sta=4803.5,5078.7
Exp/Cntr=0.3,0.1

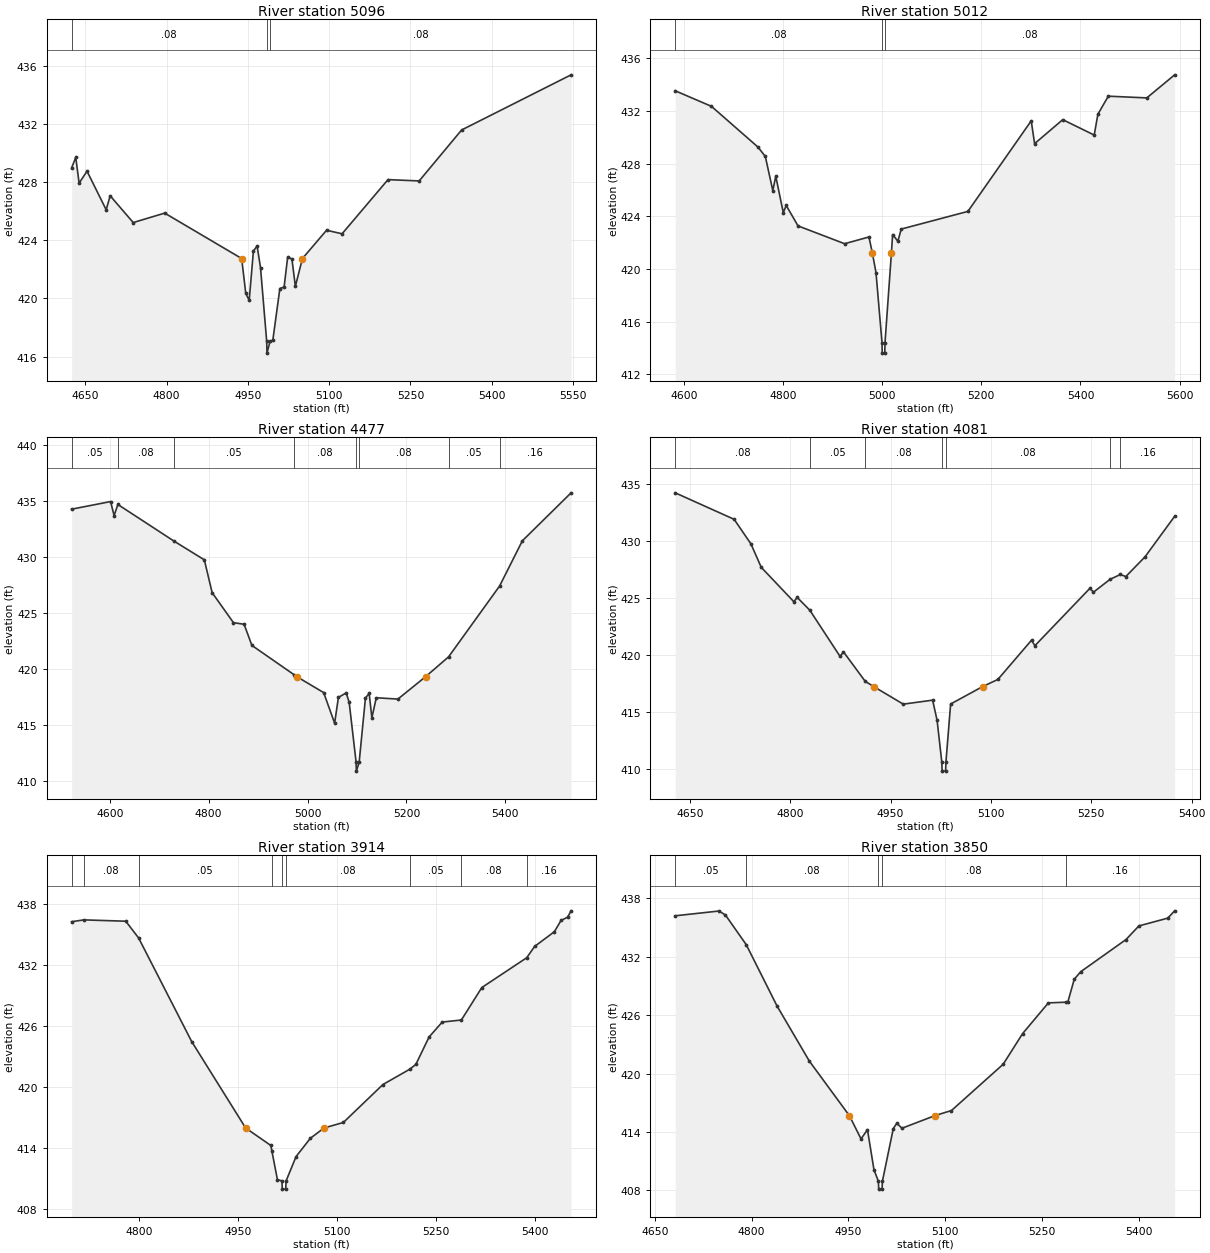
Type RM Length L Ch R = 1,5096,84,84,84
BEGIN DESCRIPTION:
Mapping XS c02a664f
END DESCRIPTION:
XS GIS Cut Line= 3
      2925818.48      6994041.99      2926127.52      6994278.11
      2926540.33      6994614.60
#Sta/Elev= 30
  4624.9  428.97  4632.5  429.69  4638.7  427.92  4653.3  428.74  4688.6  426.09
  4696.0  427.05  4738.5  425.21  4796.6  425.86  4938.6  422.74  4946.2  420.34
  4952.5  419.87  4960.3  423.26  4967.1  423.60  4973.4  422.11  4984.8  417.04
  4985.3  416.24  4990.9  417.04  4996.1  417.13  5009.1  420.68  5016.9  420.78
  5023.5  422.84  5031.3  422.71  5037.7  420.83  5050.7  422.74  5095.2  424.68
  5123.9  424.44  5208.6  428.16  5266.1  428.07  5344.4  431.57  5546.4  435.36
#Mann=3,-1,0
  4624.9    0.08       0  4984.8    0.07       0  4990.9    0.08       0
Bank Sta=4938.6,5050.7
Exp/Cntr=0.3,0.1

Type RM Length L Ch R = 1,5012,535,535,535
BEGIN DESCRIPTION:
Mapping XS 745057d3
END DESCRIPTION:
XS GIS Cut Line= 3
      2925707.36      6994101.01      2926075.44      6994340.61
      2926497.66      6994721.30
#Sta/Elev= 30
  4582.4  433.52  4655.5  432.34  4749.1  429.26  4764.2  428.54  4779.3  425.95
  4785.3  427.04  4800.4  424.28  4806.4  424.82  4830.2  423.27  4924.2  421.92
  4973.3  422.43  4980.0  421.25  4987.5  419.73  4999.6  414.42  5000.1  413.62
  5005.2  413.62  5005.7  414.42  5018.7  421.25  5021.0  422.61  5031.7  422.11
  5038.4  423.03  5172.9  424.37  5300.7  431.24  5307.5  429.51  5364.3  431.33
  5427.8  430.16  5435.2  431.74  5456.2  433.11  5533.9  432.98  5590.1  434.73
#Mann=3,-1,0
  4582.4    0.08       0  4999.6    0.07       0  5005.7    0.08       0
Bank Sta=4980,5018.7
Exp/Cntr=0.3,0.1

Type RM Length L Ch R = 1,4477,396,396,396
BEGIN DESCRIPTION:
UNT 061 IN DRY CR WATERSHED 8.0
END DESCRIPTION:
XS GIS Cut Line= 3
      2925526.83      6994566.31      2925975.00      6994825.00
      2926424.99      6995024.99
#Sta/Elev= 30
  4523.0  434.27  4601.7  434.95  4608.9  433.70  4616.5  434.69  4729.3  431.44
  4791.3  429.75  4807.1  426.82  4850.2  424.14  4871.7  424.00  4887.5  422.11
  4972.3  419.51  4978.0  419.33  5032.6  417.90  5054.8  415.17  5062.4  417.47
  5078.1  417.87  5084.2  417.03  5098.2  411.69  5098.7  410.89  5104.4  411.69
  5117.1  417.42  5124.6  417.82  5130.1  415.65  5139.0  417.44  5182.7  417.32
  5239.0  419.33  5285.2  421.09  5388.3  427.41  5434.4  431.45  5532.9  435.73
#Mann=8,-1,0
  4523.0    0.05       0  4616.5    0.08       0  4729.3    0.05       0
  4972.3    0.08       0  5098.2    0.07       0  5104.4    0.08       0
  5285.2    0.05       0  5388.3    0.16       0
Bank Sta=4978,5239
Exp/Cntr=0.3,0.1

Type RM Length L Ch R = 1,4081,167,167,167
BEGIN DESCRIPTION:
Mapping XS 2dd9453a
END DESCRIPTION:
XS GIS Cut Line= 3
      2925627.86      6995133.27      2926062.71      6995198.36
      2926367.44      6995234.83
#Sta/Elev= 30
  4628.0  434.26  4716.1  431.93  4741.2  429.77  4756.6  427.71  4805.3  424.69
  4810.4  425.06  4829.2  423.94  4874.5  419.87  4879.5  420.28  4912.1  417.68
  4924.9  417.22  4968.9  415.68  5012.8  416.03  5019.5  414.25  5026.5  410.59
  5027.0  409.79  5032.2  409.79  5032.7  410.59  5039.7  415.69  5087.4  417.22
  5110.3  417.85  5160.6  421.30  5165.7  420.82  5248.0  425.87  5253.1  425.52
  5278.2  426.66  5293.5  427.08  5301.6  426.90  5330.4  428.64  5374.6  432.20
#Mann=7,-1,0
  4628.0    0.08       0  4829.2    0.05       0  4912.1    0.08       0
  5026.5    0.07       0  5032.7    0.08       0  5278.2    0.05       0
  5293.5    0.16       0
Bank Sta=4924.9,5087.4
Exp/Cntr=0.3,0.1

Type RM Length L Ch R = 1,3914,64,64,64
BEGIN DESCRIPTION:
Mapping XS 2d0f4a4c
END DESCRIPTION:
XS GIS Cut Line= 3
      2925692.91      6995357.22      2926036.67      6995354.61
      2926450.33      6995346.81
#Sta/Elev= 30
  4697.3  436.25  4715.8  436.43  4779.4  436.30  4798.9  434.65  4879.4  424.47
  4961.2  415.98  4999.4  414.26  5001.0  413.72  5009.4  410.91  5016.3  410.77
  5016.8  409.97  5022.0  409.97  5022.5  410.77  5037.7  413.17  5059.4  414.97
  5080.2  415.98  5109.4  416.52  5169.4  420.25  5210.3  421.76  5219.4  422.23
  5239.4  424.92  5259.4  426.39  5288.4  426.59  5319.4  429.78  5387.5  432.71
  5399.5  433.82  5429.5  435.27  5439.5  436.37  5449.5  436.70  5454.8  437.32
#Mann=9,-1,0
  4697.3    0.05       0  4715.8    0.08       0  4798.9    0.05       0
  5001.0    0.08       0  5016.3    0.04       0  5022.5    0.08       0
  5210.3    0.05       0  5288.4    0.08       0  5387.5    0.16       0
Bank Sta=4961.2,5080.2
Exp/Cntr=0.3,0.1

Type RM Length L Ch R = 1,3850,303,303,303
BEGIN DESCRIPTION:
Mapping XS f36fb30b
END DESCRIPTION:
XS GIS Cut Line= 3
      2925677.25      6995417.11      2926021.04      6995419.72
      2926450.34      6995440.53
#Sta/Elev= 30
  4681.6  436.19  4749.4  436.68  4759.4  436.27  4791.6  433.23  4839.4  426.92
  4889.4  421.27  4951.3  415.68  4969.4  413.29  4979.4  414.23  4989.4  410.14
  4996.3  408.93  4996.8  408.13  5002.0  408.13  5002.5  408.93  5019.4  414.35
  5024.9  414.89  5032.8  414.38  5084.0  415.68  5109.5  416.20  5189.6  420.95
  5219.6  424.09  5259.6  427.25  5286.8  427.32  5289.7  427.33  5299.7  429.68
  5309.7  430.45  5379.8  433.75  5399.8  435.15  5444.5  435.95  5455.2  436.70
#Mann=5,-1,0
  4681.6    0.05       0  4791.6    0.08       0  4996.3    0.07       0
  5002.5    0.08       0  5286.8    0.16       0
Bank Sta=4951.3,5084
Exp/Cntr=0.3,0.1

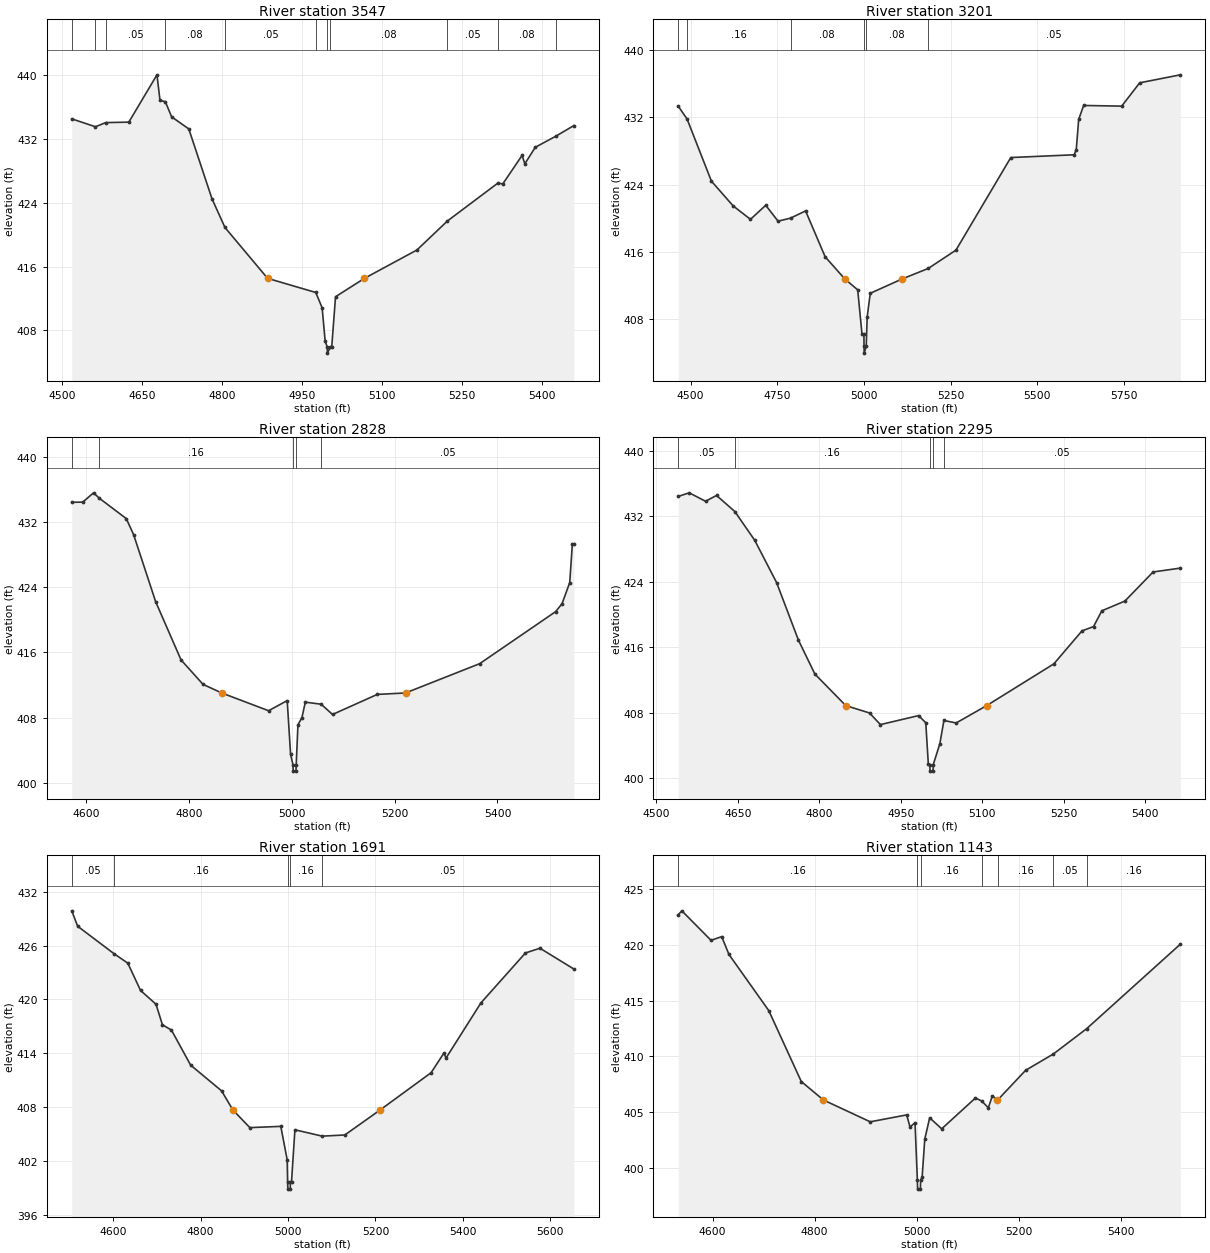
Type RM Length L Ch R = 1,3547,346,346,346
BEGIN DESCRIPTION:
Mapping XS 99775d34
END DESCRIPTION:
XS GIS Cut Line= 3
      2925531.45      6995482.21      2925955.94      6995716.59
      2926406.48      6995784.30
#Sta/Elev= 30
  4518.4  434.48  4562.8  433.49  4581.9  434.01  4625.3  434.07  4678.0  439.99
  4683.7  436.78  4693.6  436.63  4705.5  434.73  4737.6  433.22  4781.1  424.47
  4805.3  420.89  4885.2  414.52  4975.5  412.75  4987.4  410.83  4993.1  406.64
  4996.8  405.96  4997.3  405.16  5003.0  405.96  5005.4  405.96  5012.5  412.22
  5066.7  414.52  5165.0  418.07  5222.1  421.70  5316.2  426.42  5325.9  426.35
  5362.0  429.91  5367.1  428.85  5386.6  430.92  5425.2  432.31  5458.9  433.64
#Mann=11,-1,0
  4518.4    0.05       0  4562.8    0.16       0  4581.9    0.05       0
  4693.6    0.08       0  4805.3    0.05       0  4975.5    0.08       0
  4996.8    0.07       0  5003.0    0.08       0  5222.1    0.05       0
  5316.2    0.08       0  5425.2    0.16       0
Bank Sta=4885.2,5066.7
Exp/Cntr=0.3,0.1

Type RM Length L Ch R = 1,3201,373,373,373
BEGIN DESCRIPTION:
UNT 061 IN DRY CR WATERSHED 6.0
END DESCRIPTION:
XS GIS Cut Line= 3
      2925317.94      6995669.74      2925749.45      6995986.68
      2926523.69      6996469.22
#Sta/Elev= 30
  4464.6  433.34  4490.3  431.79  4560.2  424.43  4622.8  421.49  4672.9  419.89
  4716.9  421.56  4752.4  419.67  4788.4  420.03  4831.8  420.89  4888.2  415.44
  4945.0  412.80  4982.1  411.51  4994.4  406.27  5000.0  406.27  5000.3  404.79
  5000.8  403.99  5006.6  404.79  5009.4  408.29  5018.3  411.10  5109.9  412.80
  5185.4  414.05  5265.4  416.23  5423.5  427.23  5606.4  427.56  5612.3  428.18
  5619.3  431.77  5633.6  433.42  5743.3  433.34  5795.2  436.11  5912.3  437.06
#Mann=6,-1,0
  4464.6    0.05       0  4490.3    0.16       0  4788.4    0.08       0
  5000.3    0.07       0  5006.6    0.08       0  5185.4    0.05       0
Bank Sta=4945,5109.9
Exp/Cntr=0.3,0.1

Type RM Length L Ch R = 1,2828,533,533,533
BEGIN DESCRIPTION:
UNT 061 IN DRY CR WATERSHED 5.0
END DESCRIPTION:
XS GIS Cut Line= 3
      2925074.98      6995824.98      2925425.00      6996125.00
      2925675.01      6996575.02
#Sta/Elev= 30
  4572.6  434.41  4594.0  434.43  4614.9  435.57  4625.9  434.92  4678.5  432.41
  4692.8  430.44  4735.6  422.22  4785.0  415.07  4827.8  412.07  4864.0  411.02
  4955.1  408.84  4991.3  410.08  4997.9  403.48  5002.5  402.23  5003.0  401.43
  5008.3  401.43  5008.8  402.23  5012.2  407.12  5019.9  407.99  5026.5  409.89
  5057.3  409.64  5079.4  408.38  5166.3  410.84  5221.3  411.02  5365.3  414.61
  5512.9  420.99  5525.5  421.97  5540.4  424.56  5545.5  429.29  5548.4  429.29
#Mann=5,-1,0
  4572.6    0.05       0  4625.9    0.16       0  5002.5    0.07       0
  5008.8    0.16       0  5057.3    0.05       0
Bank Sta=4864,5221.3
Exp/Cntr=0.3,0.1

Type RM Length L Ch R = 1,2295,604,604,604
BEGIN DESCRIPTION:
UNT 061 IN DRY CR WATERSHED 4.0
END DESCRIPTION:
XS GIS Cut Line= 3
      2924975.00      6995874.97      2924925.00      6996325.00
      2925175.00      6996725.00
#Sta/Elev= 30
  4540.5  434.42  4560.7  434.86  4590.8  433.83  4611.0  434.54  4644.7  432.58
  4681.4  429.06  4721.6  423.91  4761.9  416.87  4792.1  412.74  4849.0  408.89
  4892.7  407.99  4912.8  406.57  4983.2  407.67  4996.3  406.79  5001.0  401.76
  5003.7  401.69  5004.2  400.89  5009.6  400.89  5010.1  401.69  5022.2  404.23
  5029.7  407.07  5052.3  406.77  5108.5  408.89  5232.1  413.98  5284.0  418.01
  5305.2  418.53  5320.5  420.46  5363.0  421.65  5414.9  425.20  5465.0  425.67
#Mann=5,-1,0
  4540.5    0.05       0  4644.7    0.16       0  5003.7    0.07       0
  5010.1    0.16       0  5029.7    0.05       0
Bank Sta=4849,5108.5
Exp/Cntr=0.3,0.1

Type RM Length L Ch R = 1,1691,548,548,548
BEGIN DESCRIPTION:
UNT 061 IN DRY CR WATERSHED 3.0
END DESCRIPTION:
XS GIS Cut Line= 3
      2924625.00      6995925.00      2924325.00      6996325.00
      2924498.82      6996949.67
#Sta/Elev= 30
  4505.3  429.87  4518.8  428.15  4603.0  425.05  4633.4  424.04  4662.6  420.99
  4698.0  419.45  4712.6  417.17  4733.4  416.56  4777.2  412.66  4848.0  409.79
  4873.8  407.66  4912.6  405.69  4983.4  405.83  4998.0  402.11  4999.0  399.63
  4999.5  398.83  5004.9  398.83  5005.4  399.63  5007.9  399.63  5015.7  405.45
  5078.0  404.74  5129.9  404.87  5210.6  407.66  5327.3  411.82  5356.3  413.99
  5361.5  413.46  5441.3  419.61  5543.0  425.17  5576.2  425.70  5653.7  423.38
#Mann=5,-1,0
  4505.3    0.05       0  4603.0    0.16       0  4999.0    0.07       0
  5005.4    0.16       0  5078.0    0.05       0
Bank Sta=4873.8,5210.6
Exp/Cntr=0.3,0.1

Type RM Length L Ch R = 1,1143,139,139,139
BEGIN DESCRIPTION:
UNT 061 IN DRY CR WATERSHED 2.0
END DESCRIPTION:
XS GIS Cut Line= 3
      2924175.00      6995875.00      2923825.00      6996175.00
      2923975.00      6996675.01
#Sta/Elev= 30
  4532.9  422.73  4540.0  423.08  4597.1  420.43  4618.0  420.76  4632.2  419.16
  4710.2  414.11  4773.8  407.74  4817.2  406.08  4908.8  404.12  4980.2  404.74
  4986.7  403.65  4996.5  404.04  5001.1  398.87  5001.6  398.07  5007.0  398.07
  5007.5  398.87  5010.4  399.13  5015.6  402.57  5025.2  404.48  5048.7  403.49
  5114.8  406.26  5127.3  405.98  5140.0  405.38  5147.9  406.45  5157.9  406.07
  5158.7  406.10  5213.1  408.75  5267.2  410.21  5332.3  412.48  5515.9  420.08
#Mann=7,-1,0
  4532.9    0.16       0  5001.1    0.07       0  5007.5    0.16       0
  5127.3    0.12       0  5158.7    0.16       0  5267.2    0.05       0
  5332.3    0.16       0
Bank Sta=4817.2,5157.9
Exp/Cntr=0.3,0.1

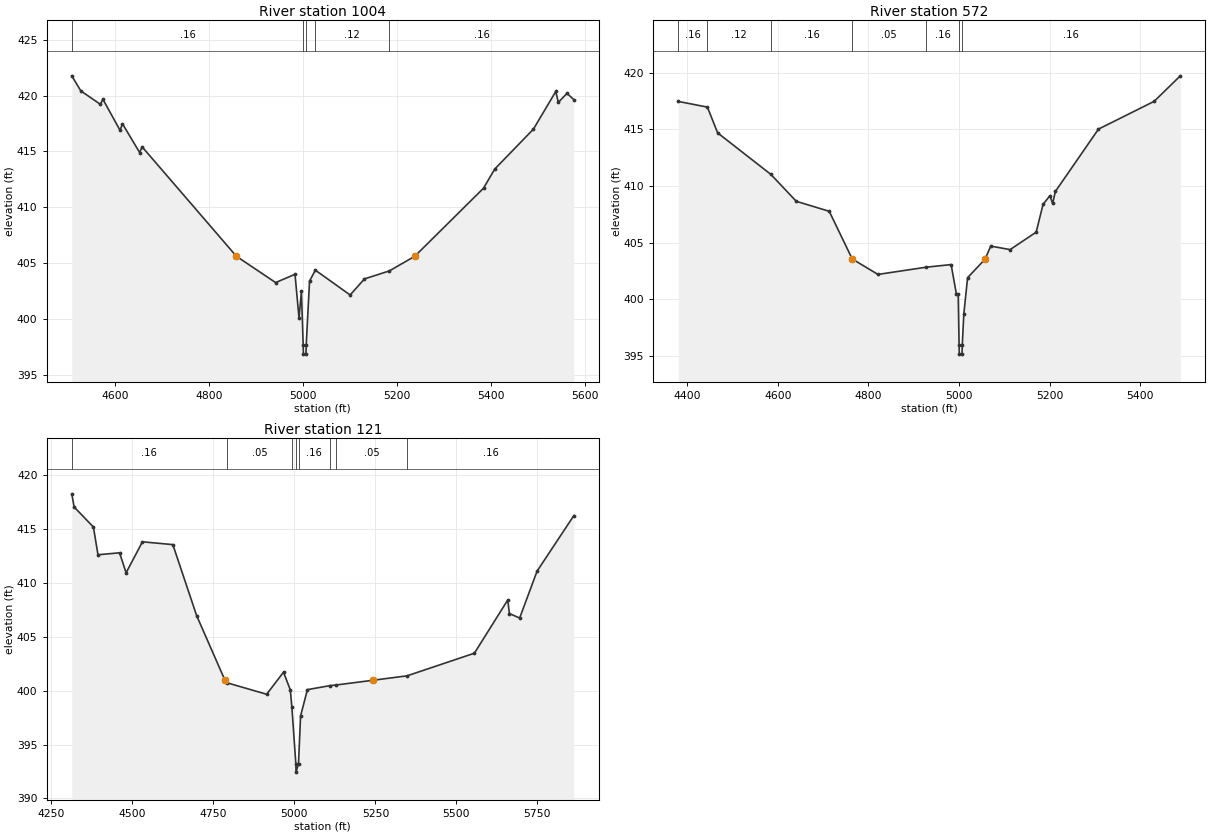
Type RM Length L Ch R = 1,1004,432,432,432
BEGIN DESCRIPTION:
Mapping XS a5b914c6
END DESCRIPTION:
XS GIS Cut Line= 3
      2923805.24      6995704.04      2923675.04      6996237.86
      2923874.70      6996715.32
#Sta/Elev= 30
  4508.6  421.76  4527.9  420.41  4569.6  419.21  4574.7  419.67  4611.2  416.89
  4616.4  417.47  4652.9  414.90  4658.1  415.41  4858.6  405.62  4941.9  403.27
  4983.1  404.01  4991.6  400.10  4996.7  402.48  5000.5  397.67  5001.0  396.87
  5006.4  396.87  5006.9  397.67  5014.0  403.40  5026.3  404.38  5100.3  402.16
  5130.8  403.60  5183.5  404.31  5237.6  405.62  5383.8  411.71  5407.6  413.42
  5489.8  416.99  5537.4  420.36  5542.8  419.39  5561.2  420.19  5575.6  419.64
#Mann=5,-1,0
  4508.6    0.16       0  5000.5    0.07       0  5006.9    0.16       0
  5026.3    0.12       0  5183.5    0.16       0
Bank Sta=4858.6,5237.6
Exp/Cntr=0.3,0.1

Type RM Length L Ch R = 1,572,451,451,451
BEGIN DESCRIPTION:
Mapping XS f338349d
END DESCRIPTION:
XS GIS Cut Line= 3
      2923184.57      6995864.56      2923414.62      6996437.51
      2923826.93      6996702.26
#Sta/Elev= 30
  4380.7  417.47  4444.9  416.97  4467.4  414.70  4585.0  411.03  4641.0  408.66
  4713.6  407.78  4764.2  403.59  4764.9  403.56  4821.1  402.21  4927.7  402.85
  4982.5  403.08  4994.1  400.49  4998.1  400.49  5000.1  395.98  5000.6  395.18
  5006.6  395.18  5007.1  395.98  5010.5  398.71  5018.8  401.92  5057.4  403.56
  5069.9  404.71  5112.6  404.40  5170.1  405.94  5185.3  408.39  5200.5  409.16
  5206.4  408.47  5212.5  409.53  5307.6  415.03  5430.4  417.48  5488.1  419.73
#Mann=7,-1,0
  4380.7    0.16       0  4444.9    0.12       0  4585.0    0.16       0
  4764.2    0.05       0  4927.7    0.16       0  5000.1    0.07       0
  5007.1    0.16       0
Bank Sta=4764.9,5057.4
Exp/Cntr=0.3,0.1

Type RM Length L Ch R = 1,121,0,0,0
BEGIN DESCRIPTION:
UNT 061 IN DRY CR WATERSHED 1.0
END DESCRIPTION:
XS GIS Cut Line= 4
      2923080.41      6995738.76      2923000.00      6996350.00
      2923050.00      6996500.00      2923770.28      6996784.64
#Sta/Elev= 30
  4313.1  418.25  4320.4  417.03  4379.9  415.17  4394.0  412.60  4460.6  412.78
  4480.8  410.93  4531.2  413.80  4625.0  413.54  4698.6  406.94  4785.9  400.96
  4791.7  400.73  4914.5  399.66  4966.5  401.71  4987.6  400.06  4992.3  398.47
  5004.5  393.24  5005.2  392.44  5012.8  393.24  5019.2  397.65  5040.3  400.09
  5109.5  400.46  5128.6  400.52  5242.6  400.96  5347.8  401.37  5555.6  403.47
  5658.4  408.40  5663.7  407.15  5695.2  406.73  5749.0  411.08  5862.2  416.22
#Mann=8,-1,0
  4313.1    0.16       0  4791.7    0.05       0  4992.3    0.16       0
  5004.5    0.07       0  5012.8    0.16       0  5109.5    0.07       0
  5128.6    0.05       0  5347.8    0.16       0
Bank Sta=4785.9,5242.6
Exp/Cntr=0.3,0.1

Chan Stop Cuts=-1