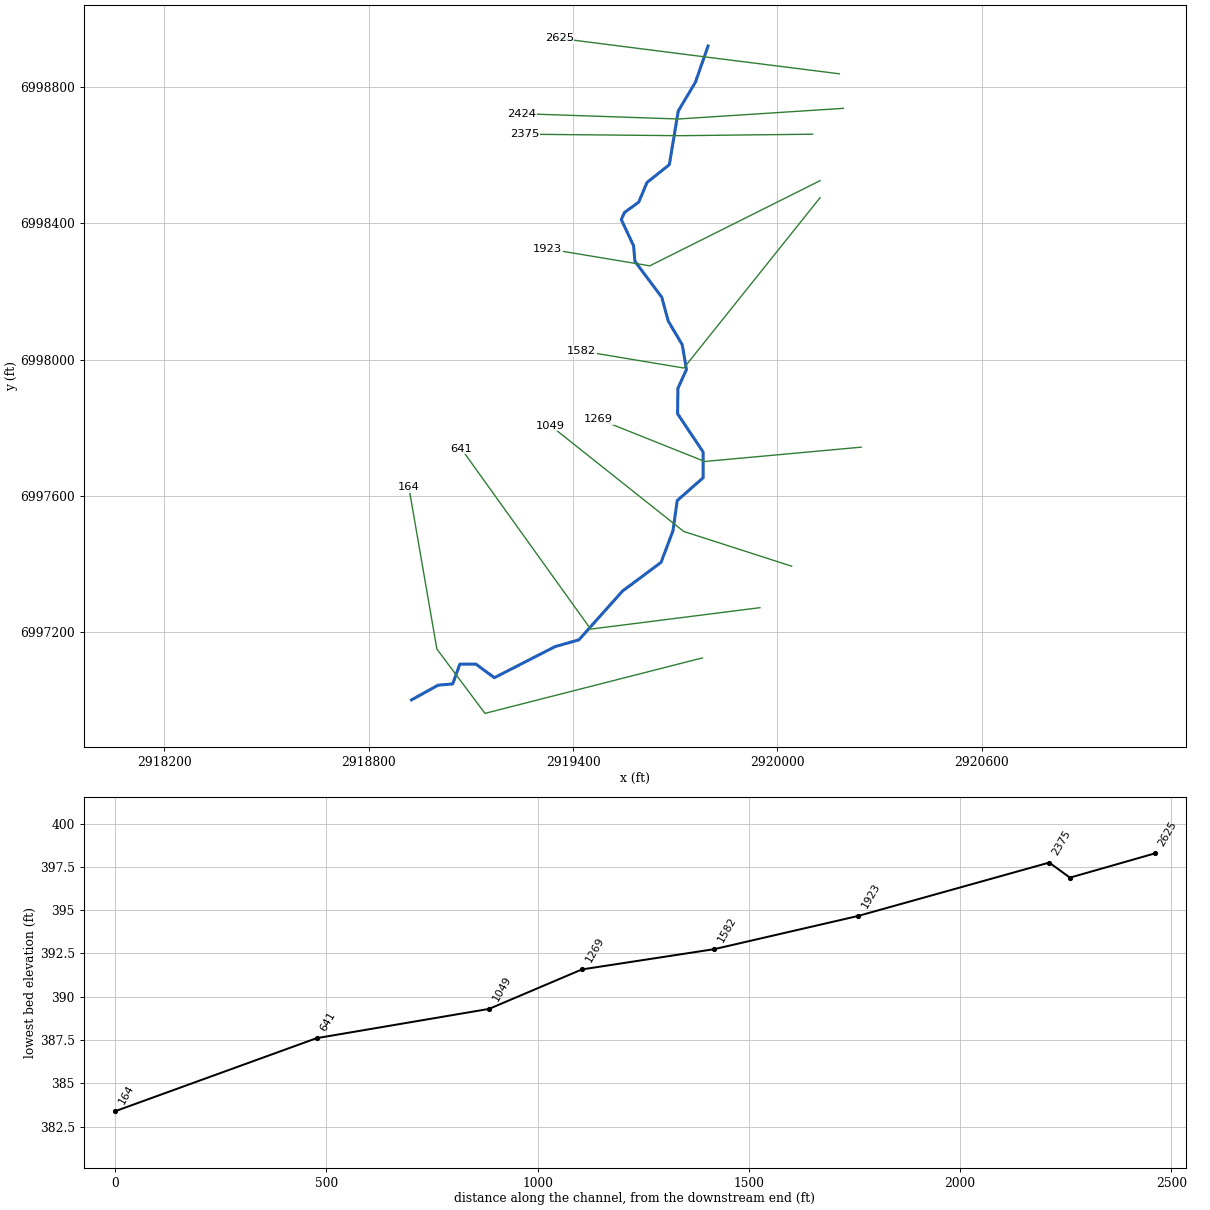
--- UNT 062 IN DRY CR WATERSHED.prj (project) ---

Proj Title=UNT 062 IN DRY CR WATERSHED Base Level Engineering
Current Plan=p01
Default Exp/Contr=0.3,0.1
English Units
Geom File=g01
Flow File=f01
Plan File=p01
BEGIN DESCRIPTION:
UNT 062 IN DRY CR WATERSHED
END DESCRIPTION:

--- UNT 062 IN DRY CR WATERSHED.p01 (plan) ---

Plan Title=Multiple Run
Short Identifier=Multiple
Geom File=g01
Flow File=f01
Subcritical Flow
K Sum by GR= 0
Std Step Tol= 0.01
Critical Tol= 0.01
Num of Std Step Trials= 20
Max Error Tol= 0.3
Flow Tol Ratio= 0.001
Split Flow NTrial= 30
Split Flow Tol= 0.02
Split Flow Ratio= 0.02
Log Output Level= 0
Friction Slope Method= 1
Unsteady Friction Slope Method= 2
Unsteady Bridges Friction Slope Method= 1
Parabolic Critical Depth
Global Vel Dist=  1 , 1 , 1
Global Log Level= 0
CheckData=True
Encroach Param= -1, 0, 0, 0
BEGIN DESCRIPTION:
Multiple Run
END DESCRIPTION:

--- UNT 062 IN DRY CR WATERSHED.f01 (steady flow) ---

Flow Title=Multiple
Number of Profiles=7
Profile Names=10-year,25-year,50-year,1pct_min,100-year,1pct_plu,500-year
River Rch & RM= UNT 062 IN DRY C,Reach-1,2625
     572     769     930     559    1116    2226    1609
Boundary for River Rch & Prof#=UNT 062 IN DRY C,Reach-1,1
Up Type=0
Dn Type=3
Dn Slope=0.005
Boundary for River Rch & Prof#=UNT 062 IN DRY C,Reach-1,2
Up Type=0
Dn Type=3
Dn Slope=0.005
Boundary for River Rch & Prof#=UNT 062 IN DRY C,Reach-1,3
Up Type=0
Dn Type=3
Dn Slope=0.005
Boundary for River Rch & Prof#=UNT 062 IN DRY C,Reach-1,4
Up Type=0
Dn Type=3
Dn Slope=0.005
Boundary for River Rch & Prof#=UNT 062 IN DRY C,Reach-1,5
Up Type=0
Dn Type=3
Dn Slope=0.005
Boundary for River Rch & Prof#=UNT 062 IN DRY C,Reach-1,6
Up Type=0
Dn Type=3
Dn Slope=0.005
Boundary for River Rch & Prof#=UNT 062 IN DRY C,Reach-1,7
Up Type=0
Dn Type=3
Dn Slope=0.005

--- UNT 062 IN DRY CR WATERSHED.g01 (geometry) ---

Geom Title=Existing Conditions

River Reach=UNT 062 IN DRY C,Reach-1
Reach XY= 30
      2919796.28      6998920.42      2919759.03      6998814.00
      2919708.65      6998729.44      2919682.46      6998571.87
      2919616.83      6998519.57      2919592.59      6998461.98
      2919550.90      6998431.77      2919541.45      6998410.89
      2919577.51      6998333.88      2919581.46      6998288.47
      2919660.07      6998183.14      2919679.55      6998112.32
      2919720.21      6998043.81      2919732.87      6997970.86
      2919707.62      6997915.13      2919706.72      6997840.74
      2919781.76      6997728.32      2919781.91      6997652.93
      2919705.66      6997585.79      2919693.07      6997496.75
      2919658.12      6997404.35      2919544.96      6997320.08
      2919416.86      6997176.90      2919347.13      6997157.08
      2919168.77      6997065.78      2919114.32      6997105.87
      2919067.52      6997105.65      2919046.47      6997047.60
      2919003.36      6997043.80      2918925.59      6997000.71

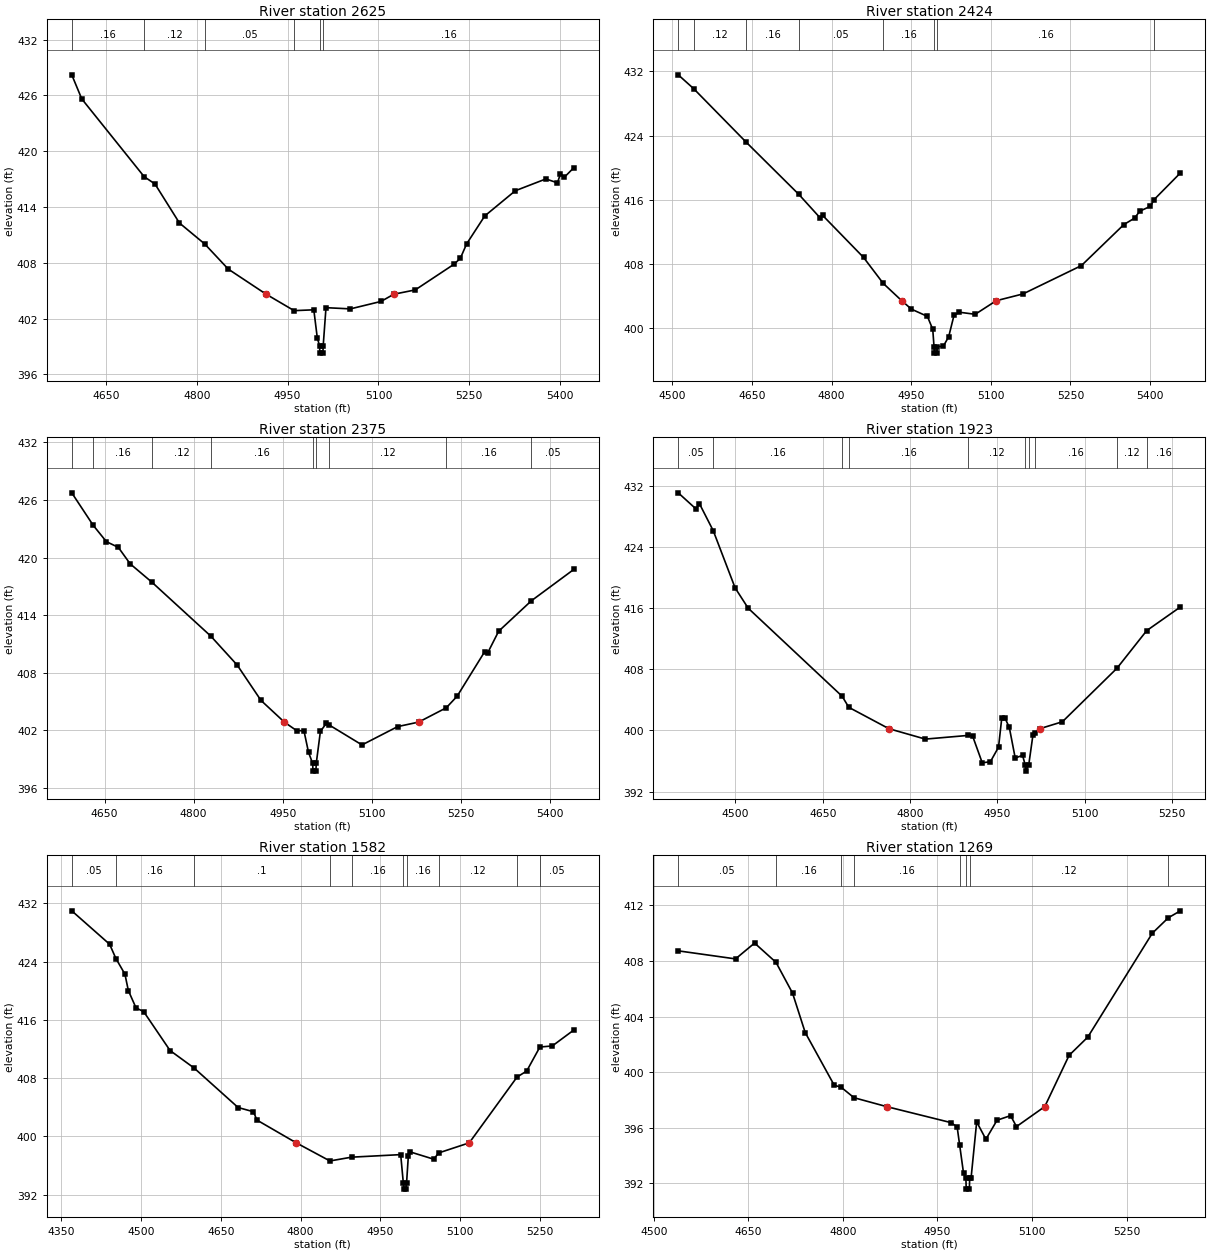
Type RM Length L Ch R = 1,2625,201,201,201
BEGIN DESCRIPTION:
UNT 062 IN DRY CR WATERSHED 5.0
END DESCRIPTION:
XS GIS Cut Line= 3
      2920181.32      6998838.85      2919778.31      6998889.58
      2919359.19      6998942.92
#Sta/Elev= 30
  4593.8  428.22  4610.3  425.63  4713.2  417.27  4731.2  416.47  4771.5  412.28
  4813.3  410.02  4852.1  407.32  4914.6  404.62  4960.8  402.85  4993.3  402.94
  4999.1  399.89  5002.8  399.08  5003.3  398.28  5008.3  398.28  5008.8  399.08
  5013.4  403.17  5053.7  403.04  5104.1  403.84  5125.5  404.62  5160.7  405.08
  5225.1  407.86  5235.2  408.49  5245.6  410.04  5275.5  413.04  5325.9  415.75
  5376.3  417.02  5395.4  416.60  5400.4  417.56  5406.6  417.19  5422.5  418.23
#Mann=6,-1,0
  4593.8    0.16       0  4713.2    0.12       0  4813.3    0.05       0
  4960.8    0.16       0  5002.8    0.07       0  5008.8    0.16       0
Bank Sta=4914.6,5125.5
Exp/Cntr=0.3,0.1

Type RM Length L Ch R = 1,2424,49,49,49
BEGIN DESCRIPTION:
Mapping XS 40d0eac2
END DESCRIPTION:
XS GIS Cut Line= 3
      2920193.56      6998737.38      2919709.20      6998706.13
      2919248.73      6998721.71
#Sta/Elev= 30
  4511.0  431.57  4540.0  429.85  4639.1  423.17  4738.2  416.67  4778.1  413.76
  4783.1  414.05  4860.3  408.80  4897.2  405.58  4932.2  403.41  4950.5  402.36
  4980.5  401.46  4990.6  399.85  4993.0  397.68  4993.5  396.88  4998.5  396.88
  4999.0  397.68  5010.6  397.75  5020.6  398.92  5030.6  401.58  5040.6  401.98
  5070.6  401.72  5110.1  403.41  5160.7  404.26  5270.7  407.79  5350.8  412.91
  5370.8  413.70  5380.8  414.58  5400.8  415.18  5407.6  416.01  5457.1  419.33
#Mann=8,-1,0
  4511.0    0.16       0  4540.0    0.12       0  4639.1    0.16       0
  4738.2    0.05       0  4897.2    0.16       0  4993.0    0.07       0
  4999.0    0.16       0  5407.6    0.05       0
Bank Sta=4932.2,5110.1
Exp/Cntr=0.3,0.1

Type RM Length L Ch R = 1,2375,452,452,452
BEGIN DESCRIPTION:
Mapping XS e684cabd
END DESCRIPTION:
XS GIS Cut Line= 3
      2920103.34      6998661.43      2919712.67      6998657.09
      2919258.49      6998661.42
#Sta/Elev= 30
  4594.9  426.75  4630.9  423.37  4653.2  421.66  4673.2  421.07  4693.2  419.35
  4729.9  417.43  4829.0  411.81  4873.3  408.80  4913.3  405.12  4952.6  402.86
  4973.3  401.97  4985.6  401.96  4993.3  399.71  5000.3  398.55  5000.8  397.75
  5005.8  397.75  5006.3  398.55  5013.3  401.89  5023.3  402.73  5027.0  402.60
  5083.3  400.48  5143.3  402.39  5178.7  402.86  5225.1  404.35  5243.3  405.55
  5289.7  410.19  5294.7  410.06  5313.3  412.33  5368.3  415.50  5439.8  418.77
#Mann=9,-1,0
  4594.9    0.05       0  4630.9    0.16       0  4729.9    0.12       0
  4829.0    0.16       0  5000.3    0.07       0  5006.3    0.16       0
  5027.0    0.12       0  5225.1    0.16       0  5368.3    0.05       0
Bank Sta=4952.6,5178.7
Exp/Cntr=0.3,0.1

Type RM Length L Ch R = 1,1923,341,341,341
BEGIN DESCRIPTION:
UNT 062 IN DRY CR WATERSHED 4.0
END DESCRIPTION:
XS GIS Cut Line= 3
      2920124.97      6998524.98      2919625.00      6998275.00
      2919325.02      6998325.00
#Sta/Elev= 30
  4401.6  431.08  4432.3  428.96  4437.9  429.68  4461.8  426.12  4499.4  418.64
  4521.8  415.99  4683.4  404.46  4694.8  403.02  4763.8  400.22  4826.4  398.86
  4899.7  399.34  4907.5  399.29  4924.2  395.76  4938.2  395.90  4952.2  397.80
  4957.8  401.64  4963.1  401.64  4970.7  400.40  4980.9  396.38  4993.5  396.74
  4998.1  395.47  4998.6  394.67  5004.1  395.47  5011.3  399.36  5015.2  399.68
  5023.1  400.22  5062.0  401.13  5155.8  408.13  5206.9  413.05  5264.7  416.14
#Mann=10,-1,0
  4401.6    0.05       0  4461.8    0.16       0  4683.4    0.05       0
  4694.8    0.16       0  4899.7    0.12       0  4998.1    0.07       0
  5004.1    0.12       0  5015.2    0.16       0  5155.8    0.12       0
  5206.9    0.16       0
Bank Sta=4763.8,5023.1
Exp/Cntr=0.3,0.1

Type RM Length L Ch R = 1,1582,313,313,313
BEGIN DESCRIPTION:
UNT 062 IN DRY CR WATERSHED 3.0
END DESCRIPTION:
XS GIS Cut Line= 3
      2920125.00      6998474.99      2919725.00      6997975.00
      2919425.04      6998024.99
#Sta/Elev= 30
  4369.5  430.98  4440.7  426.39  4452.5  424.43  4469.5  422.28  4475.9  420.03
  4490.4  417.64  4504.8  417.13  4554.4  411.79  4599.7  409.38  4682.4  403.96
  4711.3  403.38  4717.7  402.24  4791.7  399.11  4855.1  396.62  4895.7  397.14
  4988.2  397.49  4993.2  393.55  4993.7  392.75  4998.7  392.75  4999.2  393.55
  5002.6  397.32  5006.6  397.85  5050.4  396.86  5059.5  397.72  5117.2  399.11
  5207.1  408.15  5225.2  408.97  5250.0  412.27  5273.4  412.42  5313.9  414.61
#Mann=10,-1,0
  4369.5    0.05       0  4452.5    0.16       0  4599.7     0.1       0
  4855.1    0.12       0  4895.7    0.16       0  4993.2    0.07       0
  4999.2    0.16       0  5059.5    0.12       0  5207.1    0.16       0
  5250.0    0.05       0
Bank Sta=4791.7,5117.2
Exp/Cntr=0.3,0.1

Type RM Length L Ch R = 1,1269,220,220,220
BEGIN DESCRIPTION:
UNT 062 IN DRY CR WATERSHED 2.0
END DESCRIPTION:
XS GIS Cut Line= 3
      2920245.57      6997742.61      2919786.39      6997700.62
      2919475.01      6997825.00
#Sta/Elev= 30
  4538.9  408.73  4629.8  408.15  4660.0  409.29  4694.0  407.90  4720.2  405.69
  4740.3  402.85  4786.3  399.06  4797.4  398.91  4817.7  398.16  4869.4  397.52
  4971.3  396.37  4981.3  396.06  4985.3  394.75  4991.4  392.74  4995.2  392.38
  4995.7  391.58  5000.7  391.58  5001.2  392.38  5003.4  392.38  5012.3  396.42
  5026.9  395.17  5044.6  396.54  5066.1  396.87  5075.4  396.08  5120.3  397.52
  5158.9  401.21  5188.5  402.52  5290.9  410.00  5316.3  411.11  5335.3  411.61
#Mann=8,-1,0
  4538.9    0.05       0  4694.0    0.16       0  4797.4    0.12       0
  4817.7    0.16       0  4985.3    0.12       0  4995.2    0.07       0
  5001.2    0.12       0  5316.3    0.05       0
Bank Sta=4869.4,5120.3
Exp/Cntr=0.3,0.1

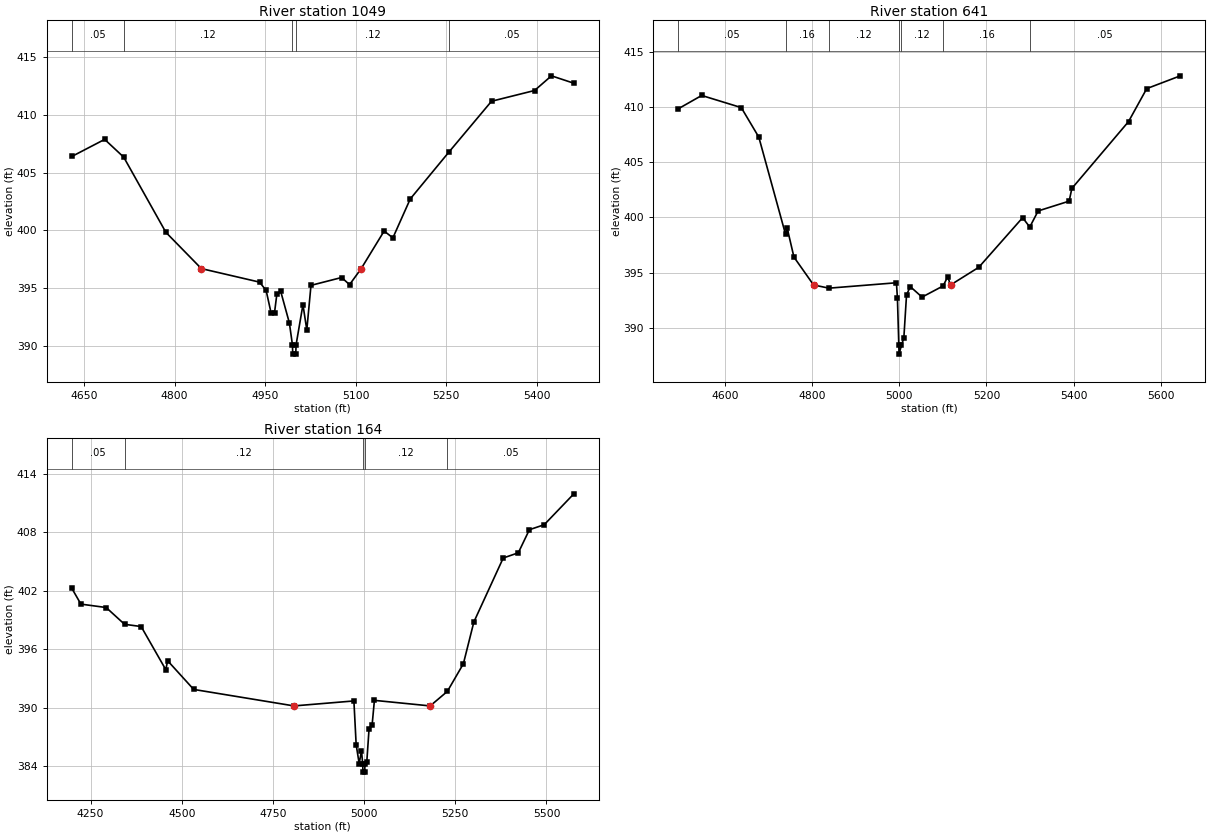
Type RM Length L Ch R = 1,1049,408,408,408
BEGIN DESCRIPTION:
Mapping XS 6daffd29
END DESCRIPTION:
XS GIS Cut Line= 3
      2920041.55      6997393.21      2919724.70      6997495.22
      2919334.04      6997805.57
#Sta/Elev= 30
  4629.6  406.40  4684.1  407.88  4715.7  406.34  4785.5  399.84  4844.3  396.70
  4940.7  395.53  4951.6  394.81  4959.7  392.89  4965.5  392.89  4969.3  394.46
  4975.7  394.74  4990.1  392.00  4995.2  390.10  4995.7  389.30  5000.7  389.30
  5001.2  390.10  5012.6  393.58  5019.0  391.39  5025.9  395.25  5076.7  395.93
  5089.8  395.31  5109.1  396.70  5147.1  399.95  5161.6  399.36  5190.4  402.73
  5254.7  406.80  5325.0  411.18  5396.3  412.11  5424.3  413.38  5461.4  412.74
#Mann=5,-1,0
  4629.6    0.05       0  4715.7    0.12       0  4995.2    0.07       0
  5001.2    0.12       0  5254.7    0.05       0
Bank Sta=4844.3,5109.1
Exp/Cntr=0.3,0.1

Type RM Length L Ch R = 1,641,477,477,477
BEGIN DESCRIPTION:
Mapping XS d1215d7b
END DESCRIPTION:
XS GIS Cut Line= 3
      2919948.52      6997271.40      2919451.55      6997208.47
      2919071.75      6997738.01
#Sta/Elev= 30
  4492.4  409.85  4546.3  411.06  4637.1  409.96  4677.4  407.28  4738.8  398.46
  4742.6  399.02  4758.0  396.41  4803.1  393.88  4838.4  393.59  4993.3  394.08
  4995.6  392.67  4998.8  388.41  4999.3  387.61  5004.8  388.41  5010.3  389.07
  5016.5  392.98  5025.1  393.73  5052.1  392.78  5100.4  393.79  5111.0  394.62
  5117.5  393.88  5182.3  395.48  5283.0  399.98  5299.4  399.13  5318.6  400.59
  5389.8  401.48  5396.0  402.63  5526.1  408.69  5567.9  411.68  5645.0  412.84
#Mann=7,-1,0
  4492.4    0.05       0  4738.8    0.16       0  4838.4    0.12       0
  4998.8    0.07       0  5004.8    0.12       0  5100.4    0.16       0
  5299.4    0.05       0
Bank Sta=4803.1,5117.5
Exp/Cntr=0.3,0.1

Type RM Length L Ch R = 1,164,0,0,0
BEGIN DESCRIPTION:
UNT 062 IN DRY CR WATERSHED 1.0
END DESCRIPTION:
XS GIS Cut Line= 4
      2919779.25      6997123.84      2919141.22      6996961.07
      2919000.00      6997150.00      2918917.70      6997625.09
#Sta/Elev= 30
  4198.5  402.25  4223.5  400.62  4292.8  400.27  4343.2  398.55  4388.7  398.32
  4456.2  393.90  4461.4  394.81  4532.8  391.87  4807.7  390.18  4972.0  390.69
  4978.2  386.20  4986.5  384.26  4992.8  385.60  4996.2  384.19  4996.7  383.39
  5001.7  383.39  5002.2  384.19  5007.4  384.47  5013.6  387.86  5022.0  388.25
  5028.2  390.75  5181.1  390.18  5228.2  391.67  5272.1  394.50  5300.9  398.79
  5381.4  405.35  5422.7  405.88  5453.1  408.25  5493.7  408.76  5575.0  411.93
#Mann=5,-1,0
  4198.5    0.05       0  4343.2    0.12       0  4996.2    0.07       0
  5002.2    0.12       0  5228.2    0.05       0
Bank Sta=4807.7,5181.1
Exp/Cntr=0.3,0.1

Chan Stop Cuts=-1