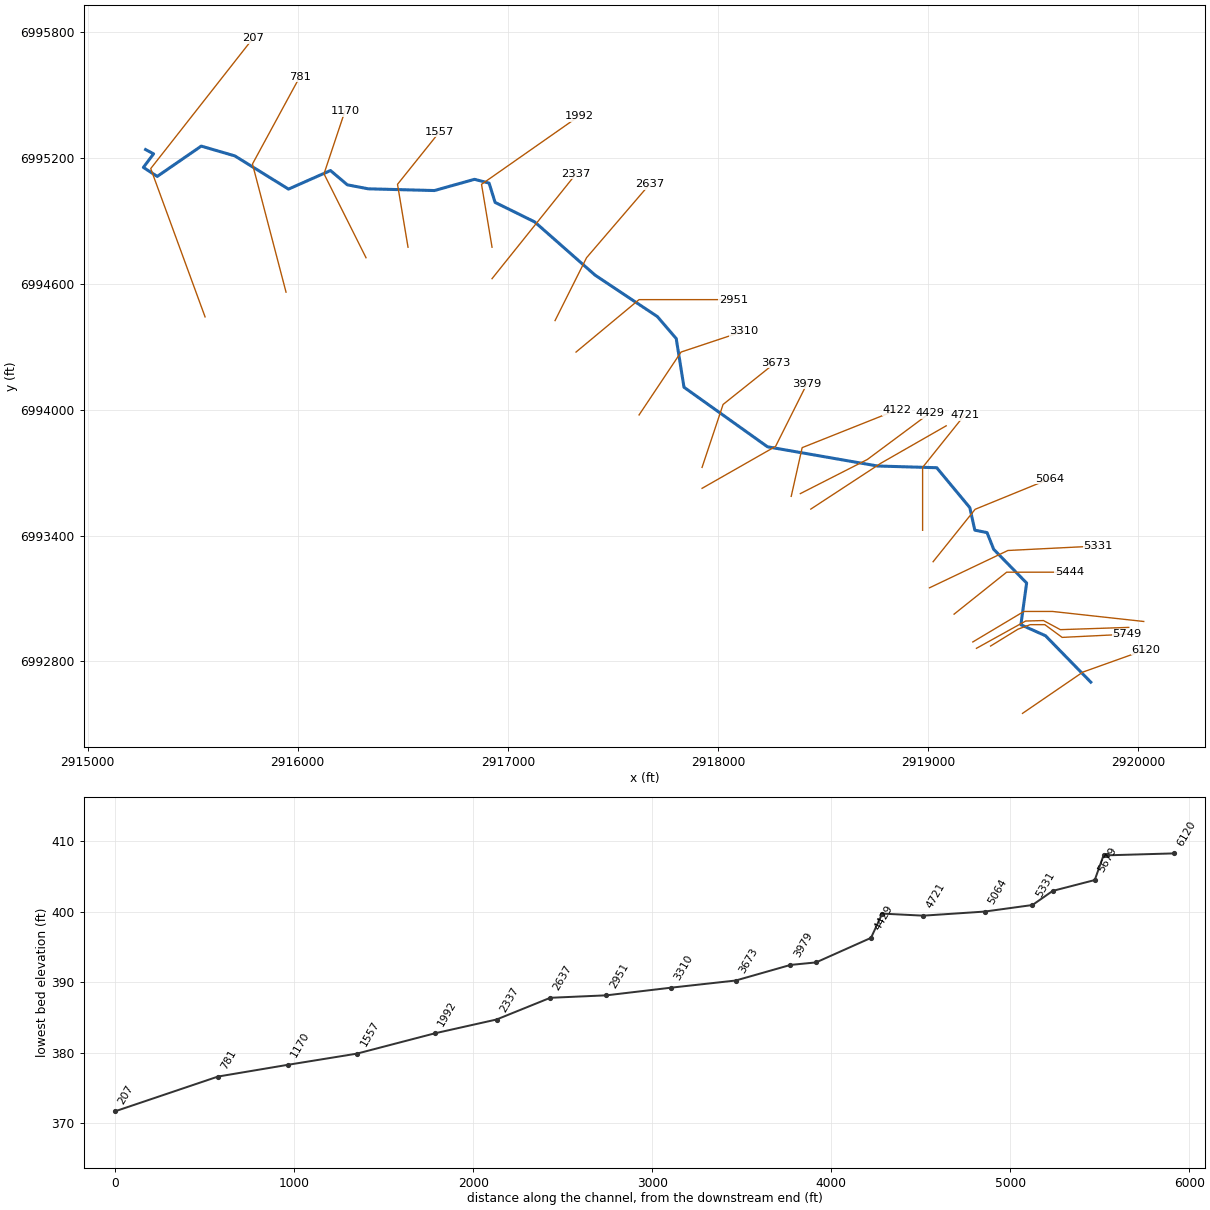
--- UNT 063 IN DRY CR WATERSHED.prj (project) ---

Proj Title=UNT 063 IN DRY CR WATERSHED Base Level Engineering
Current Plan=p01
Default Exp/Contr=0.3,0.1
English Units
Geom File=g01
Flow File=f01
Plan File=p01
BEGIN DESCRIPTION:
UNT 063 IN DRY CR WATERSHED
END DESCRIPTION:

--- UNT 063 IN DRY CR WATERSHED.p01 (plan) ---

Plan Title=Multiple Run
Short Identifier=Multiple
Geom File=g01
Flow File=f01
Subcritical Flow
K Sum by GR= 0
Std Step Tol= 0.01
Critical Tol= 0.01
Num of Std Step Trials= 20
Max Error Tol= 0.3
Flow Tol Ratio= 0.001
Split Flow NTrial= 30
Split Flow Tol= 0.02
Split Flow Ratio= 0.02
Log Output Level= 0
Friction Slope Method= 1
Unsteady Friction Slope Method= 2
Unsteady Bridges Friction Slope Method= 1
Parabolic Critical Depth
Global Vel Dist=  1 , 1 , 1
Global Log Level= 0
CheckData=True
Encroach Param= -1, 0, 0, 0
BEGIN DESCRIPTION:
Multiple Run
END DESCRIPTION:

--- UNT 063 IN DRY CR WATERSHED.f01 (steady flow) ---

Flow Title=Multiple
Number of Profiles=7
Profile Names=10-year,25-year,50-year,1pct_min,100-year,1pct_plu,500-year
River Rch & RM= UNT 063 IN DRY C,Reach-1,6120
     541     724     871     522    1041    2077    1489
River Rch & RM= UNT 063 IN DRY C,Reach-1,781
     608     817     988     594    1184    2363    1705
Boundary for River Rch & Prof#=UNT 063 IN DRY C,Reach-1,1
Up Type=0
Dn Type=3
Dn Slope=0.005
Boundary for River Rch & Prof#=UNT 063 IN DRY C,Reach-1,2
Up Type=0
Dn Type=3
Dn Slope=0.005
Boundary for River Rch & Prof#=UNT 063 IN DRY C,Reach-1,3
Up Type=0
Dn Type=3
Dn Slope=0.005
Boundary for River Rch & Prof#=UNT 063 IN DRY C,Reach-1,4
Up Type=0
Dn Type=3
Dn Slope=0.005
Boundary for River Rch & Prof#=UNT 063 IN DRY C,Reach-1,5
Up Type=0
Dn Type=3
Dn Slope=0.005
Boundary for River Rch & Prof#=UNT 063 IN DRY C,Reach-1,6
Up Type=0
Dn Type=3
Dn Slope=0.005
Boundary for River Rch & Prof#=UNT 063 IN DRY C,Reach-1,7
Up Type=0
Dn Type=3
Dn Slope=0.005

--- UNT 063 IN DRY CR WATERSHED.g01 (geometry) ---

Geom Title=Existing Conditions

River Reach=UNT 063 IN DRY C,Reach-1
Reach XY= 30
      2919775.59      6992700.71      2919559.99      6992922.01
      2919442.98      6992974.33      2919470.23      6993173.21
      2919313.54      6993334.07      2919281.73      6993413.93
      2919223.61      6993425.53      2919199.80      6993533.00
      2919042.19      6993723.30      2918760.90      6993731.46
      2918236.57      6993823.09      2917838.91      6994107.20
      2917801.99      6994339.22      2917712.24      6994444.11
      2917415.55      6994641.93      2917128.20      6994895.62
      2916939.54      6994988.85      2916911.03      6995080.78
      2916841.53      6995098.81      2916650.75      6995045.30
      2916335.64      6995053.52      2916236.05      6995072.58
      2916155.77      6995140.70      2915955.99      6995052.17
      2915700.42      6995210.57      2915540.56      6995257.21
      2915330.94      6995112.65      2915265.01      6995155.65
      2915313.59      6995220.38      2915275.59      6995240.71

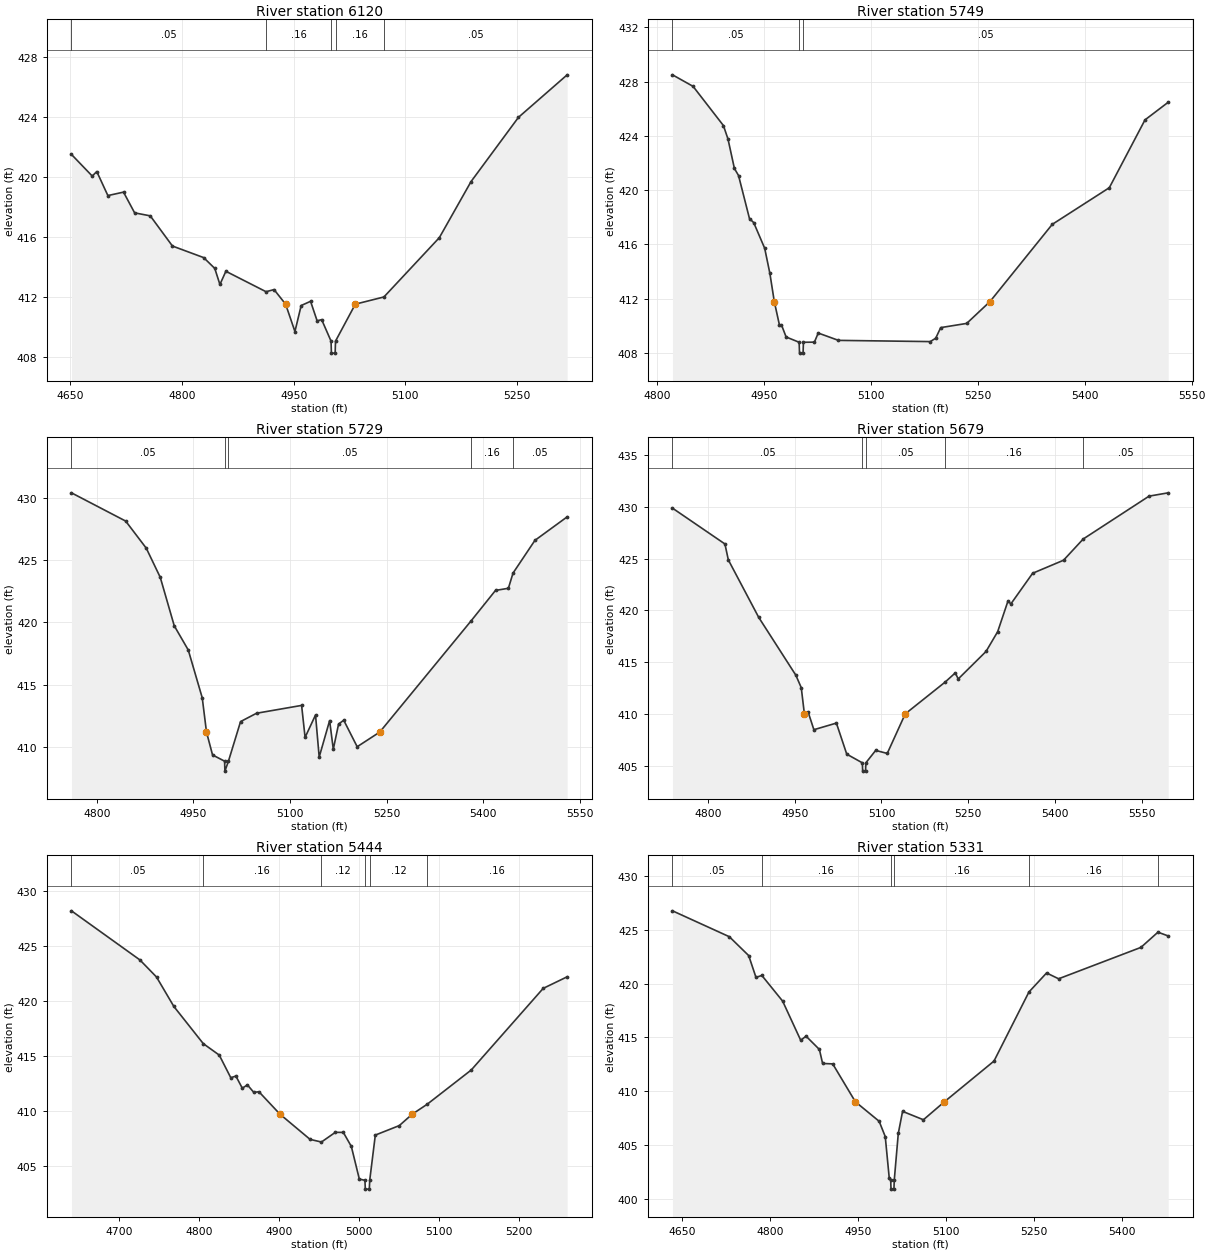
Type RM Length L Ch R = 1,6120,371,371,371
BEGIN DESCRIPTION:
UNT 063 IN DRY CR WATERSHED 15.0
END DESCRIPTION:
XS GIS Cut Line= 3
      2919450.64      6992551.67      2919737.95      6992748.56
      2920036.59      6992855.48
#Sta/Elev= 30
  4651.7  421.49  4679.6  420.05  4685.7  420.35  4700.6  418.75  4721.6  418.98
  4736.5  417.60  4757.5  417.40  4787.3  415.39  4829.2  414.62  4844.1  413.90
  4851.0  412.83  4859.0  413.71  4912.9  412.35  4923.7  412.49  4939.2  411.52
  4951.7  409.70  4960.1  411.43  4972.7  411.71  4981.5  410.41  4987.6  410.49
  5000.2  409.06  5000.7  408.26  5005.7  408.26  5006.2  409.06  5032.8  411.52
  5071.2  412.00  5145.6  415.95  5188.1  419.68  5251.8  423.96  5317.2  426.79
#Mann=5,-1,0
  4651.7    0.05       0  4912.9    0.16       0  5000.2    0.07       0
  5006.2    0.16       0  5071.2    0.05       0
Bank Sta=4939.2,5032.8
Exp/Cntr=0.3,0.1

Type RM Length L Ch R = 1,5749,20,20,20
BEGIN DESCRIPTION:
Mapping XS 88b77ffd
END DESCRIPTION:
XS GIS Cut Line= 6
      2919298.66      6992872.80      2919428.90      6992953.12
      2919487.50      6992974.82      2919556.94      6992974.82
      2919639.41      6992914.05      2919947.55      6992929.24
#Sta/Elev= 30
  4821.2  428.50  4850.1  427.65  4892.7  424.76  4899.1  423.77  4908.1  421.60
  4913.9  421.08  4929.3  417.90  4935.2  417.61  4950.6  415.72  4957.9  413.87
  4964.1  411.79  4971.3  410.07  4974.2  410.07  4980.7  409.18  4999.0  408.79
  4999.5  407.99  5004.5  407.99  5005.0  408.79  5020.4  408.80  5025.8  409.47
  5054.2  408.93  5183.1  408.84  5190.7  409.09  5197.7  409.87  5234.2  410.18
  5266.9  411.79  5354.3  417.48  5434.4  420.18  5484.5  425.18  5517.1  426.48
#Mann=3,-1,0
  4821.2    0.05       0  4999.0    0.03       0  5005.0    0.05       0
Bank Sta=4964.1,5266.9
Exp/Cntr=0.3,0.1

Type RM Length L Ch R = 1,5729,50,50,50
BEGIN DESCRIPTION:
Mapping XS 4d1c009d
END DESCRIPTION:
XS GIS Cut Line= 5
      2919231.40      6992861.96      2919465.80      6992992.18
      2919550.43      6992994.35      2919630.73      6992950.95
      2919956.26      6992961.80
#Sta/Elev= 30
  4760.7  430.40  4844.9  428.13  4876.9  425.95  4898.6  423.61  4920.3  419.72
  4942.1  417.77  4963.8  413.93  4970.4  411.18  4979.8  409.34  4998.5  408.84
  4999.0  408.04  5004.5  408.84  5023.3  412.02  5048.1  412.69  5118.1  413.32
  5123.5  410.75  5139.7  412.55  5145.4  409.17  5161.6  412.10  5167.3  409.80
  5175.5  411.82  5183.5  412.13  5204.4  410.00  5239.5  411.18  5381.1  420.10
  5419.2  422.56  5439.2  422.73  5446.4  423.95  5480.4  426.58  5530.5  428.47
#Mann=5,-1,0
  4760.7    0.05       0  4998.5    0.03       0  5004.5    0.05       0
  5381.1    0.16       0  5446.4    0.05       0
Bank Sta=4970.4,5239.5
Exp/Cntr=0.3,0.1

Type RM Length L Ch R = 1,5679,235,235,235
BEGIN DESCRIPTION:
Mapping XS 4c3d968e
END DESCRIPTION:
XS GIS Cut Line= 4
      2919214.08      6992892.36      2919457.12      6993037.75
      2919593.83      6993037.75      2920027.89      6992990.01
#Sta/Elev= 30
  4738.9  429.88  4829.5  426.42  4835.4  424.88  4887.9  419.33  4952.1  413.74
  4961.4  412.54  4966.8  410.01  4973.5  410.15  4983.2  408.48  5022.1  409.12
  5040.0  406.12  5067.0  405.28  5067.5  404.48  5072.5  404.48  5073.0  405.28
  5090.0  406.48  5110.0  406.19  5141.1  410.01  5210.0  413.08  5227.6  413.97
  5232.6  413.38  5280.7  416.04  5300.8  417.95  5318.6  420.91  5323.6  420.63
  5361.2  423.59  5414.6  424.85  5448.6  426.90  5562.4  431.04  5595.5  431.36
#Mann=5,-1,0
  4738.9    0.05       0  5067.0    0.03       0  5073.0    0.05       0
  5210.0    0.16       0  5448.6    0.05       0
Bank Sta=4966.8,5141.1
Exp/Cntr=0.3,0.1

Type RM Length L Ch R = 1,5444,113,113,113
BEGIN DESCRIPTION:
UNT 063 IN DRY CR WATERSHED 14.0
END DESCRIPTION:
XS GIS Cut Line= 3
      2919125.01      6993025.01      2919375.00      6993225.00
      2919674.95      6993225.00
#Sta/Elev= 30
  4640.7  428.17  4726.3  423.72  4747.1  422.17  4768.8  419.50  4805.6  416.13
  4825.6  415.09  4840.0  413.04  4846.4  413.19  4854.4  412.09  4860.8  412.39
  4868.8  411.71  4875.2  411.77  4901.6  409.73  4939.2  407.45  4953.4  407.21
  4970.8  408.09  4980.8  408.08  4990.8  406.81  5000.8  403.85  5007.8  403.74
  5008.3  402.94  5013.3  402.94  5013.8  403.74  5020.8  407.84  5050.8  408.70
  5066.9  409.73  5085.6  410.63  5140.8  413.74  5230.8  421.14  5260.8  422.19
#Mann=6,-1,0
  4640.7    0.05       0  4805.6    0.16       0  4953.4    0.12       0
  5007.8    0.07       0  5013.8    0.12       0  5085.6    0.16       0
Bank Sta=4901.6,5066.9
Exp/Cntr=0.3,0.1

Type RM Length L Ch R = 1,5331,267,267,267
BEGIN DESCRIPTION:
Mapping XS db162e0d
END DESCRIPTION:
XS GIS Cut Line= 3
      2919007.86      6993150.58      2919381.16      6993328.55
      2919811.47      6993350.17
#Sta/Elev= 30
  4634.3  426.74  4731.1  424.34  4764.1  422.59  4776.5  420.57  4786.5  420.75
  4821.9  418.37  4852.7  414.74  4861.8  415.12  4884.5  413.89  4890.0  412.59
  4907.2  412.55  4945.8  409.04  4986.3  407.23  4996.7  405.81  5003.5  401.96
  5006.0  401.74  5006.5  400.94  5011.5  400.94  5012.0  401.74  5018.9  406.10
  5026.2  408.15  5061.7  407.37  5097.5  409.04  5181.9  412.81  5241.4  419.21
  5271.5  420.98  5292.0  420.44  5432.2  423.35  5461.2  424.76  5478.7  424.41
#Mann=6,-1,0
  4634.3    0.05       0  4786.5    0.16       0  5006.0    0.07       0
  5012.0    0.16       0  5241.4    0.16       0  5461.2    0.05       0
Bank Sta=4945.8,5097.5
Exp/Cntr=0.3,0.1

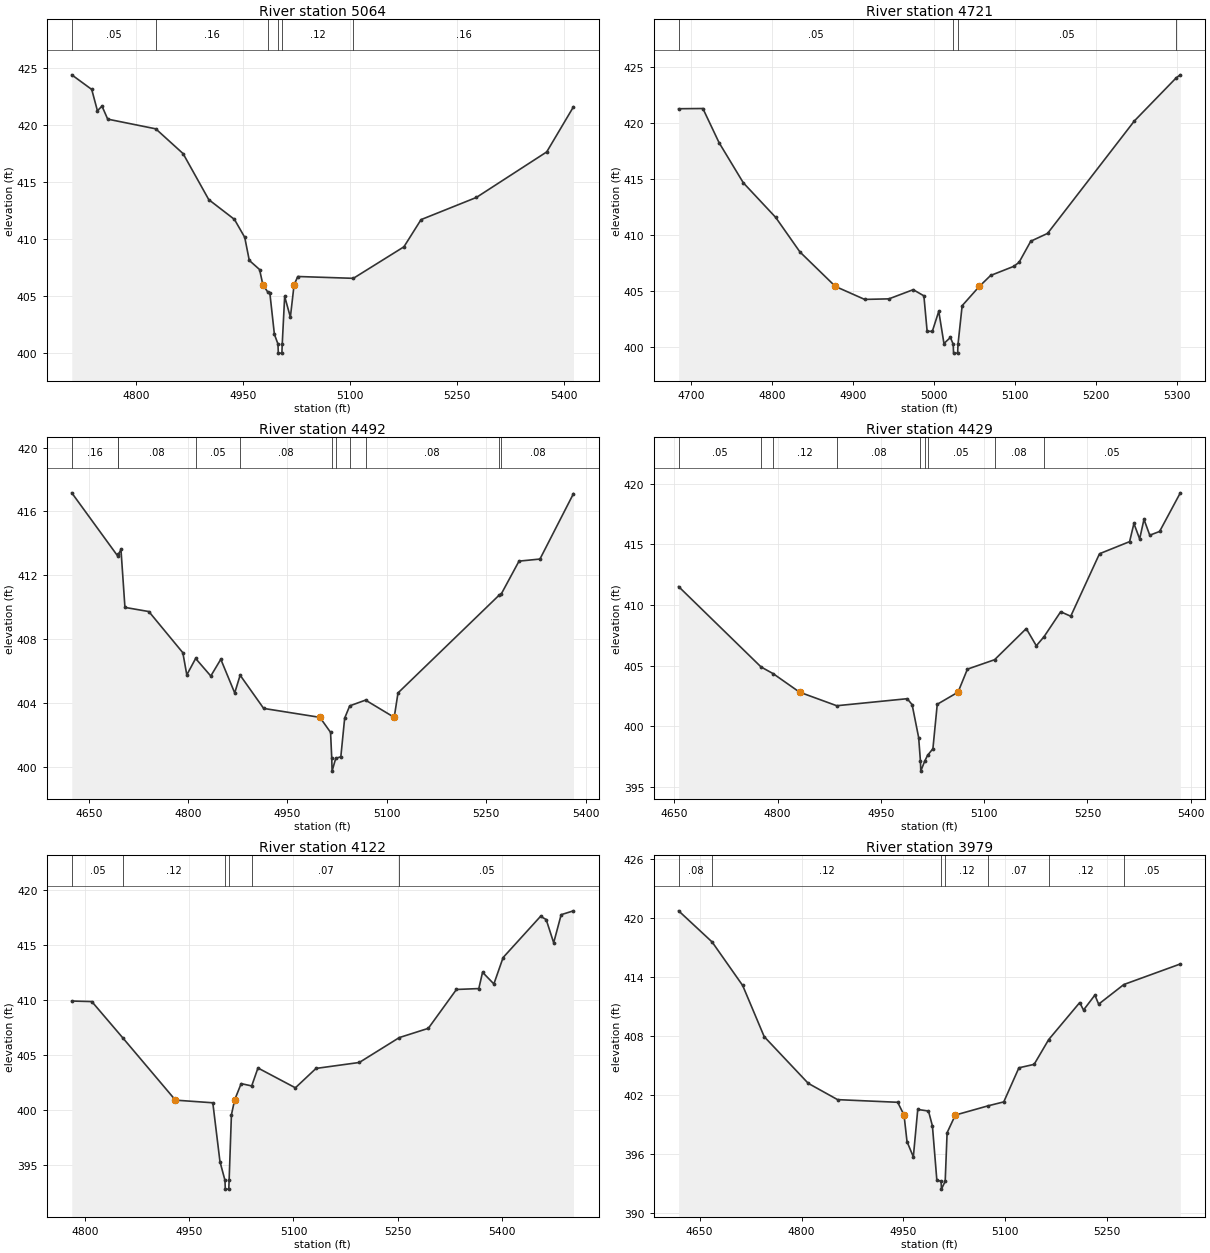
Type RM Length L Ch R = 1,5064,343,343,343
BEGIN DESCRIPTION:
UNT 063 IN DRY CR WATERSHED 13.0
END DESCRIPTION:
XS GIS Cut Line= 3
      2919025.01      6993275.01      2919225.00      6993525.00
      2919579.72      6993670.10
#Sta/Elev= 30
  4710.0  424.38  4738.0  423.10  4746.0  421.23  4752.4  421.64  4760.4  420.50
  4827.8  419.65  4866.1  417.48  4902.1  413.45  4938.1  411.72  4952.5  410.15
  4958.9  408.13  4973.3  407.33  4978.0  405.99  4984.7  405.37  4987.7  405.29
  4994.1  401.66  4999.1  400.81  4999.6  400.01  5004.6  400.01  5005.1  400.81
  5008.5  404.98  5016.5  403.16  5021.7  405.99  5026.9  406.72  5104.8  406.56
  5175.7  409.32  5199.7  411.70  5277.2  413.64  5375.9  417.63  5413.4  421.58
#Mann=6,-1,0
  4710.0    0.05       0  4827.8    0.16       0  4984.7    0.12       0
  4999.1    0.07       0  5005.1    0.12       0  5104.8    0.16       0
Bank Sta=4978,5021.7
Exp/Cntr=0.3,0.1

Type RM Length L Ch R = 1,4721,229,229,229
BEGIN DESCRIPTION:
UNT 063 IN DRY CR WATERSHED 12.0
END DESCRIPTION:
XS GIS Cut Line= 3
      2918975.00      6993424.97      2918975.00      6993725.00
      2919175.01      6993975.01
#Sta/Elev= 30
  4684.1  421.27  4714.1  421.29  4734.1  418.24  4764.1  414.65  4804.1  411.56
  4834.1  408.47  4877.9  405.39  4914.1  404.23  4944.1  404.28  4974.1  405.10
  4987.3  404.55  4991.3  401.39  4997.7  401.37  5005.7  403.17  5012.1  400.29
  5020.1  400.83  5023.5  400.23  5024.0  399.43  5029.0  399.43  5029.5  400.23
  5034.6  403.67  5055.8  405.39  5069.8  406.37  5098.6  407.19  5105.0  407.55
  5119.4  409.43  5140.2  410.13  5247.5  420.18  5299.2  424.03  5304.3  424.30
#Mann=4,-1,0
  4684.1    0.05       0  5023.5    0.03       0  5029.5    0.05       0
  5299.2    0.08       0
Bank Sta=4877.9,5055.8
Exp/Cntr=0.3,0.1

Type RM Length L Ch R = 1,4492,63,63,63
BEGIN DESCRIPTION:
Mapping XS 873036f4
END DESCRIPTION:
XS GIS Cut Line= 3
      2918442.77      6993526.04      2918776.96      6993745.22
      2919087.31      6993923.18
#Sta/Elev= 30
  4624.4  417.16  4693.6  413.21  4694.8  413.30  4698.7  413.61  4704.7  409.98
  4740.8  409.72  4792.1  407.14  4798.1  405.75  4811.4  406.78  4834.3  405.68
  4849.4  406.73  4870.4  404.62  4878.6  405.73  4914.1  403.65  4999.0  403.09
  5015.1  402.15  5016.9  400.52  5017.4  399.72  5022.9  400.52  5030.6  400.62
  5036.4  403.04  5044.0  403.81  5067.9  404.17  5111.2  403.09  5116.9  404.62
  5269.4  410.74  5272.9  410.83  5299.6  412.88  5331.2  413.01  5381.8  417.11
#Mann=11,-1,0
  4624.4    0.16       0  4693.6    0.05       0  4694.8    0.08       0
  4811.4    0.05       0  4878.6    0.08       0  5016.9    0.07       0
  5022.9    0.08       0  5044.0     0.1       0  5067.9    0.08       0
  5269.4    0.05       0  5272.9    0.08       0
Bank Sta=4999,5111.2
Exp/Cntr=0.3,0.1

Type RM Length L Ch R = 1,4429,307,307,307
BEGIN DESCRIPTION:
Mapping XS af6646a4
END DESCRIPTION:
XS GIS Cut Line= 3
      2918392.84      6993599.81      2918711.85      6993762.58
      2919009.16      6993983.93
#Sta/Elev= 30
  4656.1  411.52  4775.9  404.88  4793.4  404.33  4831.8  402.80  4885.8  401.68
  4988.1  402.26  4995.3  401.77  5004.8  399.05  5007.4  397.08  5007.9  396.28
  5013.4  397.08  5017.8  397.59  5025.5  398.13  5031.8  401.80  5062.0  402.80
  5075.6  404.70  5115.1  405.48  5161.1  408.05  5175.7  406.63  5186.9  407.38
  5211.1  409.44  5225.7  409.07  5267.5  414.23  5311.2  415.23  5317.5  416.73
  5325.8  415.45  5332.1  417.07  5340.5  415.76  5354.8  416.07  5384.9  419.26
#Mann=9,-1,0
  4656.1    0.05       0  4775.9    0.08       0  4793.4    0.12       0
  4885.8    0.08       0  5007.4    0.07       0  5013.4    0.08       0
  5017.8    0.05       0  5115.1    0.08       0  5186.9    0.05       0
Bank Sta=4831.8,5062
Exp/Cntr=0.3,0.1

Type RM Length L Ch R = 1,4122,143,143,143
BEGIN DESCRIPTION:
Mapping XS 3322ead0
END DESCRIPTION:
XS GIS Cut Line= 3
      2918349.45      6993586.82      2918401.52      6993819.00
      2918851.48      6993998.55
#Sta/Elev= 30
  4780.8  409.88  4809.7  409.83  4854.5  406.52  4930.1  400.88  4983.9  400.64
  4994.2  395.30  5001.4  393.60  5001.9  392.80  5006.9  392.80  5007.4  393.60
  5010.7  399.55  5015.3  400.89  5024.7  402.38  5039.9  402.17  5048.9  403.80
  5102.8  402.00  5132.5  403.76  5194.8  404.30  5252.4  406.56  5294.2  407.40
  5334.7  410.93  5366.9  411.01  5372.3  412.49  5388.6  411.43  5401.9  413.83
  5455.8  417.57  5463.9  417.28  5474.7  415.17  5485.5  417.72  5503.2  418.07
#Mann=6,-1,0
  4780.8    0.05       0  4854.5    0.12       0  5001.4    0.07       0
  5007.4    0.12       0  5039.9    0.07       0  5252.4    0.05       0
Bank Sta=4930.1,5015.3
Exp/Cntr=0.3,0.1

Type RM Length L Ch R = 1,3979,306,306,306
BEGIN DESCRIPTION:
UNT 063 IN DRY CR WATERSHED 10.0
END DESCRIPTION:
XS GIS Cut Line= 3
      2917925.00      6993625.00      2918275.00      6993825.00
      2918424.99      6994124.97
#Sta/Elev= 30
  4619.0  420.77  4668.3  417.60  4713.3  413.17  4745.0  407.96  4809.8  403.21
  4853.0  401.55  4941.5  401.28  4950.8  399.98  4955.2  397.28  4964.5  395.72
  4971.0  400.55  4986.8  400.39  4992.6  398.87  4999.1  393.36  5005.4  393.24
  5005.9  392.44  5011.4  393.24  5014.2  398.18  5026.3  399.98  5075.1  400.93
  5097.6  401.32  5119.9  404.79  5142.3  405.14  5163.7  407.66  5209.4  411.43
  5215.0  410.67  5231.7  412.19  5237.3  411.27  5274.4  413.27  5357.5  415.36
#Mann=7,-1,0
  4619.0    0.08       0  4668.3    0.12       0  5005.4    0.07       0
  5011.4    0.12       0  5075.1    0.07       0  5163.7    0.12       0
  5274.4    0.05       0
Bank Sta=4950.8,5026.3
Exp/Cntr=0.3,0.1

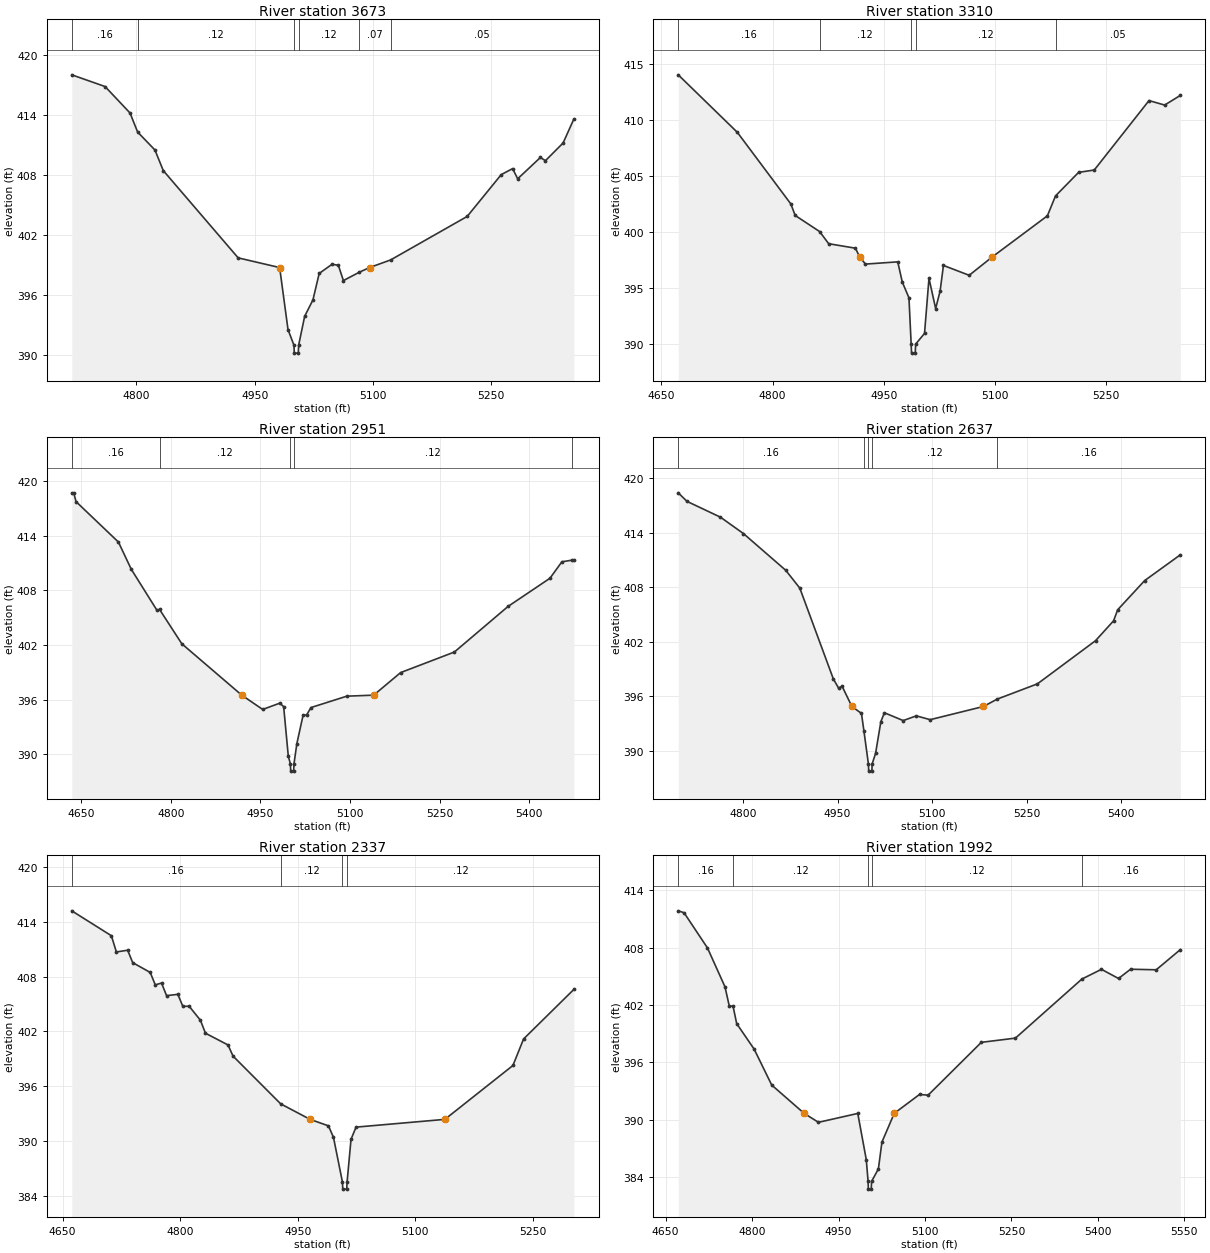
Type RM Length L Ch R = 1,3673,363,363,363
BEGIN DESCRIPTION:
UNT 063 IN DRY CR WATERSHED 9.0
END DESCRIPTION:
XS GIS Cut Line= 3
      2917924.99      6993724.96      2918025.00      6994025.00
      2918274.98      6994224.99
#Sta/Elev= 30
  4718.2  418.04  4760.4  416.87  4792.0  414.23  4801.7  412.32  4823.6  410.53
  4834.2  408.47  4929.1  399.75  4981.7  398.78  4992.3  392.58  4999.8  391.03
  5000.3  390.23  5005.3  390.23  5005.8  391.03  5013.4  393.91  5023.9  395.55
  5031.8  398.19  5048.1  399.11  5056.1  399.01  5062.5  397.48  5082.8  398.32
  5095.6  398.78  5122.3  399.54  5219.4  403.89  5262.6  408.07  5277.0  408.67
  5283.4  407.65  5312.2  409.78  5318.6  409.46  5341.0  411.23  5354.6  413.62
#Mann=6,-1,0
  4718.2    0.16       0  4801.7    0.12       0  4999.8    0.07       0
  5005.8    0.12       0  5082.8    0.07       0  5122.3    0.05       0
Bank Sta=4981.7,5095.6
Exp/Cntr=0.3,0.1

Type RM Length L Ch R = 1,3310,359,359,359
BEGIN DESCRIPTION:
UNT 063 IN DRY CR WATERSHED 8.0
END DESCRIPTION:
XS GIS Cut Line= 3
      2917625.00      6993975.01      2917825.00      6994275.00
      2918125.02      6994375.01
#Sta/Elev= 30
  4672.9  414.06  4752.5  408.93  4824.6  402.54  4830.6  401.50  4863.4  400.07
  4875.7  398.98  4911.8  398.58  4917.4  397.80  4925.3  397.16  4968.8  397.36
  4974.9  395.56  4983.9  394.15  4986.9  390.01  4987.4  389.21  4992.4  389.21
  4992.9  390.01  5004.9  390.97  5010.9  395.89  5019.9  393.19  5025.9  394.75
  5030.4  397.04  5065.1  396.16  5096.2  397.80  5170.5  401.47  5181.5  403.25
  5212.6  405.35  5233.7  405.56  5307.5  411.76  5328.6  411.36  5349.7  412.22
#Mann=5,-1,0
  4672.9    0.16       0  4863.4    0.12       0  4986.9    0.07       0
  4992.9    0.12       0  5181.5    0.05       0
Bank Sta=4917.4,5096.2
Exp/Cntr=0.3,0.1

Type RM Length L Ch R = 1,2951,314,314,314
BEGIN DESCRIPTION:
UNT 063 IN DRY CR WATERSHED 7.0
END DESCRIPTION:
XS GIS Cut Line= 3
      2917325.00      6994275.00      2917625.00      6994525.00
      2918074.99      6994525.00
#Sta/Elev= 30
  4634.3  418.72  4637.5  418.72  4641.5  417.75  4712.4  413.31  4733.9  410.32
  4776.8  405.82  4781.3  405.90  4818.5  402.13  4918.9  396.48  4953.9  394.91
  4982.5  395.60  4989.0  395.22  4996.8  389.76  5000.3  388.93  5000.8  388.13
  5005.8  388.13  5006.3  388.93  5011.1  391.15  5021.6  394.29  5027.3  394.29
  5034.8  395.12  5094.8  396.37  5139.7  396.48  5184.8  398.96  5274.8  401.22
  5364.8  406.24  5434.8  409.33  5454.8  411.14  5472.0  411.32  5474.8  411.32
#Mann=5,-1,0
  4634.3    0.16       0  4781.3    0.12       0  5000.3    0.07       0
  5006.3    0.12       0  5472.0    0.05       0
Bank Sta=4918.9,5139.7
Exp/Cntr=0.3,0.1

Type RM Length L Ch R = 1,2637,300,300,300
BEGIN DESCRIPTION:
UNT 063 IN DRY CR WATERSHED 6.0
END DESCRIPTION:
XS GIS Cut Line= 3
      2917225.02      6994425.04      2917375.00      6994725.00
      2917674.97      6995074.97
#Sta/Elev= 30
  4697.3  418.39  4711.2  417.45  4764.3  415.71  4800.7  413.91  4867.8  409.87
  4890.1  407.91  4943.2  397.94  4951.6  396.91  4957.2  397.12  4972.7  394.89
  4987.9  394.13  4991.8  392.20  4998.9  388.58  4999.4  387.78  5004.4  387.78
  5004.9  388.58  5010.3  389.74  5018.7  393.23  5024.3  394.20  5054.1  393.34
  5074.9  393.86  5096.9  393.44  5181.3  394.89  5203.2  395.70  5267.0  397.38
  5359.2  402.13  5387.7  404.31  5394.3  405.53  5437.1  408.74  5493.6  411.57
#Mann=5,-1,0
  4697.3    0.16       0  4991.8    0.12       0  4998.9    0.07       0
  5004.9    0.12       0  5203.2    0.16       0
Bank Sta=4972.7,5181.3
Exp/Cntr=0.3,0.1

Type RM Length L Ch R = 1,2337,345,345,345
BEGIN DESCRIPTION:
UNT 063 IN DRY CR WATERSHED 5.0
END DESCRIPTION:
XS GIS Cut Line= 3
      2916924.97      6994624.96      2917125.00      6994875.00
      2917325.03      6995125.03
#Sta/Elev= 30
  4661.7  415.22  4712.2  412.49  4718.6  410.71  4733.0  410.90  4739.4  409.54
  4761.8  408.46  4768.2  407.10  4776.2  407.30  4782.6  405.92  4797.0  406.06
  4803.4  404.74  4811.4  404.76  4825.8  403.22  4832.2  401.80  4861.0  400.51
  4867.4  399.29  4928.2  394.05  4965.7  392.35  4989.1  391.64  4995.5  390.38
  5006.9  385.50  5007.4  384.70  5012.4  384.70  5012.9  385.50  5017.9  390.17
  5024.3  391.50  5137.6  392.35  5224.4  398.26  5238.0  401.17  5302.1  406.60
#Mann=4,-1,0
  4661.7    0.16       0  4928.2    0.12       0  5006.9    0.07       0
  5012.9    0.12       0
Bank Sta=4965.7,5137.6
Exp/Cntr=0.3,0.1

Type RM Length L Ch R = 1,1992,435,435,435
BEGIN DESCRIPTION:
UNT 063 IN DRY CR WATERSHED 4.0
END DESCRIPTION:
XS GIS Cut Line= 3
      2916925.00      6994775.03      2916875.00      6995075.00
      2917339.25      6995400.50
#Sta/Elev= 30
  4671.9  411.86  4682.0  411.66  4722.6  407.98  4753.0  403.91  4760.6  401.86
  4766.9  401.91  4773.3  400.06  4803.7  397.38  4834.1  393.63  4890.3  390.67
  4915.2  389.73  4983.4  390.66  4998.2  385.81  5001.3  383.54  5001.8  382.74
  5006.8  382.74  5007.3  383.54  5019.2  384.86  5025.3  387.66  5046.7  390.67
  5090.6  392.65  5105.4  392.57  5197.8  398.10  5256.9  398.54  5372.2  404.72
  5406.2  405.74  5435.8  404.78  5456.7  405.75  5501.2  405.69  5543.0  407.80
#Mann=5,-1,0
  4671.9    0.16       0  4766.9    0.12       0  5001.3    0.07       0
  5007.3    0.12       0  5372.2    0.16       0
Bank Sta=4890.3,5046.7
Exp/Cntr=0.3,0.1

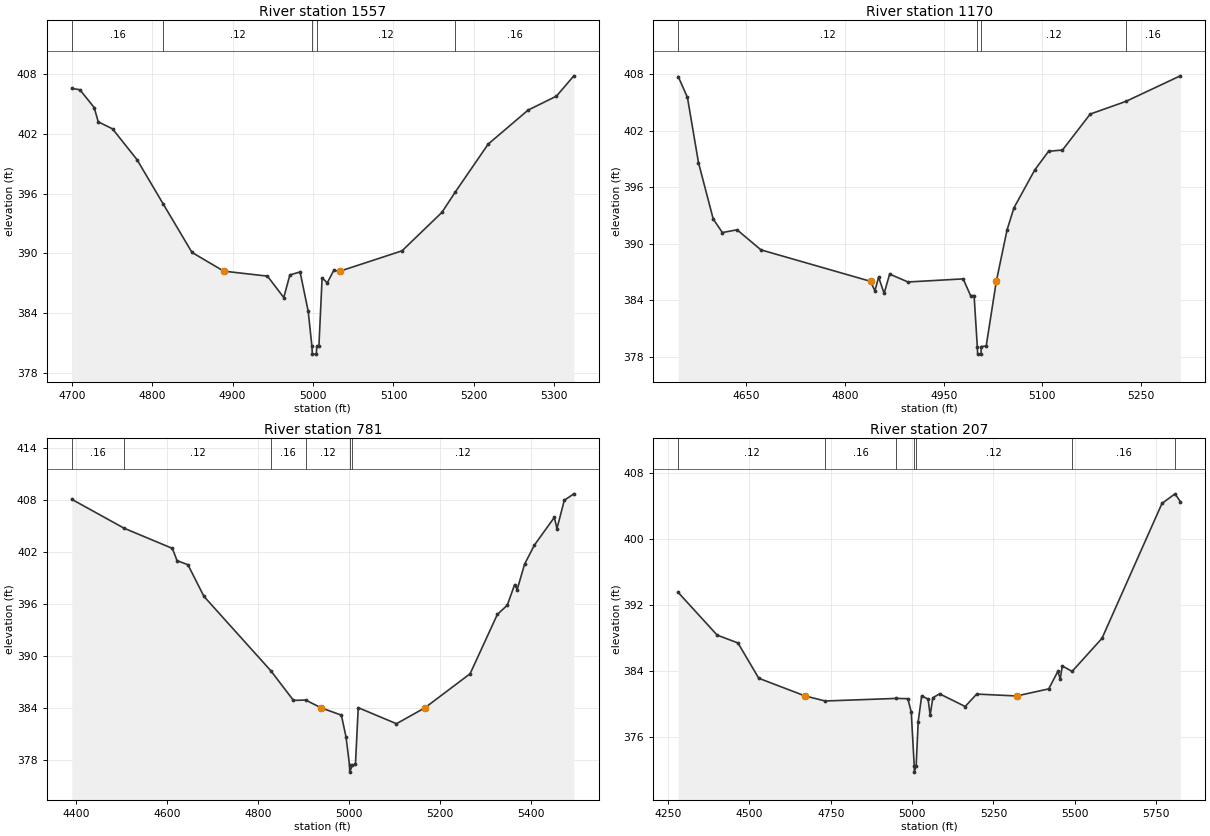
Type RM Length L Ch R = 1,1557,387,387,387
BEGIN DESCRIPTION:
UNT 063 IN DRY CR WATERSHED 3.0
END DESCRIPTION:
XS GIS Cut Line= 3
      2916525.00      6994775.00      2916475.00      6995075.00
      2916675.00      6995325.01
#Sta/Elev= 30
  4700.0  406.57  4710.1  406.43  4727.9  404.64  4732.9  403.21  4750.7  402.50
  4781.1  399.41  4814.0  394.91  4849.5  390.08  4889.0  388.20  4943.3  387.70
  4963.6  385.55  4971.2  387.82  4983.9  388.12  4994.0  384.16  4998.6  380.66
  4999.1  379.86  5004.1  379.86  5004.6  380.66  5007.3  380.66  5011.3  387.53
  5017.7  387.02  5025.7  388.27  5033.5  388.20  5110.6  390.24  5160.2  394.10
  5177.1  396.18  5217.8  400.97  5267.5  404.39  5302.7  405.79  5324.3  407.83
#Mann=5,-1,0
  4700.0    0.16       0  4814.0    0.12       0  4998.6    0.07       0
  5004.6    0.12       0  5177.1    0.16       0
Bank Sta=4889,5033.5
Exp/Cntr=0.3,0.1

Type RM Length L Ch R = 1,1170,389,389,389
BEGIN DESCRIPTION:
UNT 063 IN DRY CR WATERSHED 2.0
END DESCRIPTION:
XS GIS Cut Line= 3
      2916325.02      6994724.96      2916125.00      6995125.00
      2916225.00      6995425.01
#Sta/Elev= 30
  4546.3  407.74  4560.3  405.52  4577.1  398.60  4599.5  392.62  4613.4  391.18
  4635.8  391.47  4672.1  389.34  4838.7  386.00  4845.4  384.99  4851.0  386.44
  4859.4  384.72  4867.8  386.77  4895.7  385.93  4979.6  386.26  4990.8  384.49
  4996.2  384.49  5001.1  379.07  5001.6  378.27  5006.6  378.27  5007.1  379.07
  5014.6  379.13  5030.0  386.00  5046.3  391.45  5056.8  393.80  5088.4  397.82
  5109.5  399.81  5130.6  399.94  5172.8  403.76  5226.9  405.10  5309.8  407.82
#Mann=4,-1,0
  4546.3    0.12       0  5001.1    0.07       0  5007.1    0.12       0
  5226.9    0.16       0
Bank Sta=4838.7,5030
Exp/Cntr=0.3,0.1

Type RM Length L Ch R = 1,781,574,574,574
BEGIN DESCRIPTION:
Mapping XS 21377d7d
END DESCRIPTION:
XS GIS Cut Line= 3
      2915944.18      6994560.72      2915784.45      6995171.87
      2916010.07      6995588.41
#Sta/Elev= 30
  4389.9  408.06  4505.3  404.72  4611.4  402.40  4621.7  400.99  4645.6  400.52
  4680.9  396.87  4827.9  388.31  4878.0  384.88  4904.9  384.92  4938.8  384.02
  4983.5  383.18  4993.8  380.64  5001.4  377.41  5001.9  376.61  5007.5  377.41
  5014.5  377.54  5020.6  384.04  5104.8  382.19  5167.2  384.02  5266.9  387.95
  5326.9  394.79  5348.7  395.85  5364.9  398.22  5370.6  397.66  5386.8  400.58
  5408.6  402.79  5452.4  405.98  5458.1  404.68  5474.3  407.95  5495.3  408.69
#Mann=6,-1,0
  4389.9    0.16       0  4505.3    0.12       0  4827.9    0.16       0
  4904.9    0.12       0  5001.4    0.07       0  5007.5    0.12       0
Bank Sta=4938.8,5167.2
Exp/Cntr=0.3,0.1

Type RM Length L Ch R = 1,207,0,0,0
BEGIN DESCRIPTION:
UNT 063 IN DRY CR WATERSHED 1.0
END DESCRIPTION:
XS GIS Cut Line= 3
      2915558.76      6994442.66      2915300.00      6995150.00
      2915786.89      6995771.25
#Sta/Elev= 30
  4281.6  393.51  4401.2  388.33  4465.1  387.38  4529.0  383.09  4671.4  380.94
  4733.1  380.33  4949.3  380.64  4986.9  380.61  4997.5  378.99  5006.5  372.49
  5007.0  371.69  5012.6  372.49  5018.8  377.82  5029.5  380.95  5049.2  380.56
  5055.6  378.60  5063.7  380.72  5084.5  381.20  5163.2  379.66  5198.4  381.17
  5321.0  380.94  5419.9  381.80  5447.7  383.92  5455.2  383.02  5461.5  384.59
  5491.6  383.92  5583.5  387.94  5768.0  404.34  5808.0  405.49  5824.1  404.55
#Mann=7,-1,0
  4281.6    0.12       0  4733.1    0.16       0  4949.3    0.12       0
  5006.5    0.07       0  5012.6    0.12       0  5491.6    0.16       0
  5808.0    0.12       0
Bank Sta=4671.4,5321
Exp/Cntr=0.3,0.1

Chan Stop Cuts=-1