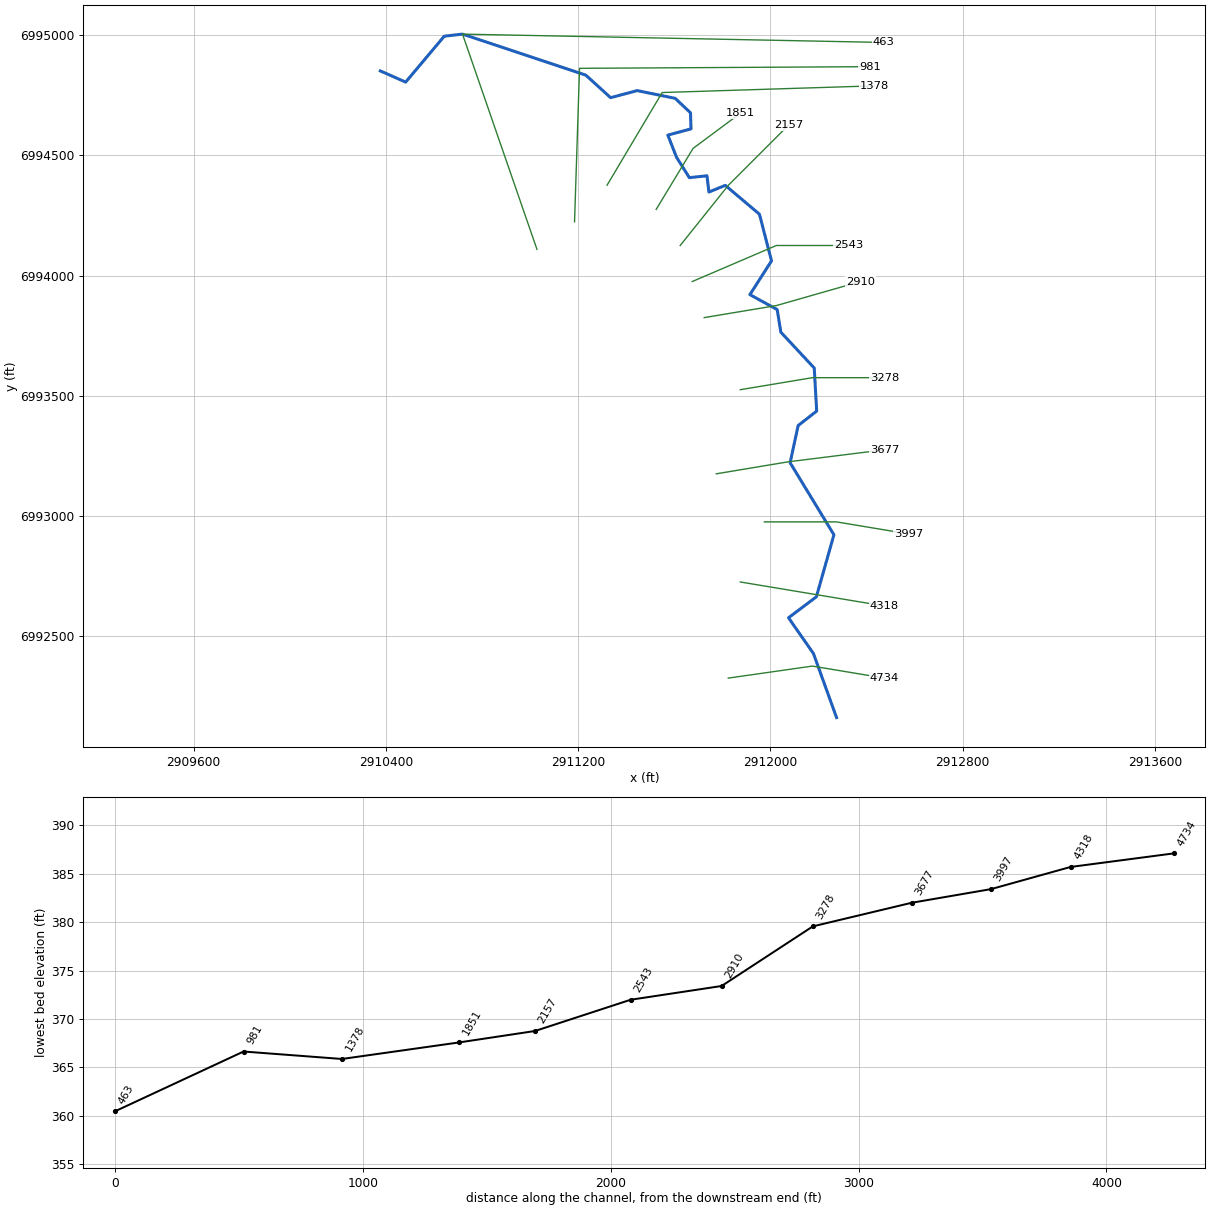
--- UNT 064 IN DRY CR WATERSHED.prj (project) ---

Proj Title=UNT 064 IN DRY CR WATERSHED Base Level Engineering
Current Plan=p01
Default Exp/Contr=0.3,0.1
English Units
Geom File=g01
Flow File=f01
Plan File=p01
BEGIN DESCRIPTION:
UNT 064 IN DRY CR WATERSHED
END DESCRIPTION:

--- UNT 064 IN DRY CR WATERSHED.p01 (plan) ---

Plan Title=Multiple Run
Short Identifier=Multiple
Geom File=g01
Flow File=f01
Subcritical Flow
K Sum by GR= 0
Std Step Tol= 0.01
Critical Tol= 0.01
Num of Std Step Trials= 20
Max Error Tol= 0.3
Flow Tol Ratio= 0.001
Split Flow NTrial= 30
Split Flow Tol= 0.02
Split Flow Ratio= 0.02
Log Output Level= 0
Friction Slope Method= 1
Unsteady Friction Slope Method= 2
Unsteady Bridges Friction Slope Method= 1
Parabolic Critical Depth
Global Vel Dist=  1 , 1 , 1
Global Log Level= 0
CheckData=True
Encroach Param= -1, 0, 0, 0
BEGIN DESCRIPTION:
Multiple Run
END DESCRIPTION:

--- UNT 064 IN DRY CR WATERSHED.f01 (steady flow) ---

Flow Title=Multiple
Number of Profiles=7
Profile Names=10-year,25-year,50-year,1pct_min,100-year,1pct_plu,500-year
River Rch & RM= UNT 064 IN DRY C,Reach-1,4734
     407     533     633     374     747    1490    1039
Boundary for River Rch & Prof#=UNT 064 IN DRY C,Reach-1,1
Up Type=0
Dn Type=3
Dn Slope=0.005
Boundary for River Rch & Prof#=UNT 064 IN DRY C,Reach-1,2
Up Type=0
Dn Type=3
Dn Slope=0.005
Boundary for River Rch & Prof#=UNT 064 IN DRY C,Reach-1,3
Up Type=0
Dn Type=3
Dn Slope=0.005
Boundary for River Rch & Prof#=UNT 064 IN DRY C,Reach-1,4
Up Type=0
Dn Type=3
Dn Slope=0.005
Boundary for River Rch & Prof#=UNT 064 IN DRY C,Reach-1,5
Up Type=0
Dn Type=3
Dn Slope=0.005
Boundary for River Rch & Prof#=UNT 064 IN DRY C,Reach-1,6
Up Type=0
Dn Type=3
Dn Slope=0.005
Boundary for River Rch & Prof#=UNT 064 IN DRY C,Reach-1,7
Up Type=0
Dn Type=3
Dn Slope=0.005

--- UNT 064 IN DRY CR WATERSHED.g01 (geometry) ---

Geom Title=Existing Conditions

River Reach=UNT 064 IN DRY C,Reach-1
Reach XY= 30
      2912275.59      6992160.71      2912179.26      6992427.51
      2912075.65      6992576.05      2912191.56      6992663.29
      2912264.62      6992921.35      2912082.34      6993221.13
      2912115.69      6993375.81      2912192.84      6993436.00
      2912182.68      6993615.21      2912043.78      6993764.22
      2912028.52      6993858.33      2911914.92      6993920.57
      2912004.97      6994061.07      2911954.73      6994255.16
      2911812.77      6994375.20      2911744.36      6994347.49
      2911736.40      6994414.99      2911662.91      6994407.33
      2911609.60      6994492.48      2911573.51      6994584.27
      2911670.01      6994610.23      2911667.86      6994677.11
      2911604.16      6994737.24      2911445.94      6994769.40
      2911335.48      6994740.01      2911232.22      6994833.77
      2910719.24      6995004.48      2910643.29      6994995.80
      2910482.70      6994804.83      2910377.23      6994851.48

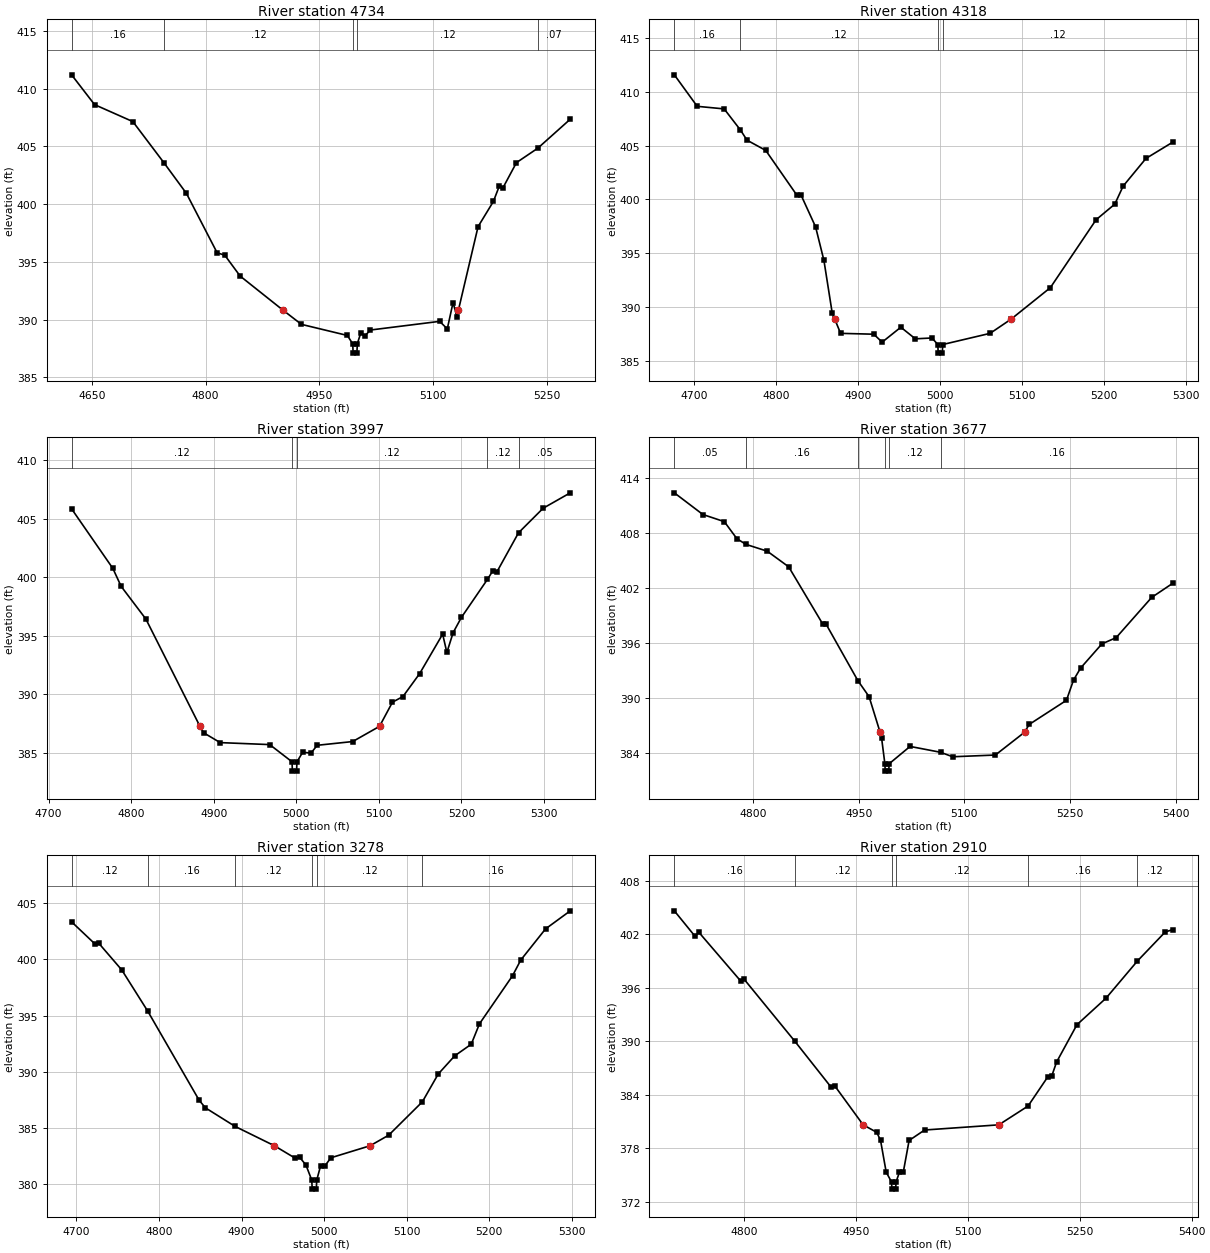
Type RM Length L Ch R = 1,4734,416,416,416
BEGIN DESCRIPTION:
UNT 064 IN DRY CR WATERSHED 10.0
END DESCRIPTION:
XS GIS Cut Line= 3
      2911824.98      6992325.00      2912175.00      6992375.00
      2912474.99      6992325.00
#Sta/Elev= 30
  4623.4  411.19  4653.7  408.61  4704.2  407.14  4745.5  403.55  4774.9  400.92
  4815.3  395.79  4825.5  395.57  4845.7  393.77  4902.0  390.83  4926.5  389.59
  4987.1  388.63  4994.2  387.90  4994.7  387.10  4999.7  387.10  5000.2  387.90
  5004.9  388.87  5009.9  388.57  5017.5  389.10  5108.8  389.85  5118.9  389.20
  5126.5  391.48  5131.6  390.24  5133.6  390.83  5159.5  398.05  5179.7  400.23
  5187.3  401.53  5192.4  401.42  5210.1  403.59  5238.3  404.84  5281.1  407.35
#Mann=5,-1,0
  4623.4    0.16       0  4745.5    0.12       0  4994.2    0.07       0
  5000.2    0.12       0  5238.3    0.07       0
Bank Sta=4902,5133.6
Exp/Cntr=0.3,0.1

Type RM Length L Ch R = 1,4318,321,321,321
BEGIN DESCRIPTION:
UNT 064 IN DRY CR WATERSHED 9.0
END DESCRIPTION:
XS GIS Cut Line= 3
      2911875.00      6992725.00      2912175.00      6992675.00
      2912475.02      6992625.00
#Sta/Elev= 30
  4675.8  411.59  4703.7  408.66  4736.6  408.42  4756.4  406.46  4764.5  405.51
  4787.3  404.56  4825.3  400.39  4830.4  400.40  4848.1  397.45  4858.3  394.32
  4868.4  389.43  4871.5  388.86  4878.6  387.54  4919.1  387.46  4929.3  386.72
  4952.1  388.11  4969.8  387.03  4990.1  387.11  4997.2  386.50  4997.7  385.70
  5002.7  385.70  5003.2  386.50  5061.0  387.54  5086.6  388.86  5134.5  391.79
  5190.3  398.11  5213.1  399.56  5223.3  401.24  5251.1  403.81  5284.1  405.34
#Mann=4,-1,0
  4675.8    0.16       0  4756.4    0.12       0  4997.2    0.07       0
  5003.2    0.12       0
Bank Sta=4871.5,5086.6
Exp/Cntr=0.3,0.1

Type RM Length L Ch R = 1,3997,320,320,320
BEGIN DESCRIPTION:
UNT 064 IN DRY CR WATERSHED 8.0
END DESCRIPTION:
XS GIS Cut Line= 3
      2911975.01      6992975.00      2912275.00      6992975.00
      2912574.97      6992925.00
#Sta/Elev= 30
  4727.8  405.85  4777.8  400.75  4787.8  399.22  4817.8  396.42  4883.3  387.24
  4887.8  386.69  4907.8  385.85  4967.8  385.68  4994.8  384.21  4995.3  383.41
  5000.3  383.41  5000.8  384.21  5007.8  385.03  5017.8  384.95  5025.3  385.62
  5068.3  385.94  5100.8  387.24  5116.5  389.31  5129.2  389.79  5149.4  391.75
  5177.3  395.13  5182.4  393.56  5190.0  395.26  5200.1  396.57  5231.6  399.82
  5238.2  400.56  5243.2  400.48  5269.2  403.80  5299.0  405.90  5331.9  407.22
#Mann=5,-1,0
  4727.8    0.12       0  4994.8    0.07       0  5000.8    0.12       0
  5231.6    0.12       0  5269.2    0.05       0
Bank Sta=4883.3,5100.8
Exp/Cntr=0.3,0.1

Type RM Length L Ch R = 1,3677,399,399,399
BEGIN DESCRIPTION:
UNT 064 IN DRY CR WATERSHED 7.0
END DESCRIPTION:
XS GIS Cut Line= 3
      2911775.02      6993175.00      2912075.00      6993225.00
      2912474.97      6993275.00
#Sta/Elev= 30
  4688.6  412.42  4729.1  410.05  4759.5  409.27  4777.3  407.41  4790.0  406.79
  4820.4  406.04  4850.8  404.33  4898.9  398.10  4904.0  398.04  4948.9  391.89
  4964.8  390.14  4980.4  386.25  4982.6  385.58  4987.2  382.80  4987.7  382.00
  4992.7  382.00  4993.2  382.80  5022.9  384.70  5066.1  384.06  5083.4  383.57
  5143.9  383.76  5185.3  386.25  5191.8  387.10  5244.7  389.74  5254.7  391.95
  5264.8  393.27  5295.0  395.91  5315.2  396.59  5365.6  400.99  5395.8  402.55
#Mann=6,-1,0
  4688.6    0.05       0  4790.0    0.16       0  4948.9    0.12       0
  4987.2    0.07       0  4993.2    0.12       0  5066.1    0.16       0
Bank Sta=4980.4,5185.3
Exp/Cntr=0.3,0.1

Type RM Length L Ch R = 1,3278,368,368,368
BEGIN DESCRIPTION:
UNT 064 IN DRY CR WATERSHED 6.0
END DESCRIPTION:
XS GIS Cut Line= 3
      2911874.99      6993525.00      2912175.00      6993575.00
      2912475.05      6993575.00
#Sta/Elev= 30
  4694.1  403.34  4722.0  401.40  4727.1  401.43  4754.9  399.06  4786.3  395.40
  4848.7  387.46  4856.3  386.79  4892.2  385.14  4939.8  383.42  4965.3  382.30
  4970.4  382.39  4978.0  381.71  4985.1  380.36  4985.6  379.56  4990.6  379.56
  4991.1  380.36  4995.7  381.61  5000.8  381.61  5008.3  382.35  5055.8  383.42
  5078.3  384.36  5119.1  387.33  5138.3  389.80  5158.3  391.42  5178.3  392.45
  5188.3  394.27  5228.3  398.54  5238.3  399.94  5268.3  402.71  5298.3  404.32
#Mann=6,-1,0
  4694.1    0.12       0  4786.3    0.16       0  4892.2    0.12       0
  4985.1    0.07       0  4991.1    0.12       0  5119.1    0.16       0
Bank Sta=4939.8,5055.8
Exp/Cntr=0.3,0.1

Type RM Length L Ch R = 1,2910,367,367,367
BEGIN DESCRIPTION:
UNT 064 IN DRY CR WATERSHED 5.0
END DESCRIPTION:
XS GIS Cut Line= 3
      2911724.95      6993824.99      2912025.00      6993875.00
      2912375.01      6993975.00
#Sta/Elev= 30
  4706.8  404.61  4734.7  401.74  4739.8  402.19  4795.6  396.75  4800.6  396.91
  4868.4  389.97  4917.2  384.80  4922.3  384.92  4959.8  380.61  4978.0  379.77
  4983.1  378.88  4990.7  375.30  4997.9  374.20  4998.4  373.40  5003.4  373.40
  5003.9  374.20  5008.5  375.31  5013.6  375.31  5021.4  378.86  5042.2  380.03
  5141.6  380.61  5180.8  382.72  5207.3  386.00  5212.5  386.08  5219.0  387.65
  5246.3  391.84  5285.3  394.82  5327.4  398.99  5364.6  402.24  5375.0  402.51
#Mann=6,-1,0
  4706.8    0.16       0  4868.4    0.12       0  4997.9    0.07       0
  5003.9    0.12       0  5180.8    0.16       0  5327.4    0.12       0
Bank Sta=4959.8,5141.6
Exp/Cntr=0.3,0.1

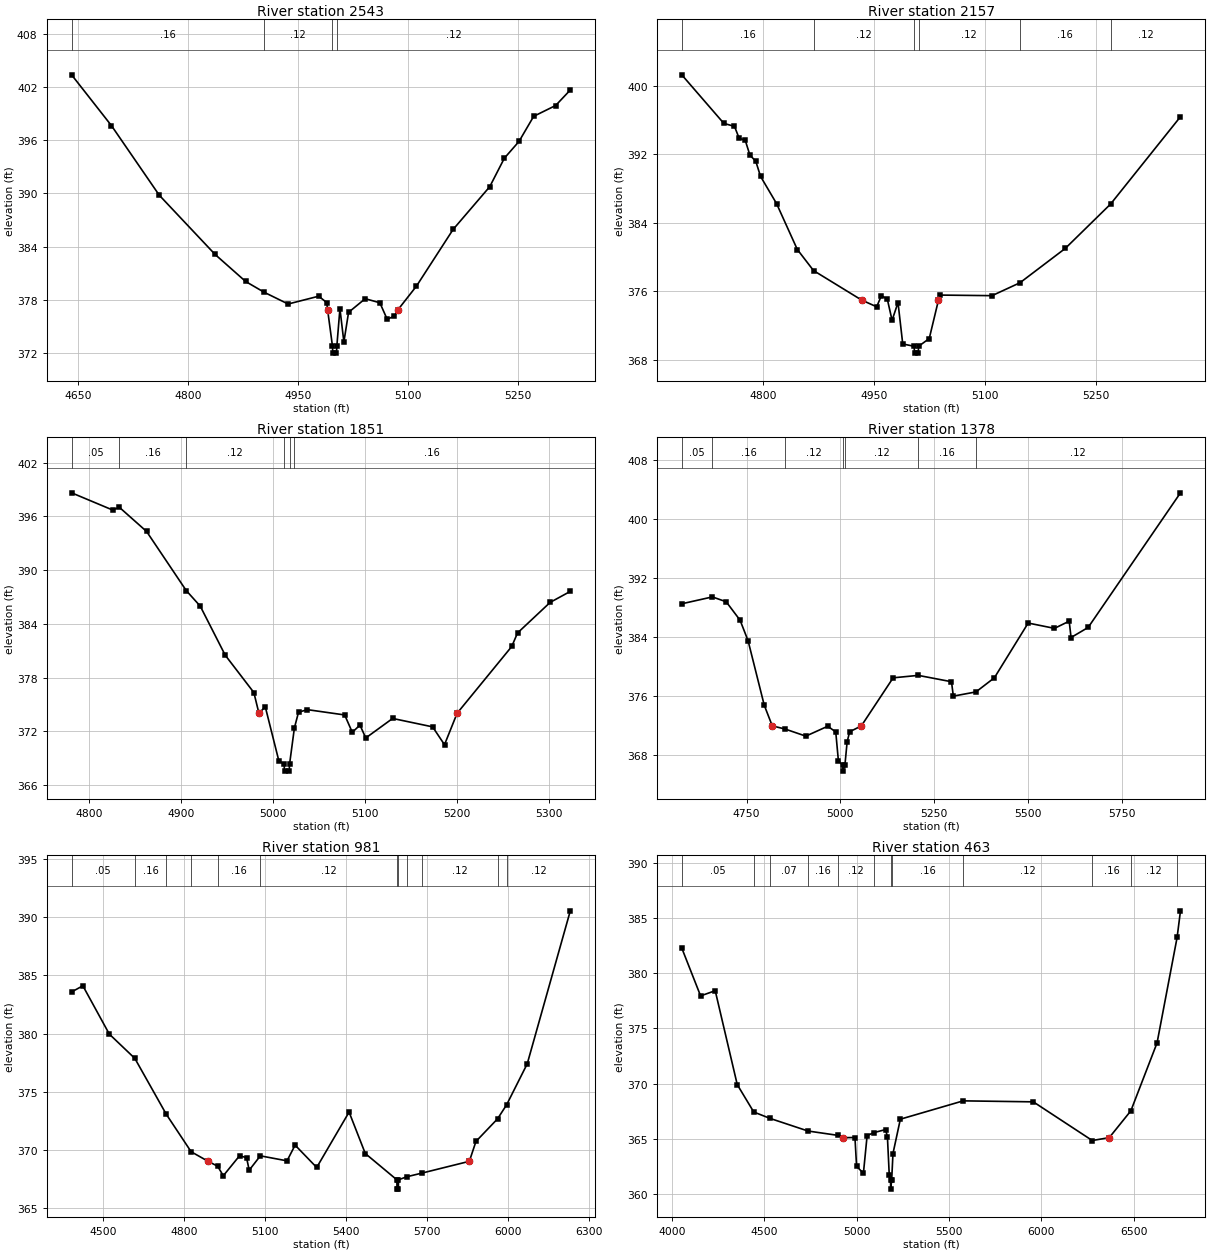
Type RM Length L Ch R = 1,2543,386,386,386
BEGIN DESCRIPTION:
UNT 064 IN DRY CR WATERSHED 4.0
END DESCRIPTION:
XS GIS Cut Line= 3
      2911674.98      6993974.99      2912025.00      6994125.00
      2912324.99      6994125.00
#Sta/Elev= 30
  4641.0  403.37  4695.4  397.64  4760.7  389.79  4836.9  383.11  4878.6  380.06
  4904.0  378.84  4936.6  377.52  4978.3  378.40  4989.2  377.69  4990.5  376.86
  4997.1  372.78  4997.6  371.98  5002.6  371.98  5003.1  372.78  5007.3  376.99
  5012.7  373.24  5019.1  376.58  5041.8  378.12  5061.8  377.66  5071.8  375.80
  5081.8  376.16  5086.4  376.86  5111.8  379.54  5161.8  385.93  5211.8  390.75
  5231.8  393.97  5251.8  395.86  5271.8  398.69  5301.8  399.91  5321.8  401.66
#Mann=4,-1,0
  4641.0    0.16       0  4904.0    0.12       0  4997.1    0.07       0
  5003.1    0.12       0
Bank Sta=4990.5,5086.4
Exp/Cntr=0.3,0.1

Type RM Length L Ch R = 1,2157,306,306,306
BEGIN DESCRIPTION:
UNT 064 IN DRY CR WATERSHED 3.0
END DESCRIPTION:
XS GIS Cut Line= 3
      2911625.01      6994125.01      2911825.00      6994375.00
      2912075.01      6994625.01
#Sta/Elev= 30
  4690.2  401.25  4747.0  395.58  4761.4  395.23  4767.8  393.82  4775.8  393.64
  4782.2  391.88  4790.2  391.15  4796.6  389.39  4818.2  386.22  4846.3  380.85
  4868.2  378.39  4933.1  374.95  4953.5  374.16  4959.9  375.47  4967.9  375.04
  4974.3  372.58  4982.3  374.66  4988.7  369.82  5004.1  369.55  5004.6  368.75
  5009.6  368.75  5010.1  369.55  5024.5  370.45  5037.0  374.95  5038.6  375.53
  5109.3  375.46  5147.1  376.97  5208.3  380.98  5269.5  386.16  5363.9  396.36
#Mann=6,-1,0
  4690.2    0.16       0  4868.2    0.12       0  5004.1    0.07       0
  5010.1    0.12       0  5147.1    0.16       0  5269.5    0.12       0
Bank Sta=4933.1,5037
Exp/Cntr=0.3,0.1

Type RM Length L Ch R = 1,1851,473,473,473
BEGIN DESCRIPTION:
UNT 064 IN DRY CR WATERSHED 2.0
END DESCRIPTION:
XS GIS Cut Line= 3
      2911525.02      6994275.02      2911678.40      6994528.82
      2911874.97      6994674.98
#Sta/Elev= 30
  4781.3  398.63  4825.9  396.71  4833.1  397.02  4862.7  394.32  4905.8  387.72
  4921.0  385.98  4948.1  380.51  4979.2  376.34  4984.7  374.03  4991.6  374.75
  5006.4  368.69  5012.0  368.37  5012.5  367.57  5017.5  367.57  5018.0  368.37
  5023.2  372.38  5027.7  374.15  5037.4  374.43  5077.8  373.84  5086.1  371.90
  5094.4  372.71  5100.7  371.27  5129.9  373.45  5173.3  372.51  5186.2  370.52
  5199.9  374.03  5259.2  381.48  5265.5  382.99  5300.9  386.40  5322.8  387.63
#Mann=6,-1,0
  4781.3    0.05       0  4833.1    0.16       0  4905.8    0.12       0
  5012.0    0.07       0  5018.0    0.12       0  5023.2    0.16       0
Bank Sta=4984.7,5199.9
Exp/Cntr=0.3,0.1

Type RM Length L Ch R = 1,1378,397,397,397
BEGIN DESCRIPTION:
Mapping XS 53d144f5
END DESCRIPTION:
XS GIS Cut Line= 3
      2911320.75      6994376.02      2911549.93      6994761.46
      2912430.97      6994789.20
#Sta/Elev= 30
  4577.3  388.53  4658.9  389.46  4695.8  388.80  4732.8  386.30  4754.2  383.51
  4797.2  374.79  4818.6  371.99  4852.9  371.56  4908.1  370.60  4966.5  371.94
  4987.9  371.17  4994.9  367.29  5006.3  366.66  5006.8  365.86  5012.3  366.66
  5018.2  369.80  5024.9  371.19  5056.2  371.99  5140.9  378.50  5208.0  378.83
  5296.5  377.97  5301.5  376.02  5361.8  376.59  5411.0  378.51  5501.0  385.92
  5571.1  385.20  5610.4  386.17  5615.4  383.96  5661.1  385.33  5907.2  403.56
#Mann=7,-1,0
  4577.3    0.05       0  4658.9    0.16       0  4852.9    0.12       0
  5006.3    0.07       0  5012.3    0.12       0  5208.0    0.16       0
  5361.8    0.12       0
Bank Sta=4818.6,5056.2
Exp/Cntr=0.3,0.1

Type RM Length L Ch R = 1,981,518,518,518
BEGIN DESCRIPTION:
Mapping XS 40d5d3a7
END DESCRIPTION:
XS GIS Cut Line= 3
      2911185.35      6994223.31      2911206.18      6994862.15
      2912414.48      6994869.09
#Sta/Elev= 30
  4383.6  383.57  4425.3  384.10  4523.3  379.95  4617.9  377.86  4734.4  373.06
  4826.5  369.84  4889.4  369.02  4924.5  368.60  4945.6  367.78  5005.6  369.49
  5031.6  369.34  5041.6  368.26  5082.8  369.49  5181.6  369.06  5211.6  370.41
  5291.6  368.49  5411.6  373.25  5471.6  369.69  5588.6  367.43  5589.1  366.63
  5594.1  366.63  5594.6  367.43  5624.8  367.69  5680.1  368.00  5857.1  369.02
  5881.6  370.73  5961.6  372.67  5995.3  373.88  6071.6  377.40  6231.1  390.54
#Mann=12,-1,0
  4383.6    0.05       0  4617.9    0.16       0  4734.4    0.12       0
  4826.5    0.07       0  4924.5    0.16       0  5082.8    0.12       0
  5588.6    0.07       0  5594.6    0.12       0  5624.8    0.16       0
  5680.1    0.12       0  5961.6    0.16       0  5995.3    0.12       0
Bank Sta=4889.4,5857.1
Exp/Cntr=0.3,0.1

Type RM Length L Ch R = 1,463,0,0,0
BEGIN DESCRIPTION:
UNT 064 IN DRY CR WATERSHED 1.0
END DESCRIPTION:
XS GIS Cut Line= 3
      2911029.11      6994108.66      2910719.24      6995004.48
      2912471.80      6994969.82
#Sta/Elev= 30
  4052.1  382.28  4154.0  377.95  4233.2  378.42  4352.5  369.92  4441.9  367.44
  4530.3  366.86  4735.7  365.72  4900.4  365.32  4926.9  365.12  4990.0  365.13
  4998.8  362.52  5035.8  361.90  5055.8  365.30  5091.2  365.57  5155.8  365.85
  5165.8  365.19  5175.8  361.71  5182.8  361.26  5183.3  360.46  5188.8  361.26
  5195.8  363.68  5235.8  366.79  5576.4  368.45  5955.9  368.36  6275.1  364.86
  6367.1  365.12  6484.2  367.55  6626.1  373.70  6734.6  383.24  6752.9  385.65
#Mann=12,-1,0
  4052.1    0.05       0  4441.9    0.16       0  4530.3    0.07       0
  4735.7    0.16       0  4900.4    0.12       0  5091.2    0.16       0
  5182.8    0.07       0  5188.8    0.16       0  5576.4    0.12       0
  6275.1    0.16       0  6484.2    0.12       0  6734.6    0.16       0
Bank Sta=4926.9,6367.1
Exp/Cntr=0.3,0.1

Chan Stop Cuts=-1