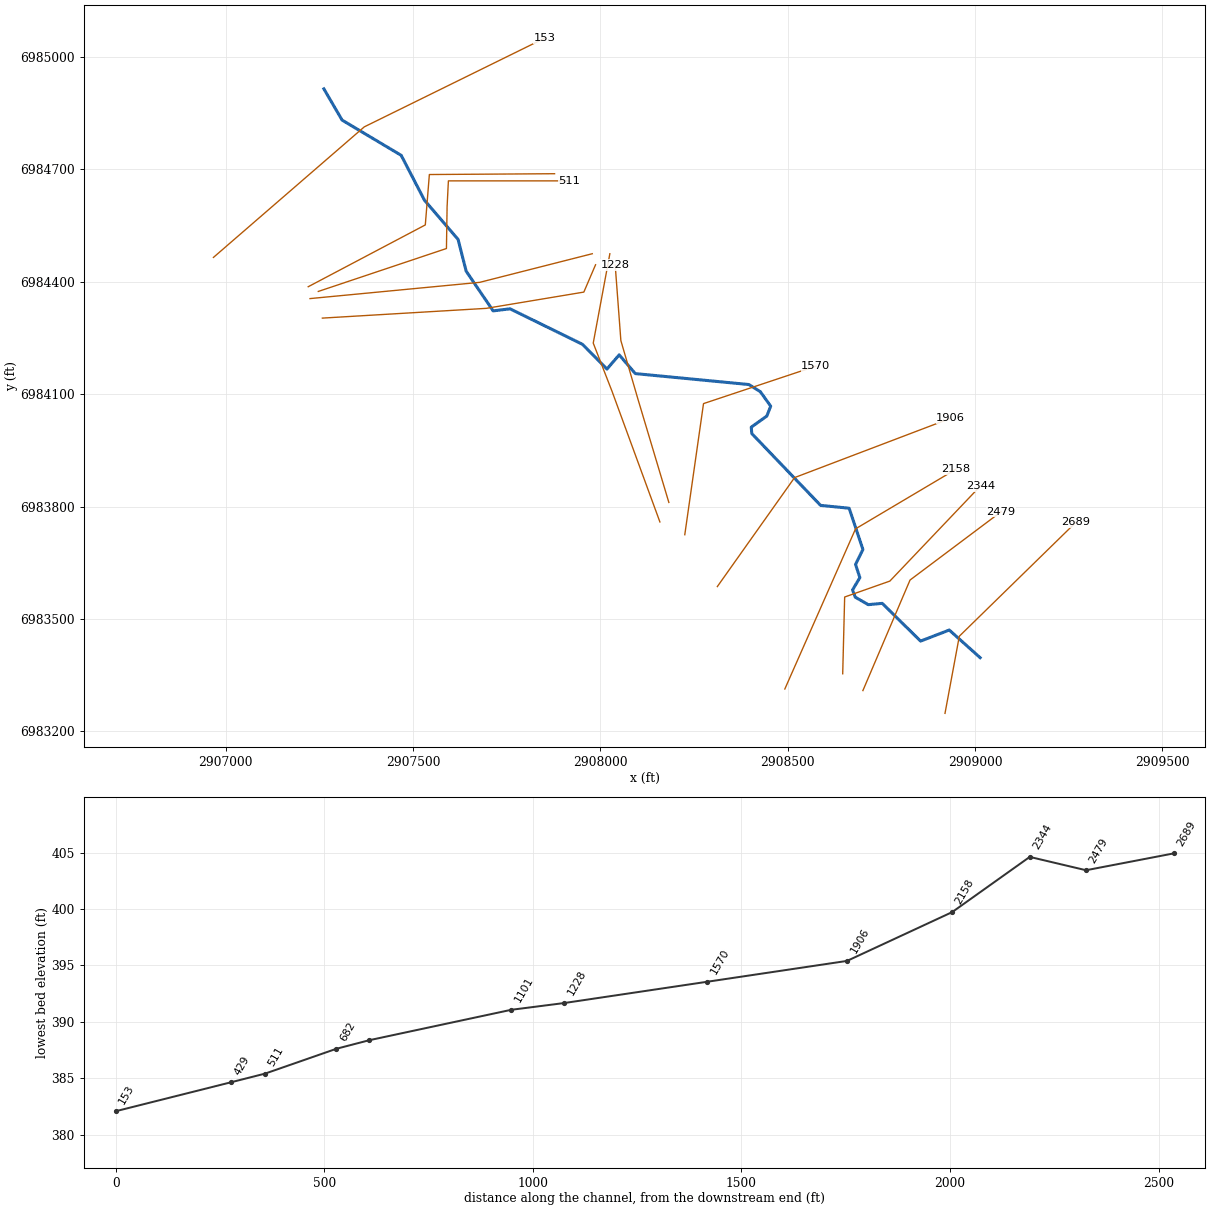
--- UNT 065 IN DRY CR WATERSHED.prj (project) ---

Proj Title=UNT 065 IN DRY CR WATERSHED Base Level Engineering
Current Plan=p01
Default Exp/Contr=0.3,0.1
English Units
Geom File=g01
Flow File=f01
Plan File=p01
BEGIN DESCRIPTION:
UNT 065 IN DRY CR WATERSHED
END DESCRIPTION:

--- UNT 065 IN DRY CR WATERSHED.p01 (plan) ---

Plan Title=Multiple Run
Short Identifier=Multiple
Geom File=g01
Flow File=f01
Subcritical Flow
K Sum by GR= 0
Std Step Tol= 0.01
Critical Tol= 0.01
Num of Std Step Trials= 20
Max Error Tol= 0.3
Flow Tol Ratio= 0.001
Split Flow NTrial= 30
Split Flow Tol= 0.02
Split Flow Ratio= 0.02
Log Output Level= 0
Friction Slope Method= 1
Unsteady Friction Slope Method= 2
Unsteady Bridges Friction Slope Method= 1
Parabolic Critical Depth
Global Vel Dist=  1 , 1 , 1
Global Log Level= 0
CheckData=True
Encroach Param= -1, 0, 0, 0
BEGIN DESCRIPTION:
Multiple Run
END DESCRIPTION:

--- UNT 065 IN DRY CR WATERSHED.f01 (steady flow) ---

Flow Title=Multiple
Number of Profiles=7
Profile Names=10-year,25-year,50-year,1pct_min,100-year,1pct_plu,500-year
River Rch & RM= UNT 065 IN DRY C,Reach-1,2689
     287     367     429     250     499     996     676
Boundary for River Rch & Prof#=UNT 065 IN DRY C,Reach-1,1
Up Type=0
Dn Type=3
Dn Slope=0.005
Boundary for River Rch & Prof#=UNT 065 IN DRY C,Reach-1,2
Up Type=0
Dn Type=3
Dn Slope=0.005
Boundary for River Rch & Prof#=UNT 065 IN DRY C,Reach-1,3
Up Type=0
Dn Type=3
Dn Slope=0.005
Boundary for River Rch & Prof#=UNT 065 IN DRY C,Reach-1,4
Up Type=0
Dn Type=3
Dn Slope=0.005
Boundary for River Rch & Prof#=UNT 065 IN DRY C,Reach-1,5
Up Type=0
Dn Type=3
Dn Slope=0.005
Boundary for River Rch & Prof#=UNT 065 IN DRY C,Reach-1,6
Up Type=0
Dn Type=3
Dn Slope=0.005
Boundary for River Rch & Prof#=UNT 065 IN DRY C,Reach-1,7
Up Type=0
Dn Type=3
Dn Slope=0.005

--- UNT 065 IN DRY CR WATERSHED.g01 (geometry) ---

Geom Title=Existing Conditions

River Reach=UNT 065 IN DRY C,Reach-1
Reach XY= 30
      2909013.39      6983396.83      2908930.92      6983470.61
      2908854.50      6983441.06      2908752.10      6983541.79
      2908714.78      6983538.32      2908680.05      6983558.28
      2908672.80      6983577.67      2908692.38      6983610.51
      2908680.81      6983645.71      2908700.52      6983685.62
      2908663.73      6983795.74      2908587.49      6983803.34
      2908403.81      6983995.08      2908402.43      6984012.15
      2908443.95      6984041.79      2908454.35      6984068.12
      2908426.75      6984106.66      2908396.02      6984125.93
      2908092.96      6984155.10      2908049.90      6984205.10
      2908017.27      6984167.25      2907951.99      6984233.22
      2907758.59      6984328.01      2907713.46      6984322.56
      2907641.48      6984428.43      2907619.85      6984513.25
      2907530.13      6984617.88      2907468.06      6984737.67
      2907310.23      6984831.79      2907261.62      6984915.12

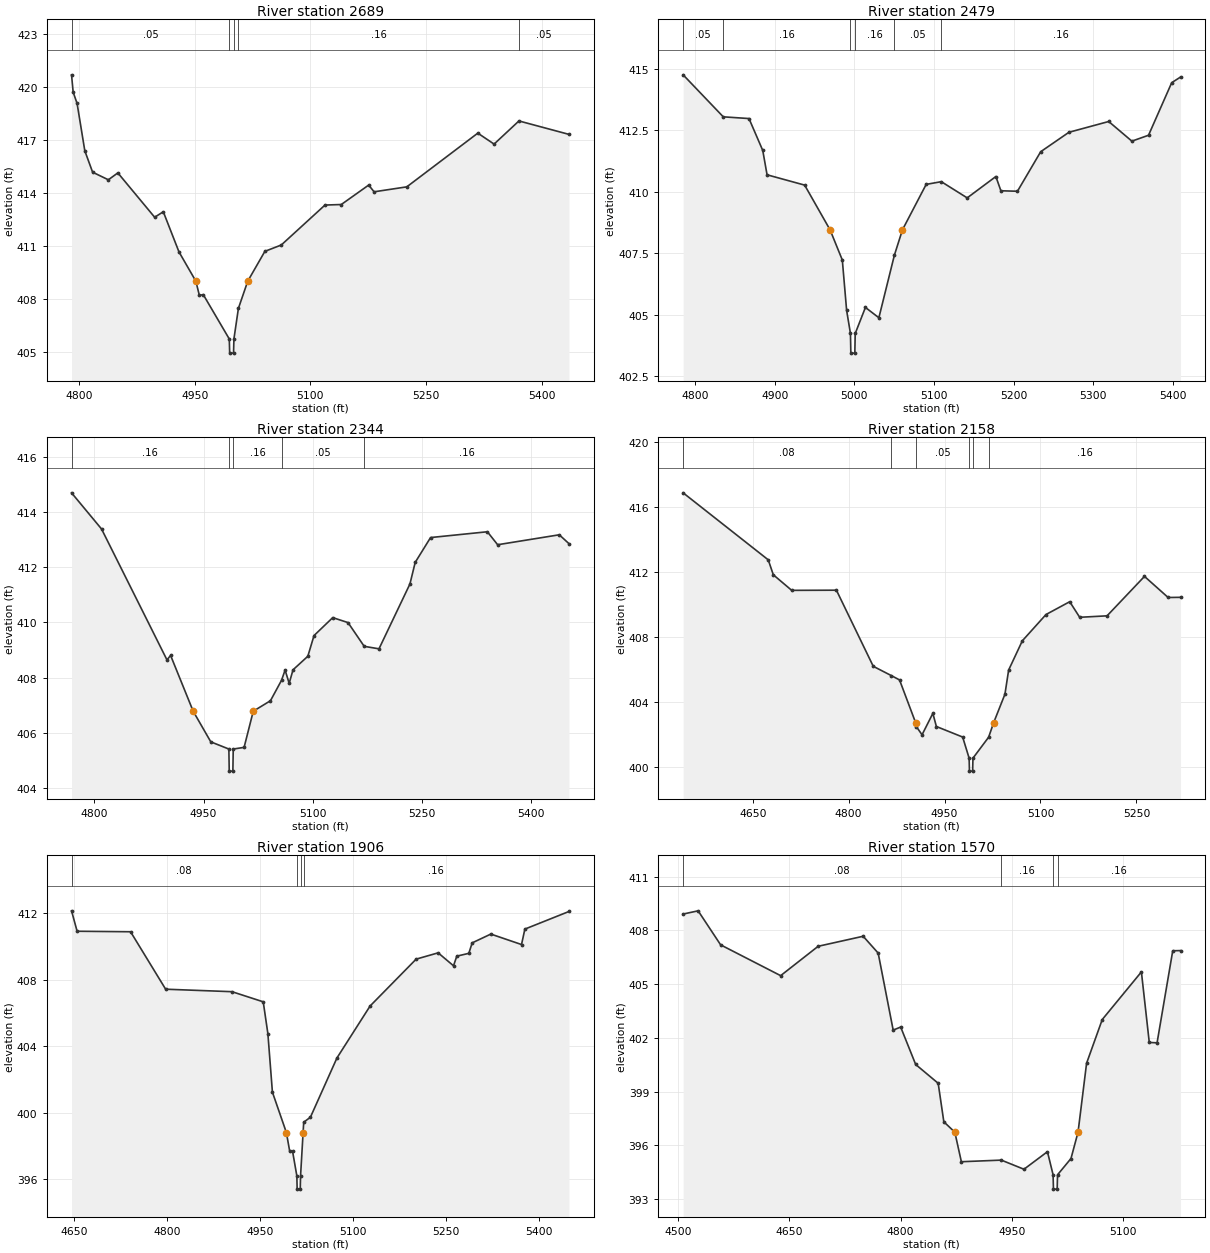
Type RM Length L Ch R = 1,2689,210,210,210
BEGIN DESCRIPTION:
UNT 065 IN DRY CR WATERSHED 5.0
END DESCRIPTION:
XS GIS Cut Line= 3
      2908919.58      6983248.14      2908957.83      6983454.12
      2909268.97      6983758.12
#Sta/Elev= 30
  4790.5  420.67  4792.6  419.69  4797.7  419.05  4807.7  416.37  4817.8  415.16
  4838.2  414.73  4850.5  415.12  4898.2  412.61  4909.4  412.92  4929.7  410.65
  4951.6  408.99  4956.1  408.19  4961.2  408.23  4994.9  405.72  4995.4  404.92
  5000.4  404.92  5000.9  405.72  5006.7  407.45  5018.8  408.99  5041.0  410.68
  5062.3  411.04  5118.9  413.30  5140.0  413.33  5175.5  414.43  5182.5  414.05
  5224.9  414.33  5316.9  417.37  5338.0  416.75  5370.2  418.06  5435.0  417.30
#Mann=5,-1,0
  4790.5    0.05       0  4994.9    0.04       0  5000.9    0.05       0
  5006.7    0.16       0  5370.2    0.05       0
Bank Sta=4951.6,5018.8
Exp/Cntr=0.3,0.1

Type RM Length L Ch R = 1,2479,135,135,135
BEGIN DESCRIPTION:
Mapping XS fd6b91fc
END DESCRIPTION:
XS GIS Cut Line= 3
      2908700.41      6983308.94      2908826.26      6983604.04
      2909069.29      6983786.31
#Sta/Elev= 30
  4785.0  414.76  4835.4  413.05  4867.7  412.98  4885.0  411.68  4890.4  410.69
  4937.6  410.27  4969.5  408.45  4984.9  407.22  4990.3  405.17  4995.1  404.23
  4995.6  403.43  5000.6  403.43  5001.1  404.23  5013.9  405.29  5030.8  404.87
  5050.3  407.42  5060.4  408.45  5090.2  410.30  5109.2  410.41  5141.7  409.75
  5177.7  410.62  5184.0  410.04  5204.8  410.02  5234.0  411.63  5269.4  412.42
  5319.4  412.86  5348.5  412.06  5369.4  412.30  5398.5  414.44  5409.6  414.67
#Mann=6,-1,0
  4785.0    0.05       0  4835.4    0.16       0  4995.1    0.07       0
  5001.1    0.16       0  5050.3    0.05       0  5109.2    0.16       0
Bank Sta=4969.5,5060.4
Exp/Cntr=0.3,0.1

Type RM Length L Ch R = 1,2344,186,186,186
BEGIN DESCRIPTION:
Mapping XS 187aa8e5
END DESCRIPTION:
XS GIS Cut Line= 4
      2908646.55      6983353.85      2908651.76      6983558.74
      2908772.42      6983601.27      2909013.76      6983854.77
#Sta/Elev= 30
  4768.7  414.69  4809.9  413.38  4899.7  408.64  4904.7  408.80  4935.7  406.78
  4959.9  405.67  4984.7  405.41  4985.2  404.61  4990.2  404.61  4990.7  405.41
  5005.6  405.47  5018.2  406.78  5041.8  407.16  5057.0  407.90  5061.9  408.27
  5067.5  407.79  5072.8  408.28  5093.1  408.77  5101.6  409.52  5127.3  410.17
  5148.3  409.99  5170.5  409.13  5190.8  409.04  5233.3  411.39  5240.5  412.17
  5261.6  413.07  5339.6  413.28  5353.7  412.81  5438.3  413.17  5451.6  412.85
#Mann=5,-1,0
  4768.7    0.16       0  4984.7    0.07       0  4990.7    0.16       0
  5057.0    0.05       0  5170.5    0.16       0
Bank Sta=4935.7,5018.2
Exp/Cntr=0.3,0.1

Type RM Length L Ch R = 1,2158,252,252,252
BEGIN DESCRIPTION:
Mapping XS fde988ac
END DESCRIPTION:
XS GIS Cut Line= 3
      2908492.05      6983313.21      2908680.86      6983740.76
      2908947.81      6983899.19
#Sta/Elev= 30
  4541.2  416.87  4674.3  412.74  4682.2  411.82  4711.0  410.86  4780.9  410.87
  4838.5  406.18  4866.6  405.61  4879.6  405.34  4904.7  402.71  4906.1  402.45
  4914.8  401.96  4931.7  403.28  4937.2  402.47  4978.3  401.82  4988.4  400.52
  4988.9  399.72  4993.9  399.72  4994.4  400.52  5018.9  401.81  5026.8  402.71
  5044.4  404.46  5050.2  405.95  5071.6  407.75  5108.6  409.37  5145.7  410.16
  5161.3  409.20  5204.1  409.29  5262.6  411.72  5299.6  410.42  5319.0  410.43
#Mann=6,-1,0
  4541.2    0.08       0  4866.6    0.16       0  4906.1    0.05       0
  4988.4    0.04       0  4994.4    0.05       0  5018.9    0.16       0
Bank Sta=4904.7,5026.8
Exp/Cntr=0.3,0.1

Type RM Length L Ch R = 1,1906,336,336,336
BEGIN DESCRIPTION:
Mapping XS fbf46784
END DESCRIPTION:
XS GIS Cut Line= 3
      2908311.91      6983586.64      2908518.10      6983877.48
      2908934.79      6984035.90
#Sta/Elev= 30
  4645.9  412.16  4654.9  410.93  4741.1  410.90  4797.7  407.44  4904.7  407.29
  4955.1  406.68  4962.6  404.76  4969.9  401.24  4992.4  398.81  4997.8  397.68
  5002.4  397.68  5009.3  396.20  5009.8  395.40  5014.8  395.40  5015.3  396.20
  5019.4  398.81  5020.4  399.43  5031.2  399.73  5074.0  403.30  5127.5  406.43
  5201.7  409.25  5237.2  409.63  5262.0  408.85  5267.3  409.43  5286.7  409.60
  5292.1  410.23  5322.2  410.76  5371.7  410.13  5377.1  411.06  5448.2  412.12
#Mann=4,-1,0
  4645.9    0.08       0  5009.3    0.07       0  5015.3    0.08       0
  5020.4    0.16       0
Bank Sta=4992.4,5019.4
Exp/Cntr=0.3,0.1

Type RM Length L Ch R = 1,1570,342,342,342
BEGIN DESCRIPTION:
UNT 065 IN DRY CR WATERSHED 4.0
END DESCRIPTION:
XS GIS Cut Line= 3
      2908225.01      6983725.04      2908275.00      6984075.00
      2908574.96      6984174.99
#Sta/Elev= 30
  4507.3  408.91  4527.5  409.09  4557.8  407.19  4638.6  405.47  4689.1  407.11
  4749.7  407.67  4769.9  406.73  4790.1  402.43  4800.2  402.60  4820.4  400.51
  4850.7  399.46  4858.3  397.31  4873.1  396.73  4881.9  395.08  4935.7  395.17
  4966.2  394.66  4997.8  395.64  5005.4  394.35  5005.9  393.55  5010.9  393.55
  5011.4  394.35  5029.5  395.26  5039.0  396.73  5050.5  400.58  5071.6  403.02
  5124.3  405.68  5134.9  401.74  5145.4  401.72  5166.5  406.86  5177.0  406.87
#Mann=4,-1,0
  4507.3    0.08       0  4935.7    0.16       0  5005.4    0.07       0
  5011.4    0.16       0
Bank Sta=4873.1,5039
Exp/Cntr=0.3,0.1

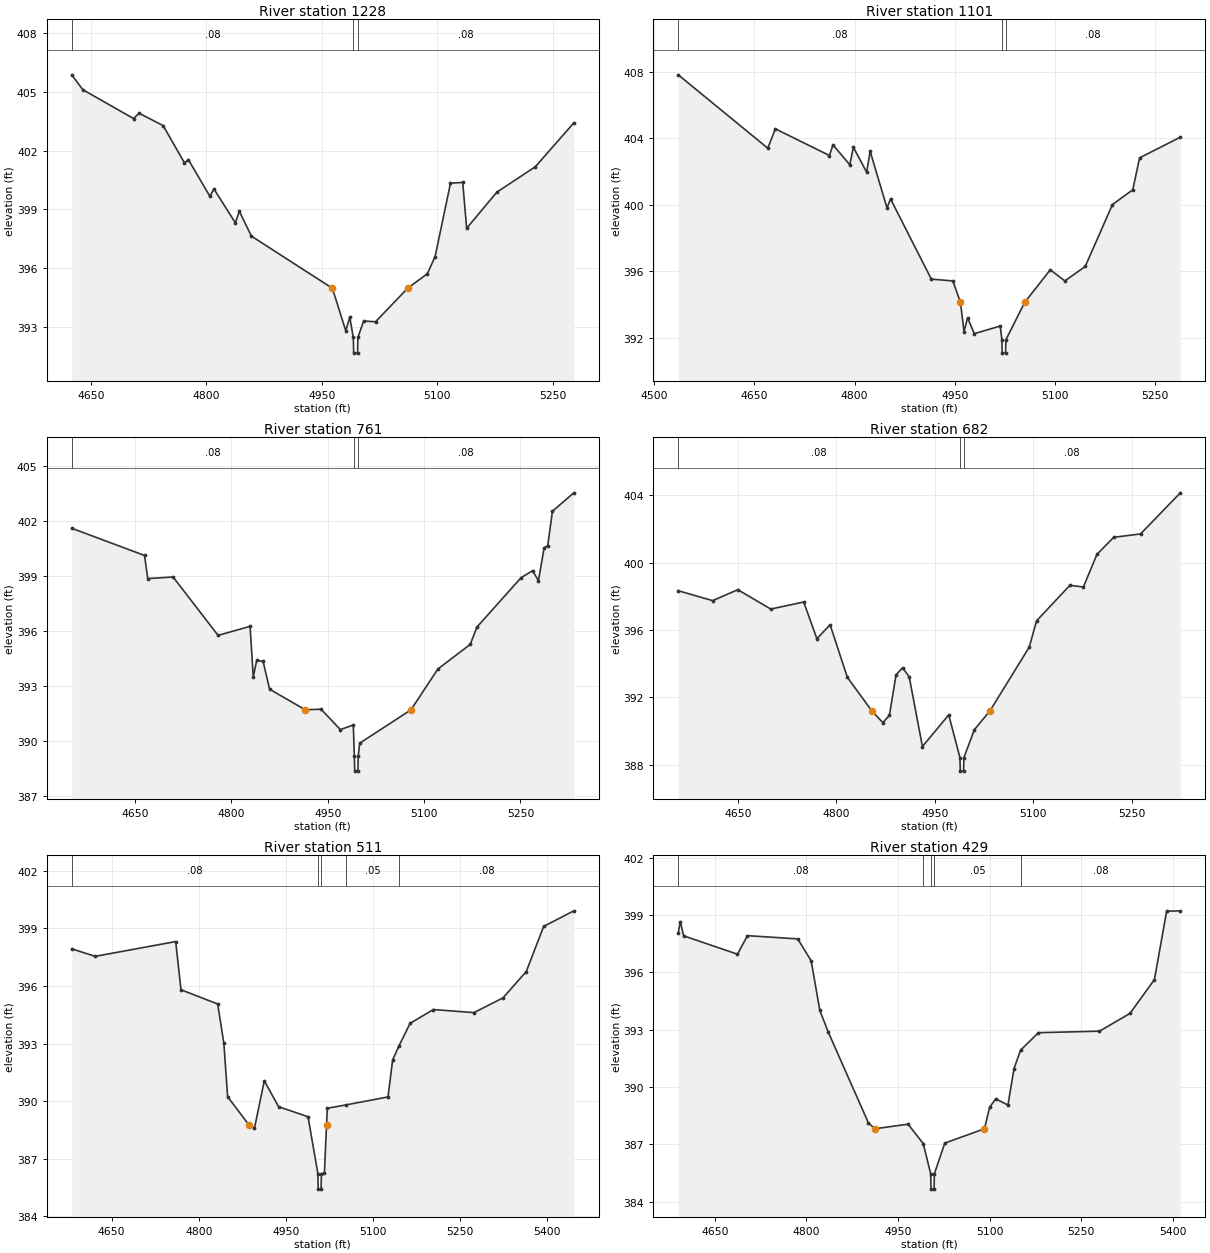
Type RM Length L Ch R = 1,1228,127,127,127
BEGIN DESCRIPTION:
Mapping XS 29f9ca6b
END DESCRIPTION:
XS GIS Cut Line= 4
      2908182.46      6983811.19      2908099.99      6984086.82
      2908054.42      6984243.07      2908039.22      6984444.94
#Sta/Elev= 30
  4624.8  405.87  4639.2  405.11  4705.1  403.64  4712.3  403.91  4743.6  403.28
  4771.3  401.38  4776.5  401.54  4804.4  399.67  4809.6  400.05  4837.5  398.32
  4842.7  398.91  4858.4  397.64  4963.7  394.98  4981.1  392.81  4986.3  393.50
  4990.9  392.47  4991.4  391.67  4996.4  391.67  4996.9  392.47  5004.4  393.31
  5019.8  393.27  5061.6  394.98  5087.2  395.72  5097.3  396.60  5117.3  400.34
  5133.2  400.38  5138.3  398.04  5177.5  399.88  5227.6  401.18  5277.7  403.42
#Mann=3,-1,0
  4624.8    0.08       0  4990.9    0.07       0  4996.9    0.08       0
Bank Sta=4963.7,5061.6
Exp/Cntr=0.3,0.1

Type RM Length L Ch R = 1,1101,340,340,340
BEGIN DESCRIPTION:
UNT 065 IN DRY CR WATERSHED 3.0
END DESCRIPTION:
XS GIS Cut Line= 4
      2908158.59      6983759.11      2908030.55      6984108.52
      2907980.63      6984236.56      2908025.00      6984475.00
#Sta/Elev= 30
  4535.9  407.80  4670.0  403.39  4681.5  404.55  4762.4  402.95  4767.7  403.59
  4792.9  402.39  4798.2  403.45  4818.1  401.95  4823.4  403.20  4848.6  399.80
  4853.9  400.34  4915.0  395.52  4947.2  395.41  4958.7  394.12  4964.0  392.36
  4969.3  393.20  4979.4  392.24  5018.3  392.70  5020.7  391.87  5021.2  391.07
  5026.2  391.07  5026.7  391.87  5054.9  394.12  5093.2  396.08  5115.1  395.41
  5145.6  396.28  5186.3  400.00  5216.8  400.89  5227.0  402.81  5288.0  404.05
#Mann=3,-1,0
  4535.9    0.08       0  5020.7    0.07       0  5026.7    0.08       0
Bank Sta=4958.7,5054.9
Exp/Cntr=0.3,0.1

Type RM Length L Ch R = 1,761,79,79,79
BEGIN DESCRIPTION:
Mapping XS 1f2b329a
END DESCRIPTION:
XS GIS Cut Line= 4
      2907257.59      6984303.23      2907695.13      6984329.27
      2907955.55      6984372.67      2907986.81      6984445.63
#Sta/Elev= 30
  4551.4  401.60  4664.7  400.12  4669.7  398.86  4709.1  398.95  4779.2  395.77
  4829.0  396.26  4834.0  393.50  4839.3  394.41  4849.3  394.35  4859.4  392.84
  4914.9  391.72  4939.5  391.75  4969.6  390.64  4989.7  390.89  4991.4  389.18
  4991.9  388.38  4996.9  388.38  4997.4  389.18  4999.7  389.90  5079.6  391.72
  5121.4  393.94  5171.8  395.28  5182.2  396.22  5250.9  398.91  5268.8  399.29
  5278.0  398.75  5286.9  400.54  5292.4  400.65  5299.8  402.53  5333.1  403.53
#Mann=3,-1,0
  4551.4    0.08       0  4991.4    0.07       0  4997.4    0.08       0
Bank Sta=4914.9,5079.6
Exp/Cntr=0.3,0.1

Type RM Length L Ch R = 1,682,171,171,171
BEGIN DESCRIPTION:
Mapping XS 397d2d52
END DESCRIPTION:
XS GIS Cut Line= 3
      2907224.64      6984355.31      2907677.77      6984398.72
      2907978.10      6984475.10
#Sta/Elev= 30
  4558.9  398.33  4611.3  397.74  4649.7  398.39  4699.9  397.24  4750.1  397.66
  4770.2  395.48  4790.3  396.31  4816.6  393.19  4854.0  391.19  4870.7  390.50
  4880.7  390.93  4890.8  393.33  4900.8  393.76  4910.9  393.21  4931.0  389.08
  4971.1  390.96  4988.2  388.42  4988.7  387.62  4993.7  387.62  4994.2  388.42
  5010.2  390.08  5033.8  391.19  5093.8  394.98  5104.9  396.54  5155.7  398.65
  5176.3  398.55  5197.0  400.49  5222.5  401.50  5263.4  401.70  5324.0  404.14
#Mann=3,-1,0
  4558.9    0.08       0  4988.2    0.07       0  4994.2    0.08       0
Bank Sta=4854,5033.8
Exp/Cntr=0.3,0.1

Type RM Length L Ch R = 1,511,82,82,82
BEGIN DESCRIPTION:
Mapping XS 350f7742
END DESCRIPTION:
XS GIS Cut Line= 5
      2907246.77      6984374.40      2907588.79      6984488.99
      2907590.53      6984600.10      2907594.00      6984669.55
      2907916.93      6984669.55
#Sta/Elev= 30
  4581.4  397.93  4621.7  397.54  4760.3  398.31  4769.4  395.80  4832.6  395.06
  4843.2  393.01  4849.7  390.23  4886.0  388.78  4895.9  388.59  4912.8  391.06
  4937.5  389.71  4988.1  389.19  5005.1  386.22  5005.6  385.42  5010.6  385.42
  5011.1  386.22  5016.3  386.25  5020.0  388.78  5021.3  389.63  5054.2  389.81
  5125.8  390.22  5133.8  392.15  5144.7  392.88  5163.8  394.05  5203.8  394.77
  5273.8  394.61  5323.8  395.38  5363.8  396.75  5393.8  399.10  5445.7  399.91
#Mann=5,-1,0
  4581.4    0.08       0  5005.1    0.07       0  5011.1    0.08       0
  5054.2    0.05       0  5144.7    0.08       0
Bank Sta=4886,5020
Exp/Cntr=0.3,0.1

Type RM Length L Ch R = 1,429,276,276,276
BEGIN DESCRIPTION:
Mapping XS 25d43d44
END DESCRIPTION:
XS GIS Cut Line= 4
      2907219.88      6984387.00      2907532.37      6984551.93
      2907543.22      6984686.48      2907877.39      6984688.65
#Sta/Elev= 30
  4590.0  398.05  4593.3  398.66  4598.9  397.91  4687.0  396.95  4703.4  397.92
  4785.8  397.75  4807.8  396.60  4821.9  394.01  4835.5  392.89  4901.5  388.12
  4912.0  387.81  4966.5  388.05  4991.4  387.03  5003.6  385.45  5004.1  384.65
  5009.1  384.65  5009.6  385.45  5026.7  387.06  5091.7  387.81  5100.1  388.93
  5110.1  389.38  5130.1  389.05  5140.1  390.96  5150.7  391.92  5180.1  392.84
  5280.1  392.92  5330.1  393.85  5370.1  395.62  5390.1  399.20  5412.5  399.22
#Mann=5,-1,0
  4590.0    0.08       0  4991.4    0.05       0  5003.6    0.04       0
  5009.6    0.05       0  5150.7    0.08       0
Bank Sta=4912,5091.7
Exp/Cntr=0.3,0.1

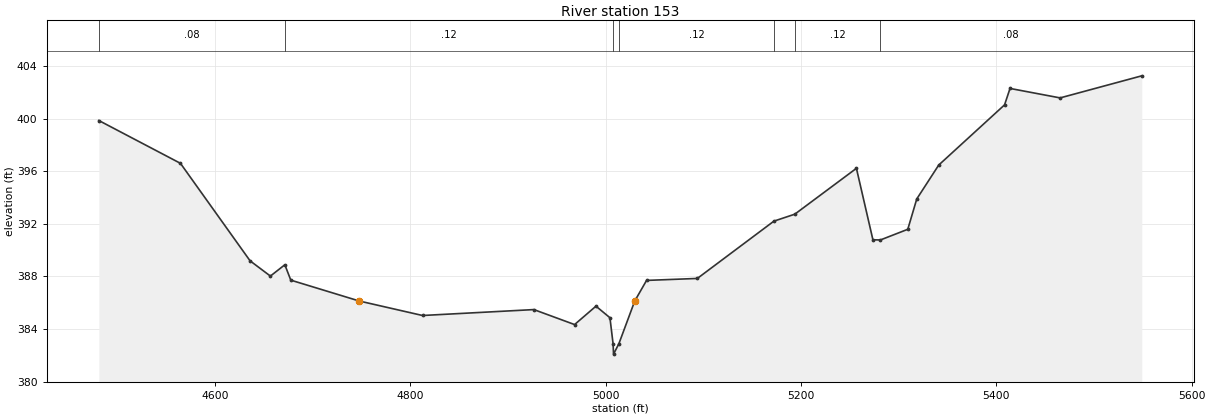
Type RM Length L Ch R = 1,153,0,0,0
BEGIN DESCRIPTION:
UNT 065 IN DRY CR WATERSHED 1.0
END DESCRIPTION:
XS GIS Cut Line= 3
      2906966.86      6984465.23      2907369.47      6984813.69
      2907850.04      6985050.02
#Sta/Elev= 30
  4480.9  399.87  4564.5  396.61  4635.8  389.19  4656.6  388.03  4671.4  388.89
  4677.5  387.72  4747.7  386.13  4812.4  385.03  4926.4  385.48  4968.1  384.34
  4990.0  385.74  5004.3  384.86  5007.5  382.89  5008.0  382.09  5013.5  382.89
  5029.7  386.13  5041.8  387.70  5093.8  387.85  5172.2  392.21  5193.6  392.74
  5256.7  396.23  5273.6  390.79  5281.3  390.78  5309.3  391.59  5318.5  393.90
  5341.0  396.48  5408.4  401.06  5414.0  402.31  5465.3  401.59  5548.9  403.27
#Mann=7,-1,0
  4480.9    0.08       0  4671.4    0.12       0  5007.5    0.07       0
  5013.5    0.12       0  5172.2    0.05       0  5193.6    0.12       0
  5281.3    0.08       0
Bank Sta=4747.7,5029.7
Exp/Cntr=0.3,0.1

Chan Stop Cuts=-1