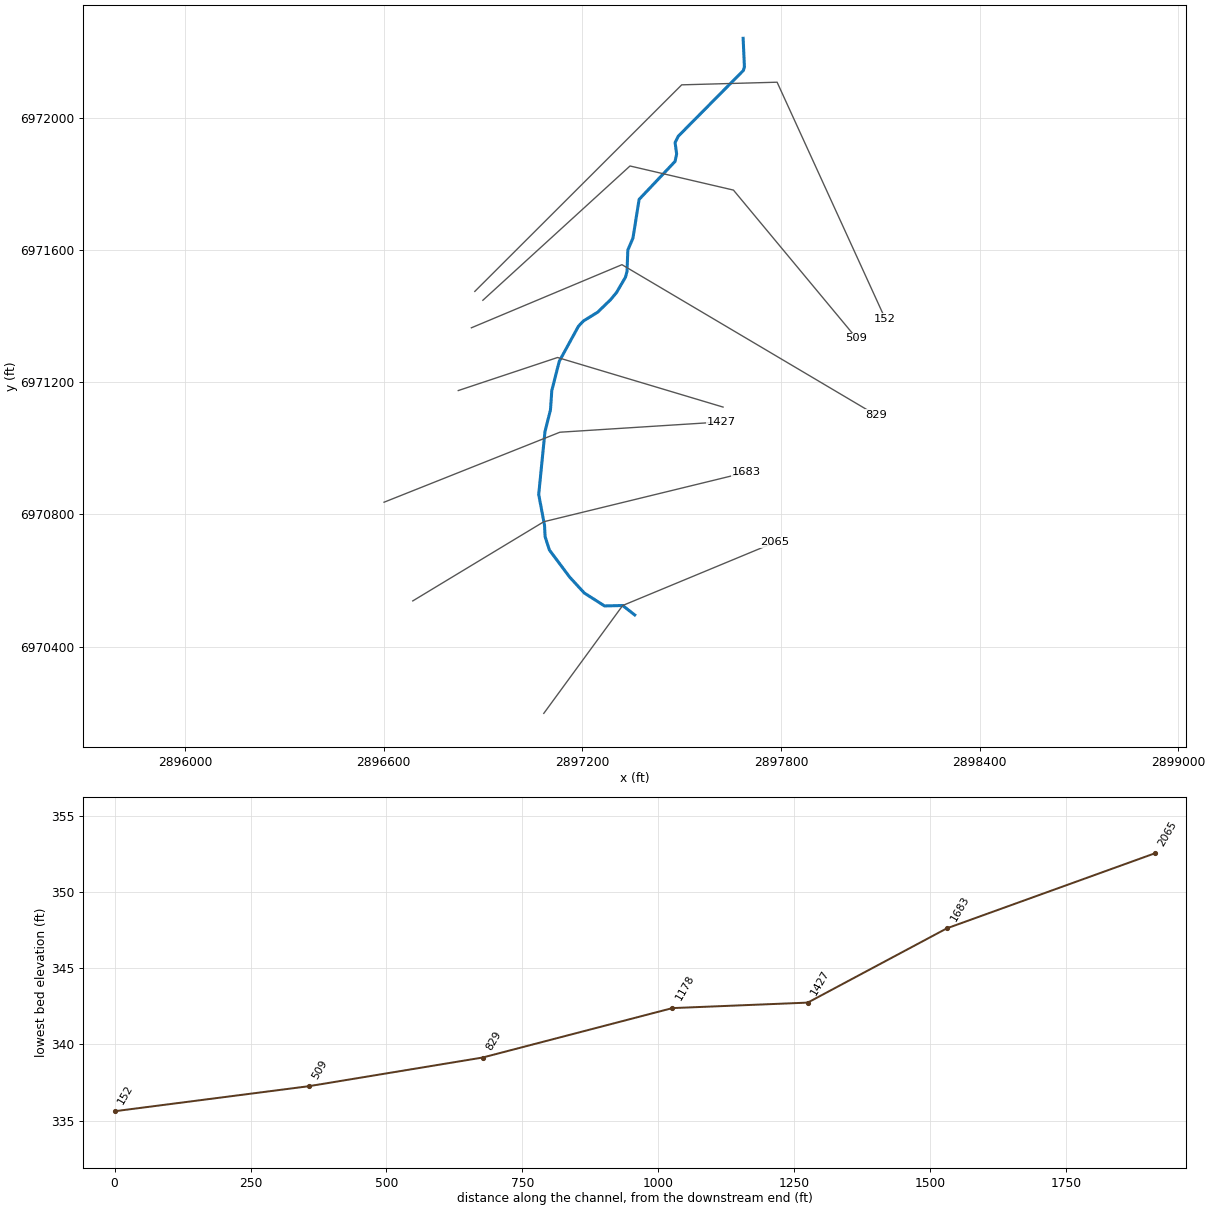
--- UNT 066 IN DRY CR WATERSHED.prj (project) ---

Proj Title=UNT 066 IN DRY CR WATERSHED Base Level Engineering
Current Plan=p01
Default Exp/Contr=0.3,0.1
English Units
Geom File=g01
Flow File=f01
Plan File=p01
BEGIN DESCRIPTION:
UNT 066 IN DRY CR WATERSHED
END DESCRIPTION:

--- UNT 066 IN DRY CR WATERSHED.p01 (plan) ---

Plan Title=Multiple Run
Short Identifier=Multiple
Geom File=g01
Flow File=f01
Subcritical Flow
K Sum by GR= 0
Std Step Tol= 0.01
Critical Tol= 0.01
Num of Std Step Trials= 20
Max Error Tol= 0.3
Flow Tol Ratio= 0.001
Split Flow NTrial= 30
Split Flow Tol= 0.02
Split Flow Ratio= 0.02
Log Output Level= 0
Friction Slope Method= 1
Unsteady Friction Slope Method= 2
Unsteady Bridges Friction Slope Method= 1
Parabolic Critical Depth
Global Vel Dist=  1 , 1 , 1
Global Log Level= 0
CheckData=True
Encroach Param= -1, 0, 0, 0
BEGIN DESCRIPTION:
Multiple Run
END DESCRIPTION:

--- UNT 066 IN DRY CR WATERSHED.f01 (steady flow) ---

Flow Title=Multiple
Number of Profiles=7
Profile Names=10-year,25-year,50-year,1pct_min,100-year,1pct_plu,500-year
River Rch & RM= UNT 066 IN DRY C,Reach-1,2065
     162     202     232     133     266     530     348
Boundary for River Rch & Prof#=UNT 066 IN DRY C,Reach-1,1
Up Type=0
Dn Type=3
Dn Slope=0.005
Boundary for River Rch & Prof#=UNT 066 IN DRY C,Reach-1,2
Up Type=0
Dn Type=3
Dn Slope=0.005
Boundary for River Rch & Prof#=UNT 066 IN DRY C,Reach-1,3
Up Type=0
Dn Type=3
Dn Slope=0.005
Boundary for River Rch & Prof#=UNT 066 IN DRY C,Reach-1,4
Up Type=0
Dn Type=3
Dn Slope=0.005
Boundary for River Rch & Prof#=UNT 066 IN DRY C,Reach-1,5
Up Type=0
Dn Type=3
Dn Slope=0.005
Boundary for River Rch & Prof#=UNT 066 IN DRY C,Reach-1,6
Up Type=0
Dn Type=3
Dn Slope=0.005
Boundary for River Rch & Prof#=UNT 066 IN DRY C,Reach-1,7
Up Type=0
Dn Type=3
Dn Slope=0.005

--- UNT 066 IN DRY CR WATERSHED.g01 (geometry) ---

Geom Title=Existing Conditions

River Reach=UNT 066 IN DRY C,Reach-1
Reach XY= 30
      2897358.13      6970495.97      2897321.67      6970524.61
      2897266.98      6970523.31      2897205.78      6970562.37
      2897161.51      6970610.55      2897100.31      6970692.58
      2897087.29      6970732.95      2897085.66      6970766.68
      2897068.01      6970860.65      2897086.96      6971050.81
      2897103.49      6971116.24      2897107.62      6971175.20
      2897130.15      6971263.53      2897188.14      6971369.65
      2897203.09      6971385.53      2897245.81      6971411.85
      2897284.76      6971449.55      2897303.21      6971471.66
      2897330.21      6971518.22      2897334.90      6971535.99
      2897337.24      6971600.02      2897352.82      6971636.47
      2897371.33      6971753.32      2897479.86      6971868.19
      2897484.70      6971890.71      2897480.04      6971925.56
      2897489.74      6971944.65      2897686.39      6972143.63
      2897689.49      6972154.48      2897685.59      6972240.71

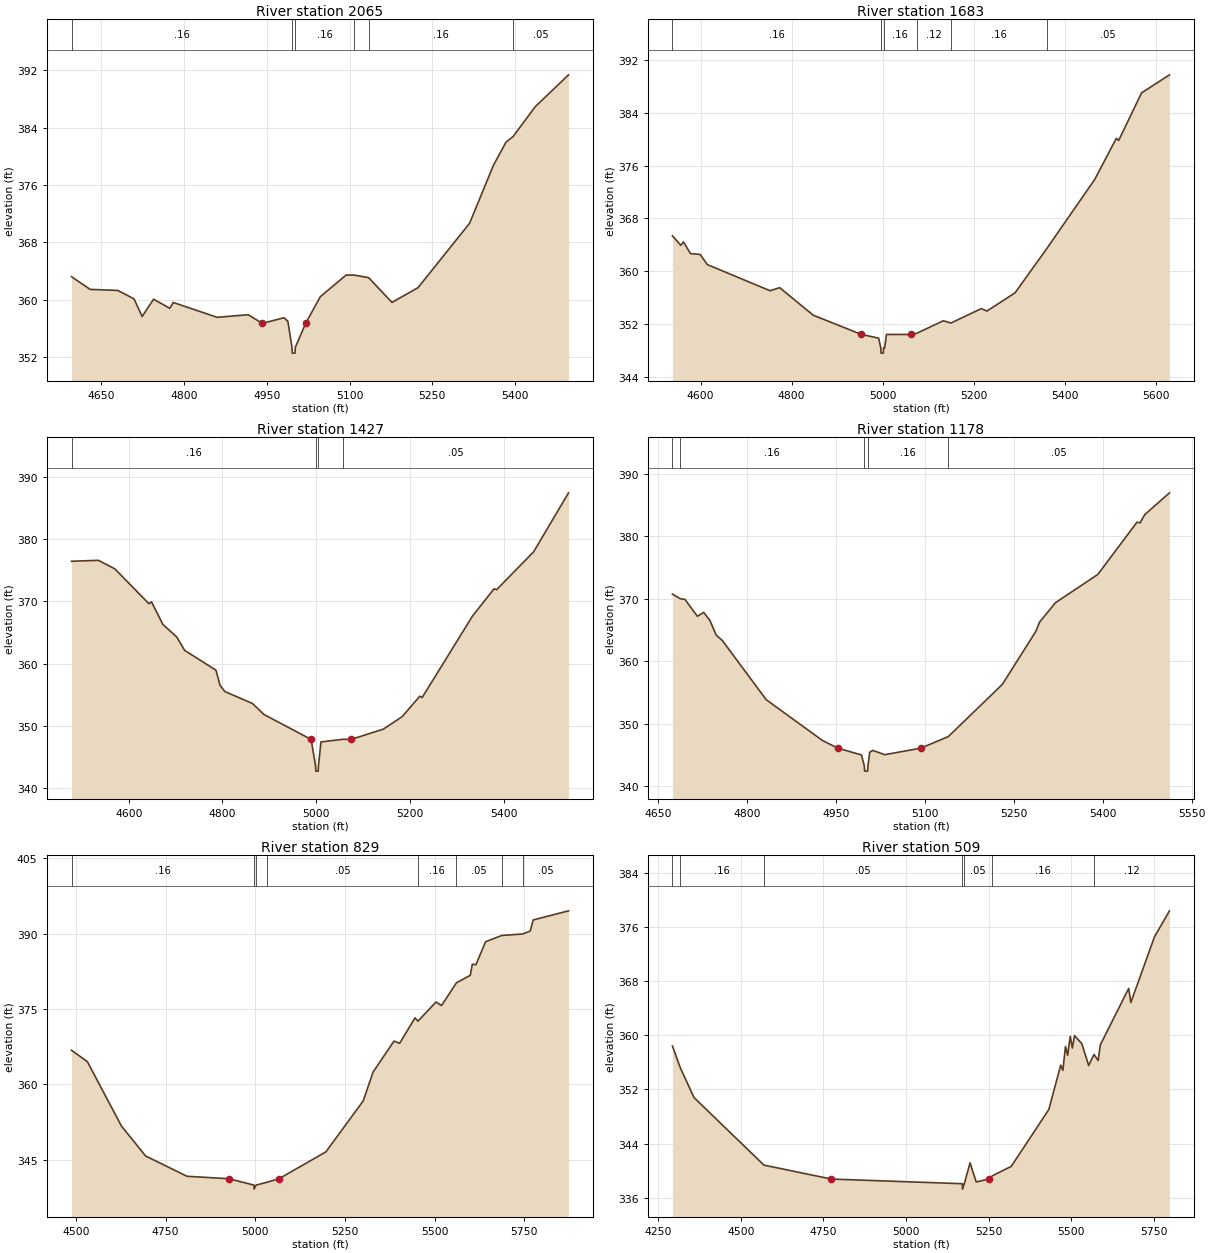
Type RM Length L Ch R = 1,2065,382,382,382
BEGIN DESCRIPTION:
UNT 066 IN DRY CR WATERSHED 3.0
END DESCRIPTION:
XS GIS Cut Line= 3
      2897083.39      6970198.24      2897321.67      6970524.61
      2897780.63      6970715.31
#Sta/Elev= 30
  4595.9  363.19  4629.6  361.42  4679.8  361.27  4709.2  360.10  4723.9  357.64
  4744.7  360.05  4774.1  358.77  4780.3  359.59  4859.8  357.52  4916.2  357.88
  4941.8  356.67  4981.1  357.46  4988.1  356.97  4995.6  353.32  4996.1  352.52
  5001.1  352.52  5001.6  353.32  5020.3  356.67  5046.9  360.39  5093.9  363.43
  5108.2  363.41  5134.5  363.06  5176.9  359.60  5224.1  361.66  5317.6  370.65
  5361.0  378.77  5383.5  381.96  5396.5  382.76  5436.8  386.94  5497.0  391.37
#Mann=6,-1,0
  4595.9    0.16       0  4995.6    0.07       0  5001.6    0.16       0
  5108.2    0.12       0  5134.5    0.16       0  5396.5    0.05       0
Bank Sta=4941.8,5020.3
Exp/Cntr=0.3,0.1

Type RM Length L Ch R = 1,1683,256,256,256
BEGIN DESCRIPTION:
Mapping XS 72ae7dcb
END DESCRIPTION:
XS GIS Cut Line= 3
      2896687.57      6970538.52      2897083.39      6970778.10
      2897694.54      6970927.41
#Sta/Elev= 30
  4538.1  365.37  4556.4  363.94  4562.3  364.44  4577.8  362.68  4599.1  362.55
  4614.6  361.02  4752.4  357.06  4773.7  357.52  4847.4  353.35  4953.2  350.44
  4991.0  349.88  4995.8  348.41  4996.3  347.61  5001.3  347.61  5001.8  348.41
  5004.2  348.41  5008.2  350.44  5062.7  350.44  5075.0  350.62  5133.2  352.51
  5149.9  352.17  5216.5  354.35  5228.9  353.98  5290.7  356.74  5360.0  363.40
  5465.7  373.91  5513.2  380.14  5518.3  379.81  5568.6  387.02  5629.9  389.75
#Mann=6,-1,0
  4538.1    0.16       0  4995.8    0.07       0  5001.8    0.16       0
  5075.0    0.12       0  5149.9    0.16       0  5360.0    0.05       0
Bank Sta=4953.2,5062.7
Exp/Cntr=0.3,0.1

Type RM Length L Ch R = 1,1427,249,249,249
BEGIN DESCRIPTION:
Mapping XS d5b3ed4c
END DESCRIPTION:
XS GIS Cut Line= 3
      2896600.76      6970837.13      2897132.00      6971048.93
      2897619.40      6971080.04
#Sta/Elev= 30
  4478.0  376.45  4535.4  376.60  4570.4  375.23  4643.2  369.62  4648.6  369.93
  4672.9  366.30  4702.5  364.28  4719.4  362.13  4786.1  358.96  4794.8  356.53
  4805.0  355.53  4864.3  353.59  4888.5  351.84  4989.2  347.83  4998.7  343.54
  4999.2  342.74  5004.2  342.74  5004.7  343.54  5010.1  347.43  5057.8  347.86
  5074.1  347.83  5143.1  349.48  5183.2  351.48  5221.0  354.77  5226.0  354.56
  5333.5  367.66  5379.6  372.04  5384.6  371.87  5463.7  377.96  5538.3  387.44
#Mann=4,-1,0
  4478.0    0.16       0  4998.7    0.07       0  5004.7    0.16       0
  5057.8    0.05       0
Bank Sta=4989.2,5074.1
Exp/Cntr=0.3,0.1

Type RM Length L Ch R = 1,1178,349,349,349
BEGIN DESCRIPTION:
UNT 066 IN DRY CR WATERSHED 2.0
END DESCRIPTION:
XS GIS Cut Line= 3
      2896825.03      6971175.01      2897125.00      6971275.00
      2897624.99      6971125.00
#Sta/Elev= 30
  4674.4  370.72  4687.8  369.97  4695.4  369.88  4716.5  367.16  4727.1  367.80
  4737.6  366.50  4748.2  364.16  4758.7  363.27  4832.5  353.82  4927.3  347.29
  4953.1  346.06  4993.2  344.97  4998.0  343.18  4998.5  342.38  5003.5  342.38
  5004.0  343.18  5007.1  345.40  5012.3  345.70  5032.4  345.01  5093.4  346.06
  5139.6  347.91  5230.7  356.26  5287.3  364.76  5293.4  366.22  5320.3  369.34
  5391.7  373.86  5457.8  382.23  5463.0  382.12  5470.8  383.43  5512.6  386.93
#Mann=5,-1,0
  4674.4    0.12       0  4687.8    0.16       0  4998.0    0.07       0
  5004.0    0.16       0  5139.6    0.05       0
Bank Sta=4953.1,5093.4
Exp/Cntr=0.3,0.1

Type RM Length L Ch R = 1,829,320,320,320
BEGIN DESCRIPTION:
Mapping XS ee717073
END DESCRIPTION:
XS GIS Cut Line= 3
      2896864.62      6971364.89      2897319.50      6971555.87
      2898086.87      6971101.01
#Sta/Elev= 30
  4488.0  366.79  4532.1  364.53  4627.2  351.70  4694.5  345.74  4809.8  341.70
  4927.0  341.21  4996.4  339.94  4996.9  339.14  5002.4  339.94  5032.8  340.51
  5066.4  341.21  5197.0  346.56  5301.2  356.72  5328.5  362.45  5386.9  368.62
  5402.6  368.17  5445.4  373.25  5453.7  372.59  5503.9  376.40  5519.5  375.71
  5560.8  380.22  5599.4  381.71  5605.2  383.93  5615.1  383.83  5642.3  388.41
  5687.1  389.65  5745.5  389.95  5766.6  390.54  5774.9  392.74  5873.4  394.56
#Mann=8,-1,0
  4488.0    0.16       0  4996.4    0.07       0  5002.4    0.16       0
  5032.8    0.05       0  5453.7    0.16       0  5560.8    0.05       0
  5687.1     0.1       0  5745.5    0.05       0
Bank Sta=4927,5066.4
Exp/Cntr=0.3,0.1

Type RM Length L Ch R = 1,509,357,357,357
BEGIN DESCRIPTION:
Mapping XS 89d732c5
END DESCRIPTION:
XS GIS Cut Line= 4
      2896899.33      6971448.20      2897343.81      6971854.49
      2897656.31      6971781.57      2898027.82      6971333.67
#Sta/Elev= 30
  4292.9  358.41  4316.4  355.24  4358.2  350.80  4570.0  340.81  4774.0  338.75
  5170.6  338.06  5171.1  337.26  5176.6  338.06  5194.1  341.15  5212.7  338.32
  5250.5  338.75  5261.4  339.22  5318.9  340.63  5432.4  349.02  5468.6  355.60
  5475.1  354.82  5483.0  358.36  5489.5  357.06  5497.3  359.85  5503.8  358.12
  5510.3  359.96  5532.4  358.77  5553.3  355.53  5569.3  357.18  5581.9  356.28
  5588.4  358.58  5674.4  366.94  5680.9  364.85  5752.5  374.57  5797.9  378.41
#Mann=7,-1,0
  4292.9    0.12       0  4316.4    0.16       0  4570.0    0.05       0
  5170.6    0.03       0  5176.6    0.05       0  5261.4    0.16       0
  5569.3    0.12       0
Bank Sta=4774,5250.5
Exp/Cntr=0.3,0.1

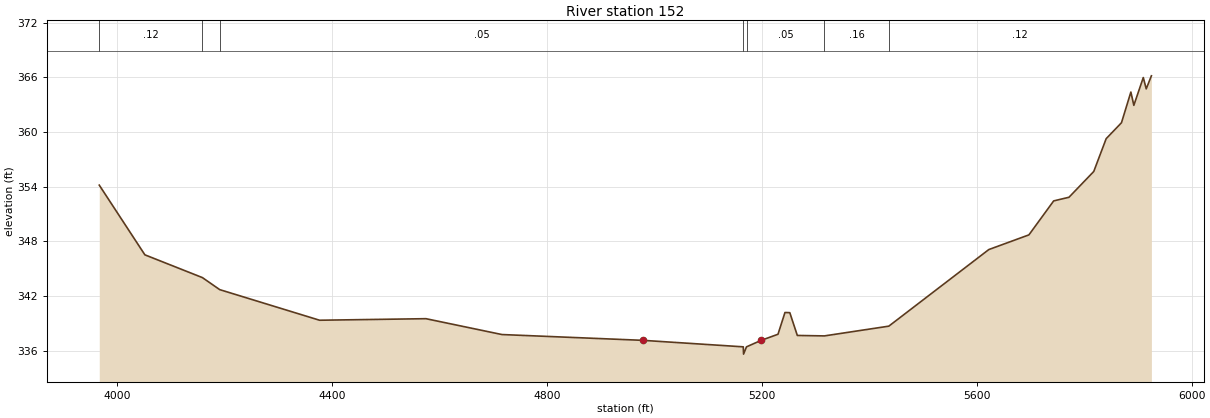
Type RM Length L Ch R = 1,152,0,0,0
BEGIN DESCRIPTION:
UNT 066 IN DRY CR WATERSHED 1.0
END DESCRIPTION:
XS GIS Cut Line= 4
      2896875.00      6971475.00      2897500.00      6972100.00
      2897788.25      6972107.96      2898114.65      6971392.66
#Sta/Elev= 30
  3966.6  354.17  4051.5  346.52  4158.6  344.02  4190.8  342.70  4376.7  339.34
  4574.7  339.51  4716.1  337.77  4979.5  337.13  5165.4  336.42  5165.9  335.62
  5171.4  336.42  5198.6  337.13  5230.0  337.80  5243.0  340.19  5252.0  340.17
  5266.0  337.67  5316.4  337.62  5436.3  338.69  5622.5  347.10  5697.1  348.71
  5743.2  352.44  5771.7  352.84  5817.8  355.67  5840.9  359.27  5869.4  361.02
  5886.9  364.39  5892.4  362.93  5910.0  365.98  5915.5  364.74  5925.1  366.17
#Mann=7,-1,0
  3966.6    0.12       0  4158.6    0.16       0  4190.8    0.05       0
  5165.4    0.03       0  5171.4    0.05       0  5316.4    0.16       0
  5436.3    0.12       0
Bank Sta=4979.5,5198.6
Exp/Cntr=0.3,0.1

Chan Stop Cuts=-1