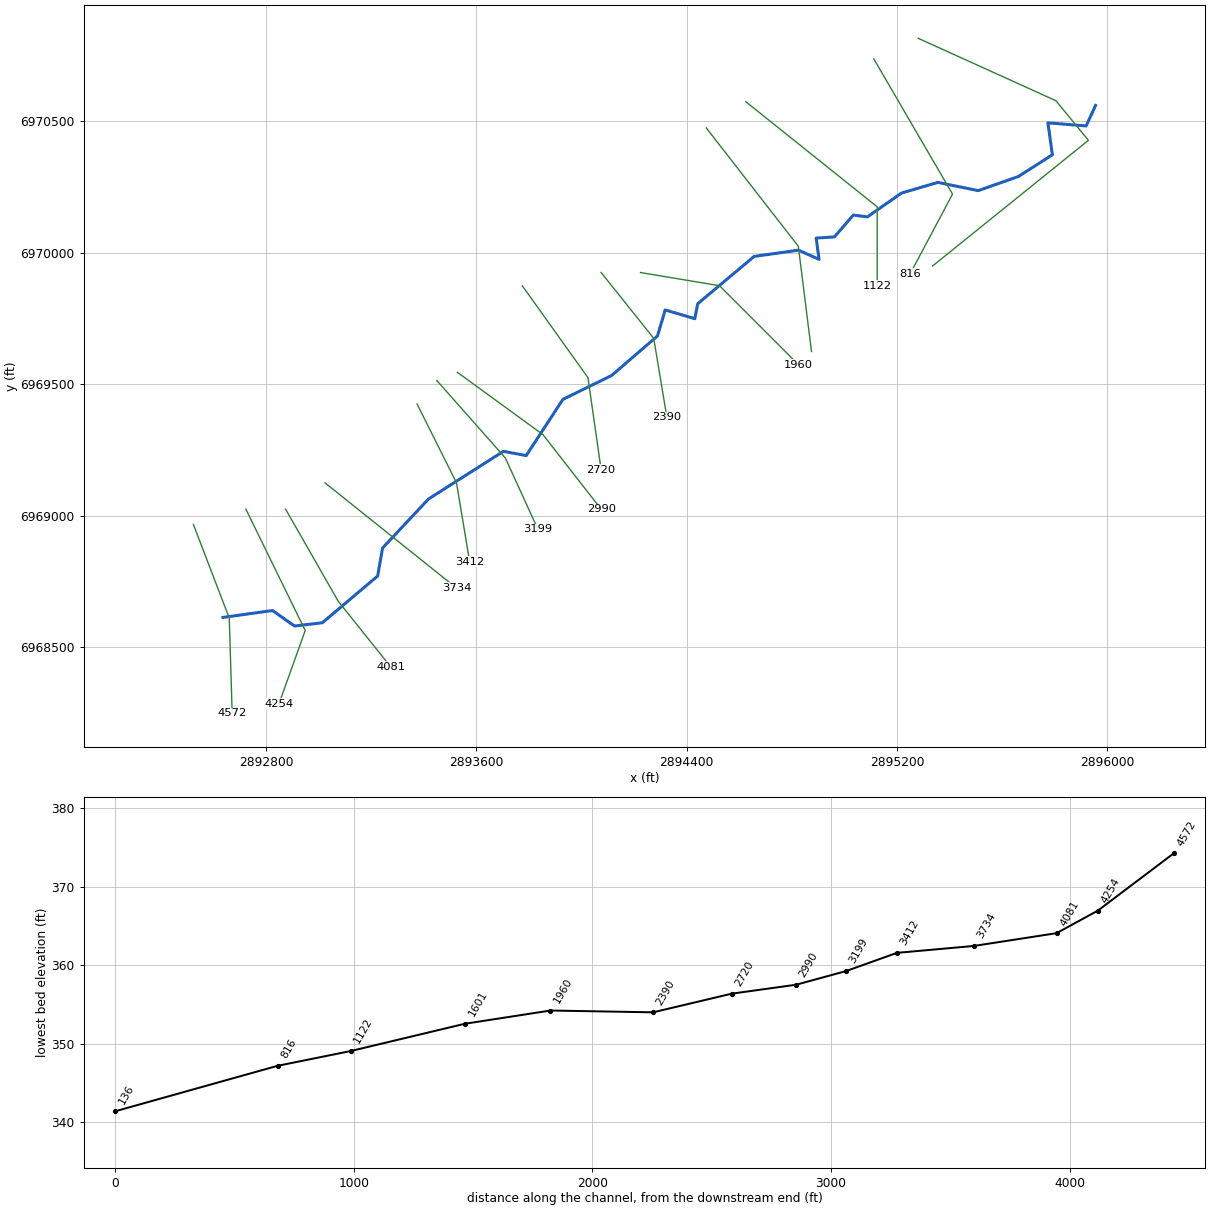
--- UNT 067 IN DRY CR WATERSHED.prj (project) ---

Proj Title=UNT 067 IN DRY CR WATERSHED Base Level Engineering
Current Plan=p01
Default Exp/Contr=0.3,0.1
English Units
Geom File=g01
Flow File=f01
Plan File=p01
BEGIN DESCRIPTION:
UNT 067 IN DRY CR WATERSHED
END DESCRIPTION:

--- UNT 067 IN DRY CR WATERSHED.p01 (plan) ---

Plan Title=Multiple Run
Short Identifier=Multiple
Geom File=g01
Flow File=f01
Subcritical Flow
K Sum by GR= 0
Std Step Tol= 0.01
Critical Tol= 0.01
Num of Std Step Trials= 20
Max Error Tol= 0.3
Flow Tol Ratio= 0.001
Split Flow NTrial= 30
Split Flow Tol= 0.02
Split Flow Ratio= 0.02
Log Output Level= 0
Friction Slope Method= 1
Unsteady Friction Slope Method= 2
Unsteady Bridges Friction Slope Method= 1
Parabolic Critical Depth
Global Vel Dist=  1 , 1 , 1
Global Log Level= 0
CheckData=True
Encroach Param= -1, 0, 0, 0
BEGIN DESCRIPTION:
Multiple Run
END DESCRIPTION:

--- UNT 067 IN DRY CR WATERSHED.f01 (steady flow) ---

Flow Title=Multiple
Number of Profiles=7
Profile Names=10-year,25-year,50-year,1pct_min,100-year,1pct_plu,500-year
River Rch & RM= UNT 067 IN DRY C,Reach-1,4572
     580     781     945     569    1136    2266    1642
River Rch & RM= UNT 067 IN DRY C,Reach-1,136
     934    1292    1591     974    1943    3876    2902
Boundary for River Rch & Prof#=UNT 067 IN DRY C,Reach-1,1
Up Type=0
Dn Type=3
Dn Slope=0.005
Boundary for River Rch & Prof#=UNT 067 IN DRY C,Reach-1,2
Up Type=0
Dn Type=3
Dn Slope=0.005
Boundary for River Rch & Prof#=UNT 067 IN DRY C,Reach-1,3
Up Type=0
Dn Type=3
Dn Slope=0.005
Boundary for River Rch & Prof#=UNT 067 IN DRY C,Reach-1,4
Up Type=0
Dn Type=3
Dn Slope=0.005
Boundary for River Rch & Prof#=UNT 067 IN DRY C,Reach-1,5
Up Type=0
Dn Type=3
Dn Slope=0.005
Boundary for River Rch & Prof#=UNT 067 IN DRY C,Reach-1,6
Up Type=0
Dn Type=3
Dn Slope=0.005
Boundary for River Rch & Prof#=UNT 067 IN DRY C,Reach-1,7
Up Type=0
Dn Type=3
Dn Slope=0.005

--- UNT 067 IN DRY CR WATERSHED.g01 (geometry) ---

Geom Title=Existing Conditions

River Reach=UNT 067 IN DRY C,Reach-1
Reach XY= 30
      2892636.68      6968613.34      2892825.32      6968639.58
      2892908.71      6968580.73      2893014.61      6968593.03
      2893225.08      6968770.85      2893243.64      6968877.09
      2893418.20      6969063.54      2893703.23      6969245.01
      2893790.00      6969228.92      2893929.71      6969442.70
      2894114.70      6969533.28      2894289.26      6969683.73
      2894318.72      6969782.74      2894431.29      6969749.63
      2894442.42      6969806.56      2894657.12      6969986.38
      2894825.75      6970010.12      2894904.03      6969974.91
      2894892.78      6970056.10      2894962.25      6970060.48
      2895033.97      6970143.56      2895087.84      6970136.77
      2895217.17      6970227.16      2895355.47      6970267.81
      2895509.40      6970236.64      2895662.15      6970290.39
      2895791.30      6970372.91      2895774.27      6970494.50
      2895919.65      6970482.62      2895955.59      6970560.71

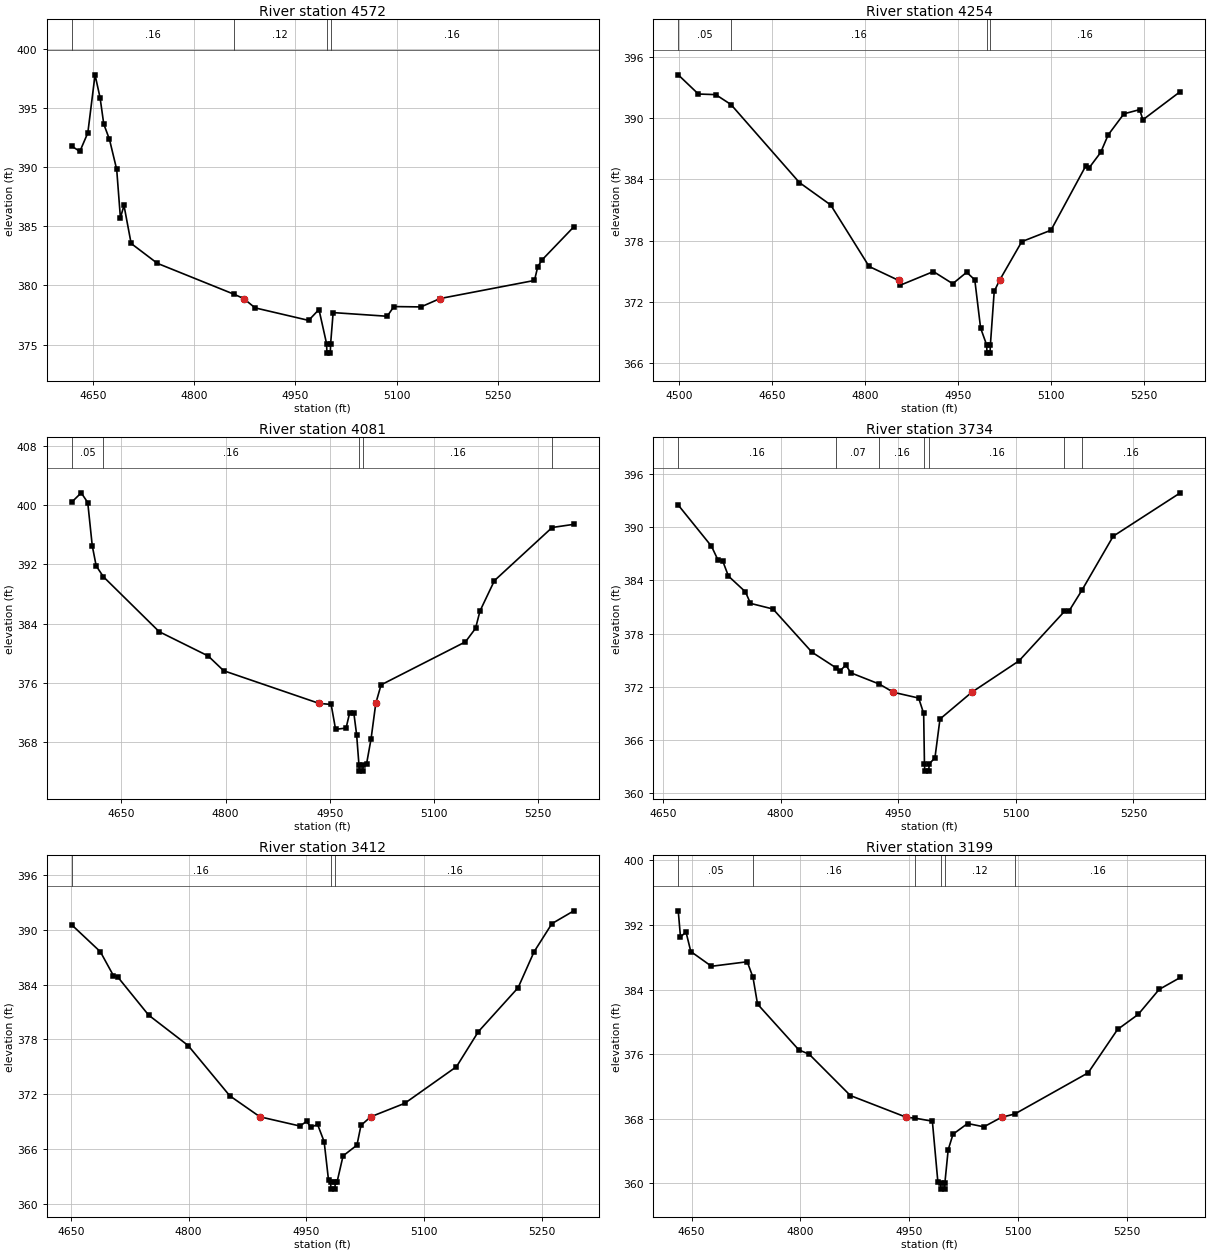
Type RM Length L Ch R = 1,4572,318,318,318
BEGIN DESCRIPTION:
UNT 067 IN DRY CR WATERSHED 11.0
END DESCRIPTION:
XS GIS Cut Line= 3
      2892524.16      6968967.18      2892660.67      6968610.83
      2892671.68      6968248.40
#Sta/Elev= 30
  4618.4  391.78  4630.4  391.34  4642.2  392.91  4652.9  397.82  4660.4  395.87
  4665.8  393.66  4674.3  392.35  4685.0  389.81  4690.5  385.72  4695.8  386.77
  4706.4  383.55  4745.2  381.87  4858.6  379.26  4873.2  378.89  4890.1  378.10
  4969.5  377.04  4984.8  377.96  4996.1  375.07  4996.6  374.27  5001.6  374.27
  5002.1  375.07  5005.8  377.70  5085.9  377.39  5095.9  378.21  5135.9  378.18
  5164.4  378.89  5304.2  380.42  5309.2  381.60  5316.0  382.19  5362.6  384.96
#Mann=4,-1,0
  4618.4    0.16       0  4858.6    0.12       0  4996.1    0.07       0
  5002.1    0.16       0
Bank Sta=4873.2,5164.4
Exp/Cntr=0.3,0.1

Type RM Length L Ch R = 1,4254,173,173,173
BEGIN DESCRIPTION:
Mapping XS 1c9e9090
END DESCRIPTION:
XS GIS Cut Line= 3
      2892723.82      6969025.34      2892949.51      6968563.55
      2892849.39      6968283.92
#Sta/Elev= 30
  4498.0  394.23  4530.5  392.35  4558.6  392.29  4583.2  391.32  4693.7  383.68
  4744.3  381.48  4806.3  375.46  4853.8  374.10  4856.9  373.63  4910.2  374.96
  4941.4  373.77  4963.9  374.89  4977.0  374.15  4986.4  369.43  4996.2  367.77
  4996.7  366.97  5001.7  366.97  5002.2  367.77  5008.4  373.02  5017.0  374.10
  5052.9  377.89  5100.1  379.01  5156.4  385.32  5161.7  385.12  5180.4  386.63
  5192.4  388.34  5217.9  390.41  5243.3  390.82  5248.6  389.83  5309.0  392.59
#Mann=4,-1,0
  4498.0    0.05       0  4583.2    0.16       0  4996.2    0.07       0
  5002.2    0.16       0
Bank Sta=4853.8,5017
Exp/Cntr=0.3,0.1

Type RM Length L Ch R = 1,4081,347,347,347
BEGIN DESCRIPTION:
UNT 067 IN DRY CR WATERSHED 10.0
END DESCRIPTION:
XS GIS Cut Line= 3
      2892875.02      6969024.96      2893075.00      6968675.00
      2893274.99      6968425.02
#Sta/Elev= 30
  4578.4  400.41  4592.0  401.66  4601.4  400.35  4607.9  394.52  4613.6  391.79
  4624.0  390.33  4704.3  382.92  4774.9  379.64  4797.2  377.65  4934.7  373.24
  4952.0  373.10  4958.4  369.74  4973.5  369.91  4978.6  371.94  4984.7  371.94
  4988.7  369.03  4992.1  364.90  4992.6  364.10  4997.6  364.10  4998.1  364.90
  5003.1  365.12  5009.5  368.45  5016.3  373.24  5023.9  375.74  5145.5  381.55
  5160.0  383.37  5166.4  385.71  5187.2  389.81  5270.3  396.98  5301.6  397.41
#Mann=5,-1,0
  4578.4    0.05       0  4624.0    0.16       0  4992.1    0.07       0
  4998.1    0.16       0  5270.3    0.05       0
Bank Sta=4934.7,5016.3
Exp/Cntr=0.3,0.1

Type RM Length L Ch R = 1,3734,322,322,322
BEGIN DESCRIPTION:
UNT 067 IN DRY CR WATERSHED 9.0
END DESCRIPTION:
XS GIS Cut Line= 3
      2893024.99      6969125.01      2893275.00      6968925.00
      2893524.98      6968725.02
#Sta/Elev= 30
  4669.5  392.51  4711.9  387.86  4719.9  386.36  4726.3  386.18  4733.5  384.49
  4755.2  382.71  4761.6  381.41  4790.4  380.77  4840.0  375.90  4870.8  374.13
  4875.2  373.72  4883.2  374.45  4889.6  373.57  4925.9  372.30  4944.0  371.37
  4976.1  370.72  4982.5  368.99  4983.5  363.27  4984.0  362.47  4989.0  362.47
  4989.5  363.27  4996.9  363.98  5003.3  368.35  5043.8  371.37  5104.1  374.92
  5162.1  380.51  5168.2  380.59  5184.3  382.89  5224.2  388.99  5309.8  393.89
#Mann=7,-1,0
  4669.5    0.16       0  4870.8    0.07       0  4925.9    0.16       0
  4983.5    0.07       0  4989.5    0.16       0  5162.1    0.07       0
  5184.3    0.16       0
Bank Sta=4944,5043.8
Exp/Cntr=0.3,0.1

Type RM Length L Ch R = 1,3412,213,213,213
BEGIN DESCRIPTION:
UNT 067 IN DRY CR WATERSHED 8.0
END DESCRIPTION:
XS GIS Cut Line= 3
      2893374.98      6969425.04      2893525.00      6969125.00
      2893575.00      6968824.99
#Sta/Elev= 30
  4651.2  390.53  4687.6  387.59  4704.3  384.97  4709.9  384.81  4749.1  380.65
  4799.4  377.32  4852.5  371.81  4890.9  369.51  4941.9  368.50  4950.3  369.01
  4955.9  368.36  4964.3  368.68  4972.7  366.79  4978.3  362.56  4980.9  362.39
  4981.4  361.59  4986.4  361.59  4986.9  362.39  4989.2  362.39  4996.8  365.23
  5014.5  366.41  5019.6  368.57  5032.0  369.51  5075.4  370.99  5141.3  375.00
  5169.1  378.83  5219.8  383.65  5240.1  387.58  5262.9  390.67  5290.8  392.07
#Mann=3,-1,0
  4651.2    0.16       0  4980.9    0.07       0  4986.9    0.16       0
Bank Sta=4890.9,5032
Exp/Cntr=0.3,0.1

Type RM Length L Ch R = 1,3199,209,209,209
BEGIN DESCRIPTION:
Mapping XS 2b0296b7
END DESCRIPTION:
XS GIS Cut Line= 3
      2893449.93      6969514.59      2893710.36      6969220.31
      2893834.64      6968948.44
#Sta/Elev= 30
  4631.6  393.75  4634.7  390.51  4642.3  391.13  4648.9  388.71  4677.4  386.88
  4726.7  387.44  4734.6  385.51  4740.9  382.19  4797.8  376.52  4812.1  375.98
  4868.9  370.86  4946.0  368.17  4958.0  368.06  4981.8  367.69  4989.4  360.16
  4993.1  360.07  4993.6  359.27  4998.6  359.27  4999.1  360.07  5003.6  364.14
  5010.3  366.08  5030.4  367.40  5052.8  366.99  5077.1  368.17  5095.4  368.58
  5196.5  373.68  5237.0  379.05  5265.5  380.92  5294.3  384.01  5323.5  385.49
#Mann=6,-1,0
  4631.6    0.05       0  4734.6    0.16       0  4958.0    0.12       0
  4993.1    0.07       0  4999.1    0.12       0  5095.4    0.16       0
Bank Sta=4946,5077.1
Exp/Cntr=0.3,0.1

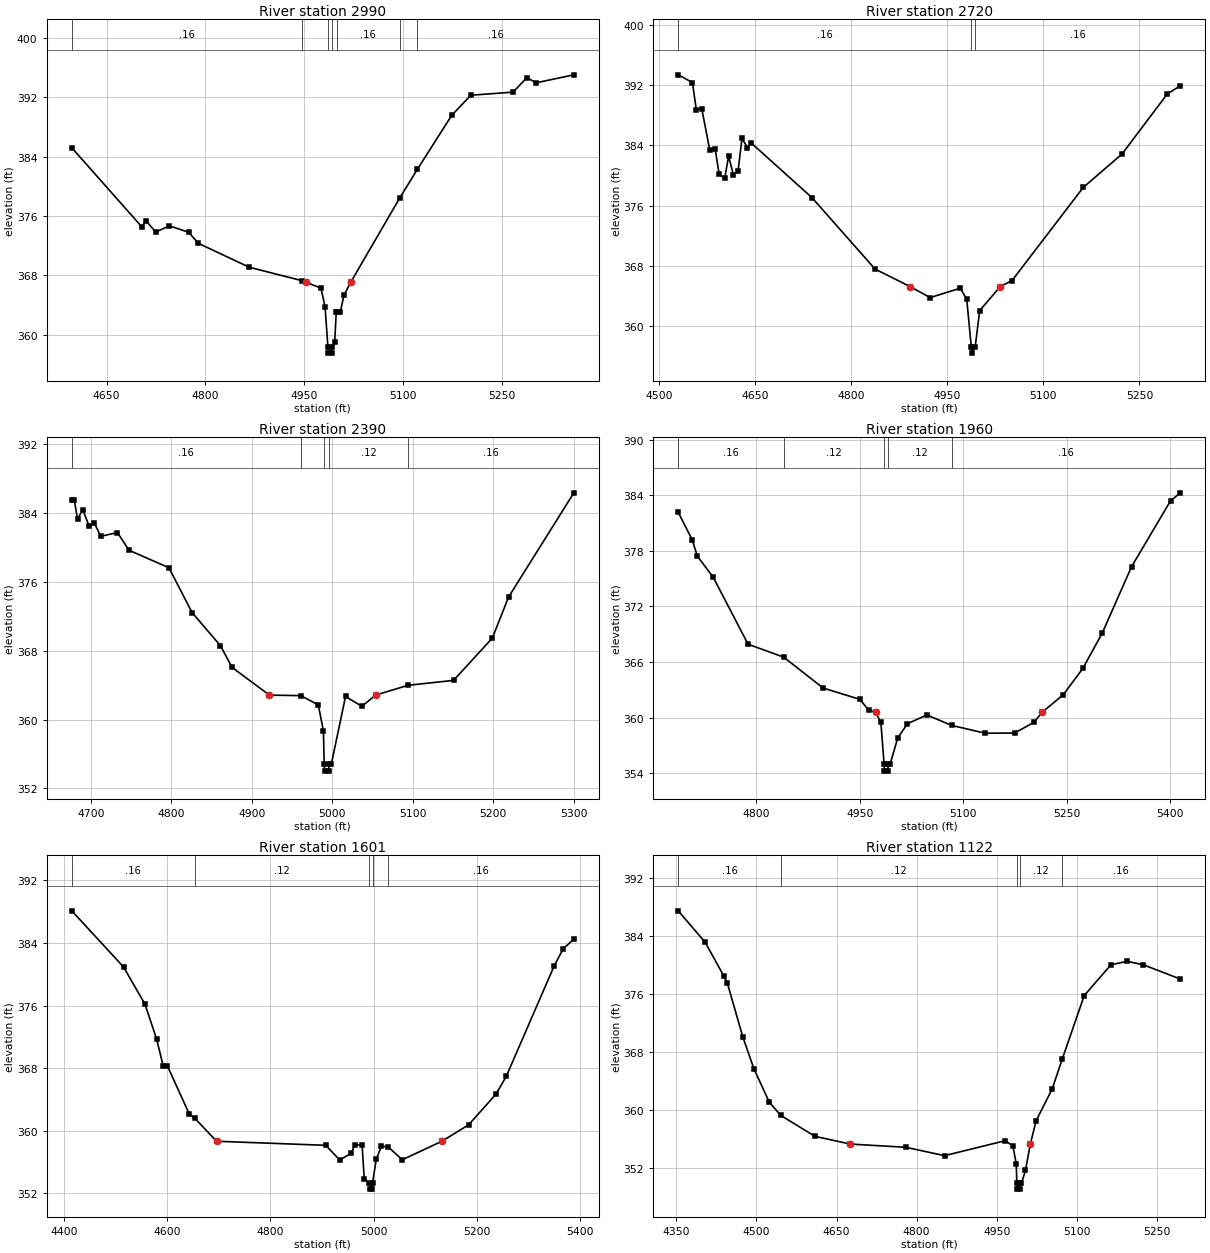
Type RM Length L Ch R = 1,2990,270,270,270
BEGIN DESCRIPTION:
UNT 067 IN DRY CR WATERSHED 7.0
END DESCRIPTION:
XS GIS Cut Line= 3
      2893528.08      6969545.81      2893853.75      6969308.60
      2894075.00      6969025.00
#Sta/Elev= 30
  4597.1  385.20  4703.7  374.52  4709.8  375.38  4724.5  373.84  4745.4  374.67
  4774.7  373.81  4789.4  372.32  4866.7  369.10  4946.7  367.29  4952.5  367.08
  4975.6  366.29  4981.8  363.79  4986.2  358.33  4986.7  357.53  4991.7  357.53
  4992.2  358.33  4996.5  359.06  4998.8  363.11  5000.1  363.11  5005.1  363.11
  5010.5  365.33  5020.8  367.08  5094.9  378.38  5122.0  382.29  5174.3  389.57
  5203.2  392.27  5267.4  392.69  5288.2  394.63  5302.7  393.95  5359.7  395.02
#Mann=7,-1,0
  4597.1    0.16       0  4946.7    0.12       0  4986.2    0.07       0
  4992.2    0.12       0  5000.1    0.16       0  5094.9    0.12       0
  5122.0    0.16       0
Bank Sta=4952.5,5020.8
Exp/Cntr=0.3,0.1

Type RM Length L Ch R = 1,2720,330,330,330
BEGIN DESCRIPTION:
UNT 067 IN DRY CR WATERSHED 6.0
END DESCRIPTION:
XS GIS Cut Line= 3
      2893775.03      6969874.96      2894025.00      6969525.00
      2894075.00      6969175.02
#Sta/Elev= 30
  4530.1  393.38  4552.2  392.36  4558.3  388.77  4566.9  388.84  4579.2  383.43
  4587.8  383.50  4594.0  380.15  4602.6  379.62  4608.7  382.57  4616.1  380.12
  4623.4  380.58  4629.6  384.93  4638.2  383.70  4644.3  384.30  4739.0  377.04
  4837.3  367.56  4892.1  365.23  4923.3  363.77  4970.3  365.02  4980.4  363.54
  4987.5  357.19  4988.0  356.39  4993.5  357.19  5000.6  362.05  5032.6  365.23
  5051.1  366.04  5162.2  378.41  5222.8  382.86  5293.5  390.85  5313.7  391.93
#Mann=3,-1,0
  4530.1    0.16       0  4987.5    0.07       0  4993.5    0.16       0
Bank Sta=4892.1,5032.6
Exp/Cntr=0.3,0.1

Type RM Length L Ch R = 1,2390,430,430,430
BEGIN DESCRIPTION:
UNT 067 IN DRY CR WATERSHED 5.0
END DESCRIPTION:
XS GIS Cut Line= 3
      2894075.02      6969924.97      2894275.00      6969675.00
      2894325.01      6969374.96
#Sta/Elev= 30
  4676.0  385.45  4679.2  385.45  4683.2  383.26  4689.6  384.40  4697.6  382.47
  4704.0  382.85  4712.0  381.29  4732.8  381.72  4747.2  379.67  4796.8  377.64
  4825.6  372.43  4860.9  368.58  4875.3  366.06  4921.8  362.84  4960.8  362.78
  4982.5  361.71  4988.9  358.69  4989.9  354.81  4990.4  354.01  4995.4  354.01
  4995.9  354.81  4998.7  354.81  5016.4  362.68  5036.7  361.54  5053.8  362.84
  5094.1  363.98  5150.7  364.55  5198.9  369.46  5219.2  374.24  5300.3  386.34
#Mann=5,-1,0
  4676.0    0.16       0  4960.8    0.12       0  4989.9    0.07       0
  4995.9    0.12       0  5094.1    0.16       0
Bank Sta=4921.8,5053.8
Exp/Cntr=0.3,0.1

Type RM Length L Ch R = 1,1960,359,359,359
BEGIN DESCRIPTION:
UNT 067 IN DRY CR WATERSHED 4.0
END DESCRIPTION:
XS GIS Cut Line= 3
      2894225.03      6969925.00      2894525.00      6969875.00
      2894825.02      6969574.98
#Sta/Elev= 30
  4686.5  382.16  4706.7  379.20  4714.3  377.42  4737.2  375.16  4787.8  367.93
  4839.3  366.54  4896.8  363.20  4950.1  361.98  4962.7  360.81  4973.0  360.57
  4980.5  359.49  4985.1  355.04  4985.6  354.24  4990.6  354.24  4991.1  355.04
  4994.1  355.04  5004.8  357.79  5018.9  359.35  5047.2  360.30  5083.2  359.17
  5132.0  358.33  5174.5  358.35  5202.7  359.51  5214.1  360.57  5245.2  362.49
  5273.5  365.32  5301.7  369.14  5344.2  376.30  5400.7  383.39  5414.9  384.26
#Mann=5,-1,0
  4686.5    0.16       0  4839.3    0.12       0  4985.1    0.07       0
  4991.1    0.12       0  5083.2    0.16       0
Bank Sta=4973,5214.1
Exp/Cntr=0.3,0.1

Type RM Length L Ch R = 1,1601,479,479,479
BEGIN DESCRIPTION:
UNT 067 IN DRY CR WATERSHED 3.0
END DESCRIPTION:
XS GIS Cut Line= 3
      2894475.03      6970474.96      2894825.00      6970025.00
      2894875.01      6969624.96
#Sta/Elev= 30
  4414.9  388.12  4515.3  380.94  4556.9  376.17  4579.5  371.70  4592.2  368.26
  4600.4  368.28  4642.9  362.12  4653.0  361.63  4695.5  358.67  4907.1  358.15
  4934.3  356.28  4956.9  357.14  4963.2  358.23  4977.7  358.15  4981.8  353.90
  4992.0  353.35  4992.5  352.55  4997.5  352.55  4998.0  353.35  5005.1  356.38
  5015.2  358.03  5028.1  357.96  5055.5  356.30  5132.3  358.67  5184.0  360.76
  5236.9  364.67  5257.0  366.95  5350.3  381.13  5367.9  383.30  5388.1  384.49
#Mann=5,-1,0
  4414.9    0.16       0  4653.0    0.12       0  4992.0    0.07       0
  4998.0    0.12       0  5028.1    0.16       0
Bank Sta=4695.5,5132.3
Exp/Cntr=0.3,0.1

Type RM Length L Ch R = 1,1122,306,306,306
BEGIN DESCRIPTION:
UNT 067 IN DRY CR WATERSHED 2.0
END DESCRIPTION:
XS GIS Cut Line= 3
      2894624.98      6970575.02      2895125.00      6970175.00
      2895125.00      6969875.04
#Sta/Elev= 30
  4353.5  387.41  4404.0  383.07  4439.2  378.39  4445.6  377.42  4474.4  370.05
  4495.2  365.66  4524.0  361.05  4545.6  359.22  4609.7  356.34  4675.6  355.28
  4780.1  354.83  4852.2  353.68  4965.8  355.74  4980.2  355.02  4986.6  352.56
  4987.6  349.87  4988.1  349.07  4993.1  349.07  4993.6  349.87  4996.3  349.87
  5003.8  351.65  5012.9  355.28  5023.8  358.50  5053.8  362.86  5072.9  367.03
  5113.8  375.73  5163.8  379.97  5193.8  380.45  5223.8  380.00  5293.8  378.01
#Mann=5,-1,0
  4353.5    0.16       0  4545.6    0.12       0  4987.6    0.07       0
  4993.6    0.12       0  5072.9    0.16       0
Bank Sta=4675.6,5012.9
Exp/Cntr=0.3,0.1

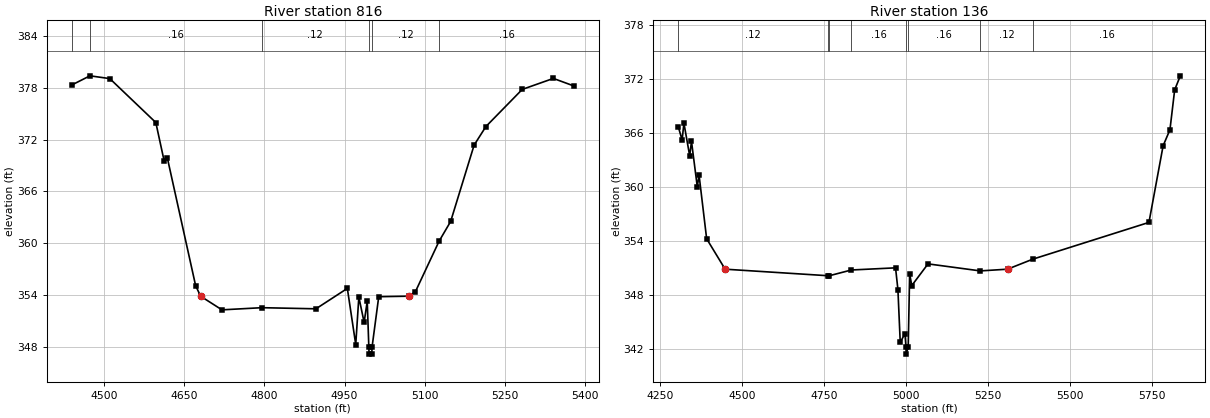
Type RM Length L Ch R = 1,816,680,680,680
BEGIN DESCRIPTION:
Mapping XS d2421057
END DESCRIPTION:
XS GIS Cut Line= 3
      2895112.01      6970737.72      2895411.52      6970223.36
      2895250.07      6969919.84
#Sta/Elev= 30
  4439.8  378.31  4473.8  379.37  4510.9  379.05  4597.0  373.97  4612.7  369.49
  4618.5  369.89  4671.4  355.12  4680.7  353.89  4720.7  352.31  4795.3  352.56
  4896.5  352.43  4955.2  354.79  4970.9  348.30  4976.7  353.79  4986.6  350.86
  4992.4  353.32  4995.4  347.99  4995.9  347.19  5000.9  347.19  5001.4  347.99
  5013.9  353.83  5069.7  353.89  5082.5  354.41  5126.8  360.25  5148.4  362.53
  5192.3  371.36  5214.4  373.51  5282.3  377.80  5340.5  379.07  5378.8  378.20
#Mann=6,-1,0
  4439.8    0.12       0  4473.8    0.16       0  4795.3    0.12       0
  4995.4    0.07       0  5001.4    0.12       0  5126.8    0.16       0
Bank Sta=4680.7,5069.7
Exp/Cntr=0.3,0.1

Type RM Length L Ch R = 1,136,0,0,0
BEGIN DESCRIPTION:
UNT 067 IN DRY CR WATERSHED 1.0
END DESCRIPTION:
XS GIS Cut Line= 4
      2895281.30      6970815.81      2895804.82      6970578.49
      2895928.28      6970427.94      2895335.61      6969949.96
#Sta/Elev= 30
  4305.9  366.68  4317.7  365.20  4323.2  367.07  4340.8  363.44  4346.3  365.04
  4363.9  360.02  4369.4  361.29  4392.5  354.22  4448.9  350.84  4763.9  350.11
  4766.2  350.11  4833.6  350.75  4968.5  350.99  4975.7  348.58  4982.8  342.71
  4997.2  343.68  5000.3  342.20  5000.8  341.40  5007.1  342.20  5011.5  350.33
  5018.0  349.02  5067.5  351.43  5226.9  350.65  5309.9  350.84  5387.5  351.96
  5741.2  356.04  5784.4  364.56  5805.2  366.34  5819.6  370.77  5836.8  372.33
#Mann=8,-1,0
  4305.9    0.12       0  4763.9    0.16       0  4766.2    0.12       0
  4833.6    0.16       0  5000.3    0.07       0  5007.1    0.16       0
  5226.9    0.12       0  5387.5    0.16       0
Bank Sta=4448.9,5309.9
Exp/Cntr=0.3,0.1

Chan Stop Cuts=-1