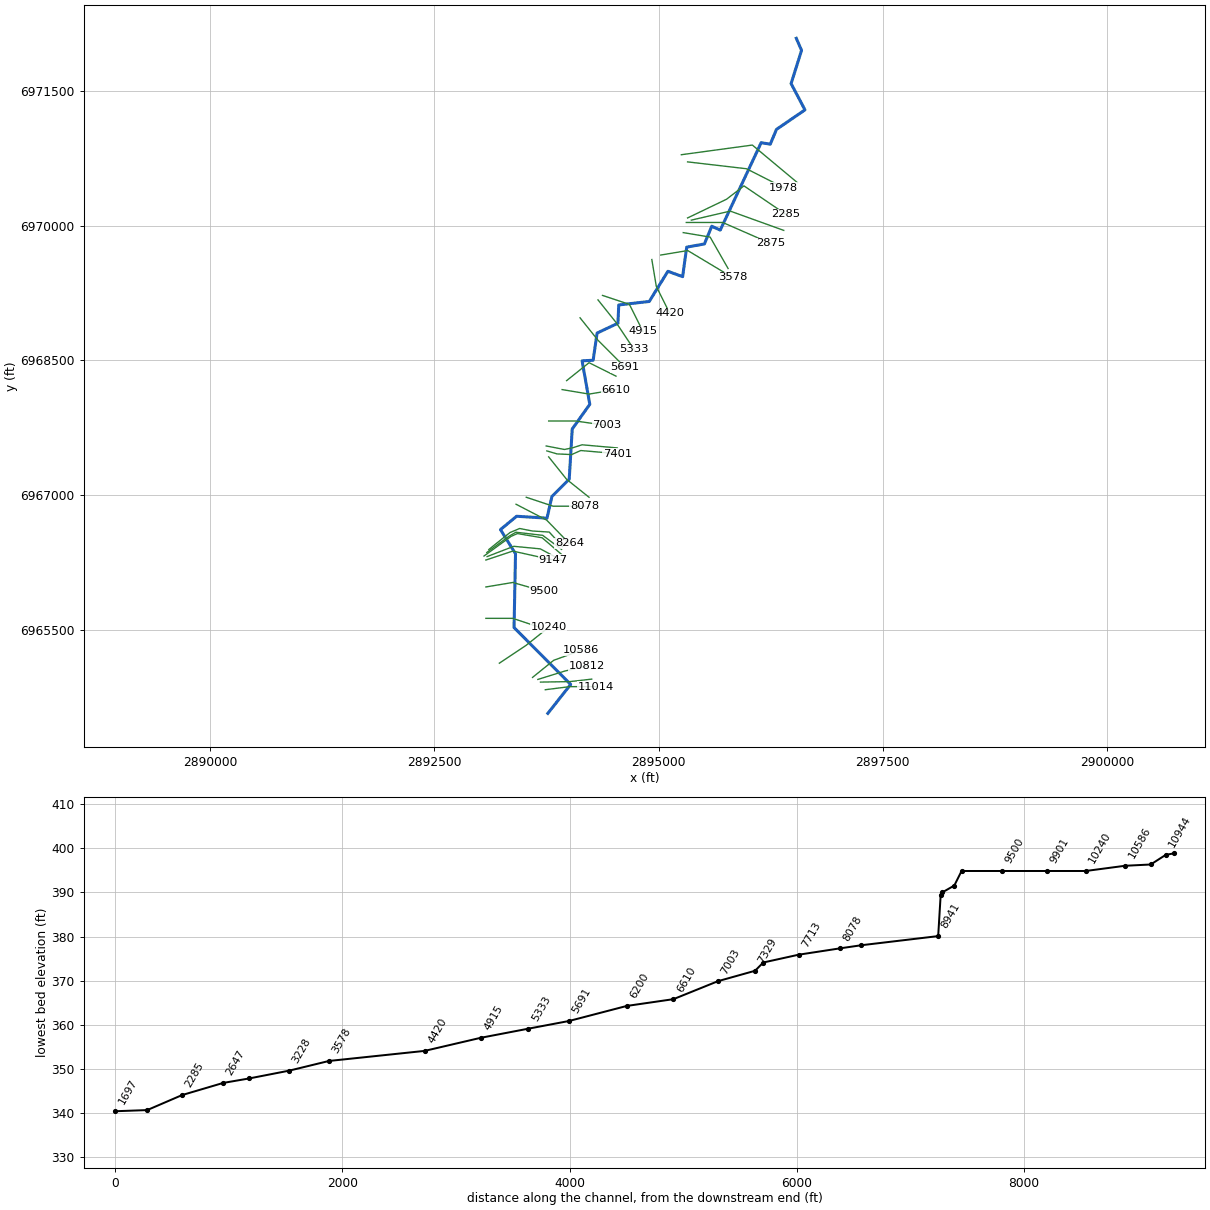
--- UNT 068 IN DRY CR WATERSHED.prj (project) ---

Proj Title=UNT 068 IN DRY CR WATERSHED Base Level Engineering
Current Plan=p01
Default Exp/Contr=0.3,0.1
English Units
Geom File=g01
Flow File=f01
Plan File=p01
BEGIN DESCRIPTION:
UNT 068 IN DRY CR WATERSHED
END DESCRIPTION:

--- UNT 068 IN DRY CR WATERSHED.p01 (plan) ---

Plan Title=Multiple Run
Short Identifier=Multiple
Geom File=g01
Flow File=f01
Subcritical Flow
K Sum by GR= 0
Std Step Tol= 0.01
Critical Tol= 0.01
Num of Std Step Trials= 20
Max Error Tol= 0.3
Flow Tol Ratio= 0.001
Split Flow NTrial= 30
Split Flow Tol= 0.02
Split Flow Ratio= 0.02
Log Output Level= 0
Friction Slope Method= 1
Unsteady Friction Slope Method= 2
Unsteady Bridges Friction Slope Method= 1
Parabolic Critical Depth
Global Vel Dist=  1 , 1 , 1
Global Log Level= 0
CheckData=True
Encroach Param= -1, 0, 0, 0
BEGIN DESCRIPTION:
Multiple Run
END DESCRIPTION:

--- UNT 068 IN DRY CR WATERSHED.f01 (steady flow) ---

Flow Title=Multiple
Number of Profiles=7
Profile Names=10-year,25-year,50-year,1pct_min,100-year,1pct_plu,500-year
River Rch & RM= UNT 068 IN DRY C,Reach-1,11014
     545     733     886     533    1064    2122    1535
River Rch & RM= UNT 068 IN DRY C,Reach-1,2285
     934    1292    1591     974    1943    3876    2902
Boundary for River Rch & Prof#=UNT 068 IN DRY C,Reach-1,1
Up Type=0
Dn Type=3
Dn Slope=0.005
Boundary for River Rch & Prof#=UNT 068 IN DRY C,Reach-1,2
Up Type=0
Dn Type=3
Dn Slope=0.005
Boundary for River Rch & Prof#=UNT 068 IN DRY C,Reach-1,3
Up Type=0
Dn Type=3
Dn Slope=0.005
Boundary for River Rch & Prof#=UNT 068 IN DRY C,Reach-1,4
Up Type=0
Dn Type=3
Dn Slope=0.005
Boundary for River Rch & Prof#=UNT 068 IN DRY C,Reach-1,5
Up Type=0
Dn Type=3
Dn Slope=0.005
Boundary for River Rch & Prof#=UNT 068 IN DRY C,Reach-1,6
Up Type=0
Dn Type=3
Dn Slope=0.005
Boundary for River Rch & Prof#=UNT 068 IN DRY C,Reach-1,7
Up Type=0
Dn Type=3
Dn Slope=0.005

--- UNT 068 IN DRY CR WATERSHED.g01 (geometry) ---

Geom Title=Existing Conditions

River Reach=UNT 068 IN DRY C,Reach-1
Reach XY= 30
      2893765.59      6964565.71      2894020.37      6964888.67
      2893389.13      6965522.17      2893405.37      6966345.56
      2893237.64      6966614.57      2893418.02      6966763.13
      2893756.21      6966741.72      2893811.27      6966983.35
      2894004.08      6967176.46      2894037.60      6967735.51
      2894233.45      6968011.05      2894147.70      6968495.63
      2894270.69      6968502.04      2894314.70      6968805.30
      2894547.23      6968914.90      2894556.21      6969118.75
      2894896.49      6969157.50      2895103.94      6969493.94
      2895268.21      6969434.14      2895313.71      6969762.95
      2895511.32      6969798.73      2895592.80      6969995.85
      2895687.68      6969953.05      2896143.51      6970926.94
      2896245.69      6970911.01      2896314.11      6971075.31
      2896631.95      6971293.12      2896477.55      6971586.41
      2896593.98      6971956.51      2896535.59      6972090.71

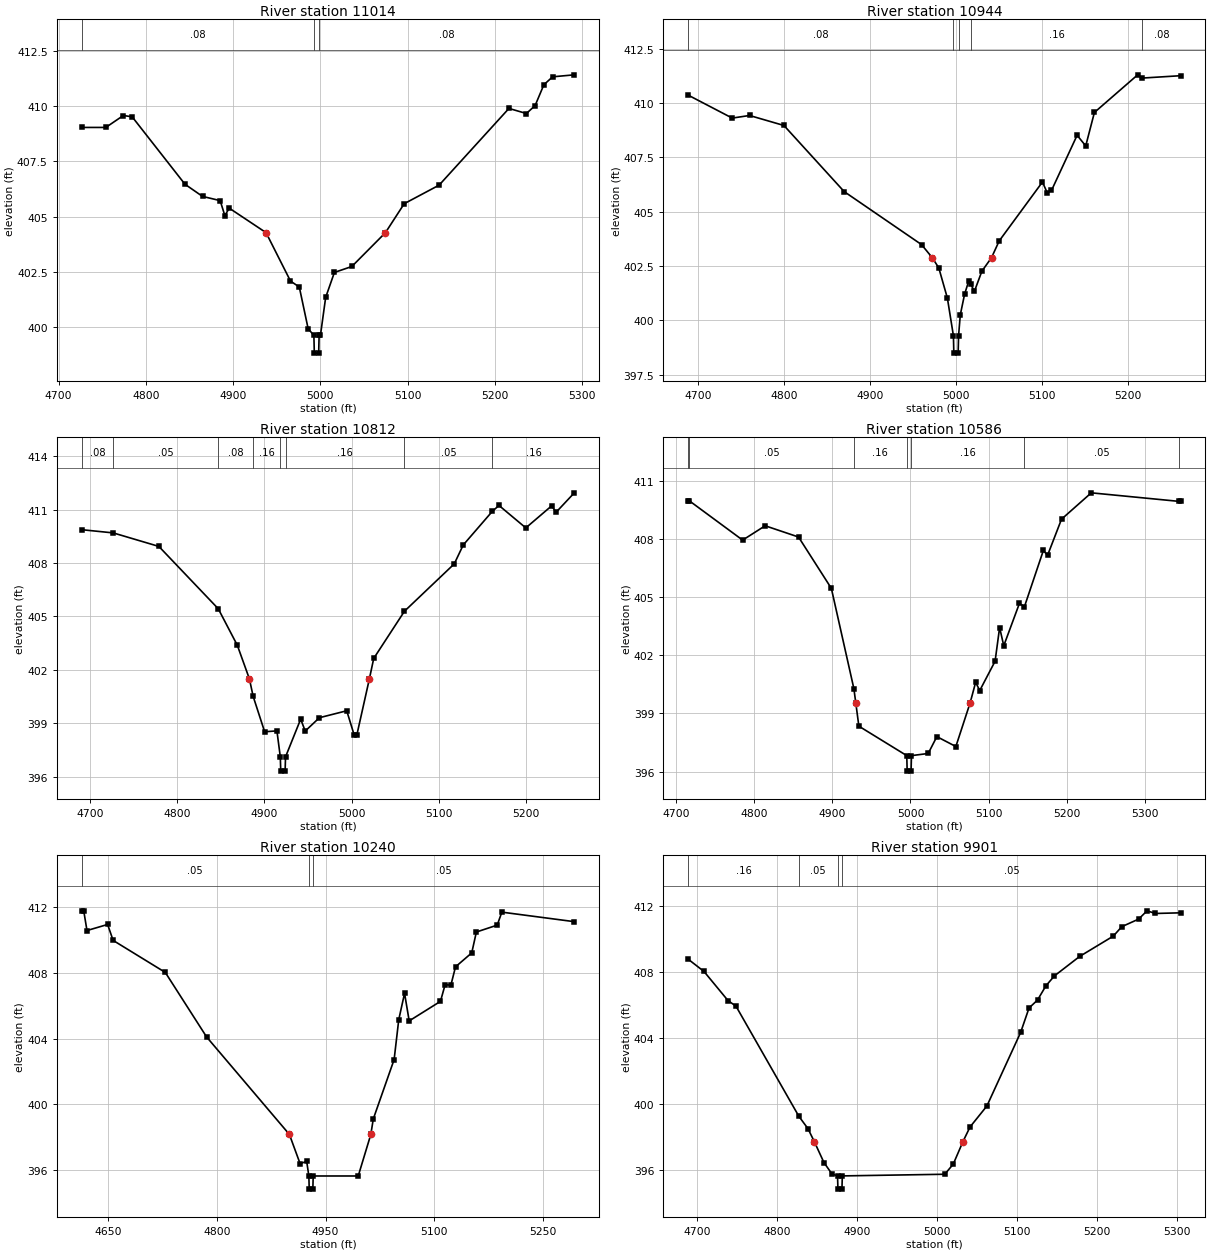
Type RM Length L Ch R = 1,11014,70,70,70
BEGIN DESCRIPTION:
UNT 068 IN DRY CR WATERSHED 21.0
END DESCRIPTION:
XS GIS Cut Line= 3
      2893737.45      6964829.42      2894009.01      6964863.65
      2894299.90      6964864.14
#Sta/Elev= 30
  4726.3  409.03  4754.1  409.03  4774.2  409.57  4784.3  409.51  4844.8  406.46
  4864.9  405.91  4885.1  405.72  4890.5  405.04  4895.5  405.38  4937.7  404.27
  4965.7  402.08  4975.8  401.81  4985.9  399.93  4992.5  399.62  4993.0  398.82
  4998.0  398.82  4998.5  399.62  5000.0  399.62  5006.0  401.34  5016.0  402.47
  5036.0  402.74  5074.5  404.27  5096.0  405.58  5136.0  406.42  5216.0  409.89
  5236.0  409.66  5246.0  410.02  5256.0  410.96  5266.0  411.32  5290.9  411.41
#Mann=3,-1,0
  4726.3    0.08       0  4992.5    0.07       0  4998.5    0.08       0
Bank Sta=4937.7,5074.5
Exp/Cntr=0.3,0.1

Type RM Length L Ch R = 1,10944,132,132,132
BEGIN DESCRIPTION:
Mapping XS d795021a
END DESCRIPTION:
XS GIS Cut Line= 3
      2893683.56      6964914.49      2894009.99      6964919.69
      2894254.75      6964947.47
#Sta/Elev= 30
  4688.4  410.36  4739.8  409.30  4759.9  409.42  4799.9  408.96  4869.9  405.92
  4959.9  403.48  4972.3  402.88  4979.9  402.41  4989.9  401.02  4996.9  399.29
  4997.4  398.49  5002.4  398.49  5002.9  399.29  5004.9  400.25  5009.9  401.20
  5014.9  401.83  5017.2  401.65  5021.3  401.33  5030.0  402.26  5041.2  402.88
  5050.1  403.65  5100.4  406.36  5105.9  405.87  5110.9  405.97  5140.7  408.51
  5150.7  408.02  5160.8  409.56  5211.1  411.29  5216.0  411.14  5261.2  411.25
#Mann=5,-1,0
  4688.4    0.08       0  4996.9    0.07       0  5002.9    0.08       0
  5017.2    0.16       0  5216.0    0.08       0
Bank Sta=4972.3,5041.2
Exp/Cntr=0.3,0.1

Type RM Length L Ch R = 1,10812,226,226,226
BEGIN DESCRIPTION:
Mapping XS 7b408091
END DESCRIPTION:
XS GIS Cut Line= 3
      2893654.10      6964944.00      2893956.17      6965037.75
      2894199.23      6965095.04
#Sta/Elev= 30
  4689.9  409.87  4726.2  409.69  4778.7  408.93  4846.9  405.43  4868.8  403.38
  4882.7  401.49  4887.0  400.51  4900.2  398.52  4914.3  398.57  4918.2  397.11
  4918.7  396.31  4923.7  396.31  4924.2  397.11  4941.6  399.23  4946.8  398.56
  4963.1  399.31  4994.5  399.70  5002.9  398.36  5006.2  398.36  5020.5  401.49
  5025.5  402.64  5060.8  405.29  5118.0  407.95  5128.3  409.01  5161.9  410.91
  5169.4  411.23  5200.2  409.97  5229.9  411.21  5235.0  410.85  5255.9  411.94
#Mann=8,-1,0
  4689.9    0.08       0  4726.2    0.05       0  4846.9    0.08       0
  4887.0    0.16       0  4918.2    0.07       0  4924.2    0.16       0
  5060.8    0.05       0  5161.9    0.16       0
Bank Sta=4882.7,5020.5
Exp/Cntr=0.3,0.1

Type RM Length L Ch R = 1,10586,346,346,346
BEGIN DESCRIPTION:
Mapping XS 308015eb
END DESCRIPTION:
XS GIS Cut Line= 3
      2893595.02      6964966.54      2893831.17      6965157.54
      2894138.48      6965268.66
#Sta/Elev= 30
  4715.4  409.97  4717.0  409.97  4785.3  407.94  4814.1  408.68  4856.8  408.10
  4898.8  405.45  4927.6  400.28  4930.0  399.56  4934.0  398.34  4995.3  396.82
  4995.8  396.02  5000.8  396.02  5001.3  396.82  5022.7  396.93  5033.8  397.80
  5058.1  397.29  5076.5  399.56  5083.4  400.60  5088.7  400.18  5108.3  401.69
  5114.1  403.43  5119.4  402.49  5139.4  404.67  5145.9  404.51  5170.1  407.41
  5175.4  407.15  5193.3  409.02  5231.4  410.38  5343.4  409.94  5345.9  409.94
#Mann=7,-1,0
  4715.4    0.08       0  4717.0    0.05       0  4927.6    0.16       0
  4995.3    0.07       0  5001.3    0.16       0  5145.9    0.05       0
  5343.4    0.16       0
Bank Sta=4930,5076.5
Exp/Cntr=0.3,0.1

Type RM Length L Ch R = 1,10240,339,339,339
BEGIN DESCRIPTION:
UNT 068 IN DRY CR WATERSHED 20.0
END DESCRIPTION:
XS GIS Cut Line= 3
      2893225.01      6965125.01      2893525.00      6965325.00
      2893775.00      6965525.00
#Sta/Elev= 30
  4612.9  411.78  4615.9  411.78  4620.4  410.58  4648.9  410.95  4656.5  409.98
  4728.6  408.03  4785.7  404.10  4900.0  398.17  4914.8  396.39  4923.9  396.53
  4926.9  395.64  4927.4  394.84  4932.4  394.84  4932.9  395.64  4995.1  395.64
  5012.5  398.17  5015.9  399.11  5044.7  402.73  5051.1  405.16  5059.1  406.76
  5065.5  405.08  5108.7  406.27  5115.1  407.28  5123.1  407.26  5129.5  408.37
  5151.9  409.22  5158.3  410.49  5187.1  410.91  5193.5  411.70  5293.6  411.12
#Mann=3,-1,0
  4612.9    0.05       0  4926.9    0.03       0  4932.9    0.05       0
Bank Sta=4900,5012.5
Exp/Cntr=0.3,0.1

Type RM Length L Ch R = 1,9901,401,401,401
BEGIN DESCRIPTION:
UNT 068 IN DRY CR WATERSHED 19.0
END DESCRIPTION:
XS GIS Cut Line= 3
      2893074.96      6965625.00      2893375.00      6965625.00
      2893675.03      6965524.99
#Sta/Elev= 30
  4688.9  408.76  4708.9  408.01  4738.9  406.25  4748.9  405.91  4827.5  399.25
  4838.9  398.50  4846.8  397.72  4858.9  396.45  4868.9  395.76  4875.9  395.64
  4876.4  394.84  4881.4  394.84  4881.9  395.64  5010.0  395.74  5020.6  396.35
  5032.8  397.72  5041.6  398.60  5062.7  399.87  5104.9  404.32  5115.4  405.80
  5126.0  406.28  5136.5  407.14  5147.1  407.74  5178.7  408.92  5220.8  410.15
  5231.4  410.72  5252.5  411.18  5263.0  411.68  5273.5  411.52  5305.2  411.56
#Mann=4,-1,0
  4688.9    0.16       0  4827.5    0.05       0  4875.9   0.033       0
  4881.9    0.05       0
Bank Sta=4846.8,5032.8
Exp/Cntr=0.3,0.1

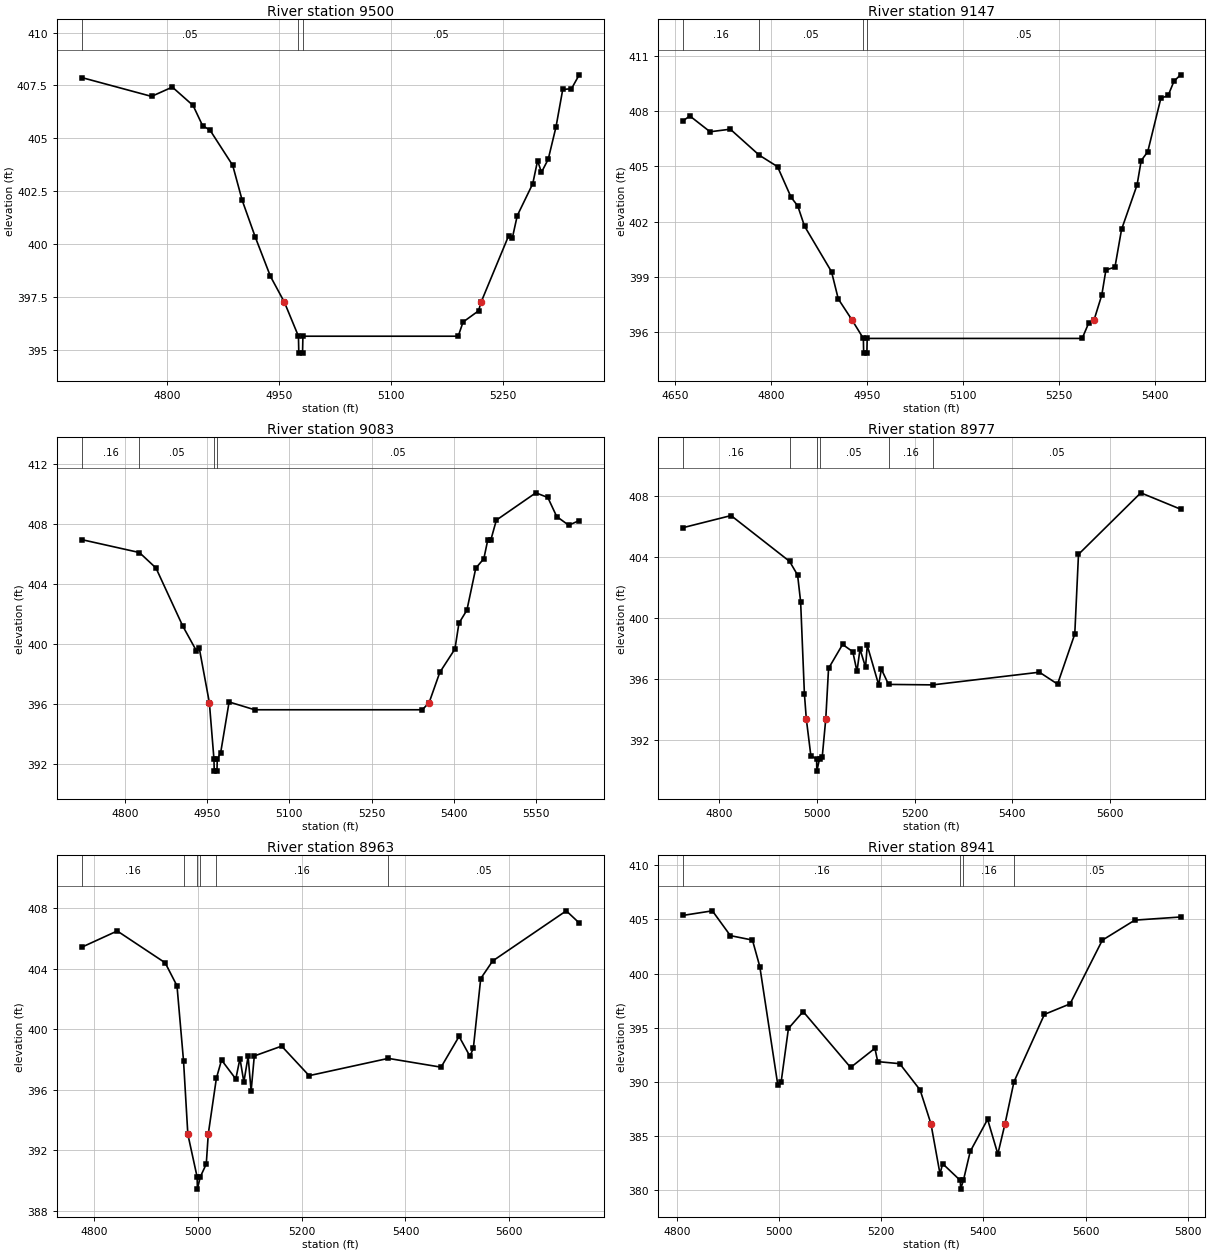
Type RM Length L Ch R = 1,9500,353,353,353
BEGIN DESCRIPTION:
UNT 068 IN DRY CR WATERSHED 18.0
END DESCRIPTION:
XS GIS Cut Line= 3
      2893075.04      6965975.01      2893375.00      6966025.00
      2893725.00      6965925.00
#Sta/Elev= 30
  4684.9  407.87  4778.6  406.98  4806.5  407.42  4834.4  406.55  4847.1  405.60
  4857.2  405.38  4887.6  403.72  4900.3  402.07  4918.0  400.32  4938.3  398.47
  4957.0  397.25  4975.9  395.64  4976.4  394.84  4981.4  394.84  4981.9  395.64
  5190.5  395.64  5197.0  396.31  5217.8  396.84  5221.2  397.25  5258.1  400.38
  5263.3  400.30  5269.8  401.34  5290.6  402.85  5297.1  403.94  5302.3  403.39
  5311.4  404.01  5321.8  405.53  5330.9  407.31  5342.6  407.34  5353.0  408.00
#Mann=3,-1,0
  4684.9    0.05       0  4975.9   0.033       0  4981.9    0.05       0
Bank Sta=4957,5221.2
Exp/Cntr=0.3,0.1

Type RM Length L Ch R = 1,9147,64,64,64
BEGIN DESCRIPTION:
UNT 068 IN DRY CR WATERSHED 17.0
END DESCRIPTION:
XS GIS Cut Line= 3
      2893075.05      6966275.02      2893375.00      6966375.00
      2893825.04      6966274.99
#Sta/Elev= 30
  4663.0  407.49  4673.5  407.75  4705.1  406.89  4736.7  407.03  4781.8  405.62
  4810.5  404.99  4831.6  403.33  4842.1  402.85  4852.7  401.75  4894.9  399.27
  4905.4  397.79  4926.8  396.65  4944.6  395.64  4945.1  394.84  4950.1  394.84
  4950.6  395.64  5286.5  395.64  5296.7  396.48  5305.1  396.65  5317.2  398.01
  5323.6  399.37  5337.7  399.52  5348.0  401.57  5372.3  404.00  5378.7  405.32
  5388.9  405.80  5409.4  408.71  5420.9  408.87  5429.9  409.64  5440.2  409.99
#Mann=4,-1,0
  4663.0    0.16       0  4781.8    0.05       0  4944.6   0.033       0
  4950.6    0.05       0
Bank Sta=4926.8,5305.1
Exp/Cntr=0.3,0.1

Type RM Length L Ch R = 1,9083,106,106,106
BEGIN DESCRIPTION:
Mapping XS bdeab09c
END DESCRIPTION:
XS GIS Cut Line= 4
      2893088.90      6966313.57      2893385.73      6966428.14
      2893682.60      6966399.49      2893937.84      6966261.45
#Sta/Elev= 30
  4721.6  406.98  4826.6  406.12  4856.8  405.09  4905.5  401.23  4930.2  399.59
  4935.5  399.79  4954.1  396.12  4962.5  392.35  4963.0  391.55  4968.0  391.55
  4968.5  392.35  4974.7  392.77  4990.1  396.16  5036.7  395.64  5342.2  395.64
  5354.7  396.12  5374.1  398.13  5401.7  399.69  5409.0  401.41  5423.5  402.28
  5439.7  405.08  5454.4  405.71  5461.6  406.97  5467.3  406.98  5477.2  408.28
  5549.1  410.10  5571.0  409.79  5587.2  408.52  5609.1  407.94  5628.2  408.25
#Mann=4,-1,0
  4721.6    0.16       0  4826.6    0.05       0  4962.5    0.03       0
  4968.5    0.05       0
Bank Sta=4954.1,5354.7
Exp/Cntr=0.3,0.1

Type RM Length L Ch R = 1,8977,14,14,14
BEGIN DESCRIPTION:
Mapping XS 0c5f2557
END DESCRIPTION:
XS GIS Cut Line= 5
      2893054.11      6966319.96      2893356.22      6966538.73
      2893426.53      6966569.98      2893702.57      6966523.10
      2893920.68      6966336.15
#Sta/Elev= 30
  4726.7  405.94  4824.7  406.73  4944.4  403.73  4960.8  402.83  4967.0  401.08
  4974.7  395.06  4978.6  393.41  4987.9  391.00  4999.6  390.79  5000.1  389.99
  5005.6  390.79  5011.1  390.90  5018.4  393.41  5024.1  396.72  5052.8  398.29
  5073.7  397.81  5082.2  396.52  5088.4  397.98  5099.7  396.80  5103.3  398.22
  5126.6  395.64  5132.1  396.67  5146.8  395.67  5237.0  395.64  5455.3  396.47
  5492.4  395.69  5527.6  398.97  5535.2  404.19  5662.6  408.22  5743.9  407.15
#Mann=6,-1,0
  4726.7    0.16       0  4944.4    0.05       0  4999.6    0.03       0
  5005.6    0.05       0  5146.8    0.16       0  5237.0    0.05       0
Bank Sta=4978.6,5018.4
Exp/Cntr=0.3,0.1

Type RM Length L Ch R = 1,8963,22,22,22
BEGIN DESCRIPTION:
Mapping XS c00be276
END DESCRIPTION:
XS GIS Cut Line= 5
      2893085.23      6966359.40      2893335.21      6966541.68
      2893409.86      6966585.08      2893708.47      6966550.36
      2893918.57      6966394.09
#Sta/Elev= 30
  4776.5  405.41  4844.8  406.48  4937.1  404.38  4959.9  402.86  4972.5  397.90
  4980.8  393.06  4998.7  390.24  4999.2  389.44  5004.7  390.24  5016.3  391.10
  5020.2  393.09  5035.8  396.76  5045.7  397.96  5073.2  396.71  5081.2  398.06
  5088.7  396.51  5096.9  398.20  5102.7  395.91  5108.8  398.23  5161.5  398.88
  5214.4  396.93  5366.9  398.07  5468.6  397.49  5503.3  399.52  5524.2  398.21
  5530.8  398.75  5545.0  403.34  5568.0  404.50  5709.8  407.81  5734.7  407.01
#Mann=6,-1,0
  4776.5    0.16       0  4972.5    0.05       0  4998.7    0.03       0
  5004.7    0.05       0  5035.8    0.16       0  5366.9    0.05       0
Bank Sta=4980.8,5020.2
Exp/Cntr=0.3,0.1

Type RM Length L Ch R = 1,8941,677,677,677
BEGIN DESCRIPTION:
Mapping XS e2780182
END DESCRIPTION:
XS GIS Cut Line= 6
      2893107.76      6966392.36      2893343.89      6966581.61
      2893451.53      6966626.75      2893592.15      6966598.97
      2893781.39      6966586.82      2893930.36      6966423.99
#Sta/Elev= 30
  4812.6  405.37  4869.8  405.79  4905.0  403.50  4948.2  403.09  4962.6  400.64
  4997.8  389.71  5004.2  389.95  5018.6  394.93  5047.4  396.49  5140.2  391.33
  5187.8  393.10  5193.2  391.87  5236.3  391.68  5276.2  389.25  5297.3  386.14
  5315.1  381.50  5320.2  382.45  5354.8  380.90  5355.3  380.10  5360.8  380.90
  5374.2  383.58  5408.2  386.54  5428.2  383.34  5442.3  386.14  5459.7  390.00
  5519.3  396.23  5569.5  397.20  5632.6  403.08  5696.1  404.93  5785.6  405.22
#Mann=4,-1,0
  4812.6    0.16       0  5354.8    0.07       0  5360.8    0.16       0
  5459.7    0.05       0
Bank Sta=5297.3,5442.3
Exp/Cntr=0.3,0.1

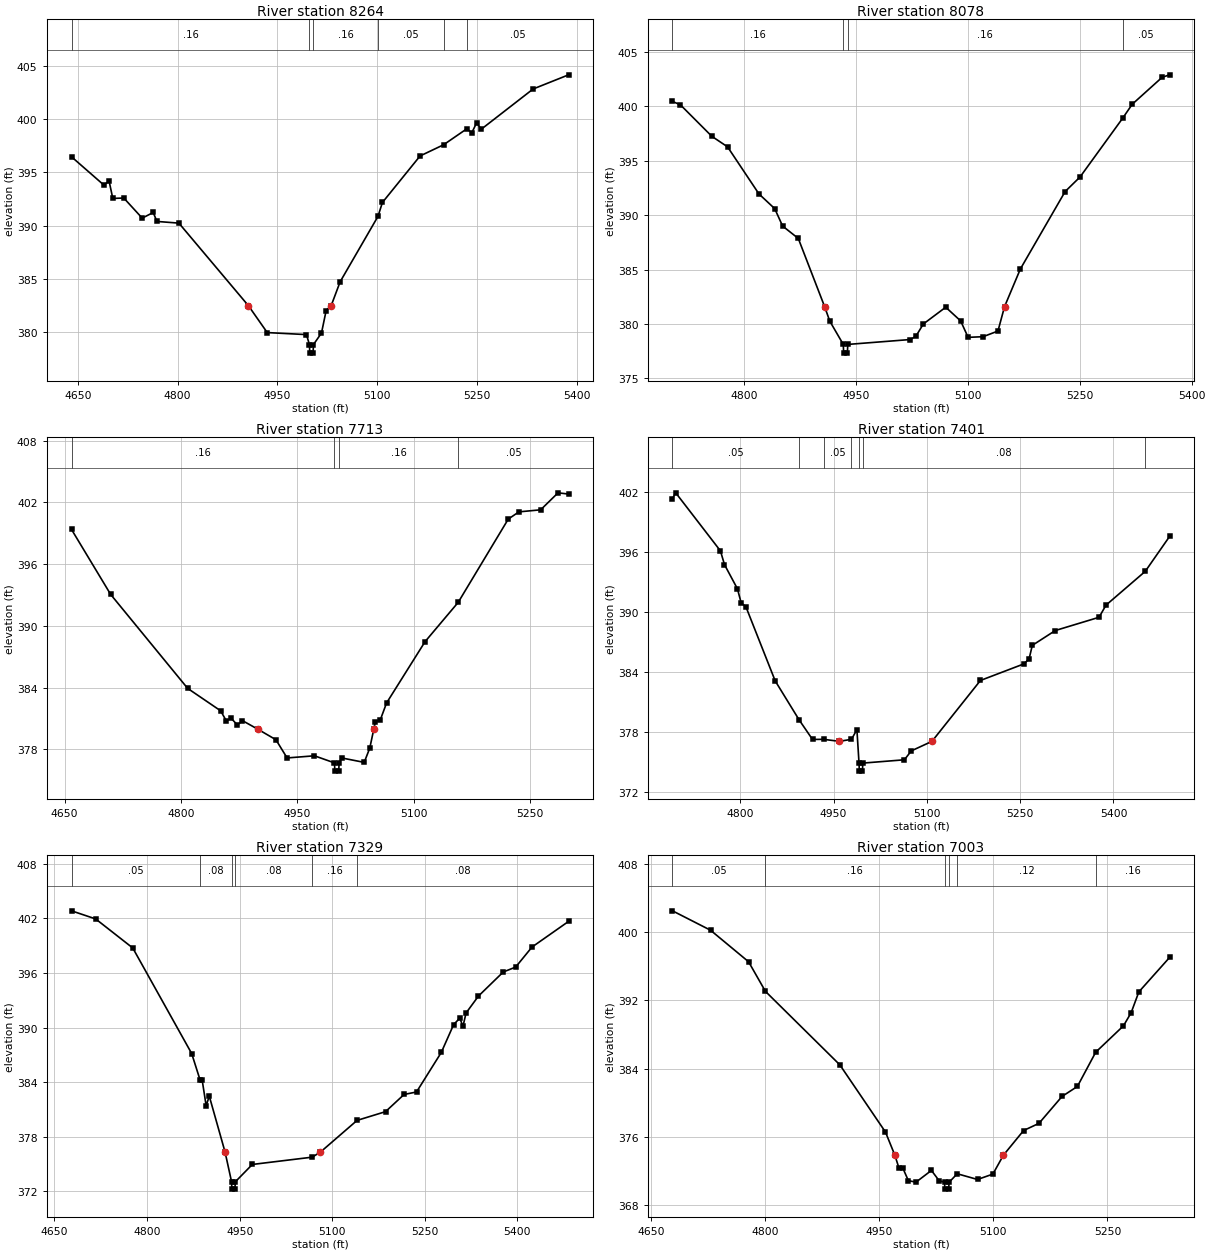
Type RM Length L Ch R = 1,8264,186,186,186
BEGIN DESCRIPTION:
Mapping XS 11385dad
END DESCRIPTION:
XS GIS Cut Line= 3
      2893411.77      6966896.89      2893752.92      6966719.80
      2894005.19      6966459.73
#Sta/Elev= 30
  4640.7  396.47  4689.4  393.81  4697.1  394.20  4702.7  392.56  4719.2  392.60
  4746.9  390.71  4763.4  391.24  4769.0  390.40  4802.0  390.24  4906.5  382.48
  4934.7  379.96  4993.6  379.77  4998.1  378.83  4998.6  378.03  5003.6  378.03
  5004.1  378.83  5016.2  379.92  5023.2  382.03  5030.7  382.48  5044.2  384.73
  5101.1  390.88  5107.7  392.18  5164.3  396.55  5199.6  397.60  5234.5  399.10
  5242.0  398.73  5249.2  399.66  5256.2  399.06  5334.1  402.84  5387.4  404.17
#Mann=6,-1,0
  4640.7    0.16       0  4998.1    0.07       0  5004.1    0.16       0
  5101.1    0.05       0  5199.6    0.16       0  5234.5    0.05       0
Bank Sta=4906.5,5030.7
Exp/Cntr=0.3,0.1

Type RM Length L Ch R = 1,8078,365,365,365
BEGIN DESCRIPTION:
UNT 068 IN DRY CR WATERSHED 14.0
END DESCRIPTION:
XS GIS Cut Line= 3
      2893525.02      6966974.99      2893825.00      6966875.00
      2894174.99      6966875.00
#Sta/Elev= 30
  4704.2  400.46  4714.7  400.16  4756.9  397.26  4778.0  396.29  4820.1  391.96
  4841.2  390.61  4851.8  389.01  4872.8  387.87  4908.1  381.60  4915.0  380.27
  4933.1  378.13  4933.6  377.33  4938.6  377.33  4939.1  378.13  5022.9  378.58
  5030.4  378.88  5040.4  380.01  5070.4  381.55  5090.4  380.29  5100.4  378.78
  5120.4  378.84  5140.4  379.36  5149.2  381.60  5170.4  385.06  5230.4  392.18
  5250.4  393.52  5307.4  398.91  5320.4  400.21  5360.4  402.68  5370.4  402.91
#Mann=4,-1,0
  4704.2    0.16       0  4933.1    0.07       0  4939.1    0.16       0
  5307.4    0.05       0
Bank Sta=4908.1,5149.2
Exp/Cntr=0.3,0.1

Type RM Length L Ch R = 1,7713,312,312,312
BEGIN DESCRIPTION:
UNT 068 IN DRY CR WATERSHED 13.0
END DESCRIPTION:
XS GIS Cut Line= 3
      2893775.02      6967424.98      2893975.00      6967175.00
      2894225.01      6966974.99
#Sta/Elev= 30
  4659.0  399.37  4709.4  393.06  4808.6  383.93  4851.1  381.75  4858.3  380.78
  4864.7  381.02  4872.7  380.37  4879.1  380.80  4898.6  379.98  4922.3  378.94
  4936.7  377.17  4971.9  377.38  4997.7  376.69  4998.2  375.89  5003.2  375.89
  5003.7  376.69  5007.1  377.17  5036.0  376.74  5043.2  378.13  5048.4  379.98
  5050.4  380.69  5056.8  380.88  5064.8  382.51  5114.4  388.47  5157.1  392.29
  5221.6  400.38  5235.3  401.08  5263.3  401.28  5285.7  402.93  5299.3  402.81
#Mann=4,-1,0
  4659.0    0.16       0  4997.7    0.07       0  5003.7    0.16       0
  5157.1    0.05       0
Bank Sta=4898.6,5048.4
Exp/Cntr=0.3,0.1

Type RM Length L Ch R = 1,7401,72,72,72
BEGIN DESCRIPTION:
Mapping XS 823d4123
END DESCRIPTION:
XS GIS Cut Line= 5
      2893754.82      6967491.43      2893868.13      6967458.01
      2894030.86      6967450.75      2894132.58      6967495.79
      2894538.01      6967460.92
#Sta/Elev= 30
  4691.0  401.30  4696.2  401.87  4768.1  396.08  4774.6  394.71  4795.4  392.30
  4801.4  390.90  4809.1  390.50  4856.1  383.12  4894.6  379.23  4916.1  377.28
  4934.0  377.29  4959.2  377.09  4978.8  377.29  4987.5  378.26  4990.9  374.92
  4991.4  374.12  4996.4  374.12  4996.9  374.92  5063.8  375.25  5075.0  376.14
  5108.2  377.09  5186.1  383.16  5256.3  384.82  5264.4  385.33  5269.5  386.66
  5306.5  388.14  5376.8  389.46  5388.0  390.67  5451.1  394.04  5490.2  397.52
#Mann=7,-1,0
  4691.0    0.05       0  4894.6    0.08       0  4934.0    0.05       0
  4978.8    0.08       0  4990.9    0.07       0  4996.9    0.08       0
  5451.1    0.05       0
Bank Sta=4959.2,5108.2
Exp/Cntr=0.3,0.1

Type RM Length L Ch R = 1,7329,326,326,326
BEGIN DESCRIPTION:
Mapping XS 92174b9b
END DESCRIPTION:
XS GIS Cut Line= 5
      2893747.57      6967546.64      2893950.95      6967507.42
      2894042.49      6967526.31      2894147.11      6967559.73
      2894540.45      6967524.89
#Sta/Elev= 30
  4677.6  402.82  4716.7  401.93  4776.8  398.74  4872.3  387.14  4886.0  384.21
  4889.3  384.21  4895.7  381.42  4900.8  382.46  4926.4  376.31  4936.9  373.05
  4937.4  372.25  4942.4  372.25  4942.9  373.05  4970.5  374.96  5067.4  375.76
  5080.7  376.31  5140.2  379.80  5186.3  380.76  5216.4  382.65  5236.5  382.92
  5276.6  387.26  5296.7  390.33  5306.7  391.04  5311.7  390.12  5316.8  391.60
  5336.9  393.46  5377.0  396.10  5397.1  396.64  5423.6  398.84  5482.9  401.66
#Mann=6,-1,0
  4677.6    0.05       0  4886.0    0.08       0  4936.9    0.07       0
  4942.9    0.08       0  5067.4    0.16       0  5140.2    0.08       0
Bank Sta=4926.4,5080.7
Exp/Cntr=0.3,0.1

Type RM Length L Ch R = 1,7003,393,393,393
BEGIN DESCRIPTION:
UNT 068 IN DRY CR WATERSHED 11.0
END DESCRIPTION:
XS GIS Cut Line= 3
      2893775.02      6967825.00      2894075.00      6967825.00
      2894424.97      6967775.00
#Sta/Elev= 30
  4678.2  402.48  4728.2  400.21  4778.2  396.52  4800.4  393.05  4898.2  384.45
  4958.2  376.58  4970.5  373.88  4975.7  372.43  4980.7  372.43  4988.3  370.89
  4998.4  370.72  5018.6  372.09  5028.7  370.89  5035.8  370.70  5036.3  369.90
  5041.3  369.90  5041.8  370.70  5052.5  371.70  5079.2  371.03  5099.4  371.66
  5113.3  373.88  5139.8  376.76  5160.0  377.60  5190.3  380.75  5210.5  381.92
  5234.6  385.93  5271.1  389.02  5281.2  390.56  5291.3  392.99  5331.7  397.02
#Mann=6,-1,0
  4678.2    0.05       0  4800.4    0.16       0  5035.8    0.07       0
  5041.8    0.16       0  5052.5    0.12       0  5234.6    0.16       0
Bank Sta=4970.5,5113.3
Exp/Cntr=0.3,0.1

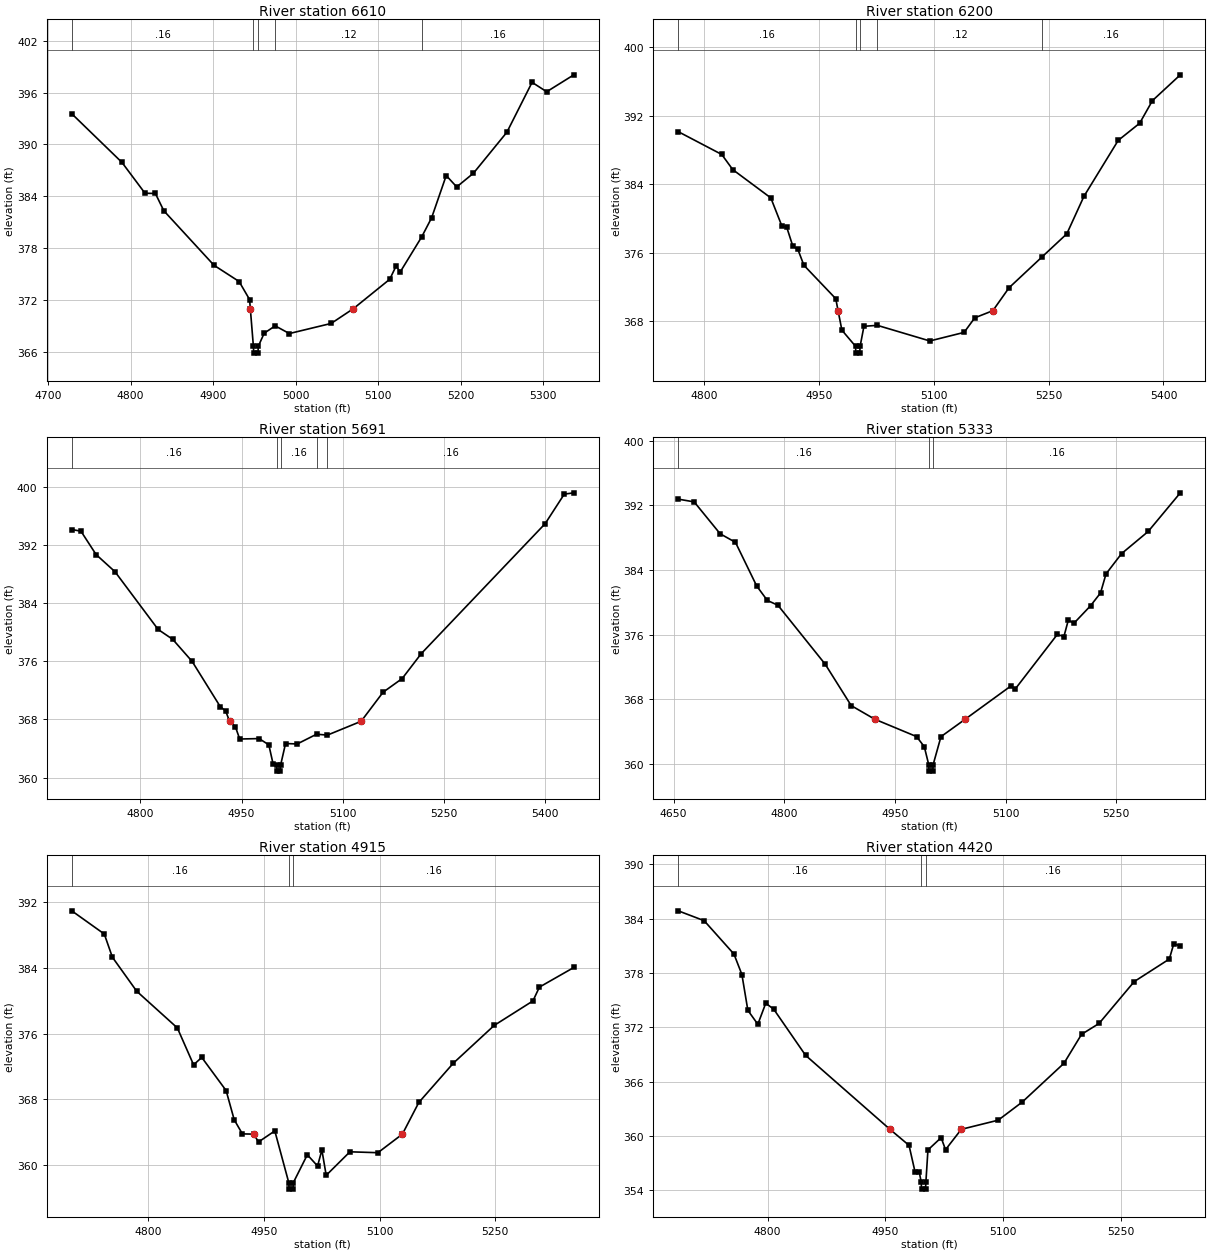
Type RM Length L Ch R = 1,6610,410,410,410
BEGIN DESCRIPTION:
UNT 068 IN DRY CR WATERSHED 10.0
END DESCRIPTION:
XS GIS Cut Line= 3
      2893925.03      6968174.99      2894225.00      6968125.00
      2894524.96      6968174.99
#Sta/Elev= 30
  4728.8  393.56  4789.6  387.92  4817.5  384.35  4830.1  384.32  4840.3  382.32
  4901.1  376.00  4931.5  374.12  4944.2  372.03  4945.1  370.97  4948.8  366.62
  4949.3  365.82  4954.3  365.82  4954.8  366.62  4961.9  368.13  4975.2  368.98
  4992.4  368.09  5043.0  369.26  5069.9  370.97  5114.0  374.38  5121.6  375.90
  5126.7  375.23  5152.7  379.29  5164.7  381.50  5182.4  386.40  5195.1  385.08
  5215.4  386.67  5255.9  391.42  5286.4  397.20  5304.1  396.11  5337.0  398.07
#Mann=5,-1,0
  4728.8    0.16       0  4948.8    0.07       0  4954.8    0.16       0
  4975.2    0.12       0  5152.7    0.16       0
Bank Sta=4945.1,5069.9
Exp/Cntr=0.3,0.1

Type RM Length L Ch R = 1,6200,509,509,509
BEGIN DESCRIPTION:
UNT 068 IN DRY CR WATERSHED 9.0
END DESCRIPTION:
XS GIS Cut Line= 3
      2893974.99      6968274.99      2894225.00      6968475.00
      2894525.02      6968324.99
#Sta/Elev= 30
  4766.4  390.13  4823.2  387.47  4837.6  385.70  4887.3  382.40  4901.7  379.13
  4908.1  378.97  4916.1  376.75  4922.5  376.42  4930.5  374.54  4972.1  370.64
  4975.1  369.24  4980.1  366.97  4997.9  365.09  4998.4  364.29  5003.4  364.29
  5003.9  365.09  5008.9  367.42  5026.4  367.53  5094.9  365.71  5139.7  366.71
  5153.6  368.41  5177.2  369.24  5198.4  371.92  5240.9  375.47  5273.8  378.21
  5296.2  382.59  5340.9  389.11  5368.9  391.11  5385.6  393.75  5422.0  396.76
#Mann=5,-1,0
  4766.4    0.16       0  4997.9    0.07       0  5003.9    0.16       0
  5026.4    0.12       0  5240.9    0.16       0
Bank Sta=4975.1,5177.2
Exp/Cntr=0.3,0.1

Type RM Length L Ch R = 1,5691,358,358,358
BEGIN DESCRIPTION:
UNT 068 IN DRY CR WATERSHED 8.0
END DESCRIPTION:
XS GIS Cut Line= 3
      2894124.97      6968975.03      2894325.00      6968725.00
      2894625.03      6968424.97
#Sta/Elev= 30
  4698.2  394.14  4711.8  393.91  4734.3  390.69  4762.3  388.33  4826.3  380.38
  4847.9  379.02  4876.7  375.98  4918.3  369.77  4926.4  369.15  4932.2  367.74
  4940.8  367.00  4947.2  365.30  4976.0  365.36  4990.4  364.50  4996.8  361.84
  5001.8  361.68  5002.3  360.88  5007.3  360.88  5007.8  361.68  5015.2  364.68
  5032.5  364.62  5061.2  365.96  5077.3  365.84  5127.3  367.74  5159.8  371.74
  5188.1  373.62  5216.4  377.05  5400.2  394.95  5428.5  399.01  5442.7  399.19
#Mann=5,-1,0
  4698.2    0.16       0  5001.8    0.07       0  5007.8    0.16       0
  5061.2    0.12       0  5077.3    0.16       0
Bank Sta=4932.2,5127.3
Exp/Cntr=0.3,0.1

Type RM Length L Ch R = 1,5333,418,418,418
BEGIN DESCRIPTION:
UNT 068 IN DRY CR WATERSHED 7.0
END DESCRIPTION:
XS GIS Cut Line= 3
      2894325.03      6969174.97      2894525.00      6968925.00
      2894725.02      6968624.97
#Sta/Elev= 30
  4656.2  392.76  4677.8  392.42  4713.0  388.48  4733.8  387.42  4762.6  382.02
  4777.0  380.24  4791.4  379.64  4855.5  372.35  4890.7  367.24  4922.6  365.56
  4979.3  363.41  4989.8  362.16  4995.8  359.94  4996.3  359.14  5001.3  359.14
  5001.8  359.94  5012.4  363.40  5045.3  365.56  5107.0  369.65  5113.0  369.28
  5170.1  376.03  5179.1  375.78  5185.1  377.82  5192.6  377.41  5215.2  379.58
  5228.7  381.16  5236.2  383.52  5257.2  386.02  5293.3  388.76  5336.9  393.54
#Mann=3,-1,0
  4656.2    0.16       0  4995.8    0.07       0  5001.8    0.16       0
Bank Sta=4922.6,5045.3
Exp/Cntr=0.3,0.1

Type RM Length L Ch R = 1,4915,495,495,495
BEGIN DESCRIPTION:
UNT 068 IN DRY CR WATERSHED 6.0
END DESCRIPTION:
XS GIS Cut Line= 3
      2894375.00      6969225.00      2894675.00      6969125.00
      2894824.98      6968825.04
#Sta/Elev= 30
  4700.6  390.93  4742.8  388.11  4753.3  385.29  4784.9  381.15  4837.6  376.69
  4858.7  372.20  4869.3  373.10  4900.9  369.07  4911.4  365.52  4922.0  363.80
  4936.6  363.77  4943.0  362.82  4964.1  364.16  4982.2  357.88  4982.7  357.08
  4987.7  357.08  4988.2  357.88  5006.3  361.26  5019.6  359.89  5025.2  361.84
  5030.8  358.76  5061.6  361.62  5097.9  361.51  5129.7  363.77  5151.0  367.62
  5195.7  372.39  5248.8  376.99  5299.1  379.97  5307.5  381.65  5352.2  384.04
#Mann=3,-1,0
  4700.6    0.16       0  4982.2    0.07       0  4988.2    0.16       0
Bank Sta=4936.6,5129.7
Exp/Cntr=0.3,0.1

Type RM Length L Ch R = 1,4420,842,842,842
BEGIN DESCRIPTION:
UNT 068 IN DRY CR WATERSHED 5.0
END DESCRIPTION:
XS GIS Cut Line= 3
      2894925.00      6969625.01      2894975.00      6969325.00
      2895125.02      6969024.96
#Sta/Elev= 30
  4686.1  384.87  4719.1  383.78  4757.1  380.09  4767.2  377.83  4774.8  373.87
  4787.5  372.33  4797.6  374.66  4807.8  373.99  4848.3  368.90  4955.8  360.72
  4980.1  358.95  4987.7  356.04  4993.0  356.04  4995.6  354.91  4996.1  354.11
  5001.1  354.11  5001.6  354.91  5004.2  358.44  5021.0  359.80  5026.6  358.47
  5046.7  360.72  5093.7  361.73  5124.4  363.74  5177.5  368.02  5199.9  371.22
  5222.2  372.42  5267.0  377.05  5311.7  379.54  5317.3  381.21  5325.7  381.00
#Mann=3,-1,0
  4686.1    0.16       0  4995.6    0.07       0  5001.6    0.16       0
Bank Sta=4955.8,5046.7
Exp/Cntr=0.3,0.1

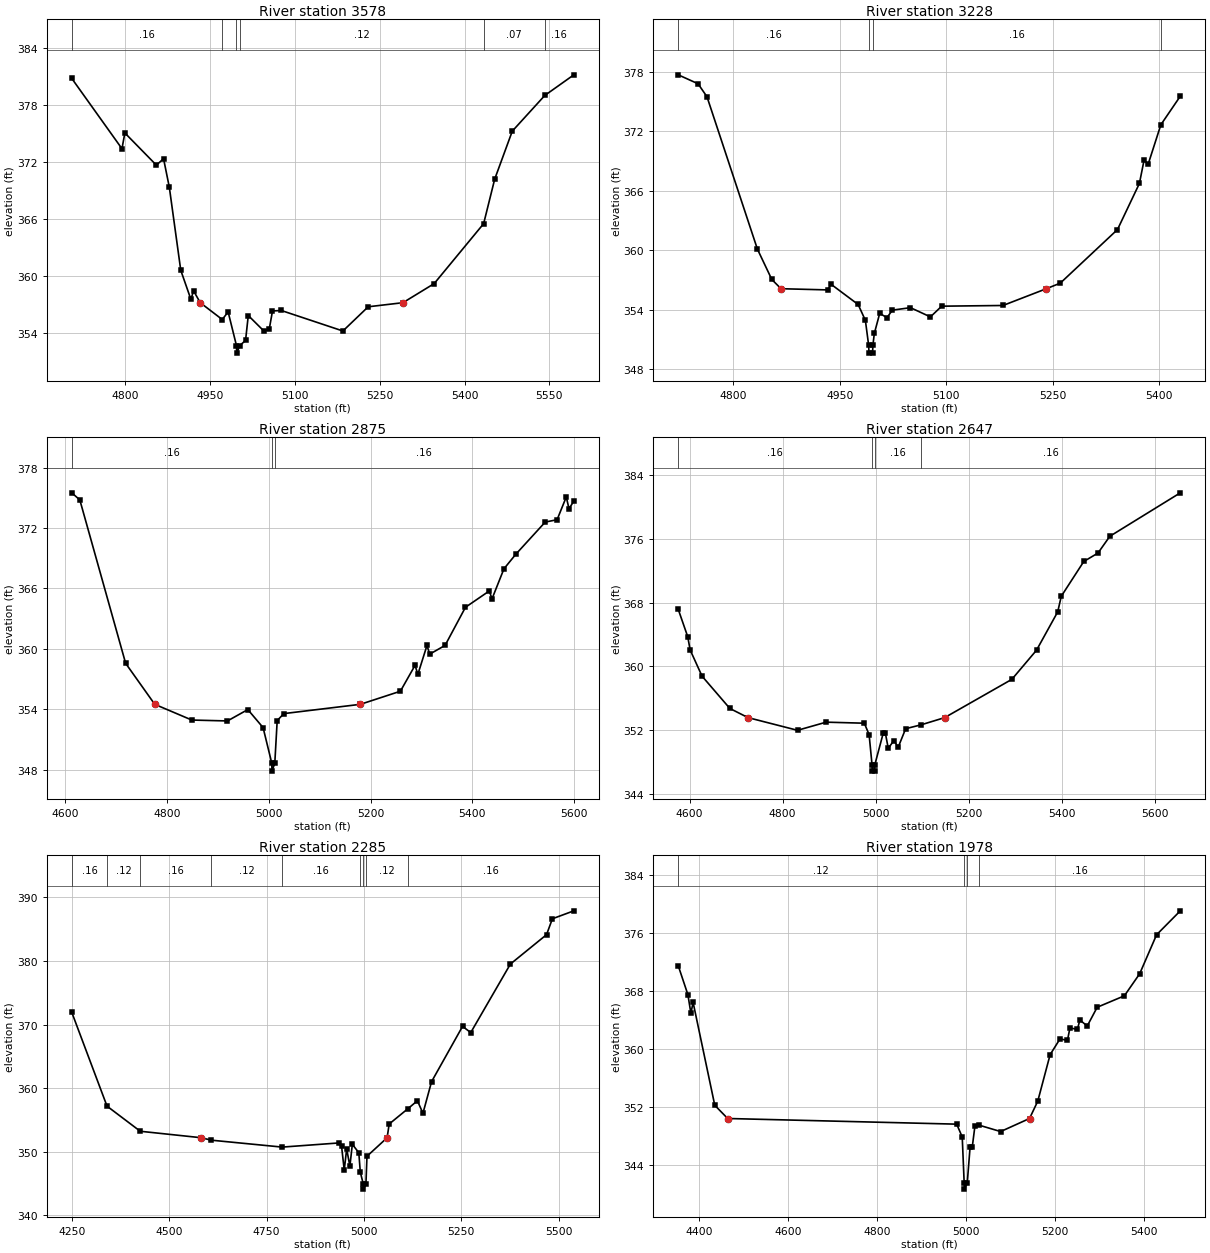
Type RM Length L Ch R = 1,3578,350,350,350
BEGIN DESCRIPTION:
UNT 068 IN DRY CR WATERSHED 4.0
END DESCRIPTION:
XS GIS Cut Line= 3
      2895024.99      6969675.00      2895325.00      6969725.00
      2895824.96      6969425.02
#Sta/Elev= 30
  4706.0  380.75  4794.7  373.35  4799.8  375.01  4855.5  371.62  4868.2  372.30
  4878.4  369.29  4898.6  360.55  4916.4  357.51  4921.4  358.37  4933.0  357.14
  4971.9  355.37  4982.3  356.17  4997.0  352.63  4997.5  351.83  5003.0  352.63
  5013.1  353.17  5017.9  355.79  5045.1  354.18  5054.9  354.34  5060.7  356.27
  5076.2  356.32  5185.1  354.16  5229.8  356.71  5291.2  357.14  5346.4  359.15
  5433.8  365.46  5453.3  370.14  5484.4  375.20  5541.9  378.96  5593.2  381.13
#Mann=6,-1,0
  4706.0    0.16       0  4971.9    0.12       0  4997.0    0.07       0
  5003.0    0.12       0  5433.8    0.07       0  5541.9    0.16       0
Bank Sta=4933,5291.2
Exp/Cntr=0.3,0.1

Type RM Length L Ch R = 1,3228,353,353,353
BEGIN DESCRIPTION:
UNT 068 IN DRY CR WATERSHED 3.0
END DESCRIPTION:
XS GIS Cut Line= 3
      2895275.03      6969925.00      2895575.00      6969875.00
      2895774.99      6969525.02
#Sta/Elev= 30
  4722.5  377.68  4750.4  376.78  4763.0  375.47  4834.0  360.12  4854.3  357.06
  4867.3  356.13  4932.8  356.01  4937.9  356.57  4975.9  354.54  4986.1  352.94
  4990.7  350.44  4991.2  349.64  4996.2  349.64  4996.7  350.44  4998.7  351.62
  5006.3  353.65  5016.5  353.21  5024.1  353.97  5049.6  354.22  5077.7  353.29
  5093.6  354.37  5179.9  354.44  5241.0  356.13  5260.6  356.69  5341.2  362.09
  5372.1  366.74  5378.6  369.07  5384.4  368.67  5402.3  372.65  5429.7  375.53
#Mann=4,-1,0
  4722.5    0.16       0  4990.7    0.07       0  4996.7    0.16       0
  5402.3    0.07       0
Bank Sta=4867.3,5241
Exp/Cntr=0.3,0.1

Type RM Length L Ch R = 1,2875,228,228,228
BEGIN DESCRIPTION:
Mapping XS aec4208e
END DESCRIPTION:
XS GIS Cut Line= 3
      2895309.18      6970037.95      2895715.44      6970037.95
      2896246.68      6969805.32
#Sta/Elev= 30
  4613.1  375.49  4628.9  374.79  4718.9  358.57  4776.1  354.50  4848.9  352.94
  4918.9  352.85  4958.9  353.98  4988.9  352.19  5005.9  348.67  5006.4  347.87
  5011.9  348.67  5016.6  352.89  5029.8  353.58  5180.0  354.50  5258.6  355.80
  5287.4  358.37  5292.9  357.47  5310.8  360.34  5316.2  359.48  5346.4  360.35
  5386.4  364.13  5433.2  365.75  5438.6  364.97  5462.0  367.95  5485.4  369.40
  5543.1  372.59  5566.4  372.82  5584.4  375.08  5589.8  373.91  5599.3  374.67
#Mann=3,-1,0
  4613.1    0.16       0  5005.9    0.07       0  5011.9    0.16       0
Bank Sta=4776.1,5180
Exp/Cntr=0.3,0.1

Type RM Length L Ch R = 1,2647,362,362,362
BEGIN DESCRIPTION:
Mapping XS 00841777
END DESCRIPTION:
XS GIS Cut Line= 3
      2895365.16      6970064.17      2895799.17      6970164.86
      2896395.86      6969949.77
#Sta/Elev= 30
  4575.7  367.15  4596.1  363.72  4601.3  362.06  4626.9  358.77  4686.7  354.72
  4725.8  353.57  4832.2  351.98  4893.8  353.00  4975.9  352.87  4986.2  351.44
  4992.5  347.66  4993.0  346.86  4998.0  346.86  4998.5  347.66  5016.5  351.61
  5021.2  351.61  5027.4  349.72  5039.5  350.70  5048.7  349.85  5064.8  352.18
  5098.2  352.67  5148.7  353.57  5293.2  358.37  5346.3  362.03  5391.8  366.83
  5399.5  368.79  5447.9  373.15  5478.5  374.21  5503.9  376.31  5655.5  381.76
#Mann=4,-1,0
  4575.7    0.16       0  4992.5    0.07       0  4998.5    0.16       0
  5098.2    0.16       0
Bank Sta=4725.8,5148.7
Exp/Cntr=0.3,0.1

Type RM Length L Ch R = 1,2285,307,307,307
BEGIN DESCRIPTION:
Mapping XS e3031705
END DESCRIPTION:
XS GIS Cut Line= 4
      2895323.50      6970088.48      2895757.51      6970296.80
      2895951.95      6970446.11      2896417.23      6970130.13
#Sta/Elev= 30
  4250.0  371.92  4340.5  357.16  4425.9  353.21  4583.0  352.19  4607.9  351.81
  4790.3  350.72  4935.0  351.37  4942.6  350.87  4949.5  347.13  4955.8  350.44
  4964.0  347.71  4970.3  351.16  4986.9  349.84  4990.8  346.78  4998.4  344.91
  4998.9  344.11  5005.2  344.91  5007.9  349.28  5059.6  352.19  5064.9  354.35
  5112.4  356.73  5137.4  358.01  5151.6  356.04  5173.7  361.01  5253.3  369.71
  5274.3  368.73  5376.1  379.51  5468.9  384.13  5483.9  386.63  5539.0  387.88
#Mann=9,-1,0
  4250.0    0.16       0  4340.5    0.12       0  4425.9    0.16       0
  4607.9    0.12       0  4790.3    0.16       0  4990.8    0.12       0
  4998.4    0.07       0  5005.2    0.12       0  5112.4    0.16       0
Bank Sta=4583,5059.6
Exp/Cntr=0.3,0.1

Type RM Length L Ch R = 1,1978,281,281,281
BEGIN DESCRIPTION:
Mapping XS c3c5aca2
END DESCRIPTION:
XS GIS Cut Line= 3
      2895323.46      6970713.47      2895979.73      6970637.08
      2896396.39      6970425.28
#Sta/Elev= 30
  4352.9  371.52  4374.6  367.53  4381.3  364.97  4386.3  366.46  4435.0  352.27
  4464.0  350.45  4978.6  349.67  4991.0  347.90  4995.4  341.51  4995.9  340.71
  5002.2  341.51  5008.7  346.55  5013.6  346.55  5019.5  349.40  5027.8  349.55
  5077.3  348.65  5142.2  350.45  5160.7  352.84  5188.5  359.26  5210.8  361.44
  5227.4  361.21  5233.0  362.95  5249.7  362.73  5255.3  364.03  5271.9  363.21
  5294.2  365.79  5355.3  367.37  5389.7  370.41  5427.7  375.79  5481.0  379.09
#Mann=4,-1,0
  4352.9    0.12       0  4995.4    0.07       0  5002.2    0.12       0
  5027.8    0.16       0
Bank Sta=4464,5142.2
Exp/Cntr=0.3,0.1

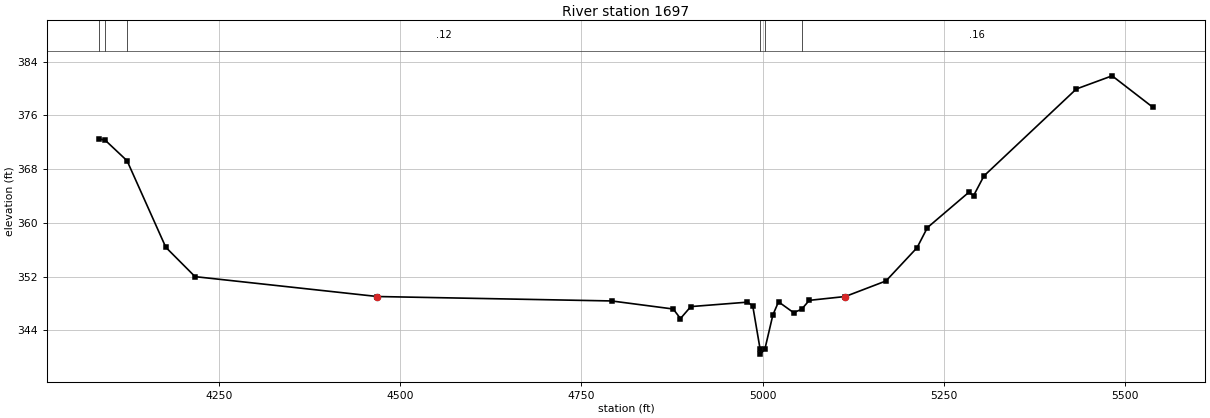
Type RM Length L Ch R = 1,1697,0,0,0
BEGIN DESCRIPTION:
UNT 068 IN DRY CR WATERSHED 2.0
END DESCRIPTION:
XS GIS Cut Line= 3
      2895254.01      6970793.33      2896045.70      6970900.97
      2896549.16      6970480.84
#Sta/Elev= 30
  4084.2  372.52  4092.5  372.29  4122.5  369.25  4176.0  356.36  4216.4  351.99
  4468.1  349.03  4791.6  348.37  4876.7  347.17  4886.7  345.75  4901.0  347.53
  4979.1  348.19  4986.5  347.65  4996.6  341.25  4997.1  340.45  5003.4  341.25
  5014.3  346.28  5022.1  348.24  5042.9  346.63  5053.9  347.12  5064.6  348.46
  5114.3  349.03  5170.5  351.35  5213.4  356.30  5227.7  359.29  5285.0  364.56
  5291.5  364.05  5305.8  366.99  5433.4  379.94  5482.8  381.90  5538.9  377.23
#Mann=6,-1,0
  4084.2    0.12       0  4092.5    0.16       0  4122.5    0.12       0
  4996.6    0.07       0  5003.4    0.12       0  5053.9    0.16       0
Bank Sta=4468.1,5114.3
Exp/Cntr=0.3,0.1

Chan Stop Cuts=-1