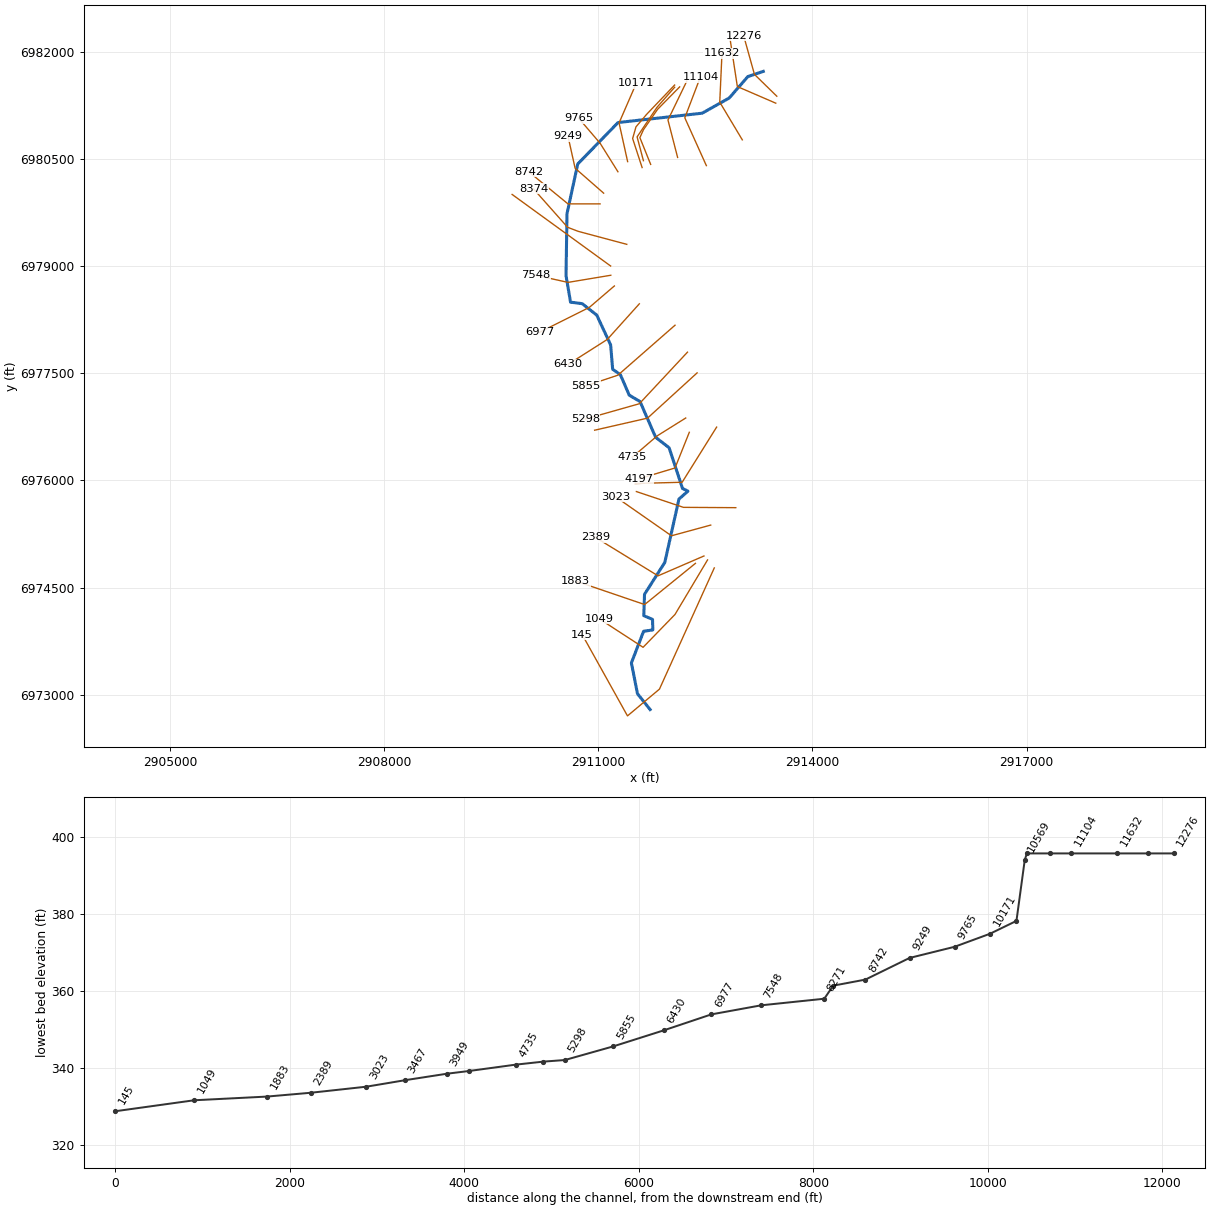
--- UNT 069 IN DRY CR WATERSHED.prj (project) ---

Proj Title=UNT 069 IN DRY CR WATERSHED Base Level Engineering
Current Plan=p01
Default Exp/Contr=0.3,0.1
English Units
Geom File=g01
Flow File=f01
Plan File=p01
Y Axis Title=Elevation
X Axis Title(PF)=Main Channel Distance
X Axis Title(XS)=Station
BEGIN DESCRIPTION:
UNT 069 IN DRY CR WATERSHED
END DESCRIPTION:
DSS Export Rating Curves= 0
DSS Export Rating Curve Sorted= 0
DSS Export Volume Flow Curves= 0
DXF OffsetX= 0
DXF OffsetY= 0
DXF ScaleX= 1
DXF ScaleY= 10

--- UNT 069 IN DRY CR WATERSHED.p01 (plan) ---

Plan Title=Multiple Run
Short Identifier=Multiple
Geom File=g01
Flow File=f01
Subcritical Flow
K Sum by GR= 0
Std Step Tol= 0.01
Critical Tol= 0.01
Num of Std Step Trials= 20
Max Error Tol= 0.3
Flow Tol Ratio= 0.001
Split Flow NTrial= 30
Split Flow Tol= 0.02
Split Flow Ratio= 0.02
Log Output Level= 0
Friction Slope Method= 1
Unsteady Friction Slope Method= 2
Unsteady Bridges Friction Slope Method= 1
Parabolic Critical Depth
Global Vel Dist=  1 , 1 , 1
Global Log Level= 0
CheckData=True
Encroach Param= -1, 0, 0, 0
BEGIN DESCRIPTION:
Multiple Run
END DESCRIPTION:

--- UNT 069 IN DRY CR WATERSHED.f01 (steady flow) ---

Flow Title=Multiple
Number of Profiles=7
Profile Names=10-year,25-year,50-year,1pct_min,100-year,1pct_plu,500-year
River Rch & RM= UNT 069 IN DRY C,Reach-1,12276
     417     549     654     389     776    1548    1090
River Rch & RM= UNT 069 IN DRY C,Reach-1,9765
     990    1367    1681    1027    2049    4089    3051
Boundary for River Rch & Prof#=UNT 069 IN DRY C,Reach-1,1
Up Type=0
Dn Type=3
Dn Slope=0.005
Boundary for River Rch & Prof#=UNT 069 IN DRY C,Reach-1,2
Up Type=0
Dn Type=3
Dn Slope=0.005
Boundary for River Rch & Prof#=UNT 069 IN DRY C,Reach-1,3
Up Type=0
Dn Type=3
Dn Slope=0.005
Boundary for River Rch & Prof#=UNT 069 IN DRY C,Reach-1,4
Up Type=0
Dn Type=3
Dn Slope=0.005
Boundary for River Rch & Prof#=UNT 069 IN DRY C,Reach-1,5
Up Type=0
Dn Type=3
Dn Slope=0.005
Boundary for River Rch & Prof#=UNT 069 IN DRY C,Reach-1,6
Up Type=0
Dn Type=3
Dn Slope=0.005
Boundary for River Rch & Prof#=UNT 069 IN DRY C,Reach-1,7
Up Type=0
Dn Type=3
Dn Slope=0.005

--- UNT 069 IN DRY CR WATERSHED.g01 (geometry) ---

Geom Title=Existing Conditions
Program Version=5.07

River Reach=UNT 069 IN DRY C,Reach-1
Reach XY= 30
      2913311.45        6981731.      2913094.89      6981657.95
      2912834.47      6981358.47      2912455.64      6981145.26
      2911276.43      6981014.31      2910712.11      6980433.62
      2910561.33      6979736.51      2910547.88      6978869.01
      2910611.28      6978497.67      2910774.02       6978477.2
      2910978.06      6978317.06      2911172.86      6977899.49
      2911201.24      6977558.19      2911309.09      6977482.17
      2911433.57      6977194.99      2911585.07       6977105.2
      2911803.63      6976604.44      2911991.87      6976458.56
      2912180.03      6975887.55      2912255.59      6975850.71
      2912129.75      6975738.65      2911931.87      6974852.25
      2911647.42       6974404.9      2911637.59      6974105.76
      2911759.95      6974053.28      2911763.78      6973906.03
      2911634.77      6973887.39      2911463.71      6973444.13
      2911549.14      6973012.18      2911725.59      6972790.71

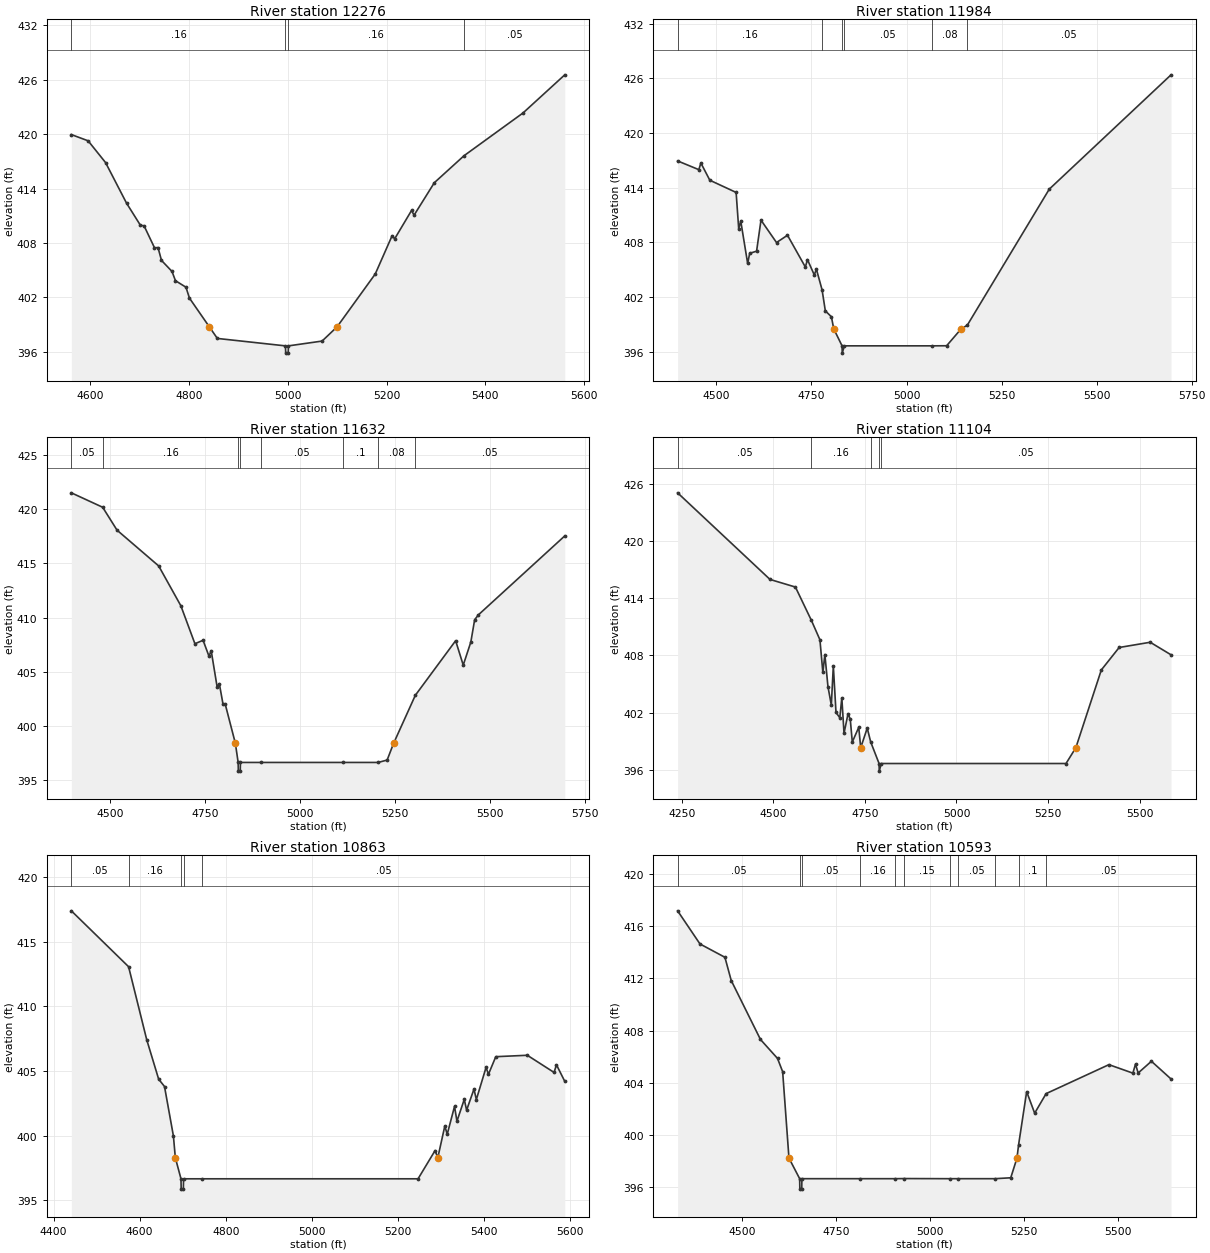
Type RM Length L Ch R = 1 ,12276   ,292,292,292
BEGIN DESCRIPTION:
UNT 069 IN DRY CR WATERSHED 16.0
END DESCRIPTION:
XS GIS Cut Line= 3
      2913501.01      6981382.95      2913187.62      6981689.23
      2913036.59      6982229.31
#Sta/Elev= 30
  4561.8  419.96  4595.8  419.27  4631.1  416.87  4673.6  412.39  4701.8  409.94
    4709   409.9  4730.1  407.48  4737.3  407.49  4744.3  406.08  4765.6  404.86
  4772.6  403.84  4793.9  403.12  4800.9  401.92  4841.2  398.75  4857.4  397.47
  4995.3  396.65  4995.8  395.85  5000.8  395.85  5001.3  396.65  5069.5  397.18
  5099.8  398.75  5177.1  404.58  5211.2   408.8  5216.4  408.46  5250.6  411.59
  5255.7  411.07  5296.7  414.65  5356.7  417.62  5476.2  422.34  5560.8  426.55
#Mann= 4 ,-1 , 0
  4561.8     .16       0  4995.3     .07       0  5001.3     .16       0
  5356.7     .05       0
Bank Sta=4841.2,5099.8
XS Rating Curve= 0 ,0
Exp/Cntr=0.3,0.1

Type RM Length L Ch R = 1 ,11984   ,352,352,352
BEGIN DESCRIPTION:
Mapping XS c79ea0df
END DESCRIPTION:
XS GIS Cut Line= 3
      2913486.27      6981285.73      2912948.05      6981518.38
      2912840.65      6982221.67
#Sta/Elev= 30
    4398  416.95  4453.8  415.99  4459.2  416.72  4482.7  414.83  4551.9  413.49
  4558.7  409.49  4564.1  410.34  4582.2   405.7  4587.6  406.81  4605.7  407.04
  4617.3  410.45  4658.1  407.99    4687  408.79    4734   405.3  4739.5  406.12
  4757.5  404.43    4763  405.07    4778  402.79  4786.5  400.49  4802.5  399.84
  4808.6  398.52  4830.5  396.65    4831  395.85  4836.5  396.65  5066.4  396.65
  5105.6  396.66  5143.9  398.52  5159.8  398.91  5375.5  413.85  5695.8   426.4
#Mann= 6 ,-1 , 0
    4398     .16       0    4778     .05       0  4830.5    .033       0
  4836.5     .05       0  5066.4     .08       0  5159.8     .05       0
Bank Sta=4808.6,5143.9
XS Rating Curve= 0 ,0
Exp/Cntr=0.3,0.1

Type RM Length L Ch R = 1 ,11632   ,528,528,528
BEGIN DESCRIPTION:
Mapping XS 49d23bcc
END DESCRIPTION:
XS GIS Cut Line= 3
      2913017.48      6980771.88      2912701.52      6981299.63
      2912732.69      6981981.81
#Sta/Elev= 30
  4398.8   421.5  4481.2  420.17    4519  418.06  4628.6  414.76  4686.9  411.09
  4723.9  407.59  4745.3  407.91  4760.9  406.44  4766.7  406.95  4782.2  403.63
  4788.1  403.91  4797.8  402.02  4803.6  402.02  4830.3  398.41  4837.6  396.65
  4838.1  395.85  4843.1  395.85  4843.6  396.65  4896.4  396.65    5114  396.65
  5205.7  396.65  5229.5  396.87  5246.5  398.41  5303.7  402.84  5409.7  407.87
  5429.7  405.62  5449.7  407.75  5459.7   409.8  5469.8  410.26  5696.8  417.53
#Mann= 8 ,-1 , 0
  4398.8     .05       0  4481.2     .16       0  4837.6    .033       0
  4843.6     .16       0  4896.4     .05       0    5114      .1       0
  5205.7     .08       0  5303.7     .05       0
Bank Sta=4830.3,5246.5
XS Rating Curve= 0 ,0
Exp/Cntr=0.3,0.1

Type RM Length L Ch R = 1 ,11104   ,241,241,241
BEGIN DESCRIPTION:
Mapping XS bdb60c08
END DESCRIPTION:
XS GIS Cut Line= 3
      2912514.02      6980410.74      2912211.94      6981080.88
      2912430.35      6981652.92
#Sta/Elev= 30
  4238.5  425.09  4490.8  415.99  4560.2  415.19  4603.9  411.68  4627.1  409.65
  4635.1  406.22  4640.6   408.1    4649  404.74  4658.2  402.79  4663.7   406.9
    4671  402.01  4681.4  401.46  4686.9  403.56  4692.9  399.82  4703.9  401.89
    4710  401.28  4715.5  398.91  4733.1  400.45  4738.5  398.31  4756.3  400.37
  4765.7  398.92  4788.6  396.65  4789.1  395.85  4794.6  396.65  5299.1  396.65
  5325.9  398.31  5395.5  406.48  5444.2  408.84    5529  409.39  5585.9  408.07
#Mann= 5 ,-1 , 0
  4238.5     .05       0  4603.9     .16       0  4765.7     .05       0
  4788.6    .033       0  4794.6     .05       0
Bank Sta=4738.5,5325.9
XS Rating Curve= 0 ,0
Exp/Cntr=0.3,0.1

Type RM Length L Ch R = 1 ,10863   ,270,270,270
BEGIN DESCRIPTION:
Mapping XS 185d2a7c
END DESCRIPTION:
XS GIS Cut Line= 3
      2912111.25      6980525.27      2911975.83      6981049.63
      2912239.71      6981594.76
#Sta/Elev= 30
  4441.1  417.41  4574.2  413.08  4616.4  407.42  4644.1  404.37  4657.7   403.8
  4678.4  399.97  4682.9  398.28    4696  396.65  4696.5  395.85  4701.5  395.85
    4702  396.65  4745.3  396.65  5247.2  396.65  5286.8  398.84  5293.1  398.28
  5309.4  400.74    5315   400.1    5332  402.26  5337.6  401.11  5354.6   402.8
  5360.1  401.97  5377.2   403.6  5382.7  402.79  5405.3  405.28  5410.9  404.75
  5427.9  406.11  5501.2  406.22  5563.4  404.89    5569  405.48  5588.3   404.2
#Mann= 5 ,-1 , 0
  4441.1     .05       0  4574.2     .16       0    4696    .033       0
    4702     .16       0  4745.3     .05       0
Bank Sta=4682.9,5293.1
XS Rating Curve= 0 ,0
Exp/Cntr=0.3,0.1

Type RM Length L Ch R = 1 ,10593   ,24,24,24
BEGIN DESCRIPTION:
Mapping XS 43dd58bc
END DESCRIPTION:
XS GIS Cut Line= 5
      2911733.62      6980428.14       2911582.6       6980803.1
      2911632.08      6980912.47      2911829.99      6981198.93
      2912139.88      6981514.03
#Sta/Elev= 30
  4327.5  417.18  4387.1  414.64  4453.5  413.62  4470.3  411.84  4548.2  407.32
  4593.6  405.87  4607.3  404.85  4624.1  398.23  4652.6  396.65  4653.1  395.85
  4658.1  395.85  4658.6  396.65  4814.6  396.65  4906.4  396.65  4931.2  396.66
  5052.1  396.65    5075  396.65    5173  396.65  5214.9  396.72  5231.5  398.23
  5235.7  399.23  5257.3  403.32  5278.6  401.67  5309.1  403.17  5476.4  405.39
  5540.2  404.74  5547.2  405.43  5554.3  404.75  5589.6  405.65  5641.9  404.29
#Mann= 11 ,-1 , 0
  4327.5     .05       0  4652.6     .07       0  4658.6     .05       0
  4814.6     .16       0  4906.4     .05       0  4931.2     .15       0
  5052.1     .08       0    5075     .05       0    5173     .08       0
  5235.7      .1       0  5309.1     .05       0
Bank Sta=4624.1,5231.5
XS Rating Curve= 0 ,0
Exp/Cntr=0.3,0.1

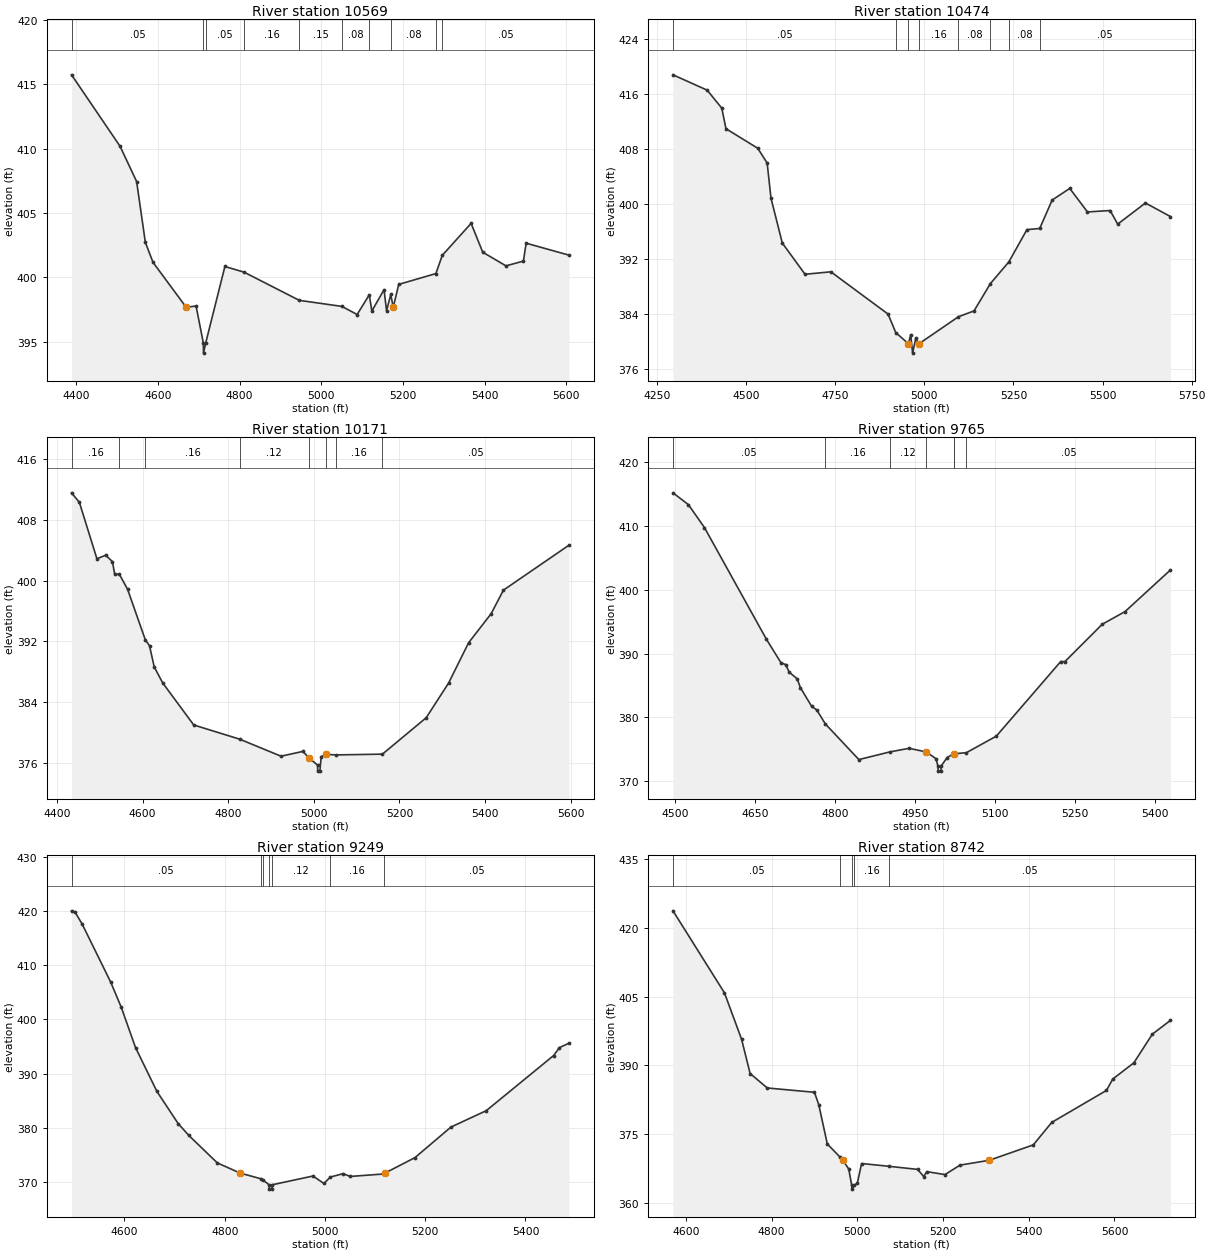
Type RM Length L Ch R = 1 ,10569   ,95,95,95
BEGIN DESCRIPTION:
Mapping XS 1c6d9c10
END DESCRIPTION:
XS GIS Cut Line= 4
      2911632.07      6980480.22      2911543.53      6980813.52
      2911822.18      6981227.58      2912069.56      6981508.81
#Sta/Elev= 30
  4388.5  415.73  4507.3  410.18  4547.9  407.44  4569.3  402.71  4588.1  401.16
  4669.3  397.67  4693.5  397.77  4711.2  394.91  4711.7  394.11  4717.2  394.91
  4764.1  400.84    4811   400.4  4946.3  398.21  5050.6  397.74    5088  397.11
  5117.7  398.64    5124  397.38  5153.9  399.04    5160   397.4  5170.4  398.67
  5176.3  397.67  5189.9  399.45  5280.8  400.29  5296.6  401.71  5367.1  404.19
  5395.6  401.95  5452.5  400.89  5495.2  401.26  5501.9  402.65    5607  401.72
#Mann= 10 ,-1 , 0
  4388.5     .05       0  4711.2     .07       0  4717.2     .05       0
    4811     .16       0  4946.3     .15       0  5050.6     .08       0
  5117.7     .05       0  5170.4     .08       0  5280.8      .1       0
  5296.6     .05       0
Bank Sta=4669.3,5176.3
XS Rating Curve= 0 ,0
Exp/Cntr=0.3,0.1

Type RM Length L Ch R = 1 ,10474   ,303,303,303
BEGIN DESCRIPTION:
Mapping XS 74e4e527
END DESCRIPTION:
XS GIS Cut Line= 5
      2911613.86       6980383.8      2911481.03      6980790.08
      2911527.91      6980954.14      2911678.95      6981131.22
      2912069.52      6981540.02
#Sta/Elev= 30
  4294.4  418.76  4390.4  416.53  4431.4  413.91    4443  410.93  4532.2  408.09
  4558.7  405.94  4569.4  400.83  4601.2  394.31    4665  389.77  4737.4  390.13
  4897.9  383.99  4919.6   381.3    4955  379.68  4961.6     381  4966.8  378.31
  4975.9  380.52  4983.6  379.63  5095.5   383.6  5139.3  384.45  5185.2  388.42
  5237.2  391.59  5287.7  396.26  5323.6  396.43  5358.5  400.56  5407.9  402.25
  5457.6  398.83  5521.1  399.04  5542.5  397.06  5620.2  400.13  5690.6  398.16
#Mann= 8 ,-1 , 0
  4294.4     .05       0  4919.6     .16       0    4955     .07       0
  4983.6     .16       0  5095.5     .08       0  5185.2     .05       0
  5237.2     .08       0  5323.6     .05       0
Bank Sta=4955,4983.6
XS Rating Curve= 0 ,0
Exp/Cntr=0.3,0.1

Type RM Length L Ch R = 1 ,10171   ,406,406,406
BEGIN DESCRIPTION:
Mapping XS ea2ecd2c
END DESCRIPTION:
XS GIS Cut Line= 3
      2911410.73      6980467.12      2911290.93      6981008.83
       2911533.1      6981566.08
#Sta/Elev= 30
  4433.9  411.52  4452.2  410.27  4493.2  402.86  4513.7  403.33  4529.5  402.48
  4534.6  400.86  4545.9   400.8  4564.9  398.84  4606.2  392.22  4616.1  391.43
    4627  388.67  4646.8  386.56  4719.4  381.03  4826.6  379.17  4923.3  376.93
  4974.5  377.56  4988.7  376.69  5008.6  375.77  5009.1  374.97  5014.1  374.97
  5017.2  376.87  5028.1  377.17  5052.5   377.1  5160.2   377.2  5262.5  381.98
  5314.8  386.53  5361.7  391.84  5414.1  395.63    5443  398.74  5596.3  404.65
#Mann= 8 ,-1 , 0
  4433.9     .16       0  4545.9     .05       0  4606.2     .16       0
  4826.6     .12       0  4988.7     .07       0  5028.1     .12       0
  5052.5     .16       0  5160.2     .05       0
Bank Sta=4988.7,5028.1
XS Rating Curve= 0 ,0
Exp/Cntr=0.3,0.1

Type RM Length L Ch R = 1 ,9765    ,516,516,516
BEGIN DESCRIPTION:
UNT 069 IN DRY CR WATERSHED 15.0
END DESCRIPTION:
XS GIS Cut Line= 3
      2911275.02      6980324.97        2911025.        6980725.
      2910725.01      6981074.99
#Sta/Elev= 30
  4496.2  415.23  4525.1  413.38  4555.2  409.78  4671.4  392.26  4698.5   388.6
  4707.9  388.27  4713.8  387.12  4729.1  386.06    4735  384.68  4756.3  381.72
  4765.7  381.18  4781.8  378.99  4844.7  373.39    4903   374.6    4939  375.16
  4971.2  374.58  4989.3  373.53  4992.9  372.38  4993.4  371.58  4998.4  371.58
  4998.9  372.38  5010.2  373.71  5022.1  374.29  5046.4  374.48  5102.4  377.07
  5223.1  388.77  5230.8  388.75    5301  394.62  5343.8  396.61  5428.9  403.14
#Mann= 7 ,-1 , 0
  4496.2     .05       0  4781.8     .16       0    4903     .12       0
  4971.2     .07       0  5022.1     .12       0  5022.1     .16       0
  5046.4     .05       0
Bank Sta=4971.2,5022.1
XS Rating Curve= 0 ,0
Exp/Cntr=0.3,0.1

Type RM Length L Ch R = 1 ,9249    ,507,507,507
BEGIN DESCRIPTION:
UNT 069 IN DRY CR WATERSHED 14.0
END DESCRIPTION:
XS GIS Cut Line= 3
      2911074.97      6980025.03        2910675.        6980375.
      2910575.01      6980824.96
#Sta/Elev= 30
  4494.5  420.04  4501.6   419.8  4515.8  417.57  4572.8  406.85  4593.6  402.26
  4622.1  394.81  4664.8  386.71  4707.1  380.79  4728.4  378.59  4785.4  373.51
  4830.4  371.66  4872.2  370.59  4876.3  370.36  4888.7  369.48  4889.2  368.68
  4894.2  368.68  4894.7  369.48  4976.1   371.1    4998  369.72  5010.6   370.9
  5036.2  371.54  5050.3  371.02  5117.9  371.48  5120.1  371.66  5179.6   374.5
  5251.3  380.13  5321.8  383.16  5456.2  393.34  5467.7  394.79  5486.9  395.62
#Mann= 7 ,-1 , 0
  4494.5     .05       0  4872.2     .16       0  4876.3     .12       0
  4888.7     .07       0  4894.7     .12       0  5010.6     .16       0
  5117.9     .05       0
Bank Sta=4830.4,5120.1
XS Rating Curve= 0 ,0
Exp/Cntr=0.3,0.1

Type RM Length L Ch R = 1 ,8742    ,368,368,368
BEGIN DESCRIPTION:
UNT 069 IN DRY CR WATERSHED 13.0
END DESCRIPTION:
XS GIS Cut Line= 3
        2911025.        6979875.        2910575.        6979875.
      2910025.03      6980324.98
#Sta/Elev= 30
  4570.1  423.69  4690.1  405.83  4730.1  395.71  4750.1  388.23  4790.1  385.09
  4900.1  384.15  4910.1  381.48  4930.1  372.89  4959.2  370.09  4966.7  369.34
  4980.1  367.42  4987.1  363.85  4987.6  363.05  4993.2  363.85  5000.1  364.34
  5010.1  368.63  5073.3  368.03  5140.7  367.35    5155   365.8  5162.2  366.86
  5204.6  366.22  5239.8  368.28  5308.1  369.34  5410.6  372.69  5453.7  377.59
  5581.4  384.56  5595.8  387.02  5645.3  390.58  5688.4  396.82  5730.7  399.83
#Mann= 5 ,-1 , 0
  4570.1     .05       0  4959.2     .16       0  4987.1     .07       0
  4993.2     .16       0  5073.3     .05       0
Bank Sta=4966.7,5308.1
XS Rating Curve= 0 ,0
Exp/Cntr=0.3,0.1

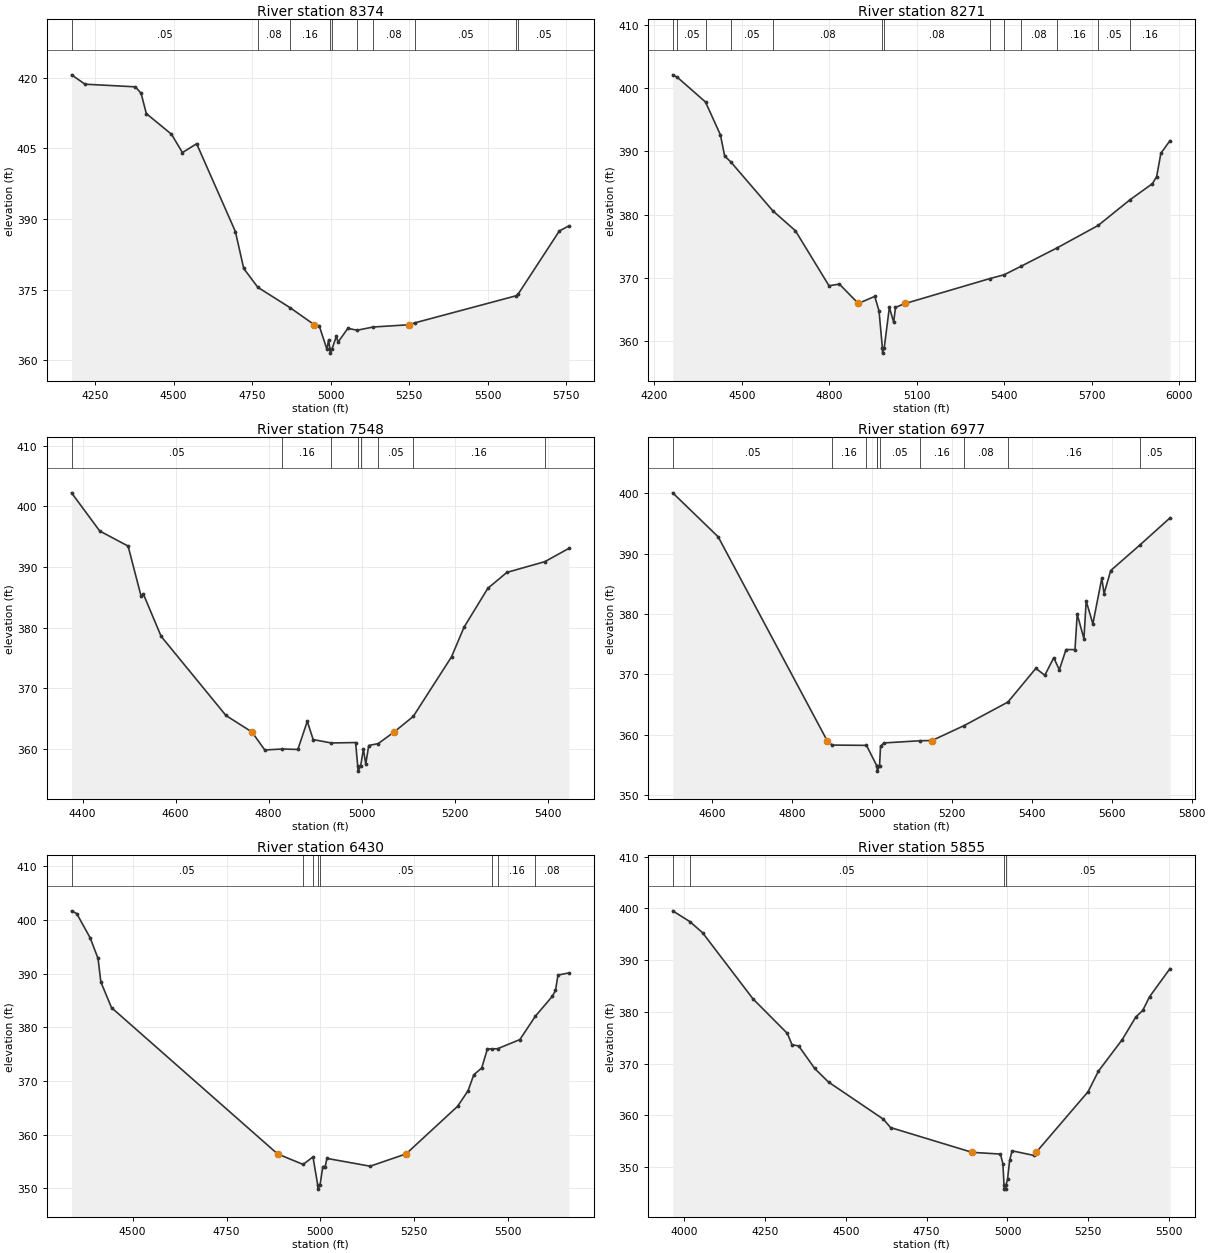
Type RM Length L Ch R = 1 ,8374    ,103,103,103
BEGIN DESCRIPTION:
Mapping XS 1dbfdf82
END DESCRIPTION:
XS GIS Cut Line= 4
      2911398.84      6979308.19      2910717.42      6979490.48
      2910569.85       6979546.9      2910092.43      6980085.09
#Sta/Elev= 30
  4174.9  420.62  4217.9  418.63  4378.1  418.07  4396.3   416.7  4412.9  412.39
    4493     408  4527.9   404.1  4573.1  405.98  4696.5  387.31    4723  379.47
    4768  375.46  4870.3  371.15  4947.7  367.51  4963.1  367.32  4987.8   362.3
  4993.1   364.3  4997.6  362.28  4998.1  361.48  5003.7  362.28  5017.8  365.08
  5023.2  363.82  5054.4  366.74  5084.3  366.35  5134.8  367.03  5248.9  367.51
  5268.4  367.93  5590.7  373.68    5597  374.08  5727.7  387.45  5757.7  388.51
#Mann= 10 ,-1 , 0
  4174.9     .05       0    4768     .08       0  4870.3     .16       0
  4997.6     .07       0  5003.7     .16       0  5084.3     .05       0
  5134.8     .08       0  5268.4     .05       0  5590.7     .08       0
    5597     .05       0
Bank Sta=4947.7,5248.9
XS Rating Curve= 0 ,0
Exp/Cntr=0.3,0.1

Type RM Length L Ch R = 1 ,8271    ,723,723,723
BEGIN DESCRIPTION:
Mapping XS d6390479
END DESCRIPTION:
XS GIS Cut Line= 3
      2911173.13      6979004.38      2910617.59      6979408.01
      2909792.94      6980006.97
#Sta/Elev= 30
  4263.1  402.13  4278.8  401.75  4375.6  397.83  4426.7  392.63  4441.4  389.27
  4461.7  388.38  4606.3  380.62  4684.1  377.45  4799.3  368.74  4834.8  369.01
  4899.7  365.94  4956.2  367.06  4970.9  364.75  4982.4  358.88  4982.9  358.08
  4988.6  358.88  5006.4  365.35  5021.1  362.96  5027.3  365.33    5061  365.94
  5351.7  369.89    5400  370.48  5457.6  371.82  5582.1  374.75  5722.6  378.29
  5831.1  382.33  5908.5   384.9  5923.2  386.02  5937.8  389.72    5969  391.71
#Mann= 13 ,-1 , 0
  4263.1     .08       0  4278.8     .05       0  4375.6     .08       0
  4461.7     .05       0  4606.3     .08       0  4982.4     .07       0
  4988.6     .08       0  5351.7     .16       0    5400     .05       0
  5457.6     .08       0  5582.1     .16       0  5722.6     .05       0
  5831.1     .16       0
Bank Sta=4899.7,5061
XS Rating Curve= 0 ,0
Exp/Cntr=0.3,0.1

Type RM Length L Ch R = 1 ,7548    ,571,571,571
BEGIN DESCRIPTION:
UNT 069 IN DRY CR WATERSHED 11.0
END DESCRIPTION:
XS GIS Cut Line= 3
      2911174.99        6978875.        2910575.        6978775.
      2910125.04      6978874.99
#Sta/Elev= 30
  4376.1  402.23  4436.9  395.93  4497.7  393.46  4525.6  385.22  4530.7  385.53
  4568.7  378.59  4708.1  365.54    4764  362.82  4791.7  359.85  4829.5  360.02
  4862.7  359.94    4883  364.58  4895.7  361.57  4934.5  361.01  4986.9  361.08
  4991.5  357.17    4992  356.37  4997.7  357.17  5003.6  360.04  5008.7  357.54
  5015.1  360.59  5035.5  360.91  5069.7  362.82  5110.8  365.38  5193.1   375.2
    5220  380.08  5271.2   386.5  5312.2  389.12  5393.8  390.89  5445.3  393.07
#Mann= 8 ,-1 , 0
  4376.1     .05       0  4829.5     .16       0  4934.5     .12       0
  4991.5     .07       0  4997.7     .12       0  5035.5     .05       0
  5110.8     .16       0  5393.8     .05       0
Bank Sta=4764,5069.7
XS Rating Curve= 0 ,0
Exp/Cntr=0.3,0.1

Type RM Length L Ch R = 1 ,6977    ,547,547,547
BEGIN DESCRIPTION:
UNT 069 IN DRY CR WATERSHED 10.0
END DESCRIPTION:
XS GIS Cut Line= 3
      2911224.99      6978724.99        2910875.        6978425.
      2910174.99      6978074.99
#Sta/Elev= 30
  4502.2  400.04  4615.8  392.77  4888.3  359.07  4900.8  358.32  4986.8  358.27
  5012.3  354.93  5013.1  354.81  5013.6  354.01  5019.4  354.81  5021.9   358.1
  5030.2  358.67  5121.7  359.04  5150.7  359.07  5231.2  361.55  5340.6  365.44
  5410.4  371.01  5432.7  369.86  5455.1  372.76  5469.1  370.78  5485.8  374.12
  5508.2  374.11  5513.8  379.96  5530.6  375.91  5536.2  382.15  5552.9  378.36
  5575.3  385.92  5580.9  383.36  5597.6  387.19  5670.2  391.39  5745.8  395.89
#Mann= 10 ,-1 , 0
  4502.2     .05       0  4900.8     .16       0  4986.8      .1       0
  5012.3     .05       0  5013.1     .07       0  5019.4     .05       0
  5121.7     .16       0  5231.2     .08       0  5340.6     .16       0
  5670.2     .05       0
Bank Sta=4888.3,5150.7
XS Rating Curve= 0 ,0
Exp/Cntr=0.3,0.1

Type RM Length L Ch R = 1 ,6430    ,575,575,575
BEGIN DESCRIPTION:
UNT 069 IN DRY CR WATERSHED 9.0
END DESCRIPTION:
XS GIS Cut Line= 3
      2911575.01      6978475.01        2911125.        6977975.
      2910575.02      6977625.01
#Sta/Elev= 30
  4337.2  401.68    4351  401.17  4386.9  396.64  4407.8  392.81  4415.3  388.43
  4443.7  383.65    4886  356.41    4954  354.45  4980.4  355.85  4992.9  350.65
  4993.4  349.85  4999.2  350.65  5006.5  354.05  5012.9  354.05  5017.5  355.57
  5132.7  354.12  5228.3  356.41  5365.5  365.27  5393.4  368.17  5408.7  371.15
  5429.8  372.41  5445.1  375.99  5457.3  375.96  5472.5  376.01  5531.4   377.7
    5573  382.08  5617.8  385.75  5626.3  386.85    5633  389.72  5661.8  390.11
#Mann= 8 ,-1 , 0
  4337.2     .05       0    4954      .1       0  4980.4     .05       0
  4992.9     .03       0  4999.2     .05       0  5457.3     .08       0
  5472.5     .16       0    5573     .08       0
Bank Sta=4886,5228.3
XS Rating Curve= 0 ,0
Exp/Cntr=0.3,0.1

Type RM Length L Ch R = 1 ,5855    ,557,557,557
BEGIN DESCRIPTION:
UNT 069 IN DRY CR WATERSHED 8.0
END DESCRIPTION:
XS GIS Cut Line= 3
      2912074.97      6978174.98        2911275.        6977475.
      2910825.02      6977325.01
#Sta/Elev= 30
  3965.2  399.54  4018.1  397.46  4057.7  395.29  4213.4  382.51  4319.7  375.82
  4333.9  373.65  4354.8   373.4  4404.1  369.05  4446.8  366.42  4616.7  359.23
  4638.6  357.62  4890.5  352.83  4978.3  352.49  4985.9  350.65  4989.4  346.51
  4989.9  345.71  4995.2  345.71  4995.7  346.51  5000.2  347.58  5006.8  351.28
  5014.4  353.12  5080.9  352.24  5088.8  352.83  5249.5  364.58  5281.2  368.52
  5354.9  374.64  5397.1  379.03  5418.2  380.27  5439.3  382.92  5502.5  388.37
#Mann= 4 ,-1 , 0
  3965.2     .08       0  4018.1     .05       0  4989.4     .03       0
  4995.7     .05       0
Bank Sta=4890.5,5088.8
XS Rating Curve= 0 ,0
Exp/Cntr=0.3,0.1

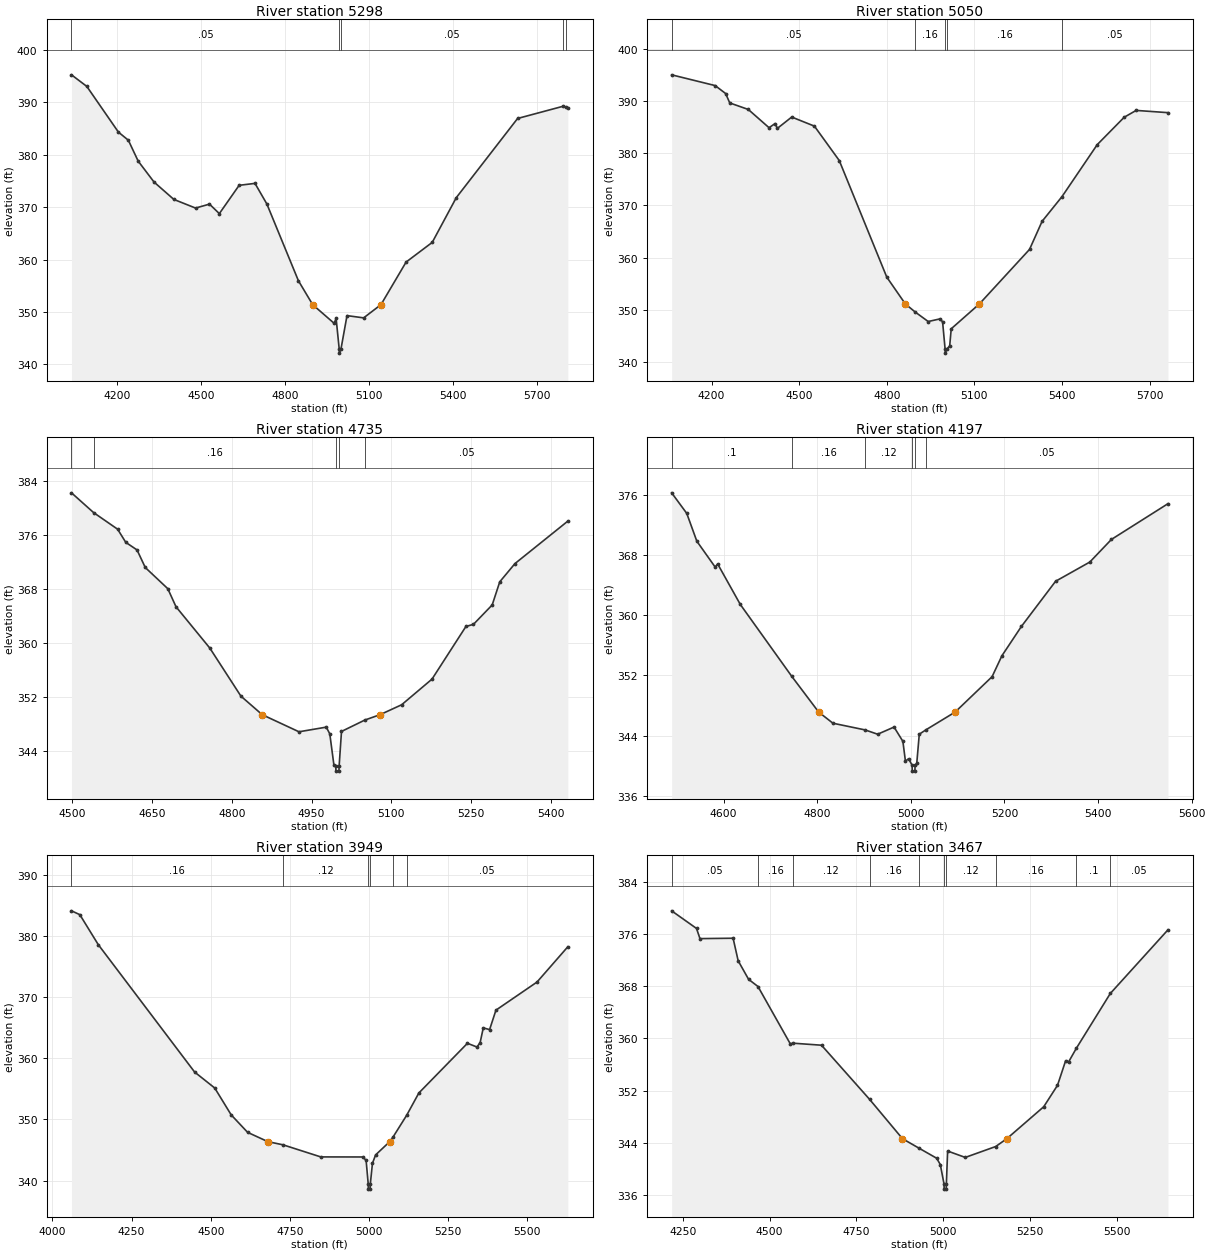
Type RM Length L Ch R = 1 ,5298    ,248,248,248
BEGIN DESCRIPTION:
UNT 069 IN DRY CR WATERSHED 7.0
END DESCRIPTION:
XS GIS Cut Line= 3
      2912249.52      6977797.75        2911575.        6977075.
      2910818.59      6976860.65
#Sta/Elev= 30
  4035.5  395.27  4090.3  393.06  4203.4  384.33  4238.8  382.79    4274   378.8
  4330.6  374.81  4401.5  371.49  4479.1  369.84    4529  370.59  4564.2  368.78
    4635  374.18  4691.7  374.55  4734.2  370.61    4847  355.96    4898   351.4
  4974.5  347.85  4981.8  348.76  4992.8  342.95  4993.3  342.15  4999.2  342.95
  5020.7  349.31  5080.2  348.88  5142.1   351.4    5232  359.53  5325.5  363.29
  5411.5  371.83  5630.7  386.94  5794.2  389.28  5802.6  389.15  5810.3  388.95
#Mann= 5 ,-1 , 0
  4035.5     .05       0  4992.8     .03       0  4999.2     .05       0
  5794.2     .16       0  5802.6     .05       0
Bank Sta=4898,5142.1
XS Rating Curve= 0 ,0
Exp/Cntr=0.3,0.1

Type RM Length L Ch R = 1 ,5050    ,315,315,315
BEGIN DESCRIPTION:
Mapping XS 079b731e
END DESCRIPTION:
XS GIS Cut Line= 3
      2912384.07      6977506.96      2911689.64      6976873.29
      2910948.76      6976704.32
#Sta/Elev= 30
  4063.3  394.99  4212.4  392.93  4248.2  391.41  4262.4  389.61  4325.9  388.36
  4396.9  384.87  4417.8  385.67  4425.2  384.73  4474.6  386.91  4552.3  385.17
  4637.4  378.59  4800.2  356.27  4863.8  351.14  4897.4   349.6    4942  347.78
    4984   348.3  4991.4  347.67  4999.9  342.53  5000.4  341.73  5006.4  342.53
  5015.7  343.14  5020.9  346.39  5117.3  351.14  5289.1  361.58  5332.1  366.95
  5400.4  371.69    5521  381.63  5613.3  386.87  5654.3  388.18  5763.3  387.75
#Mann= 5 ,-1 , 0
  4063.3     .05       0  4897.4     .16       0  4999.9     .07       0
  5006.4     .16       0  5400.4     .05       0
Bank Sta=4863.8,5117.3
XS Rating Curve= 0 ,0
Exp/Cntr=0.3,0.1

Type RM Length L Ch R = 1 ,4735    ,538,538,538
BEGIN DESCRIPTION:
UNT 069 IN DRY CR WATERSHED 6.0
END DESCRIPTION:
XS GIS Cut Line= 3
      2912225.01      6976875.01        2911825.        6976625.
      2911474.99      6976324.99
#Sta/Elev= 30
  4498.9  382.26  4540.4  379.33  4585.6  376.86  4600.9  374.91  4622.1  373.78
  4637.5  371.18  4679.9  368.03  4695.3  365.35  4758.9  359.21  4817.3  352.08
  4857.3  349.33  4926.4  346.79  4977.7  347.48  4984.3  346.48    4992  341.88
  4995.4  341.75  4995.9  340.95  5001.4  340.95  5001.9  341.75  5006.3  346.84
  5050.1  348.53  5078.8  349.33  5119.3   350.8  5176.4  354.61  5240.1  362.42
  5254.3  362.74  5289.5  365.62  5303.7  369.05  5332.3  371.76  5431.6  378.06
#Mann= 5 ,-1 , 0
  4498.9     .05       0  4540.4     .16       0  4995.4     .07       0
  5001.9     .16       0  5050.1     .05       0
Bank Sta=4857.3,5078.8
XS Rating Curve= 0 ,0
Exp/Cntr=0.3,0.1

Type RM Length L Ch R = 1 ,4197    ,248,248,248
BEGIN DESCRIPTION:
UNT 069 IN DRY CR WATERSHED 5.0
END DESCRIPTION:
XS GIS Cut Line= 3
        2912275.        6976675.        2912075.        6976175.
      2911575.03      6976025.01
#Sta/Elev= 30
  4488.9  376.24  4521.2  373.51  4542.7  369.82  4581.8  366.39  4587.2   366.8
  4635.6  361.42  4745.7  351.86  4803.1  347.13  4833.5  345.65  4902.3  344.76
  4929.1  344.19  4964.1  345.14    4983  343.24  4988.4  340.62  4995.1  340.93
  5002.6  340.09  5003.1  339.29  5008.6  339.29  5009.1  340.09  5012.6  340.31
    5018  344.19  5031.6  344.75  5094.6  347.13  5173.6  351.83  5194.5   354.6
  5236.2   358.5  5309.3   364.5  5382.4  367.05  5428.5  370.05  5549.4   374.8
#Mann= 6 ,-1 , 0
  4488.9      .1       0  4745.7     .16       0  4902.3     .12       0
  5002.6     .07       0  5009.1     .12       0  5031.6     .05       0
Bank Sta=4803.1,5094.6
XS Rating Curve= 0 ,0
Exp/Cntr=0.3,0.1

Type RM Length L Ch R = 1 ,3949    ,482,482,482
BEGIN DESCRIPTION:
UNT 069 IN DRY CR WATERSHED 4.0
END DESCRIPTION:
XS GIS Cut Line= 3
      2912657.53      6976747.43        2912175.        6975975.
      2911517.99      6975957.54
#Sta/Elev= 30
  4060.1  384.13  4086.5   383.5  4144.7   378.6    4449  357.76  4512.7  355.14
  4564.6  350.75  4616.5  347.89  4680.4  346.37  4728.3  345.85  4847.6  343.87
  4980.9  343.86  4990.9  343.29  4997.6   339.4  4998.1   338.6  5003.6   338.6
  5004.1   339.4  5010.9  342.83  5020.9   344.2  5065.5  346.37  5076.4  347.16
  5119.2   350.7  5157.5  354.33    5311  362.46    5341  361.85    5351  362.56
    5361  364.98    5381   364.7    5401  367.88  5530.8  372.48  5628.1  378.25
#Mann= 6 ,-1 , 0
  4060.1     .16       0  4728.3     .12       0  4997.6     .07       0
  5004.1     .12       0  5076.4     .16       0  5119.2     .05       0
Bank Sta=4680.4,5065.5
XS Rating Curve= 0 ,0
Exp/Cntr=0.3,0.1

Type RM Length L Ch R = 1 ,3467    ,444,444,444
BEGIN DESCRIPTION:
Mapping XS f46e48dc
END DESCRIPTION:
XS GIS Cut Line= 3
       2912926.6      6975618.95      2912193.11      6975623.29
      2911533.35      6975844.66
#Sta/Elev= 30
  4217.7  379.57  4289.3  376.87  4299.3  375.31  4394.7  375.37  4409.3  371.91
  4439.3  369.07  4466.3  367.97  4559.3  359.19  4567.5  359.28  4649.3  358.97
  4787.8  350.67  4882.5  344.64  4928.7  343.23  4980.8  341.65  4991.4  340.68
  5002.1  337.71  5002.6  336.91  5008.4  336.91  5008.9  337.71  5012.5  342.75
  5063.3  341.77  5150.9  343.44    5183  344.64  5289.3  349.54  5328.9  352.82
  5352.4   356.6  5360.6  356.38  5383.3  358.51    5481   366.9  5647.1  376.66
#Mann= 10 ,-1 , 0
  4217.7     .05       0  4466.3     .16       0  4567.5     .12       0
  4787.8     .16       0  4928.7     .12       0  5002.1     .07       0
  5008.9     .12       0  5150.9     .16       0  5383.3      .1       0
    5481     .05       0
Bank Sta=4882.5,5183
XS Rating Curve= 0 ,0
Exp/Cntr=0.3,0.1

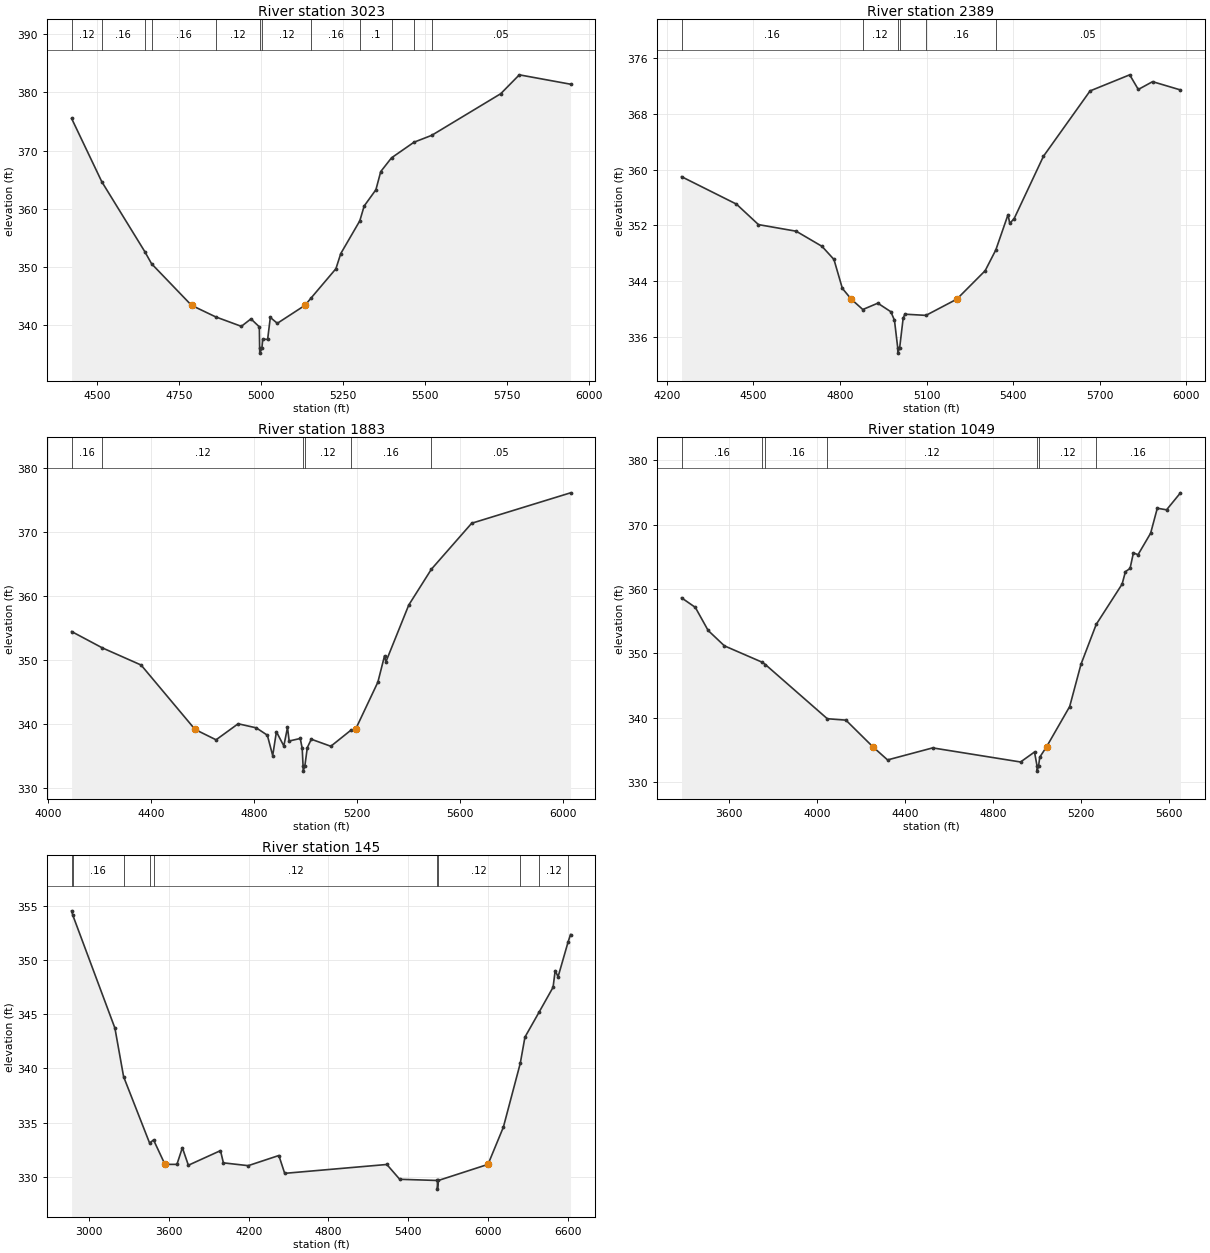
Type RM Length L Ch R = 1 ,3023    ,634,634,634
BEGIN DESCRIPTION:
UNT 069 IN DRY CR WATERSHED 3.0
END DESCRIPTION:
XS GIS Cut Line= 3
      2912575.01        6975375.        2912025.        6975225.
      2911243.17      6975770.46
#Sta/Elev= 30
  4421.3  375.51  4513.4  364.65  4644.6  352.66  4665.5  350.56  4787.4  343.43
  4861.3  341.44  4939.6  339.82  4968.9   341.1  4994.5  339.73  4995.4  336.02
  4995.9  335.22  5002.2  336.02  5004.9  337.63  5019.8  337.57    5028  341.35
  5049.4  340.34  5133.9  343.43  5152.6  344.69  5228.3  349.71  5243.1  352.31
  5301.2  357.93  5314.6  360.48  5350.4  363.27  5365.2  366.39  5398.1  368.75
  5466.7  371.43  5520.8  372.61  5731.6  379.76  5788.3     383  5944.7  381.39
#Mann= 12 ,-1 , 0
  4421.3     .12       0  4513.4     .16       0  4644.6     .12       0
  4665.5     .16       0  4861.3     .12       0  4995.4     .07       0
  5002.2     .12       0  5152.6     .16       0  5301.2      .1       0
  5398.1     .05       0  5466.7      .1       0  5520.8     .05       0
Bank Sta=4787.4,5133.9
XS Rating Curve= 0 ,0
Exp/Cntr=0.3,0.1

Type RM Length L Ch R = 1 ,2389    ,506,506,506
BEGIN DESCRIPTION:
Mapping XS f544a877
END DESCRIPTION:
XS GIS Cut Line= 3
      2912479.59      6974941.87      2911837.21      6974664.09
      2910960.48      6975202.28
#Sta/Elev= 30
  4251.1  358.98  4441.3  355.04  4517.6   352.1  4648.3  351.15  4737.7  348.98
  4779.1   347.1  4808.2  342.95  4839.1   341.4  4879.1  339.91  4931.1  340.82
  4976.3  339.59  4988.8  338.37    5000  334.45  5000.5  333.65  5006.9  334.45
  5018.9  338.65  5024.7  339.24  5097.9  339.07  5204.9   341.4    5303  345.48
    5340  348.47  5382.3  353.53  5388.2  352.27  5403.6  352.97    5505  361.91
  5666.5  371.29  5803.8   373.6  5833.6   371.5  5883.1  372.62  5979.7  371.43
#Mann= 6 ,-1 , 0
  4251.1     .16       0  4879.1     .12       0    5000     .07       0
  5006.9     .12       0  5097.9     .16       0    5340     .05       0
Bank Sta=4839.1,5204.9
XS Rating Curve= 0 ,0
Exp/Cntr=0.3,0.1

Type RM Length L Ch R = 1 ,1883    ,834,834,834
BEGIN DESCRIPTION:
Mapping XS 391e0b7a
END DESCRIPTION:
XS GIS Cut Line= 3
      2912361.06      6974838.99      2911649.28      6974261.75
      2910681.38      6974591.61
#Sta/Elev= 30
  4091.6  354.49  4211.1  351.93  4361.6  349.25  4571.4  339.17    4653  337.55
  4738.8  340.06  4809.2  339.42  4852.3  338.27  4873.1  335.08  4887.5  338.81
  4916.3  336.59  4930.6  339.48  4937.1  337.36  4980.2  337.76  4987.8   336.2
  4991.1  333.45  4991.6  332.65    4998  333.45  5007.6  336.33  5023.1  337.64
    5099  336.54  5176.6  339.04  5194.9  339.17  5281.8  346.57  5307.8   350.7
  5313.1  349.76  5401.9  358.64  5489.8  364.24  5646.4  371.43  6030.6  376.19
#Mann= 6 ,-1 , 0
  4091.6     .16       0  4211.1     .12       0  4991.1     .07       0
    4998     .12       0  5176.6     .16       0  5489.8     .05       0
Bank Sta=4571.4,5194.9
XS Rating Curve= 0 ,0
Exp/Cntr=0.3,0.1

Type RM Length L Ch R = 1 ,1049    ,904,904,904
BEGIN DESCRIPTION:
Mapping XS 22c3e5a0
END DESCRIPTION:
XS GIS Cut Line= 4
      2912530.35      6974886.73      2912074.62      6974122.86
      2911627.58      6973662.79      2911008.47      6974065.42
#Sta/Elev= 30
  3384.1  358.61  3446.7  357.13  3505.1  353.54  3579.1  351.15  3751.4   348.6
    3766  348.23  4047.2  339.83  4131.8  339.61  4254.1  335.48  4321.3  333.43
  4526.4   335.3  4926.2  333.11  4989.7  334.66  5001.2  332.49  5001.7  331.69
  5008.2  332.49  5013.6  333.86  5044.6  335.48  5149.6  341.72    5201  348.28
  5270.3  354.48  5388.1  360.74  5403.2  362.67  5424.3  363.18  5439.5  365.59
  5460.6  365.31  5517.9  368.65  5548.2  372.53  5590.4  372.28  5653.6  374.92
#Mann= 7 ,-1 , 0
  3384.1     .16       0  3751.4     .12       0    3766     .16       0
  4047.2     .12       0  5001.2     .07       0  5008.2     .12       0
  5270.3     .16       0
Bank Sta=4254.1,5044.6
XS Rating Curve= 0 ,0
Exp/Cntr=0.3,0.1

Type RM Length L Ch R = 1 ,145     ,0,0,0
BEGIN DESCRIPTION:
UNT 069 IN DRY CR WATERSHED 1.0
END DESCRIPTION:
XS GIS Cut Line= 4
      2912625.01      6974775.03      2911856.74      6973076.85
      2911408.83      6972701.85       2910774.1      6973841.23
#Sta/Elev= 30
  2868.3  354.58  2876.5   354.2    3194  343.73  3259.3  339.24  3454.8   333.1
  3484.5  333.39  3570.3  331.13  3660.4  331.13  3701.2  332.67  3746.4  331.05
  3987.9   332.4  4009.8  331.27  4196.4  331.01  4426.9  331.95  4470.8   330.3
    5239  331.12  5335.8  329.75  5619.2  329.64  5619.7  328.84  5626.2  329.64
  5999.9  331.13  6115.4  334.57  6242.6  340.48  6277.7   342.9  6385.5  345.24
  6489.2  347.51  6505.2  349.05  6526.9  348.48  6601.2  351.66  6620.6  352.39
#Mann= 10 ,-1 , 0
  2868.3     .05       0  2876.5     .16       0  3259.3     .12       0
  3454.8     .16       0  3484.5     .12       0  5619.2     .07       0
  5626.2     .12       0  6242.6     .16       0  6385.5     .12       0
  6601.2     .16       0
Bank Sta=3570.3,5999.9
XS Rating Curve= 0 ,0
Exp/Cntr=0.3,0.1
LCMann Table=0

Chan Stop Cuts=-1
Use User Specified Reach Order=0
Composite Channel Slope=5