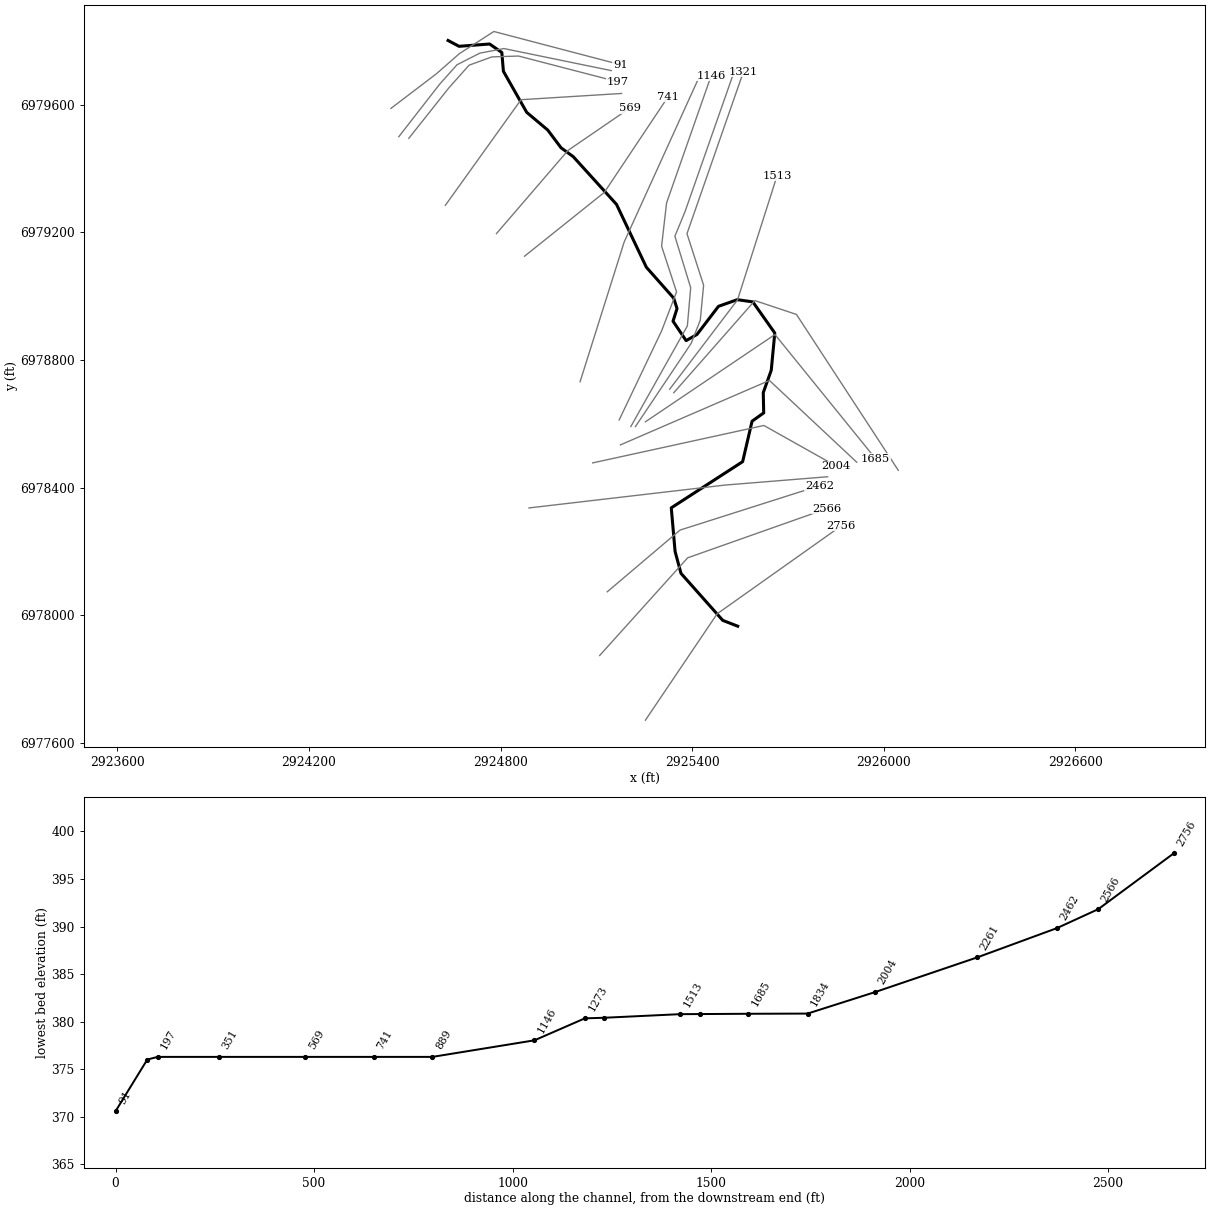
--- UNT 070 IN DRY CR WATERSHED.prj (project) ---

Proj Title=UNT 070 IN DRY CR WATERSHED Base Level Engineering
Current Plan=p01
Default Exp/Contr=0.3,0.1
English Units
Geom File=g01
Flow File=f01
Plan File=p01
BEGIN DESCRIPTION:
UNT 070 IN DRY CR WATERSHED
END DESCRIPTION:

--- UNT 070 IN DRY CR WATERSHED.p01 (plan) ---

Plan Title=Multiple Run
Short Identifier=Multiple
Geom File=g01
Flow File=f01
Subcritical Flow
K Sum by GR= 0
Std Step Tol= 0.01
Critical Tol= 0.01
Num of Std Step Trials= 20
Max Error Tol= 0.3
Flow Tol Ratio= 0.001
Split Flow NTrial= 30
Split Flow Tol= 0.02
Split Flow Ratio= 0.02
Log Output Level= 0
Friction Slope Method= 1
Unsteady Friction Slope Method= 2
Unsteady Bridges Friction Slope Method= 1
Parabolic Critical Depth
Global Vel Dist=  1 , 1 , 1
Global Log Level= 0
CheckData=True
Encroach Param= -1, 0, 0, 0
BEGIN DESCRIPTION:
Multiple Run
END DESCRIPTION:

--- UNT 070 IN DRY CR WATERSHED.f01 (steady flow) ---

Flow Title=Multiple
Number of Profiles=7
Profile Names=10-year,25-year,50-year,1pct_min,100-year,1pct_plu,500-year
River Rch & RM= UNT 070 IN DRY C,Reach-1,2756
     829    1152    1427     879    1754    3499    2654
Boundary for River Rch & Prof#=UNT 070 IN DRY C,Reach-1,1
Up Type=0
Dn Type=3
Dn Slope=0.005
Boundary for River Rch & Prof#=UNT 070 IN DRY C,Reach-1,2
Up Type=0
Dn Type=3
Dn Slope=0.005
Boundary for River Rch & Prof#=UNT 070 IN DRY C,Reach-1,3
Up Type=0
Dn Type=3
Dn Slope=0.005
Boundary for River Rch & Prof#=UNT 070 IN DRY C,Reach-1,4
Up Type=0
Dn Type=3
Dn Slope=0.005
Boundary for River Rch & Prof#=UNT 070 IN DRY C,Reach-1,5
Up Type=0
Dn Type=3
Dn Slope=0.005
Boundary for River Rch & Prof#=UNT 070 IN DRY C,Reach-1,6
Up Type=0
Dn Type=3
Dn Slope=0.005
Boundary for River Rch & Prof#=UNT 070 IN DRY C,Reach-1,7
Up Type=0
Dn Type=3
Dn Slope=0.005

--- UNT 070 IN DRY CR WATERSHED.g01 (geometry) ---

Geom Title=Existing Conditions

River Reach=UNT 070 IN DRY C,Reach-1
Reach XY= 30
      2925542.77      6977966.19      2925495.89      6977984.42
      2925365.03      6978131.77      2925346.59      6978200.13
      2925334.65      6978336.85      2925558.18      6978481.53
      2925587.69      6978608.26      2925624.15      6978634.30
      2925622.76      6978697.67      2925647.76      6978767.81
      2925658.87      6978884.48      2925590.12      6978981.95
      2925541.51      6978988.89      2925482.48      6978968.06
      2925415.17      6978879.93      2925381.14      6978860.65
      2925340.13      6978921.53      2925352.67      6978961.01
      2925342.25      6978993.75      2925256.54      6979090.55
      2925163.04      6979287.50      2925027.62      6979436.81
      2924989.43      6979464.59      2924947.76      6979520.14
      2924881.79      6979575.70      2924808.87      6979704.17
      2924803.90      6979763.12      2924765.68      6979789.70
      2924669.90      6979782.45      2924635.59      6979800.71

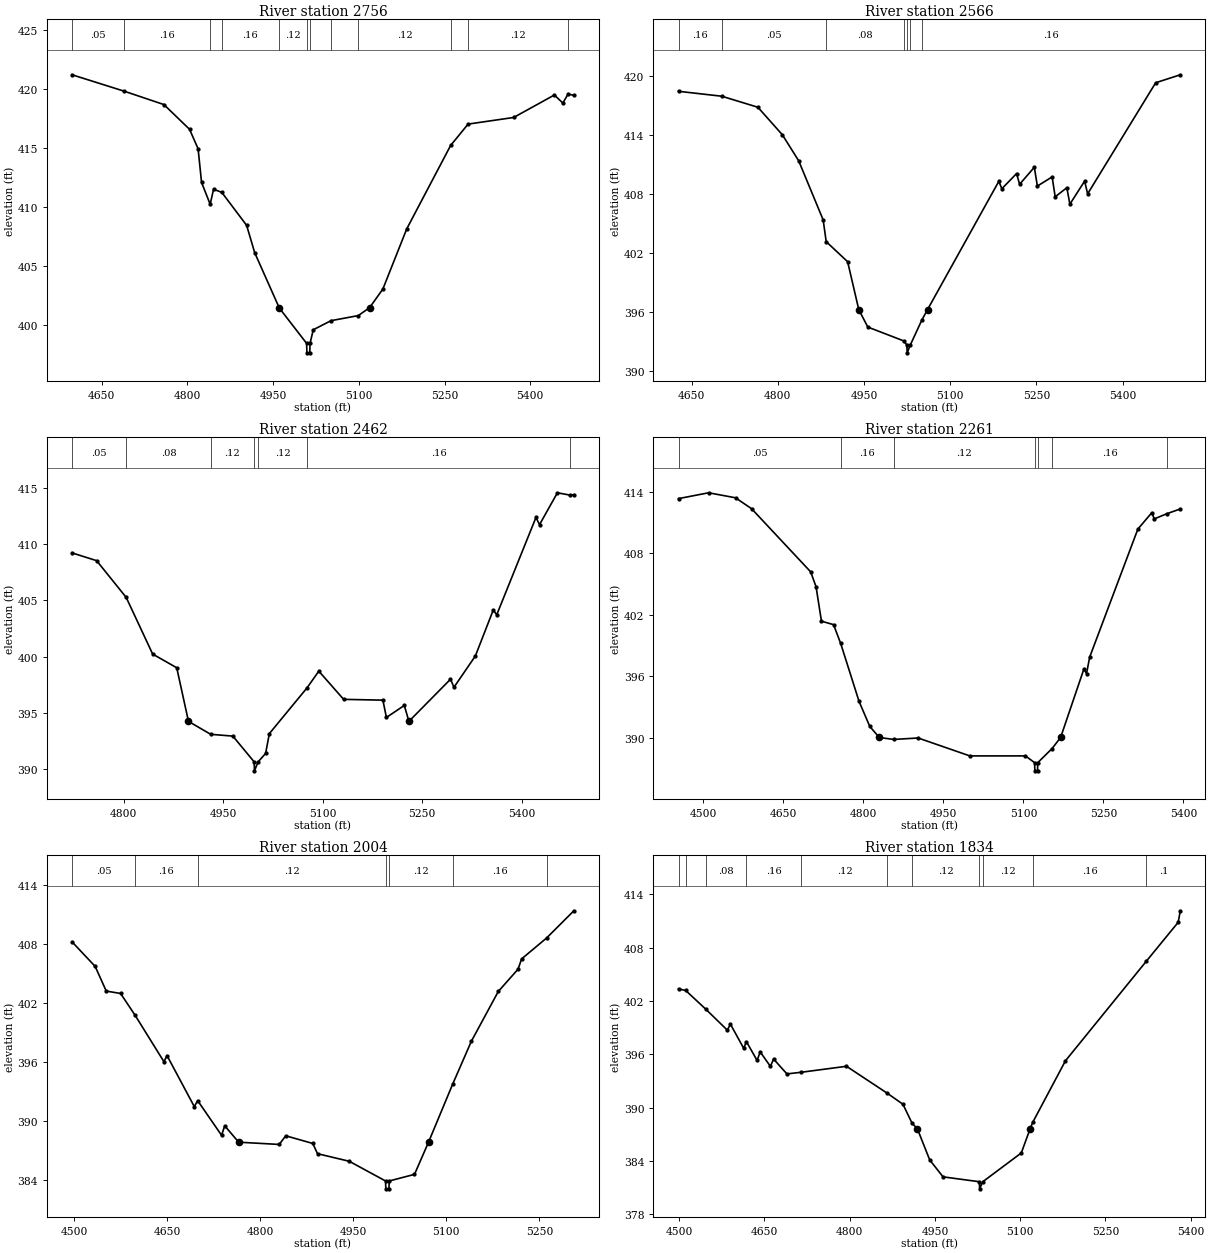
Type RM Length L Ch R = 1,2756,190,190,190
BEGIN DESCRIPTION:
UNT 070 IN DRY CR WATERSHED 4.0
END DESCRIPTION:
XS GIS Cut Line= 3
      2925253.57      6977671.71      2925478.26      6978004.94
      2925866.86      6978280.34
#Sta/Elev= 30
  4598.1  421.19  4688.8  419.81  4758.9  418.67  4803.7  416.58  4818.7  414.93
  4824.7  412.09  4839.8  410.24  4845.7  411.51  4860.1  411.25  4903.6  408.46
  4917.7  406.15  4959.7  401.59  4960.3  401.50  5008.6  398.48  5009.1  397.68
  5014.1  397.68  5014.6  398.48  5020.2  399.63  5051.3  400.40  5099.1  400.83
  5118.8  401.50  5142.0  403.07  5183.8  408.16  5260.7  415.22  5291.2  417.02
  5370.9  417.58  5442.2  419.48  5457.0  418.80  5466.2  419.56  5476.3  419.45
#Mann=12,-1,0
  4598.1    0.05       0  4688.8    0.16       0  4839.8    0.08       0
  4860.1    0.16       0  4959.7    0.12       0  5008.6    0.07       0
  5014.6    0.12       0  5051.3    0.16       0  5099.1    0.12       0
  5260.7    0.16       0  5291.2    0.12       0  5466.2    0.16       0
Bank Sta=4960.3,5118.8
Exp/Cntr=0.3,0.1

Type RM Length L Ch R = 1,2566,104,104,104
BEGIN DESCRIPTION:
Mapping XS 97657315
END DESCRIPTION:
XS GIS Cut Line= 3
      2925110.33      6977874.38      2925385.94      6978180.37
      2925821.08      6978334.08
#Sta/Elev= 30
  4627.3  418.40  4702.6  417.90  4765.4  416.78  4808.0  413.98  4836.4  411.34
  4879.0  405.33  4884.3  403.12  4921.6  401.08  4941.0  396.21  4956.7  394.44
  5018.9  393.04  5024.7  392.62  5025.2  391.82  5030.7  392.62  5050.8  395.16
  5060.6  396.21  5184.7  409.25  5190.0  408.50  5215.6  410.04  5220.9  408.95
  5246.5  410.68  5251.8  408.77  5277.5  409.70  5282.8  407.68  5303.1  408.60
  5308.4  406.93  5334.0  409.27  5339.3  407.98  5457.7  419.27  5500.6  420.08
#Mann=7,-1,0
  4627.3    0.16       0  4702.6    0.05       0  4884.3    0.08       0
  5018.9    0.12       0  5024.7    0.07       0  5030.7    0.12       0
  5050.8    0.16       0
Bank Sta=4941,5060.6
Exp/Cntr=0.3,0.1

Type RM Length L Ch R = 1,2462,201,201,201
BEGIN DESCRIPTION:
Mapping XS 33370c6b
END DESCRIPTION:
XS GIS Cut Line= 3
      2925134.20      6978074.03      2925362.07      6978267.18
      2925798.27      6978406.07
#Sta/Elev= 30
  4722.4  409.22  4759.4  408.53  4804.0  405.26  4843.9  400.22  4880.2  399.00
  4897.9  394.23  4931.4  393.08  4964.8  392.92  4996.9  390.63  4997.4  389.83
  5002.9  390.63  5014.2  391.38  5019.8  393.14  5076.6  397.21  5094.4  398.70
  5131.8  396.19  5191.0  396.12  5196.3  394.58  5223.3  395.65  5230.2  394.23
  5292.9  397.98  5298.2  397.27  5330.4  400.05  5357.4  404.14  5362.6  403.71
  5421.8  412.38  5427.1  411.73  5454.1  414.57  5473.3  414.36  5478.9  414.40
#Mann=7,-1,0
  4722.4    0.05       0  4804.0    0.08       0  4931.4    0.12       0
  4996.9    0.07       0  5002.9    0.12       0  5076.6    0.16       0
  5473.3     0.1       0
Bank Sta=4897.9,5230.2
Exp/Cntr=0.3,0.1

Type RM Length L Ch R = 1,2261,257,257,257
BEGIN DESCRIPTION:
Mapping XS b7d2ec97
END DESCRIPTION:
XS GIS Cut Line= 3
      2924888.94      6978336.62      2925503.12      6978408.24
      2925824.33      6978434.28
#Sta/Elev= 30
  4453.5  413.36  4509.9  413.93  4560.3  413.44  4590.5  412.37  4701.2  406.20
  4711.3  404.74  4721.4  401.38  4744.1  401.04  4757.4  399.21  4791.8  393.55
  4812.0  391.09  4829.8  390.01  4856.9  389.82  4902.6  389.96  4999.5  388.21
  5103.8  388.21  5120.9  387.55  5121.4  386.75  5126.4  386.75  5126.9  387.55
  5153.7  388.93  5169.7  390.01  5213.3  396.70  5218.3  396.26  5224.2  397.87
  5314.5  410.38  5340.4  411.97  5345.4  411.38  5369.2  411.89  5394.1  412.35
#Mann=7,-1,0
  4453.5    0.05       0  4757.4    0.16       0  4856.9    0.12       0
  5120.9    0.07       0  5126.9    0.12       0  5153.7    0.16       0
  5369.2     0.1       0
Bank Sta=4829.8,5169.7
Exp/Cntr=0.3,0.1

Type RM Length L Ch R = 1,2004,170,170,170
BEGIN DESCRIPTION:
Mapping XS 8f893d5b
END DESCRIPTION:
XS GIS Cut Line= 3
      2925088.63      6978477.68      2925624.65      6978594.87
      2925851.25      6978467.55
#Sta/Elev= 30
  4496.9  408.20  4534.1  405.71  4552.0  403.20  4575.1  402.96  4598.5  400.74
  4644.9  396.03  4650.0  396.64  4693.9  391.46  4699.3  392.07  4737.8  388.55
  4742.9  389.51  4765.4  387.85  4830.7  387.62  4841.2  388.50  4884.8  387.72
  4892.4  386.68  4943.6  385.91  5002.0  383.91  5002.5  383.11  5007.5  383.11
  5008.0  383.91  5048.7  384.58  5071.3  387.85  5110.1  393.73  5140.3  398.10
  5183.7  403.16  5215.6  405.43  5221.3  406.47  5261.5  408.59  5305.5  411.36
#Mann=7,-1,0
  4496.9    0.05       0  4598.5    0.16       0  4699.3    0.12       0
  5002.0    0.07       0  5008.0    0.12       0  5110.1    0.16       0
  5261.5     0.1       0
Bank Sta=4765.4,5071.3
Exp/Cntr=0.3,0.1

Type RM Length L Ch R = 1,1834,149,149,149
BEGIN DESCRIPTION:
Mapping XS 9072e7f1
END DESCRIPTION:
XS GIS Cut Line= 3
      2925175.45      6978534.12      2925642.01      6978735.93
      2925915.41      6978479.89
#Sta/Elev= 30
  4498.9  403.36  4511.4  403.19  4547.0  401.07  4584.7  398.72  4590.2  399.39
  4613.6  396.67  4618.3  397.43  4637.1  395.31  4642.6  396.27  4660.6  394.63
  4666.1  395.47  4689.6  393.79  4715.2  393.98  4794.4  394.65  4866.5  391.60
  4893.8  390.37  4909.8  388.24  4919.1  387.62  4940.8  384.11  4964.3  382.20
  5028.2  381.65  5028.7  380.85  5034.2  381.65  5102.0  384.89  5117.6  387.63
  5122.2  388.35  5179.7  395.27  5322.1  406.49  5378.0  410.86  5381.8  412.16
#Mann=11,-1,0
  4498.9    0.05       0  4511.4    0.16       0  4547.0    0.08       0
  4618.3    0.16       0  4715.2    0.12       0  4866.5    0.16       0
  4909.8    0.12       0  5028.2    0.07       0  5034.2    0.12       0
  5122.2    0.16       0  5322.1     0.1       0
Bank Sta=4919.1,5117.6
Exp/Cntr=0.3,0.1

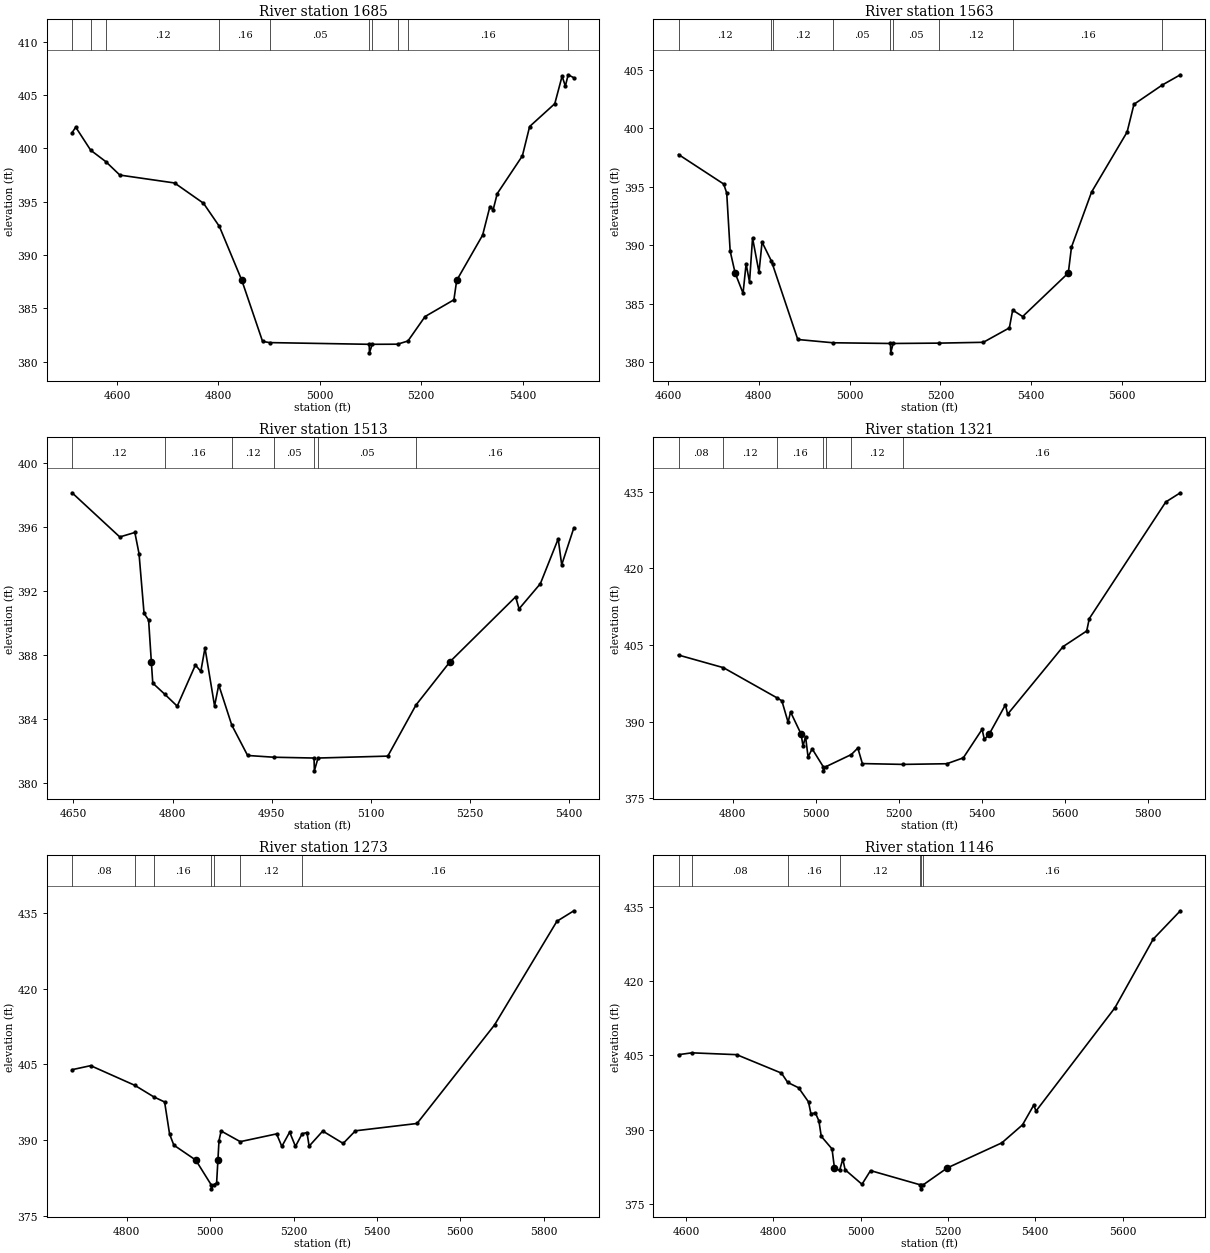
Type RM Length L Ch R = 1,1685,122,122,122
BEGIN DESCRIPTION:
Mapping XS 278bd148
END DESCRIPTION:
XS GIS Cut Line= 3
      2925253.54      6978606.29      2925659.37      6978879.74
      2925974.06      6978491.27
#Sta/Elev= 30
  4511.6  401.46  4518.8  401.98  4548.3  399.82  4578.1  398.75  4605.8  397.49
  4713.7  396.75  4770.7  394.85  4802.0  392.68  4846.3  387.62  4887.2  381.90
  4901.0  381.79  5097.4  381.63  5097.9  380.83  5103.4  381.63  5153.3  381.64
  5173.8  381.94  5207.5  384.23  5264.4  385.80  5269.9  387.62  5321.0  391.86
  5335.4  394.54  5341.8  394.24  5349.8  395.75  5399.4  399.29  5413.7  402.04
  5463.3  404.18  5477.7  406.76  5484.1  405.83  5489.7  406.89  5500.9  406.61
#Mann=10,-1,0
  4511.6    0.08       0  4548.3    0.16       0  4578.1    0.12       0
  4802.0    0.16       0  4901.0    0.05       0  5097.4   0.033       0
  5103.4    0.05       0  5153.3    0.12       0  5173.8    0.16       0
  5489.7     0.1       0
Bank Sta=4846.3,5269.9
Exp/Cntr=0.3,0.1

Type RM Length L Ch R = 1,1563,50,50,50
BEGIN DESCRIPTION:
Mapping XS eab760d7
END DESCRIPTION:
XS GIS Cut Line= 4
      2925342.51      6978697.42      2925596.44      6978986.07
      2925726.65      6978942.67      2926045.68      6978454.36
#Sta/Elev= 30
  4623.3  397.74  4722.7  395.22  4729.4  394.45  4737.0  389.49  4747.9  387.62
  4765.4  385.89  4772.1  388.41  4779.6  386.84  4786.3  390.61  4800.5  387.68
  4807.2  390.26  4827.3  388.68  4830.3  388.36  4885.9  381.94  4963.3  381.66
  5090.0  381.60  5090.5  380.80  5096.0  381.60  5197.3  381.63  5294.5  381.70
  5351.8  382.93  5359.1  384.45  5381.1  383.90  5481.6  387.62  5488.6  389.83
  5532.8  394.53  5611.1  399.66  5626.2  402.03  5688.7  403.68  5728.3  404.55
#Mann=9,-1,0
  4623.3    0.12       0  4827.3    0.16       0  4830.3    0.12       0
  4963.3    0.05       0  5090.0   0.033       0  5096.0    0.05       0
  5197.3    0.12       0  5359.1    0.16       0  5688.7     0.1       0
Bank Sta=4747.9,5481.6
Exp/Cntr=0.3,0.1

Type RM Length L Ch R = 1,1513,192,192,192
BEGIN DESCRIPTION:
Mapping XS bd131c43
END DESCRIPTION:
XS GIS Cut Line= 3
      2925329.53      6978708.31      2925542.19      6978988.24
      2925665.88      6979376.68
#Sta/Elev= 30
  4647.9  398.16  4720.1  395.40  4742.9  395.68  4749.2  394.36  4756.8  390.63
  4763.7  390.21  4767.8  387.62  4770.0  386.27  4788.3  385.57  4807.0  384.83
  4834.5  387.40  4842.7  387.00  4849.0  388.47  4863.5  384.84  4869.8  386.16
  4889.5  383.65  4913.5  381.75  4953.3  381.64  5014.0  381.59  5014.5  380.79
  5020.0  381.59  5125.6  381.71  5168.2  384.90  5220.0  387.62  5319.0  391.66
  5324.2  390.91  5356.4  392.48  5383.4  395.28  5388.7  393.66  5407.1  395.97
#Mann=7,-1,0
  4647.9    0.12       0  4788.3    0.16       0  4889.5    0.12       0
  4953.3    0.05       0  5014.0   0.033       0  5020.0    0.05       0
  5168.2    0.16       0
Bank Sta=4767.8,5220
Exp/Cntr=0.3,0.1

Type RM Length L Ch R = 1,1321,48,48,48
BEGIN DESCRIPTION:
Mapping XS e7e4f224
END DESCRIPTION:
XS GIS Cut Line= 6
      2925222.39      6978591.46      2925396.86      6978851.87
      2925425.51      6978924.79      2925435.93      6979034.16
      2925383.84      6979195.62      2925560.93      6979703.44
#Sta/Elev= 30
  4669.3  403.06  4777.6  400.59  4906.9  394.68  4918.4  394.11  4933.4  389.92
  4939.4  391.92  4964.7  387.61  4969.4  385.26  4975.5  387.11  4981.6  383.11
  4991.4  384.72  5018.2  381.21  5018.7  380.41  5024.2  381.21  5085.9  383.60
  5101.5  384.87  5112.5  381.83  5210.1  381.67  5316.1  381.80  5355.8  382.95
  5401.1  388.53  5406.6  386.56  5418.3  387.60  5457.4  393.33  5462.6  391.48
  5596.4  404.72  5653.3  407.77  5659.5  410.19  5843.9  433.01  5879.0  434.81
#Mann=7,-1,0
  4669.3    0.08       0  4777.6    0.12       0  4906.9    0.16       0
  5018.2    0.07       0  5024.2    0.16       0  5085.9    0.12       0
  5210.1    0.16       0
Bank Sta=4964.7,5418.3
Exp/Cntr=0.3,0.1

Type RM Length L Ch R = 1,1273,127,127,127
BEGIN DESCRIPTION:
Mapping XS 45422183
END DESCRIPTION:
XS GIS Cut Line= 6
      2925207.93      6978591.42      2925385.02      6978906.53
      2925395.44      6979026.32      2925345.96      6979187.78
      2925377.21      6979263.30      2925533.45      6979708.58
#Sta/Elev= 30
  4668.6  403.96  4713.2  404.76  4819.2  400.86  4864.6  398.58  4890.7  397.56
  4902.6  391.21  4912.8  389.01  4965.4  386.05  5002.4  381.15  5002.9  380.35
  5008.4  381.15  5015.5  381.52  5018.6  386.05  5021.2  389.90  5026.3  391.81
  5072.2  389.70  5159.4  391.24  5172.0  388.76  5190.8  391.59  5204.7  388.76
  5220.8  391.27  5232.3  391.51  5237.5  388.81  5270.2  391.80  5319.2  389.35
  5348.6  391.85  5496.4  393.30  5682.4  412.82  5832.1  433.37  5872.8  435.45
#Mann=7,-1,0
  4668.6    0.08       0  4819.2    0.12       0  4864.6    0.16       0
  5002.4    0.07       0  5008.4    0.16       0  5072.2    0.12       0
  5220.8    0.16       0
Bank Sta=4965.4,5018.6
Exp/Cntr=0.3,0.1

Type RM Length L Ch R = 1,1146,257,257,257
BEGIN DESCRIPTION:
Mapping XS f65d87de
END DESCRIPTION:
XS GIS Cut Line= 6
      2925171.47      6978612.25      2925304.29      6978890.91
      2925351.17      6979013.30      2925304.29      6979156.53
      2925319.92      6979291.95      2925459.76      6979690.76
#Sta/Elev= 30
  4582.9  405.11  4613.5  405.48  4716.1  405.11  4818.6  401.39  4833.0  399.51
  4857.9  398.43  4880.6  395.58  4886.1  393.22  4896.5  393.33  4904.4  391.76
  4909.8  388.64  4934.5  386.09  4940.0  382.27  4951.8  381.75  4959.2  384.06
  4964.5  381.89  5003.1  378.96  5022.7  381.72  5136.1  378.86  5137.2  378.84
  5137.7  378.04  5143.2  378.84  5198.7  382.27  5323.5  387.32  5370.8  390.95
  5396.5  394.92  5401.8  393.74  5582.5  414.57  5670.2  428.42  5732.3  434.14
#Mann=7,-1,0
  4582.9    0.05       0  4613.5    0.08       0  4833.0    0.16       0
  4951.8    0.12       0  5136.1    0.16       0  5137.2    0.07       0
  5143.2    0.16       0
Bank Sta=4940,5198.7
Exp/Cntr=0.3,0.1

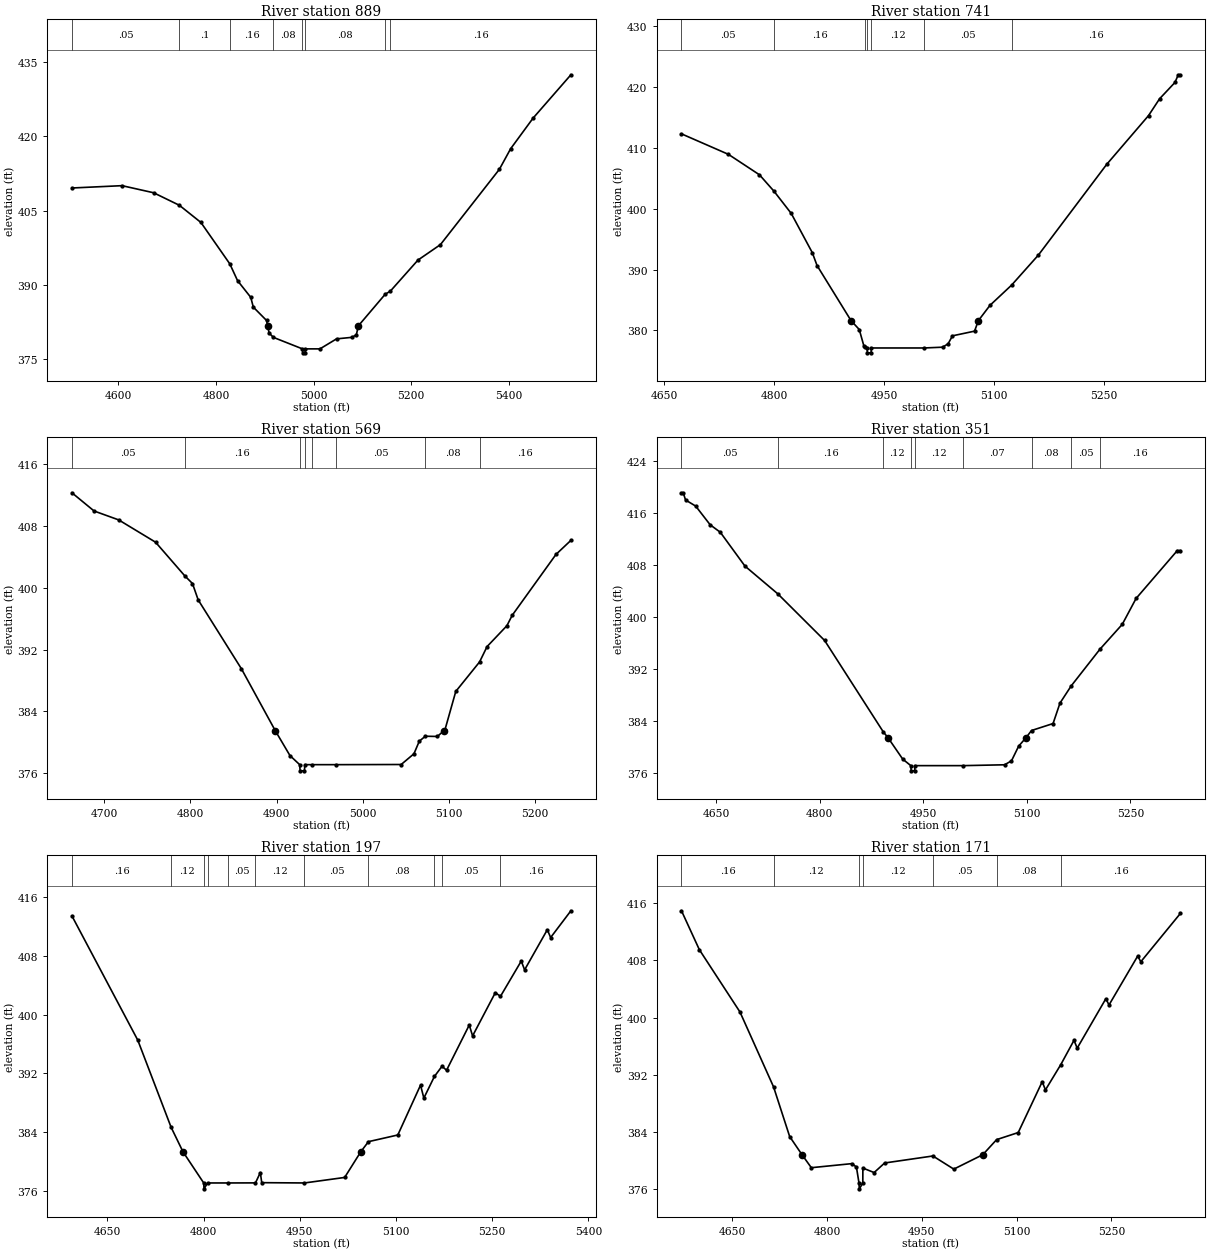
Type RM Length L Ch R = 1,889,148,148,148
BEGIN DESCRIPTION:
Mapping XS cb3ce61f
END DESCRIPTION:
XS GIS Cut Line= 3
      2925049.07      6978732.01      2925187.11      6979169.55
      2925420.74      6979683.54
#Sta/Elev= 30
  4504.5  409.57  4607.3  410.04  4672.0  408.61  4724.9  406.08  4769.0  402.62
  4828.3  394.26  4844.2  390.87  4871.3  387.50  4876.5  385.53  4903.7  382.83
  4905.9  381.74  4908.9  380.30  4917.7  379.42  4977.3  377.10  4977.8  376.30
  4982.8  376.30  4983.3  377.10  5013.2  377.10  5047.2  379.12  5079.1  379.43
  5087.9  379.96  5091.9  381.74  5147.3  388.16  5157.2  388.71  5214.2  395.02
  5260.3  398.14  5381.2  413.34  5404.2  417.48  5450.4  423.68  5527.9  432.42
#Mann=8,-1,0
  4504.5    0.05       0  4724.9     0.1       0  4828.3    0.16       0
  4917.7    0.08       0  4977.3    0.07       0  4983.3    0.08       0
  5147.3    0.05       0  5157.2    0.16       0
Bank Sta=4905.9,5091.9
Exp/Cntr=0.3,0.1

Type RM Length L Ch R = 1,741,172,172,172
BEGIN DESCRIPTION:
UNT 070 IN DRY CR WATERSHED 2.0
END DESCRIPTION:
XS GIS Cut Line= 3
      2924875.01      6979125.01      2925125.00      6979325.00
      2925325.00      6979625.00
#Sta/Elev= 30
  4673.7  412.33  4737.7  408.96  4780.1  405.59  4799.9  402.89  4823.4  399.24
  4852.2  392.77  4858.6  390.67  4905.0  381.60  4916.2  380.14  4922.6  377.40
  4924.4  377.27  4926.8  377.10  4927.3  376.30  4932.3  376.30  4932.8  377.10
  5004.6  377.10  5029.9  377.23  5037.4  377.79  5043.4  379.10  5073.5  379.87
  5078.7  381.60  5094.5  384.11  5124.1  387.45  5160.6  392.39  5253.7  407.30
  5310.8  415.33  5325.9  418.10  5346.9  420.79  5351.4  422.05  5354.4  422.05
#Mann=7,-1,0
  4673.7    0.05       0  4799.9    0.16       0  4924.4    0.12       0
  4926.8    0.07       0  4932.8    0.12       0  5004.6    0.05       0
  5124.1    0.16       0
Bank Sta=4905,5078.7
Exp/Cntr=0.3,0.1

Type RM Length L Ch R = 1,569,218,218,218
BEGIN DESCRIPTION:
Mapping XS 46120b53
END DESCRIPTION:
XS GIS Cut Line= 3
      2924787.22      6979195.96      2925011.19      6979456.40
      2925205.19      6979589.20
#Sta/Elev= 30
  4662.7  412.30  4688.4  409.94  4716.9  408.79  4759.7  405.90  4793.6  401.54
  4802.5  400.55  4809.1  398.43  4859.3  389.50  4898.5  381.50  4915.5  378.28
  4926.8  377.10  4927.3  376.30  4932.3  376.30  4932.8  377.10  4941.2  377.10
  4969.4  377.10  5044.5  377.12  5059.3  378.51  5065.5  380.14  5072.5  380.78
  5086.5  380.75  5094.0  381.50  5095.3  381.63  5107.8  386.58  5135.4  390.40
  5144.1  392.39  5167.1  395.09  5173.2  396.43  5224.0  404.32  5241.3  406.14
#Mann=8,-1,0
  4662.7    0.05       0  4793.6    0.16       0  4926.8    0.04       0
  4932.8    0.16       0  4941.2    0.07       0  4969.4    0.05       0
  5072.5    0.08       0  5135.4    0.16       0
Bank Sta=4898.5,5094
Exp/Cntr=0.3,0.1

Type RM Length L Ch R = 1,351,154,154,154
BEGIN DESCRIPTION:
Mapping XS d8b40b3a
END DESCRIPTION:
XS GIS Cut Line= 3
      2924627.08      6979284.53      2924864.06      6979615.26
      2925179.19      6979634.79
#Sta/Elev= 30
  4599.9  419.05  4602.4  419.05  4605.8  417.94  4620.5  417.00  4641.4  414.13
  4656.1  412.98  4691.8  407.78  4739.5  403.50  4807.2  396.34  4892.0  382.31
  4899.0  381.39  4920.3  378.10  4932.0  377.10  4932.5  376.30  4937.5  376.30
  4938.0  377.10  5007.7  377.10  5067.8  377.23  5077.8  377.84  5088.2  380.10
  5098.8  381.39  5106.8  382.50  5138.0  383.57  5148.0  386.71  5164.2  389.35
  5205.9  395.00  5238.2  398.82  5258.2  402.80  5317.9  410.16  5322.5  410.16
#Mann=9,-1,0
  4599.9    0.05       0  4739.5    0.16       0  4892.0    0.12       0
  4932.0    0.07       0  4938.0    0.12       0  5007.7    0.07       0
  5106.8    0.08       0  5164.2    0.05       0  5205.9    0.16       0
Bank Sta=4899,5098.8
Exp/Cntr=0.3,0.1

Type RM Length L Ch R = 1,197,26,26,26
BEGIN DESCRIPTION:
Mapping XS 5e3884be
END DESCRIPTION:
XS GIS Cut Line= 6
      2924512.50      6979494.17      2924637.50      6979651.71
      2924701.30      6979723.33      2924772.91      6979749.37
      2924856.25      6979751.97      2925167.45      6979671.24
#Sta/Elev= 30
  4594.7  413.44  4697.4  396.53  4749.4  384.67  4767.9  381.34  4800.2  377.10
  4800.7  376.30  4806.2  377.10  4837.7  377.10  4880.9  377.11  4888.5  378.51
  4890.7  377.14  4957.3  377.10  5020.0  377.85  5045.1  381.34  5057.1  382.72
  5102.9  383.63  5138.3  390.41  5143.5  388.65  5160.0  391.60  5171.8  392.98
  5178.9  392.44  5214.3  398.59  5219.5  397.11  5254.9  402.99  5263.0  402.50
  5295.4  407.30  5300.6  406.10  5336.0  411.56  5341.2  410.50  5372.8  414.14
#Mann=11,-1,0
  4594.7    0.16       0  4749.4    0.12       0  4800.2    0.04       0
  4806.2    0.12       0  4837.7    0.05       0  4880.9    0.12       0
  4957.3    0.05       0  5057.1    0.08       0  5160.0    0.16       0
  5171.8    0.05       0  5263.0    0.16       0
Bank Sta=4767.9,5045.1
Exp/Cntr=0.3,0.1

Type RM Length L Ch R = 1,171,80,80,80
BEGIN DESCRIPTION:
Mapping XS 1ff5f8b0
END DESCRIPTION:
XS GIS Cut Line= 6
      2924481.27      6979499.40      2924608.85      6979663.43
      2924663.54      6979724.63      2924735.15      6979761.09
      2924810.67      6979775.41      2925146.65      6979706.39
#Sta/Elev= 30
  4569.4  414.95  4597.7  409.50  4662.0  400.78  4715.2  390.29  4740.7  383.34
  4760.2  380.80  4775.0  378.98  4839.3  379.55  4846.4  379.07  4850.5  376.82
  4851.0  376.02  4856.5  376.82  4856.6  378.93  4874.4  378.30  4891.1  379.64
  4967.5  380.62  5000.6  378.78  5046.5  380.80  5068.4  382.91  5102.6  383.90
  5140.6  391.02  5145.7  389.87  5170.0  393.41  5190.9  396.81  5196.0  395.72
  5241.3  402.63  5246.4  401.77  5291.7  408.60  5296.8  407.82  5359.5  414.59
#Mann=7,-1,0
  4569.4    0.16       0  4715.2    0.12       0  4850.5    0.04       0
  4856.5    0.12       0  4967.5    0.05       0  5068.4    0.08       0
  5170.0    0.16       0
Bank Sta=4760.2,5046.5
Exp/Cntr=0.3,0.1

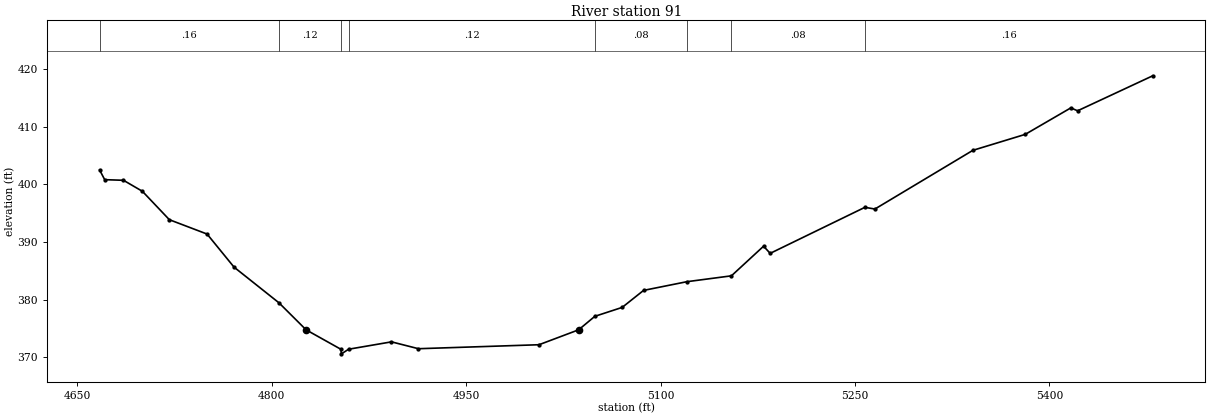
Type RM Length L Ch R = 1,91,0,0,0
BEGIN DESCRIPTION:
UNT 070 IN DRY CR WATERSHED 1.0
END DESCRIPTION:
XS GIS Cut Line= 5
      2924456.53      6979587.93      2924598.43      6979695.98
      2924671.35      6979759.79      2924779.04      6979828.87
      2925175.05      6979724.99
#Sta/Elev= 30
  4667.1  402.49  4671.0  400.82  4685.5  400.71  4700.1  398.80  4720.9  393.87
  4750.0  391.38  4770.8  385.64  4805.5  379.44  4826.4  374.76  4853.2  371.39
  4853.7  370.59  4859.2  371.39  4892.3  372.67  4913.1  371.48  5006.1  372.17
  5036.7  374.76  5049.2  377.10  5070.3  378.65  5086.8  381.60  5120.2  383.11
  5154.6  384.13  5179.4  389.27  5184.5  388.03  5257.6  396.02  5265.3  395.72
  5340.9  405.91  5381.3  408.68  5416.5  413.28  5421.7  412.77  5479.7  418.85
#Mann=8,-1,0
  4667.1    0.16       0  4805.5    0.12       0  4853.2    0.07       0
  4859.2    0.12       0  5049.2    0.08       0  5120.2    0.05       0
  5154.6    0.08       0  5257.6    0.16       0
Bank Sta=4826.4,5036.7
Exp/Cntr=0.3,0.1

Chan Stop Cuts=-1