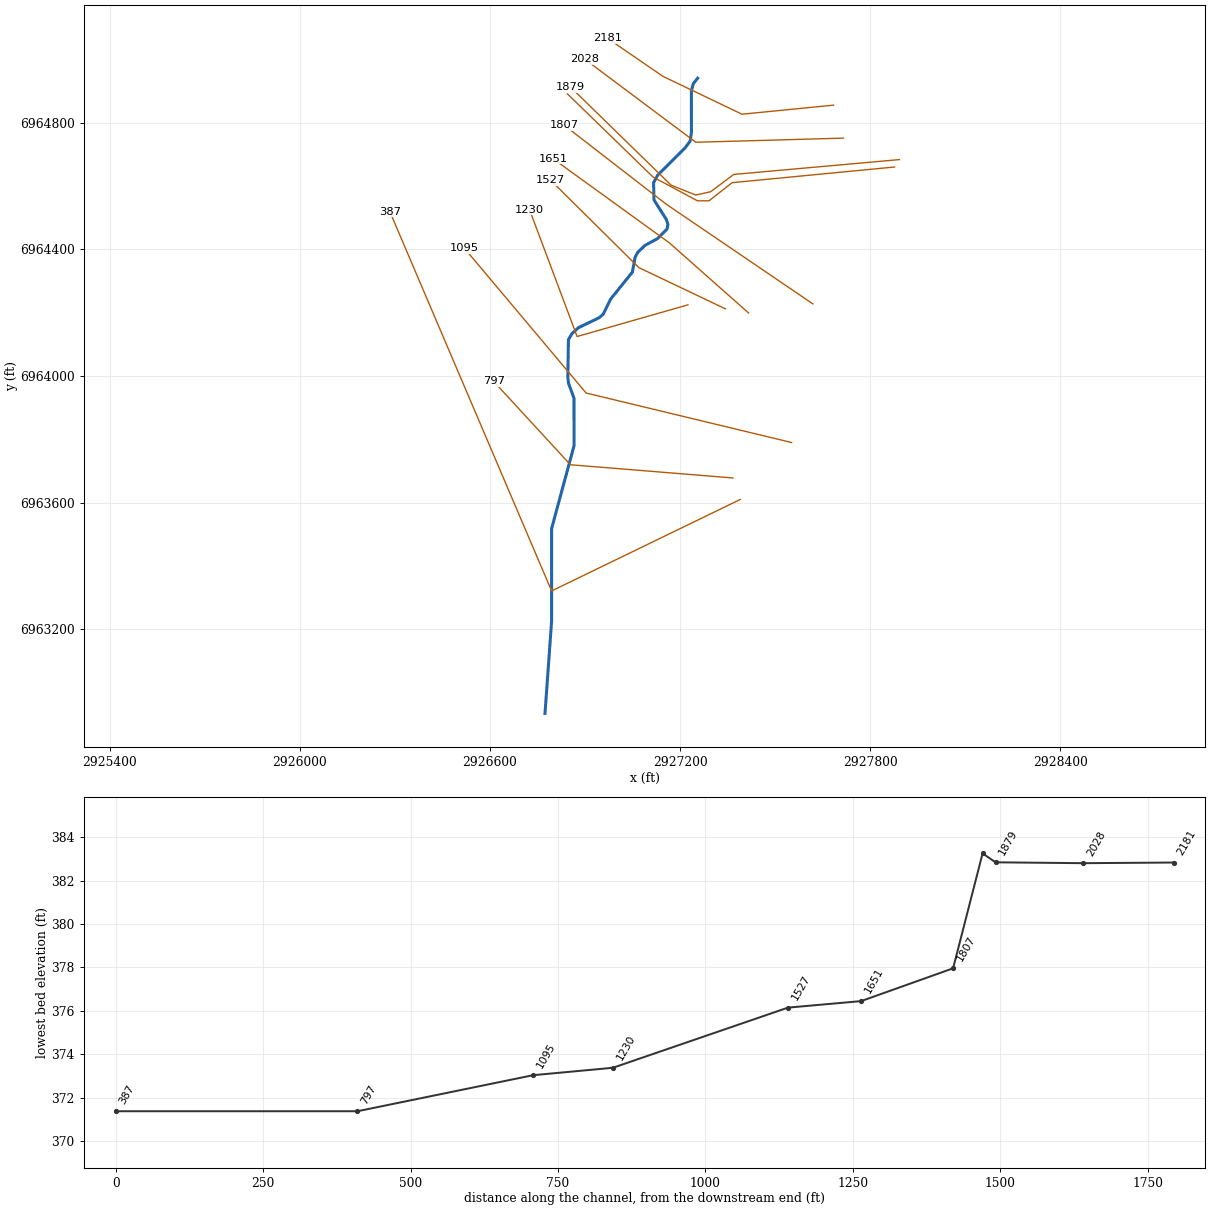
--- UNT 071 IN DRY CR WATERSHED.prj (project) ---

Proj Title=UNT 071 IN DRY CR WATERSHED Base Level Engineering
Current Plan=p01
Default Exp/Contr=0.3,0.1
English Units
Geom File=g01
Flow File=f01
Plan File=p01
BEGIN DESCRIPTION:
UNT 071 IN DRY CR WATERSHED
END DESCRIPTION:

--- UNT 071 IN DRY CR WATERSHED.p01 (plan) ---

Plan Title=Multiple Run
Short Identifier=Multiple
Geom File=g01
Flow File=f01
Subcritical Flow
K Sum by GR= 0
Std Step Tol= 0.01
Critical Tol= 0.01
Num of Std Step Trials= 20
Max Error Tol= 0.3
Flow Tol Ratio= 0.001
Split Flow NTrial= 30
Split Flow Tol= 0.02
Split Flow Ratio= 0.02
Log Output Level= 0
Friction Slope Method= 1
Unsteady Friction Slope Method= 2
Unsteady Bridges Friction Slope Method= 1
Parabolic Critical Depth
Global Vel Dist=  1 , 1 , 1
Global Log Level= 0
CheckData=True
Encroach Param= -1, 0, 0, 0
BEGIN DESCRIPTION:
Multiple Run
END DESCRIPTION:

--- UNT 071 IN DRY CR WATERSHED.f01 (steady flow) ---

Flow Title=Multiple
Number of Profiles=7
Profile Names=10-year,25-year,50-year,1pct_min,100-year,1pct_plu,500-year
River Rch & RM= UNT 071 IN DRY C,Reach-1,2181
     438     582     698     417     833    1662    1186
Boundary for River Rch & Prof#=UNT 071 IN DRY C,Reach-1,1
Up Type=0
Dn Type=3
Dn Slope=0.005
Boundary for River Rch & Prof#=UNT 071 IN DRY C,Reach-1,2
Up Type=0
Dn Type=3
Dn Slope=0.005
Boundary for River Rch & Prof#=UNT 071 IN DRY C,Reach-1,3
Up Type=0
Dn Type=3
Dn Slope=0.005
Boundary for River Rch & Prof#=UNT 071 IN DRY C,Reach-1,4
Up Type=0
Dn Type=3
Dn Slope=0.005
Boundary for River Rch & Prof#=UNT 071 IN DRY C,Reach-1,5
Up Type=0
Dn Type=3
Dn Slope=0.005
Boundary for River Rch & Prof#=UNT 071 IN DRY C,Reach-1,6
Up Type=0
Dn Type=3
Dn Slope=0.005
Boundary for River Rch & Prof#=UNT 071 IN DRY C,Reach-1,7
Up Type=0
Dn Type=3
Dn Slope=0.005

--- UNT 071 IN DRY CR WATERSHED.g01 (geometry) ---

Geom Title=Existing Conditions

River Reach=UNT 071 IN DRY C,Reach-1
Reach XY= 30
      2927255.59      6964940.71      2927241.96      6964923.40
      2927235.85      6964900.66      2927236.03      6964770.53
      2927232.05      6964742.17      2927214.83      6964719.36
      2927129.57      6964634.79      2927116.46      6964610.77
      2927117.75      6964556.46      2927156.14      6964495.51
      2927161.83      6964479.75      2927159.12      6964464.31
      2927129.26      6964434.30      2927089.30      6964412.67
      2927066.30      6964390.58      2927058.02      6964374.85
      2927049.66      6964328.47      2926980.84      6964243.15
      2926957.27      6964195.05      2926944.19      6964184.09
      2926879.07      6964152.83      2926858.88      6964134.23
      2926847.60      6964115.19      2926845.72      6963994.98
      2926848.15      6963976.62      2926865.17      6963930.58
      2926865.59      6963781.09      2926794.52      6963518.50
      2926794.52      6963226.83      2926773.69      6962935.17

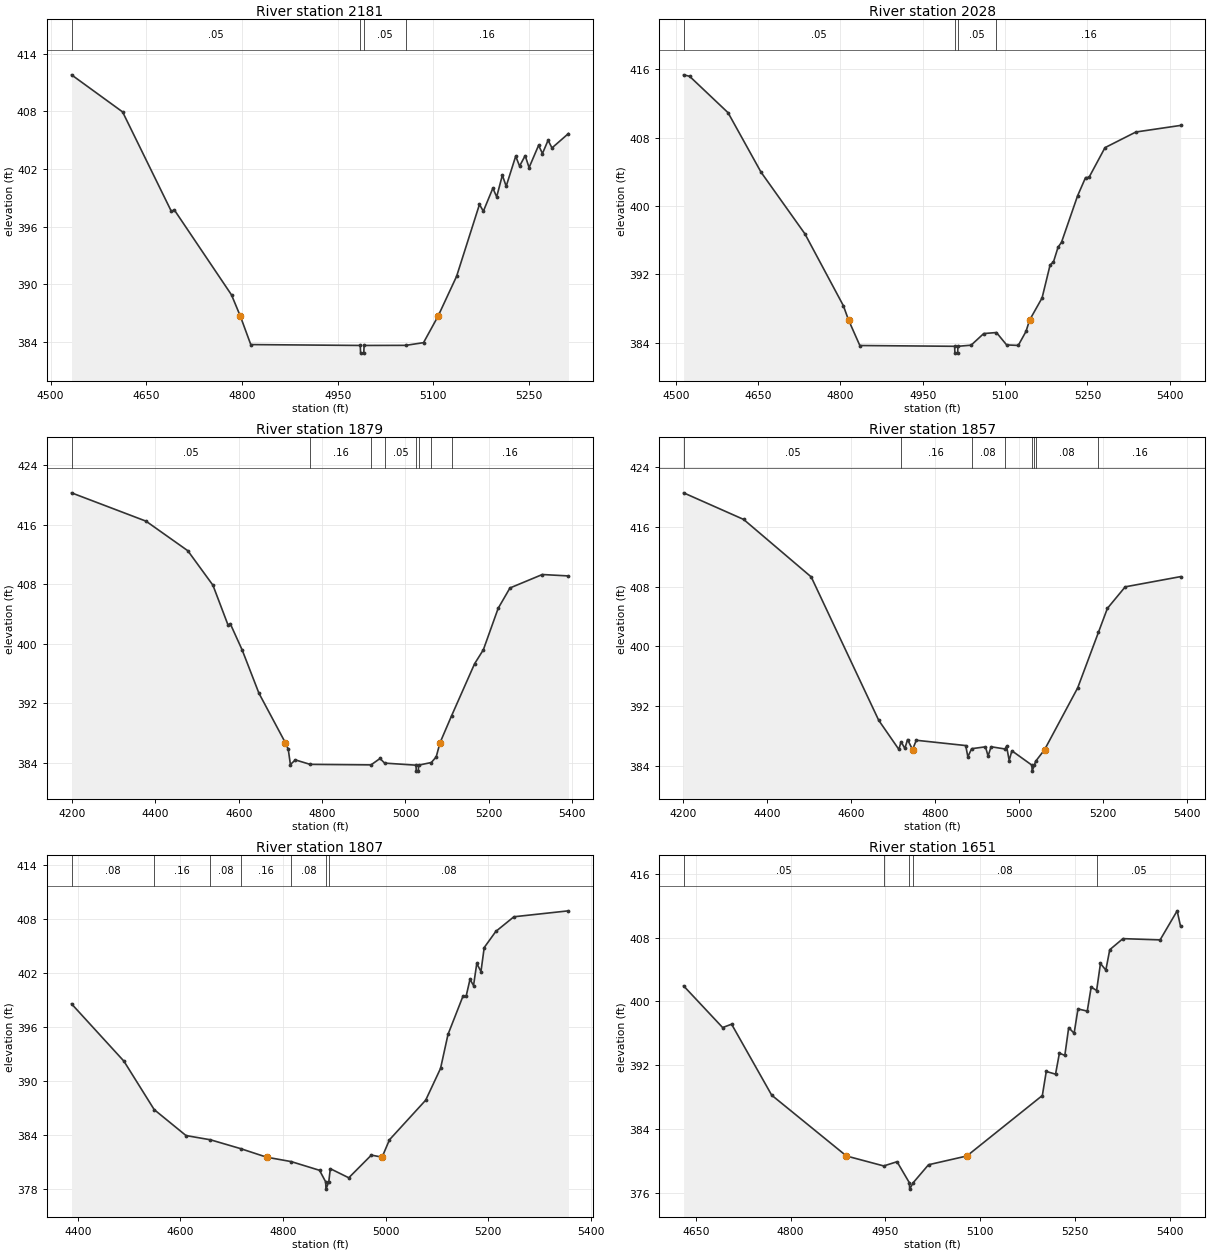
Type RM Length L Ch R = 1,2181,153,153,153
BEGIN DESCRIPTION:
UNT 071 IN DRY CR WATERSHED 4.0
END DESCRIPTION:
XS GIS Cut Line= 4
      2927684.69      6964855.52      2927395.63      6964826.87
      2927145.63      6964946.66      2926971.18      6965066.44
#Sta/Elev= 30
  4532.7  411.80  4612.8  407.94  4689.1  397.61  4694.1  397.72  4783.6  388.89
  4797.4  386.68  4813.8  383.72  4985.5  383.63  4986.0  382.83  4991.0  382.83
  4991.5  383.63  5056.9  383.64  5084.7  383.92  5107.5  386.68  5136.5  390.82
  5172.4  398.31  5178.5  397.60  5193.4  400.00  5199.4  399.10  5208.3  401.35
  5214.3  400.20  5229.2  403.33  5235.3  402.30  5244.1  403.39  5250.2  402.14
  5265.1  404.46  5271.2  403.61  5280.0  404.99  5286.1  404.19  5312.0  405.69
#Mann=4,-1,0
  4532.7    0.05       0  4985.5   0.033       0  4991.5    0.05       0
  5056.9    0.16       0
Bank Sta=4797.4,5107.5
Exp/Cntr=0.3,0.1

Type RM Length L Ch R = 1,2028,149,149,149
BEGIN DESCRIPTION:
Mapping XS 9a258317
END DESCRIPTION:
XS GIS Cut Line= 3
      2927715.94      6964751.35      2927249.80      6964738.33
      2926898.22      6965001.36
#Sta/Elev= 30
  4514.3  415.36  4525.2  415.19  4595.3  410.93  4655.3  403.98  4735.3  396.76
  4805.3  388.36  4814.9  386.66  4835.4  383.69  5008.1  383.60  5008.6  382.80
  5013.6  382.80  5014.1  383.60  5038.1  383.73  5061.1  385.09  5084.3  385.21
  5102.8  383.76  5124.0  383.70  5138.2  385.35  5144.6  386.66  5167.4  389.26
  5182.0  393.11  5188.2  393.48  5196.5  395.19  5202.8  395.77  5232.0  401.19
  5246.6  403.34  5252.8  403.35  5282.0  406.84  5338.3  408.67  5419.7  409.44
#Mann=4,-1,0
  4514.3    0.05       0  5008.1   0.033       0  5014.1    0.05       0
  5084.3    0.16       0
Bank Sta=4814.9,5144.6
Exp/Cntr=0.3,0.1

Type RM Length L Ch R = 1,1879,22,22,22
BEGIN DESCRIPTION:
Mapping XS d6937c48
END DESCRIPTION:
XS GIS Cut Line= 6
      2927893.02      6964683.64      2927369.59      6964636.77
      2927296.67      6964582.08      2927249.80      6964571.66
      2927171.67      6964602.91      2926853.98      6964912.80
#Sta/Elev= 30
  4198.5  420.28  4377.2  416.47  4477.6  412.49  4537.9  407.85  4574.3  402.47
  4579.4  402.68  4608.2  399.12  4648.3  393.32  4711.8  386.65  4718.6  385.80
  4723.8  383.73  4735.7  384.35  4771.1  383.75  4917.3  383.68  4938.9  384.54
  4949.9  383.92  5025.3  383.64  5025.8  382.84  5030.8  382.84  5031.3  383.64
  5062.0  384.00  5073.7  384.75  5082.8  386.65  5110.5  390.27  5165.8  397.28
  5186.9  399.17  5222.4  404.74  5250.7  407.48  5328.4  409.29  5391.2  409.10
#Mann=8,-1,0
  4198.5    0.05       0  4771.1    0.16       0  4917.3    0.08       0
  4949.9    0.05       0  5025.3   0.033       0  5031.3    0.05       0
  5062.0    0.08       0  5110.5    0.16       0
Bank Sta=4711.8,5082.8
Exp/Cntr=0.3,0.1

Type RM Length L Ch R = 1,1857,50,50,50
BEGIN DESCRIPTION:
Mapping XS a7eeec4b
END DESCRIPTION:
XS GIS Cut Line= 6
      2927877.37      6964660.20      2927364.38      6964610.73
      2927291.47      6964553.43      2927255.01      6964553.43
      2927114.38      6964628.95      2926844.60      6964890.96
#Sta/Elev= 30
  4201.6  420.58  4344.6  417.01  4505.4  409.30  4666.1  390.07  4714.1  386.16
  4719.3  387.19  4728.4  386.30  4734.8  387.49  4746.6  386.14  4755.6  387.39
  4873.2  386.68  4878.3  385.17  4887.3  386.26  4920.3  386.51  4926.4  385.27
  4933.7  386.52  4966.7  386.22  4970.5  386.59  4976.7  384.67  4983.1  385.98
  5030.8  384.05  5031.3  383.25  5036.8  384.05  5039.4  384.55  5061.1  386.14
  5139.8  394.42  5189.2  401.87  5210.5  405.08  5252.9  407.97  5384.7  409.34
#Mann=8,-1,0
  4201.6    0.05       0  4719.3    0.16       0  4887.3    0.08       0
  4966.7    0.05       0  5030.8   0.033       0  5036.8    0.05       0
  5039.4    0.08       0  5189.2    0.16       0
Bank Sta=4746.6,5061.1
Exp/Cntr=0.3,0.1

Type RM Length L Ch R = 1,1807,156,156,156
BEGIN DESCRIPTION:
Mapping XS 7061f74a
END DESCRIPTION:
XS GIS Cut Line= 3
      2927619.56      6964227.93      2927156.05      6964543.02
      2926833.17      6964792.99
#Sta/Elev= 30
  4387.7  398.54  4489.9  392.17  4548.9  386.79  4610.9  383.91  4658.5  383.44
  4717.2  382.46  4767.9  381.51  4815.8  381.02  4871.2  380.05  4883.2  378.76
  4883.7  377.96  4889.2  378.76  4892.2  380.23  4928.2  379.22  4972.2  381.74
  4993.1  381.51  5007.5  383.44  5078.1  387.84  5107.1  391.37  5121.6  395.14
  5150.6  399.36  5156.9  399.37  5164.5  401.26  5171.4  400.57  5177.7  403.02
  5185.9  402.13  5192.2  404.79  5214.8  406.58  5250.1  408.21  5356.5  408.87
#Mann=7,-1,0
  4387.7    0.08       0  4548.9    0.16       0  4658.5    0.08       0
  4717.2    0.16       0  4815.8    0.08       0  4883.2    0.07       0
  4889.2    0.08       0
Bank Sta=4767.9,4993.1
Exp/Cntr=0.3,0.1

Type RM Length L Ch R = 1,1651,124,124,124
BEGIN DESCRIPTION:
Mapping XS 7158db2d
END DESCRIPTION:
XS GIS Cut Line= 3
      2927416.47      6964199.26      2927166.47      6964420.62
      2926799.62      6964686.00
#Sta/Elev= 30
  4630.7  401.96  4692.5  396.73  4706.7  397.15  4770.2  388.24  4888.5  380.61
  4947.5  379.36  4968.6  379.89  4988.1  377.25  4988.6  376.45  4994.1  377.25
  5018.4  379.51  5079.1  380.61  5198.6  388.20  5204.8  391.22  5219.5  390.88
  5225.6  393.51  5234.2  393.24  5240.3  396.72  5248.9  396.01  5255.0  399.07
  5269.7  398.79  5275.9  401.81  5284.5  401.38  5290.6  404.77  5299.1  403.94
  5305.3  406.50  5326.2  407.89  5385.0  407.73  5412.0  411.38  5417.4  409.43
#Mann=5,-1,0
  4630.7    0.05       0  4947.5    0.08       0  4988.1    0.07       0
  4994.1    0.08       0  5284.5    0.05       0
Bank Sta=4888.5,5079.1
Exp/Cntr=0.3,0.1

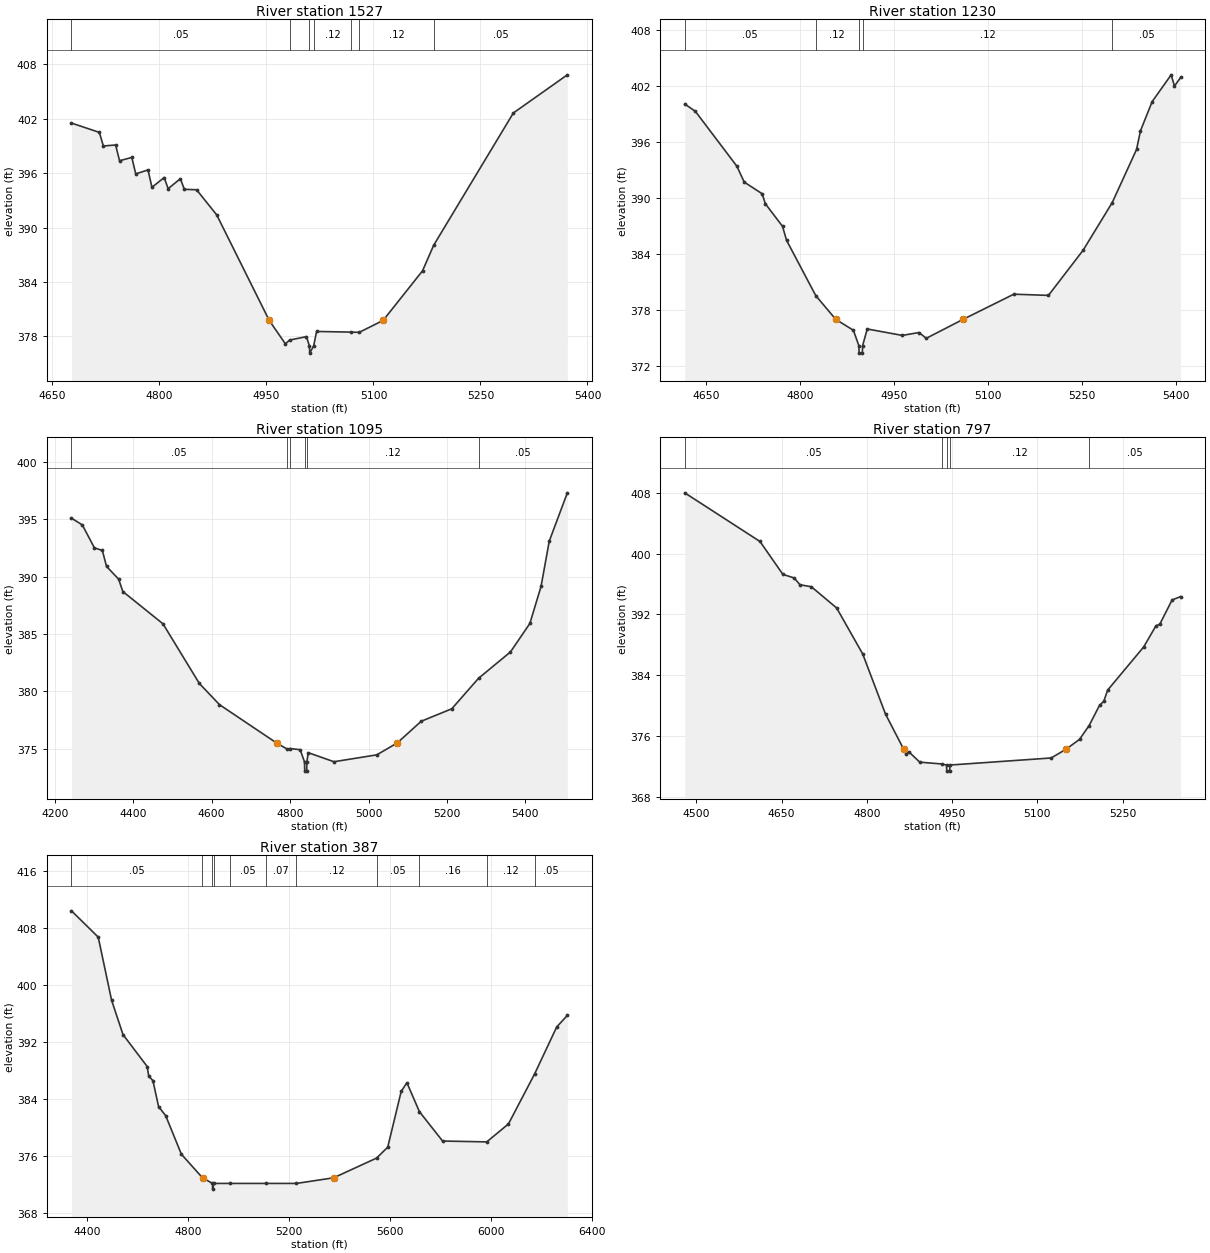
Type RM Length L Ch R = 1,1527,297,297,297
BEGIN DESCRIPTION:
Mapping XS d3e2df3e
END DESCRIPTION:
XS GIS Cut Line= 3
      2927343.52      6964212.30      2927070.11      6964342.50
      2926791.43      6964618.57
#Sta/Elev= 30
  4676.7  401.53  4715.8  400.50  4721.4  399.00  4738.6  399.11  4744.1  397.37
  4761.3  397.74  4766.8  395.92  4784.0  396.36  4789.5  394.44  4806.7  395.52
  4812.2  394.29  4829.4  395.39  4834.9  394.22  4852.1  394.17  4880.3  391.40
  4953.9  379.76  4976.6  377.17  4982.4  377.59  5006.1  377.97  5010.2  376.95
  5010.7  376.15  5016.2  376.95  5020.3  378.54  5068.7  378.47  5080.0  378.44
  5113.6  379.76  5168.8  385.23  5184.5  388.06  5296.1  402.64  5371.8  406.85
#Mann=7,-1,0
  4676.7    0.05       0  4982.4    0.12       0  5010.2    0.07       0
  5016.2    0.12       0  5068.7    0.08       0  5080.0    0.12       0
  5184.5    0.05       0
Bank Sta=4953.9,5113.6
Exp/Cntr=0.3,0.1

Type RM Length L Ch R = 1,1230,135,135,135
BEGIN DESCRIPTION:
UNT 071 IN DRY CR WATERSHED 2.0
END DESCRIPTION:
XS GIS Cut Line= 3
      2927225.01      6964225.00      2926875.00      6964125.00
      2926725.00      6964524.99
#Sta/Elev= 30
  4616.1  400.09  4633.0  399.31  4699.3  393.42  4711.0  391.72  4739.6  390.47
  4744.8  389.39  4772.1  386.98  4778.6  385.47  4825.2  379.54  4857.1  377.00
  4885.2  375.83  4893.9  374.18  4894.4  373.38  4899.4  373.38  4899.9  374.18
  4907.3  375.97  4963.2  375.28  4989.9  375.59  5001.5  374.97  5060.2  377.00
  5141.2  379.70  5196.4  379.57  5251.6  384.40  5298.1  389.51  5337.0  395.22
  5343.2  397.21  5361.9  400.35  5392.2  403.22  5397.5  402.01  5407.3  402.94
#Mann=5,-1,0
  4616.1    0.05       0  4825.2    0.12       0  4893.9    0.07       0
  4899.9    0.12       0  5298.1    0.05       0
Bank Sta=4857.1,5060.2
Exp/Cntr=0.3,0.1

Type RM Length L Ch R = 1,1095,298,298,298
BEGIN DESCRIPTION:
Mapping XS def41ee6
END DESCRIPTION:
XS GIS Cut Line= 3
      2927551.90      6963790.41      2926903.44      6963946.66
      2926519.03      6964403.80
#Sta/Elev= 30
  4242.6  395.11  4270.3  394.52  4301.1  392.52  4321.4  392.29  4332.0  390.90
  4362.8  389.79  4373.6  388.71  4476.0  385.89  4568.6  380.69  4620.0  378.84
  4765.4  375.50  4792.1  374.97  4799.9  375.01  4825.7  374.91  4836.8  373.84
  4837.3  373.04  4842.3  373.04  4842.8  373.84  4846.3  374.65  4911.8  373.86
  5021.1  374.46  5073.2  375.50  5134.3  377.39  5212.3  378.48  5280.5  381.14
  5361.9  383.44  5411.3  385.92  5439.9  389.16  5460.8  393.11  5506.9  397.32
#Mann=6,-1,0
  4242.6    0.05       0  4792.1     0.1       0  4799.9    0.12       0
  4836.8    0.07       0  4842.8    0.12       0  5280.5    0.05       0
Bank Sta=4765.4,5073.2
Exp/Cntr=0.3,0.1

Type RM Length L Ch R = 1,797,410,410,410
BEGIN DESCRIPTION:
Mapping XS 8a6a14a5
END DESCRIPTION:
XS GIS Cut Line= 3
      2927367.01      6963678.43      2926853.97      6963720.10
      2926611.76      6963983.14
#Sta/Elev= 30
  4479.7  407.98  4612.1  401.58  4652.3  397.26  4672.3  396.78  4682.4  395.89
  4702.4  395.63  4746.9  392.84  4792.7  386.80  4832.9  378.88  4864.7  374.28
  4868.8  373.64  4873.8  373.93  4893.1  372.56  4932.4  372.32  4940.2  372.18
  4940.7  371.38  4945.7  371.38  4946.2  372.18  5124.3  373.11  5150.9  374.28
  5174.2  375.56  5191.1  377.38  5209.4  380.04  5216.8  380.56  5223.6  382.03
  5287.1  387.72  5308.6  390.49  5315.4  390.71  5337.0  393.89  5352.0  394.34
#Mann=5,-1,0
  4479.7    0.05       0  4932.4    0.12       0  4940.2    0.07       0
  4946.2    0.12       0  5191.1    0.05       0
Bank Sta=4864.7,5150.9
Exp/Cntr=0.3,0.1

Type RM Length L Ch R = 1,387,0,0,0
BEGIN DESCRIPTION:
UNT 071 IN DRY CR WATERSHED 1.0
END DESCRIPTION:
XS GIS Cut Line= 3
      2927390.41      6963610.72      2926794.52      6963321.66
      2926283.65      6964519.58
#Sta/Elev= 30
  4337.7  410.44  4443.7  406.75  4496.7  397.89  4541.9  393.07  4637.7  388.59
  4643.8  387.24  4660.3  386.62  4682.9  382.96  4711.0  381.69  4773.2  376.28
  4856.7  372.98  4857.0  372.97  4896.4  372.18  4896.9  371.38  4902.4  372.18
  4965.5  372.18  5107.7  372.18  5229.0  372.18  5376.4  372.97  5546.7  375.74
  5590.7  377.27  5644.2  385.12  5666.8  386.31  5716.1  382.26  5808.1  378.13
  5983.0  378.01  6069.0  380.53  6172.9  387.57  6260.0  394.13  6302.3  395.77
#Mann=11,-1,0
  4337.7    0.05       0  4856.7    0.16       0  4896.4   0.033       0
  4902.4    0.16       0  4965.5    0.05       0  5107.7    0.07       0
  5229.0    0.12       0  5546.7    0.05       0  5716.1    0.16       0
  5983.0    0.12       0  6172.9    0.05       0
Bank Sta=4857,5376.4
Exp/Cntr=0.3,0.1

Chan Stop Cuts=-1