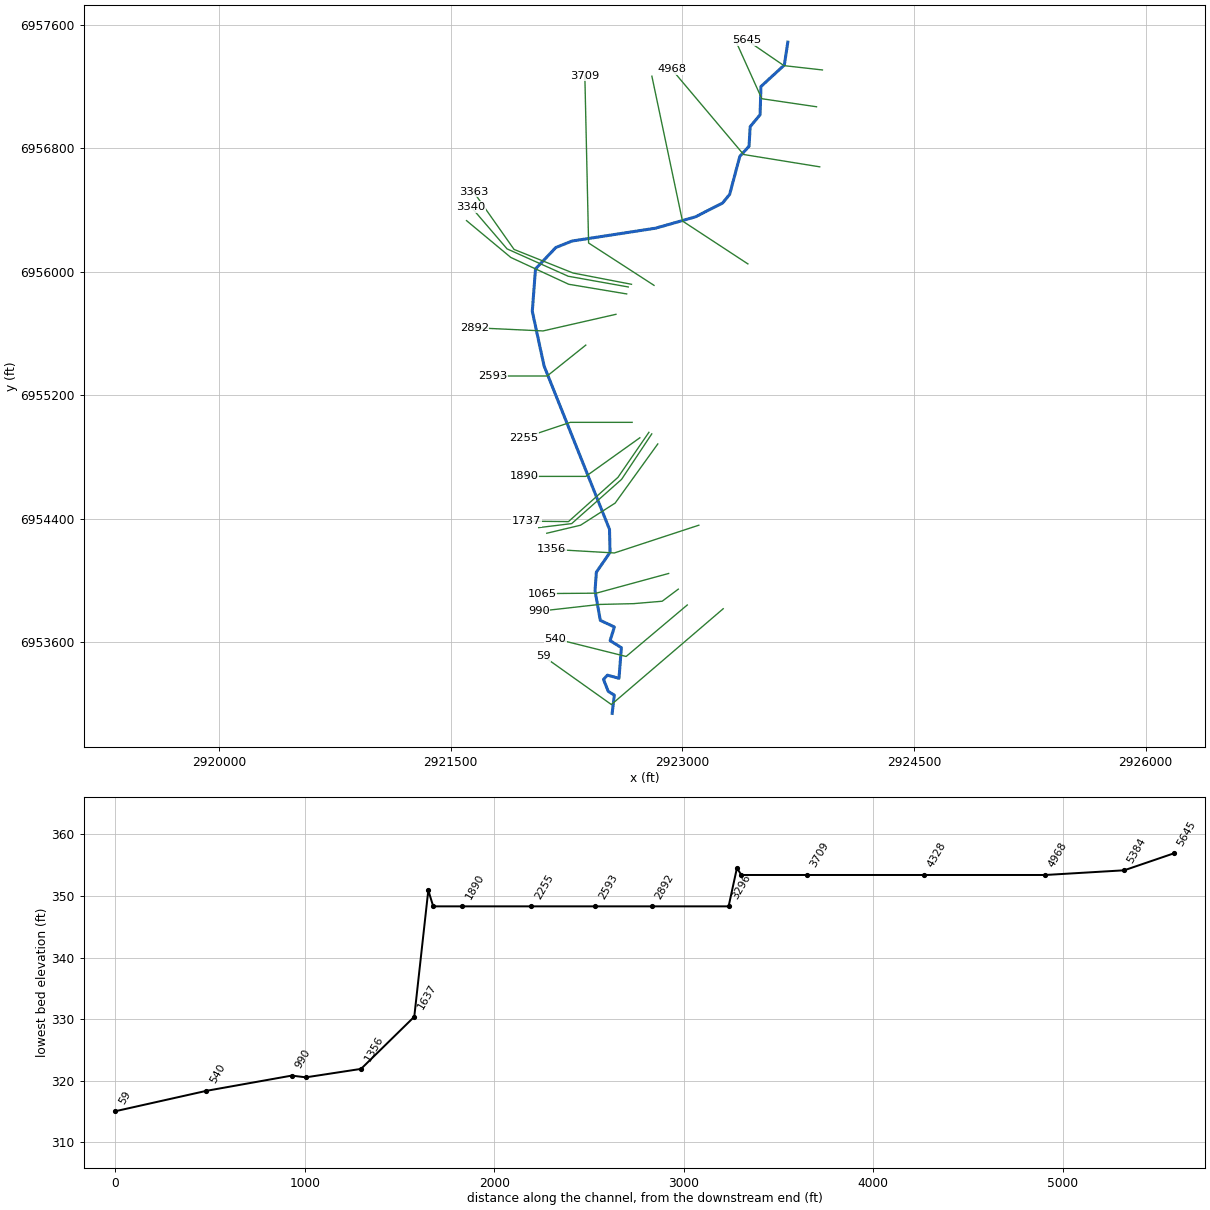
--- UNT 072 IN DRY CR WATERSHED.prj (project) ---

Proj Title=UNT 072 IN DRY CR WATERSHED Base Level Engineering
Current Plan=p01
Default Exp/Contr=0.3,0.1
English Units
Geom File=g01
Flow File=f01
Plan File=p01
BEGIN DESCRIPTION:
UNT 072 IN DRY CR WATERSHED
END DESCRIPTION:

--- UNT 072 IN DRY CR WATERSHED.p01 (plan) ---

Plan Title=Multiple Run
Short Identifier=Multiple
Geom File=g01
Flow File=f01
Subcritical Flow
K Sum by GR= 0
Std Step Tol= 0.01
Critical Tol= 0.01
Num of Std Step Trials= 20
Max Error Tol= 0.3
Flow Tol Ratio= 0.001
Split Flow NTrial= 30
Split Flow Tol= 0.02
Split Flow Ratio= 0.02
Log Output Level= 0
Friction Slope Method= 1
Unsteady Friction Slope Method= 2
Unsteady Bridges Friction Slope Method= 1
Parabolic Critical Depth
Global Vel Dist=  1 , 1 , 1
Global Log Level= 0
CheckData=True
Encroach Param= -1, 0, 0, 0
BEGIN DESCRIPTION:
Multiple Run
END DESCRIPTION:

--- UNT 072 IN DRY CR WATERSHED.f01 (steady flow) ---

Flow Title=Multiple
Number of Profiles=7
Profile Names=10-year,25-year,50-year,1pct_min,100-year,1pct_plu,500-year
River Rch & RM= UNT 072 IN DRY C,Reach-1,5645
     457     602     718     426     850    1696    1193
Boundary for River Rch & Prof#=UNT 072 IN DRY C,Reach-1,1
Up Type=0
Dn Type=3
Dn Slope=0.005
Boundary for River Rch & Prof#=UNT 072 IN DRY C,Reach-1,2
Up Type=0
Dn Type=3
Dn Slope=0.005
Boundary for River Rch & Prof#=UNT 072 IN DRY C,Reach-1,3
Up Type=0
Dn Type=3
Dn Slope=0.005
Boundary for River Rch & Prof#=UNT 072 IN DRY C,Reach-1,4
Up Type=0
Dn Type=3
Dn Slope=0.005
Boundary for River Rch & Prof#=UNT 072 IN DRY C,Reach-1,5
Up Type=0
Dn Type=3
Dn Slope=0.005
Boundary for River Rch & Prof#=UNT 072 IN DRY C,Reach-1,6
Up Type=0
Dn Type=3
Dn Slope=0.005
Boundary for River Rch & Prof#=UNT 072 IN DRY C,Reach-1,7
Up Type=0
Dn Type=3
Dn Slope=0.005

--- UNT 072 IN DRY CR WATERSHED.g01 (geometry) ---

Geom Title=Existing Conditions

River Reach=UNT 072 IN DRY C,Reach-1
Reach XY= 30
      2923683.06      6957486.61      2923660.43      6957338.20
      2923509.16      6957199.32      2923503.46      6957016.59
      2923439.23      6956939.20      2923432.03      6956812.18
      2923372.30      6956747.25      2923306.42      6956500.94
      2923261.28      6956445.38      2923084.20      6956355.11
      2922827.25      6956282.19      2922285.59      6956198.85
      2922181.42      6956157.19      2922049.48      6956018.30
      2922028.64      6955743.99      2922105.03      6955389.83
      2922528.64      6954332.54      2922532.12      6954183.23
      2922443.57      6954054.76      2922434.89      6953934.97
      2922469.01      6953742.99      2922560.02      6953700.18
      2922532.74      6953611.77      2922605.38      6953565.88
      2922590.02      6953367.72      2922515.09      6953388.07
      2922489.68      6953360.86      2922520.31      6953283.39
      2922559.92      6953258.71      2922545.59      6953140.71

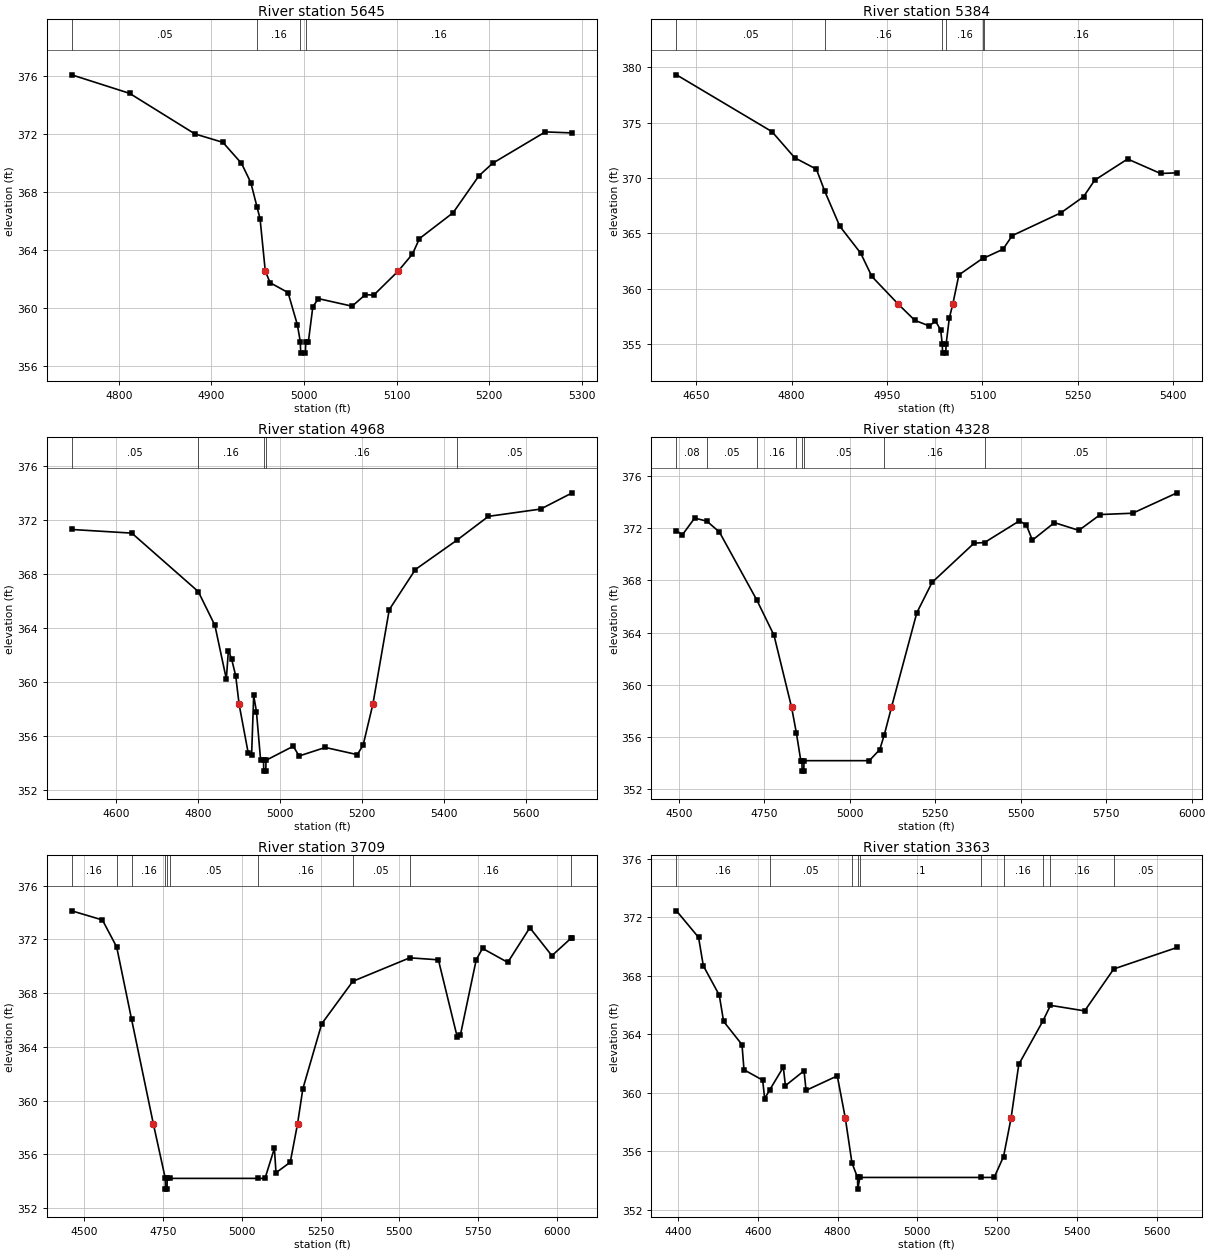
Type RM Length L Ch R = 1,5645,261,261,261
BEGIN DESCRIPTION:
UNT 072 IN DRY CR WATERSHED 8.0
END DESCRIPTION:
XS GIS Cut Line= 3
      2923907.24      6957306.48      2923657.91      6957334.57
      2923418.85      6957498.37
#Sta/Elev= 30
  4749.1  376.11  4811.7  374.83  4882.2  372.03  4912.4  371.45  4932.5  370.00
  4942.6  368.67  4949.4  366.96  4952.6  366.16  4958.2  362.57  4963.4  361.76
  4982.8  361.08  4992.9  358.85  4996.0  357.70  4996.5  356.90  5001.5  356.90
  5002.0  357.70  5004.8  357.70  5009.6  360.11  5015.7  360.66  5052.0  360.14
  5066.4  360.94  5075.3  360.90  5101.9  362.57  5117.2  363.74  5124.8  364.81
  5161.1  366.59  5189.0  369.14  5203.9  370.01  5260.7  372.17  5289.8  372.10
#Mann=4,-1,0
  4749.1    0.05       0  4949.4    0.16       0  4996.0    0.07       0
  5002.0    0.16       0
Bank Sta=4958.2,5101.9
Exp/Cntr=0.3,0.1

Type RM Length L Ch R = 1,5384,416,416,416
BEGIN DESCRIPTION:
Mapping XS 3b1a8988
END DESCRIPTION:
XS GIS Cut Line= 3
      2923868.96      6957068.19      2923514.75      6957120.28
      2923338.28      6957511.27
#Sta/Elev= 30
  4618.9  379.32  4769.1  374.18  4804.8  371.82  4838.9  370.79  4852.0  368.80
  4875.6  365.64  4908.6  363.19  4926.1  361.09  4967.7  358.58  4993.5  357.13
  5016.6  356.61  5026.0  357.08  5034.3  356.24  5036.8  354.96  5037.3  354.16
  5042.3  354.16  5042.8  354.96  5047.9  357.34  5053.3  358.58  5062.9  361.23
  5100.4  362.73  5102.4  362.76  5132.3  363.55  5146.7  364.78  5223.5  366.85
  5258.9  368.30  5276.5  369.80  5328.2  371.71  5380.0  370.40  5405.9  370.46
#Mann=6,-1,0
  4618.9    0.05       0  4852.0    0.16       0  5036.8    0.07       0
  5042.8    0.16       0  5100.4    0.12       0  5102.4    0.16       0
Bank Sta=4967.7,5053.3
Exp/Cntr=0.3,0.1

Type RM Length L Ch R = 1,4968,640,640,640
BEGIN DESCRIPTION:
Mapping XS 8942ab6c
END DESCRIPTION:
XS GIS Cut Line= 3
      2923889.72      6956679.31      2923396.69      6956759.17
      2922931.96      6957310.60
#Sta/Elev= 30
  4491.9  371.27  4638.5  371.00  4800.5  366.68  4841.1  364.18  4869.0  360.21
  4874.0  362.31  4881.6  361.72  4891.8  360.46  4900.2  358.33  4922.2  354.76
  4930.6  354.58  4935.7  359.00  4942.4  357.80  4952.5  354.24  4959.7  354.20
  4960.2  353.40  4965.2  353.40  4965.7  354.20  5032.2  355.24  5046.5  354.52
  5110.3  355.15  5188.3  354.62  5202.6  355.33  5226.2  358.33  5266.3  365.34
  5330.0  368.31  5431.8  370.49  5508.1  372.24  5635.6  372.78  5712.5  373.98
#Mann=5,-1,0
  4491.9    0.05       0  4800.5    0.16       0  4959.7    0.07       0
  4965.7    0.16       0  5431.8    0.05       0
Bank Sta=4900.2,5226.2
Exp/Cntr=0.3,0.1

Type RM Length L Ch R = 1,4328,619,619,619
BEGIN DESCRIPTION:
Mapping XS f18a2f13
END DESCRIPTION:
XS GIS Cut Line= 3
      2923424.48      6956050.82      2923000.86      6956328.61
      2922802.95      6957266.06
#Sta/Elev= 30
  4492.6  371.79  4509.6  371.46  4545.8  372.75  4581.7  372.51  4618.2  371.68
  4727.3  366.50  4777.9  363.79  4829.4  358.28  4843.3  356.34  4856.3  354.21
  4859.7  354.20  4860.2  353.40  4865.2  353.40  4865.7  354.20  5056.8  354.20
  5087.5  355.05  5100.9  356.20  5121.7  358.28  5195.9  365.51  5240.5  367.83
  5363.4  370.83  5394.1  370.88  5496.3  372.54  5516.7  372.20  5534.0  371.06
  5598.5  372.40  5670.0  371.81  5733.0  373.02  5827.4  373.12  5957.3  374.68
#Mann=8,-1,0
  4492.6    0.08       0  4581.7    0.05       0  4727.3    0.16       0
  4843.3    0.05       0  4859.7   0.033       0  4865.7    0.05       0
  5100.9    0.16       0  5394.1    0.05       0
Bank Sta=4829.4,5121.7
Exp/Cntr=0.3,0.1

Type RM Length L Ch R = 1,3709,346,346,346
BEGIN DESCRIPTION:
Mapping XS 188ea8a7
END DESCRIPTION:
XS GIS Cut Line= 3
      2922816.79      6955911.97      2922393.22      6956186.25
      2922368.91      6957269.55
#Sta/Elev= 30
  4460.4  374.13  4557.8  373.45  4603.1  371.44  4650.5  366.04  4719.5  358.26
  4757.4  354.20  4757.9  353.40  4762.9  353.40  4763.4  354.20  4771.7  354.20
  5051.9  354.20  5073.8  354.20  5103.6  356.44  5108.6  354.62  5153.8  355.40
  5177.0  358.26  5193.8  360.87  5253.8  365.72  5352.4  368.88  5533.1  370.63
  5623.9  370.48  5684.0  364.70  5694.0  364.91  5744.0  370.49  5764.0  371.33
  5844.0  370.29  5914.0  372.87  5984.0  370.79  6045.8  372.11  6048.6  372.11
#Mann=10,-1,0
  4460.4    0.16       0  4603.1    0.05       0  4650.5    0.16       0
  4757.4   0.033       0  4763.4    0.16       0  4771.7    0.05       0
  5051.9    0.16       0  5352.4    0.05       0  5533.1    0.16       0
  6045.8    0.05       0
Bank Sta=4719.5,5177
Exp/Cntr=0.3,0.1

Type RM Length L Ch R = 1,3363,23,23,23
BEGIN DESCRIPTION:
Mapping XS b8341013
END DESCRIPTION:
XS GIS Cut Line= 4
      2922671.04      6955918.88      2922292.52      6955991.81
      2921910.58      6956144.58      2921646.69      6956519.59
#Sta/Elev= 30
  4396.1  372.45  4451.5  370.63  4463.4  368.69  4503.4  366.68  4514.3  364.88
  4560.4  363.29  4565.4  361.57  4612.2  360.86  4617.3  359.60  4630.3  360.21
  4664.1  361.75  4669.2  360.48  4716.0  361.50  4721.1  360.16  4799.4  361.15
  4819.6  358.25  4836.2  355.19  4850.2  354.20  4850.7  353.40  4856.2  354.20
  5159.1  354.20  5192.9  354.20  5216.4  355.63  5235.2  358.25  5254.6  361.94
  5314.9  364.90  5334.1  365.98  5419.8  365.60  5492.8  368.47  5651.5  369.94
#Mann=10,-1,0
  4396.1    0.16       0  4630.3    0.05       0  4836.2     0.1       0
  4850.2    0.07       0  4856.2     0.1       0  5159.1    0.08       0
  5216.4    0.16       0  5314.9    0.05       0  5334.1    0.16       0
  5492.8    0.05       0
Bank Sta=4819.6,5235.2
Exp/Cntr=0.3,0.1

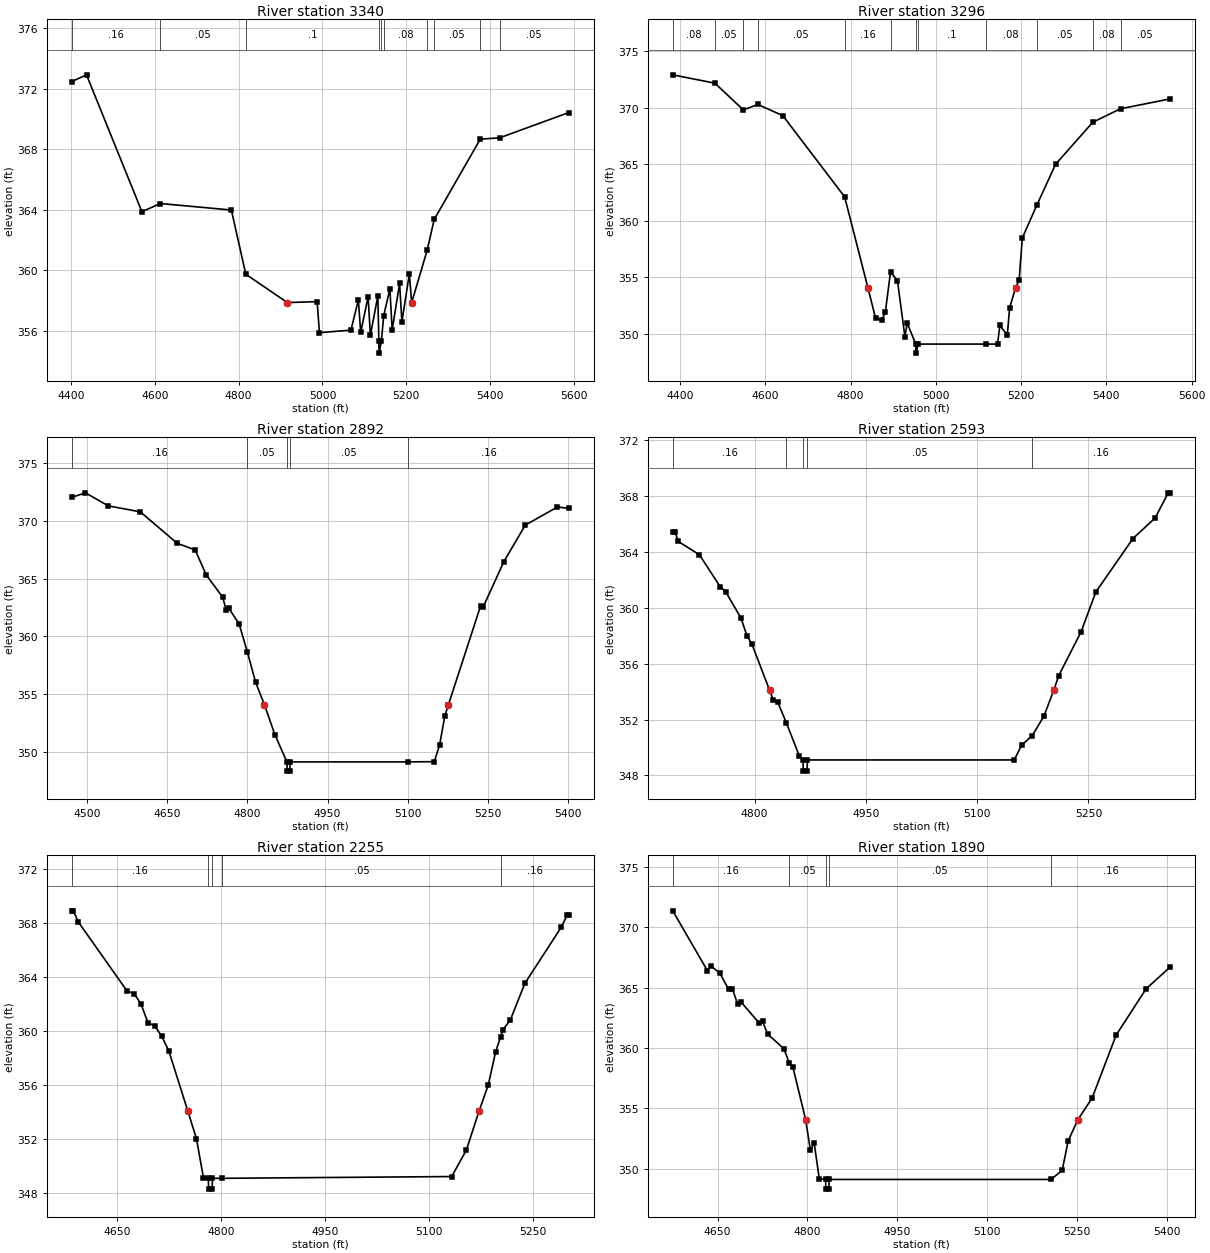
Type RM Length L Ch R = 1,3340,44,44,44
BEGIN DESCRIPTION:
Mapping XS 4a1b83d4
END DESCRIPTION:
XS GIS Cut Line= 4
      2922650.19      6955901.52      2922261.27      6955970.97
      2921865.44      6956148.06      2921632.82      6956418.86
#Sta/Elev= 30
  4401.7  372.47  4437.4  372.92  4569.5  363.88  4613.6  364.42  4782.8  363.99
  4817.2  359.75  4916.3  357.88  4987.3  357.94  4992.8  355.89  5067.9  356.06
  5085.6  358.05  5091.1  355.91  5108.8  358.25  5114.3  355.72  5132.0  358.32
  5134.5  355.34  5135.0  354.54  5140.5  355.34  5146.0  357.01  5160.7  358.79
  5166.2  356.06  5183.9  359.14  5189.4  356.61  5207.1  359.76  5212.7  357.88
  5249.7  361.34  5266.4  363.37  5376.2  368.67  5422.5  368.76  5587.4  370.43
#Mann=10,-1,0
  4401.7    0.16       0  4613.6    0.05       0  4817.2     0.1       0
  5134.5    0.07       0  5140.5     0.1       0  5146.0    0.08       0
  5249.7    0.16       0  5266.4    0.05       0  5376.2    0.16       0
  5422.5    0.05       0
Bank Sta=4916.3,5212.7
Exp/Cntr=0.3,0.1

Type RM Length L Ch R = 1,3296,404,404,404
BEGIN DESCRIPTION:
Mapping XS f585c8d1
END DESCRIPTION:
XS GIS Cut Line= 4
      2922639.71      6955856.40      2922264.75      6955918.89
      2921889.75      6956092.50      2921602.82      6956331.03
#Sta/Elev= 30
  4382.8  372.92  4481.7  372.18  4548.4  369.82  4582.5  370.30  4641.0  369.31
  4786.0  362.13  4840.6  354.09  4858.6  351.39  4872.8  351.21  4881.5  351.94
  4893.6  355.49  4909.9  354.72  4927.3  349.78  4932.8  350.96  4952.7  349.11
  4953.2  348.31  4958.7  349.11  5116.9  349.11  5144.6  349.11  5150.1  350.76
  5167.5  349.91  5173.1  352.33  5186.9  354.09  5195.3  354.74  5202.7  358.49
  5236.9  361.40  5280.8  365.01  5368.2  368.73  5433.2  369.92  5549.3  370.79
#Mann=12,-1,0
  4382.8    0.08       0  4481.7    0.05       0  4548.4    0.16       0
  4582.5    0.05       0  4786.0    0.16       0  4893.6     0.1       0
  4952.7    0.07       0  4958.7     0.1       0  5116.9    0.08       0
  5236.9    0.05       0  5368.2    0.08       0  5433.2    0.05       0
Bank Sta=4840.6,5186.9
Exp/Cntr=0.3,0.1

Type RM Length L Ch R = 1,2892,299,299,299
BEGIN DESCRIPTION:
Mapping XS 417229f4
END DESCRIPTION:
XS GIS Cut Line= 3
      2922570.34      6955724.45      2922098.08      6955616.81
      2921653.65      6955637.64
#Sta/Elev= 30
  4471.5  372.03  4497.5  372.43  4540.1  371.30  4600.1  370.78  4669.1  368.05
  4702.6  367.48  4723.1  365.32  4753.9  363.39  4760.3  362.31  4765.4  362.43
  4784.7  361.06  4799.9  358.66  4815.4  356.02  4831.9  354.08  4851.4  351.48
  4874.0  349.11  4874.5  348.31  4879.5  348.31  4880.0  349.11  5100.3  349.11
  5149.2  349.13  5159.2  350.55  5169.2  353.12  5175.9  354.08  5236.0  362.64
  5241.0  362.56  5279.3  366.46  5319.4  369.63  5379.4  371.20  5400.8  371.09
#Mann=5,-1,0
  4471.5    0.16       0  4799.9    0.05       0  4874.0   0.033       0
  4880.0    0.05       0  5100.3    0.16       0
Bank Sta=4831.9,5175.9
Exp/Cntr=0.3,0.1

Type RM Length L Ch R = 1,2593,338,338,338
BEGIN DESCRIPTION:
UNT 072 IN DRY CR WATERSHED 7.0
END DESCRIPTION:
XS GIS Cut Line= 3
      2922375.01      6955525.01      2922125.00      6955325.00
      2921774.97      6955325.00
#Sta/Elev= 30
  4689.8  365.43  4693.0  365.43  4697.0  364.74  4725.8  363.78  4753.8  361.49
  4761.1  361.14  4781.9  359.24  4789.9  357.97  4796.3  357.42  4820.4  354.08
  4825.1  353.43  4831.5  353.22  4843.1  351.74  4860.3  349.41  4865.3  349.11
  4865.8  348.31  4870.8  348.31  4871.3  349.11  5150.0  349.11  5160.0  350.17
  5174.3  350.85  5190.0  352.24  5203.2  354.08  5210.0  355.14  5240.0  358.26
  5260.0  361.12  5310.0  364.94  5340.0  366.42  5357.5  368.21  5360.0  368.21
#Mann=5,-1,0
  4689.8    0.16       0  4843.1    0.05       0  4865.3   0.033       0
  4871.3    0.05       0  5174.3    0.16       0
Bank Sta=4820.4,5203.2
Exp/Cntr=0.3,0.1

Type RM Length L Ch R = 1,2255,365,365,365
BEGIN DESCRIPTION:
UNT 072 IN DRY CR WATERSHED 6.0
END DESCRIPTION:
XS GIS Cut Line= 3
      2922675.02      6955025.00      2922275.00      6955025.00
      2921974.95      6954924.98
#Sta/Elev= 30
  4584.9  368.89  4587.4  368.89  4594.9  368.05  4664.9  362.96  4674.9  362.77
  4684.9  362.01  4694.9  360.63  4704.9  360.37  4714.9  359.60  4724.9  358.55
  4752.5  354.07  4764.9  352.02  4774.9  349.16  4781.9  349.11  4782.4  348.31
  4787.4  348.31  4787.9  349.11  4801.8  349.11  5132.5  349.24  5153.6  351.20
  5171.8  354.07  5185.2  356.02  5195.7  358.45  5202.9  359.57  5206.3  360.10
  5216.8  360.80  5237.9  363.53  5290.6  367.70  5298.5  368.55  5301.2  368.55
#Mann=5,-1,0
  4584.9    0.16       0  4781.9   0.033       0  4787.9    0.16       0
  4801.8    0.05       0  5202.9    0.16       0
Bank Sta=4752.5,5171.8
Exp/Cntr=0.3,0.1

Type RM Length L Ch R = 1,1890,153,153,153
BEGIN DESCRIPTION:
UNT 072 IN DRY CR WATERSHED 5.0
END DESCRIPTION:
XS GIS Cut Line= 3
      2922725.02      6954925.01      2922375.00      6954675.00
      2921975.04      6954675.00
#Sta/Elev= 30
  4575.2  371.35  4633.0  366.40  4639.1  366.78  4653.9  366.18  4668.6  364.84
  4674.8  364.89  4683.4  363.64  4689.5  363.78  4719.0  362.09  4725.1  362.19
  4733.7  361.14  4760.8  359.93  4769.8  358.73  4775.5  358.46  4797.0  354.07
  4805.0  351.51  4811.2  352.16  4819.8  349.16  4830.3  349.11  4830.8  348.31
  4835.8  348.31  4836.3  349.11  5206.6  349.11  5225.3  349.87  5235.3  352.32
  5251.6  354.07  5275.3  355.86  5315.3  361.06  5365.3  364.89  5405.3  366.69
#Mann=5,-1,0
  4575.2    0.16       0  4769.8    0.05       0  4830.3   0.033       0
  4836.3    0.05       0  5206.6    0.16       0
Bank Sta=4797,5251.6
Exp/Cntr=0.3,0.1

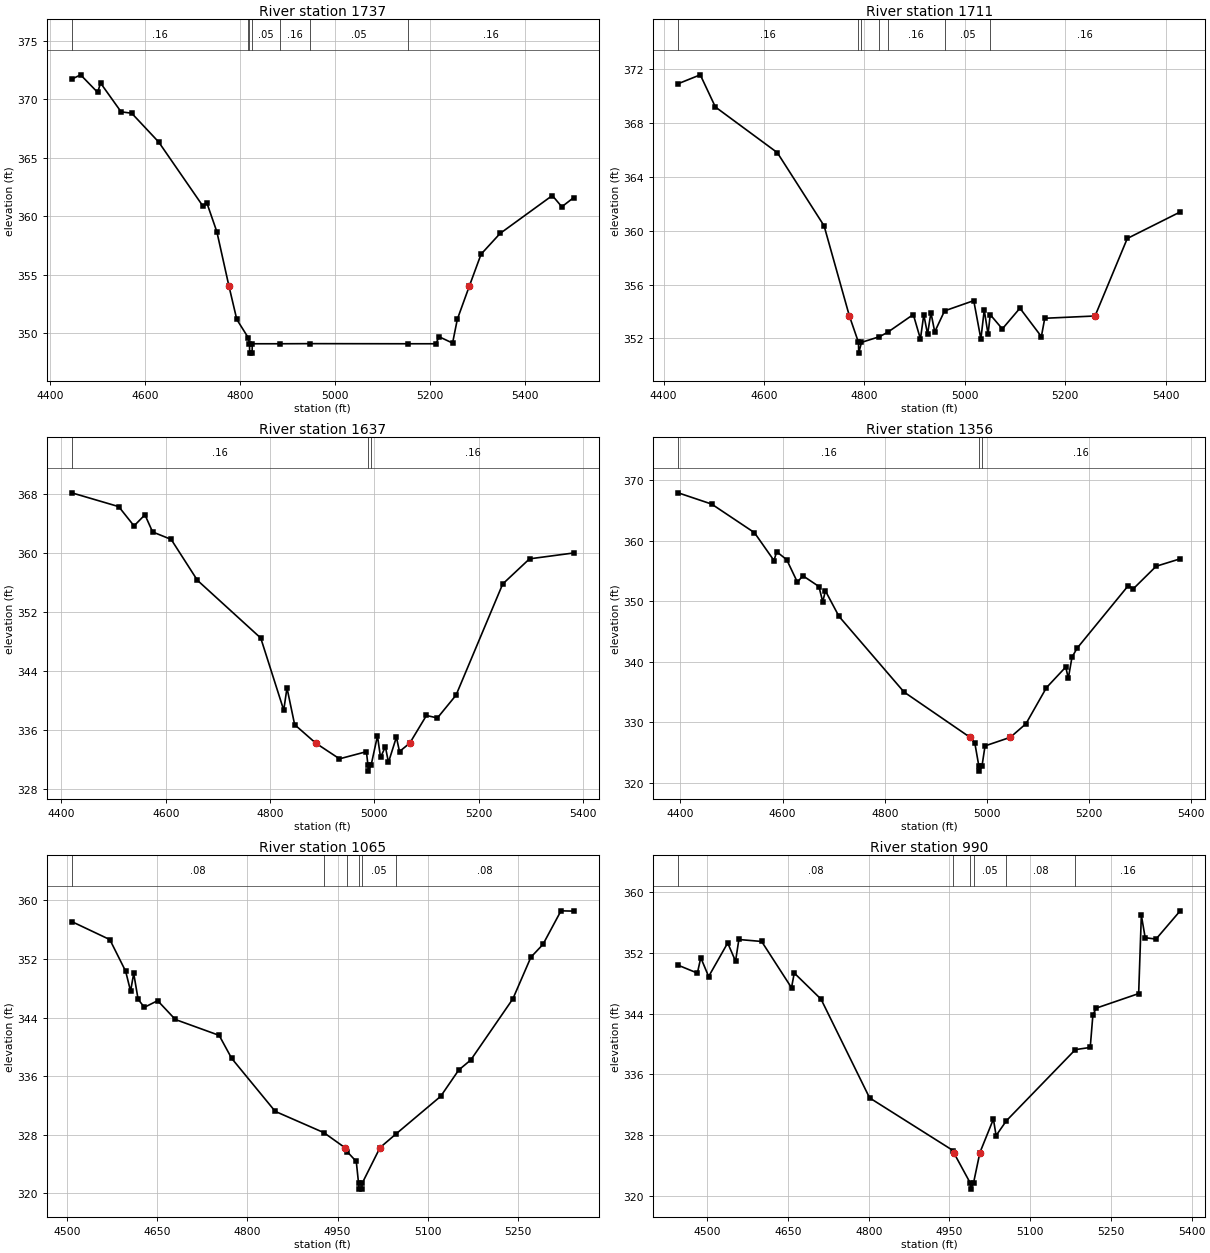
Type RM Length L Ch R = 1,1737,26,26,26
BEGIN DESCRIPTION:
Mapping XS 045584d6
END DESCRIPTION:
XS GIS Cut Line= 4
      2922783.86      6954960.58      2922583.32      6954668.89
      2922263.01      6954382.43      2921989.81      6954385.03
#Sta/Elev= 30
  4446.2  371.71  4464.8  372.08  4500.7  370.58  4506.8  371.38  4550.0  368.92
  4572.4  368.80  4629.2  366.34  4721.9  360.89  4730.7  361.13  4751.7  358.67
  4776.9  354.07  4793.6  351.19  4817.7  349.63  4820.3  349.11  4820.8  348.31
  4825.8  348.31  4826.3  349.11  4884.9  349.11  4947.9  349.12  5154.8  349.11
  5212.8  349.11  5219.5  349.71  5247.9  349.17  5257.9  351.20  5283.5  354.07
  5307.9  356.76  5347.9  358.53  5457.9  361.77  5477.9  360.81  5503.1  361.60
#Mann=7,-1,0
  4446.2    0.16       0  4817.7    0.05       0  4820.3   0.033       0
  4826.3    0.05       0  4884.9    0.16       0  4947.9    0.05       0
  5154.8    0.16       0
Bank Sta=4776.9,5283.5
Exp/Cntr=0.3,0.1

Type RM Length L Ch R = 1,1711,74,74,74
BEGIN DESCRIPTION:
Mapping XS 09da22c2
END DESCRIPTION:
XS GIS Cut Line= 4
      2922802.05      6954950.10      2922606.76      6954655.87
      2922283.84      6954369.41      2922070.34      6954343.37
#Sta/Elev= 30
  4429.0  370.93  4473.0  371.59  4503.1  369.20  4626.4  365.81  4719.6  360.37
  4770.0  353.67  4788.1  351.71  4788.6  350.91  4794.1  351.71  4829.9  352.13
  4846.3  352.46  4897.3  353.78  4911.5  351.96  4918.2  353.77  4925.7  352.32
  4932.4  353.92  4940.0  352.49  4959.6  354.05  5017.7  354.81  5031.9  351.96
  5038.6  354.12  5046.2  352.30  5050.5  353.77  5074.6  352.71  5109.7  354.25
  5152.4  352.14  5159.1  353.50  5259.3  353.67  5323.5  359.43  5428.9  361.40
#Mann=7,-1,0
  4429.0    0.16       0  4788.1   0.033       0  4794.1    0.16       0
  4829.9    0.05       0  4846.3    0.16       0  4959.6    0.05       0
  5050.5    0.16       0
Bank Sta=4770,5259.3
Exp/Cntr=0.3,0.1

Type RM Length L Ch R = 1,1637,281,281,281
BEGIN DESCRIPTION:
Mapping XS 1c7e1183
END DESCRIPTION:
XS GIS Cut Line= 4
      2922841.15      6954885.06      2922565.09      6954502.22
      2922341.13      6954358.99      2922122.38      6954306.91
#Sta/Elev= 30
  4419.8  368.17  4509.8  366.30  4539.2  363.68  4560.1  365.19  4574.8  362.86
  4610.4  361.85  4660.7  356.30  4782.2  348.46  4826.3  338.67  4832.5  341.70
  4847.2  336.71  4887.5  334.21  4933.2  332.07  4984.8  333.04  4987.8  331.20
  4988.3  330.40  4993.8  331.20  5006.0  335.18  5011.9  332.26  5021.2  333.71
  5027.1  331.59  5042.3  335.01  5048.3  333.06  5068.1  334.21  5099.9  337.95
  5121.0  337.62  5156.7  340.71  5246.2  355.80  5297.6  359.21  5382.5  360.01
#Mann=3,-1,0
  4419.8    0.16       0  4987.8    0.07       0  4993.8    0.16       0
Bank Sta=4887.5,5068.1
Exp/Cntr=0.3,0.1

Type RM Length L Ch R = 1,1356,291,291,291
BEGIN DESCRIPTION:
Mapping XS 0ec2363c
END DESCRIPTION:
XS GIS Cut Line= 3
      2923106.75      6954358.99      2922559.88      6954179.31
      2922153.59      6954202.75
#Sta/Elev= 30
  4395.6  367.95  4461.1  366.09  4544.8  361.37  4583.1  356.76  4588.4  358.21
  4608.0  356.90  4629.0  353.17  4639.5  354.25  4671.1  352.46  4678.5  349.94
  4683.8  351.74  4710.3  347.53  4837.6  335.02  4966.8  327.53  4976.2  326.58
  4984.2  322.74  4984.7  321.94  4990.2  322.74  4996.2  326.11  5045.7  327.53
  5076.3  329.77  5116.4  335.74  5154.2  339.15  5159.2  337.28  5166.4  340.78
  5176.5  342.27  5276.6  352.61  5286.6  352.10  5331.1  355.81  5378.2  357.04
#Mann=3,-1,0
  4395.6    0.16       0  4984.2    0.07       0  4990.2    0.16       0
Bank Sta=4966.8,5045.7
Exp/Cntr=0.3,0.1

Type RM Length L Ch R = 1,1065,75,75,75
BEGIN DESCRIPTION:
Mapping XS 82d7a925
END DESCRIPTION:
XS GIS Cut Line= 3
      2922911.46      6954046.50      2922442.70      6953918.89
      2922093.73      6953916.28
#Sta/Elev= 30
  4508.1  357.11  4571.4  354.65  4597.7  350.33  4605.9  347.61  4611.1  350.04
  4618.4  346.50  4628.8  345.40  4650.9  346.31  4680.3  343.74  4753.2  341.57
  4773.9  338.44  4846.4  331.19  4927.4  328.28  4962.2  326.24  4966.3  325.66
  4981.2  324.35  4985.0  321.37  4985.5  320.57  4990.5  320.57  4991.0  321.37
  5020.7  326.24  5047.3  328.11  5121.6  333.25  5151.6  336.84  5171.6  338.21
  5241.6  346.56  5271.6  352.25  5291.6  353.99  5321.6  358.58  5342.9  358.54
#Mann=6,-1,0
  4508.1    0.08       0  4927.4    0.16       0  4966.3    0.05       0
  4985.0    0.04       0  4991.0    0.05       0  5047.3    0.08       0
Bank Sta=4962.2,5020.7
Exp/Cntr=0.3,0.1

Type RM Length L Ch R = 1,990,450,450,450
BEGIN DESCRIPTION:
Mapping XS 75548645
END DESCRIPTION:
XS GIS Cut Line= 5
      2922973.94      6953944.93      2922869.78      6953866.81
      2922684.88      6953851.18      2922463.53      6953845.97
      2922070.29      6953801.70
#Sta/Elev= 30
  4445.9  350.37  4481.6  349.33  4487.9  351.36  4502.5  348.88  4537.9  353.30
  4552.5  350.91  4558.7  353.76  4601.0  353.50  4656.5  347.40  4661.6  349.34
  4711.4  345.89  4801.6  332.88  4956.6  325.94  4957.9  325.67  4988.7  321.65
  4989.2  320.85  4994.7  321.65  5006.6  325.67  5031.7  330.08  5036.7  327.91
  5055.9  329.87  5183.9  339.24  5211.6  339.53  5216.6  343.86  5223.1  344.72
  5301.6  346.63  5306.6  356.96  5313.7  354.00  5333.8  353.81  5378.8  357.54
#Mann=6,-1,0
  4445.9    0.08       0  4956.6    0.05       0  4988.7    0.04       0
  4994.7    0.05       0  5055.9    0.08       0  5183.9    0.16       0
Bank Sta=4957.9,5006.6
Exp/Cntr=0.3,0.1

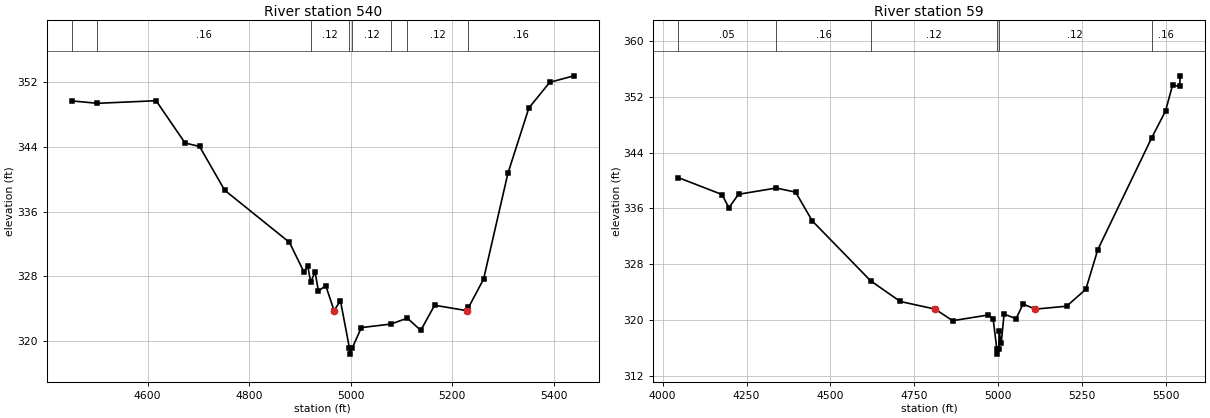
Type RM Length L Ch R = 1,540,481,481,481
BEGIN DESCRIPTION:
Mapping XS 95088618
END DESCRIPTION:
XS GIS Cut Line= 3
      2923032.08      6953842.48      2922636.27      6953509.17
      2922179.00      6953623.49
#Sta/Elev= 30
  4450.5  349.71  4501.0  349.41  4616.6  349.73  4673.6  344.50  4702.2  344.07
  4751.6  338.66  4879.1  332.21  4907.7  328.55  4915.4  329.26  4921.0  327.29
  4929.7  328.55  4936.3  326.17  4950.6  326.87  4967.1  323.76  4979.6  324.99
  4997.2  319.18  4997.7  318.38  5003.2  319.18  5020.8  321.66  5078.9  322.10
  5111.5  322.83  5137.8  321.32  5165.1  324.43  5228.1  323.76  5231.8  324.15
  5261.5  327.65  5309.4  340.74  5350.7  348.83  5391.9  352.01  5439.3  352.81
#Mann=8,-1,0
  4450.5    0.05       0  4501.0    0.16       0  4921.0    0.12       0
  4997.2    0.07       0  5003.2    0.12       0  5078.9    0.16       0
  5111.5    0.12       0  5231.8    0.16       0
Bank Sta=4967.1,5228.1
Exp/Cntr=0.3,0.1

Type RM Length L Ch R = 1,59,0,0,0
BEGIN DESCRIPTION:
UNT 072 IN DRY CR WATERSHED 1.0
END DESCRIPTION:
XS GIS Cut Line= 3
      2923264.71      6953818.17      2922540.74      6953197.81
      2922099.06      6953511.94
#Sta/Elev= 30
  4046.6  340.42  4176.7  337.99  4197.6  336.09  4226.1  338.02  4338.4  338.92
  4396.2  338.33  4445.6  334.21  4619.8  325.59  4707.9  322.63  4811.9  321.53
  4863.8  319.87  4970.3  320.69  4984.5  320.14  4995.3  315.87  4995.8  315.07
  5001.3  315.87  5002.3  318.37  5008.5  316.63  5017.1  320.82  5052.8  320.16
  5073.7  322.26  5110.0  321.53  5203.4  321.95  5260.6  324.38  5296.3  330.08
  5456.5  346.10  5497.9  349.97  5518.8  353.68  5539.7  353.52  5542.0  355.03
#Mann=6,-1,0
  4046.6    0.05       0  4338.4    0.16       0  4619.8    0.12       0
  4995.3    0.07       0  5001.3    0.12       0  5456.5    0.16       0
Bank Sta=4811.9,5110
Exp/Cntr=0.3,0.1

Chan Stop Cuts=-1