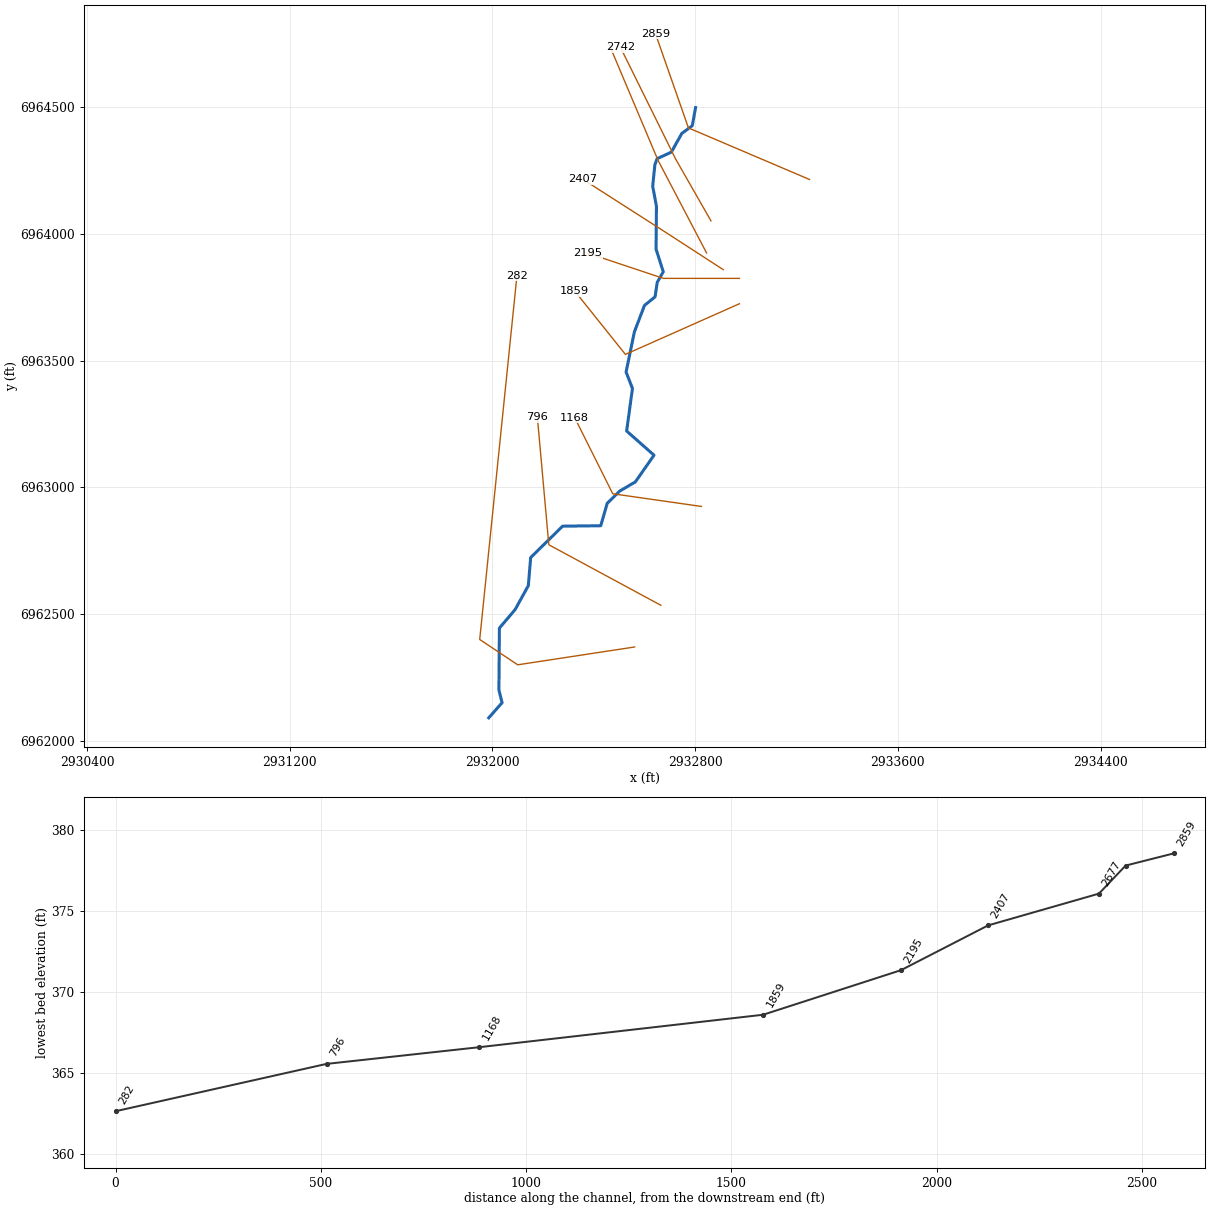
--- UNT 073 IN DRY CR WATERSHED.prj (project) ---

Proj Title=UNT 073 IN DRY CR WATERSHED Base Level Engineering
Current Plan=p01
Default Exp/Contr=0.3,0.1
English Units
Geom File=g01
Flow File=f01
Plan File=p01
BEGIN DESCRIPTION:
UNT 073 IN DRY CR WATERSHED
END DESCRIPTION:

--- UNT 073 IN DRY CR WATERSHED.p01 (plan) ---

Plan Title=Multiple Run
Short Identifier=Multiple
Geom File=g01
Flow File=f01
Subcritical Flow
K Sum by GR= 0
Std Step Tol= 0.01
Critical Tol= 0.01
Num of Std Step Trials= 20
Max Error Tol= 0.3
Flow Tol Ratio= 0.001
Split Flow NTrial= 30
Split Flow Tol= 0.02
Split Flow Ratio= 0.02
Log Output Level= 0
Friction Slope Method= 1
Unsteady Friction Slope Method= 2
Unsteady Bridges Friction Slope Method= 1
Parabolic Critical Depth
Global Vel Dist=  1 , 1 , 1
Global Log Level= 0
CheckData=True
Encroach Param= -1, 0, 0, 0
BEGIN DESCRIPTION:
Multiple Run
END DESCRIPTION:

--- UNT 073 IN DRY CR WATERSHED.f01 (steady flow) ---

Flow Title=Multiple
Number of Profiles=7
Profile Names=10-year,25-year,50-year,1pct_min,100-year,1pct_plu,500-year
River Rch & RM= UNT 073 IN DRY C,Reach-1,2859
     290     373     438     257     513    1024     702
Boundary for River Rch & Prof#=UNT 073 IN DRY C,Reach-1,1
Up Type=0
Dn Type=3
Dn Slope=0.005
Boundary for River Rch & Prof#=UNT 073 IN DRY C,Reach-1,2
Up Type=0
Dn Type=3
Dn Slope=0.005
Boundary for River Rch & Prof#=UNT 073 IN DRY C,Reach-1,3
Up Type=0
Dn Type=3
Dn Slope=0.005
Boundary for River Rch & Prof#=UNT 073 IN DRY C,Reach-1,4
Up Type=0
Dn Type=3
Dn Slope=0.005
Boundary for River Rch & Prof#=UNT 073 IN DRY C,Reach-1,5
Up Type=0
Dn Type=3
Dn Slope=0.005
Boundary for River Rch & Prof#=UNT 073 IN DRY C,Reach-1,6
Up Type=0
Dn Type=3
Dn Slope=0.005
Boundary for River Rch & Prof#=UNT 073 IN DRY C,Reach-1,7
Up Type=0
Dn Type=3
Dn Slope=0.005

--- UNT 073 IN DRY CR WATERSHED.g01 (geometry) ---

Geom Title=Existing Conditions

River Reach=UNT 073 IN DRY C,Reach-1
Reach XY= 30
      2932801.89      6964499.13      2932788.87      6964427.52
      2932747.63      6964397.14      2932706.40      6964323.35
      2932649.98      6964297.31      2932641.30      6964273.44
      2932632.62      6964188.80      2932647.47      6964109.27
      2932645.95      6963940.34      2932674.31      6963851.31
      2932650.47      6963809.10      2932642.01      6963752.27
      2932600.13      6963718.07      2932560.29      6963613.48
      2932527.63      6963455.53      2932552.75      6963390.67
      2932529.83      6963222.68      2932637.85      6963127.22
      2932564.38      6963021.94      2932502.64      6962985.70
      2932453.33      6962937.48      2932427.55      6962848.82
      2932277.06      6962847.17      2932151.20      6962723.35
      2932141.78      6962612.29      2932089.81      6962518.15
      2932027.69      6962444.84      2932025.81      6962200.53
      2932038.31      6962150.45      2931985.59      6962090.71

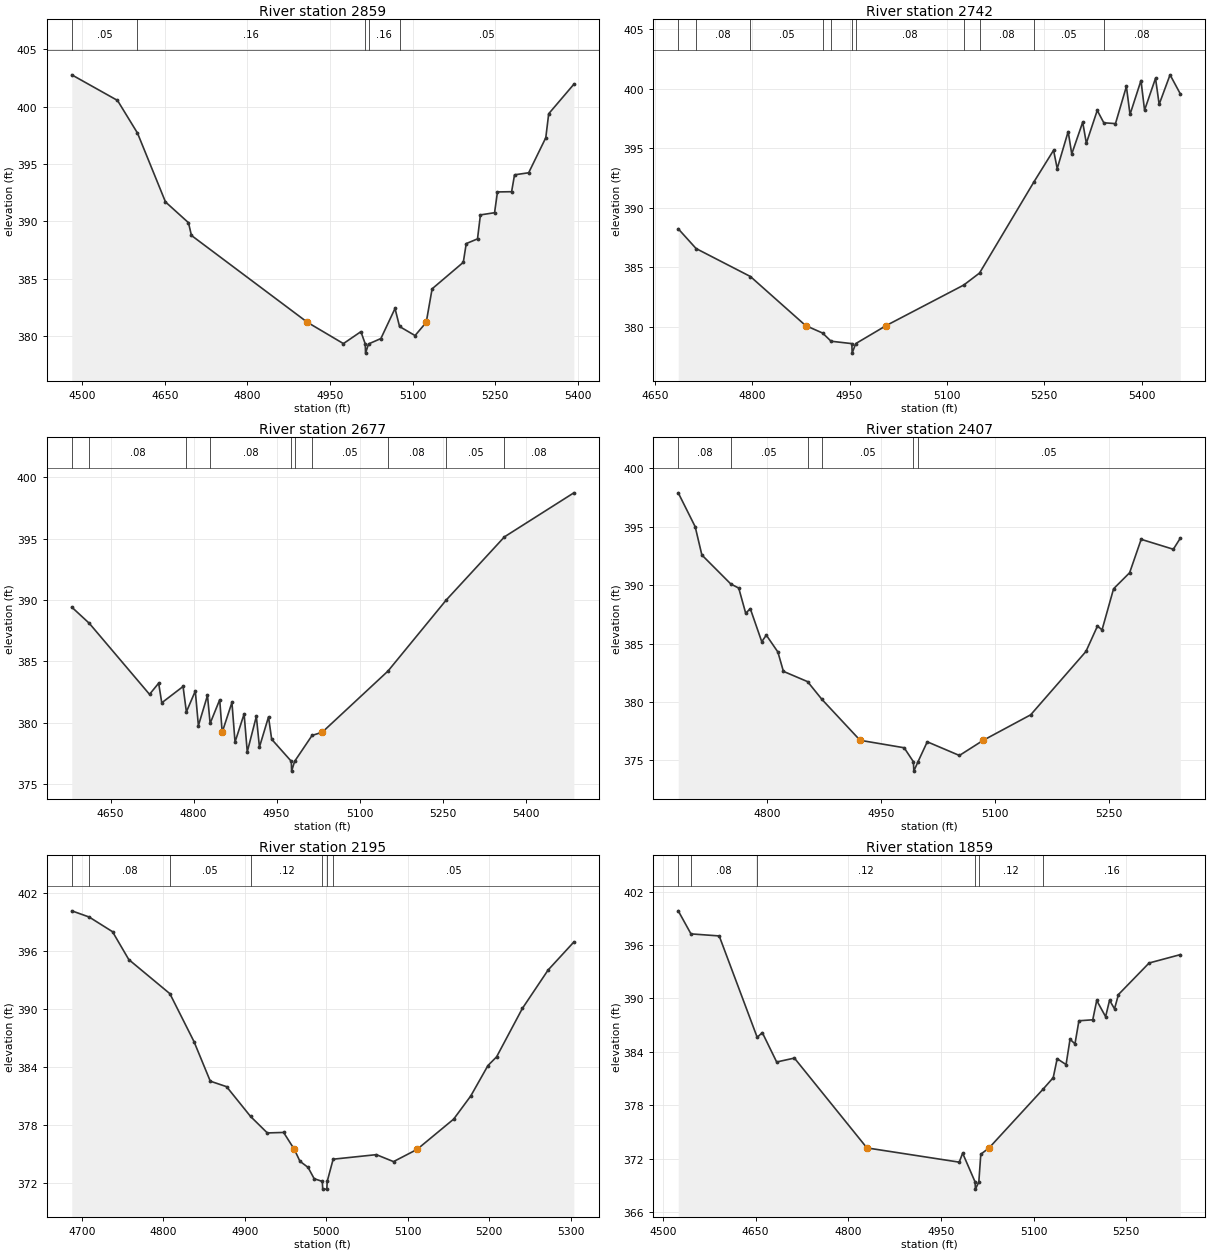
Type RM Length L Ch R = 1,2859,117,117,117
BEGIN DESCRIPTION:
UNT 073 IN DRY CR WATERSHED 5.0
END DESCRIPTION:
XS GIS Cut Line= 3
      2933251.43      6964215.32      2932773.67      6964418.84
      2932643.77      6964789.96
#Sta/Elev= 30
  4480.7  402.77  4563.8  400.54  4600.1  397.70  4651.0  391.70  4692.8  389.89
  4698.2  388.78  4909.1  381.21  4974.4  379.36  5006.2  380.40  5014.1  379.33
  5014.6  378.53  5020.1  379.33  5042.5  379.80  5068.2  382.42  5076.4  380.85
  5104.6  380.06  5124.9  381.21  5135.6  384.13  5192.3  386.44  5197.6  388.07
  5218.1  388.48  5223.4  390.57  5249.1  390.76  5254.4  392.57  5280.1  392.59
  5285.4  394.06  5311.1  394.24  5342.2  397.29  5347.5  399.38  5393.2  401.95
#Mann=5,-1,0
  4480.7    0.05       0  4600.1    0.16       0  5014.1    0.07       0
  5020.1    0.16       0  5076.4    0.05       0
Bank Sta=4909.1,5124.9
Exp/Cntr=0.3,0.1

Type RM Length L Ch R = 1,2742,65,65,65
BEGIN DESCRIPTION:
Mapping XS 6684a78f
END DESCRIPTION:
XS GIS Cut Line= 3
      2932862.50      6964052.16      2932723.62      6964295.20
      2932504.88      6964737.89
#Sta/Elev= 30
  4685.9  388.23  4713.4  386.57  4797.1  384.22  4882.1  380.10  4908.3  379.47
  4921.4  378.78  4953.4  378.58  4953.9  377.78  4959.4  378.58  5006.5  380.10
  5125.8  383.50  5150.2  384.51  5233.8  392.15  5264.3  394.83  5269.9  393.29
  5286.8  396.40  5292.3  394.52  5309.2  397.19  5314.8  395.42  5331.6  398.18
  5341.7  397.14  5359.7  397.07  5376.5  400.19  5382.1  397.84  5399.0  400.69
  5404.5  398.20  5421.4  400.88  5427.0  398.69  5443.8  401.17  5459.6  399.57
#Mann=11,-1,0
  4685.9    0.16       0  4713.4    0.08       0  4797.1    0.05       0
  4908.3    0.16       0  4921.4    0.08       0  4953.4    0.07       0
  4959.4    0.08       0  5125.8    0.05       0  5150.2    0.08       0
  5233.8    0.05       0  5341.7    0.08       0
Bank Sta=4882.1,5006.5
Exp/Cntr=0.3,0.1

Type RM Length L Ch R = 1,2677,270,270,270
BEGIN DESCRIPTION:
Mapping XS 15bbb918
END DESCRIPTION:
XS GIS Cut Line= 3
      2932845.15      6963925.39      2932654.17      6964290.00
      2932461.46      6964746.60
#Sta/Elev= 30
  4580.0  389.42  4611.7  388.10  4720.5  382.31  4737.0  383.22  4742.6  381.62
  4781.1  382.95  4787.1  380.88  4803.2  382.58  4808.8  379.76  4825.2  382.22
  4830.0  379.94  4847.3  381.87  4851.8  379.22  4869.4  381.65  4875.0  378.42
  4891.4  380.71  4897.1  377.62  4913.5  380.51  4919.1  378.01  4935.5  380.47
  4941.2  378.65  4976.7  376.85  4977.2  376.05  4982.7  376.85  5014.2  378.96
  5032.5  379.22  5151.4  384.21  5256.6  390.00  5361.8  395.15  5487.2  398.74
#Mann=10,-1,0
  4580.0    0.05       0  4611.7    0.08       0  4787.1    0.05       0
  4830.0    0.08       0  4976.7    0.07       0  4982.7    0.08       0
  5014.2    0.05       0  5151.4    0.08       0  5256.6    0.05       0
  5361.8    0.08       0
Bank Sta=4851.8,5032.5
Exp/Cntr=0.3,0.1

Type RM Length L Ch R = 1,2407,212,212,212
BEGIN DESCRIPTION:
Mapping XS 28db28c7
END DESCRIPTION:
XS GIS Cut Line= 3
      2932911.11      6963859.44      2932688.89      6964003.54
      2932355.57      6964217.07
#Sta/Elev= 30
  4683.5  397.91  4705.8  395.01  4714.6  392.59  4752.8  390.10  4763.1  389.76
  4772.3  387.60  4778.3  388.00  4793.4  385.17  4799.4  385.73  4814.6  384.29
  4821.9  382.63  4853.7  381.75  4872.6  380.23  4922.8  376.73  4980.8  376.09
  4993.0  374.89  4993.5  374.09  4999.0  374.89  5011.2  376.60  5053.5  375.43
  5084.9  376.73  5147.3  378.91  5220.0  384.33  5235.2  386.51  5241.2  386.18
  5256.4  389.70  5277.5  391.07  5292.7  393.93  5335.0  393.08  5344.2  394.03
#Mann=6,-1,0
  4683.5    0.08       0  4752.8    0.05       0  4853.7    0.08       0
  4872.6    0.05       0  4993.0    0.03       0  4999.0    0.05       0
Bank Sta=4922.8,5084.9
Exp/Cntr=0.3,0.1

Type RM Length L Ch R = 1,2195,336,336,336
BEGIN DESCRIPTION:
UNT 073 IN DRY CR WATERSHED 4.0
END DESCRIPTION:
XS GIS Cut Line= 3
      2932975.00      6963825.00      2932675.00      6963825.00
      2932375.02      6963924.99
#Sta/Elev= 30
  4687.8  400.15  4709.1  399.51  4737.8  397.99  4757.8  395.10  4808.2  391.57
  4837.8  386.61  4857.8  382.51  4877.8  381.94  4907.2  378.86  4927.8  377.15
  4947.8  377.20  4961.0  375.44  4967.8  374.22  4977.8  373.58  4985.3  372.41
  4995.3  372.13  4995.8  371.33  5000.8  371.33  5001.3  372.13  5008.6  374.43
  5061.6  374.90  5082.7  374.18  5111.5  375.44  5156.5  378.58  5177.5  380.98
  5198.6  384.13  5209.2  385.03  5240.8  390.04  5272.4  394.02  5304.0  396.92
#Mann=7,-1,0
  4687.8    0.05       0  4709.1    0.08       0  4808.2    0.05       0
  4907.2    0.12       0  4995.3    0.07       0  5001.3    0.12       0
  5008.6    0.05       0
Bank Sta=4961,5111.5
Exp/Cntr=0.3,0.1

Type RM Length L Ch R = 1,1859,691,691,691
BEGIN DESCRIPTION:
UNT 073 IN DRY CR WATERSHED 3.0
END DESCRIPTION:
XS GIS Cut Line= 3
      2932974.96      6963724.98      2932525.00      6963525.00
      2932324.97      6963775.04
#Sta/Elev= 30
  4524.9  399.84  4545.5  397.25  4591.2  397.02  4652.7  385.63  4661.0  386.16
  4684.2  382.86  4712.9  383.30  4830.3  373.21  4979.7  371.61  4985.2  372.62
  5005.4  369.38  5005.9  368.58  5011.4  369.38  5014.6  372.50  5028.0  373.21
  5115.4  379.81  5131.8  381.10  5138.2  383.23  5152.6  382.57  5159.0  385.41
  5167.0  384.90  5173.4  387.49  5195.8  387.60  5202.2  389.77  5216.6  387.95
  5223.0  389.80  5231.0  388.83  5237.4  390.44  5287.0  393.98  5337.5  394.92
#Mann=6,-1,0
  4524.9    0.05       0  4545.5    0.08       0  4652.7    0.12       0
  5005.4    0.07       0  5011.4    0.12       0  5115.4    0.16       0
Bank Sta=4830.3,5028
Exp/Cntr=0.3,0.1

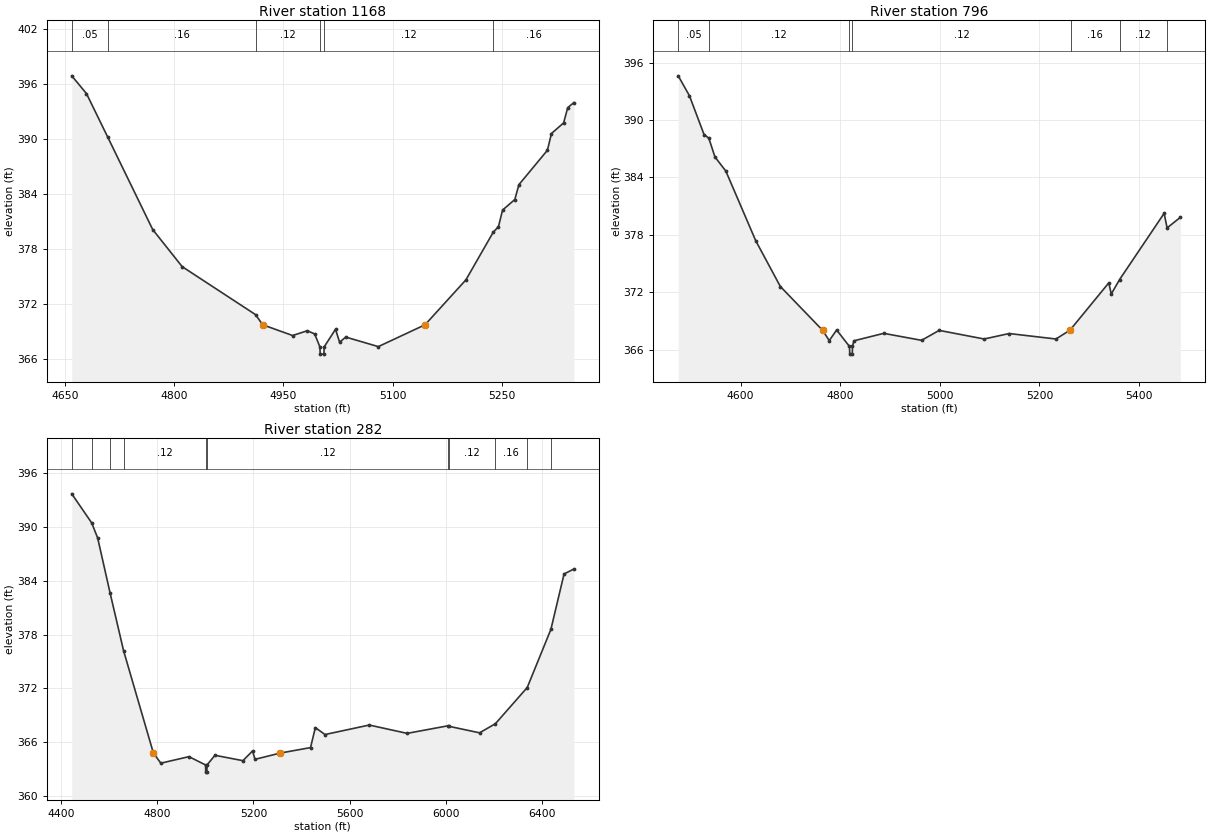
Type RM Length L Ch R = 1,1168,372,372,372
BEGIN DESCRIPTION:
UNT 073 IN DRY CR WATERSHED 2.0
END DESCRIPTION:
XS GIS Cut Line= 3
      2932824.96      6962925.01      2932475.00      6962975.00
      2932325.01      6963274.98
#Sta/Elev= 30
  4659.5  396.93  4679.7  394.99  4708.7  390.27  4770.6  380.16  4811.0  376.12
  4911.6  370.89  4921.5  369.78  4962.5  368.61  4982.7  369.13  4992.8  368.78
  4999.9  367.38  5000.4  366.58  5005.4  366.58  5005.9  367.38  5021.4  369.29
  5027.0  367.88  5035.4  368.44  5080.1  367.40  5144.2  369.78  5200.3  374.68
  5237.7  379.86  5245.0  380.49  5250.6  382.29  5267.4  383.44  5273.0  385.06
  5312.1  388.81  5317.7  390.64  5334.4  391.80  5340.0  393.46  5348.4  394.01
#Mann=6,-1,0
  4659.5    0.05       0  4708.7    0.16       0  4911.6    0.12       0
  4999.9    0.07       0  5005.9    0.12       0  5237.7    0.16       0
Bank Sta=4921.5,5144.2
Exp/Cntr=0.3,0.1

Type RM Length L Ch R = 1,796,514,514,514
BEGIN DESCRIPTION:
Mapping XS aabb8e3e
END DESCRIPTION:
XS GIS Cut Line= 3
      2932664.81      6962534.98      2932222.71      6962773.78
      2932177.54      6963277.18
#Sta/Elev= 30
  4475.0  394.61  4497.5  392.53  4526.8  388.48  4536.4  388.10  4548.7  386.14
  4570.6  384.66  4630.5  377.40  4680.0  372.61  4765.2  368.02  4778.1  366.96
  4793.0  368.07  4818.8  366.35  4819.3  365.55  4824.3  365.55  4824.8  366.35
  4827.5  366.94  4887.5  367.72  4963.5  366.99  4998.8  368.03  5089.1  367.13
  5139.3  367.70  5233.2  367.13  5260.5  368.02  5262.8  368.14  5339.3  372.99
  5344.3  371.83  5360.9  373.33  5450.4  380.25  5456.4  378.73  5482.9  379.83
#Mann=7,-1,0
  4475.0    0.05       0  4536.4    0.12       0  4818.8    0.07       0
  4824.8    0.12       0  5262.8    0.16       0  5360.9    0.12       0
  5456.4    0.16       0
Bank Sta=4765.2,5260.5
Exp/Cntr=0.3,0.1

Type RM Length L Ch R = 1,282,0,0,0
BEGIN DESCRIPTION:
UNT 073 IN DRY CR WATERSHED 1.0
END DESCRIPTION:
XS GIS Cut Line= 4
      2932561.52      6962370.42      2932100.00      6962300.00
      2931950.00      6962400.00      2932096.87      6963835.46
#Sta/Elev= 30
  4443.6  393.72  4526.4  390.48  4551.4  388.79  4602.7  382.69  4659.2  376.20
  4783.4  364.76  4814.4  363.63  4931.5  364.36  5000.6  363.43  5001.1  362.63
  5006.1  362.63  5006.6  363.43  5039.7  364.51  5156.1  363.91  5196.3  365.00
  5206.3  364.06  5311.5  364.76  5437.5  365.37  5457.6  367.60  5497.9  366.83
  5682.0  367.89  5839.6  366.96  6010.5  367.81  6013.6  367.75  6141.2  367.02
  6207.2  368.04  6339.6  372.08  6438.2  378.58  6493.0  384.77  6533.7  385.32
#Mann=11,-1,0
  4443.6    0.05       0  4526.4    0.12       0  4602.7    0.16       0
  4659.2    0.12       0  5000.6    0.07       0  5006.6    0.12       0
  6010.5    0.16       0  6013.6    0.12       0  6207.2    0.16       0
  6339.6    0.05       0  6438.2    0.16       0
Bank Sta=4783.4,5311.5
Exp/Cntr=0.3,0.1

Chan Stop Cuts=-1