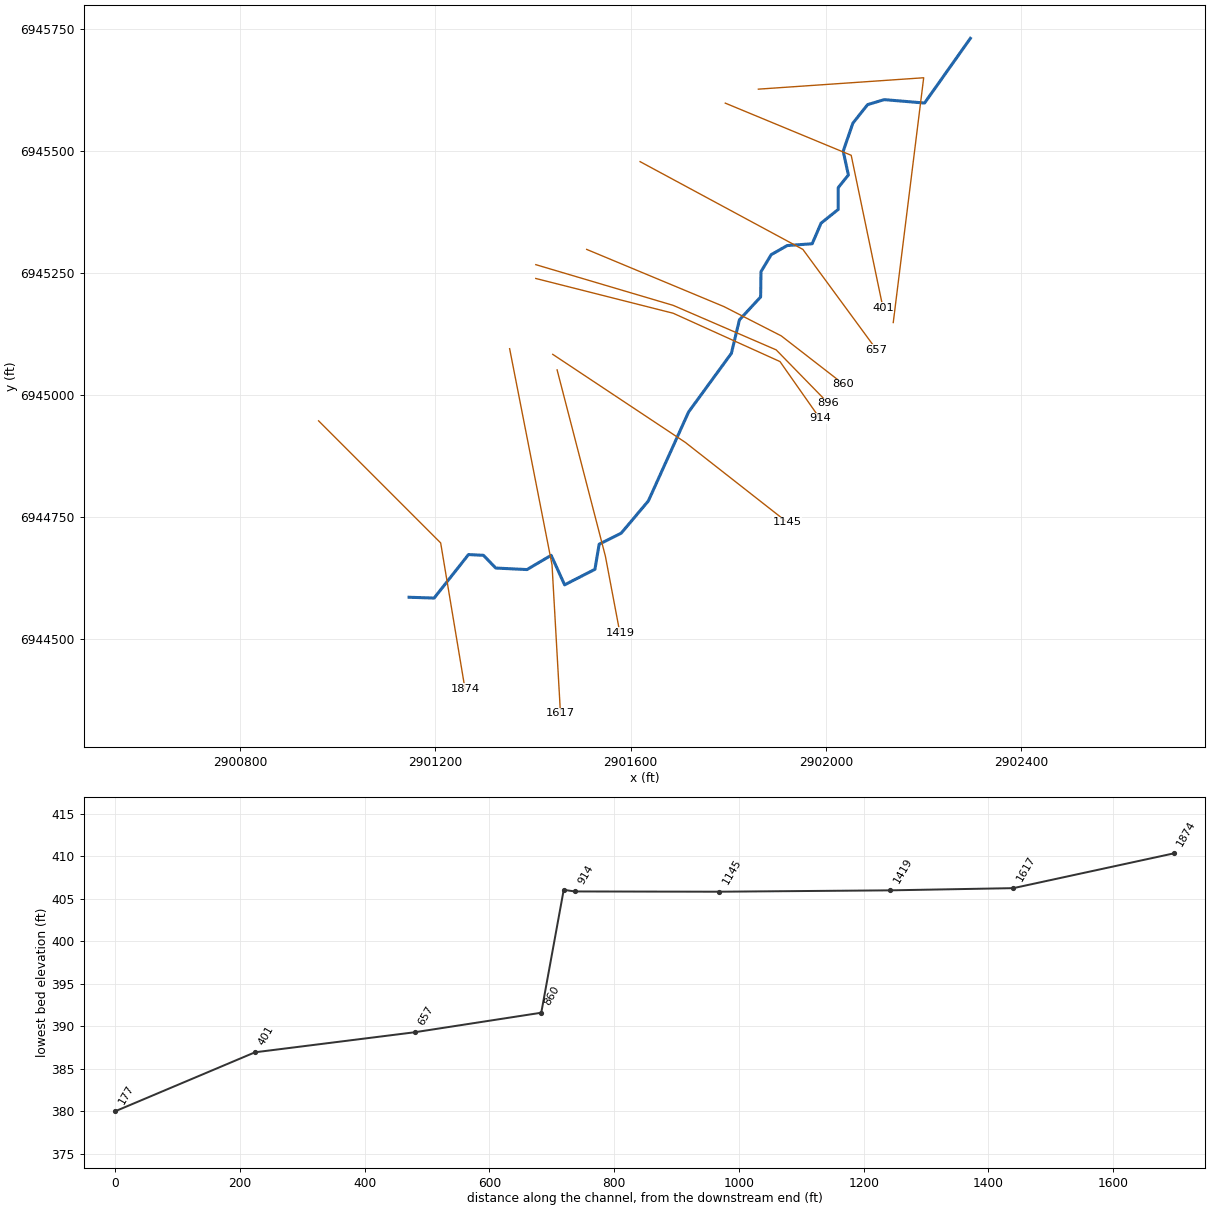
--- UNT 074 IN DRY CR WATERSHED.prj (project) ---

Proj Title=UNT 074 IN DRY CR WATERSHED Base Level Engineering
Current Plan=p01
Default Exp/Contr=0.3,0.1
English Units
Geom File=g01
Flow File=f01
Plan File=p01
BEGIN DESCRIPTION:
UNT 074 IN DRY CR WATERSHED
END DESCRIPTION:

--- UNT 074 IN DRY CR WATERSHED.p01 (plan) ---

Plan Title=Multiple Run
Short Identifier=Multiple
Geom File=g01
Flow File=f01
Subcritical Flow
K Sum by GR= 0
Std Step Tol= 0.01
Critical Tol= 0.01
Num of Std Step Trials= 20
Max Error Tol= 0.3
Flow Tol Ratio= 0.001
Split Flow NTrial= 30
Split Flow Tol= 0.02
Split Flow Ratio= 0.02
Log Output Level= 0
Friction Slope Method= 1
Unsteady Friction Slope Method= 2
Unsteady Bridges Friction Slope Method= 1
Parabolic Critical Depth
Global Vel Dist=  1 , 1 , 1
Global Log Level= 0
CheckData=True
Encroach Param= -1, 0, 0, 0
BEGIN DESCRIPTION:
Multiple Run
END DESCRIPTION:

--- UNT 074 IN DRY CR WATERSHED.f01 (steady flow) ---

Flow Title=Multiple
Number of Profiles=7
Profile Names=10-year,25-year,50-year,1pct_min,100-year,1pct_plu,500-year
River Rch & RM= UNT 074 IN DRY C,Reach-1,1874
     319     416     492     291     581    1160     809
Boundary for River Rch & Prof#=UNT 074 IN DRY C,Reach-1,1
Up Type=0
Dn Type=3
Dn Slope=0.005
Boundary for River Rch & Prof#=UNT 074 IN DRY C,Reach-1,2
Up Type=0
Dn Type=3
Dn Slope=0.005
Boundary for River Rch & Prof#=UNT 074 IN DRY C,Reach-1,3
Up Type=0
Dn Type=3
Dn Slope=0.005
Boundary for River Rch & Prof#=UNT 074 IN DRY C,Reach-1,4
Up Type=0
Dn Type=3
Dn Slope=0.005
Boundary for River Rch & Prof#=UNT 074 IN DRY C,Reach-1,5
Up Type=0
Dn Type=3
Dn Slope=0.005
Boundary for River Rch & Prof#=UNT 074 IN DRY C,Reach-1,6
Up Type=0
Dn Type=3
Dn Slope=0.005
Boundary for River Rch & Prof#=UNT 074 IN DRY C,Reach-1,7
Up Type=0
Dn Type=3
Dn Slope=0.005

--- UNT 074 IN DRY CR WATERSHED.g01 (geometry) ---

Geom Title=Existing Conditions

River Reach=UNT 074 IN DRY C,Reach-1
Reach XY= 30
      2901146.25      6944586.20      2901197.58      6944584.58
      2901267.89      6944673.64      2901298.62      6944672.08
      2901323.62      6944646.04      2901387.68      6944642.91
      2901437.16      6944672.08      2901464.77      6944611.66
      2901526.75      6944643.43      2901535.50      6944694.91
      2901580.64      6944717.48      2901636.19      6944783.45
      2901718.66      6944965.74      2901806.21      6945085.71
      2901822.71      6945154.28      2901866.10      6945201.16
      2901866.80      6945252.90      2901887.73      6945287.73
      2901920.60      6945306.43      2901971.65      6945310.07
      2901989.87      6945352.26      2902025.00      6945380.38
      2902025.00      6945425.00      2902045.79      6945450.86
      2902035.19      6945499.66      2902054.98      6945556.95
      2902085.19      6945594.97      2902119.08      6945605.20
      2902201.80      6945598.24      2902295.59      6945730.71

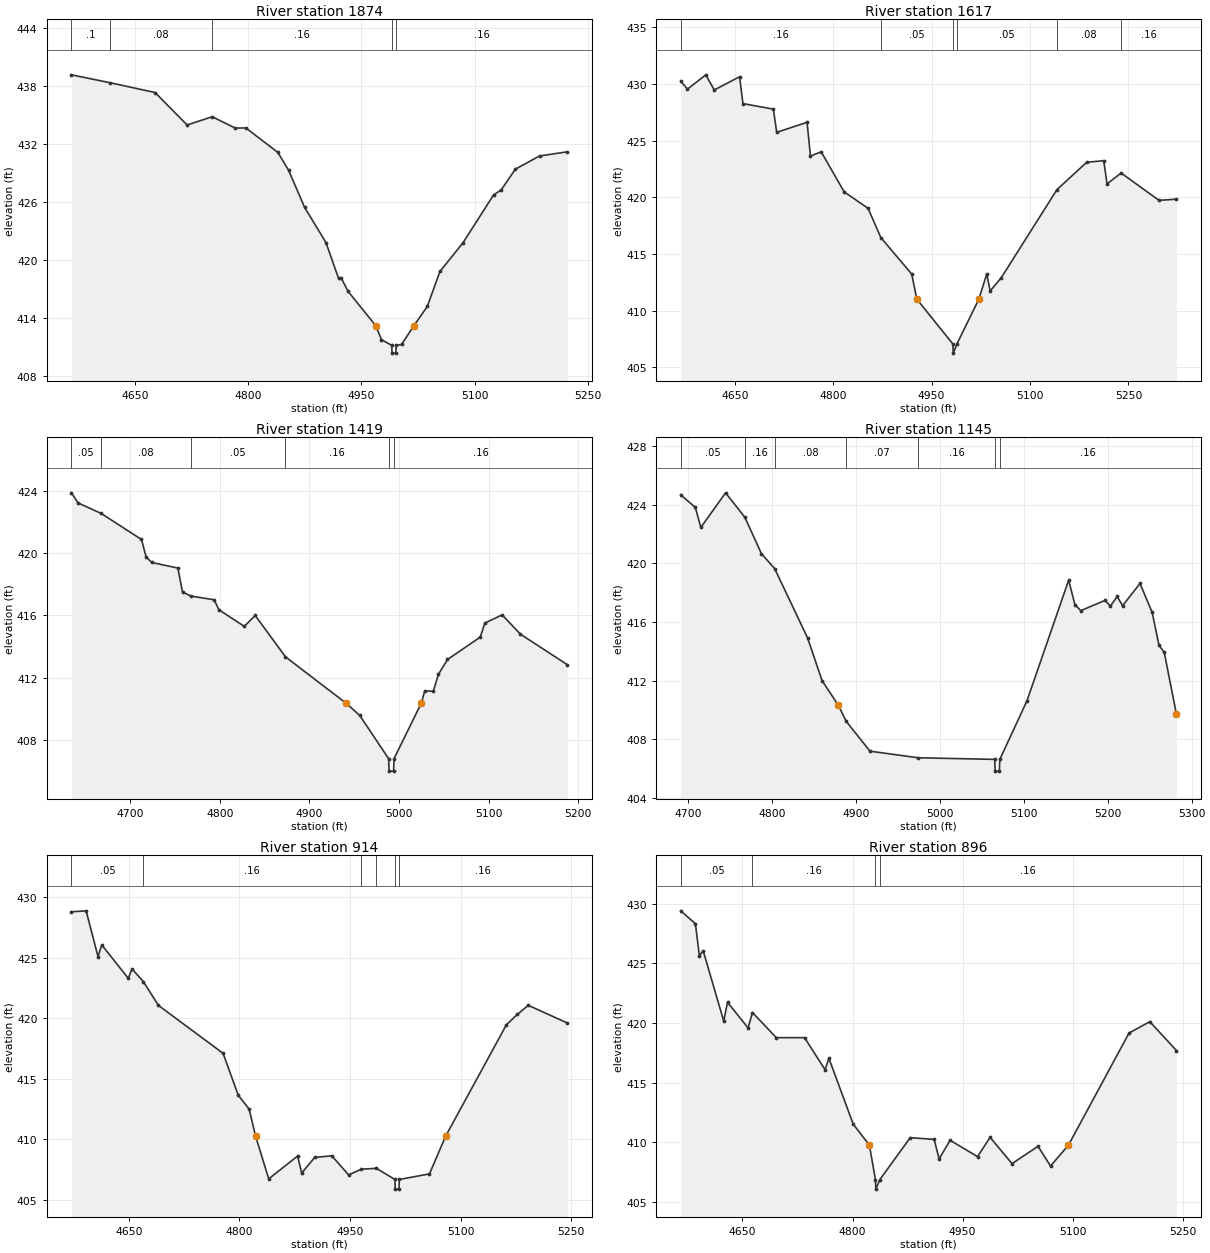
Type RM Length L Ch R = 1,1874,257,257,257
BEGIN DESCRIPTION:
double UNT 074 IN DRY CR WATERSHED 2.0
END DESCRIPTION:
XS GIS Cut Line= 3
      2900960.94      6944947.48      2901210.94      6944697.48
      2901260.72      6944398.76
#Sta/Elev= 30
  4566.1  439.15  4617.3  438.33  4676.8  437.32  4719.2  433.96  4752.5  434.81
  4782.9  433.64  4797.0  433.65  4839.4  431.12  4853.6  429.27  4874.8  425.43
  4903.1  421.78  4919.7  418.09  4923.4  418.09  4932.3  416.74  4969.4  413.14
  4976.4  411.75  4990.1  411.14  4990.6  410.34  4995.6  410.34  4996.1  411.14
  5003.3  411.25  5019.1  413.14  5037.2  415.17  5054.0  418.80  5084.4  421.75
  5124.9  426.71  5135.1  427.24  5153.8  429.38  5185.8  430.75  5222.5  431.18
#Mann=5,-1,0
  4566.1     0.1       0  4617.3    0.08       0  4752.5    0.16       0
  4990.1    0.07       0  4996.1    0.16       0
Bank Sta=4969.4,5019.1
Exp/Cntr=0.3,0.1

Type RM Length L Ch R = 1,1617,198,198,198
BEGIN DESCRIPTION:
Mapping XS ac660ea2
END DESCRIPTION:
XS GIS Cut Line= 3
      2901352.14      6945095.22      2901438.95      6944652.49
      2901456.23      6944348.44
#Sta/Elev= 30
  4567.5  430.25  4577.9  429.56  4605.9  430.82  4618.7  429.48  4657.3  430.65
  4662.4  428.28  4708.8  427.79  4713.9  425.74  4760.2  426.63  4765.3  423.65
  4781.7  424.02  4816.8  420.48  4853.1  419.04  4872.6  416.45  4919.7  413.23
  4927.5  411.01  4982.5  407.05  4983.0  406.25  4988.5  407.05  5022.0  411.01
  5034.1  413.24  5039.2  411.73  5056.2  412.91  5141.0  420.68  5186.4  423.10
  5212.4  423.24  5217.4  421.19  5238.9  422.15  5296.6  419.74  5323.2  419.84
#Mann=6,-1,0
  4567.5    0.16       0  4872.6    0.05       0  4982.5    0.04       0
  4988.5    0.05       0  5141.0    0.08       0  5238.9    0.16       0
Bank Sta=4927.5,5022
Exp/Cntr=0.3,0.1

Type RM Length L Ch R = 1,1419,274,274,274
BEGIN DESCRIPTION:
Mapping XS 2d662173
END DESCRIPTION:
XS GIS Cut Line= 3
      2901449.36      6945051.82      2901548.33      6944669.85
      2901577.84      6944513.60
#Sta/Elev= 30
  4634.2  423.89  4641.6  423.24  4667.2  422.57  4712.4  420.89  4717.6  419.76
  4723.9  419.41  4753.0  419.05  4758.2  417.51  4767.6  417.25  4793.6  417.01
  4798.8  416.37  4827.2  415.30  4839.4  416.00  4873.2  413.34  4940.6  410.37
  4956.0  409.58  4988.4  406.79  4988.9  405.99  4993.9  405.99  4994.4  406.79
  5024.9  410.37  5028.7  411.15  5038.3  411.13  5043.9  412.21  5054.1  413.17
  5090.7  414.61  5095.8  415.51  5115.1  416.04  5135.5  414.80  5187.8  412.84
#Mann=6,-1,0
  4634.2    0.05       0  4667.2    0.08       0  4767.6    0.05       0
  4873.2    0.16       0  4988.4    0.07       0  4994.4    0.16       0
Bank Sta=4940.6,5024.9
Exp/Cntr=0.3,0.1

Type RM Length L Ch R = 1,1145,231,231,231
BEGIN DESCRIPTION:
Mapping XS df978cc9
END DESCRIPTION:
XS GIS Cut Line= 3
      2901440.43      6945083.61      2901711.72      6944903.47
      2901920.20      6944740.13
#Sta/Elev= 30
  4691.4  424.67  4708.9  423.80  4715.4  422.44  4744.9  424.80  4767.9  423.13
  4787.6  420.65  4803.3  419.64  4842.5  414.92  4859.8  412.00  4879.3  410.31
  4888.6  409.22  4916.9  407.19  4974.2  406.74  5065.5  406.63  5066.0  405.83
  5071.0  405.83  5071.5  406.63  5103.8  410.61  5153.5  418.84  5161.0  417.18
  5168.0  416.77  5196.9  417.47  5203.2  417.07  5211.3  417.74  5217.7  417.10
  5238.5  418.62  5253.0  416.65  5261.1  414.41  5267.4  413.92  5281.9  409.71
#Mann=7,-1,0
  4691.4    0.05       0  4767.9    0.16       0  4803.3    0.08       0
  4888.6    0.07       0  4974.2    0.16       0  5065.5    0.07       0
  5071.5    0.16       0
Bank Sta=4879.3,5281.9
Exp/Cntr=0.3,0.1

Type RM Length L Ch R = 1,914,18,18,18
BEGIN DESCRIPTION:
Mapping XS 779e3334
END DESCRIPTION:
XS GIS Cut Line= 4
      2901405.72      6945238.98      2901686.98      6945167.80
      2901905.73      6945068.84      2901987.32      6944952.53
#Sta/Elev= 30
  4572.3  428.81  4592.2  428.89  4608.3  425.10  4613.4  426.07  4649.3  423.31
  4654.5  424.08  4669.7  423.04  4690.3  421.06  4777.9  417.10  4798.5  413.63
  4813.3  412.48  4822.0  410.24  4839.8  406.71  4879.0  408.60  4884.5  407.19
  4902.1  408.48  4925.3  408.62  4948.1  407.04  4965.5  407.51  4985.9  407.58
  5010.9  406.66  5011.4  405.86  5016.4  405.86  5016.9  406.66  5057.8  407.12
  5079.7  410.24  5162.2  419.47  5177.0  420.32  5191.8  421.07  5244.6  419.61
#Mann=6,-1,0
  4572.3    0.05       0  4669.7    0.16       0  4965.5    0.05       0
  4985.9    0.16       0  5010.9    0.07       0  5016.9    0.16       0
Bank Sta=4822,5079.7
Exp/Cntr=0.3,0.1

Type RM Length L Ch R = 1,896,36,36,36
BEGIN DESCRIPTION:
Mapping XS 22b4e3a9
END DESCRIPTION:
XS GIS Cut Line= 4
      2901405.74      6945267.27      2901686.98      6945183.94
      2901897.92      6945092.80      2902004.72      6944983.40
#Sta/Elev= 30
  4565.7  429.42  4585.8  428.34  4591.2  425.64  4596.4  426.07  4624.4  420.16
  4629.6  421.74  4657.6  419.59  4663.6  420.88  4696.1  418.77  4734.6  418.77
  4762.6  416.08  4767.8  417.04  4801.0  411.50  4823.0  409.75  4831.3  406.85
  4831.8  406.05  4837.3  406.85  4878.7  410.37  4911.3  410.23  4918.1  408.59
  4933.1  410.15  4970.5  408.78  4987.6  410.40  5017.5  408.19  5053.0  409.65
  5070.0  407.99  5094.5  409.75  5177.1  419.16  5205.4  420.11  5241.7  417.69
#Mann=4,-1,0
  4565.7    0.05       0  4663.6    0.16       0  4831.3    0.07       0
  4837.3    0.16       0
Bank Sta=4823,5094.5
Exp/Cntr=0.3,0.1

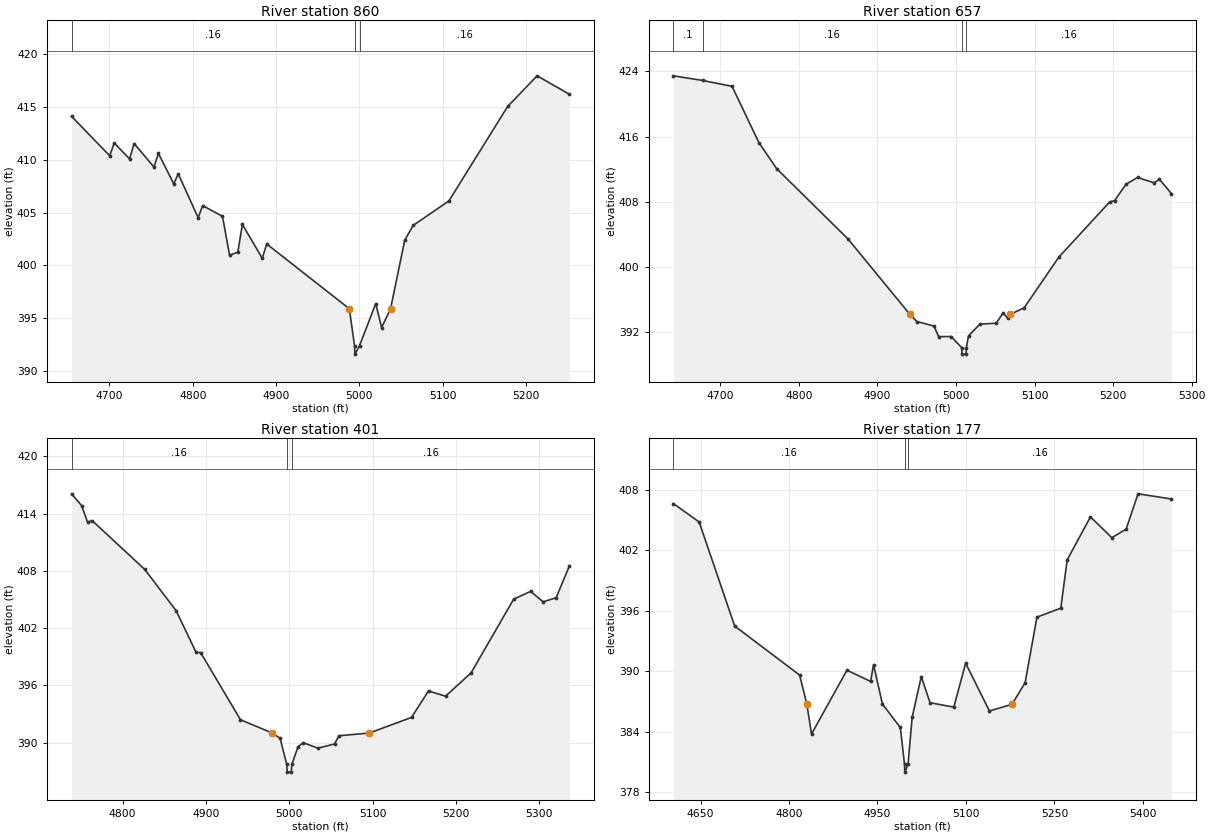
Type RM Length L Ch R = 1,860,203,203,203
BEGIN DESCRIPTION:
Mapping XS ebc3df9f
END DESCRIPTION:
XS GIS Cut Line= 4
      2901509.90      6945298.53      2901791.15      6945181.34
      2901908.34      6945121.44      2902035.96      6945022.47
#Sta/Elev= 30
  4654.5  414.12  4700.3  410.38  4705.7  411.59  4724.1  410.09  4729.6  411.54
  4753.4  409.32  4758.8  410.60  4777.2  407.72  4782.6  408.67  4806.5  404.51
  4811.9  405.66  4835.7  404.64  4844.2  400.96  4854.1  401.24  4859.6  403.88
  4883.4  400.67  4888.8  402.02  4988.0  395.88  4994.2  392.38  4994.7  391.58
  5000.2  392.38  5019.7  396.37  5026.7  394.10  5037.5  395.88  5054.5  402.38
  5064.6  403.78  5107.5  406.10  5178.1  415.06  5213.4  417.96  5252.3  416.21
#Mann=3,-1,0
  4654.5    0.16       0  4994.2    0.07       0  5000.2    0.16       0
Bank Sta=4988,5037.5
Exp/Cntr=0.3,0.1

Type RM Length L Ch R = 1,657,256,256,256
BEGIN DESCRIPTION:
Mapping XS 63c25dac
END DESCRIPTION:
XS GIS Cut Line= 3
      2901619.30      6945478.20      2901952.61      6945298.53
      2902103.66      6945092.78
#Sta/Elev= 30
  4640.3  423.45  4677.4  422.88  4714.9  422.16  4749.0  415.26  4771.7  412.05
  4862.6  403.41  4941.3  394.16  4950.2  393.28  4972.1  392.72  4977.8  391.43
  4994.0  391.44  5007.2  390.08  5007.7  389.28  5012.7  389.28  5013.2  390.08
  5015.9  391.52  5030.5  392.97  5051.3  393.07  5059.8  394.34  5066.0  393.69
  5069.1  394.16  5086.8  394.97  5130.8  401.18  5195.6  407.96  5201.8  408.12
  5216.5  410.14  5231.1  410.97  5252.0  410.32  5259.0  410.74  5274.2  409.00
#Mann=4,-1,0
  4640.3     0.1       0  4677.4    0.16       0  5007.2    0.07       0
  5013.2    0.16       0
Bank Sta=4941.3,5069.1
Exp/Cntr=0.3,0.1

Type RM Length L Ch R = 1,401,224,224,224
BEGIN DESCRIPTION:
Mapping XS 50bc6eef
END DESCRIPTION:
XS GIS Cut Line= 3
      2901793.76      6945598.00      2902051.57      6945491.23
      2902116.54      6945179.37
#Sta/Elev= 30
  4738.8  416.06  4751.0  414.81  4758.0  413.09  4763.5  413.26  4826.7  408.14
  4864.4  403.81  4888.3  399.45  4893.7  399.44  4941.5  392.41  4979.8  391.01
  4989.1  390.45  4997.1  387.72  4997.6  386.92  5002.6  386.92  5003.1  387.72
  5010.7  389.60  5017.0  390.00  5034.4  389.43  5054.5  389.87  5059.6  390.73
  5096.1  391.01  5146.8  392.65  5167.2  395.42  5187.6  394.87  5218.3  397.31
  5269.4  405.03  5289.8  405.85  5304.7  404.75  5320.4  405.18  5336.4  408.54
#Mann=3,-1,0
  4738.8    0.16       0  4997.1    0.07       0  5003.1    0.16       0
Bank Sta=4979.8,5096.1
Exp/Cntr=0.3,0.1

Type RM Length L Ch R = 1,177,0,0,0
BEGIN DESCRIPTION:
double UNT 074 IN DRY CR WATERSHED 1.0
END DESCRIPTION:
XS GIS Cut Line= 3
      2901861.47      6945626.65      2902200.00      6945650.00
      2902137.67      6945148.79
#Sta/Elev= 30
  4604.0  406.63  4647.6  404.80  4707.8  394.48  4818.0  389.61  4830.2  386.71
  4838.1  383.76  4898.2  390.10  4938.3  388.98  4943.3  390.64  4958.4  386.73
  4988.7  384.41  4995.8  380.78  4996.3  379.98  5001.8  380.78  5008.8  385.43
  5024.2  389.46  5039.1  386.87  5079.4  386.43  5099.5  390.79  5139.8  386.05
  5178.1  386.71  5200.3  388.85  5220.4  395.36  5260.8  396.25  5271.7  401.05
  5311.1  405.31  5347.4  403.25  5371.6  404.09  5391.8  407.60  5448.4  407.09
#Mann=3,-1,0
  4604.0    0.16       0  4995.8    0.07       0  5001.8    0.16       0
Bank Sta=4830.2,5178.1
Exp/Cntr=0.3,0.1

Chan Stop Cuts=-1