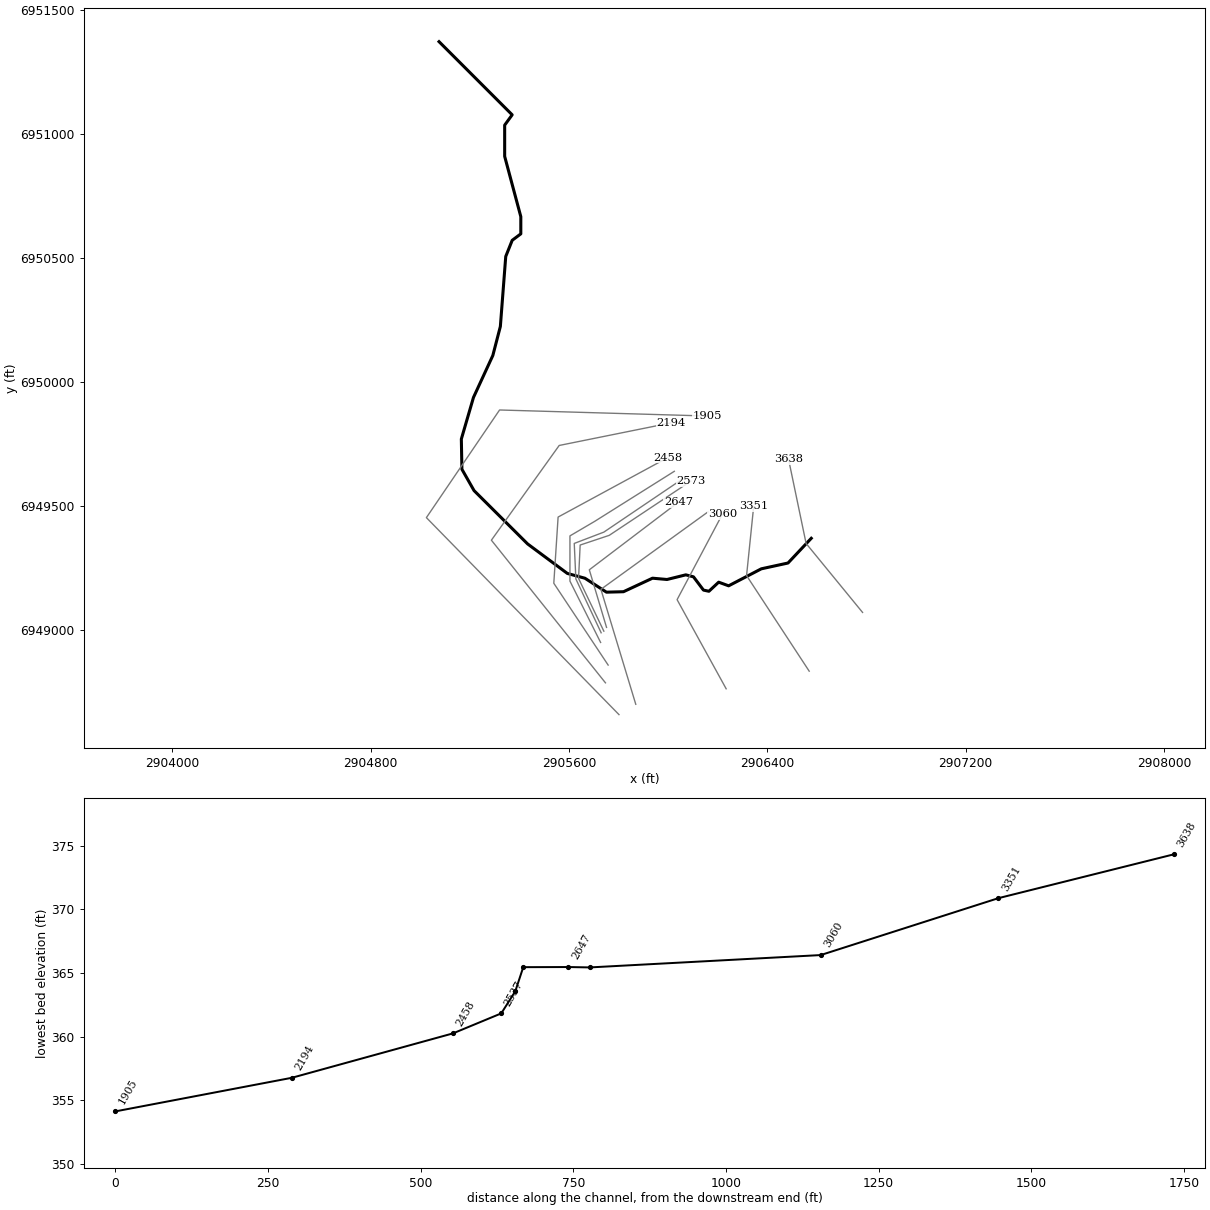
--- UNT 075 IN DRY CR WATERSHED.prj (project) ---

Proj Title=UNT 075 IN DRY CR WATERSHED Base Level Engineering
Current Plan=p01
Default Exp/Contr=0.3,0.1
English Units
Geom File=g01
Flow File=f01
Plan File=p01
BEGIN DESCRIPTION:
UNT 075 IN DRY CR WATERSHED
END DESCRIPTION:

--- UNT 075 IN DRY CR WATERSHED.p01 (plan) ---

Plan Title=Multiple Run
Short Identifier=Multiple
Geom File=g01
Flow File=f01
Subcritical Flow
K Sum by GR= 0
Std Step Tol= 0.01
Critical Tol= 0.01
Num of Std Step Trials= 20
Max Error Tol= 0.3
Flow Tol Ratio= 0.001
Split Flow NTrial= 30
Split Flow Tol= 0.02
Split Flow Ratio= 0.02
Log Output Level= 0
Friction Slope Method= 1
Unsteady Friction Slope Method= 2
Unsteady Bridges Friction Slope Method= 1
Parabolic Critical Depth
Global Vel Dist=  1 , 1 , 1
Global Log Level= 0
CheckData=True
Encroach Param= -1, 0, 0, 0
BEGIN DESCRIPTION:
Multiple Run
END DESCRIPTION:

--- UNT 075 IN DRY CR WATERSHED.f01 (steady flow) ---

Flow Title=Multiple
Number of Profiles=7
Profile Names=10-year,25-year,50-year,1pct_min,100-year,1pct_plu,500-year
River Rch & RM= UNT 075 IN DRY C,Reach-1,3638
     366     484     579     346     690    1376     979
Boundary for River Rch & Prof#=UNT 075 IN DRY C,Reach-1,1
Up Type=0
Dn Type=3
Dn Slope=0.005
Boundary for River Rch & Prof#=UNT 075 IN DRY C,Reach-1,2
Up Type=0
Dn Type=3
Dn Slope=0.005
Boundary for River Rch & Prof#=UNT 075 IN DRY C,Reach-1,3
Up Type=0
Dn Type=3
Dn Slope=0.005
Boundary for River Rch & Prof#=UNT 075 IN DRY C,Reach-1,4
Up Type=0
Dn Type=3
Dn Slope=0.005
Boundary for River Rch & Prof#=UNT 075 IN DRY C,Reach-1,5
Up Type=0
Dn Type=3
Dn Slope=0.005
Boundary for River Rch & Prof#=UNT 075 IN DRY C,Reach-1,6
Up Type=0
Dn Type=3
Dn Slope=0.005
Boundary for River Rch & Prof#=UNT 075 IN DRY C,Reach-1,7
Up Type=0
Dn Type=3
Dn Slope=0.005

--- UNT 075 IN DRY CR WATERSHED.g01 (geometry) ---

Geom Title=Existing Conditions

River Reach=UNT 075 IN DRY C,Reach-1
Reach XY= 30
      2906576.90      6949368.25      2906483.15      6949268.59
      2906375.34      6949245.16      2906243.64      6949176.64
      2906203.43      6949191.34      2906164.11      6949154.66
      2906142.12      6949159.41      2906101.86      6949212.91
      2906070.82      6949220.89      2905995.08      6949202.16
      2905936.60      6949207.39      2905819.58      6949152.88
      2905750.88      6949151.01      2905664.14      6949207.20
      2905593.11      6949226.59      2905432.73      6949345.64
      2905216.82      6949560.58      2905167.88      6949646.57
      2905165.56      6949768.42      2905214.44      6949936.04
      2905292.57      6950105.31      2905322.95      6950222.49
      2905344.65      6950504.61      2905370.69      6950569.72
      2905405.42      6950595.76      2905405.42      6950665.20
      2905340.31      6950908.26      2905340.31      6951034.13
      2905370.59      6951075.71      2905075.59      6951370.71

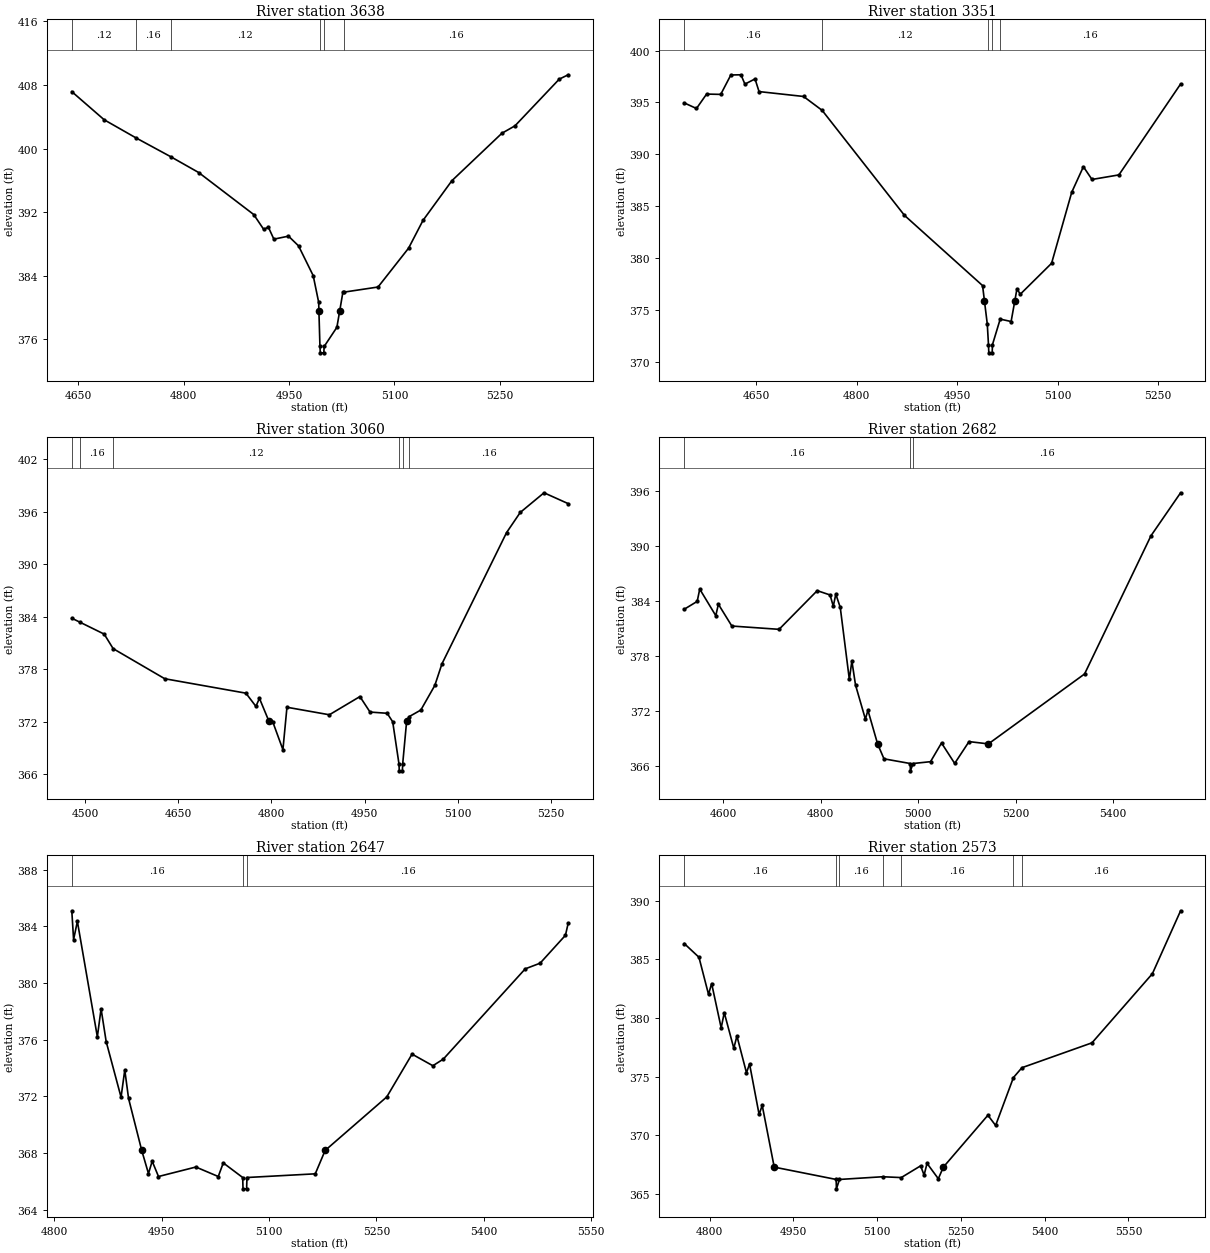
Type RM Length L Ch R = 1,3638,287,287,287
BEGIN DESCRIPTION:
UNT 075 IN DRY CR WATERSHED 2.0
END DESCRIPTION:
XS GIS Cut Line= 3
      2906783.83      6949069.35      2906556.11      6949347.40
      2906485.23      6949687.39
#Sta/Elev= 30
  4640.6  407.17  4686.7  403.63  4732.0  401.35  4781.5  398.98  4821.3  396.99
  4899.6  391.71  4913.9  389.83  4920.4  390.13  4928.3  388.61  4949.1  388.99
  4963.4  387.77  4984.3  384.02  4992.1  380.66  4992.4  379.62  4993.9  375.11
  4994.4  374.31  4999.4  374.31  4999.9  375.11  5018.0  377.52  5022.1  379.62
  5026.5  381.91  5028.4  381.95  5076.6  382.59  5120.1  387.48  5140.6  390.97
  5181.7  395.96  5252.9  401.93  5271.6  402.87  5334.6  408.74  5347.3  409.29
#Mann=6,-1,0
  4640.6    0.12       0  4732.0    0.16       0  4781.5    0.12       0
  4993.9    0.07       0  4999.9    0.12       0  5028.4    0.16       0
Bank Sta=4992.4,5022.1
Exp/Cntr=0.3,0.1

Type RM Length L Ch R = 1,3351,291,291,291
BEGIN DESCRIPTION:
Mapping XS c6b38271
END DESCRIPTION:
XS GIS Cut Line= 3
      2906568.58      6948832.51      2906315.96      6949217.95
      2906344.61      6949496.63
#Sta/Elev= 30
  4542.3  394.96  4560.6  394.42  4575.7  395.81  4596.8  395.78  4611.9  397.65
  4627.0  397.67  4632.9  396.77  4648.0  397.27  4654.0  396.05  4720.4  395.58
  4748.2  394.24  4871.1  384.12  4987.7  377.35  4990.5  375.86  4994.7  373.66
  4996.5  371.67  4997.0  370.87  5002.0  370.87  5002.5  371.67  5014.0  374.12
  5030.3  373.89  5035.8  375.87  5039.0  377.04  5044.0  376.52  5090.7  379.50
  5120.8  386.35  5138.2  388.81  5151.0  387.58  5191.2  388.02  5283.3  396.78
#Mann=5,-1,0
  4542.3    0.16       0  4748.2    0.12       0  4996.5    0.07       0
  5002.5    0.12       0  5014.0    0.16       0
Bank Sta=4990.5,5035.8
Exp/Cntr=0.3,0.1

Type RM Length L Ch R = 1,3060,378,378,378
BEGIN DESCRIPTION:
Mapping XS 361b2600
END DESCRIPTION:
XS GIS Cut Line= 3
      2906233.67      6948761.47      2906035.75      6949120.84
      2906218.06      6949464.62
#Sta/Elev= 30
  4478.4  383.85  4491.9  383.38  4530.6  382.03  4545.0  380.37  4628.1  376.93
  4758.8  375.28  4774.9  373.77  4780.6  374.69  4795.6  372.12  4802.4  371.93
  4818.4  368.82  4824.9  373.67  4893.2  372.81  4942.4  374.89  4958.7  373.12
  4986.3  372.98  4995.2  372.01  5005.3  367.20  5005.8  366.40  5010.8  366.40
  5011.3  367.20  5017.7  372.12  5022.0  372.61  5040.5  373.35  5063.0  376.16
  5074.5  378.63  5178.6  393.64  5200.6  395.94  5238.9  398.19  5277.8  396.95
#Mann=6,-1,0
  4478.4    0.12       0  4491.9    0.16       0  4545.0    0.12       0
  5005.3    0.07       0  5011.3    0.12       0  5022.0    0.16       0
Bank Sta=4795.6,5017.7
Exp/Cntr=0.3,0.1

Type RM Length L Ch R = 1,2682,35,35,35
BEGIN DESCRIPTION:
Mapping XS 0defdb32
END DESCRIPTION:
XS GIS Cut Line= 3
      2905869.08      6948699.00      2905728.46      6949162.51
      2906160.36      6949474.72
#Sta/Elev= 30
  4520.6  383.06  4547.2  383.92  4552.4  385.26  4585.3  382.36  4590.6  383.61
  4618.2  381.23  4715.0  380.87  4793.2  385.09  4819.5  384.62  4826.1  383.39
  4831.3  384.71  4840.4  383.26  4859.0  375.41  4864.2  377.41  4871.7  374.79
  4891.9  371.07  4897.1  372.04  4916.9  368.37  4930.0  366.74  4983.7  366.23
  4984.2  365.43  4989.7  366.23  5025.4  366.43  5047.9  368.47  5074.9  366.24
  5104.3  368.62  5144.0  368.37  5341.1  376.00  5477.2  391.08  5537.9  395.77
#Mann=3,-1,0
  4520.6    0.16       0  4983.7    0.07       0  4989.7    0.16       0
Bank Sta=4916.9,5144
Exp/Cntr=0.3,0.1

Type RM Length L Ch R = 1,2647,74,74,74
BEGIN DESCRIPTION:
Mapping XS 0bd84fab
END DESCRIPTION:
XS GIS Cut Line= 3
      2905751.16      6949009.01      2905681.71      6949241.23
      2906040.96      6949513.92
#Sta/Elev= 30
  4824.5  385.09  4827.0  383.06  4832.3  384.34  4860.2  376.19  4865.4  378.17
  4872.5  375.86  4893.3  371.93  4898.5  373.85  4903.8  371.84  4922.2  368.17
  4931.6  366.54  4936.8  367.41  4945.6  366.33  4997.8  367.00  5029.1  366.33
  5036.1  367.29  5063.2  366.26  5063.7  365.46  5068.7  365.46  5069.2  366.26
  5164.6  366.52  5178.4  368.17  5264.5  371.95  5299.8  374.97  5328.9  374.15
  5343.5  374.62  5457.9  380.99  5478.7  381.39  5514.1  383.36  5517.9  384.21
#Mann=3,-1,0
  4824.5    0.16       0  5063.2    0.07       0  5069.2    0.16       0
Bank Sta=4922.2,5178.4
Exp/Cntr=0.3,0.1

Type RM Length L Ch R = 1,2573,13,13,13
BEGIN DESCRIPTION:
Mapping XS b994e40e
END DESCRIPTION:
XS GIS Cut Line= 5
      2905740.30      6948993.85      2905638.31      6949206.51
      2905644.82      6949341.06      2905762.01      6949380.12
      2906090.93      6949598.68
#Sta/Elev= 30
  4754.5  386.35  4780.9  385.18  4798.0  382.02  4803.6  382.94  4820.7  379.16
  4826.2  380.46  4843.3  377.43  4848.9  378.47  4866.0  375.34  4871.5  376.09
  4888.6  371.79  4894.2  372.56  4915.7  367.30  5026.6  366.25  5027.1  365.45
  5032.6  366.25  5109.9  366.48  5143.2  366.41  5177.9  367.41  5184.1  366.62
  5189.4  367.62  5209.6  366.31  5218.6  367.30  5298.4  371.72  5312.2  370.85
  5344.1  374.93  5359.3  375.77  5484.8  377.89  5593.0  383.78  5643.5  389.14
#Mann=7,-1,0
  4754.5    0.16       0  5026.6    0.07       0  5032.6    0.16       0
  5109.9    0.05       0  5143.2    0.16       0  5344.1    0.05       0
  5359.3    0.16       0
Bank Sta=4915.7,5218.6
Exp/Cntr=0.3,0.1

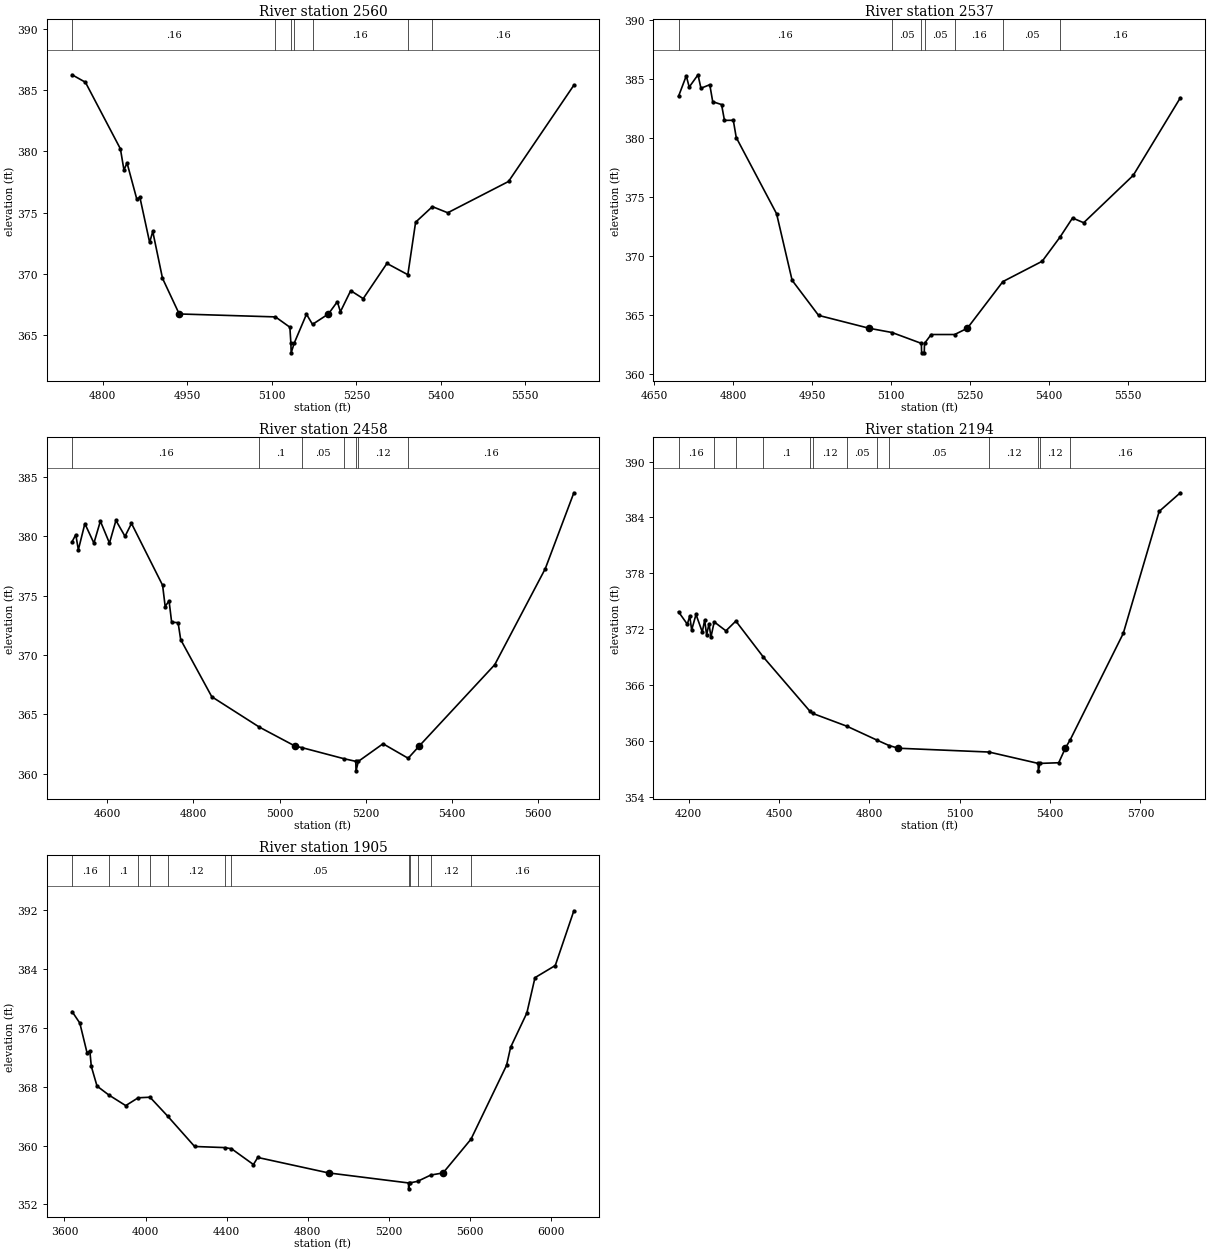
Type RM Length L Ch R = 1,2560,23,23,23
BEGIN DESCRIPTION:
Mapping XS fb590101
END DESCRIPTION:
XS GIS Cut Line= 5
      2905729.46      6948987.32      2905627.46      6949204.34
      2905620.95      6949347.57      2905740.31      6949393.14
      2906054.95      6949605.80
#Sta/Elev= 30
  4745.4  386.23  4769.1  385.62  4831.2  380.19  4837.5  378.47  4843.0  379.04
  4860.3  376.09  4865.8  376.24  4883.1  372.56  4888.6  373.46  4905.9  369.64
  4935.6  366.73  5106.4  366.49  5132.0  365.65  5133.8  364.36  5134.3  363.56
  5139.8  364.36  5161.5  366.71  5172.2  365.88  5200.4  366.73  5216.3  367.73
  5221.7  366.91  5240.0  368.63  5262.2  367.98  5304.3  370.85  5341.4  369.93
  5355.2  374.21  5385.0  375.48  5412.2  374.98  5520.1  377.53  5636.1  385.38
#Mann=7,-1,0
  4745.4    0.16       0  5106.4    0.05       0  5133.8    0.07       0
  5139.8    0.05       0  5172.2    0.16       0  5341.4    0.05       0
  5385.0    0.16       0
Bank Sta=4935.6,5200.4
Exp/Cntr=0.3,0.1

Type RM Length L Ch R = 1,2537,79,79,79
BEGIN DESCRIPTION:
Mapping XS da43ad20
END DESCRIPTION:
XS GIS Cut Line= 5
      2905727.27      6948948.30      2905603.59      6949195.66
      2905603.59      6949377.95      2905703.42      6949436.55
      2906024.57      6949638.35
#Sta/Elev= 30
  4696.5  383.53  4711.2  385.26  4716.8  384.31  4733.5  385.35  4739.1  384.21
  4755.9  384.51  4761.5  383.07  4778.3  382.83  4783.8  381.49  4800.6  381.50
  4806.2  380.04  4882.9  373.59  4912.4  367.96  4962.7  364.99  5058.8  363.90
  5102.4  363.54  5158.1  362.62  5158.6  361.82  5163.6  361.82  5164.1  362.62
  5176.8  363.37  5221.4  363.37  5245.5  363.90  5313.1  367.85  5387.8  369.57
  5421.8  371.62  5445.5  373.23  5466.7  372.83  5560.9  376.84  5650.4  383.40
#Mann=7,-1,0
  4696.5    0.16       0  5102.4    0.05       0  5158.1    0.07       0
  5164.1    0.05       0  5221.4    0.16       0  5313.1    0.05       0
  5421.8    0.16       0
Bank Sta=5058.8,5245.5
Exp/Cntr=0.3,0.1

Type RM Length L Ch R = 1,2458,264,264,264
BEGIN DESCRIPTION:
Mapping XS 3ff112c7
END DESCRIPTION:
XS GIS Cut Line= 4
      2905757.65      6948857.15      2905538.49      6949186.98
      2905555.85      6949453.91      2905996.42      6949692.64
#Sta/Elev= 30
  4518.5  379.55  4527.1  380.14  4533.1  378.87  4548.2  381.07  4569.2  379.43
  4584.2  381.28  4605.3  379.43  4620.3  381.34  4641.4  380.00  4656.4  381.09
  4728.6  375.88  4734.6  374.09  4743.6  374.57  4749.6  372.77  4764.6  372.73
  4770.6  371.30  4842.8  366.49  4953.3  363.93  5036.8  362.32  5051.5  362.21
  5149.7  361.27  5177.0  361.05  5177.5  360.25  5183.0  361.05  5240.2  362.53
  5298.5  361.31  5323.7  362.32  5499.5  369.19  5616.8  377.28  5683.1  383.67
#Mann=7,-1,0
  4518.5    0.16       0  4953.3     0.1       0  5051.5    0.05       0
  5149.7    0.12       0  5177.0    0.07       0  5183.0    0.12       0
  5298.5    0.16       0
Bank Sta=5036.8,5323.7
Exp/Cntr=0.3,0.1

Type RM Length L Ch R = 1,2194,289,289,289
BEGIN DESCRIPTION:
Mapping XS d4132e45
END DESCRIPTION:
XS GIS Cut Line= 4
      2905746.85      6948785.47      2905286.75      6949360.59
      2905560.19      6949742.54      2906010.74      6949833.51
#Sta/Elev= 30
  4166.4  373.85  4195.6  372.52  4203.6  373.40  4210.0  371.90  4224.4  373.57
  4245.2  371.69  4253.2  372.96  4259.6  371.37  4267.6  372.57  4274.0  371.14
  4284.8  372.77  4323.7  371.81  4356.7  372.86  4448.0  368.99  4602.8  363.16
  4611.2  362.94  4725.8  361.55  4826.7  360.04  4865.4  359.48  4896.3  359.19
  5197.3  358.78  5360.4  357.56  5360.9  356.76  5366.4  357.56  5428.6  357.63
  5450.4  359.19  5466.8  360.10  5642.8  371.53  5762.1  384.65  5832.3  386.65
#Mann=13,-1,0
  4166.4    0.16       0  4284.8     0.1       0  4356.7    0.16       0
  4448.0     0.1       0  4602.8    0.16       0  4611.2    0.12       0
  4725.8    0.05       0  4826.7    0.16       0  4865.4    0.05       0
  5197.3    0.12       0  5360.4    0.03       0  5366.4    0.12       0
  5466.8    0.16       0
Bank Sta=4896.3,5450.4
Exp/Cntr=0.3,0.1

Type RM Length L Ch R = 1,1905,0,0,0
BEGIN DESCRIPTION:
UNT 075 IN DRY CR WATERSHED 1.0
END DESCRIPTION:
XS GIS Cut Line= 4
      2905801.36      6948657.33      2905024.60      6949451.59
      2905319.74      6949885.62      2906156.56      6949861.31
#Sta/Elev= 30
  3637.9  378.19  3676.2  376.62  3711.5  372.61  3725.6  372.84  3732.6  370.76
  3760.9  368.07  3818.6  366.87  3902.3  365.42  3963.6  366.48  4021.9  366.56
  4108.7  364.00  4241.8  359.87  4389.3  359.72  4423.4  359.57  4531.7  357.42
  4553.0  358.38  4902.1  356.28  5296.0  354.92  5296.5  354.12  5302.0  354.92
  5340.7  355.14  5405.6  355.99  5466.2  356.28  5603.9  360.86  5779.2  370.89
  5799.2  373.34  5879.2  377.99  5919.3  382.79  6019.3  384.44  6110.9  391.87
#Mann=12,-1,0
  3637.9    0.16       0  3818.6     0.1       0  3963.6    0.16       0
  4021.9     0.1       0  4108.7    0.12       0  4389.3    0.16       0
  4423.4    0.05       0  5296.0    0.03       0  5302.0    0.05       0
  5340.7    0.16       0  5405.6    0.12       0  5603.9    0.16       0
Bank Sta=4902.1,5466.2
Exp/Cntr=0.3,0.1

Chan Stop Cuts=-1