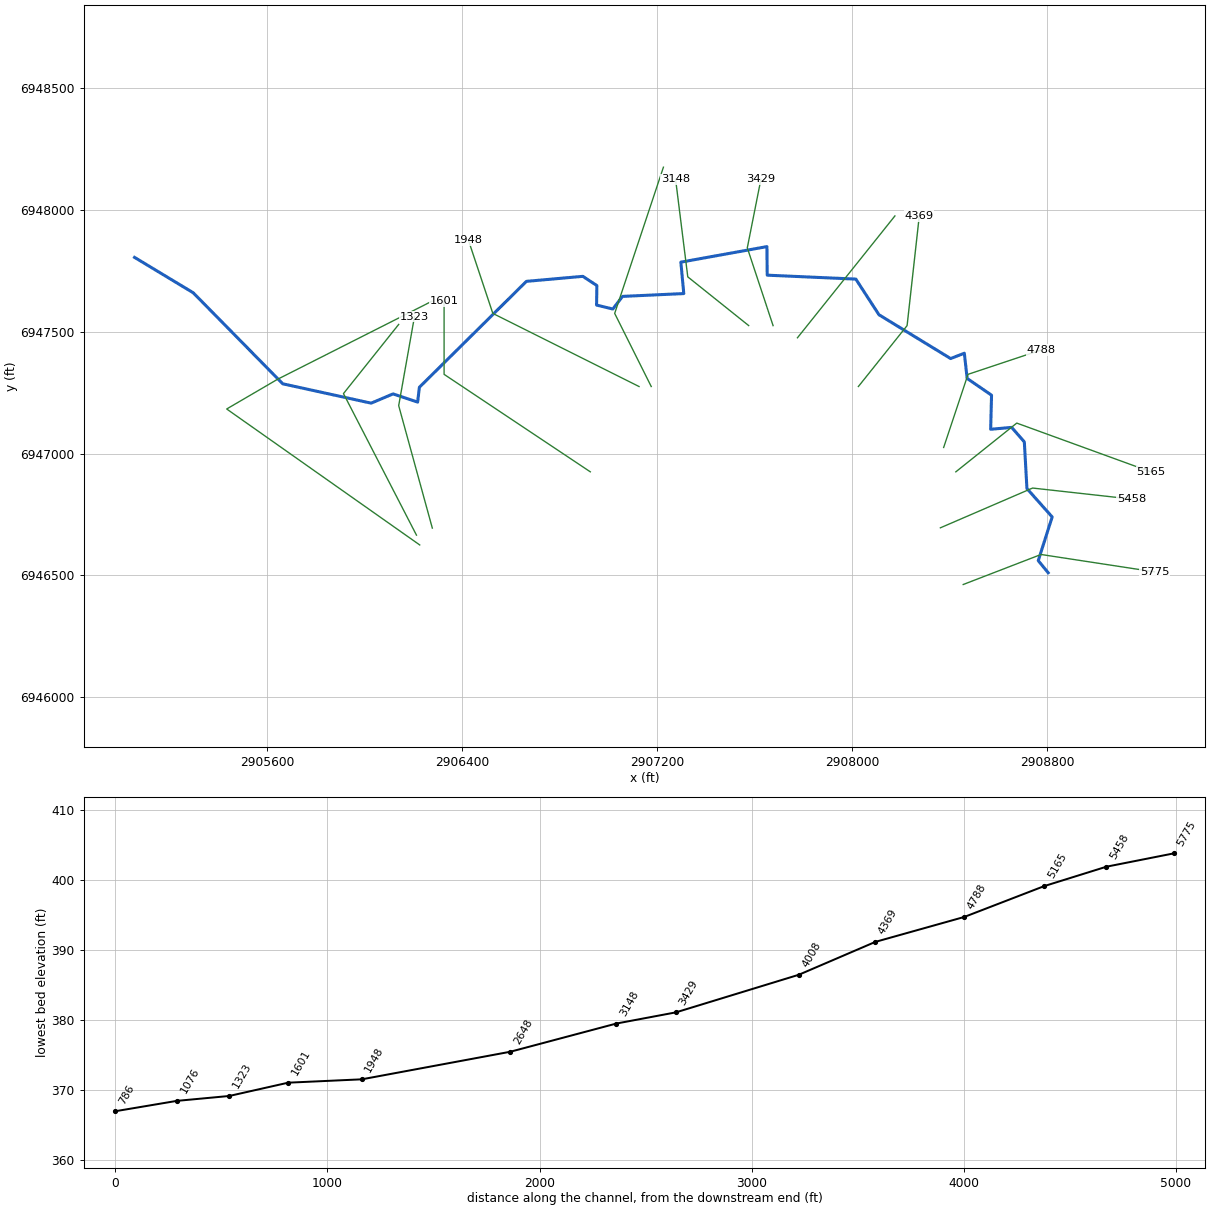
--- UNT 076 IN DRY CR WATERSHED.prj (project) ---

Proj Title=UNT 076 IN DRY CR WATERSHED Base Level Engineering
Current Plan=p01
Default Exp/Contr=0.3,0.1
English Units
Geom File=g01
Flow File=f01
Plan File=p01
BEGIN DESCRIPTION:
UNT 076 IN DRY CR WATERSHED
END DESCRIPTION:

--- UNT 076 IN DRY CR WATERSHED.p01 (plan) ---

Plan Title=Multiple Run
Short Identifier=Multiple
Geom File=g01
Flow File=f01
Subcritical Flow
K Sum by GR= 0
Std Step Tol= 0.01
Critical Tol= 0.01
Num of Std Step Trials= 20
Max Error Tol= 0.3
Flow Tol Ratio= 0.001
Split Flow NTrial= 30
Split Flow Tol= 0.02
Split Flow Ratio= 0.02
Log Output Level= 0
Friction Slope Method= 1
Unsteady Friction Slope Method= 2
Unsteady Bridges Friction Slope Method= 1
Parabolic Critical Depth
Global Vel Dist=  1 , 1 , 1
Global Log Level= 0
CheckData=True
Encroach Param= -1, 0, 0, 0
BEGIN DESCRIPTION:
Multiple Run
END DESCRIPTION:

--- UNT 076 IN DRY CR WATERSHED.f01 (steady flow) ---

Flow Title=Multiple
Number of Profiles=7
Profile Names=10-year,25-year,50-year,1pct_min,100-year,1pct_plu,500-year
River Rch & RM= UNT 076 IN DRY C,Reach-1,5775
     452     604     727     437     871    1738    1250
River Rch & RM= UNT 076 IN DRY C,Reach-1,1323
     580     786     956     580    1156    2307    1692
Boundary for River Rch & Prof#=UNT 076 IN DRY C,Reach-1,1
Up Type=0
Dn Type=3
Dn Slope=0.005
Boundary for River Rch & Prof#=UNT 076 IN DRY C,Reach-1,2
Up Type=0
Dn Type=3
Dn Slope=0.005
Boundary for River Rch & Prof#=UNT 076 IN DRY C,Reach-1,3
Up Type=0
Dn Type=3
Dn Slope=0.005
Boundary for River Rch & Prof#=UNT 076 IN DRY C,Reach-1,4
Up Type=0
Dn Type=3
Dn Slope=0.005
Boundary for River Rch & Prof#=UNT 076 IN DRY C,Reach-1,5
Up Type=0
Dn Type=3
Dn Slope=0.005
Boundary for River Rch & Prof#=UNT 076 IN DRY C,Reach-1,6
Up Type=0
Dn Type=3
Dn Slope=0.005
Boundary for River Rch & Prof#=UNT 076 IN DRY C,Reach-1,7
Up Type=0
Dn Type=3
Dn Slope=0.005

--- UNT 076 IN DRY CR WATERSHED.g01 (geometry) ---

Geom Title=Existing Conditions

River Reach=UNT 076 IN DRY C,Reach-1
Reach XY= 30
      2908803.87      6946510.94      2908763.21      6946560.65
      2908820.31      6946739.86      2908716.75      6946856.36
      2908706.05      6947047.67      2908654.17      6947107.32
      2908567.89      6947099.62      2908571.50      6947239.46
      2908471.49      6947308.11      2908459.85      6947411.63
      2908403.59      6947389.77      2908109.62      6947569.50
      2908014.58      6947715.83      2907650.89      6947731.91
      2907649.78      6947849.14      2907296.63      6947785.31
      2907308.53      6947656.41      2907057.33      6947644.84
      2907017.40      6947593.06      2906950.73      6947609.19
      2906951.91      6947689.29      2906894.44      6947727.12
      2906662.71      6947706.54      2906223.58      6947271.95
      2906216.45      6947211.16      2906115.58      6947244.72
      2906025.60      6947206.78      2905662.97      6947286.17
      2905295.56      6947659.74      2905054.72      6947804.96

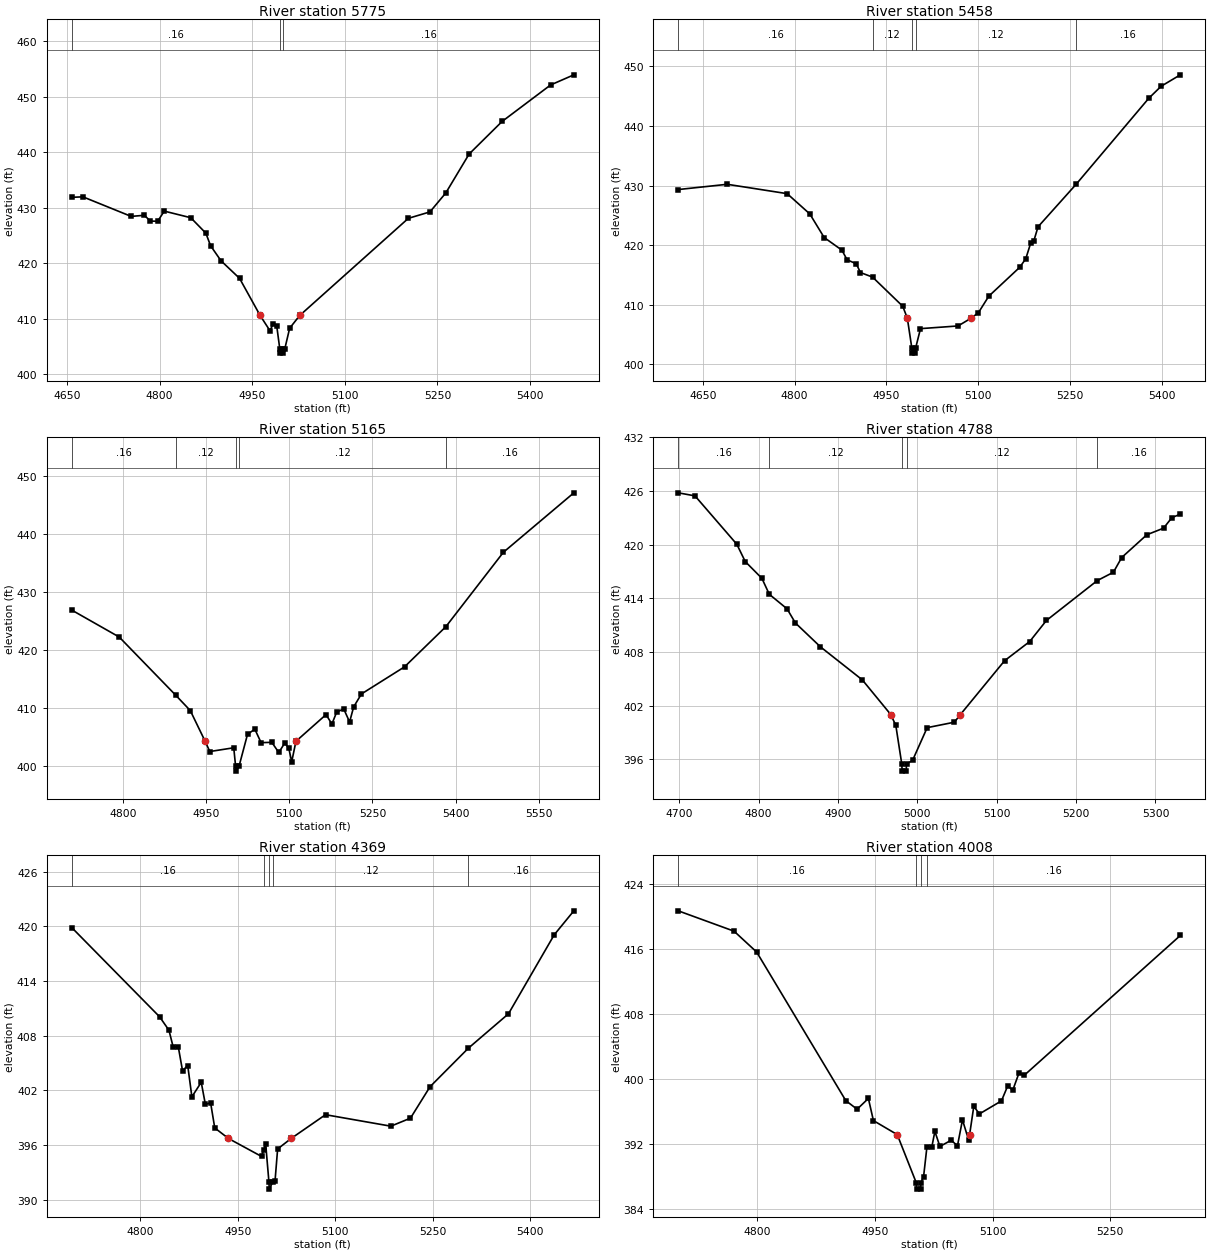
Type RM Length L Ch R = 1,5775,317,317,317
BEGIN DESCRIPTION:
UNT 076 IN DRY CR WATERSHED 11.0
END DESCRIPTION:
XS GIS Cut Line= 3
      2908455.27      6946462.64      2908774.51      6946585.87
      2909239.90      6946514.72
#Sta/Elev= 30
  4657.8  431.85  4675.9  431.93  4754.0  428.41  4775.4  428.61  4785.0  427.56
  4796.9  427.54  4807.6  429.36  4850.5  428.17  4874.9  425.39  4882.6  423.12
  4899.5  420.41  4929.5  417.25  4962.8  410.56  4978.7  407.82  4984.1  409.07
  4989.8  408.58  4994.6  404.58  4995.1  403.78  5000.1  403.78  5000.6  404.58
  5002.8  404.58  5010.6  408.26  5026.9  410.56  5202.8  428.06  5237.8  429.22
  5263.5  432.64  5301.2  439.64  5354.6  445.51  5433.1  452.08  5470.8  453.91
#Mann=3,-1,0
  4657.8    0.16       0  4994.6    0.07       0  5000.6    0.16       0
Bank Sta=4962.8,5026.9
Exp/Cntr=0.3,0.1

Type RM Length L Ch R = 1,5458,293,293,293
BEGIN DESCRIPTION:
Mapping XS d47f1cbe
END DESCRIPTION:
XS GIS Cut Line= 3
      2908361.47      6946695.26      2908739.95      6946858.46
      2909146.19      6946813.32
#Sta/Elev= 30
  4609.7  429.33  4689.8  430.21  4787.8  428.64  4824.8  425.24  4848.3  421.28
  4877.3  419.16  4885.8  417.54  4900.8  416.87  4907.6  415.40  4927.4  414.64
  4976.8  409.74  4984.3  407.73  4991.7  402.68  4992.2  401.88  4997.2  401.88
  4997.7  402.68  5005.8  405.99  5067.2  406.44  5088.3  407.73  5100.4  408.65
  5117.5  411.44  5167.8  416.26  5177.9  417.71  5186.0  420.35  5191.0  420.69
  5198.0  423.08  5260.4  430.23  5379.1  444.65  5399.2  446.66  5430.6  448.58
#Mann=5,-1,0
  4609.7    0.16       0  4927.4    0.12       0  4991.7    0.07       0
  4997.7    0.12       0  5260.4    0.16       0
Bank Sta=4984.3,5088.3
Exp/Cntr=0.3,0.1

Type RM Length L Ch R = 1,5165,377,377,377
BEGIN DESCRIPTION:
UNT 076 IN DRY CR WATERSHED 10.0
END DESCRIPTION:
XS GIS Cut Line= 3
      2908425.02      6946925.02      2908675.00      6947125.00
      2909225.04      6946924.99
#Sta/Elev= 30
  4707.7  426.89  4793.3  422.24  4895.0  412.22  4921.4  409.56  4948.2  404.26
  4956.6  402.49  4999.8  403.14  5003.2  399.91  5003.7  399.11  5009.2  399.91
  5024.6  405.45  5037.8  406.35  5049.1  404.02  5068.4  404.08  5081.0  402.33
  5091.7  403.94  5099.0  403.09  5104.3  400.72  5112.0  404.26  5166.2  408.86
  5176.8  407.24  5185.4  409.29  5198.1  409.85  5208.7  407.59  5216.0  410.18
  5230.0  412.42  5307.8  417.10  5382.3  424.03  5486.0  436.86  5613.1  447.12
#Mann=5,-1,0
  4707.7    0.16       0  4895.0    0.12       0  5003.2    0.07       0
  5009.2    0.12       0  5382.3    0.16       0
Bank Sta=4948.2,5112
Exp/Cntr=0.3,0.1

Type RM Length L Ch R = 1,4788,419,419,419
BEGIN DESCRIPTION:
UNT 076 IN DRY CR WATERSHED 9.0
END DESCRIPTION:
XS GIS Cut Line= 3
      2908374.99      6947024.97      2908475.00      6947325.00
      2908775.01      6947425.00
#Sta/Elev= 30
  4698.8  425.81  4719.9  425.47  4772.6  420.06  4783.2  418.13  4804.2  416.25
  4813.5  414.47  4835.9  412.84  4846.4  411.26  4878.0  408.59  4930.7  404.90
  4966.5  401.03  4972.9  399.81  4980.4  395.50  4980.9  394.70  4985.9  394.70
  4986.4  395.50  4994.0  395.90  5012.4  399.56  5046.7  400.17  5054.3  401.03
  5109.9  407.04  5141.6  409.19  5162.6  411.54  5226.7  416.00  5247.0  416.93
  5257.5  418.58  5289.1  421.12  5310.2  421.86  5320.7  423.04  5331.3  423.42
#Mann=5,-1,0
  4698.8    0.16       0  4813.5    0.12       0  4980.4    0.07       0
  4986.4    0.12       0  5226.7    0.16       0
Bank Sta=4966.5,5054.3
Exp/Cntr=0.3,0.1

Type RM Length L Ch R = 1,4369,361,361,361
BEGIN DESCRIPTION:
UNT 076 IN DRY CR WATERSHED 8.0
END DESCRIPTION:
XS GIS Cut Line= 3
      2908025.02      6947275.02      2908225.00      6947525.00
      2908275.00      6947975.00
#Sta/Elev= 30
  4694.5  419.85  4829.7  410.06  4844.1  408.58  4850.5  406.77  4858.6  406.71
  4865.0  404.14  4873.0  404.71  4879.4  401.27  4893.8  402.87  4900.2  400.43
  4908.2  400.63  4914.6  397.86  4935.7  396.70  4986.6  394.73  4989.8  395.42
  4993.0  396.10  4998.0  391.94  4998.5  391.14  5004.0  391.94  5007.4  392.03
  5011.4  395.55  5032.2  396.70  5085.1  399.31  5185.7  398.05  5215.9  398.93
  5246.0  402.38  5305.0  406.61  5366.8  410.39  5437.2  419.06  5467.4  421.69
#Mann=5,-1,0
  4694.5    0.16       0  4989.8    0.12       0  4998.0    0.07       0
  5004.0    0.12       0  5305.0    0.16       0
Bank Sta=4935.7,5032.2
Exp/Cntr=0.3,0.1

Type RM Length L Ch R = 1,4008,579,579,579
BEGIN DESCRIPTION:
UNT 076 IN DRY CR WATERSHED 7.0
END DESCRIPTION:
XS GIS Cut Line= 3
      2907775.02      6947475.03      2907975.00      6947725.00
      2908175.01      6947975.02
#Sta/Elev= 30
  4699.0  420.75  4770.2  418.24  4799.0  415.67  4912.7  397.35  4927.1  396.29
  4941.5  397.62  4947.9  394.89  4978.3  393.16  5002.5  387.24  5003.0  386.44
  5008.0  386.44  5008.5  387.24  5011.9  387.99  5016.1  391.59  5022.3  391.59
  5026.3  393.56  5032.7  391.70  5047.1  392.47  5055.1  391.78  5061.5  394.98
  5069.5  392.44  5070.6  393.16  5075.9  396.63  5083.2  395.72  5111.2  397.32
  5119.2  399.17  5125.6  398.63  5133.6  400.76  5140.0  400.45  5339.3  417.71
#Mann=4,-1,0
  4699.0    0.16       0  5002.5    0.07       0  5008.5    0.16       0
  5016.1    0.16       0
Bank Sta=4978.3,5070.6
Exp/Cntr=0.3,0.1

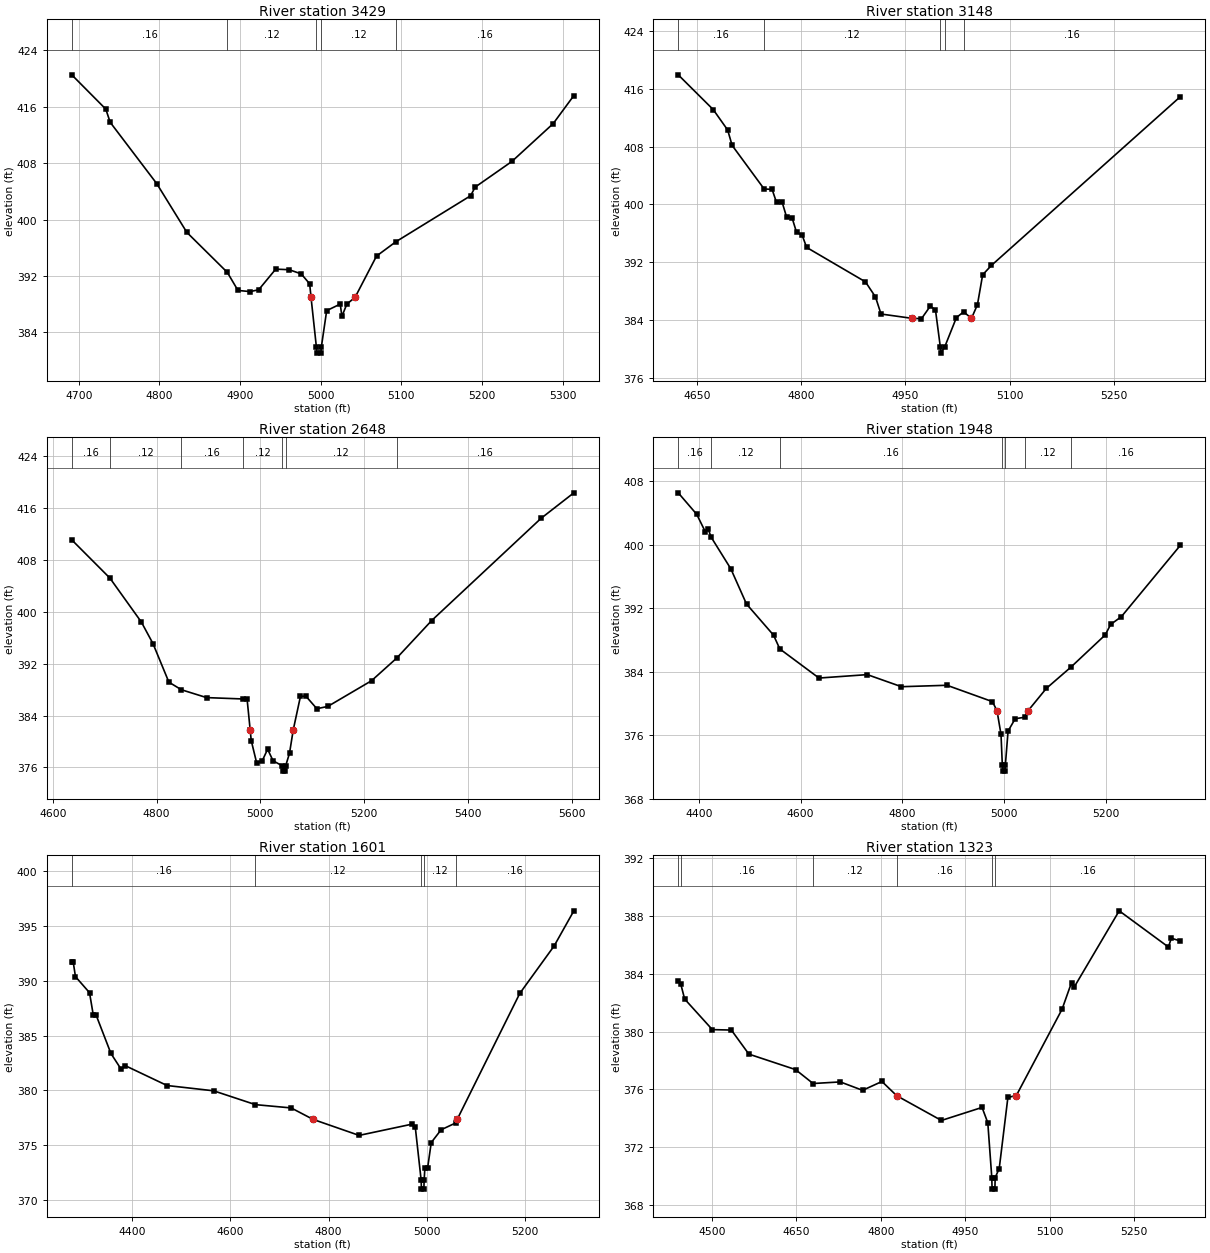
Type RM Length L Ch R = 1,3429,281,281,281
BEGIN DESCRIPTION:
UNT 076 IN DRY CR WATERSHED 6.0
END DESCRIPTION:
XS GIS Cut Line= 3
      2907675.01      6947524.96      2907569.27      6947844.09
      2907625.00      6948125.02
#Sta/Elev= 30
  4691.4  420.50  4733.6  415.64  4739.0  413.78  4796.8  405.08  4834.1  398.18
  4884.3  392.51  4897.5  389.95  4912.7  389.79  4923.2  390.05  4944.3  392.97
  4960.9  392.89  4975.9  392.30  4986.4  390.89  4988.1  388.97  4994.8  381.87
  4995.3  381.07  5000.3  381.07  5000.8  381.87  5007.5  387.09  5024.3  388.02
  5026.4  386.28  5032.5  388.02  5042.7  388.97  5069.3  394.82  5093.3  396.85
  5186.0  403.37  5191.6  404.59  5237.2  408.23  5288.4  413.59  5314.0  417.56
#Mann=5,-1,0
  4691.4    0.16       0  4884.3    0.12       0  4994.8    0.07       0
  5000.8    0.12       0  5093.3    0.16       0
Bank Sta=4988.1,5042.7
Exp/Cntr=0.3,0.1

Type RM Length L Ch R = 1,3148,500,500,500
BEGIN DESCRIPTION:
UNT 076 IN DRY CR WATERSHED 5.0
END DESCRIPTION:
XS GIS Cut Line= 3
      2907574.97      6947525.02      2907325.00      6947725.00
      2907275.00      6948124.97
#Sta/Elev= 30
  4622.7  417.90  4673.1  413.10  4693.9  410.28  4700.3  408.16  4746.4  402.14
  4757.9  402.08  4764.3  400.27  4772.3  400.33  4778.7  398.29  4786.7  398.14
  4793.1  396.16  4801.2  395.76  4807.6  394.07  4892.4  389.31  4906.8  387.23
  4914.8  384.87  4959.7  384.27  4973.1  384.23  4985.7  385.95  4993.2  385.45
  5000.3  380.27  5000.8  379.47  5006.3  380.27  5023.4  384.38  5033.8  385.17
  5045.1  384.27  5053.7  386.17  5061.2  390.29  5073.8  391.58  5345.9  414.88
#Mann=5,-1,0
  4622.7    0.16       0  4746.4    0.12       0  5000.3    0.07       0
  5006.3    0.12       0  5033.8    0.16       0
Bank Sta=4959.7,5045.1
Exp/Cntr=0.3,0.1

Type RM Length L Ch R = 1,2648,700,700,700
BEGIN DESCRIPTION:
UNT 076 IN DRY CR WATERSHED 4.0
END DESCRIPTION:
XS GIS Cut Line= 3
      2907174.99      6947275.02      2907025.00      6947575.00
      2907224.99      6948174.96
#Sta/Elev= 30
  4636.6  411.08  4710.1  405.19  4770.7  398.42  4793.1  395.10  4823.8  389.15
  4848.0  387.98  4896.5  386.77  4966.9  386.56  4974.6  386.49  4980.5  381.79
  4982.5  380.16  4993.1  376.67  5003.6  377.01  5014.1  378.81  5024.7  377.03
  5042.8  376.24  5043.3  375.44  5048.3  375.44  5048.8  376.24  5056.3  378.19
  5063.5  381.79  5077.4  386.96  5087.9  386.99  5109.0  385.06  5130.1  385.41
  5214.4  389.37  5262.8  392.85  5330.4  398.65  5541.2  414.40  5604.4  418.33
#Mann=7,-1,0
  4636.6    0.16       0  4710.1    0.12       0  4848.0    0.16       0
  4966.9    0.12       0  5042.8    0.07       0  5048.8    0.12       0
  5262.8    0.16       0
Bank Sta=4980.5,5063.5
Exp/Cntr=0.3,0.1

Type RM Length L Ch R = 1,1948,347,347,347
BEGIN DESCRIPTION:
UNT 076 IN DRY CR WATERSHED 3.0
END DESCRIPTION:
XS GIS Cut Line= 3
      2907124.99      6947275.01      2906525.00      6947575.00
      2906425.01      6947874.97
#Sta/Elev= 30
  4359.4  406.51  4395.7  403.81  4412.5  401.63  4418.1  401.99  4424.0  400.94
  4462.8  396.95  4493.6  392.52  4546.7  388.61  4559.1  386.87  4636.1  383.21
  4731.1  383.64  4798.2  382.12  4887.7  382.30  4977.1  380.24  4986.1  379.08
  4993.9  376.13  4996.5  372.30  4997.0  371.50  5002.0  371.50  5002.5  372.30
  5007.8  376.54  5021.8  378.09  5040.5  378.28  5046.9  379.08  5082.9  381.90
  5131.3  384.58  5198.9  388.64  5209.4  389.95  5230.5  390.93  5346.4  399.90
#Mann=7,-1,0
  4359.4    0.16       0  4424.0    0.12       0  4559.1    0.16       0
  4996.5    0.07       0  5002.5    0.16       0  5040.5    0.12       0
  5131.3    0.16       0
Bank Sta=4986.1,5046.9
Exp/Cntr=0.3,0.1

Type RM Length L Ch R = 1,1601,278,278,278
BEGIN DESCRIPTION:
UNT 076 IN DRY CR WATERSHED 2.0
END DESCRIPTION:
XS GIS Cut Line= 3
      2906925.00      6946925.00      2906325.00      6947325.00
      2906325.00      6947624.99
#Sta/Elev= 30
  4277.5  391.67  4280.5  391.67  4285.0  390.36  4313.6  388.90  4321.1  386.90
  4327.1  386.85  4357.1  383.37  4378.2  381.91  4385.7  382.27  4471.3  380.45
  4565.9  379.97  4651.0  378.71  4723.7  378.41  4768.1  377.37  4861.9  375.91
  4970.1  376.94  4976.1  376.67  4988.1  371.82  4988.6  371.02  4993.6  371.02
  4994.1  371.82  4995.6  372.92  5001.1  372.92  5008.6  375.26  5028.6  376.42
  5058.1  377.04  5061.4  377.37  5188.6  388.83  5258.6  393.16  5298.6  396.35
#Mann=5,-1,0
  4277.5    0.16       0  4651.0    0.12       0  4988.1    0.07       0
  4994.1    0.12       0  5058.1    0.16       0
Bank Sta=4768.1,5061.4
Exp/Cntr=0.3,0.1

Type RM Length L Ch R = 1,1323,247,247,247
BEGIN DESCRIPTION:
Mapping XS 927665d2
END DESCRIPTION:
XS GIS Cut Line= 3
      2906276.71      6946693.99      2906138.70      6947196.56
      2906203.47      6947561.89
#Sta/Elev= 30
  4440.0  383.48  4444.4  383.29  4451.4  382.24  4500.6  380.13  4534.4  380.10
  4565.5  378.44  4648.5  377.37  4679.6  376.41  4728.0  376.52  4767.6  375.94
  4802.0  376.55  4827.9  375.58  4829.1  375.55  4907.7  373.86  4979.9  374.76
  4990.1  373.70  4997.2  369.92  4997.7  369.12  5002.7  369.12  5003.2  369.92
  5010.4  370.54  5025.8  375.45  5040.8  375.58  5122.1  381.54  5138.9  383.38
  5144.0  383.09  5223.6  388.33  5311.1  385.83  5316.2  386.44  5332.2  386.25
#Mann=6,-1,0
  4440.0    0.12       0  4444.4    0.16       0  4679.6    0.12       0
  4829.1    0.16       0  4997.2    0.07       0  5003.2    0.16       0
Bank Sta=4827.9,5040.8
Exp/Cntr=0.3,0.1

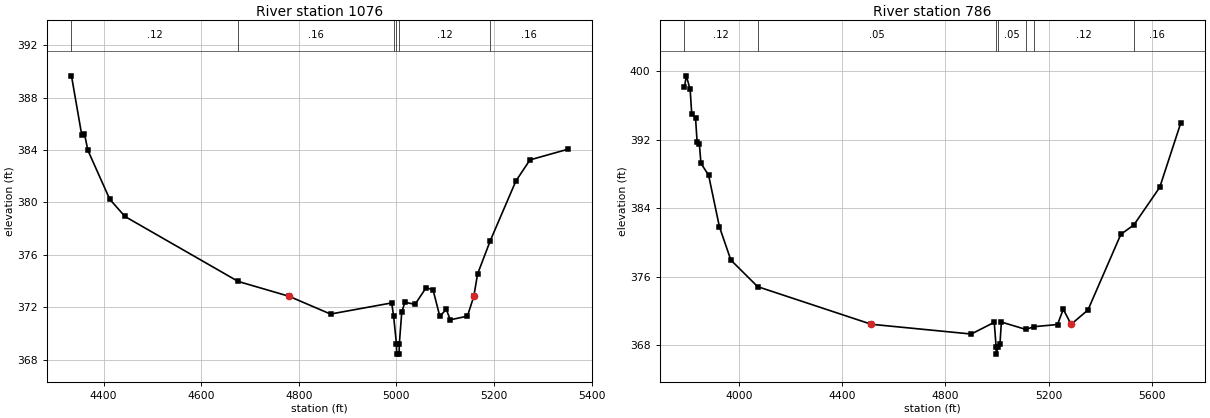
Type RM Length L Ch R = 1,1076,290,290,290
BEGIN DESCRIPTION:
Mapping XS 4e27a158
END DESCRIPTION:
XS GIS Cut Line= 3
      2906211.64      6946665.26      2905912.14      6947246.04
      2906138.68      6947529.86
#Sta/Elev= 30
  4334.3  389.67  4355.3  385.16  4360.9  385.26  4367.8  383.99  4412.8  380.24
  4443.9  378.93  4675.8  373.97  4779.8  372.84  4865.0  371.48  4990.3  372.33
  4994.3  371.32  5000.0  369.22  5000.5  368.42  5005.5  368.42  5006.0  369.22
  5011.0  371.64  5017.4  372.38  5038.2  372.22  5060.6  373.48  5075.0  373.34
  5088.8  371.32  5102.3  371.83  5110.3  371.04  5145.5  371.32  5158.6  372.84
  5166.3  374.54  5192.3  377.08  5244.8  381.64  5273.6  383.25  5350.9  384.06
#Mann=6,-1,0
  4334.3    0.12       0  4675.8    0.16       0  4994.3    0.12       0
  5000.0    0.07       0  5006.0    0.12       0  5192.3    0.16       0
Bank Sta=4779.8,5158.6
Exp/Cntr=0.3,0.1

Type RM Length L Ch R = 1,786,0,0,0
BEGIN DESCRIPTION:
UNT 076 IN DRY CR WATERSHED 1.0
END DESCRIPTION:
XS GIS Cut Line= 4
      2906225.00      6946625.00      2905432.88      6947182.84
      2905641.32      6947304.57      2906275.01      6947625.00
#Sta/Elev= 30
  3789.8  398.12  3797.2  399.48  3812.0  397.90  3818.1  395.07  3832.9  394.58
  3839.0  391.73  3847.7  391.55  3853.8  389.25  3883.4  387.87  3925.3  381.83
  3969.6  377.94  4073.2  374.83  4513.3  370.43  4900.0  369.29  4988.9  370.66
  4996.2  367.74  4996.7  366.94  5002.2  367.74  5010.9  368.07  5016.5  370.69
  5111.2  369.83  5143.2  370.15  5233.7  370.40  5256.0  372.18  5286.5  370.43
  5351.5  372.10  5478.9  380.95  5529.3  382.05  5629.3  386.44  5710.1  393.91
#Mann=7,-1,0
  3789.8    0.12       0  4073.2    0.05       0  4996.2    0.03       0
  5002.2    0.05       0  5111.2    0.16       0  5143.2    0.12       0
  5529.3    0.16       0
Bank Sta=4513.3,5286.5
Exp/Cntr=0.3,0.1

Chan Stop Cuts=-1