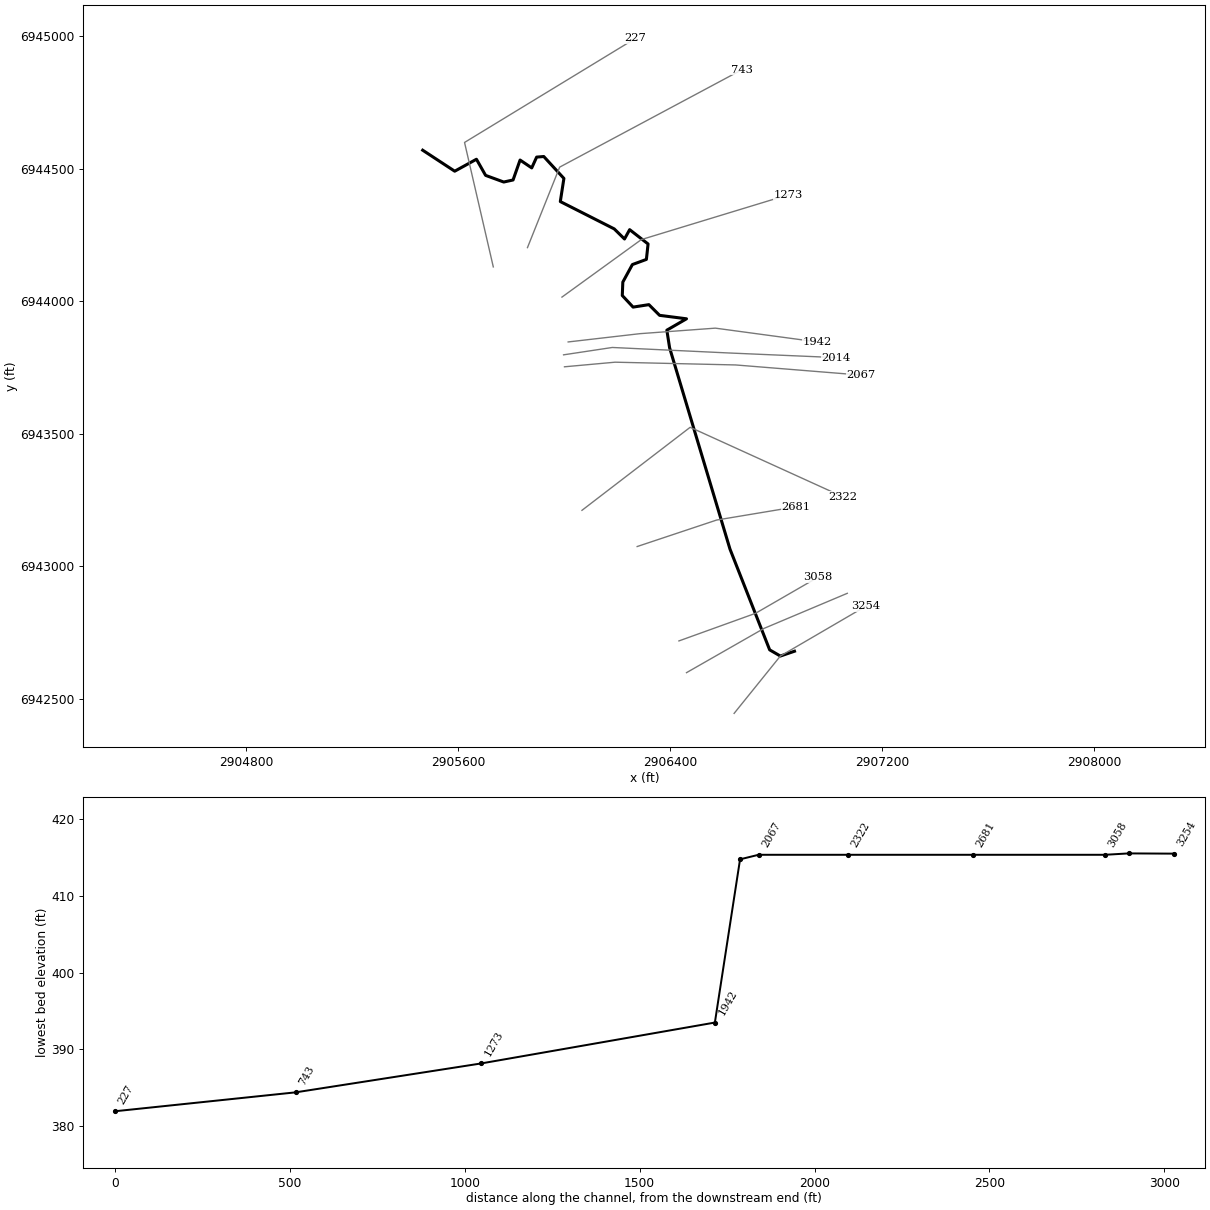
--- UNT 078 IN DRY CR WATERSHED.prj (project) ---

Proj Title=UNT 078 IN DRY CR WATERSHED Base Level Engineering
Current Plan=p01
Default Exp/Contr=0.3,0.1
English Units
Geom File=g01
Flow File=f01
Plan File=p01
BEGIN DESCRIPTION:
UNT 078 IN DRY CR WATERSHED
END DESCRIPTION:

--- UNT 078 IN DRY CR WATERSHED.p01 (plan) ---

Plan Title=Multiple Run
Short Identifier=Multiple
Geom File=g01
Flow File=f01
Subcritical Flow
K Sum by GR= 0
Std Step Tol= 0.01
Critical Tol= 0.01
Num of Std Step Trials= 20
Max Error Tol= 0.3
Flow Tol Ratio= 0.001
Split Flow NTrial= 30
Split Flow Tol= 0.02
Split Flow Ratio= 0.02
Log Output Level= 0
Friction Slope Method= 1
Unsteady Friction Slope Method= 2
Unsteady Bridges Friction Slope Method= 1
Parabolic Critical Depth
Global Vel Dist=  1 , 1 , 1
Global Log Level= 0
CheckData=True
Encroach Param= -1, 0, 0, 0
BEGIN DESCRIPTION:
Multiple Run
END DESCRIPTION:

--- UNT 078 IN DRY CR WATERSHED.f01 (steady flow) ---

Flow Title=Multiple
Number of Profiles=7
Profile Names=10-year,25-year,50-year,1pct_min,100-year,1pct_plu,500-year
River Rch & RM= UNT 078 IN DRY C,Reach-1,3254
     386     508     607     361     721    1438    1017
Boundary for River Rch & Prof#=UNT 078 IN DRY C,Reach-1,1
Up Type=0
Dn Type=3
Dn Slope=0.005
Boundary for River Rch & Prof#=UNT 078 IN DRY C,Reach-1,2
Up Type=0
Dn Type=3
Dn Slope=0.005
Boundary for River Rch & Prof#=UNT 078 IN DRY C,Reach-1,3
Up Type=0
Dn Type=3
Dn Slope=0.005
Boundary for River Rch & Prof#=UNT 078 IN DRY C,Reach-1,4
Up Type=0
Dn Type=3
Dn Slope=0.005
Boundary for River Rch & Prof#=UNT 078 IN DRY C,Reach-1,5
Up Type=0
Dn Type=3
Dn Slope=0.005
Boundary for River Rch & Prof#=UNT 078 IN DRY C,Reach-1,6
Up Type=0
Dn Type=3
Dn Slope=0.005
Boundary for River Rch & Prof#=UNT 078 IN DRY C,Reach-1,7
Up Type=0
Dn Type=3
Dn Slope=0.005

--- UNT 078 IN DRY CR WATERSHED.g01 (geometry) ---

Geom Title=Existing Conditions

River Reach=UNT 078 IN DRY C,Reach-1
Reach XY= 30
      2906868.74      6942679.92      2906815.35      6942661.70
      2906774.99      6942685.13      2906625.25      6943065.34
      2906397.39      6943825.11      2906386.97      6943891.51
      2906461.19      6943934.48      2906359.63      6943947.50
      2906319.26      6943987.87      2906259.53      6943978.59
      2906218.83      6944022.30      2906220.87      6944073.00
      2906256.90      6944139.15      2906309.80      6944158.60
      2906316.13      6944216.83      2906246.65      6944270.89
      2906227.19      6944235.63      2906188.40      6944273.79
      2905984.94      6944376.90      2905998.46      6944464.20
      2905922.54      6944546.88      2905895.63      6944544.70
      2905877.08      6944503.91      2905833.11      6944533.61
      2905806.63      6944458.34      2905771.46      6944450.63
      2905702.96      6944475.75      2905668.47      6944536.62
      2905586.43      6944491.50      2905465.59      6944570.71

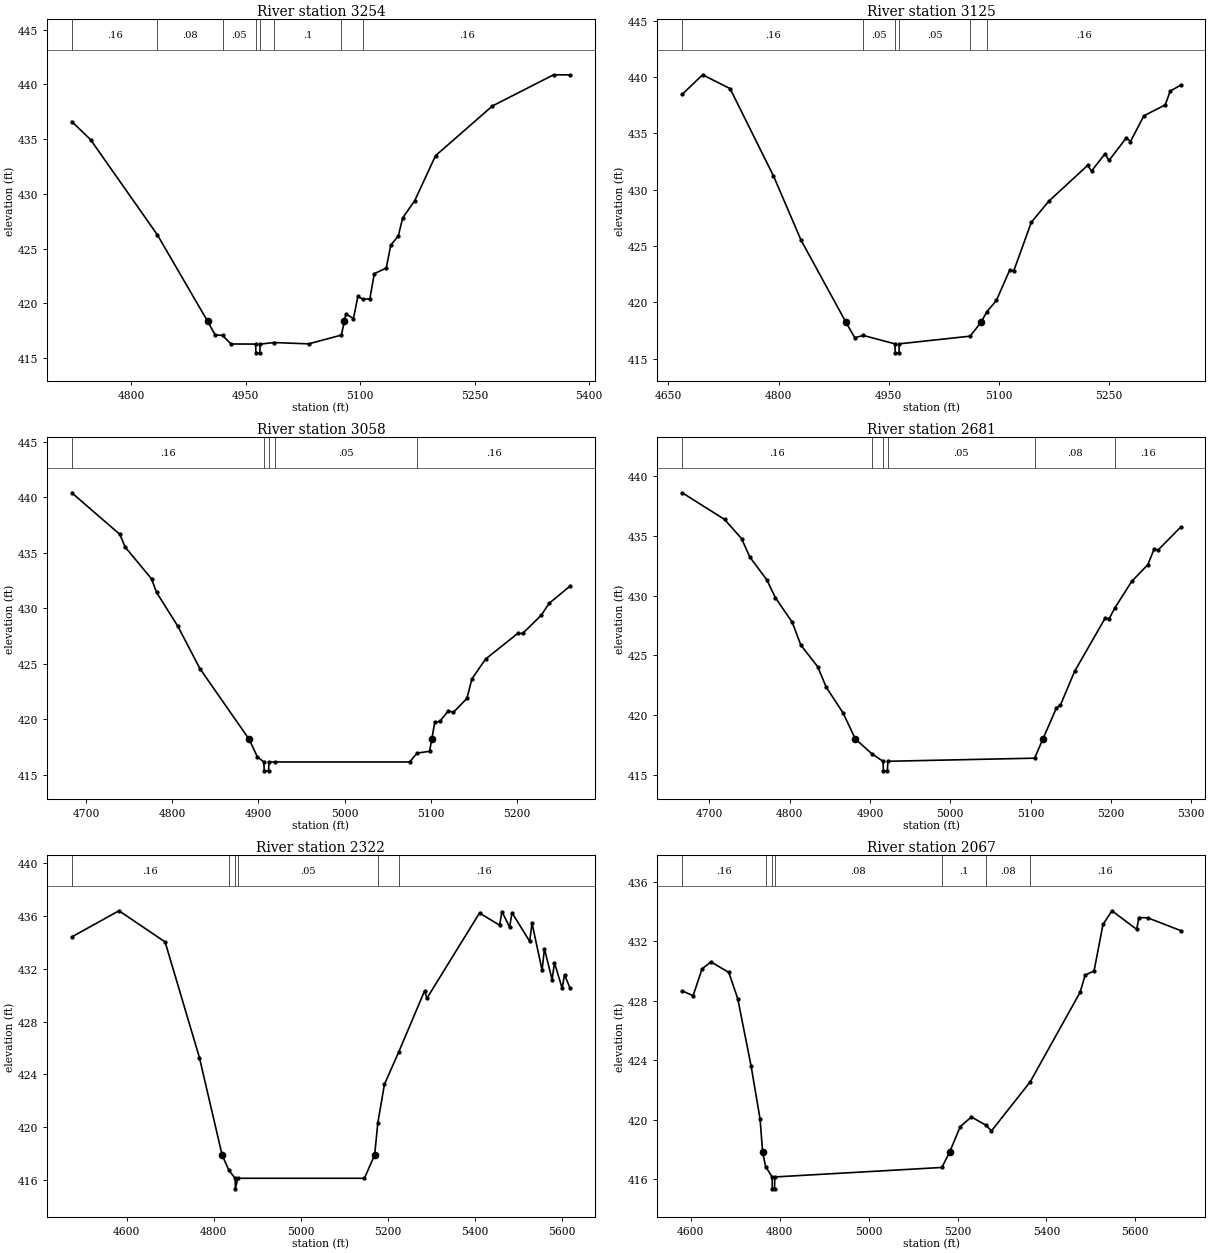
Type RM Length L Ch R = 1,3254,129,129,129
BEGIN DESCRIPTION:
UNT 078 IN DRY CR WATERSHED 6.0
END DESCRIPTION:
XS GIS Cut Line= 3
      2906640.91      6942445.36      2906815.35      6942661.70
      2907139.10      6942850.55
#Sta/Elev= 30
  4722.1  436.61  4746.7  434.96  4834.0  426.29  4900.0  418.38  4909.9  417.13
  4919.6  417.08  4930.7  416.30  4962.9  416.29  4963.4  415.49  4968.4  415.49
  4968.9  416.29  4987.3  416.43  5032.4  416.31  5075.3  417.11  5079.2  418.38
  5081.2  419.05  5091.1  418.62  5096.9  420.64  5103.8  420.37  5112.6  420.43
  5118.4  422.72  5134.1  423.23  5139.9  425.31  5149.9  426.17  5155.6  427.81
  5171.4  429.39  5198.6  433.49  5273.1  438.03  5353.3  440.88  5374.8  440.87
#Mann=8,-1,0
  4722.1    0.16       0  4834.0    0.08       0  4919.6    0.05       0
  4962.9    0.07       0  4968.9    0.05       0  4987.3     0.1       0
  5075.3    0.08       0  5103.8    0.16       0
Bank Sta=4900,5079.2
Exp/Cntr=0.3,0.1

Type RM Length L Ch R = 1,3125,67,67,67
BEGIN DESCRIPTION:
Mapping XS 354991d5
END DESCRIPTION:
XS GIS Cut Line= 3
      2906461.21      6942599.00      2906752.89      6942765.67
      2907068.00      6942898.48
#Sta/Elev= 30
  4669.0  438.48  4696.7  440.21  4734.1  438.98  4793.1  431.23  4830.6  425.53
  4891.8  418.22  4903.7  416.87  4915.6  417.06  4958.3  416.32  4958.8  415.52
  4963.8  415.52  4964.3  416.32  5060.7  417.00  5075.3  418.22  5083.7  419.19
  5096.4  420.17  5114.7  422.89  5120.1  422.81  5143.9  427.11  5167.6  428.98
  5220.5  432.16  5225.9  431.66  5244.2  433.20  5249.6  432.60  5273.3  434.62
  5278.8  434.28  5297.1  436.57  5326.2  437.54  5332.8  438.76  5346.9  439.28
#Mann=6,-1,0
  4669.0    0.16       0  4915.6    0.05       0  4958.3   0.033       0
  4964.3    0.05       0  5060.7    0.08       0  5083.7    0.16       0
Bank Sta=4891.8,5075.3
Exp/Cntr=0.3,0.1

Type RM Length L Ch R = 1,3058,377,377,377
BEGIN DESCRIPTION:
Mapping XS ef0f43fe
END DESCRIPTION:
XS GIS Cut Line= 3
      2906432.55      6942718.78      2906721.64      6942822.96
      2906956.04      6942958.39
#Sta/Elev= 30
  4683.5  440.40  4739.3  436.65  4745.3  435.52  4776.0  432.65  4781.8  431.43
  4806.7  428.35  4832.1  424.56  4889.2  418.19  4898.8  416.60  4906.3  416.14
  4906.8  415.34  4911.8  415.34  4912.3  416.14  4918.8  416.14  5075.5  416.14
  5084.0  416.94  5098.6  417.10  5101.1  418.19  5104.6  419.72  5110.4  419.79
  5120.4  420.75  5126.1  420.60  5141.9  421.87  5147.7  423.63  5163.5  425.41
  5200.8  427.72  5206.5  427.72  5228.1  429.36  5237.2  430.43  5261.5  431.99
#Mann=5,-1,0
  4683.5    0.16       0  4906.3   0.033       0  4912.3    0.16       0
  4918.8    0.05       0  5084.0    0.16       0
Bank Sta=4889.2,5101.1
Exp/Cntr=0.3,0.1

Type RM Length L Ch R = 1,2681,359,359,359
BEGIN DESCRIPTION:
UNT 078 IN DRY CR WATERSHED 5.0
END DESCRIPTION:
XS GIS Cut Line= 3
      2906274.99      6943075.00      2906575.00      6943175.00
      2906875.02      6943225.00
#Sta/Elev= 30
  4666.3  438.61  4719.0  436.38  4740.1  434.78  4750.6  433.22  4771.7  431.31
  4782.3  429.83  4803.3  427.77  4813.9  425.87  4835.0  424.05  4845.5  422.35
  4866.6  420.18  4881.8  418.01  4902.2  416.78  4916.3  416.14  4916.8  415.34
  4921.8  415.34  4922.3  416.14  5105.0  416.40  5115.4  418.01  5132.1  420.59
  5137.1  420.83  5154.9  423.67  5192.9  428.12  5198.0  428.08  5205.0  428.98
  5225.9  431.19  5246.1  432.60  5253.7  433.88  5258.8  433.82  5286.7  435.72
#Mann=6,-1,0
  4666.3    0.16       0  4902.2    0.05       0  4916.3   0.033       0
  4922.3    0.05       0  5105.0    0.08       0  5205.0    0.16       0
Bank Sta=4881.8,5115.4
Exp/Cntr=0.3,0.1

Type RM Length L Ch R = 1,2322,255,255,255
BEGIN DESCRIPTION:
UNT 078 IN DRY CR WATERSHED 4.0
END DESCRIPTION:
XS GIS Cut Line= 3
      2906066.69      6943211.67      2906475.00      6943525.00
      2907049.30      6943263.77
#Sta/Elev= 30
  4473.6  434.42  4582.2  436.40  4688.2  434.04  4767.1  425.28  4819.3  417.90
  4835.1  416.73  4849.3  416.14  4849.8  415.34  4855.3  416.14  5146.4  416.14
  5170.0  417.90  5177.3  420.34  5192.5  423.25  5224.9  425.67  5284.8  430.33
  5290.3  429.78  5411.1  436.23  5457.2  435.31  5462.7  436.34  5480.3  435.16
  5485.8  436.26  5526.4  434.08  5531.9  435.45  5555.0  431.89  5560.4  433.53
  5578.0  431.18  5583.5  432.46  5601.1  430.53  5606.6  431.56  5619.2  430.54
#Mann=6,-1,0
  4473.6    0.16       0  4835.1    0.05       0  4849.3   0.033       0
  4855.3    0.05       0  5177.3     0.1       0  5224.9    0.16       0
Bank Sta=4819.3,5170
Exp/Cntr=0.3,0.1

Type RM Length L Ch R = 1,2067,53,53,53
BEGIN DESCRIPTION:
Mapping XS 155ac108
END DESCRIPTION:
XS GIS Cut Line= 4
      2906000.69      6943753.34      2906191.69      6943770.70
      2906646.55      6943760.29      2907118.74      6943722.10
#Sta/Elev= 30
  4581.0  428.67  4605.4  428.34  4625.5  430.15  4645.6  430.62  4685.7  429.91
  4705.8  428.14  4735.9  423.60  4756.0  420.04  4761.8  417.80  4768.5  416.84
  4783.1  416.14  4783.6  415.34  4788.6  415.34  4789.1  416.14  5164.9  416.78
  5182.1  417.80  5206.2  419.53  5231.3  420.18  5264.1  419.62  5276.4  419.24
  5363.6  422.55  5475.7  428.57  5487.1  429.73  5507.1  430.01  5527.2  433.14
  5547.3  434.06  5602.9  432.81  5608.0  433.60  5627.5  433.59  5701.5  432.73
#Mann=7,-1,0
  4581.0    0.16       0  4768.5    0.08       0  4783.1    0.07       0
  4789.1    0.08       0  5164.9     0.1       0  5264.1    0.08       0
  5363.6    0.16       0
Bank Sta=4761.8,5182.1
Exp/Cntr=0.3,0.1

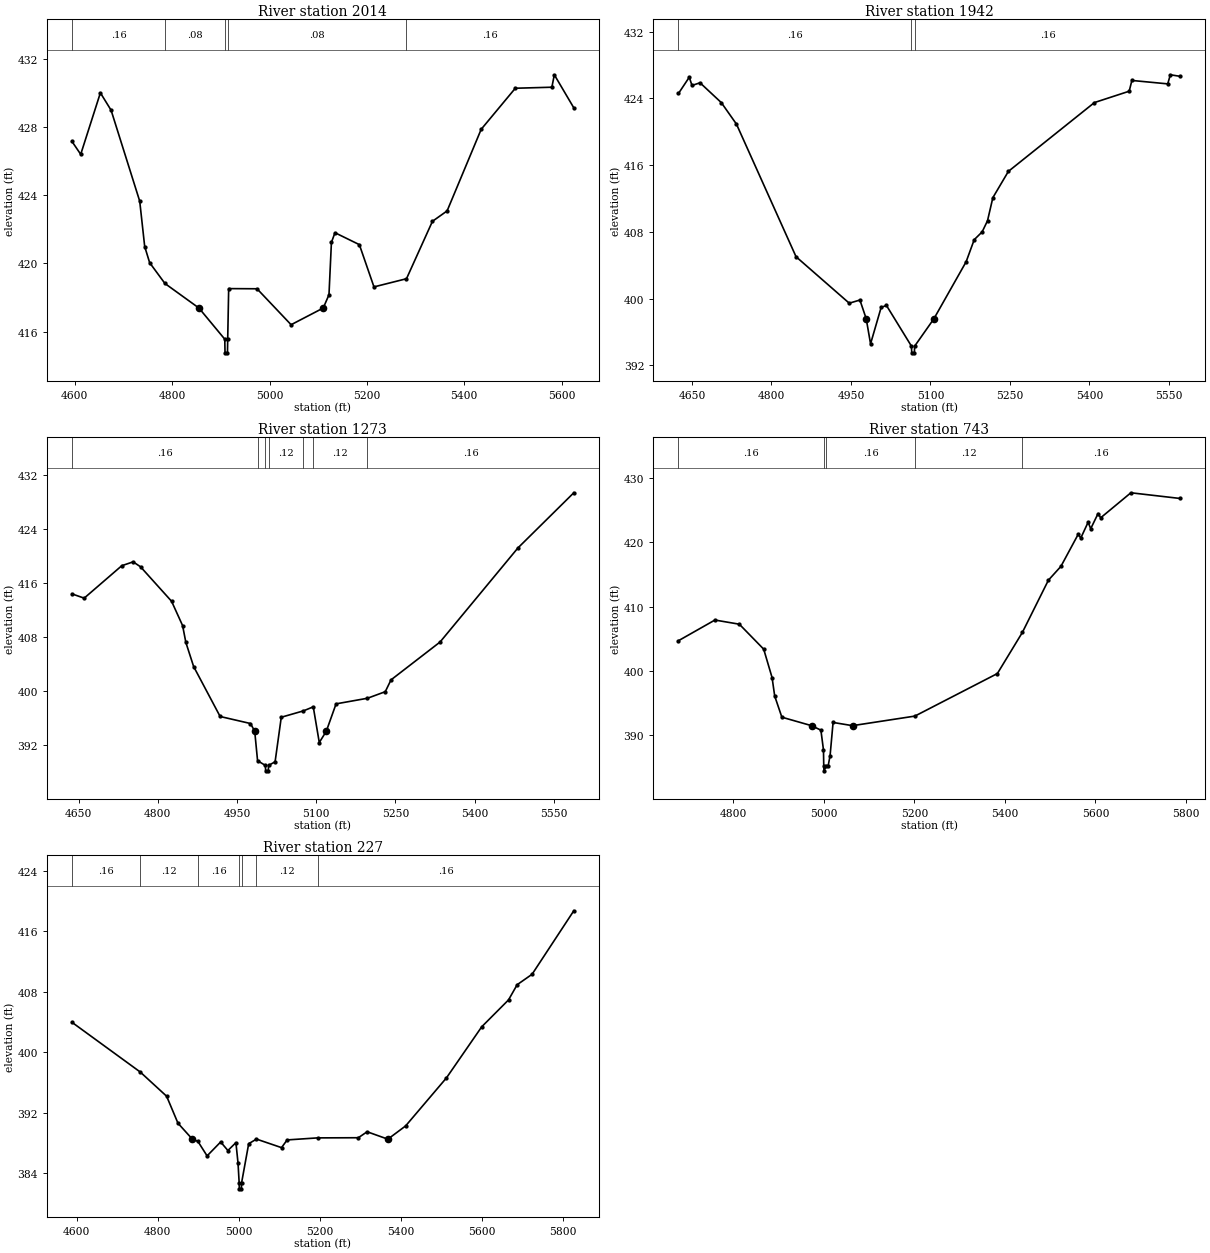
Type RM Length L Ch R = 1,2014,72,72,72
BEGIN DESCRIPTION:
Mapping XS 048ca06a
END DESCRIPTION:
XS GIS Cut Line= 4
      2905997.23      6943798.48      2906181.27      6943826.26
      2906622.24      6943805.43      2907024.98      6943788.07
#Sta/Elev= 30
  4594.2  427.16  4612.2  426.40  4652.6  430.01  4674.6  428.99  4733.4  423.65
  4743.6  420.99  4753.8  420.04  4785.2  418.82  4855.0  417.38  4908.1  415.55
  4908.6  414.75  4913.6  414.75  4914.1  415.55  4916.1  418.52  4974.3  418.51
  5044.3  416.40  5110.3  417.38  5122.1  418.16  5127.1  421.23  5134.4  421.80
  5184.5  421.10  5214.5  418.62  5281.3  419.10  5334.6  422.47  5364.7  423.08
  5434.7  427.87  5504.8  430.28  5579.9  430.34  5584.9  431.07  5624.9  429.13
#Mann=5,-1,0
  4594.2    0.16       0  4785.2    0.08       0  4908.1    0.07       0
  4914.1    0.08       0  5281.3    0.16       0
Bank Sta=4855,5110.3
Exp/Cntr=0.3,0.1

Type RM Length L Ch R = 1,1942,669,669,669
BEGIN DESCRIPTION:
Mapping XS bc48845f
END DESCRIPTION:
XS GIS Cut Line= 4
      2906014.59      6943847.09      2906285.44      6943878.34
      2906570.16      6943899.18      2906955.62      6943847.09
#Sta/Elev= 30
  4624.6  424.58  4645.0  426.53  4650.1  425.54  4665.3  425.86  4705.5  423.48
  4734.0  420.91  4846.5  405.01  4946.9  399.44  4967.0  399.82  4978.9  397.58
  4987.1  394.57  5007.1  398.94  5017.1  399.17  5064.3  394.29  5064.8  393.49
  5069.8  393.49  5070.3  394.29  5106.7  397.58  5167.5  404.41  5182.7  407.05
  5197.7  407.99  5207.8  409.32  5217.9  412.09  5247.2  415.24  5409.6  423.49
  5475.2  424.85  5480.3  426.14  5547.9  425.73  5552.9  426.82  5571.7  426.63
#Mann=3,-1,0
  4624.6    0.16       0  5064.3    0.07       0  5070.3    0.16       0
Bank Sta=4978.9,5106.7
Exp/Cntr=0.3,0.1

Type RM Length L Ch R = 1,1273,530,530,530
BEGIN DESCRIPTION:
Mapping XS a370ca34
END DESCRIPTION:
XS GIS Cut Line= 3
      2905991.18      6944016.37      2906290.65      6944233.38
      2906846.20      6944402.65
#Sta/Elev= 30
  4637.4  414.34  4660.6  413.71  4731.8  418.51  4753.3  419.08  4767.3  418.35
  4826.1  413.25  4847.0  409.65  4853.2  407.15  4867.9  403.59  4918.1  396.20
  4975.6  395.16  4983.6  394.02  4989.0  389.66  5003.8  388.96  5004.3  388.16
  5009.3  388.16  5009.8  388.96  5022.2  389.50  5033.9  396.09  5075.8  397.03
  5094.5  397.63  5105.9  392.35  5119.2  394.02  5137.7  398.07  5197.2  398.90
  5230.9  399.87  5241.8  401.62  5334.7  407.22  5482.2  421.14  5588.0  429.30
#Mann=7,-1,0
  4637.4    0.16       0  4989.0    0.12       0  5003.8    0.07       0
  5009.8    0.12       0  5075.8    0.16       0  5094.5    0.12       0
  5197.2    0.16       0
Bank Sta=4983.6,5119.2
Exp/Cntr=0.3,0.1

Type RM Length L Ch R = 1,743,516,516,516
BEGIN DESCRIPTION:
Mapping XS 0ad61bfc
END DESCRIPTION:
XS GIS Cut Line= 3
      2905860.98      6944203.04      2905982.49      6944506.82
      2906671.27      6944875.03
#Sta/Elev= 30
  4679.2  404.68  4759.7  407.90  4813.6  407.25  4867.4  403.36  4885.9  398.93
  4891.7  396.05  4907.5  392.76  4973.0  391.44  4993.7  390.74  4999.4  387.66
  5000.0  385.20  5000.5  384.40  5006.0  385.20  5009.8  385.20  5014.0  386.78
  5020.6  391.94  5063.5  391.44  5201.2  392.93  5383.4  399.56  5438.6  405.97
  5496.1  414.11  5523.7  416.26  5561.9  421.26  5567.6  420.68  5583.8  423.14
  5589.5  422.13  5605.8  424.50  5611.5  423.83  5678.2  427.73  5787.4  426.84
#Mann=5,-1,0
  4679.2    0.16       0  5000.0    0.07       0  5006.0    0.16       0
  5201.2    0.12       0  5438.6    0.16       0
Bank Sta=4973,5063.5
Exp/Cntr=0.3,0.1

Type RM Length L Ch R = 1,227,0,0,0
BEGIN DESCRIPTION:
UNT 078 IN DRY CR WATERSHED 1.0
END DESCRIPTION:
XS GIS Cut Line= 3
      2905732.03      6944130.25      2905623.51      6944600.00
      2906268.90      6944992.90
#Sta/Elev= 30
  4588.2  403.97  4756.7  397.39  4821.7  394.19  4849.7  390.62  4885.2  388.51
  4898.8  388.22  4921.5  386.30  4955.0  388.14  4972.8  387.01  4992.6  388.05
  4997.8  385.35  5000.6  382.74  5001.1  381.94  5006.1  381.94  5006.6  382.74
  5024.1  387.91  5043.3  388.52  5105.1  387.39  5118.9  388.41  5194.2  388.68
  5294.5  388.70  5316.2  389.49  5367.3  388.51  5411.1  390.26  5511.9  396.62
  5598.9  403.38  5664.9  406.93  5686.2  408.94  5723.0  410.32  5825.9  418.72
#Mann=7,-1,0
  4588.2    0.16       0  4756.7    0.12       0  4898.8    0.16       0
  5000.6    0.07       0  5006.6    0.16       0  5043.3    0.12       0
  5194.2    0.16       0
Bank Sta=4885.2,5367.3
Exp/Cntr=0.3,0.1

Chan Stop Cuts=-1