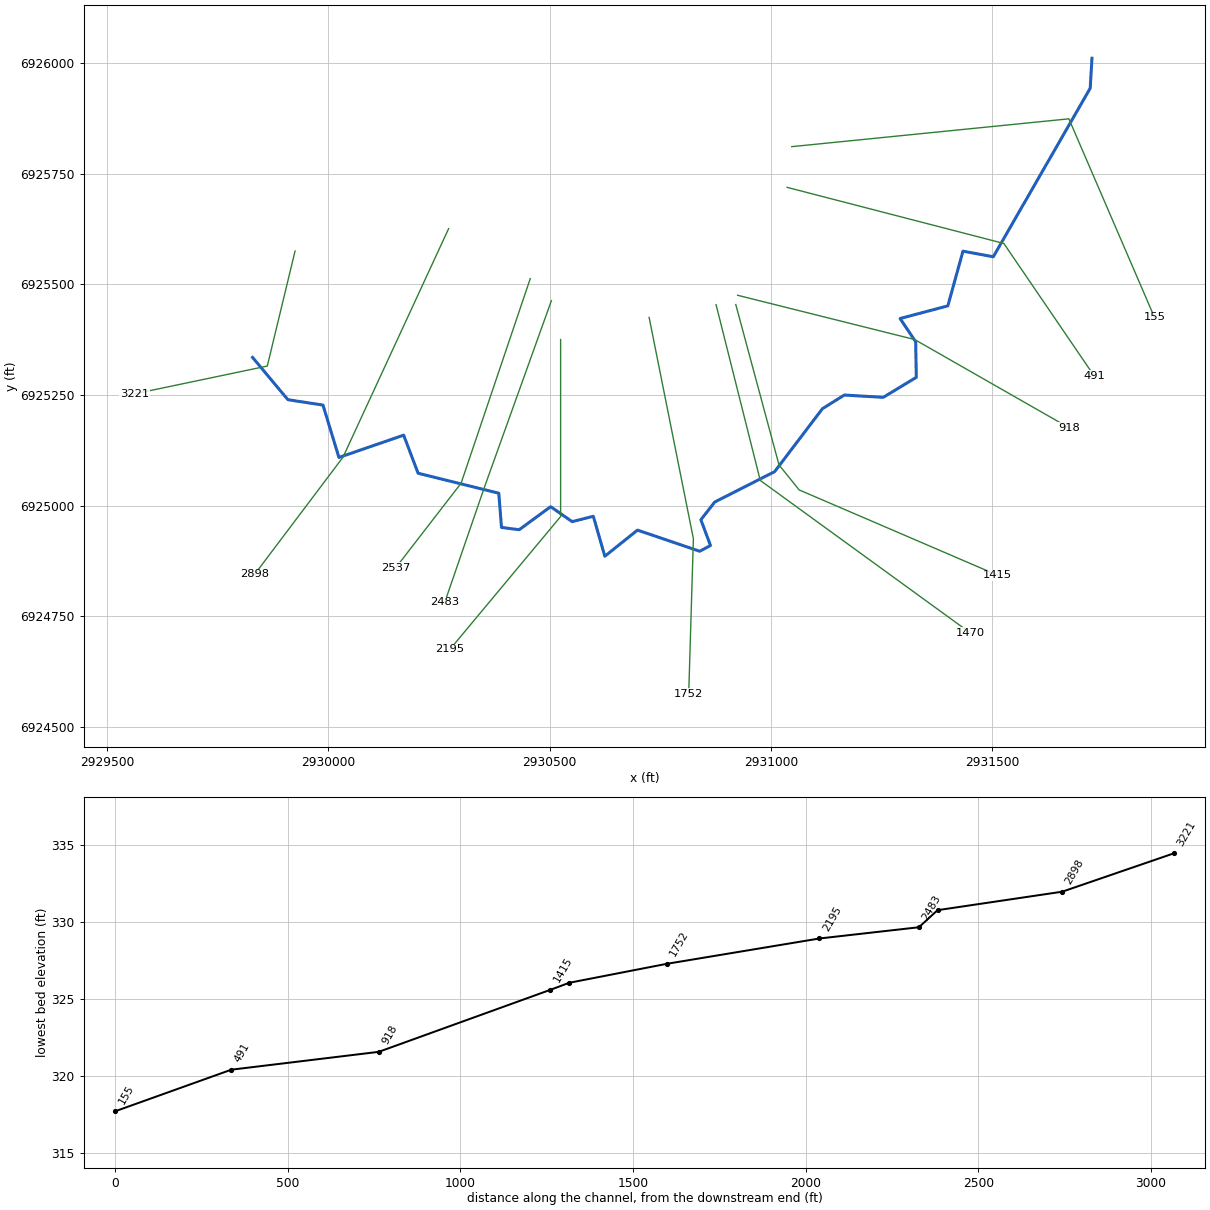
--- UNT 079 IN DRY CR WATERSHED.prj (project) ---

Proj Title=UNT 079 IN DRY CR WATERSHED Base Level Engineering
Current Plan=p01
Default Exp/Contr=0.3,0.1
English Units
Geom File=g01
Flow File=f01
Plan File=p01
BEGIN DESCRIPTION:
UNT 079 IN DRY CR WATERSHED
END DESCRIPTION:

--- UNT 079 IN DRY CR WATERSHED.p01 (plan) ---

Plan Title=Multiple Run
Short Identifier=Multiple
Geom File=g01
Flow File=f01
Subcritical Flow
K Sum by GR= 0
Std Step Tol= 0.01
Critical Tol= 0.01
Num of Std Step Trials= 20
Max Error Tol= 0.3
Flow Tol Ratio= 0.001
Split Flow NTrial= 30
Split Flow Tol= 0.02
Split Flow Ratio= 0.02
Log Output Level= 0
Friction Slope Method= 1
Unsteady Friction Slope Method= 2
Unsteady Bridges Friction Slope Method= 1
Parabolic Critical Depth
Global Vel Dist=  1 , 1 , 1
Global Log Level= 0
CheckData=True
Encroach Param= -1, 0, 0, 0
BEGIN DESCRIPTION:
Multiple Run
END DESCRIPTION:

--- UNT 079 IN DRY CR WATERSHED.f01 (steady flow) ---

Flow Title=Multiple
Number of Profiles=7
Profile Names=10-year,25-year,50-year,1pct_min,100-year,1pct_plu,500-year
River Rch & RM= UNT 079 IN DRY C,Reach-1,3221
     512     684     824     494     986    1968    1413
Boundary for River Rch & Prof#=UNT 079 IN DRY C,Reach-1,1
Up Type=0
Dn Type=3
Dn Slope=0.005
Boundary for River Rch & Prof#=UNT 079 IN DRY C,Reach-1,2
Up Type=0
Dn Type=3
Dn Slope=0.005
Boundary for River Rch & Prof#=UNT 079 IN DRY C,Reach-1,3
Up Type=0
Dn Type=3
Dn Slope=0.005
Boundary for River Rch & Prof#=UNT 079 IN DRY C,Reach-1,4
Up Type=0
Dn Type=3
Dn Slope=0.005
Boundary for River Rch & Prof#=UNT 079 IN DRY C,Reach-1,5
Up Type=0
Dn Type=3
Dn Slope=0.005
Boundary for River Rch & Prof#=UNT 079 IN DRY C,Reach-1,6
Up Type=0
Dn Type=3
Dn Slope=0.005
Boundary for River Rch & Prof#=UNT 079 IN DRY C,Reach-1,7
Up Type=0
Dn Type=3
Dn Slope=0.005

--- UNT 079 IN DRY CR WATERSHED.g01 (geometry) ---

Geom Title=Existing Conditions

River Reach=UNT 079 IN DRY C,Reach-1
Reach XY= 30
      2929828.96      6925334.56      2929908.83      6925239.09
      2929988.07      6925226.90      2930024.11      6925108.58
      2930170.37      6925158.91      2930203.04      6925072.89
      2930385.33      6925027.75      2930391.41      6924950.49
      2930431.34      6924945.28      2930502.52      6924997.37
      2930551.13      6924963.51      2930598.88      6924975.66
      2930624.92      6924885.39      2930698.70      6924944.41
      2930839.33      6924896.67      2930863.63      6924909.69
      2930841.93      6924967.85      2930873.18      6925007.78
      2931008.66      6925076.59      2931116.51      6925218.67
      2931166.01      6925249.58      2931254.06      6925244.43
      2931328.72      6925289.63      2931327.23      6925370.03
      2931292.04      6925422.48      2931399.94      6925451.09
      2931434.15      6925574.67      2931502.67      6925562.03
      2931721.64      6925942.90      2931725.59      6926010.71

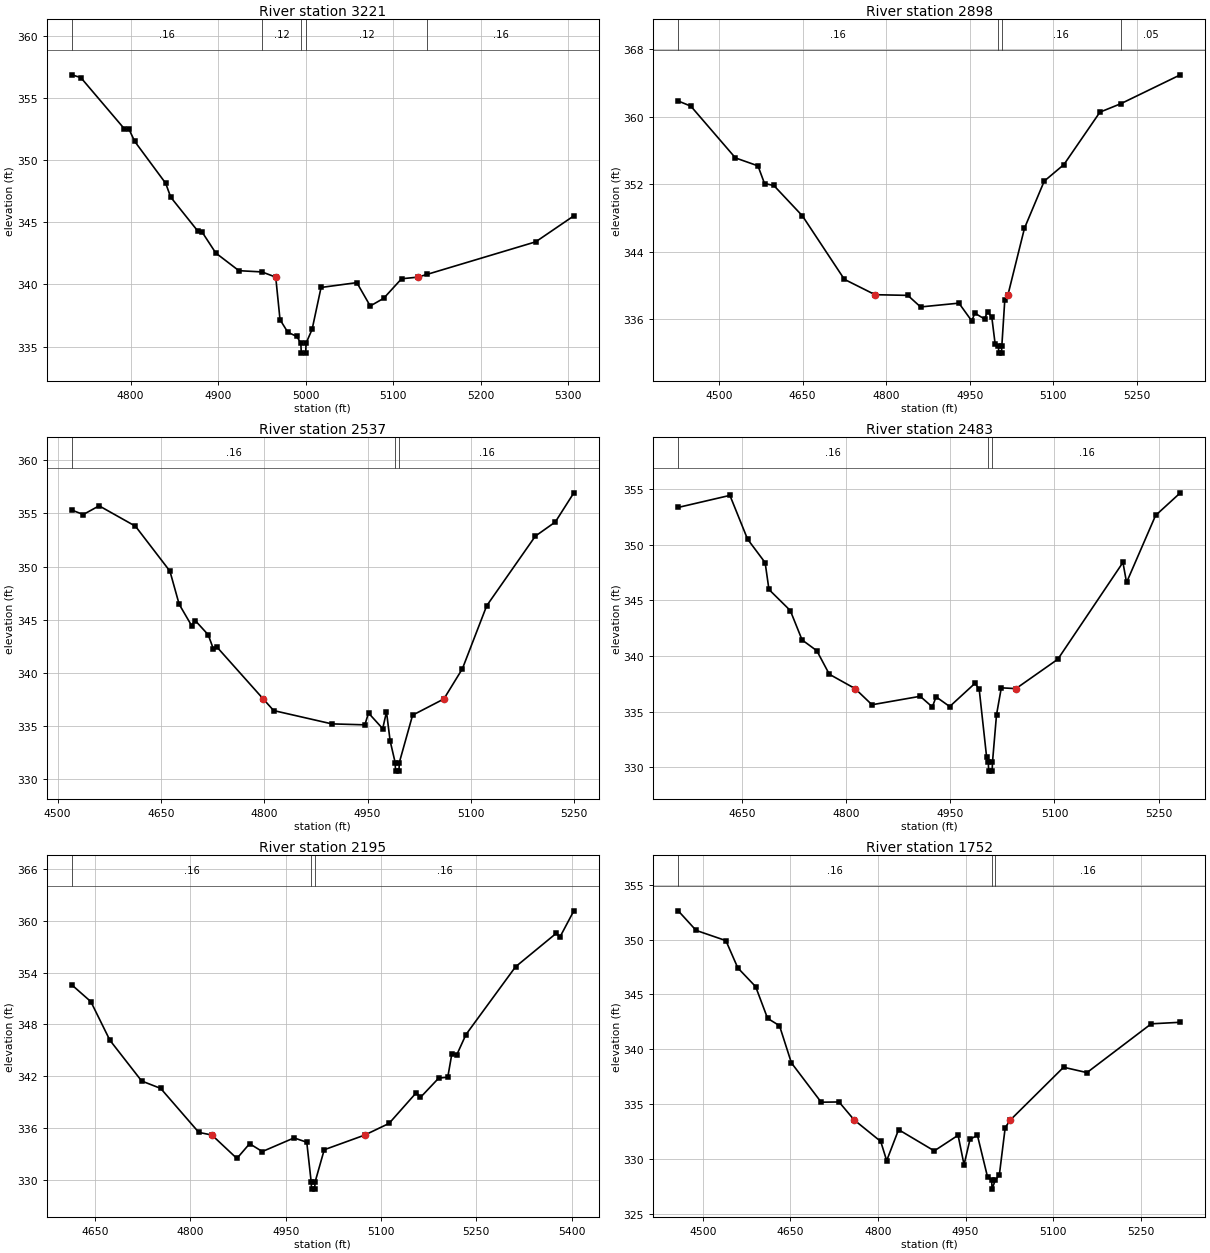
Type RM Length L Ch R = 1,3221,323,323,323
BEGIN DESCRIPTION:
UNT 079 IN DRY CR WATERSHED 7.0
END DESCRIPTION:
XS GIS Cut Line= 3
      2929925.00      6925574.98      2929862.27      6925315.14
      2929562.29      6925252.24
#Sta/Elev= 30
  4732.7  356.85  4743.0  356.63  4792.9  352.50  4798.1  352.47  4804.7  351.49
  4840.0  348.13  4845.8  347.01  4876.7  344.29  4881.8  344.19  4897.3  342.52
  4923.7  341.10  4950.1  341.00  4965.8  340.58  4970.7  337.16  4979.6  336.15
  4989.9  335.81  4994.5  335.27  4995.0  334.47  5000.0  334.47  5000.5  335.27
  5007.4  336.39  5017.6  339.75  5058.5  340.14  5073.8  338.26  5089.2  338.88
  5109.6  340.45  5128.2  340.58  5139.1  340.81  5262.9  343.42  5306.5  345.51
#Mann=5,-1,0
  4732.7    0.16       0  4950.1    0.12       0  4994.5    0.07       0
  5000.5    0.12       0  5139.1    0.16       0
Bank Sta=4965.8,5128.2
Exp/Cntr=0.3,0.1

Type RM Length L Ch R = 1,2898,361,361,361
BEGIN DESCRIPTION:
Mapping XS 5e6507c3
END DESCRIPTION:
XS GIS Cut Line= 3
      2930271.96      6925625.55      2930033.23      6925109.02
      2929833.59      6924844.28
#Sta/Elev= 30
  4427.1  361.84  4449.7  361.23  4529.7  355.10  4570.1  354.16  4581.9  352.06
  4598.5  351.84  4649.9  348.23  4725.1  340.72  4780.2  338.90  4838.9  338.82
  4861.8  337.45  4930.6  337.90  4953.6  335.79  4959.1  336.72  4976.5  336.02
  4982.0  336.89  4989.5  336.28  4995.6  333.03  5001.5  332.78  5002.0  331.98
  5007.0  331.98  5007.5  332.78  5012.8  338.22  5018.6  338.90  5048.2  346.78
  5083.6  352.35  5118.9  354.31  5183.5  360.52  5221.0  361.52  5327.7  364.94
#Mann=4,-1,0
  4427.1    0.16       0  5001.5    0.07       0  5007.5    0.16       0
  5221.0    0.05       0
Bank Sta=4780.2,5018.6
Exp/Cntr=0.3,0.1

Type RM Length L Ch R = 1,2537,54,54,54
BEGIN DESCRIPTION:
Mapping XS 8c884a7d
END DESCRIPTION:
XS GIS Cut Line= 3
      2930456.40      6925512.65      2930300.15      6925050.42
      2930152.81      6924859.74
#Sta/Elev= 30
  4520.5  355.31  4537.2  354.89  4560.2  355.71  4613.0  353.79  4663.0  349.57
  4676.4  346.46  4694.4  344.46  4699.7  344.93  4718.6  343.59  4725.9  342.29
  4731.1  342.45  4798.5  337.56  4813.6  336.47  4898.0  335.22  4946.0  335.13
  4951.3  336.24  4971.9  334.77  4977.4  336.35  4982.7  333.62  4990.0  331.58
  4990.5  330.78  4995.5  330.78  4996.0  331.58  5015.3  336.04  5060.7  337.56
  5087.6  340.40  5122.9  346.32  5193.5  352.86  5222.5  354.19  5249.4  356.93
#Mann=3,-1,0
  4520.5    0.16       0  4990.0    0.07       0  4996.0    0.16       0
Bank Sta=4798.5,5060.7
Exp/Cntr=0.3,0.1

Type RM Length L Ch R = 1,2483,288,288,288
BEGIN DESCRIPTION:
Mapping XS 2932e093
END DESCRIPTION:
XS GIS Cut Line= 3
      2930504.16      6925462.79      2930352.24      6925039.57
      2930263.26      6924781.33
#Sta/Elev= 30
  4558.4  353.35  4632.8  354.43  4658.2  350.50  4683.5  348.39  4689.0  345.98
  4719.7  344.09  4736.7  341.45  4757.9  340.48  4775.9  338.37  4813.0  337.08
  4837.3  335.63  4906.7  336.39  4924.2  335.43  4929.6  336.34  4949.2  335.47
  4985.7  337.56  4991.7  337.01  5002.3  330.96  5004.8  330.47  5005.3  329.67
  5010.3  329.67  5010.8  330.47  5016.6  334.73  5023.5  337.15  5044.6  337.08
  5104.9  339.72  5198.6  348.41  5203.8  346.61  5245.6  352.63  5281.2  354.66
#Mann=3,-1,0
  4558.4    0.16       0  5004.8    0.07       0  5010.8    0.16       0
Bank Sta=4813,5044.6
Exp/Cntr=0.3,0.1

Type RM Length L Ch R = 1,2195,443,443,443
BEGIN DESCRIPTION:
UNT 079 IN DRY CR WATERSHED 5.0
END DESCRIPTION:
XS GIS Cut Line= 3
      2930525.00      6925374.99      2930525.00      6924975.00
      2930275.00      6924675.00
#Sta/Elev= 30
  4613.1  352.59  4643.1  350.65  4673.1  346.18  4723.1  341.46  4753.1  340.60
  4813.1  335.51  4833.8  335.20  4873.1  332.49  4893.1  334.20  4913.1  333.29
  4963.1  334.87  4983.1  334.37  4990.1  329.74  4990.6  328.94  4995.6  328.94
  4996.1  329.74  5010.6  333.50  5074.4  335.20  5112.7  336.55  5155.6  340.11
  5162.1  339.56  5190.8  341.79  5205.1  341.90  5211.6  344.64  5219.4  344.51
  5233.7  346.83  5311.8  354.68  5375.6  358.54  5382.1  358.18  5403.6  361.16
#Mann=3,-1,0
  4613.1    0.16       0  4990.1    0.07       0  4996.1    0.16       0
Bank Sta=4833.8,5074.4
Exp/Cntr=0.3,0.1

Type RM Length L Ch R = 1,1752,282,282,282
BEGIN DESCRIPTION:
UNT 079 IN DRY CR WATERSHED 4.0
END DESCRIPTION:
XS GIS Cut Line= 3
      2930724.99      6925425.03      2930825.00      6924925.00
      2930814.48      6924575.19
#Sta/Elev= 30
  4457.9  352.61  4488.5  350.83  4539.5  349.90  4559.9  347.42  4590.5  345.71
  4610.9  342.83  4631.3  342.16  4651.7  338.78  4702.7  335.20  4733.3  335.22
  4759.3  333.58  4804.7  331.63  4814.9  329.88  4835.3  332.70  4896.4  330.77
  4937.2  332.19  4947.4  329.51  4957.6  331.82  4970.3  332.19  4987.8  328.36
  4994.8  328.09  4995.3  327.29  5000.8  328.09  5007.9  328.60  5017.9  332.89
  5026.7  333.58  5117.9  338.38  5157.9  337.89  5268.0  342.33  5317.8  342.47
#Mann=3,-1,0
  4457.9    0.16       0  4994.8    0.07       0  5000.8    0.16       0
Bank Sta=4759.3,5026.7
Exp/Cntr=0.3,0.1

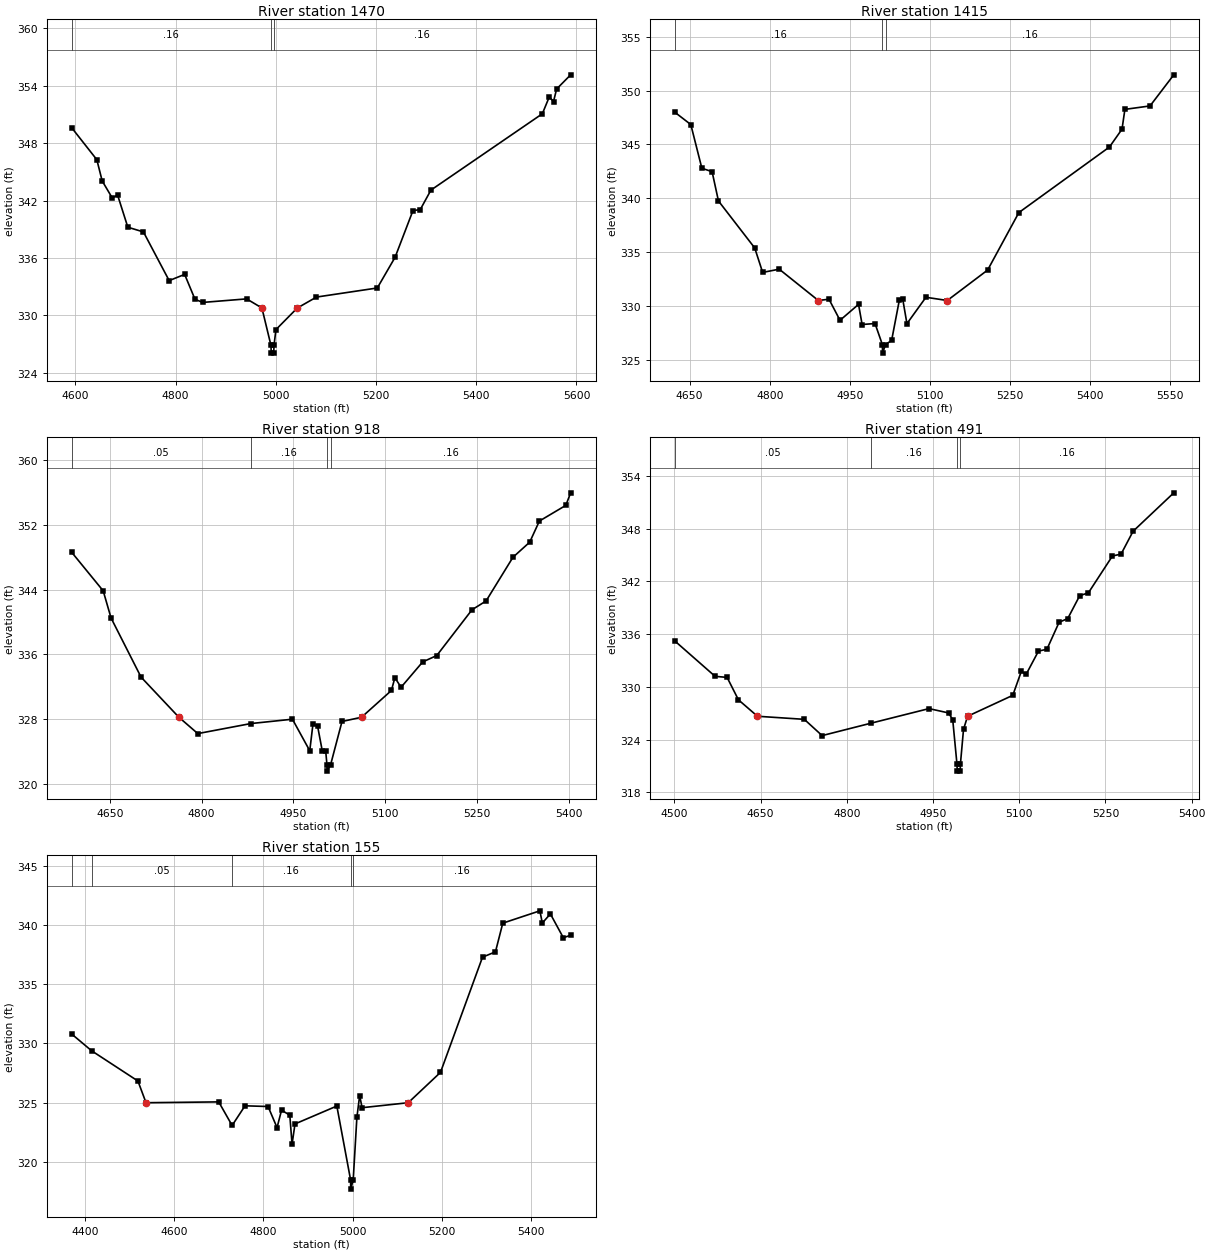
Type RM Length L Ch R = 1,1470,55,55,55
BEGIN DESCRIPTION:
Mapping XS d3f58fba
END DESCRIPTION:
XS GIS Cut Line= 3
      2930876.27      6925453.81      2930976.10      6925056.67
      2931450.71      6924712.09
#Sta/Elev= 30
  4592.4  349.63  4642.7  346.28  4653.4  344.06  4673.7  342.26  4684.0  342.61
  4704.6  339.22  4735.7  338.73  4787.1  333.64  4818.0  334.29  4838.6  331.69
  4854.0  331.36  4941.7  331.73  4972.2  330.78  4990.3  326.86  4990.8  326.06
  4995.8  326.06  4996.3  326.86  5000.2  328.52  5042.7  330.77  5081.1  331.92
  5202.5  332.87  5238.0  336.08  5273.6  340.95  5288.3  341.07  5309.5  343.10
  5531.9  351.08  5545.7  352.84  5554.2  352.36  5560.4  353.67  5588.4  355.15
#Mann=3,-1,0
  4592.4    0.16       0  4990.3    0.07       0  4996.3    0.16       0
Bank Sta=4972.2,5042.7
Exp/Cntr=0.3,0.1

Type RM Length L Ch R = 1,1415,497,497,497
BEGIN DESCRIPTION:
Mapping XS d9654f76
END DESCRIPTION:
XS GIS Cut Line= 4
      2930920.82      6925454.05      2931018.47      6925091.66
      2931064.04      6925035.23      2931511.67      6924842.77
#Sta/Elev= 30
  4622.0  347.99  4652.1  346.84  4672.8  342.78  4692.0  342.46  4703.9  339.74
  4771.9  335.37  4786.7  333.10  4817.8  333.40  4891.1  330.49  4911.0  330.61
  4931.7  328.65  4966.4  330.13  4973.1  328.26  4997.3  328.35  5011.0  326.40
  5011.5  325.60  5017.0  326.40  5028.4  326.78  5042.8  330.51  5049.2  330.62
  5057.1  328.34  5092.7  330.79  5132.7  330.49  5208.3  333.32  5266.8  338.66
  5436.5  344.75  5460.1  346.41  5465.5  348.25  5512.6  348.57  5557.1  351.46
#Mann=3,-1,0
  4622.0    0.16       0  5011.0    0.07       0  5017.0    0.16       0
Bank Sta=4891.1,5132.7
Exp/Cntr=0.3,0.1

Type RM Length L Ch R = 1,918,427,427,427
BEGIN DESCRIPTION:
UNT 079 IN DRY CR WATERSHED 2.0
END DESCRIPTION:
XS GIS Cut Line= 3
      2930924.99      6925475.00      2931325.00      6925375.00
      2931674.97      6925175.02
#Sta/Elev= 30
  4587.5  348.64  4639.1  343.86  4651.9  340.51  4700.9  333.20  4762.8  328.23
  4793.7  326.21  4880.2  327.45  4948.3  327.99  4976.6  324.09  4981.8  327.36
  4989.5  327.10  4997.2  324.01  5002.7  324.01  5004.7  322.37  5005.2  321.57
  5010.7  322.37  5029.3  327.71  5061.2  328.23  5110.0  331.54  5115.7  333.12
  5125.8  331.94  5161.1  335.07  5184.1  335.86  5241.7  341.52  5264.7  342.61
  5308.6  348.01  5336.0  349.88  5351.8  352.49  5395.0  354.43  5402.9  355.98
#Mann=4,-1,0
  4587.5    0.05       0  4880.2    0.16       0  5004.7    0.07       0
  5010.7    0.16       0
Bank Sta=4762.8,5061.2
Exp/Cntr=0.3,0.1

Type RM Length L Ch R = 1,491,336,336,336
BEGIN DESCRIPTION:
Mapping XS 353cc5f2
END DESCRIPTION:
XS GIS Cut Line= 3
      2931036.80      6925718.84      2931526.43      6925592.09
      2931730.65      6925292.67
#Sta/Elev= 30
  4500.7  335.22  4570.9  331.19  4591.8  331.07  4611.5  328.52  4644.6  326.65
  4726.1  326.30  4757.1  324.45  4842.6  325.87  4943.0  327.52  4977.0  327.03
  4984.3  326.27  4991.7  321.21  4992.2  320.41  4997.2  320.41  4997.7  321.21
  5003.1  325.16  5010.2  326.65  5088.8  329.03  5103.7  331.76  5111.9  331.40
  5133.5  334.06  5148.2  334.27  5169.4  337.34  5184.4  337.76  5205.3  340.37
  5220.3  340.68  5262.2  344.88  5277.2  345.09  5298.1  347.69  5368.9  352.06
#Mann=4,-1,0
  4500.7    0.05       0  4842.6    0.16       0  4991.7    0.07       0
  4997.7    0.16       0
Bank Sta=4644.6,5010.2
Exp/Cntr=0.3,0.1

Type RM Length L Ch R = 1,155,0,0,0
BEGIN DESCRIPTION:
UNT 079 IN DRY CR WATERSHED 1.0
END DESCRIPTION:
XS GIS Cut Line= 3
      2931047.29      6925810.84      2931673.44      6925873.72
      2931866.71      6925425.40
#Sta/Elev= 30
  4370.7  330.80  4415.6  329.38  4519.2  326.83  4537.3  325.00  4700.1  325.07
  4730.1  323.08  4759.0  324.74  4810.6  324.68  4830.7  322.90  4840.8  324.37
  4859.3  323.95  4864.3  321.49  4870.9  323.21  4964.6  324.72  4995.3  318.51
  4995.8  317.71  5001.3  318.51  5009.5  323.76  5015.7  325.60  5021.2  324.58
  5124.5  325.00  5196.7  327.56  5290.8  337.28  5319.8  337.73  5336.2  340.15
  5419.3  341.19  5424.7  340.16  5442.8  340.93  5471.8  338.92  5488.2  339.13
#Mann=5,-1,0
  4370.7    0.16       0  4415.6    0.05       0  4730.1    0.16       0
  4995.3    0.07       0  5001.3    0.16       0
Bank Sta=4537.3,5124.5
Exp/Cntr=0.3,0.1

Chan Stop Cuts=-1