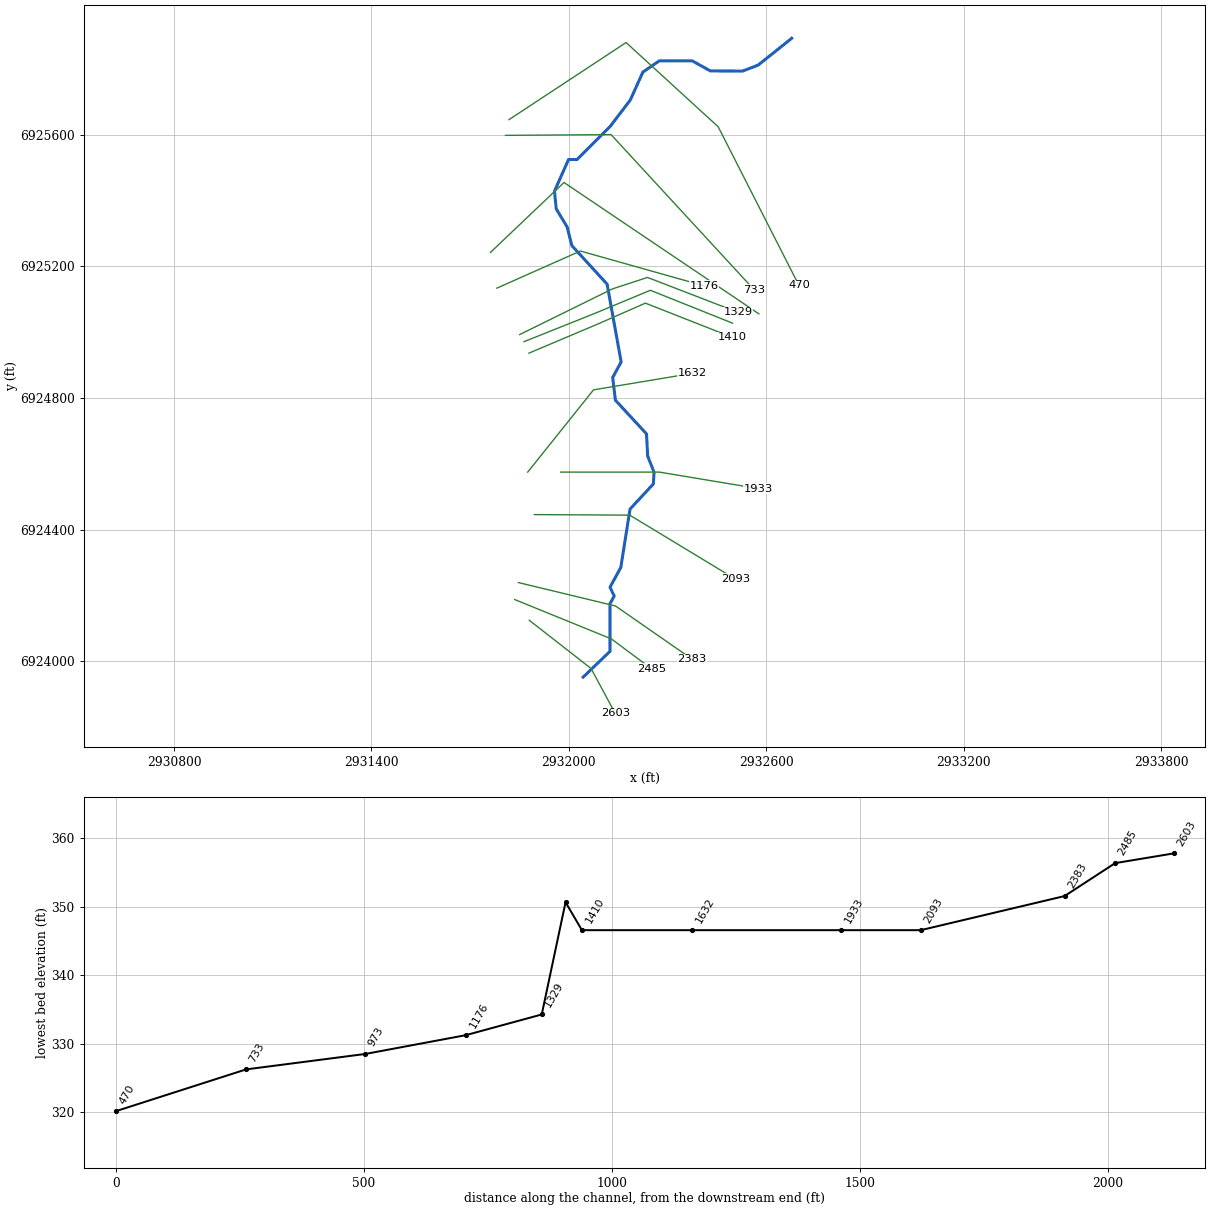
--- UNT 080 IN DRY CR WATERSHED.prj (project) ---

Proj Title=UNT 080 IN DRY CR WATERSHED Base Level Engineering
Current Plan=p01
Default Exp/Contr=0.3,0.1
English Units
Geom File=g01
Flow File=f01
Plan File=p01
BEGIN DESCRIPTION:
UNT 080 IN DRY CR WATERSHED
END DESCRIPTION:

--- UNT 080 IN DRY CR WATERSHED.p01 (plan) ---

Plan Title=Multiple Run
Short Identifier=Multiple
Geom File=g01
Flow File=f01
Subcritical Flow
K Sum by GR= 0
Std Step Tol= 0.01
Critical Tol= 0.01
Num of Std Step Trials= 20
Max Error Tol= 0.3
Flow Tol Ratio= 0.001
Split Flow NTrial= 30
Split Flow Tol= 0.02
Split Flow Ratio= 0.02
Log Output Level= 0
Friction Slope Method= 1
Unsteady Friction Slope Method= 2
Unsteady Bridges Friction Slope Method= 1
Parabolic Critical Depth
Global Vel Dist=  1 , 1 , 1
Global Log Level= 0
CheckData=True
Encroach Param= -1, 0, 0, 0
BEGIN DESCRIPTION:
Multiple Run
END DESCRIPTION:

--- UNT 080 IN DRY CR WATERSHED.f01 (steady flow) ---

Flow Title=Multiple
Number of Profiles=7
Profile Names=10-year,25-year,50-year,1pct_min,100-year,1pct_plu,500-year
River Rch & RM= UNT 080 IN DRY C,Reach-1,2603
      91     107     118      66     131     261     160
Boundary for River Rch & Prof#=UNT 080 IN DRY C,Reach-1,1
Up Type=0
Dn Type=3
Dn Slope=0.005
Boundary for River Rch & Prof#=UNT 080 IN DRY C,Reach-1,2
Up Type=0
Dn Type=3
Dn Slope=0.005
Boundary for River Rch & Prof#=UNT 080 IN DRY C,Reach-1,3
Up Type=0
Dn Type=3
Dn Slope=0.005
Boundary for River Rch & Prof#=UNT 080 IN DRY C,Reach-1,4
Up Type=0
Dn Type=3
Dn Slope=0.005
Boundary for River Rch & Prof#=UNT 080 IN DRY C,Reach-1,5
Up Type=0
Dn Type=3
Dn Slope=0.005
Boundary for River Rch & Prof#=UNT 080 IN DRY C,Reach-1,6
Up Type=0
Dn Type=3
Dn Slope=0.005
Boundary for River Rch & Prof#=UNT 080 IN DRY C,Reach-1,7
Up Type=0
Dn Type=3
Dn Slope=0.005

--- UNT 080 IN DRY CR WATERSHED.g01 (geometry) ---

Geom Title=Existing Conditions

River Reach=UNT 080 IN DRY C,Reach-1
Reach XY= 30
      2932043.23      6923951.69      2932125.00      6924030.10
      2932125.00      6924175.00      2932137.92      6924198.39
      2932125.00      6924225.00      2932157.89      6924285.19
      2932185.89      6924462.51      2932256.86      6924539.07
      2932258.94      6924574.49      2932239.50      6924623.79
      2932236.03      6924691.15      2932141.41      6924793.54
      2932133.25      6924862.64      2932158.94      6924909.86
      2932116.25      6925146.20      2932009.13      6925263.30
      2931994.85      6925319.98      2931961.52      6925375.19
      2931956.31      6925428.84      2931999.02      6925525.19
      2932025.00      6925525.00      2932125.00      6925625.00
      2932186.69      6925705.78      2932225.00      6925790.85
      2932275.00      6925825.00      2932375.00      6925825.00
      2932429.85      6925794.46      2932527.76      6925793.77
      2932574.99      6925811.82      2932677.23      6925893.40

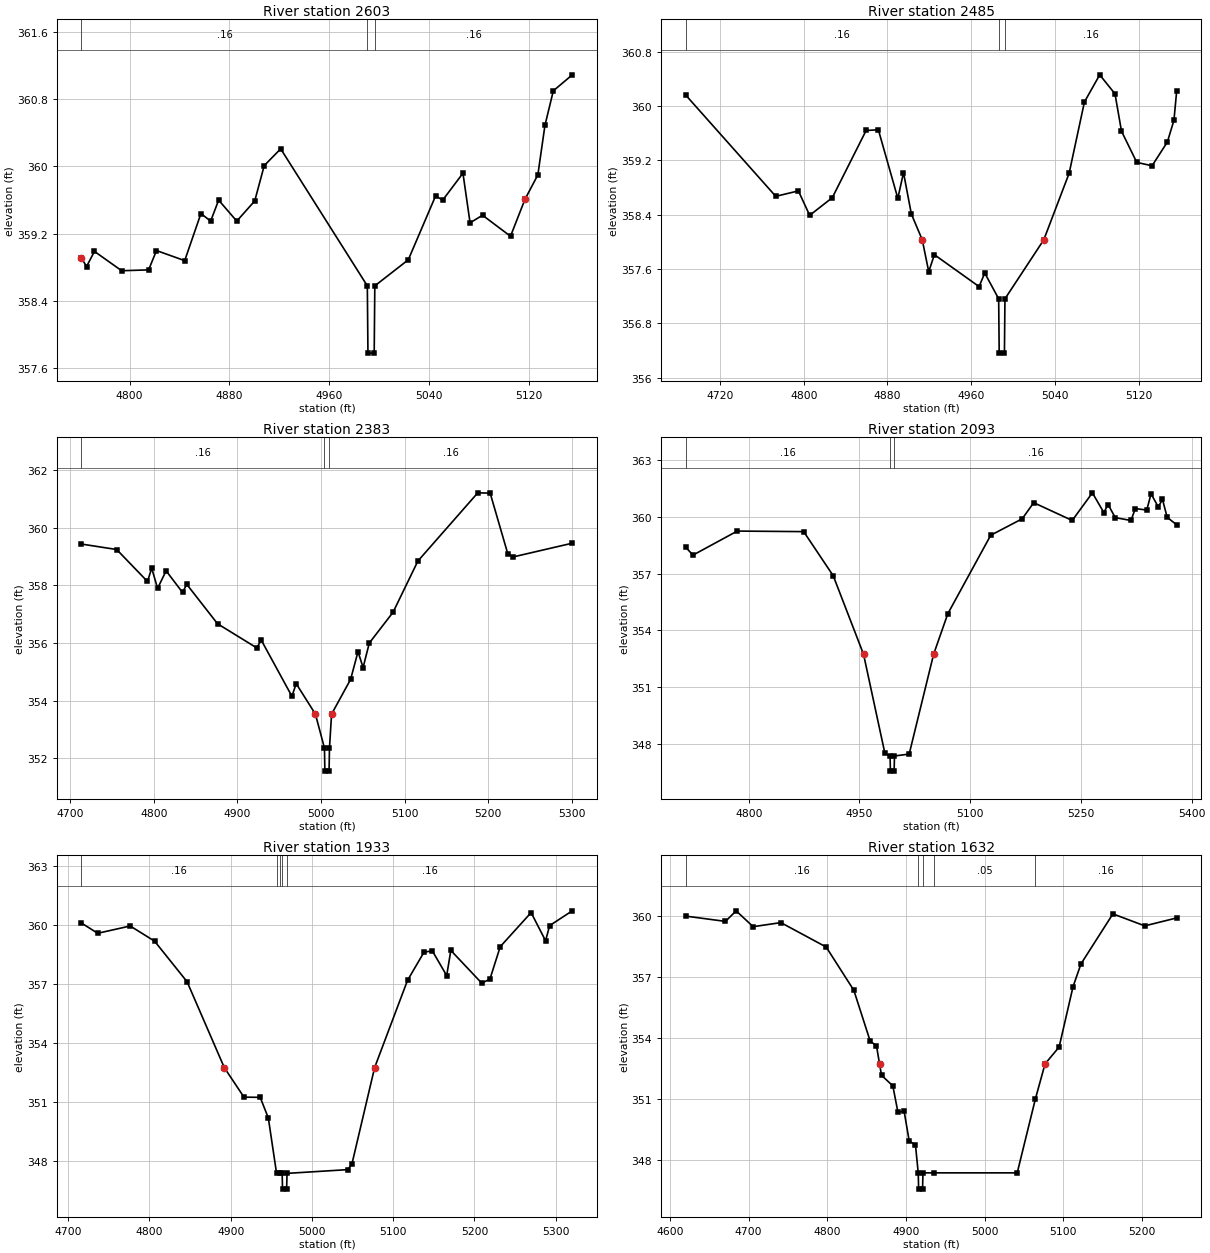
Type RM Length L Ch R = 1,2603,118,118,118
BEGIN DESCRIPTION:
UNT 080 IN DRY CR WATERSHED 5.0
END DESCRIPTION:
XS GIS Cut Line= 3
      2931879.60      6924124.68      2932067.59      6923977.90
      2932140.85      6923841.65
#Sta/Elev= 30
  4761.5  358.91  4765.6  358.81  4771.9  358.99  4793.7  358.76  4815.3  358.77
  4821.6  359.00  4844.2  358.88  4857.2  359.44  4865.0  359.35  4871.4  359.60
  4885.9  359.35  4900.3  359.59  4907.9  360.01  4921.1  360.21  4990.5  358.58
  4991.0  357.78  4996.0  357.78  4996.5  358.58  5023.3  358.89  5045.2  359.65
  5050.9  359.60  5067.1  359.92  5072.8  359.33  5082.8  359.42  5105.2  359.17
  5116.8  359.61  5127.1  359.90  5132.8  360.49  5139.5  360.90  5154.7  361.09
#Mann=3,-1,0
  4761.5    0.16       0  4990.5    0.07       0  4996.5    0.16       0
Bank Sta=4761.5,5116.8
Exp/Cntr=0.3,0.1

Type RM Length L Ch R = 1,2485,102,102,102
BEGIN DESCRIPTION:
Mapping XS b4487ea0
END DESCRIPTION:
XS GIS Cut Line= 3
      2931835.47      6924187.60      2932129.46      6924067.93
      2932250.88      6923977.51
#Sta/Elev= 30
  4687.4  360.16  4773.3  358.67  4794.9  358.75  4805.7  358.39  4827.3  358.65
  4859.6  359.64  4871.3  359.65  4889.9  358.64  4895.3  359.02  4902.8  358.41
  4913.2  358.03  4919.4  357.56  4924.8  357.81  4967.5  357.34  4972.9  357.54
  4986.2  357.16  4986.7  356.36  4991.7  356.36  4992.2  357.16  5029.3  358.03
  5053.5  359.01  5068.1  360.06  5082.7  360.46  5097.3  360.18  5103.5  359.63
  5118.1  359.17  5132.7  359.12  5147.3  359.47  5153.6  359.79  5156.2  360.22
#Mann=3,-1,0
  4687.4    0.16       0  4986.2    0.07       0  4992.2    0.16       0
Bank Sta=4913.2,5029.3
Exp/Cntr=0.3,0.1

Type RM Length L Ch R = 1,2383,290,290,290
BEGIN DESCRIPTION:
Mapping XS 350a884c
END DESCRIPTION:
XS GIS Cut Line= 3
      2931846.58      6924239.27      2932141.77      6924168.08
      2932374.38      6924006.63
#Sta/Elev= 30
  4713.6  359.44  4755.7  359.25  4792.5  358.14  4797.6  358.60  4804.6  357.90
  4814.8  358.51  4834.4  357.76  4839.5  358.04  4876.3  356.67  4923.3  355.83
  4928.4  356.11  4965.2  354.15  4970.3  354.59  4993.3  353.53  5004.1  352.35
  5004.6  351.55  5009.6  351.55  5010.1  352.35  5012.6  353.53  5035.4  354.74
  5044.2  355.70  5050.3  355.15  5057.7  356.00  5086.1  357.07  5115.8  358.85
  5187.4  361.22  5202.2  361.21  5223.2  359.11  5229.3  358.99  5300.4  359.47
#Mann=3,-1,0
  4713.6    0.16       0  5004.1    0.07       0  5010.1    0.16       0
Bank Sta=4993.3,5012.6
Exp/Cntr=0.3,0.1

Type RM Length L Ch R = 1,2093,160,160,160
BEGIN DESCRIPTION:
Mapping XS 4f704b12
END DESCRIPTION:
XS GIS Cut Line= 3
      2931895.27      6924445.85      2932185.17      6924444.12
      2932506.04      6924249.86
#Sta/Elev= 30
  4714.7  358.39  4724.4  357.98  4784.4  359.25  4874.4  359.22  4914.4  356.89
  4955.5  352.74  4984.4  347.51  4991.4  347.37  4991.9  346.57  4996.9  346.57
  4997.4  347.37  5017.3  347.47  5050.4  352.74  5069.6  354.88  5127.8  359.03
  5170.5  359.90  5186.0  360.75  5238.2  359.81  5265.5  361.27  5281.0  360.23
  5286.8  360.65  5296.5  359.96  5317.8  359.81  5323.7  360.44  5339.2  360.36
  5345.0  361.22  5354.7  360.53  5360.5  360.92  5366.8  359.98  5379.7  359.58
#Mann=3,-1,0
  4714.7    0.16       0  4991.4    0.07       0  4997.4    0.16       0
Bank Sta=4955.5,5050.4
Exp/Cntr=0.3,0.1

Type RM Length L Ch R = 1,1933,301,301,301
BEGIN DESCRIPTION:
UNT 080 IN DRY CR WATERSHED 4.0
END DESCRIPTION:
XS GIS Cut Line= 3
      2931975.04      6924575.00      2932275.00      6924575.00
      2932575.00      6924525.00
#Sta/Elev= 30
  4716.3  360.08  4736.3  359.56  4776.3  359.93  4806.3  359.16  4846.3  357.10
  4892.1  352.74  4916.3  351.24  4936.3  351.23  4946.3  350.18  4956.4  347.38
  4960.7  347.37  4963.3  347.37  4963.8  346.57  4968.8  346.57  4969.3  347.37
  5044.1  347.56  5049.2  347.85  5077.1  352.74  5117.6  357.17  5137.9  358.60
  5148.1  358.67  5165.8  357.41  5170.9  358.69  5208.9  357.03  5219.0  357.23
  5231.7  358.88  5269.7  360.61  5287.5  359.18  5292.5  359.95  5320.4  360.70
#Mann=5,-1,0
  4716.3    0.16       0  4956.4    0.05       0  4960.7    0.16       0
  4963.3    0.07       0  4969.3    0.16       0
Bank Sta=4892.1,5077.1
Exp/Cntr=0.3,0.1

Type RM Length L Ch R = 1,1632,222,222,222
BEGIN DESCRIPTION:
UNT 080 IN DRY CR WATERSHED 3.0
END DESCRIPTION:
XS GIS Cut Line= 3
      2931875.00      6924575.00      2932075.00      6924825.00
      2932375.00      6924875.00
#Sta/Elev= 30
  4620.1  360.00  4670.5  359.74  4684.1  360.26  4705.7  359.48  4741.0  359.68
  4798.6  358.48  4833.8  356.35  4854.6  353.85  4862.6  353.62  4866.5  352.73
  4869.0  352.17  4883.4  351.65  4889.8  350.37  4897.8  350.39  4904.2  348.94
  4912.2  348.74  4915.7  347.37  4916.2  346.57  4921.2  346.57  4921.7  347.37
  4935.3  347.37  5041.6  347.37  5064.8  351.02  5077.0  352.73  5094.9  353.56
  5112.6  356.53  5122.7  357.65  5163.3  360.11  5203.8  359.52  5244.4  359.91
#Mann=5,-1,0
  4620.1    0.16       0  4915.7   0.033       0  4921.7    0.16       0
  4935.3    0.05       0  5064.8    0.16       0
Bank Sta=4866.5,5077
Exp/Cntr=0.3,0.1

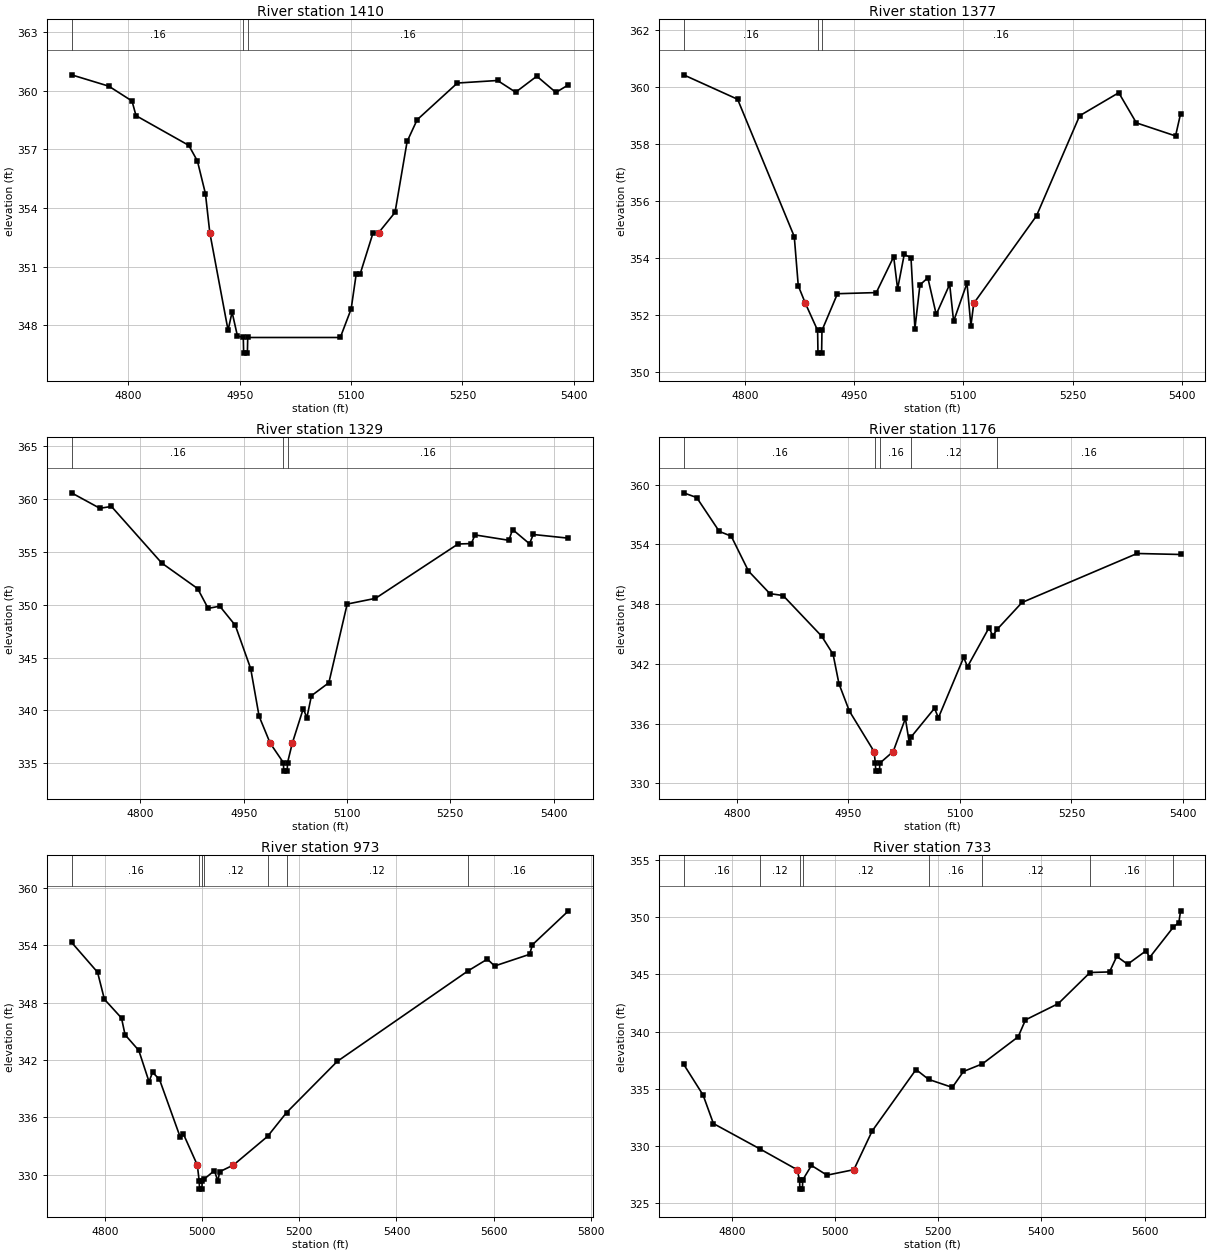
Type RM Length L Ch R = 1,1410,33,33,33
BEGIN DESCRIPTION:
Mapping XS f63d9a04
END DESCRIPTION:
XS GIS Cut Line= 4
      2931878.80      6924936.63      2932089.32      6925025.61
      2932232.55      6925088.54      2932497.30      6924984.38
#Sta/Elev= 30
  4723.3  360.81  4773.5  360.23  4804.8  359.47  4810.2  358.72  4881.3  357.20
  4892.9  356.40  4903.7  354.73  4909.6  352.73  4934.2  347.74  4939.6  348.67
  4946.8  347.45  4954.7  347.37  4955.2  346.57  4960.2  346.57  4960.7  347.37
  5085.4  347.37  5100.0  348.83  5106.9  350.64  5112.3  350.64  5129.3  352.70
  5137.0  352.73  5159.1  353.77  5175.4  357.40  5188.9  358.51  5243.1  360.39
  5297.2  360.52  5321.6  359.92  5350.1  360.74  5375.8  359.91  5392.8  360.30
#Mann=3,-1,0
  4723.3    0.16       0  4954.7    0.07       0  4960.7    0.16       0
Bank Sta=4909.6,5137
Exp/Cntr=0.3,0.1

Type RM Length L Ch R = 1,1377,48,48,48
BEGIN DESCRIPTION:
Mapping XS 46c80dfe
END DESCRIPTION:
XS GIS Cut Line= 4
      2931863.67      6924971.37      2932080.64      6925058.16
      2932247.74      6925127.60      2932497.28      6925027.79
#Sta/Elev= 30
  4715.2  360.44  4789.5  359.58  4867.4  354.75  4872.9  353.02  4882.7  352.40
  4899.5  351.45  4900.0  350.65  4905.0  350.65  4905.5  351.45  4926.8  352.74
  4980.2  352.78  5004.1  354.04  5009.5  352.91  5018.6  354.12  5027.9  354.01
  5033.3  351.51  5040.2  353.05  5051.1  353.30  5062.6  352.01  5081.1  353.07
  5086.5  351.77  5104.9  353.11  5110.3  351.61  5114.2  352.40  5200.5  355.48
  5259.8  359.00  5313.6  359.81  5337.8  358.75  5391.7  358.29  5398.6  359.07
#Mann=3,-1,0
  4715.2    0.16       0  4899.5    0.07       0  4905.5    0.16       0
Bank Sta=4882.7,5114.2
Exp/Cntr=0.3,0.1

Type RM Length L Ch R = 1,1329,153,153,153
BEGIN DESCRIPTION:
Mapping XS f9ec9b37
END DESCRIPTION:
XS GIS Cut Line= 4
      2931850.60      6924993.05      2932132.72      6925131.94
      2932239.06      6925166.67      2932514.63      6925060.34
#Sta/Elev= 30
  4700.0  360.58  4741.1  359.12  4758.0  359.29  4831.0  353.94  4883.2  351.52
  4898.4  349.65  4915.3  349.86  4937.8  348.05  4960.2  343.95  4972.4  339.45
  4988.5  336.90  5007.7  335.06  5008.2  334.26  5013.2  334.26  5013.7  335.06
  5020.6  336.90  5036.5  340.16  5041.8  339.32  5048.4  341.39  5073.7  342.62
  5100.3  350.06  5141.4  350.60  5261.3  355.74  5280.6  355.78  5285.9  356.60
  5335.1  356.09  5340.5  357.11  5365.1  355.76  5370.5  356.64  5421.7  356.29
#Mann=3,-1,0
  4700.0    0.16       0  5007.7    0.07       0  5013.7    0.16       0
Bank Sta=4988.5,5020.6
Exp/Cntr=0.3,0.1

Type RM Length L Ch R = 1,1176,203,203,203
BEGIN DESCRIPTION:
Mapping XS be761fc5
END DESCRIPTION:
XS GIS Cut Line= 3
      2931781.14      6925134.10      2932035.07      6925246.96
      2932411.35      6925141.00
#Sta/Elev= 30
  4728.1  359.18  4745.7  358.71  4776.1  355.31  4792.2  354.83  4815.4  351.33
  4844.2  349.06  4862.0  348.87  4913.9  344.79  4929.3  342.97  4937.2  340.01
  4951.2  337.27  4984.4  333.21  4986.2  332.04  4986.7  331.24  4991.7  331.24
  4992.2  332.04  5010.2  333.21  5026.6  336.53  5031.8  334.10  5034.2  334.66
  5065.8  337.55  5071.0  336.59  5105.0  342.65  5110.2  341.73  5139.1  345.63
  5144.2  344.84  5150.5  345.51  5183.5  348.17  5338.4  353.09  5396.9  352.99
#Mann=5,-1,0
  4728.1    0.16       0  4986.2    0.07       0  4992.2    0.16       0
  5034.2    0.12       0  5150.5    0.16       0
Bank Sta=4984.4,5010.2
Exp/Cntr=0.3,0.1

Type RM Length L Ch R = 1,973,240,240,240
BEGIN DESCRIPTION:
Mapping XS bd2e252f
END DESCRIPTION:
XS GIS Cut Line= 3
      2931761.66      6925242.65      2931985.15      6925455.29
      2932577.56      6925056.01
#Sta/Elev= 30
  4731.2  354.30  4784.8  351.17  4798.9  348.34  4834.1  346.38  4841.4  344.63
  4869.7  342.99  4890.7  339.73  4898.0  340.70  4912.2  339.97  4954.6  333.97
  4961.5  334.25  4990.1  331.01  4994.1  329.29  4994.6  328.49  4999.6  328.49
  5000.1  329.29  5003.3  329.50  5025.4  330.43  5032.3  329.32  5036.1  330.31
  5064.5  331.01  5134.8  334.01  5173.7  336.49  5278.2  341.85  5547.6  351.32
  5587.1  352.54  5602.0  351.82  5674.0  353.04  5680.0  354.05  5754.1  357.59
#Mann=7,-1,0
  4731.2    0.16       0  4994.1    0.07       0  5000.1    0.16       0
  5003.3    0.12       0  5134.8    0.16       0  5173.7    0.12       0
  5547.6    0.16       0
Bank Sta=4990.1,5064.5
Exp/Cntr=0.3,0.1

Type RM Length L Ch R = 1,733,263,263,263
BEGIN DESCRIPTION:
Mapping XS 43b2a8d0
END DESCRIPTION:
XS GIS Cut Line= 3
      2931807.21      6925598.52      2932128.38      6925600.69
      2932563.45      6925128.83
#Sta/Elev= 30
  4706.7  337.16  4744.5  334.46  4764.5  331.97  4854.4  329.76  4926.6  327.94
  4931.5  327.04  4932.0  326.24  4937.0  326.24  4937.5  327.04  4954.5  328.31
  4984.5  327.46  5036.7  327.94  5072.1  331.32  5157.1  336.69  5181.5  335.83
  5227.4  335.13  5249.0  336.52  5285.8  337.19  5355.0  339.55  5369.2  341.03
  5432.7  342.45  5494.3  345.17  5532.0  345.22  5546.1  346.58  5567.1  345.89
  5602.9  347.07  5609.7  346.48  5655.8  349.14  5666.4  349.53  5669.7  350.56
#Mann=8,-1,0
  4706.7    0.16       0  4854.4    0.12       0  4931.5    0.07       0
  4937.5    0.12       0  5181.5    0.16       0  5285.8    0.12       0
  5494.3    0.16       0  5655.8    0.12       0
Bank Sta=4926.6,5036.7
Exp/Cntr=0.3,0.1

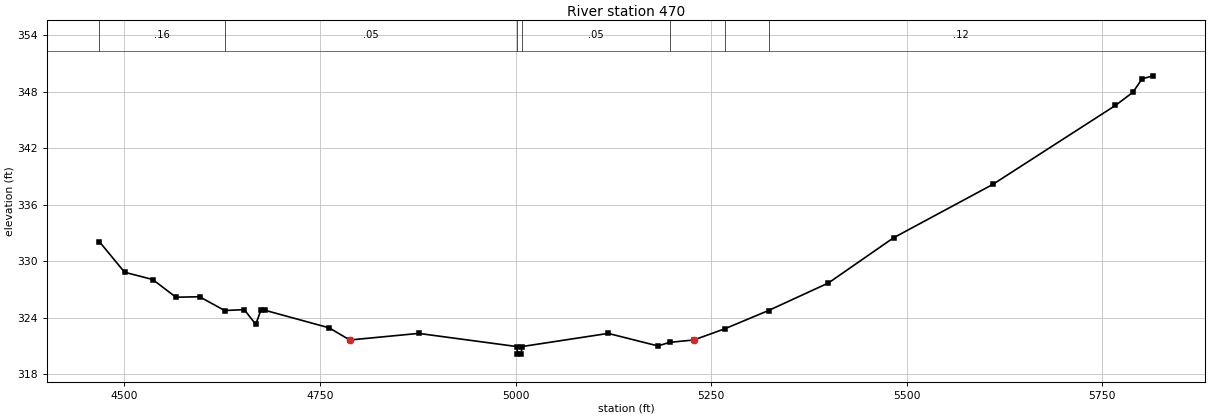
Type RM Length L Ch R = 1,470,0,0,0
BEGIN DESCRIPTION:
UNT 080 IN DRY CR WATERSHED 1.0
END DESCRIPTION:
XS GIS Cut Line= 4
      2931818.04      6925646.26      2932173.96      6925880.64
      2932453.90      6925624.56      2932699.15      6925142.76
#Sta/Elev= 30
  4468.1  332.07  4500.4  328.82  4536.3  328.05  4566.0  326.17  4596.2  326.22
  4628.2  324.76  4653.4  324.85  4668.0  323.28  4674.5  324.80  4680.4  324.77
  4761.8  322.92  4788.1  321.63  4876.2  322.33  5001.9  320.93  5002.4  320.13
  5007.4  320.13  5007.9  320.93  5118.4  322.33  5181.9  321.00  5196.9  321.38
  5227.7  321.63  5267.4  322.82  5323.3  324.76  5399.8  327.68  5483.1  332.48
  5609.8  338.14  5766.7  346.53  5788.9  347.92  5800.6  349.34  5814.3  349.67
#Mann=7,-1,0
  4468.1    0.16       0  4628.2    0.05       0  5001.9    0.03       0
  5007.9    0.05       0  5196.9    0.12       0  5267.4    0.16       0
  5323.3    0.12       0
Bank Sta=4788.1,5227.7
Exp/Cntr=0.3,0.1

Chan Stop Cuts=-1