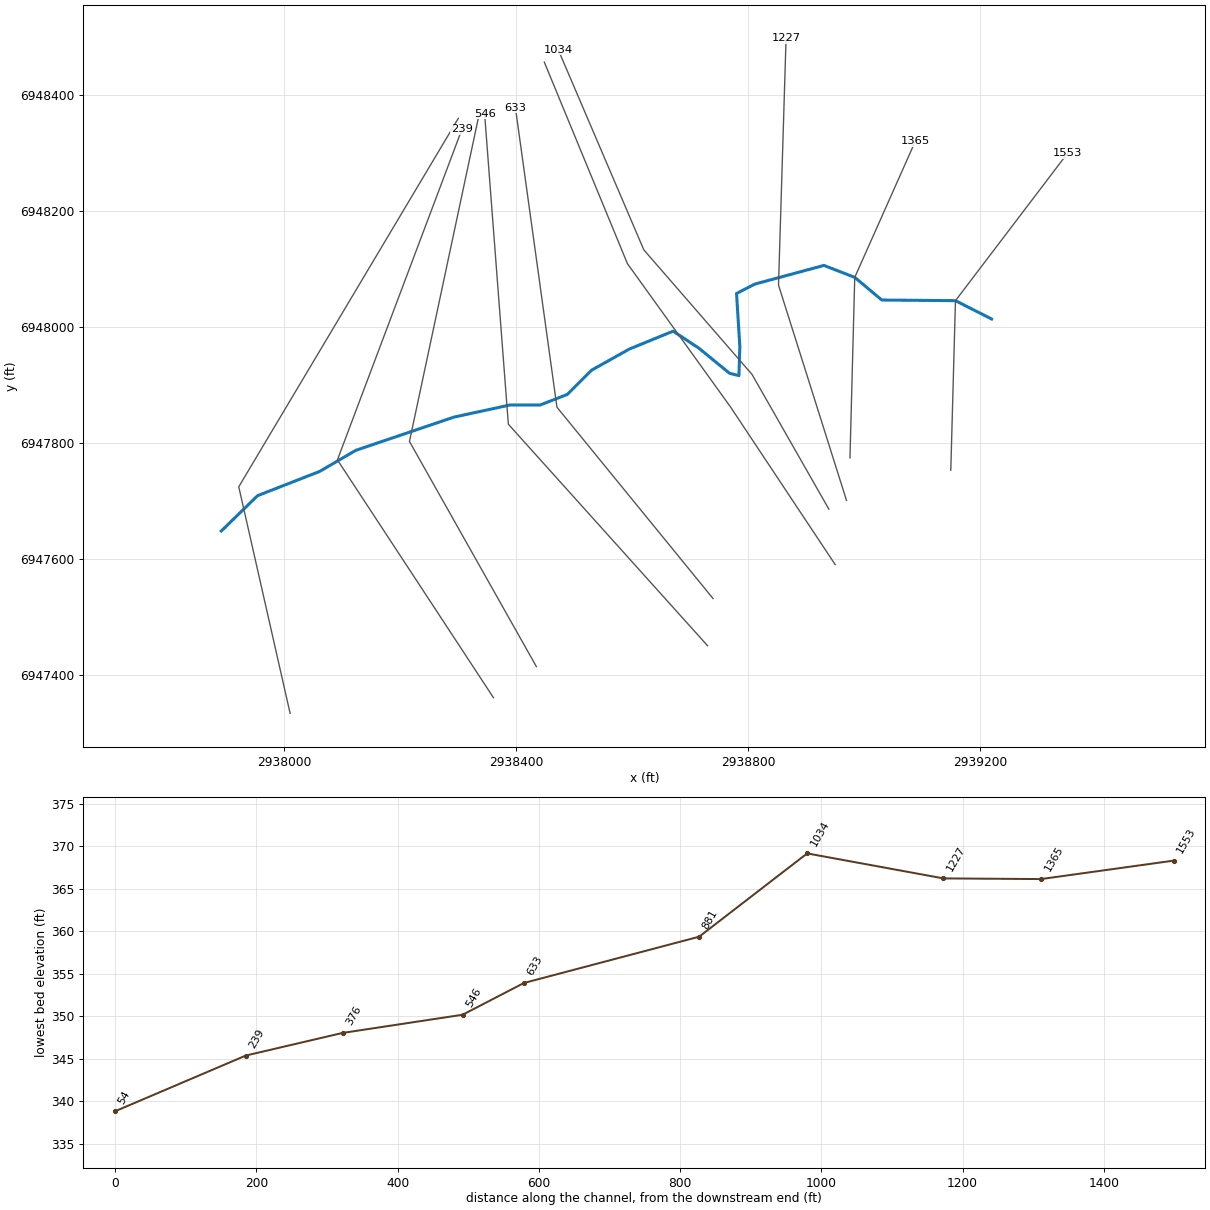
--- UNT 081 IN DRY CR WATERSHED.prj (project) ---

Proj Title=UNT 081 IN DRY CR WATERSHED Base Level Engineering
Current Plan=p01
Default Exp/Contr=0.3,0.1
English Units
Geom File=g01
Flow File=f01
Plan File=p01
BEGIN DESCRIPTION:
UNT 081 IN DRY CR WATERSHED
END DESCRIPTION:

--- UNT 081 IN DRY CR WATERSHED.p01 (plan) ---

Plan Title=Multiple Run
Short Identifier=Multiple
Geom File=g01
Flow File=f01
Subcritical Flow
K Sum by GR= 0
Std Step Tol= 0.01
Critical Tol= 0.01
Num of Std Step Trials= 20
Max Error Tol= 0.3
Flow Tol Ratio= 0.001
Split Flow NTrial= 30
Split Flow Tol= 0.02
Split Flow Ratio= 0.02
Log Output Level= 0
Friction Slope Method= 1
Unsteady Friction Slope Method= 2
Unsteady Bridges Friction Slope Method= 1
Parabolic Critical Depth
Global Vel Dist=  1 , 1 , 1
Global Log Level= 0
CheckData=True
Encroach Param= -1, 0, 0, 0
BEGIN DESCRIPTION:
Multiple Run
END DESCRIPTION:

--- UNT 081 IN DRY CR WATERSHED.f01 (steady flow) ---

Flow Title=Multiple
Number of Profiles=7
Profile Names=10-year,25-year,50-year,1pct_min,100-year,1pct_plu,500-year
River Rch & RM= UNT 081 IN DRY C,Reach-1,1553
     136     166     189     108     215     430     278
Boundary for River Rch & Prof#=UNT 081 IN DRY C,Reach-1,1
Up Type=0
Dn Type=3
Dn Slope=0.005
Boundary for River Rch & Prof#=UNT 081 IN DRY C,Reach-1,2
Up Type=0
Dn Type=3
Dn Slope=0.005
Boundary for River Rch & Prof#=UNT 081 IN DRY C,Reach-1,3
Up Type=0
Dn Type=3
Dn Slope=0.005
Boundary for River Rch & Prof#=UNT 081 IN DRY C,Reach-1,4
Up Type=0
Dn Type=3
Dn Slope=0.005
Boundary for River Rch & Prof#=UNT 081 IN DRY C,Reach-1,5
Up Type=0
Dn Type=3
Dn Slope=0.005
Boundary for River Rch & Prof#=UNT 081 IN DRY C,Reach-1,6
Up Type=0
Dn Type=3
Dn Slope=0.005
Boundary for River Rch & Prof#=UNT 081 IN DRY C,Reach-1,7
Up Type=0
Dn Type=3
Dn Slope=0.005

--- UNT 081 IN DRY CR WATERSHED.g01 (geometry) ---

Geom Title=Existing Conditions

River Reach=UNT 081 IN DRY C,Reach-1
Reach XY= 22
      2939219.15      6948014.41      2939156.85      6948045.98
      2939029.90      6948047.07      2938983.24      6948086.13
      2938930.07      6948106.75      2938810.62      6948074.44
      2938779.51      6948058.32      2938785.15      6947966.86
      2938783.59      6947916.86      2938767.50      6947920.74
      2938714.32      6947964.25      2938670.05      6947993.42
      2938594.47      6947962.46      2938529.37      6947926.00
      2938487.70      6947884.33      2938440.83      6947866.10
      2938388.74      6947866.10      2938292.39      6947845.27
      2938123.12      6947787.98      2938060.62      6947751.52
      2937953.85      6947709.85      2937891.34      6947648.97

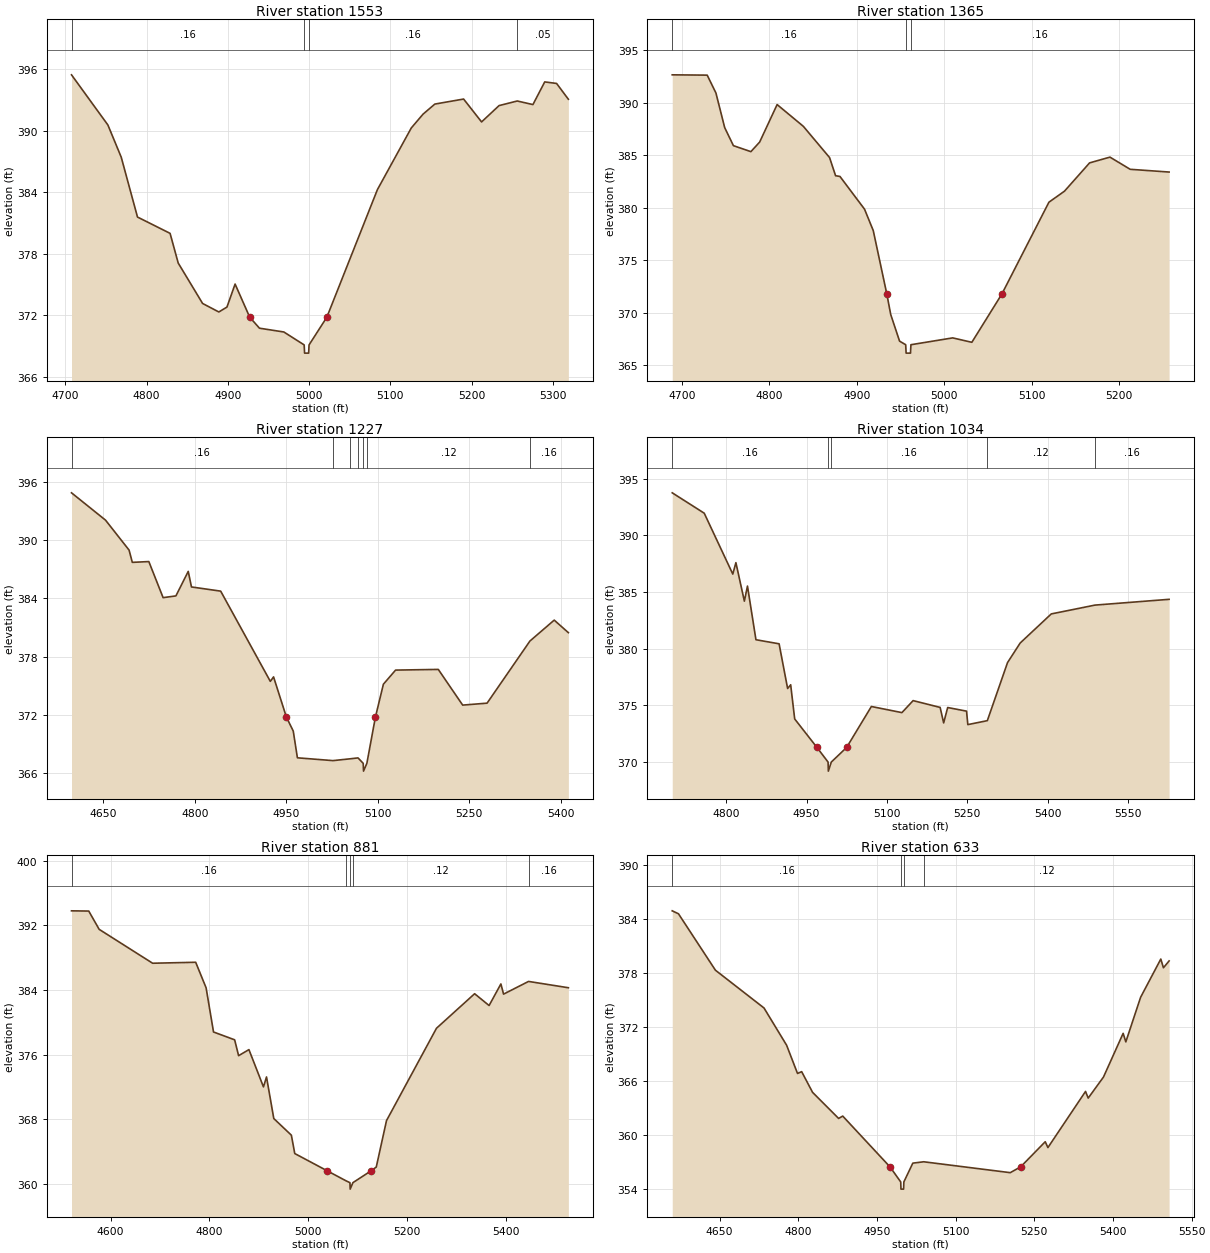
Type RM Length L Ch R = 1,1553,188,188,188
BEGIN DESCRIPTION:
UNT 081 IN DRY CR WATERSHED 4.0
END DESCRIPTION:
XS GIS Cut Line= 3
      2939148.81      6947753.79      2939156.85      6948045.98
      2939349.99      6948299.99
#Sta/Elev= 30
  4707.7  395.45  4752.5  390.56  4768.9  387.42  4788.9  381.59  4829.0  380.00
  4839.0  377.11  4869.0  373.17  4889.0  372.34  4899.0  372.82  4909.0  375.06
  4927.0  371.83  4939.0  370.76  4969.0  370.39  4994.0  369.13  4994.5  368.33
  4999.5  368.33  5000.0  369.13  5021.9  371.83  5084.1  384.26  5125.8  390.27
  5140.3  391.62  5154.8  392.60  5190.2  393.09  5212.3  390.86  5233.8  392.45
  5256.2  392.90  5275.5  392.55  5290.0  394.76  5304.6  394.61  5319.1  393.07
#Mann=4,-1,0
  4707.7    0.16       0  4994.0    0.07       0  5000.0    0.16       0
  5256.2    0.05       0
Bank Sta=4927,5021.9
Exp/Cntr=0.3,0.1

Type RM Length L Ch R = 1,1365,138,138,138
BEGIN DESCRIPTION:
UNT 081 IN DRY CR WATERSHED 3.0
END DESCRIPTION:
XS GIS Cut Line= 3
      2938975.00      6947775.04      2938983.24      6948086.13
      2939087.84      6948321.21
#Sta/Elev= 30
  4688.8  392.64  4728.8  392.61  4738.8  390.91  4748.8  387.62  4758.8  385.90
  4778.8  385.33  4788.8  386.24  4808.8  389.81  4838.8  387.74  4868.8  384.77
  4875.7  383.04  4880.7  382.97  4908.8  379.86  4918.8  377.82  4934.3  371.79
  4938.8  369.83  4948.9  367.30  4955.9  366.96  4956.4  366.16  4961.4  366.16
  4961.9  366.96  5009.7  367.61  5031.6  367.19  5066.0  371.79  5119.8  380.52
  5137.6  381.57  5166.3  384.26  5189.6  384.81  5212.8  383.65  5257.3  383.39
#Mann=3,-1,0
  4688.8    0.16       0  4955.9    0.07       0  4961.9    0.16       0
Bank Sta=4934.3,5066
Exp/Cntr=0.3,0.1

Type RM Length L Ch R = 1,1227,193,193,193
BEGIN DESCRIPTION:
Mapping XS 38fcc3bb
END DESCRIPTION:
XS GIS Cut Line= 3
      2938969.01      6947701.76      2938851.83      6948072.84
      2938864.85      6948498.20
#Sta/Elev= 30
  4598.0  394.86  4653.8  392.05  4692.4  388.97  4697.7  387.71  4724.8  387.79
  4748.2  384.08  4769.2  384.26  4789.4  386.78  4794.7  385.18  4842.6  384.75
  4924.0  375.47  4929.3  375.93  4950.4  371.79  4961.6  370.36  4968.4  367.61
  5026.7  367.32  5053.9  367.50  5067.8  367.60  5076.3  367.04  5076.8  366.24
  5082.3  367.04  5096.3  371.79  5109.4  375.18  5129.4  376.63  5199.4  376.70
  5239.4  373.03  5279.4  373.23  5349.7  379.62  5389.5  381.77  5412.7  380.48
#Mann=7,-1,0
  4598.0    0.16       0  5026.7    0.05       0  5053.9    0.16       0
  5067.8    0.12       0  5076.3    0.07       0  5082.3    0.12       0
  5349.7    0.16       0
Bank Sta=4950.4,5096.3
Exp/Cntr=0.3,0.1

Type RM Length L Ch R = 1,1034,153,153,153
BEGIN DESCRIPTION:
Mapping XS bbb67217
END DESCRIPTION:
XS GIS Cut Line= 4
      2938938.65      6947686.52      2938806.25      6947918.76
      2938619.62      6948133.61      2938472.05      6948478.66
#Sta/Elev= 30
  4699.4  393.77  4759.1  391.97  4812.4  386.59  4818.2  387.60  4834.0  384.20
  4839.8  385.53  4855.6  380.79  4898.8  380.43  4914.7  376.48  4920.4  376.81
  4927.9  373.79  4969.5  371.27  4990.2  369.98  4990.7  369.18  4996.2  369.98
  5024.8  371.27  5071.0  374.89  5128.0  374.35  5148.9  375.41  5199.3  374.81
  5205.9  373.44  5213.4  374.80  5248.6  374.48  5251.0  373.29  5287.4  373.64
  5325.1  378.77  5348.7  380.50  5406.7  383.07  5488.4  383.85  5626.6  384.36
#Mann=5,-1,0
  4699.4    0.16       0  4990.2    0.07       0  4996.2    0.16       0
  5287.4    0.12       0  5488.4    0.16       0
Bank Sta=4969.5,5024.8
Exp/Cntr=0.3,0.1

Type RM Length L Ch R = 1,881,248,248,248
BEGIN DESCRIPTION:
Mapping XS 89af229d
END DESCRIPTION:
XS GIS Cut Line= 4
      2938949.46      6947591.10      2938769.36      6947862.34
      2938591.41      6948109.73      2938448.19      6948456.93
#Sta/Elev= 30
  4520.7  393.79  4555.6  393.76  4576.7  391.50  4684.9  387.31  4772.1  387.43
  4793.2  384.27  4808.2  378.81  4851.0  377.84  4859.0  375.88  4879.9  376.63
  4909.3  372.02  4915.5  373.25  4930.2  368.11  4965.8  366.05  4972.7  363.78
  5038.8  361.63  5076.4  360.41  5084.4  360.18  5084.9  359.38  5090.4  360.18
  5126.8  361.63  5137.7  362.11  5158.4  367.85  5259.6  379.27  5336.8  383.54
  5366.1  382.08  5390.0  384.75  5395.4  383.49  5446.0  385.06  5526.6  384.28
#Mann=5,-1,0
  4520.7    0.16       0  5076.4    0.12       0  5084.4    0.07       0
  5090.4    0.12       0  5446.0    0.16       0
Bank Sta=5038.8,5126.8
Exp/Cntr=0.3,0.1

Type RM Length L Ch R = 1,633,87,87,87
BEGIN DESCRIPTION:
Mapping XS a9e8ee0e
END DESCRIPTION:
XS GIS Cut Line= 3
      2938738.96      6947532.50      2938469.88      6947862.34
      2938398.27      6948378.83
#Sta/Elev= 30
  4559.9  384.88  4571.8  384.55  4642.2  378.28  4734.8  374.08  4777.9  369.94
  4798.7  366.80  4806.6  367.00  4827.4  364.70  4877.0  361.80  4884.9  362.06
  4974.9  356.42  4995.4  354.74  4995.9  353.94  5000.9  353.94  5001.4  354.74
  5018.5  356.83  5039.3  356.98  5204.2  355.77  5224.1  356.42  5270.9  359.21
  5276.0  358.56  5347.7  364.80  5352.8  364.06  5382.0  366.41  5419.4  371.26
  5424.5  370.31  5452.7  375.27  5491.2  379.52  5496.2  378.55  5507.0  379.31
#Mann=4,-1,0
  4559.9    0.16       0  4995.4    0.07       0  5001.4    0.16       0
  5039.3    0.12       0
Bank Sta=4974.9,5224.1
Exp/Cntr=0.3,0.1

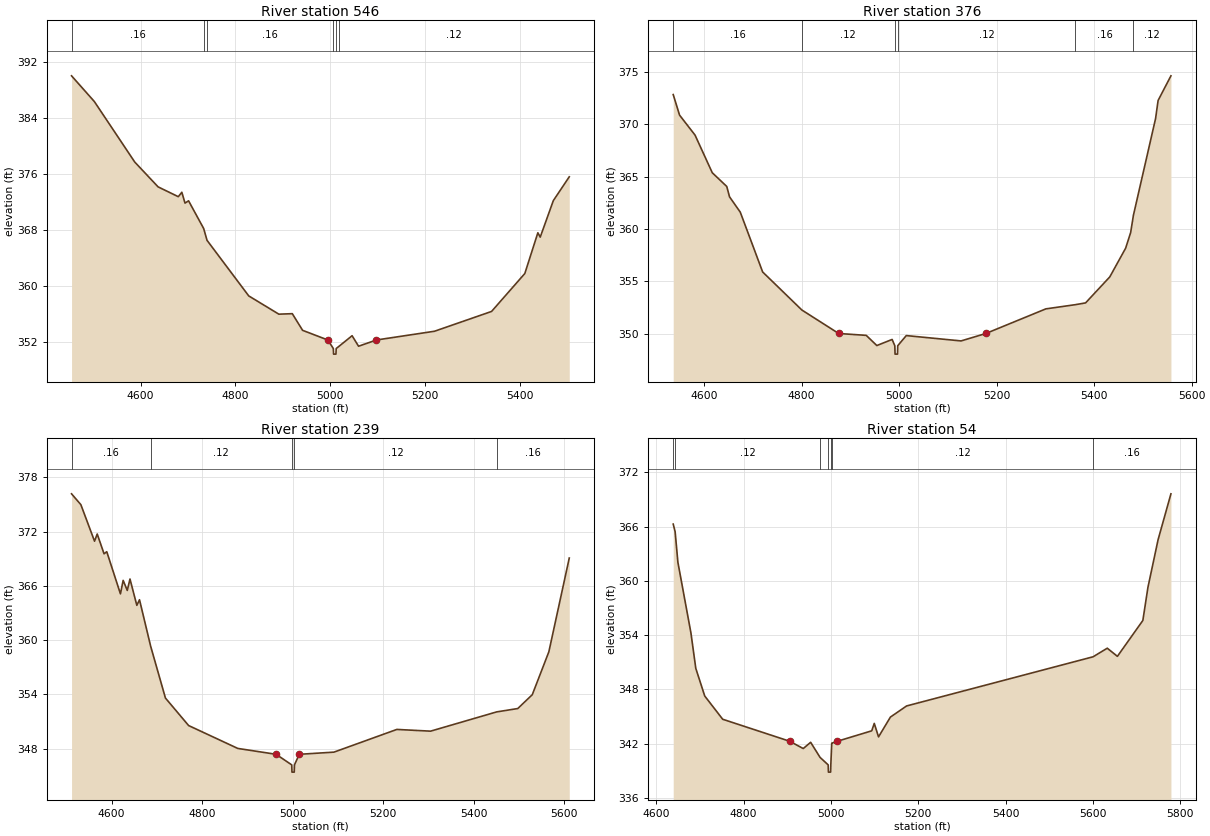
Type RM Length L Ch R = 1,546,170,170,170
BEGIN DESCRIPTION:
Mapping XS 644ce370
END DESCRIPTION:
XS GIS Cut Line= 3
      2938729.50      6947451.20      2938386.12      6947833.02
      2938345.13      6948368.53
#Sta/Elev= 30
  4454.4  389.97  4502.6  386.29  4587.8  377.65  4637.1  374.10  4679.7  372.70
  4687.2  373.33  4693.9  371.78  4701.4  372.11  4733.3  368.15  4740.4  366.46
  4828.4  358.52  4892.0  355.91  4920.4  355.98  4942.1  353.60  4995.4  352.22
  5007.0  351.00  5007.5  350.20  5012.5  350.20  5013.0  351.00  5018.8  351.31
  5046.6  352.83  5060.2  351.33  5098.0  352.22  5220.6  353.47  5341.0  356.30
  5411.2  361.72  5438.7  367.54  5443.7  366.92  5471.4  372.14  5505.0  375.54
#Mann=6,-1,0
  4454.4    0.16       0  4733.3    0.12       0  4740.4    0.16       0
  5007.0    0.07       0  5013.0    0.16       0  5018.8    0.12       0
Bank Sta=4995.4,5098
Exp/Cntr=0.3,0.1

Type RM Length L Ch R = 1,376,137,137,137
BEGIN DESCRIPTION:
Mapping XS 76a842f8
END DESCRIPTION:
XS GIS Cut Line= 3
      2938434.40      6947415.24      2938215.65      6947803.27
      2938335.45      6948365.81
#Sta/Elev= 30
  4536.9  372.83  4549.9  370.87  4581.7  368.96  4617.0  365.37  4646.7  364.06
  4652.4  363.07  4674.4  361.61  4720.3  355.90  4800.7  352.27  4876.2  350.03
  4932.7  349.85  4954.4  348.88  4985.8  349.46  4991.3  348.86  4991.8  348.06
  4996.8  348.06  4997.3  348.86  5014.8  349.83  5127.2  349.32  5178.0  350.03
  5301.1  352.38  5361.7  352.78  5382.5  352.95  5432.1  355.43  5464.6  358.17
  5474.9  359.66  5480.6  361.32  5526.0  370.54  5531.2  372.27  5557.5  374.62
#Mann=6,-1,0
  4536.9    0.16       0  4800.7    0.12       0  4991.3    0.07       0
  4997.3    0.12       0  5361.7    0.16       0  5480.6    0.12       0
Bank Sta=4876.2,5178
Exp/Cntr=0.3,0.1

Type RM Length L Ch R = 1,239,185,185,185
BEGIN DESCRIPTION:
Mapping XS d67c25e8
END DESCRIPTION:
XS GIS Cut Line= 3
      2938360.47      6947361.57      2938091.44      6947771.52
      2938306.14      6948341.48
#Sta/Elev= 30
  4511.4  376.17  4532.0  374.97  4562.2  370.93  4568.1  371.73  4583.2  369.54
  4589.2  369.77  4619.4  365.11  4625.4  366.60  4634.5  365.49  4640.5  366.75
  4655.6  363.84  4661.5  364.46  4686.2  359.31  4718.8  353.59  4770.0  350.55
  4878.6  348.02  4963.3  347.37  4997.8  346.20  4998.3  345.40  5003.3  345.40
  5003.8  346.20  5014.4  347.37  5091.0  347.61  5229.9  350.12  5304.5  349.93
  5450.5  352.06  5497.0  352.43  5529.1  353.96  5565.7  358.70  5610.8  369.07
#Mann=5,-1,0
  4511.4    0.16       0  4686.2    0.12       0  4997.8    0.07       0
  5003.8    0.12       0  5450.5    0.16       0
Bank Sta=4963.3,5014.4
Exp/Cntr=0.3,0.1

Type RM Length L Ch R = 1,54,0,0,0
BEGIN DESCRIPTION:
UNT 081 IN DRY CR WATERSHED 1.0
END DESCRIPTION:
XS GIS Cut Line= 3
      2938009.91      6947334.55      2937921.38      6947725.15
      2938299.83      6948360.23
#Sta/Elev= 30
  4638.9  366.29  4643.3  365.44  4649.6  362.07  4679.5  354.24  4690.6  350.33
  4711.1  347.27  4752.2  344.70  4905.4  342.27  4936.7  341.46  4953.6  342.15
  4975.2  340.48  4993.8  339.65  4994.3  338.85  4999.3  338.85  4999.8  339.65
  5001.9  342.05  5003.1  342.07  5015.0  342.27  5093.5  343.42  5099.3  344.24
  5109.1  342.75  5136.3  344.94  5173.3  346.17  5600.4  351.61  5632.9  352.56
  5656.1  351.66  5714.4  355.63  5726.1  359.31  5749.3  364.57  5778.7  369.64
#Mann=7,-1,0
  4638.9    0.16       0  4643.3    0.12       0  4975.2    0.16       0
  4993.8    0.07       0  4999.8    0.16       0  5003.1    0.12       0
  5600.4    0.16       0
Bank Sta=4905.4,5015
Exp/Cntr=0.3,0.1

Chan Stop Cuts=-1