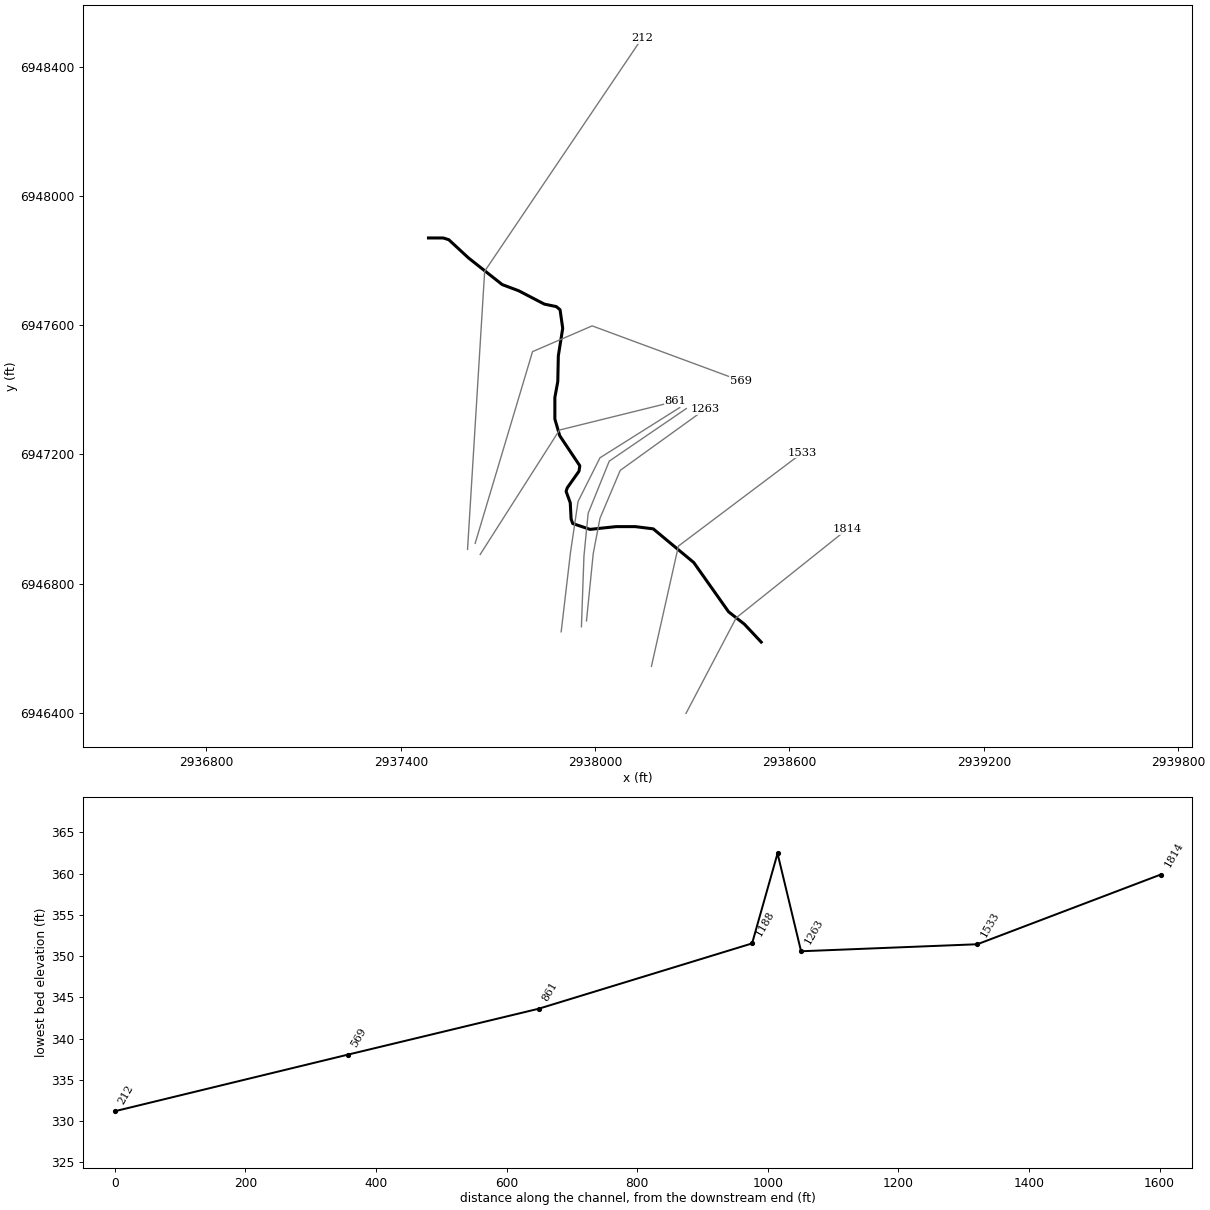
--- UNT 082 IN DRY CR WATERSHED.prj (project) ---

Proj Title=UNT 082 IN DRY CR WATERSHED Base Level Engineering
Current Plan=p01
Default Exp/Contr=0.3,0.1
English Units
Geom File=g01
Flow File=f01
Plan File=p01
BEGIN DESCRIPTION:
UNT 082 IN DRY CR WATERSHED
END DESCRIPTION:

--- UNT 082 IN DRY CR WATERSHED.p01 (plan) ---

Plan Title=Multiple Run
Short Identifier=Multiple
Geom File=g01
Flow File=f01
Subcritical Flow
K Sum by GR= 0
Std Step Tol= 0.01
Critical Tol= 0.01
Num of Std Step Trials= 20
Max Error Tol= 0.3
Flow Tol Ratio= 0.001
Split Flow NTrial= 30
Split Flow Tol= 0.02
Split Flow Ratio= 0.02
Log Output Level= 0
Friction Slope Method= 1
Unsteady Friction Slope Method= 2
Unsteady Bridges Friction Slope Method= 1
Parabolic Critical Depth
Global Vel Dist=  1 , 1 , 1
Global Log Level= 0
CheckData=True
Encroach Param= -1, 0, 0, 0
BEGIN DESCRIPTION:
Multiple Run
END DESCRIPTION:

--- UNT 082 IN DRY CR WATERSHED.f01 (steady flow) ---

Flow Title=Multiple
Number of Profiles=7
Profile Names=10-year,25-year,50-year,1pct_min,100-year,1pct_plu,500-year
River Rch & RM= UNT 082 IN DRY C,Reach-1,1814
     389     517     621     373     744    1485    1066
River Rch & RM= UNT 082 IN DRY C,Reach-1,212
     487     658     799     485     967    1929    1414
Boundary for River Rch & Prof#=UNT 082 IN DRY C,Reach-1,1
Up Type=0
Dn Type=3
Dn Slope=0.005
Boundary for River Rch & Prof#=UNT 082 IN DRY C,Reach-1,2
Up Type=0
Dn Type=3
Dn Slope=0.005
Boundary for River Rch & Prof#=UNT 082 IN DRY C,Reach-1,3
Up Type=0
Dn Type=3
Dn Slope=0.005
Boundary for River Rch & Prof#=UNT 082 IN DRY C,Reach-1,4
Up Type=0
Dn Type=3
Dn Slope=0.005
Boundary for River Rch & Prof#=UNT 082 IN DRY C,Reach-1,5
Up Type=0
Dn Type=3
Dn Slope=0.005
Boundary for River Rch & Prof#=UNT 082 IN DRY C,Reach-1,6
Up Type=0
Dn Type=3
Dn Slope=0.005
Boundary for River Rch & Prof#=UNT 082 IN DRY C,Reach-1,7
Up Type=0
Dn Type=3
Dn Slope=0.005

--- UNT 082 IN DRY CR WATERSHED.g01 (geometry) ---

Geom Title=Existing Conditions

River Reach=UNT 082 IN DRY C,Reach-1
Reach XY= 30
      2938512.76      6946618.95      2938460.68      6946674.51
      2938412.06      6946712.70      2938304.43      6946865.48
      2938179.43      6946969.65      2938123.87      6946976.59
      2938064.84      6946976.59      2937984.24      6946968.06
      2937930.84      6946986.17      2937925.90      6946999.99
      2937923.22      6947050.47      2937910.41      6947085.78
      2937914.16      6947097.01      2937950.27      6947148.28
      2937952.77      6947165.00      2937890.73      6947258.12
      2937875.70      6947309.93      2937875.74      6947376.66
      2937884.74      6947426.05      2937886.41      6947505.42
      2937899.96      6947590.95      2937891.74      6947648.39
      2937880.03      6947658.13      2937843.27      6947665.79
      2937764.11      6947707.13      2937713.19      6947726.29
      2937609.06      6947808.85      2937548.28      6947865.25
      2937531.44      6947870.63      2937485.59      6947870.71

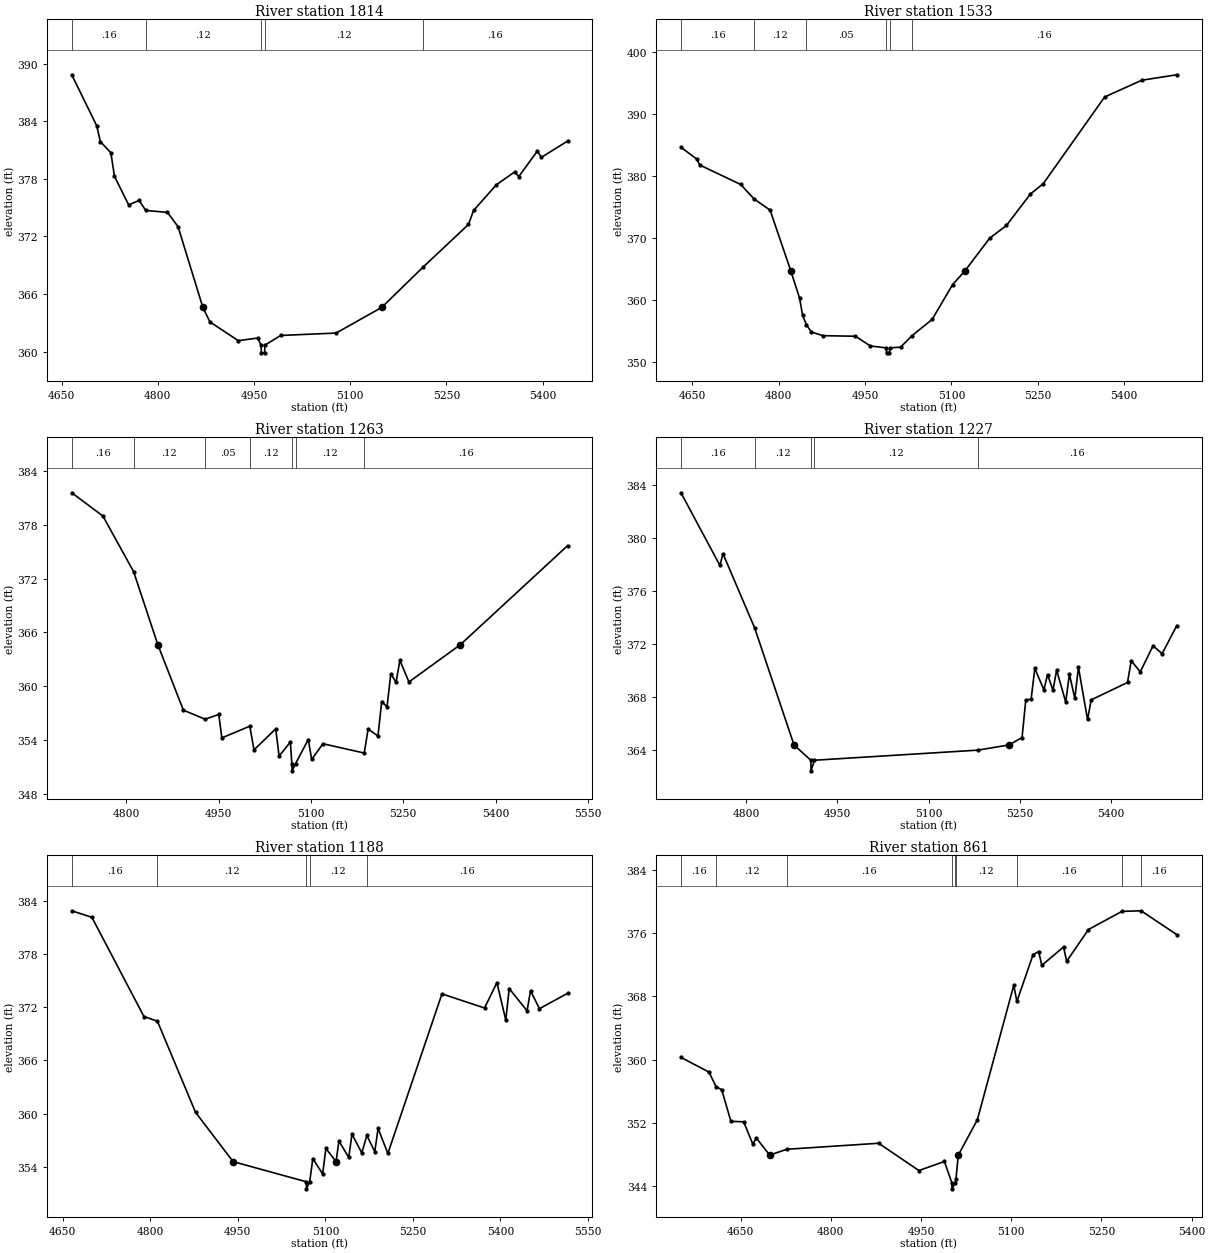
Type RM Length L Ch R = 1,1814,281,281,281
BEGIN DESCRIPTION:
UNT 082 IN DRY CR WATERSHED 2.0
END DESCRIPTION:
XS GIS Cut Line= 3
      2938280.60      6946398.12      2938435.64      6946694.18
      2938778.02      6946968.47
#Sta/Elev= 30
  4665.8  388.84  4704.7  383.53  4710.3  381.89  4726.8  380.71  4732.4  378.26
  4754.5  375.29  4770.9  375.75  4781.1  374.71  4815.0  374.51  4831.5  373.02
  4870.2  364.61  4881.2  363.10  4925.4  361.15  4955.8  361.42  4960.9  360.68
  4961.4  359.88  4966.4  359.88  4966.9  360.68  4991.6  361.69  5077.9  361.94
  5149.0  364.61  5213.1  368.78  5284.3  373.25  5292.3  374.71  5327.6  377.37
  5356.4  378.73  5362.8  378.24  5391.6  380.89  5398.0  380.24  5438.7  381.93
#Mann=5,-1,0
  4665.8    0.16       0  4781.1    0.12       0  4960.9    0.07       0
  4966.9    0.12       0  5213.1    0.16       0
Bank Sta=4870.2,5149
Exp/Cntr=0.3,0.1

Type RM Length L Ch R = 1,1533,270,270,270
BEGIN DESCRIPTION:
Mapping XS 280f9fd8
END DESCRIPTION:
XS GIS Cut Line= 3
      2938173.84      6946543.95      2938257.18      6946916.37
      2938639.97      6947205.42
#Sta/Elev= 30
  4630.2  384.61  4657.7  382.71  4662.8  381.75  4733.8  378.62  4756.9  376.30
  4785.0  374.47  4821.2  364.61  4836.2  360.28  4841.5  357.47  4848.1  355.97
  4856.7  354.79  4877.2  354.20  4933.4  354.11  4959.2  352.54  4986.9  352.23
  4987.4  351.43  4992.4  351.43  4992.9  352.23  5011.8  352.35  5031.4  354.18
  5066.6  356.83  5102.0  362.43  5123.1  364.61  5166.5  369.94  5195.6  371.99
  5237.3  377.07  5259.7  378.75  5366.3  392.74  5430.8  395.44  5491.5  396.32
#Mann=6,-1,0
  4630.2    0.16       0  4756.9    0.12       0  4848.1    0.05       0
  4986.9   0.033       0  4992.9    0.05       0  5031.4    0.16       0
Bank Sta=4821.2,5123.1
Exp/Cntr=0.3,0.1

Type RM Length L Ch R = 1,1263,36,36,36
BEGIN DESCRIPTION:
Mapping XS cad7d4be
END DESCRIPTION:
XS GIS Cut Line= 5
      2937973.32      6946684.61      2937994.16      6946892.94
      2938014.99      6947002.31      2938077.49      6947150.75
      2938339.70      6947340.27
#Sta/Elev= 30
  4711.5  381.55  4762.1  378.96  4812.0  372.76  4851.4  364.61  4892.8  357.34
  4928.1  356.33  4950.3  356.86  4955.3  354.25  5000.7  355.55  5007.5  352.91
  5042.8  355.26  5048.3  352.22  5066.6  353.79  5069.0  351.38  5069.5  350.58
  5075.0  351.38  5095.7  354.07  5101.2  351.85  5119.5  353.60  5186.6  352.56
  5192.9  355.23  5208.9  354.46  5215.0  358.30  5223.6  357.70  5229.8  361.39
  5238.3  360.44  5244.5  362.88  5259.2  360.48  5342.4  364.61  5516.8  375.65
#Mann=7,-1,0
  4711.5    0.16       0  4812.0    0.12       0  4928.1    0.05       0
  5000.7    0.12       0  5069.0   0.033       0  5075.0    0.12       0
  5186.6    0.16       0
Bank Sta=4851.4,5342.4
Exp/Cntr=0.3,0.1

Type RM Length L Ch R = 1,1227,39,39,39
BEGIN DESCRIPTION:
Mapping XS dfc9f775
END DESCRIPTION:
XS GIS Cut Line= 5
      2937957.70      6946666.42      2937965.51      6946885.12
      2937978.53      6947017.94      2938043.64      6947179.40
      2938281.60      6947342.35
#Sta/Elev= 30
  4692.9  383.40  4756.9  377.92  4761.9  378.81  4814.0  373.21  4878.7  364.39
  4906.2  363.24  4906.7  362.44  4912.2  363.24  5180.7  364.00  5231.8  364.39
  5253.5  364.95  5259.6  367.77  5268.4  367.85  5274.5  370.16  5289.4  368.54
  5295.4  369.70  5304.3  368.51  5310.3  370.03  5325.3  367.62  5331.3  369.73
  5340.2  367.91  5346.2  370.24  5361.1  366.31  5367.2  367.79  5426.8  369.10
  5432.9  370.74  5447.8  369.90  5468.8  371.87  5483.7  371.27  5507.7  373.38
#Mann=5,-1,0
  4692.9    0.16       0  4814.0    0.12       0  4906.2    0.07       0
  4912.2    0.12       0  5180.7    0.16       0
Bank Sta=4878.7,5231.8
Exp/Cntr=0.3,0.1

Type RM Length L Ch R = 1,1188,327,327,327
BEGIN DESCRIPTION:
Mapping XS 9482caa8
END DESCRIPTION:
XS GIS Cut Line= 5
      2937895.20      6946650.73      2937923.84      6946895.54
      2937947.28      6947054.40      2938014.99      6947189.81
      2938261.23      6947345.34
#Sta/Elev= 30
  4665.3  382.88  4699.8  382.14  4789.0  370.96  4812.1  370.43  4877.4  360.16
  4941.8  354.60  5067.1  352.33  5067.6  351.53  5073.1  352.33  5078.5  354.94
  5095.3  353.21  5100.9  356.08  5118.3  354.60  5123.2  356.93  5140.0  355.07
  5145.6  357.69  5162.4  355.58  5171.1  357.55  5184.7  355.72  5190.3  358.34
  5207.1  355.52  5299.8  373.51  5372.8  371.92  5394.0  374.78  5409.2  370.57
  5415.1  374.11  5445.7  371.60  5451.6  373.87  5466.9  371.84  5515.0  373.57
#Mann=5,-1,0
  4665.3    0.16       0  4812.1    0.12       0  5067.1    0.07       0
  5073.1    0.12       0  5171.1    0.16       0
Bank Sta=4941.8,5118.3
Exp/Cntr=0.3,0.1

Type RM Length L Ch R = 1,861,292,292,292
BEGIN DESCRIPTION:
Mapping XS 4e21be8b
END DESCRIPTION:
XS GIS Cut Line= 3
      2937645.22      6946890.37      2937889.99      6947275.75
      2938246.73      6947364.28
#Sta/Elev= 30
  4551.0  360.28  4597.6  358.41  4609.4  356.56  4618.7  356.18  4634.0  352.17
  4655.2  352.11  4670.4  349.28  4676.3  350.06  4698.4  347.89  4727.1  348.63
  4879.6  349.39  4946.5  345.93  4988.9  347.08  5001.1  344.41  5001.6  343.61
  5007.1  344.41  5008.0  344.80  5012.0  347.89  5043.6  352.35  5104.2  369.42
  5109.4  367.37  5136.3  373.31  5145.6  373.70  5150.8  371.95  5187.0  374.28
  5192.1  372.45  5228.3  376.49  5283.9  378.79  5315.9  378.87  5375.1  375.85
#Mann=9,-1,0
  4551.0    0.16       0  4609.4    0.12       0  4727.1    0.16       0
  5001.1    0.07       0  5007.1    0.16       0  5008.0    0.12       0
  5109.4    0.16       0  5283.9    0.12       0  5315.9    0.16       0
Bank Sta=4698.4,5012
Exp/Cntr=0.3,0.1

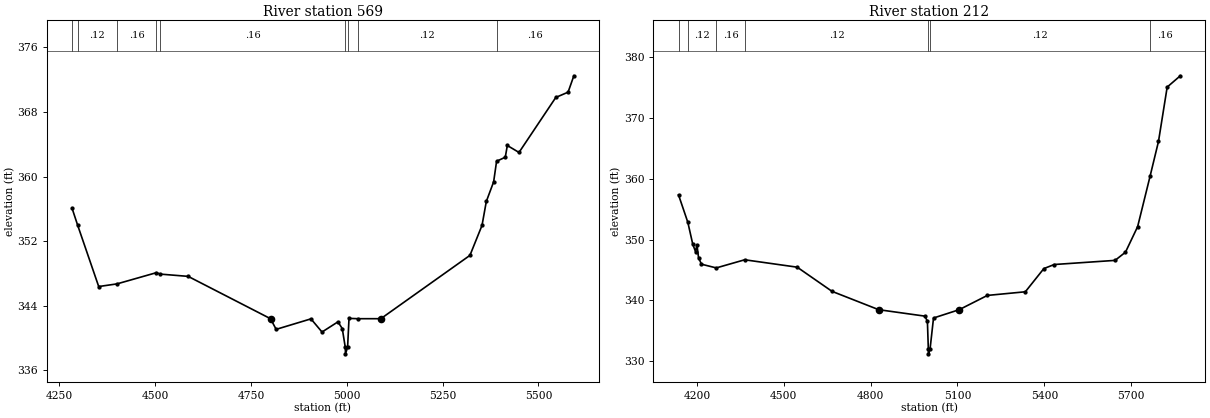
Type RM Length L Ch R = 1,569,357,357,357
BEGIN DESCRIPTION:
Mapping XS 64c63171
END DESCRIPTION:
XS GIS Cut Line= 4
      2937629.71      6946924.78      2937806.79      6947518.55
      2937990.82      6947598.41      2938449.14      6947428.28
#Sta/Elev= 30
  4283.3  356.07  4297.8  353.98  4352.8  346.38  4400.6  346.71  4503.5  348.10
  4513.2  347.92  4586.1  347.64  4801.0  342.40  4815.7  341.08  4906.5  342.38
  4935.4  340.75  4976.9  342.01  4988.2  341.18  4996.1  338.85  4996.6  338.05
  5002.1  338.85  5005.8  342.44  5028.7  342.40  5088.8  342.40  5321.3  350.24
  5352.8  353.95  5364.0  356.91  5383.1  359.34  5390.8  361.89  5413.5  362.39
  5418.8  363.84  5449.3  362.98  5545.3  369.79  5577.3  370.44  5592.4  372.47
#Mann=9,-1,0
  4283.3    0.16       0  4297.8    0.12       0  4400.6    0.16       0
  4503.5    0.12       0  4513.2    0.16       0  4996.1    0.07       0
  5002.1    0.16       0  5028.7    0.12       0  5390.8    0.16       0
Bank Sta=4801,5088.8
Exp/Cntr=0.3,0.1

Type RM Length L Ch R = 1,212,0,0,0
BEGIN DESCRIPTION:
UNT 082 IN DRY CR WATERSHED 1.0
END DESCRIPTION:
XS GIS Cut Line= 3
      2937606.14      6946905.99      2937659.00      6947767.57
      2938144.47      6948489.04
#Sta/Elev= 30
  4136.8  357.36  4168.9  352.85  4185.9  349.25  4195.4  348.03  4200.4  349.16
  4205.9  347.01  4216.0  345.95  4267.1  345.34  4365.3  346.68  4546.6  345.46
  4666.8  341.48  4828.0  338.46  4987.4  337.40  4996.2  336.56  4999.4  331.99
  4999.9  331.19  5005.4  331.99  5017.3  337.09  5106.0  338.46  5203.3  340.81
  5334.4  341.41  5398.3  345.23  5434.3  345.90  5644.2  346.58  5680.2  347.93
  5722.2  352.14  5765.3  360.47  5794.2  366.17  5824.2  375.12  5869.6  376.98
#Mann=7,-1,0
  4136.8    0.16       0  4168.9    0.12       0  4267.1    0.16       0
  4365.3    0.12       0  4999.4    0.07       0  5005.4    0.12       0
  5765.3    0.16       0
Bank Sta=4828,5106
Exp/Cntr=0.3,0.1

Chan Stop Cuts=-1