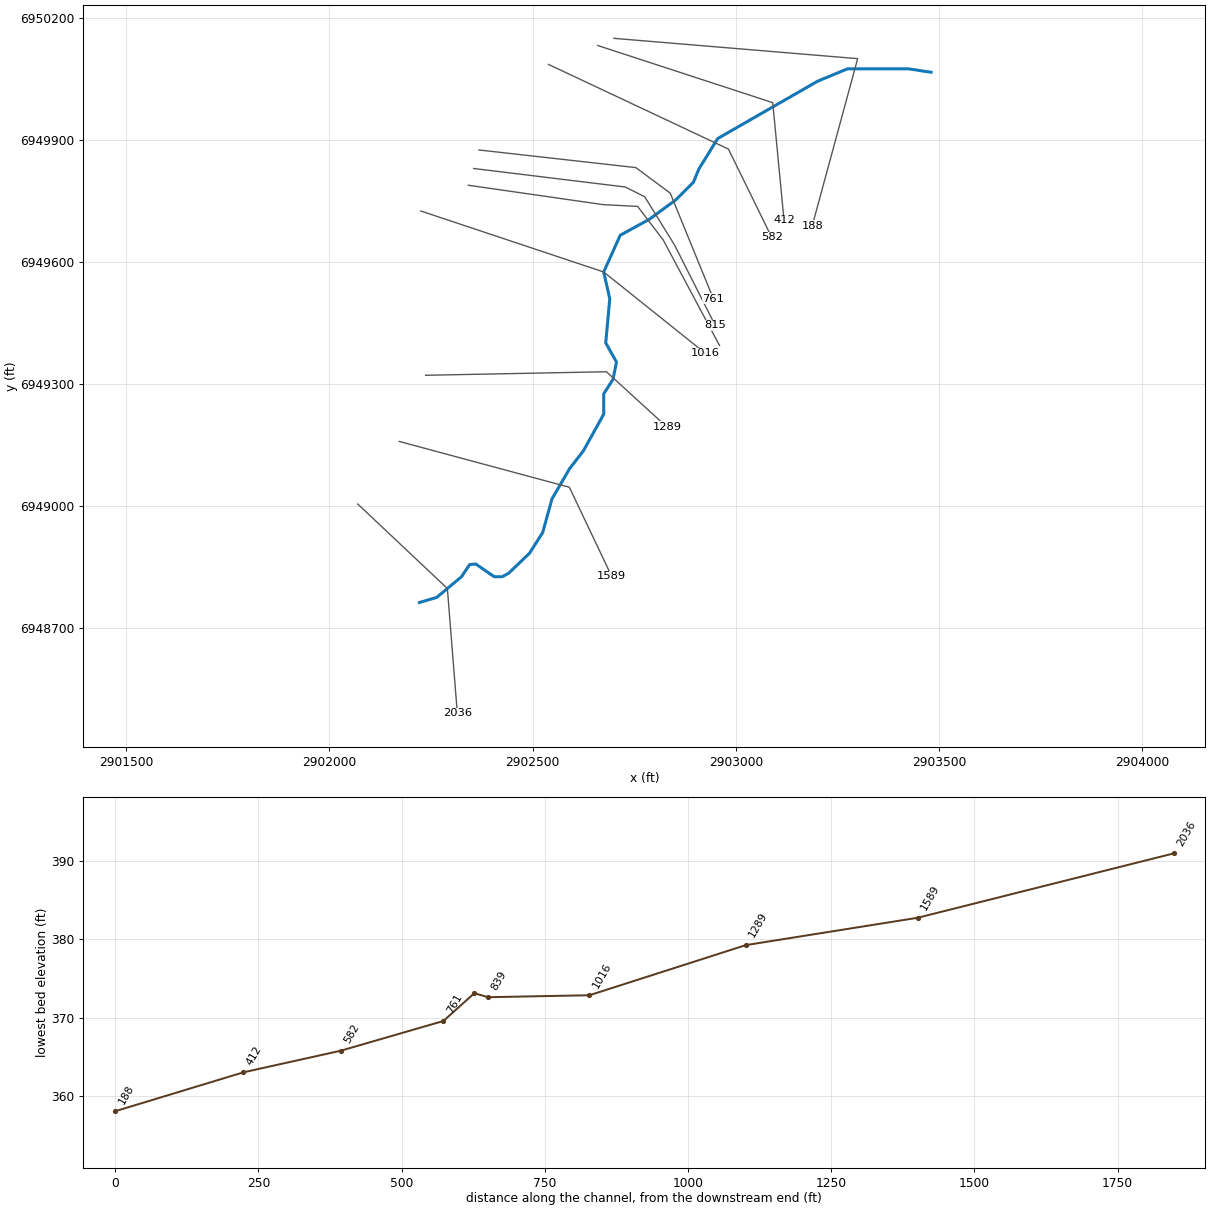
--- UNT 083 IN DRY CR WATERSHED.prj (project) ---

Proj Title=UNT 083 IN DRY CR WATERSHED Base Level Engineering
Current Plan=p01
Default Exp/Contr=0.3,0.1
English Units
Geom File=g01
Flow File=f01
Plan File=p01
BEGIN DESCRIPTION:
UNT 083 IN DRY CR WATERSHED
END DESCRIPTION:

--- UNT 083 IN DRY CR WATERSHED.p01 (plan) ---

Plan Title=Multiple Run
Short Identifier=Multiple
Geom File=g01
Flow File=f01
Subcritical Flow
K Sum by GR= 0
Std Step Tol= 0.01
Critical Tol= 0.01
Num of Std Step Trials= 20
Max Error Tol= 0.3
Flow Tol Ratio= 0.001
Split Flow NTrial= 30
Split Flow Tol= 0.02
Split Flow Ratio= 0.02
Log Output Level= 0
Friction Slope Method= 1
Unsteady Friction Slope Method= 2
Unsteady Bridges Friction Slope Method= 1
Parabolic Critical Depth
Global Vel Dist=  1 , 1 , 1
Global Log Level= 0
CheckData=True
Encroach Param= -1, 0, 0, 0
BEGIN DESCRIPTION:
Multiple Run
END DESCRIPTION:

--- UNT 083 IN DRY CR WATERSHED.f01 (steady flow) ---

Flow Title=Multiple
Number of Profiles=7
Profile Names=10-year,25-year,50-year,1pct_min,100-year,1pct_plu,500-year
River Rch & RM= UNT 083 IN DRY C,Reach-1,2036
      89     106     118      66     132     263     163
Boundary for River Rch & Prof#=UNT 083 IN DRY C,Reach-1,1
Up Type=0
Dn Type=3
Dn Slope=0.005
Boundary for River Rch & Prof#=UNT 083 IN DRY C,Reach-1,2
Up Type=0
Dn Type=3
Dn Slope=0.005
Boundary for River Rch & Prof#=UNT 083 IN DRY C,Reach-1,3
Up Type=0
Dn Type=3
Dn Slope=0.005
Boundary for River Rch & Prof#=UNT 083 IN DRY C,Reach-1,4
Up Type=0
Dn Type=3
Dn Slope=0.005
Boundary for River Rch & Prof#=UNT 083 IN DRY C,Reach-1,5
Up Type=0
Dn Type=3
Dn Slope=0.005
Boundary for River Rch & Prof#=UNT 083 IN DRY C,Reach-1,6
Up Type=0
Dn Type=3
Dn Slope=0.005
Boundary for River Rch & Prof#=UNT 083 IN DRY C,Reach-1,7
Up Type=0
Dn Type=3
Dn Slope=0.005

--- UNT 083 IN DRY CR WATERSHED.g01 (geometry) ---

Geom Title=Existing Conditions

River Reach=UNT 083 IN DRY C,Reach-1
Reach XY= 30
      2902221.57      6948761.57      2902263.93      6948774.07
      2902325.00      6948825.00      2902345.18      6948854.97
      2902360.05      6948856.37      2902405.62      6948825.00
      2902425.00      6948825.00      2902440.77      6948833.37
      2902492.42      6948882.85      2902525.00      6948934.06
      2902547.55      6949016.10      2902591.05      6949091.05
      2902625.00      6949134.80      2902675.00      6949225.00
      2902675.00      6949275.00      2902697.78      6949310.57
      2902706.46      6949353.54      2902679.98      6949400.42
      2902689.96      6949508.93      2902675.00      6949575.00
      2902715.66      6949665.34      2902786.84      6949704.40
      2902852.26      6949752.26      2902895.86      6949795.86
      2902909.01      6949828.02      2902955.50      6949903.36
      2903201.44      6950044.47      2903275.00      6950075.00
      2903425.00      6950075.00      2903480.71      6950066.47

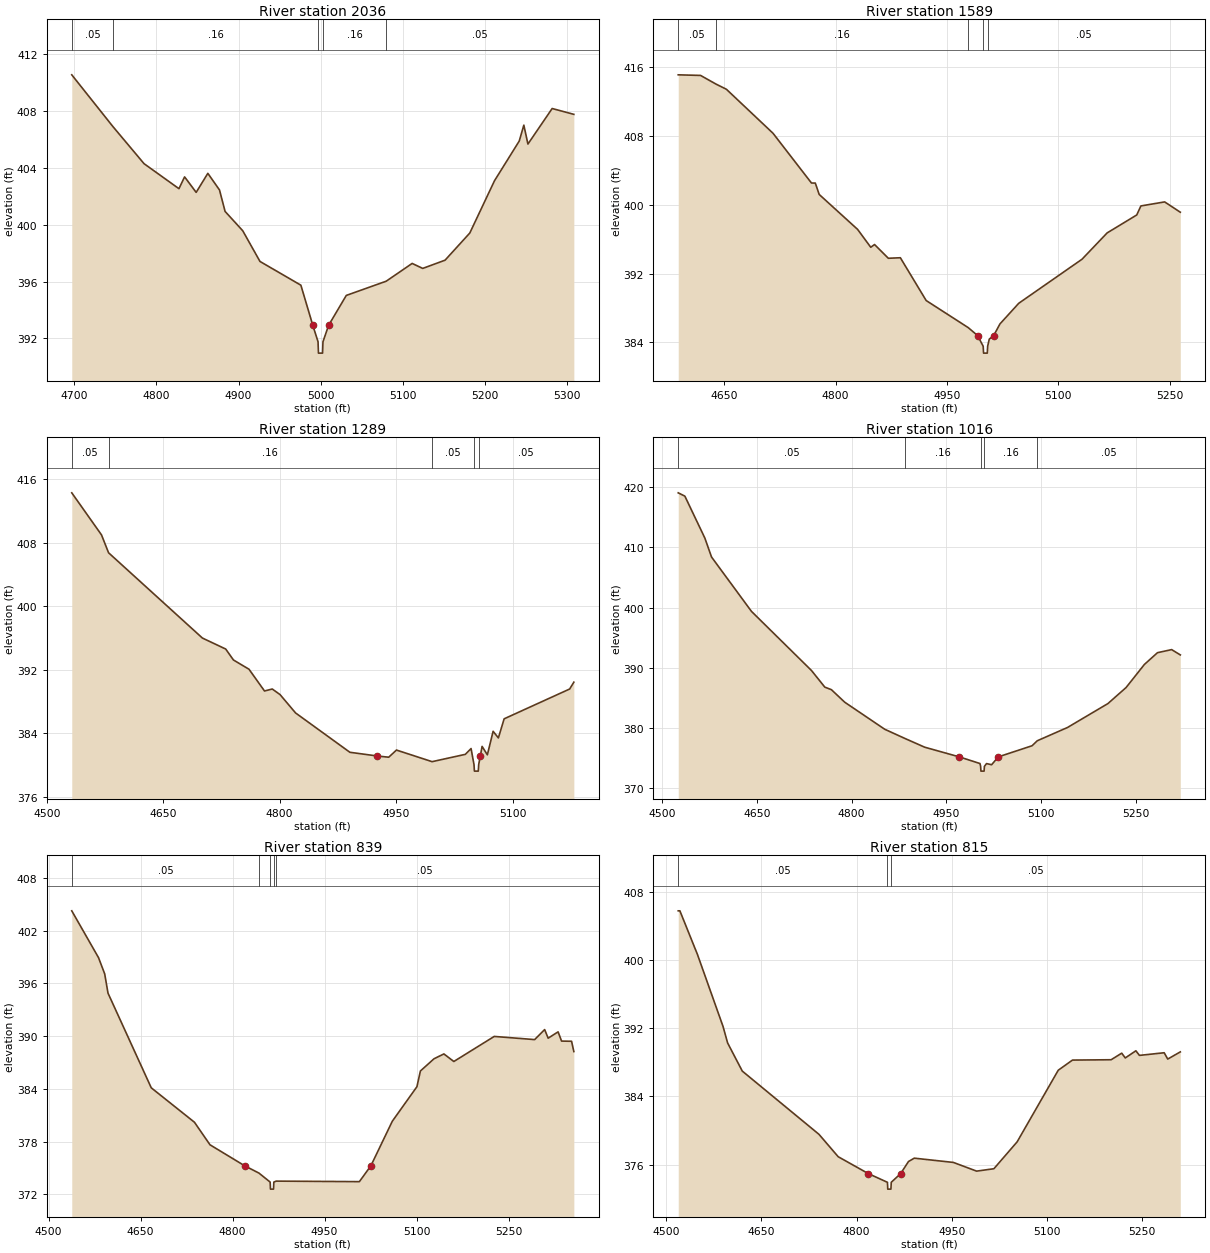
Type RM Length L Ch R = 1,2036,447,447,447
BEGIN DESCRIPTION:
UNT 083 IN DRY CR WATERSHED 5.0
END DESCRIPTION:
XS GIS Cut Line= 3
      2902069.70      6949003.92      2902290.29      6948796.05
      2902314.79      6948488.73
#Sta/Elev= 30
  4696.9  410.55  4747.0  406.91  4784.9  404.30  4827.4  402.54  4834.3  403.37
  4848.4  402.28  4862.6  403.62  4876.8  402.45  4883.6  400.94  4905.1  399.58
  4926.1  397.42  4975.9  395.75  4990.4  392.93  4996.8  391.77  4997.3  390.97
  5002.3  390.97  5002.8  391.77  5009.7  392.93  5031.2  395.03  5079.8  396.03
  5111.4  397.28  5124.3  396.93  5151.5  397.51  5181.6  399.42  5211.7  403.10
  5241.8  405.89  5247.4  407.01  5252.4  405.68  5281.9  408.18  5308.3  407.77
#Mann=5,-1,0
  4696.9    0.05       0  4747.0    0.16       0  4996.8    0.07       0
  5002.8    0.16       0  5079.8    0.05       0
Bank Sta=4990.4,5009.7
Exp/Cntr=0.3,0.1

Type RM Length L Ch R = 1,1589,300,300,300
BEGIN DESCRIPTION:
Mapping XS b8d7d3ae
END DESCRIPTION:
XS GIS Cut Line= 3
      2902171.66      6949158.04      2902590.50      6949045.19
      2902694.68      6948825.97
#Sta/Elev= 30
  4587.9  415.14  4618.0  415.07  4638.4  414.08  4652.8  413.46  4715.6  408.34
  4767.4  402.55  4772.6  402.54  4777.8  401.22  4829.6  397.15  4847.3  395.07
  4852.4  395.39  4871.0  393.79  4887.2  393.85  4922.0  388.87  4978.6  385.72
  4991.2  384.80  4998.8  383.55  4999.3  382.75  5004.3  382.75  5004.8  383.55
  5007.0  384.38  5013.0  384.80  5021.4  386.15  5046.7  388.55  5132.0  393.68
  5165.8  396.74  5205.7  398.83  5211.3  399.88  5243.3  400.35  5264.4  399.15
#Mann=5,-1,0
  4587.9    0.05       0  4638.4    0.16       0  4978.6    0.05       0
  4998.8    0.03       0  5004.8    0.05       0
Bank Sta=4991.2,5013
Exp/Cntr=0.3,0.1

Type RM Length L Ch R = 1,1289,273,273,273
BEGIN DESCRIPTION:
Mapping XS 2aa0c02d
END DESCRIPTION:
XS GIS Cut Line= 3
      2902236.74      6949320.79      2902681.65      6949329.48
      2902830.68      6949193.40
#Sta/Elev= 30
  4532.2  414.27  4570.5  408.98  4579.6  406.73  4700.5  396.00  4730.5  394.62
  4740.5  393.24  4760.5  392.08  4780.5  389.34  4790.5  389.59  4800.5  388.89
  4820.5  386.58  4890.5  381.63  4926.0  381.16  4940.5  381.01  4950.5  381.91
  4996.4  380.45  5039.2  381.37  5046.6  382.10  5050.4  380.06  5050.9  379.26
  5055.9  379.26  5056.4  380.06  5058.5  381.16  5060.8  382.37  5067.6  381.31
  5075.0  384.27  5081.8  383.44  5089.2  385.84  5173.6  389.59  5179.0  390.45
#Mann=5,-1,0
  4532.2    0.05       0  4579.6    0.16       0  4996.4    0.05       0
  5050.4    0.03       0  5056.4    0.05       0
Bank Sta=4926,5058.5
Exp/Cntr=0.3,0.1

Type RM Length L Ch R = 1,1016,177,177,177
BEGIN DESCRIPTION:
UNT 083 IN DRY CR WATERSHED 3.0
END DESCRIPTION:
XS GIS Cut Line= 3
      2902225.04      6949724.99      2902675.00      6949575.00
      2902925.03      6949374.97
#Sta/Elev= 30
  4525.7  419.03  4536.2  418.48  4567.8  411.53  4578.4  408.38  4641.6  399.36
  4736.5  389.56  4757.6  386.80  4768.1  386.37  4789.2  384.29  4852.4  379.81
  4884.2  378.29  4915.7  376.83  4970.6  375.22  5003.2  374.12  5004.2  373.66
  5004.7  372.86  5009.7  372.86  5010.2  373.66  5013.6  374.11  5021.6  373.92
  5032.1  375.22  5085.6  377.07  5093.9  377.90  5141.7  380.10  5205.7  384.07
  5234.5  386.74  5263.3  390.55  5284.1  392.51  5306.5  393.02  5320.2  392.14
#Mann=5,-1,0
  4525.7    0.05       0  4884.2    0.16       0  5004.2    0.07       0
  5010.2    0.16       0  5093.9    0.05       0
Bank Sta=4970.6,5032.1
Exp/Cntr=0.3,0.1

Type RM Length L Ch R = 1,839,24,24,24
BEGIN DESCRIPTION:
Mapping XS 3ae9d9ed
END DESCRIPTION:
XS GIS Cut Line= 5
      2902341.87      6949788.46      2902673.87      6949740.72
      2902758.51      6949736.38      2902821.44      6949653.91
      2902960.17      6949393.79
#Sta/Elev= 30
  4537.7  404.25  4581.3  398.93  4591.4  397.08  4596.8  394.89  4667.3  384.13
  4737.8  380.21  4763.1  377.65  4819.5  375.27  4843.0  374.43  4861.2  373.41
  4861.7  372.61  4866.7  372.61  4867.2  373.41  4871.0  373.52  5006.7  373.46
  5025.5  375.27  5060.4  380.33  5100.5  384.25  5106.2  386.04  5128.4  387.43
  5144.5  387.98  5160.7  387.12  5226.6  389.97  5292.5  389.61  5308.8  390.75
  5314.5  389.77  5330.7  390.49  5336.4  389.44  5352.7  389.42  5356.4  388.25
#Mann=5,-1,0
  4537.7    0.05       0  4843.0    0.16       0  4861.2    0.03       0
  4867.2    0.16       0  4871.0    0.05       0
Bank Sta=4819.5,5025.5
Exp/Cntr=0.3,0.1

Type RM Length L Ch R = 1,815,54,54,54
BEGIN DESCRIPTION:
Mapping XS 0f61b4dd
END DESCRIPTION:
XS GIS Cut Line= 5
      2902354.88      6949829.69      2902728.12      6949784.12
      2902775.87      6949760.25      2902849.65      6949640.89
      2902949.48      6949443.40
#Sta/Elev= 30
  4518.9  405.75  4521.5  405.75  4549.2  400.63  4589.5  392.19  4596.7  390.26
  4619.8  386.96  4740.7  379.54  4770.9  376.92  4818.4  374.94  4848.5  373.92
  4849.0  373.12  4854.0  373.12  4854.5  373.92  4869.3  374.94  4881.7  376.36
  4890.8  376.75  4952.4  376.25  4989.0  375.23  5016.2  375.51  5052.8  378.66
  5117.6  387.06  5140.0  388.25  5200.9  388.29  5217.6  389.06  5223.2  388.50
  5239.9  389.34  5245.5  388.80  5284.5  389.11  5290.1  388.37  5309.9  389.21
#Mann=3,-1,0
  4518.9    0.05       0  4848.5    0.03       0  4854.5    0.05       0
Bank Sta=4818.4,4869.3
Exp/Cntr=0.3,0.1

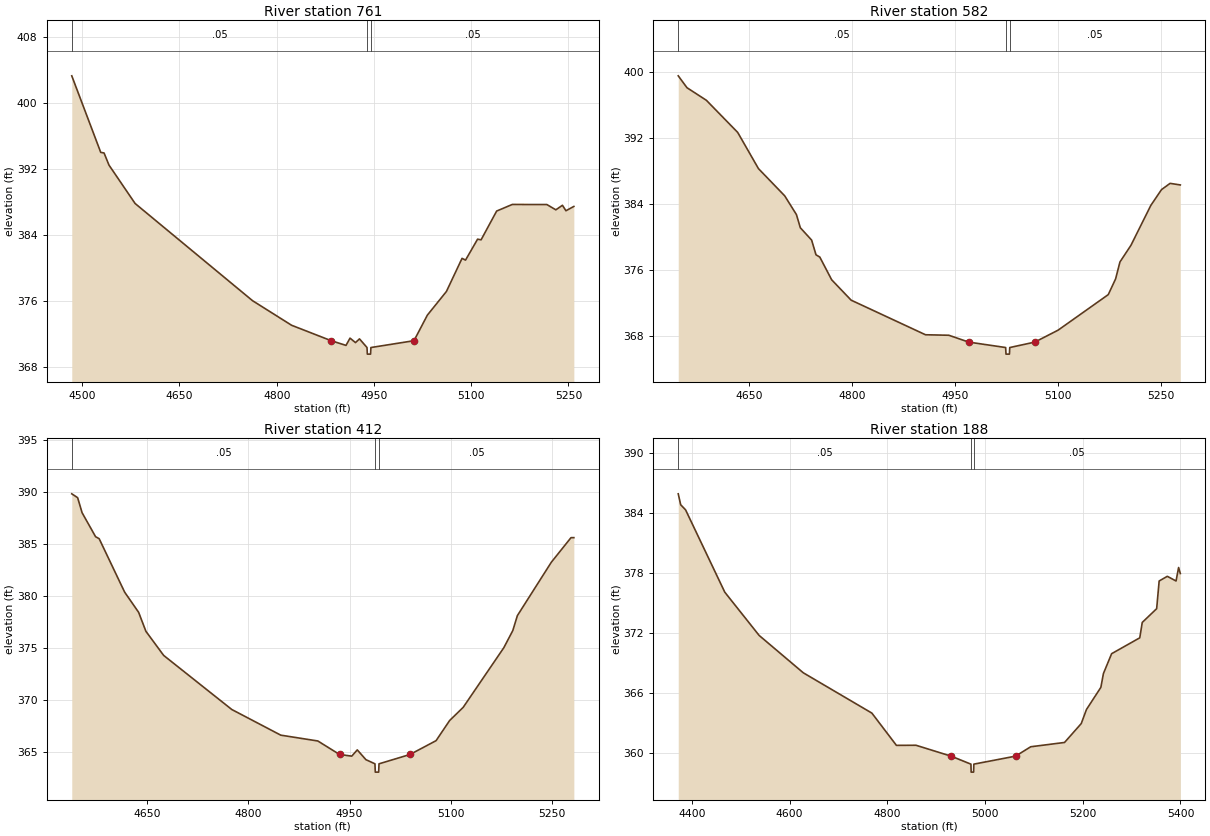
Type RM Length L Ch R = 1,761,179,179,179
BEGIN DESCRIPTION:
Mapping XS 20df1a7d
END DESCRIPTION:
XS GIS Cut Line= 4
      2902367.92      6949875.26      2902754.16      6949831.86
      2902838.80      6949768.93      2902944.82      6949509.29
#Sta/Elev= 30
  4483.8  403.34  4528.5  394.05  4533.6  393.98  4541.2  392.51  4581.5  387.85
  4762.6  376.06  4823.0  373.07  4884.0  371.20  4906.9  370.63  4913.1  371.51
  4921.5  370.97  4927.7  371.42  4939.3  370.37  4939.8  369.57  4944.8  369.57
  4945.3  370.37  5011.8  371.20  5032.4  374.30  5061.8  377.17  5085.9  381.19
  5091.3  380.98  5109.9  383.52  5115.3  383.44  5139.3  386.93  5163.4  387.73
  5216.8  387.72  5230.6  387.08  5240.8  387.63  5246.2  386.97  5258.4  387.49
#Mann=3,-1,0
  4483.8    0.05       0  4939.3    0.03       0  4945.3    0.05       0
Bank Sta=4884,5011.8
Exp/Cntr=0.3,0.1

Type RM Length L Ch R = 1,582,170,170,170
BEGIN DESCRIPTION:
Mapping XS 7db3c058
END DESCRIPTION:
XS GIS Cut Line= 3
      2902539.28      6950085.79      2902982.03      6949877.44
      2903088.37      6949660.41
#Sta/Elev= 30
  4547.1  399.55  4559.8  398.11  4588.1  396.58  4633.7  392.68  4663.9  388.29
  4702.1  384.99  4719.2  382.71  4724.9  381.11  4741.3  379.62  4747.7  377.83
  4753.2  377.56  4770.5  374.80  4798.8  372.33  4907.1  368.13  4941.1  368.07
  4970.0  367.24  5023.8  366.58  5024.3  365.78  5029.3  365.78  5029.8  366.58
  5066.3  367.24  5100.2  368.69  5173.2  373.00  5183.9  374.91  5190.2  376.96
  5206.2  378.98  5235.2  383.83  5250.7  385.74  5263.2  386.50  5278.1  386.31
#Mann=3,-1,0
  4547.1    0.05       0  5023.8    0.03       0  5029.8    0.05       0
Bank Sta=4970,5066.3
Exp/Cntr=0.3,0.1

Type RM Length L Ch R = 1,412,224,224,224
BEGIN DESCRIPTION:
Mapping XS d2608f34
END DESCRIPTION:
XS GIS Cut Line= 3
      2902660.50      6950132.30      2903091.02      6949991.69
      2903118.80      6949701.72
#Sta/Elev= 30
  4538.3  389.82  4547.0  389.45  4553.6  388.00  4573.6  385.69  4578.9  385.50
  4616.7  380.35  4637.4  378.41  4648.2  376.58  4674.5  374.26  4775.5  369.05
  4848.1  366.58  4903.0  366.02  4935.2  364.72  4953.3  364.56  4961.5  365.16
  4974.3  364.22  4987.7  363.82  4988.2  363.02  4993.2  363.02  4993.7  363.82
  5039.7  364.72  5078.3  366.05  5098.4  367.99  5118.5  369.26  5178.7  375.00
  5192.0  376.65  5198.8  378.09  5249.1  383.23  5278.3  385.60  5282.5  385.60
#Mann=3,-1,0
  4538.3    0.05       0  4987.7    0.03       0  4993.7    0.05       0
Bank Sta=4935.2,5039.7
Exp/Cntr=0.3,0.1

Type RM Length L Ch R = 1,188,0,0,0
BEGIN DESCRIPTION:
UNT 083 IN DRY CR WATERSHED 1.0
END DESCRIPTION:
XS GIS Cut Line= 3
      2902699.99      6950150.00      2903300.00      6950100.00
      2903188.37      6949689.29
#Sta/Elev= 30
  4372.0  385.92  4377.0  384.83  4387.1  384.31  4467.3  376.07  4537.6  371.74
  4627.9  368.00  4768.4  363.96  4818.6  360.73  4858.7  360.74  4930.5  359.65
  4971.1  358.85  4971.6  358.05  4976.6  358.05  4977.1  358.85  5062.5  359.65
  5093.5  360.59  5162.7  361.02  5196.9  362.91  5207.6  364.32  5237.1  366.54
  5242.3  367.92  5259.1  369.91  5316.7  371.50  5321.8  373.04  5351.3  374.42
  5356.4  377.19  5373.1  377.66  5391.0  377.19  5396.2  378.54  5399.7  377.94
#Mann=3,-1,0
  4372.0    0.05       0  4971.1    0.03       0  4977.1    0.05       0
Bank Sta=4930.5,5062.5
Exp/Cntr=0.3,0.1

Chan Stop Cuts=-1