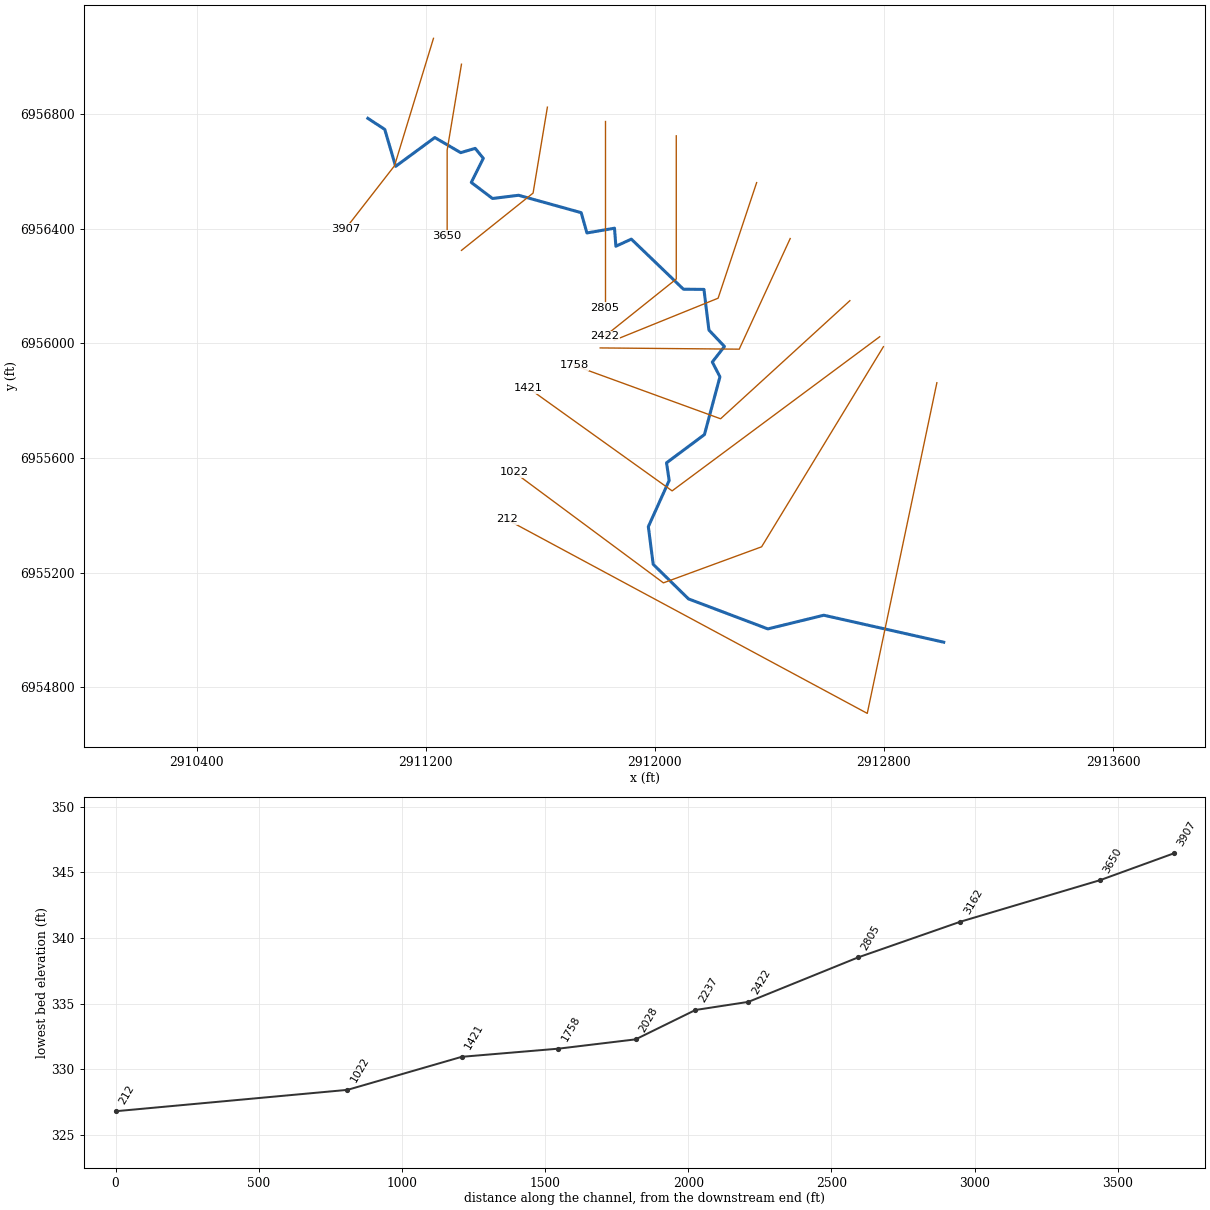
--- UNT 084 IN DRY CR WATERSHED.prj (project) ---

Proj Title=UNT 084 IN DRY CR WATERSHED Base Level Engineering
Current Plan=p01
Default Exp/Contr=0.3,0.1
English Units
Geom File=g01
Flow File=f01
Plan File=p01
BEGIN DESCRIPTION:
UNT 084 IN DRY CR WATERSHED
END DESCRIPTION:

--- UNT 084 IN DRY CR WATERSHED.p01 (plan) ---

Plan Title=Multiple Run
Short Identifier=Multiple
Geom File=g01
Flow File=f01
Subcritical Flow
K Sum by GR= 0
Std Step Tol= 0.01
Critical Tol= 0.01
Num of Std Step Trials= 20
Max Error Tol= 0.3
Flow Tol Ratio= 0.001
Split Flow NTrial= 30
Split Flow Tol= 0.02
Split Flow Ratio= 0.02
Log Output Level= 0
Friction Slope Method= 1
Unsteady Friction Slope Method= 2
Unsteady Bridges Friction Slope Method= 1
Parabolic Critical Depth
Global Vel Dist=  1 , 1 , 1
Global Log Level= 0
CheckData=True
Encroach Param= -1, 0, 0, 0
BEGIN DESCRIPTION:
Multiple Run
END DESCRIPTION:

--- UNT 084 IN DRY CR WATERSHED.f01 (steady flow) ---

Flow Title=Multiple
Number of Profiles=7
Profile Names=10-year,25-year,50-year,1pct_min,100-year,1pct_plu,500-year
River Rch & RM= UNT 084 IN DRY C,Reach-1,3907
     323     418     492     290     578    1153     795
Boundary for River Rch & Prof#=UNT 084 IN DRY C,Reach-1,1
Up Type=0
Dn Type=3
Dn Slope=0.005
Boundary for River Rch & Prof#=UNT 084 IN DRY C,Reach-1,2
Up Type=0
Dn Type=3
Dn Slope=0.005
Boundary for River Rch & Prof#=UNT 084 IN DRY C,Reach-1,3
Up Type=0
Dn Type=3
Dn Slope=0.005
Boundary for River Rch & Prof#=UNT 084 IN DRY C,Reach-1,4
Up Type=0
Dn Type=3
Dn Slope=0.005
Boundary for River Rch & Prof#=UNT 084 IN DRY C,Reach-1,5
Up Type=0
Dn Type=3
Dn Slope=0.005
Boundary for River Rch & Prof#=UNT 084 IN DRY C,Reach-1,6
Up Type=0
Dn Type=3
Dn Slope=0.005
Boundary for River Rch & Prof#=UNT 084 IN DRY C,Reach-1,7
Up Type=0
Dn Type=3
Dn Slope=0.005

--- UNT 084 IN DRY CR WATERSHED.g01 (geometry) ---

Geom Title=Existing Conditions

River Reach=UNT 084 IN DRY C,Reach-1
Reach XY= 30
      2910998.16      6956785.99      2911057.11      6956747.47
      2911095.09      6956618.30      2911231.87      6956718.97
      2911322.26      6956666.25      2911373.10      6956681.15
      2911401.19      6956646.33      2911359.21      6956562.18
      2911433.35      6956506.19      2911524.51      6956517.41
      2911742.92      6956456.72      2911763.06      6956385.83
      2911859.33      6956402.43      2911864.09      6956339.43
      2911918.07      6956364.26      2912099.99      6956189.40
      2912171.65      6956188.74      2912188.97      6956046.75
      2912243.25      6955989.55      2912200.82      6955935.19
      2912227.49      6955883.52      2912173.37      6955681.81
      2912041.01      6955583.15      2912050.21      6955521.61
      2911977.45      6955360.27      2911994.44      6955228.82
      2912117.63      6955108.06      2912394.79      6955003.30
      2912590.10      6955051.04      2913008.94      6954956.86

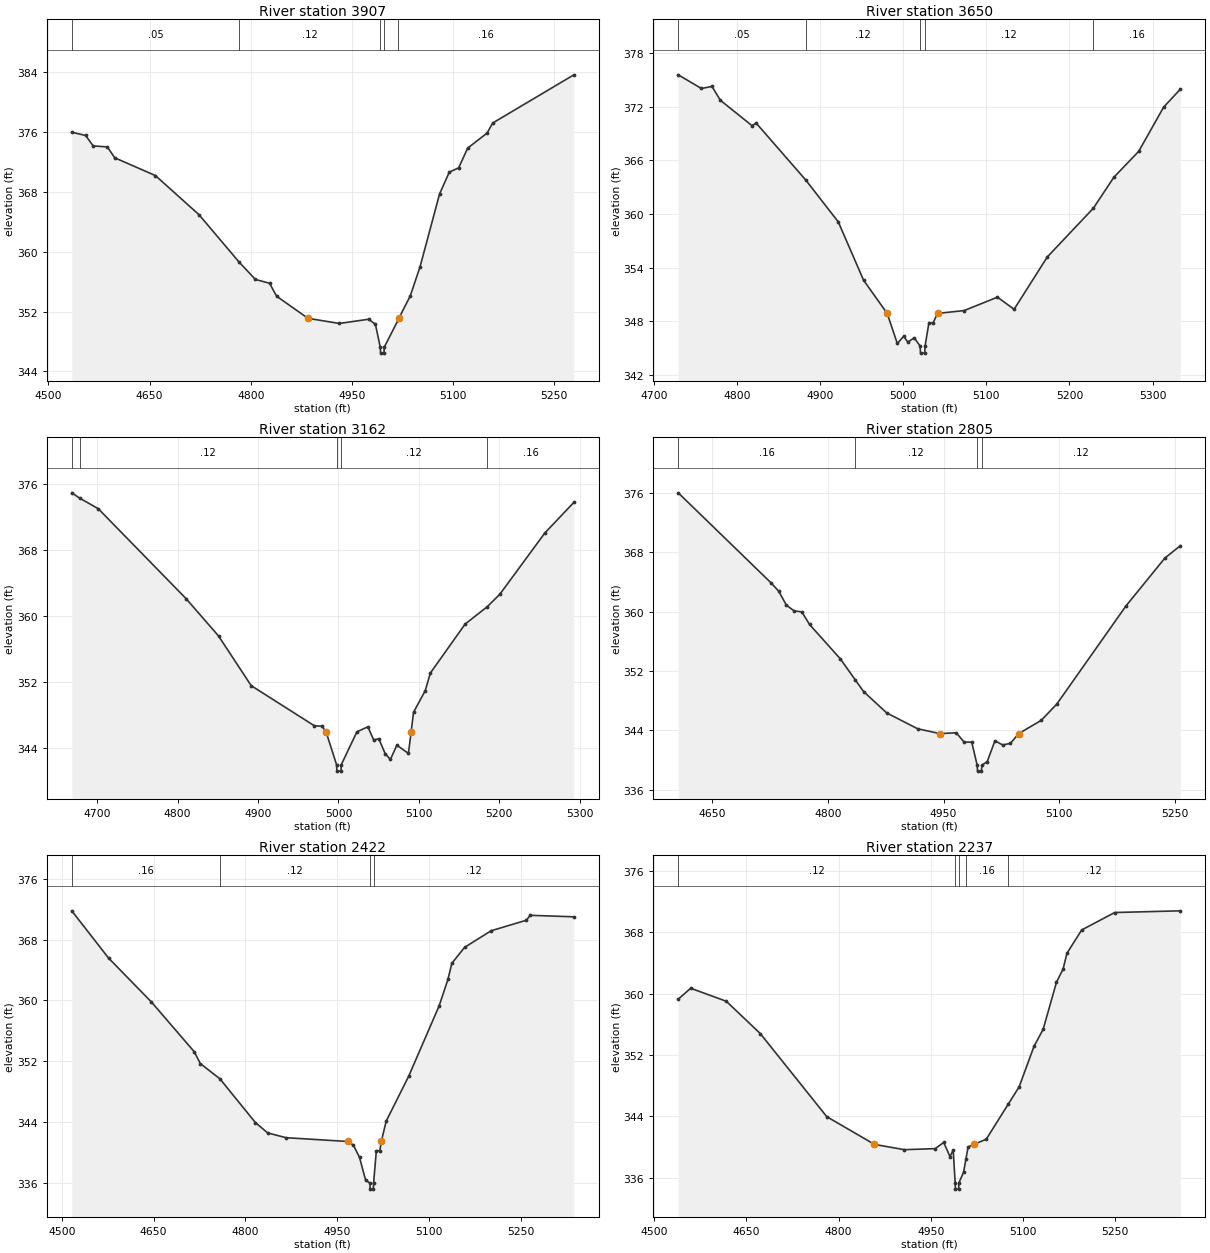
Type RM Length L Ch R = 1,3907,257,257,257
BEGIN DESCRIPTION:
UNT 084 IN DRY CR WATERSHED 6.0
END DESCRIPTION:
XS GIS Cut Line= 3
      2911227.27      6957065.38      2911091.17      6956620.42
      2910919.92      6956400.17
#Sta/Elev= 30
  4534.7  375.92  4555.2  375.49  4566.5  374.09  4587.4  373.97  4598.4  372.51
  4658.7  370.14  4723.3  364.92  4783.2  358.55  4807.0  356.28  4827.9  355.77
  4838.4  354.04  4885.0  351.09  4931.4  350.41  4974.7  350.97  4984.8  350.31
  4992.0  347.25  4992.5  346.45  4997.5  346.45  4998.0  347.25  5018.2  350.82
  5019.5  351.09  5036.5  354.08  5051.0  357.97  5080.0  367.70  5094.4  370.60
  5108.2  371.17  5121.6  373.80  5150.5  375.82  5158.7  377.15  5279.0  383.58
#Mann=5,-1,0
  4534.7    0.05       0  4783.2    0.12       0  4992.0    0.07       0
  4998.0    0.12       0  5018.2    0.16       0
Bank Sta=4885,5019.5
Exp/Cntr=0.3,0.1

Type RM Length L Ch R = 1,3650,488,488,488
BEGIN DESCRIPTION:
UNT 084 IN DRY CR WATERSHED 5.0
END DESCRIPTION:
XS GIS Cut Line= 3
      2911325.00      6956975.01      2911275.00      6956675.00
      2911275.00      6956375.05
#Sta/Elev= 30
  4729.3  375.59  4757.2  374.06  4769.9  374.29  4780.0  372.74  4818.0  369.90
  4823.1  370.18  4882.5  363.83  4921.9  359.11  4952.3  352.58  4980.7  348.86
  4992.9  345.49  5000.5  346.29  5005.6  345.64  5013.2  346.13  5020.3  345.21
  5020.8  344.41  5025.8  344.41  5026.3  345.21  5030.9  347.80  5035.9  347.80
  5041.3  348.86  5073.4  349.18  5113.4  350.68  5133.4  349.32  5173.4  355.19
  5228.9  360.66  5253.4  364.11  5283.4  367.02  5313.4  371.98  5333.4  373.98
#Mann=5,-1,0
  4729.3    0.05       0  4882.5    0.12       0  5020.3    0.07       0
  5026.3    0.12       0  5228.9    0.16       0
Bank Sta=4980.7,5041.3
Exp/Cntr=0.3,0.1

Type RM Length L Ch R = 1,3162,357,357,357
BEGIN DESCRIPTION:
UNT 084 IN DRY CR WATERSHED 4.0
END DESCRIPTION:
XS GIS Cut Line= 3
      2911625.01      6956825.05      2911575.00      6956525.00
      2911325.03      6956325.03
#Sta/Elev= 30
  4668.4  374.97  4678.2  374.33  4701.4  373.04  4810.4  362.16  4850.9  357.62
  4891.5  351.60  4970.0  346.74  4979.8  346.68  4984.8  345.93  4997.6  342.04
  4998.1  341.24  5003.1  341.24  5003.6  342.04  5023.0  346.01  5036.6  346.61
  5043.8  345.02  5050.2  345.16  5058.2  343.34  5064.6  342.66  5072.6  344.38
  5087.0  343.39  5090.3  345.93  5093.4  348.38  5107.9  350.99  5114.3  353.13
  5157.5  359.06  5184.8  361.15  5200.7  362.68  5256.7  370.11  5292.7  373.81
#Mann=5,-1,0
  4668.4    0.05       0  4678.2    0.12       0  4997.6    0.07       0
  5003.6    0.12       0  5184.8    0.16       0
Bank Sta=4984.8,5090.3
Exp/Cntr=0.3,0.1

Type RM Length L Ch R = 1,2805,383,383,383
BEGIN DESCRIPTION:
UNT 084 IN DRY CR WATERSHED 3.0
END DESCRIPTION:
XS GIS Cut Line= 3
      2911825.00      6956775.03      2911825.00      6956425.00
      2911825.00      6956125.03
#Sta/Elev= 30
  4606.5  376.04  4726.5  363.92  4736.5  362.79  4746.5  360.90  4756.5  360.12
  4766.5  359.99  4776.5  358.29  4816.5  353.64  4835.9  350.79  4846.5  349.24
  4876.5  346.36  4916.5  344.23  4945.2  343.58  4966.5  343.69  4976.5  342.44
  4986.5  342.43  4993.5  339.32  4994.0  338.52  4999.0  338.52  4999.5  339.32
  5006.5  339.80  5016.5  342.61  5026.5  342.05  5036.5  342.26  5047.3  343.58
  5076.5  345.37  5096.5  347.55  5186.5  360.84  5236.5  367.24  5256.5  368.91
#Mann=4,-1,0
  4606.5    0.16       0  4835.9    0.12       0  4993.5    0.07       0
  4999.5    0.12       0
Bank Sta=4945.2,5047.3
Exp/Cntr=0.3,0.1

Type RM Length L Ch R = 1,2422,185,185,185
BEGIN DESCRIPTION:
UNT 084 IN DRY CR WATERSHED 2.0
END DESCRIPTION:
XS GIS Cut Line= 3
      2912075.00      6956724.98      2912075.00      6956225.00
      2911825.03      6956025.02
#Sta/Elev= 30
  4516.4  371.82  4576.4  365.60  4646.4  359.81  4716.4  353.25  4726.4  351.68
  4758.3  349.68  4816.4  343.90  4836.4  342.54  4866.4  341.91  4967.7  341.41
  4976.4  340.93  4986.4  339.32  4996.4  336.30  5003.4  335.93  5003.9  335.13
  5008.9  335.13  5009.4  335.93  5013.9  340.19  5019.6  340.19  5022.0  341.41
  5030.0  344.10  5066.8  350.03  5116.4  359.28  5130.8  362.77  5137.2  364.90
  5158.0  367.00  5201.3  369.19  5258.9  370.58  5265.3  371.23  5336.5  371.03
#Mann=4,-1,0
  4516.4    0.16       0  4758.3    0.12       0  5003.4    0.07       0
  5009.4    0.12       0
Bank Sta=4967.7,5022
Exp/Cntr=0.3,0.1

Type RM Length L Ch R = 1,2237,209,209,209
BEGIN DESCRIPTION:
Mapping XS 4c823f3b
END DESCRIPTION:
XS GIS Cut Line= 3
      2912355.59      6956561.60      2912221.06      6956157.99
      2911858.20      6956011.12
#Sta/Elev= 30
  4539.0  359.27  4559.2  360.70  4617.2  359.00  4672.5  354.79  4780.6  343.96
  4858.3  340.34  4907.1  339.65  4957.1  339.79  4971.0  340.60  4981.1  338.75
  4986.4  339.61  4989.6  335.31  4990.1  334.51  4995.1  334.51  4995.6  335.31
  5003.3  336.73  5007.0  338.39  5010.6  340.01  5019.9  340.34  5040.1  341.01
  5076.2  345.62  5093.7  347.85  5117.8  353.11  5132.8  355.36  5154.4  361.48
  5165.2  363.21  5171.4  365.25  5195.5  368.30  5249.2  370.57  5355.9  370.79
#Mann=5,-1,0
  4539.0    0.12       0  4989.6    0.07       0  4995.6    0.12       0
  5007.0    0.16       0  5076.2    0.12       0
Bank Sta=4858.3,5019.9
Exp/Cntr=0.3,0.1

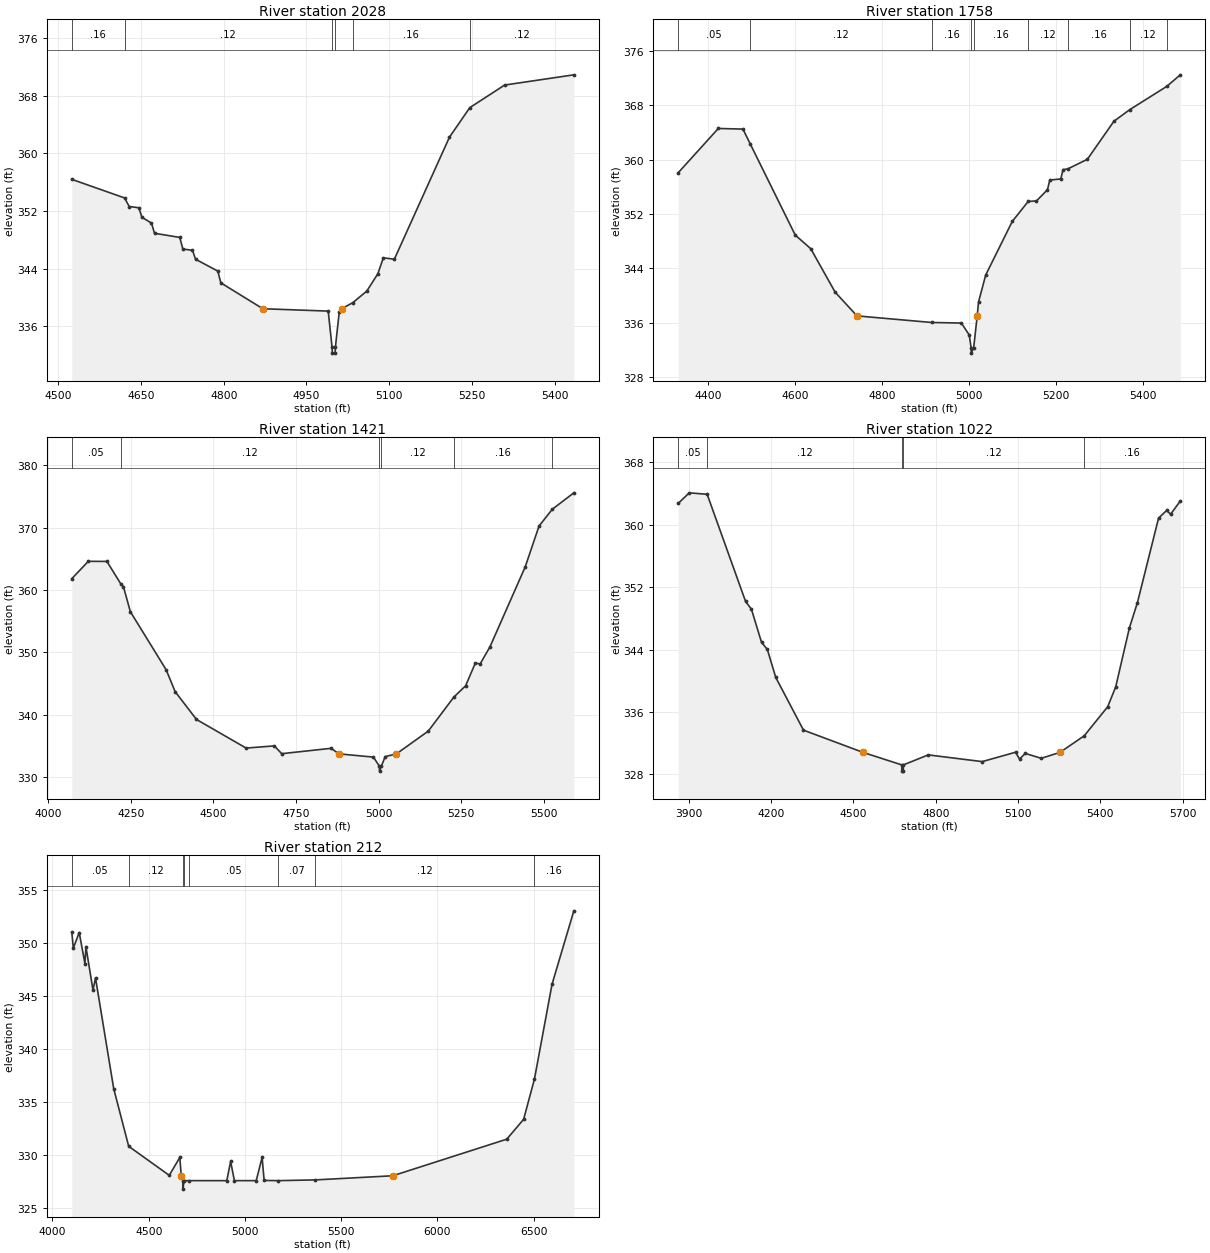
Type RM Length L Ch R = 1,2028,270,270,270
BEGIN DESCRIPTION:
Mapping XS f3da62d9
END DESCRIPTION:
XS GIS Cut Line= 3
      2912472.81      6956366.36      2912294.84      6955980.04
      2911809.40      6955984.37
#Sta/Elev= 30
  4524.2  356.38  4620.0  353.80  4628.4  352.61  4645.9  352.44  4651.4  351.12
  4668.8  350.31  4674.3  348.90  4720.2  348.32  4725.7  346.71  4743.2  346.54
  4748.7  345.30  4789.1  343.65  4794.6  342.02  4870.8  338.43  4989.4  338.10
  4996.4  333.07  4996.9  332.27  5001.9  332.27  5002.4  333.07  5009.4  337.95
  5013.8  338.43  5034.0  339.27  5059.4  340.88  5079.4  343.27  5089.4  345.49
  5109.4  345.30  5209.4  362.24  5246.3  366.33  5309.4  369.46  5435.0  370.88
#Mann=6,-1,0
  4524.2    0.16       0  4620.0    0.12       0  4996.4    0.07       0
  5002.4    0.12       0  5034.0    0.16       0  5246.3    0.12       0
Bank Sta=4870.8,5013.8
Exp/Cntr=0.3,0.1

Type RM Length L Ch R = 1,1758,337,337,337
BEGIN DESCRIPTION:
Mapping XS 92c205eb
END DESCRIPTION:
XS GIS Cut Line= 3
      2912681.14      6956149.32      2912229.74      6955736.98
      2911718.79      6955923.18
#Sta/Elev= 30
  4331.5  358.06  4423.7  364.56  4480.4  364.47  4497.4  362.26  4600.7  348.90
  4636.4  346.90  4692.5  340.52  4742.7  337.03  4914.8  336.06  4983.0  335.98
  5001.1  334.22  5005.3  332.36  5005.8  331.56  5011.3  332.36  5019.4  337.03
  5022.4  339.05  5038.9  343.03  5100.0  350.90  5136.7  353.84  5155.8  353.92
  5181.1  355.57  5186.4  356.99  5211.6  357.14  5216.9  358.51  5227.7  358.62
  5272.8  360.03  5333.9  365.62  5370.5  367.33  5455.5  370.74  5486.7  372.44
#Mann=9,-1,0
  4331.5    0.05       0  4497.4    0.12       0  4914.8    0.16       0
  5005.3    0.07       0  5011.3    0.16       0  5136.7    0.12       0
  5227.7    0.16       0  5370.5    0.12       0  5455.5    0.16       0
Bank Sta=4742.7,5019.4
Exp/Cntr=0.3,0.1

Type RM Length L Ch R = 1,1421,399,399,399
BEGIN DESCRIPTION:
Mapping XS 3dfa35b6
END DESCRIPTION:
XS GIS Cut Line= 3
      2912785.31      6956023.46      2912060.47      6955485.25
      2911558.53      6955844.39
#Sta/Elev= 30
  4071.1  361.82  4121.2  364.61  4177.5  364.59  4219.4  361.00  4227.5  360.55
  4248.4  356.53  4356.9  347.20  4384.0  343.70  4448.7  339.23  4598.9  334.64
  4684.4  334.99  4706.7  333.74  4856.2  334.60  4880.0  333.71  4984.4  333.19
  5002.3  331.74  5002.8  330.94  5008.3  331.74  5020.1  333.27  5054.0  333.71
  5150.3  337.36  5228.3  342.85  5263.4  344.63  5292.8  348.27  5307.5  348.15
  5337.0  350.87  5443.9  363.72  5485.7  370.27  5526.0  372.97  5591.1  375.60
#Mann=6,-1,0
  4071.1    0.05       0  4219.4    0.12       0  5002.3    0.07       0
  5008.3    0.12       0  5228.3    0.16       0  5526.0    0.12       0
Bank Sta=4880,5054
Exp/Cntr=0.3,0.1

Type RM Length L Ch R = 1,1022,810,810,810
BEGIN DESCRIPTION:
Mapping XS e8abf7e7
END DESCRIPTION:
XS GIS Cut Line= 4
      2912798.34      6955988.76      2912372.97      6955289.93
      2912030.08      6955164.07      2911509.90      6955549.87
#Sta/Elev= 30
  3860.9  362.73  3901.2  364.08  3966.4  363.89  4106.5  350.16  4127.8  349.17
  4164.6  344.93  4185.9  344.01  4216.5  340.43  4317.7  333.67  4534.1  330.83
  4676.0  329.22  4676.5  328.42  4681.5  328.42  4682.0  329.22  4772.7  330.50
  4969.4  329.64  5091.0  330.84  5105.6  329.96  5126.4  330.69  5184.9  330.06
  5253.5  330.83  5341.6  332.95  5426.9  336.66  5456.2  339.20  5506.2  346.77
  5535.5  350.01  5612.6  360.84  5641.9  361.82  5656.5  361.34  5691.9  363.03
#Mann=5,-1,0
  3860.9    0.05       0  3966.4    0.12       0  4676.0    0.07       0
  4682.0    0.12       0  5341.6    0.16       0
Bank Sta=4534.1,5253.5
Exp/Cntr=0.3,0.1

Type RM Length L Ch R = 1,212,0,0,0
BEGIN DESCRIPTION:
UNT 084 IN DRY CR WATERSHED 1.0
END DESCRIPTION:
XS GIS Cut Line= 3
      2912984.95      6955862.89      2912741.89      6954708.34
      2911483.21      6955385.42
#Sta/Elev= 30
  4100.2  351.05  4108.3  349.52  4138.9  350.99  4168.6  348.06  4173.7  349.67
  4210.5  345.56  4223.6  346.71  4318.1  336.27  4396.0  330.83  4606.8  328.09
  4661.7  329.78  4669.1  328.05  4677.5  327.59  4678.0  326.79  4683.5  327.59
  4707.9  327.59  4905.7  327.59  4925.8  329.40  4945.3  327.59  5058.7  327.59
  5089.3  329.78  5099.9  327.61  5174.0  327.59  5366.0  327.66  5768.3  328.05
  6360.5  331.50  6448.2  333.37  6504.6  337.17  6595.9  346.11  6709.3  353.04
#Mann=8,-1,0
  4100.2    0.05       0  4396.0    0.12       0  4677.5   0.033       0
  4683.5    0.12       0  4707.9    0.05       0  5174.0    0.07       0
  5366.0    0.12       0  6504.6    0.16       0
Bank Sta=4669.1,5768.3
Exp/Cntr=0.3,0.1

Chan Stop Cuts=-1