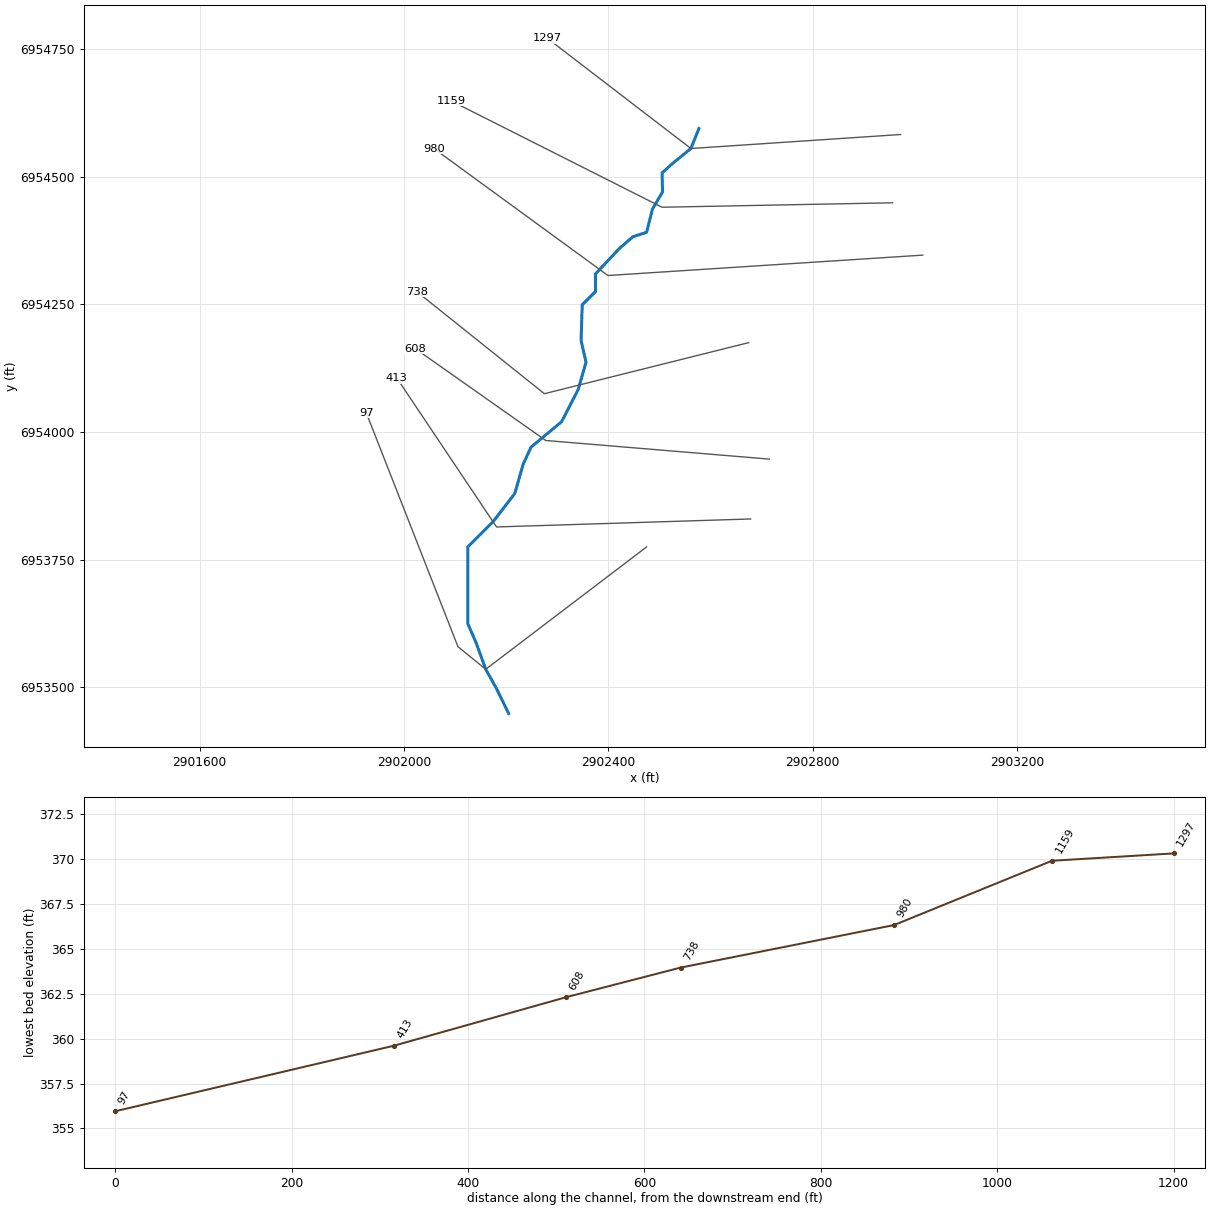
--- UNT 085 IN DRY CR WATERSHED.prj (project) ---

Proj Title=UNT 085 IN DRY CR WATERSHED Base Level Engineering
Current Plan=p01
Default Exp/Contr=0.3,0.1
English Units
Geom File=g01
Flow File=f01
Plan File=p01
BEGIN DESCRIPTION:
UNT 085 IN DRY CR WATERSHED
END DESCRIPTION:

--- UNT 085 IN DRY CR WATERSHED.p01 (plan) ---

Plan Title=Multiple Run
Short Identifier=Multiple
Geom File=g01
Flow File=f01
Subcritical Flow
K Sum by GR= 0
Std Step Tol= 0.01
Critical Tol= 0.01
Num of Std Step Trials= 20
Max Error Tol= 0.3
Flow Tol Ratio= 0.001
Split Flow NTrial= 30
Split Flow Tol= 0.02
Split Flow Ratio= 0.02
Log Output Level= 0
Friction Slope Method= 1
Unsteady Friction Slope Method= 2
Unsteady Bridges Friction Slope Method= 1
Parabolic Critical Depth
Global Vel Dist=  1 , 1 , 1
Global Log Level= 0
CheckData=True
Encroach Param= -1, 0, 0, 0
BEGIN DESCRIPTION:
Multiple Run
END DESCRIPTION:

--- UNT 085 IN DRY CR WATERSHED.f01 (steady flow) ---

Flow Title=Multiple
Number of Profiles=7
Profile Names=10-year,25-year,50-year,1pct_min,100-year,1pct_plu,500-year
River Rch & RM= UNT 085 IN DRY C,Reach-1,1297
     104     125     140      79     158     314     198
Boundary for River Rch & Prof#=UNT 085 IN DRY C,Reach-1,1
Up Type=0
Dn Type=3
Dn Slope=0.005
Boundary for River Rch & Prof#=UNT 085 IN DRY C,Reach-1,2
Up Type=0
Dn Type=3
Dn Slope=0.005
Boundary for River Rch & Prof#=UNT 085 IN DRY C,Reach-1,3
Up Type=0
Dn Type=3
Dn Slope=0.005
Boundary for River Rch & Prof#=UNT 085 IN DRY C,Reach-1,4
Up Type=0
Dn Type=3
Dn Slope=0.005
Boundary for River Rch & Prof#=UNT 085 IN DRY C,Reach-1,5
Up Type=0
Dn Type=3
Dn Slope=0.005
Boundary for River Rch & Prof#=UNT 085 IN DRY C,Reach-1,6
Up Type=0
Dn Type=3
Dn Slope=0.005
Boundary for River Rch & Prof#=UNT 085 IN DRY C,Reach-1,7
Up Type=0
Dn Type=3
Dn Slope=0.005

--- UNT 085 IN DRY CR WATERSHED.g01 (geometry) ---

Geom Title=Existing Conditions

River Reach=UNT 085 IN DRY C,Reach-1
Reach XY= 28
      2902577.46      6954594.01      2902561.83      6954554.95
      2902525.00      6954525.00      2902505.41      6954507.20
      2902506.28      6954469.88      2902486.60      6954436.60
      2902475.03      6954390.88      2902448.12      6954382.20
      2902421.21      6954358.77      2902375.00      6954309.29
      2902375.00      6954275.00      2902349.05      6954249.05
      2902346.79      6954179.09      2902356.51      6954136.73
      2902341.23      6954083.26      2902308.59      6954020.06
      2902248.97      6953970.56      2902233.35      6953936.70
      2902217.20      6953879.93      2902175.00      6953825.00
      2902125.00      6953775.00      2902125.00      6953725.00
      2902125.00      6953675.00      2902125.00      6953625.00
      2902141.68      6953586.53      2902160.13      6953535.53
      2902180.75      6953498.64      2902204.92      6953449.24

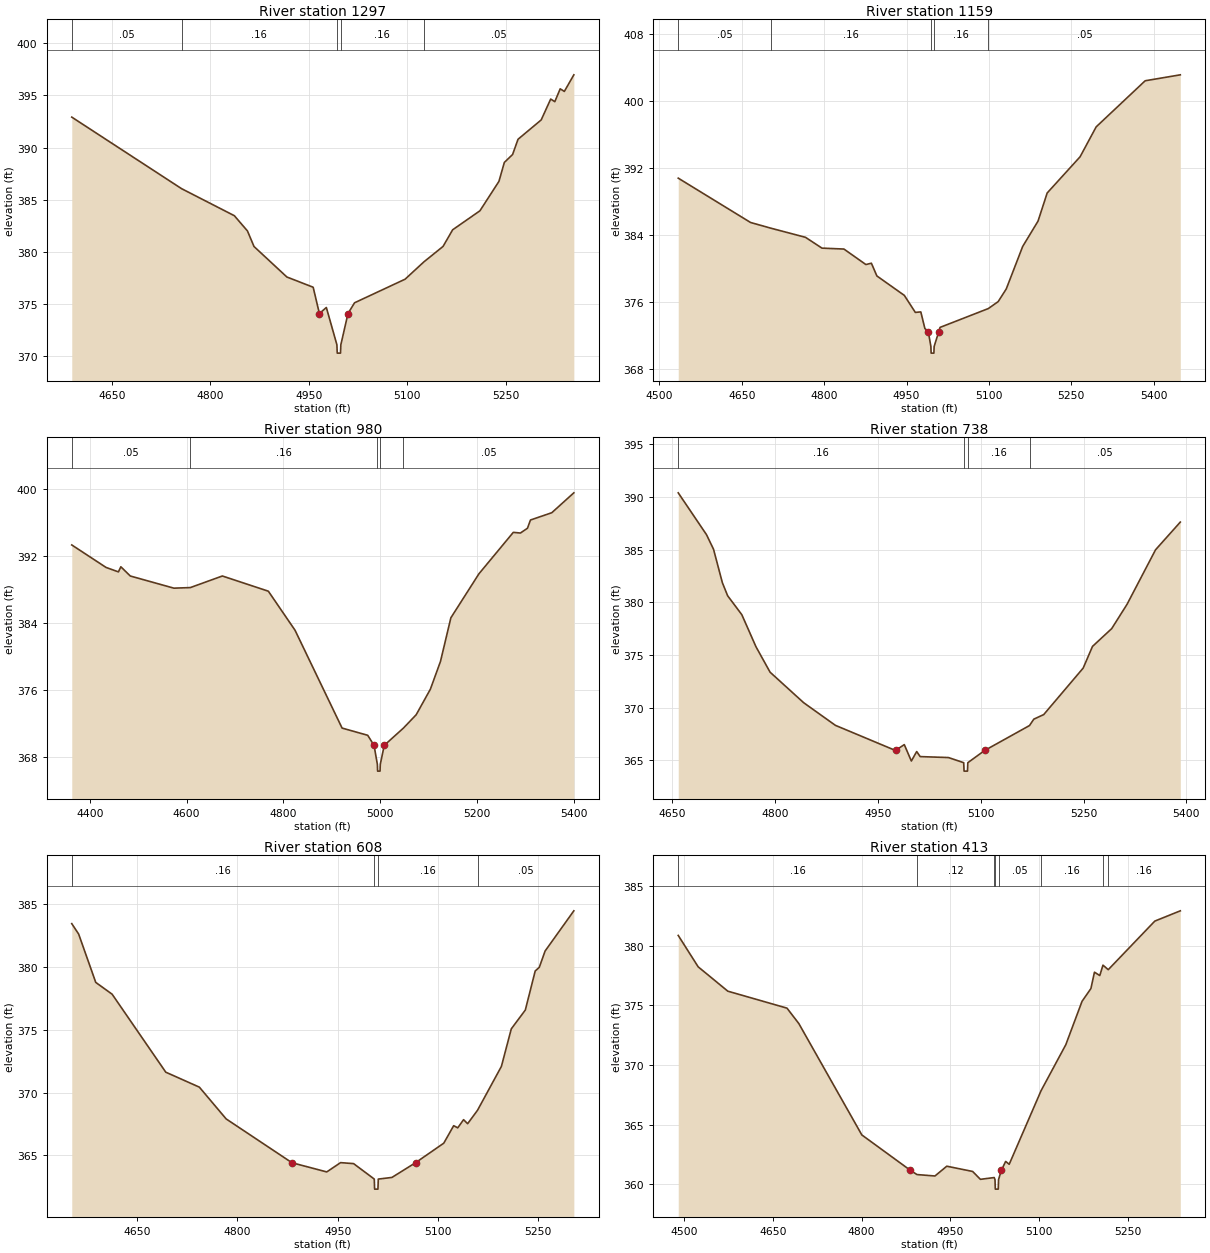
Type RM Length L Ch R = 1,1297,138,138,138
BEGIN DESCRIPTION:
UNT 085 IN DRY CR WATERSHED 3.0
END DESCRIPTION:
XS GIS Cut Line= 3
      2902972.32      6954582.39      2902561.83      6954554.95
      2902280.88      6954770.64
#Sta/Elev= 30
  4588.6  392.92  4756.0  386.07  4836.5  383.48  4856.5  382.02  4866.5  380.53
  4916.6  377.61  4956.7  376.63  4966.2  374.11  4976.8  374.69  4992.9  371.12
  4993.4  370.32  4998.4  370.32  4998.9  371.12  5009.8  374.11  5019.8  375.14
  5096.9  377.40  5125.4  379.05  5154.8  380.54  5169.4  382.13  5211.0  383.95
  5240.0  386.77  5248.2  388.58  5260.8  389.34  5269.1  390.80  5304.4  392.65
  5318.9  394.65  5325.2  394.40  5333.4  395.63  5339.7  395.38  5354.2  396.97
#Mann=5,-1,0
  4588.6    0.05       0  4756.0    0.16       0  4992.9    0.07       0
  4998.9    0.16       0  5125.4    0.05       0
Bank Sta=4966.2,5009.8
Exp/Cntr=0.3,0.1

Type RM Length L Ch R = 1,1159,179,179,179
BEGIN DESCRIPTION:
Mapping XS a832f16b
END DESCRIPTION:
XS GIS Cut Line= 3
      2902956.63      6954448.71      2902505.29      6954440.03
      2902092.07      6954648.38
#Sta/Elev= 30
  4534.2  390.79  4665.9  385.50  4703.4  384.81  4765.9  383.73  4795.9  382.44
  4835.9  382.33  4875.9  380.48  4885.9  380.64  4895.9  379.12  4945.9  376.80
  4965.9  374.77  4975.9  374.83  4983.3  372.85  4989.5  372.49  4994.2  370.71
  4994.7  369.91  4999.7  369.91  5000.2  370.71  5008.7  372.49  5010.9  372.98
  5098.9  375.23  5116.8  376.06  5131.5  377.57  5161.4  382.64  5189.3  385.66
  5206.0  389.02  5265.9  393.34  5295.2  396.91  5384.4  402.41  5448.4  403.12
#Mann=5,-1,0
  4534.2    0.05       0  4703.4    0.16       0  4994.2    0.07       0
  5000.2    0.16       0  5098.9    0.05       0
Bank Sta=4989.5,5008.7
Exp/Cntr=0.3,0.1

Type RM Length L Ch R = 1,980,242,242,242
BEGIN DESCRIPTION:
Mapping XS 7f8ae3dd
END DESCRIPTION:
XS GIS Cut Line= 3
      2903015.72      6954346.28      2902399.39      6954306.35
      2902059.55      6954554.29
#Sta/Elev= 30
  4362.4  393.28  4433.3  390.60  4458.9  390.07  4463.9  390.68  4483.4  389.58
  4573.6  388.13  4607.6  388.20  4673.8  389.58  4768.9  387.77  4824.1  383.12
  4921.4  371.46  4974.4  370.60  4987.5  369.40  4994.4  367.13  4994.9  366.33
  4999.9  366.33  5000.4  367.13  5008.6  369.40  5048.3  371.46  5074.7  373.05
  5104.0  376.09  5124.9  379.40  5146.4  384.60  5204.4  389.84  5275.5  394.78
  5290.2  394.70  5304.8  395.27  5311.0  396.25  5355.1  397.12  5400.7  399.49
#Mann=5,-1,0
  4362.4    0.05       0  4607.6    0.16       0  4994.4    0.07       0
  5000.4    0.16       0  5048.3    0.05       0
Bank Sta=4987.5,5008.6
Exp/Cntr=0.3,0.1

Type RM Length L Ch R = 1,738,130,130,130
BEGIN DESCRIPTION:
UNT 085 IN DRY CR WATERSHED 2.0
END DESCRIPTION:
XS GIS Cut Line= 3
      2902674.99      6954175.00      2902275.00      6954075.00
      2902024.97      6954275.03
#Sta/Elev= 30
  4658.6  390.40  4699.8  386.43  4710.1  385.04  4723.0  381.86  4730.7  380.62
  4751.4  378.82  4772.0  375.78  4792.6  373.36  4841.6  370.46  4887.9  368.31
  4975.6  365.92  4988.4  366.48  4998.7  364.92  5006.5  365.82  5011.6  365.34
  5052.9  365.25  5075.1  364.76  5075.6  363.96  5080.6  363.96  5081.1  364.76
  5105.6  365.92  5171.1  368.29  5177.4  368.90  5191.8  369.33  5249.4  373.75
  5263.0  375.81  5291.0  377.50  5313.4  379.81  5355.0  384.99  5391.1  387.62
#Mann=4,-1,0
  4658.6    0.16       0  5075.1    0.07       0  5081.1    0.16       0
  5171.1    0.05       0
Bank Sta=4975.6,5105.6
Exp/Cntr=0.3,0.1

Type RM Length L Ch R = 1,608,195,195,195
BEGIN DESCRIPTION:
Mapping XS 71d9fdbf
END DESCRIPTION:
XS GIS Cut Line= 3
      2902715.23      6953946.97      2902277.69      6953983.43
      2902022.46      6954163.13
#Sta/Elev= 30
  4552.2  383.45  4562.5  382.62  4588.1  378.77  4612.6  377.83  4692.9  371.62
  4743.1  370.43  4783.2  367.90  4881.7  364.41  4933.7  363.68  4954.4  364.42
  4973.9  364.34  5004.8  363.11  5005.3  362.31  5010.3  362.31  5010.8  363.11
  5031.2  363.24  5066.5  364.41  5108.8  365.97  5123.6  367.36  5129.7  367.19
  5138.4  367.84  5144.5  367.52  5159.3  368.59  5195.0  372.08  5209.8  375.07
  5230.8  376.57  5245.6  379.68  5251.7  379.97  5260.4  381.27  5303.4  384.47
#Mann=4,-1,0
  4552.2    0.16       0  5004.8    0.07       0  5010.8    0.16       0
  5159.3    0.05       0
Bank Sta=4881.7,5066.5
Exp/Cntr=0.3,0.1

Type RM Length L Ch R = 1,413,316,316,316
BEGIN DESCRIPTION:
Mapping XS 0a8454e9
END DESCRIPTION:
XS GIS Cut Line= 3
      2902678.71      6953829.79      2902181.33      6953814.16
      2901986.05      6954105.79
#Sta/Elev= 30
  4490.0  380.86  4523.7  378.23  4573.8  376.19  4673.8  374.77  4693.8  373.48
  4800.3  364.15  4882.5  361.18  4893.5  360.83  4923.9  360.71  4943.9  361.53
  4987.6  361.09  5000.7  360.43  5024.0  360.58  5025.4  360.41  5025.9  359.61
  5030.9  359.61  5031.4  360.41  5036.1  361.18  5043.4  361.93  5049.4  361.69
  5103.3  367.86  5145.1  371.71  5172.5  375.34  5187.5  376.41  5193.5  377.78
  5202.5  377.50  5207.9  378.37  5216.8  377.99  5295.5  382.06  5338.6  382.92
#Mann=8,-1,0
  4490.0    0.16       0  4893.5    0.12       0  5024.0    0.05       0
  5025.4    0.07       0  5031.4    0.05       0  5103.3    0.16       0
  5207.9    0.05       0  5216.8    0.16       0
Bank Sta=4882.5,5036.1
Exp/Cntr=0.3,0.1

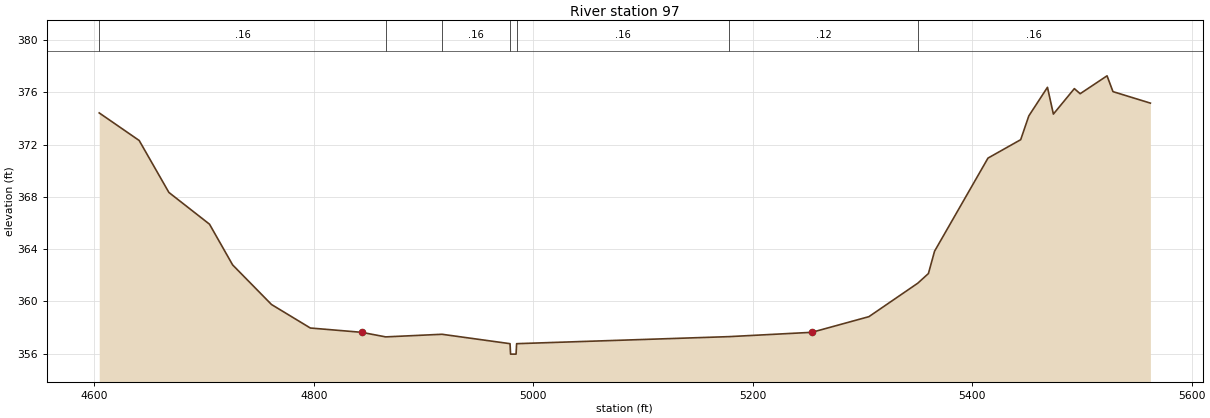
Type RM Length L Ch R = 1,97,0,0,0
BEGIN DESCRIPTION:
UNT 085 IN DRY CR WATERSHED 1.0
END DESCRIPTION:
XS GIS Cut Line= 4
      2902475.01      6953775.01      2902160.13      6953535.53
      2902105.81      6953579.79      2901926.11      6954038.16
#Sta/Elev= 30
  4604.4  374.43  4640.8  372.32  4667.9  368.34  4704.9  365.91  4726.0  362.79
  4761.4  359.76  4796.8  357.96  4843.5  357.63  4865.5  357.28  4916.8  357.48
  4978.8  356.76  4979.3  355.96  4984.3  355.96  4984.8  356.76  5178.6  357.30
  5253.9  357.63  5305.9  358.83  5350.4  361.39  5360.1  362.13  5365.7  363.84
  5414.4  370.97  5444.2  372.38  5451.6  374.20  5468.6  376.39  5474.0  374.34
  5493.1  376.29  5498.4  375.90  5522.9  377.27  5528.3  376.06  5562.4  375.18
#Mann=7,-1,0
  4604.4    0.16       0  4865.5    0.12       0  4916.8    0.16       0
  4978.8    0.07       0  4984.8    0.16       0  5178.6    0.12       0
  5350.4    0.16       0
Bank Sta=4843.5,5253.9
Exp/Cntr=0.3,0.1

Chan Stop Cuts=-1