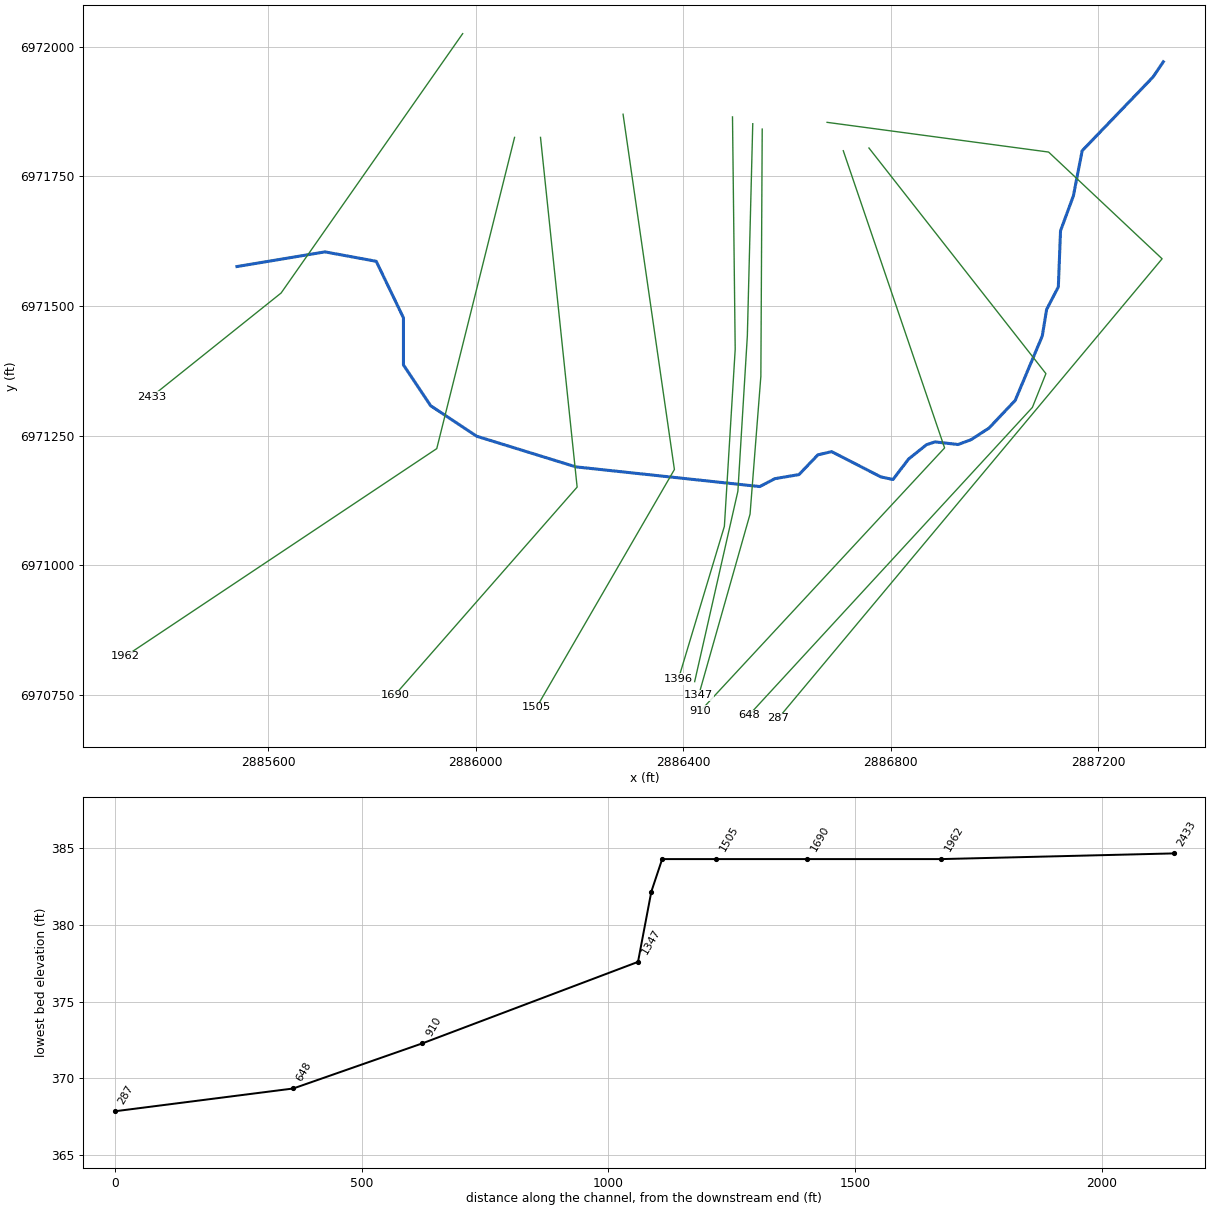
--- UNT 086 IN DRY CR WATERSHED.prj (project) ---

Proj Title=UNT 086 IN DRY CR WATERSHED Base Level Engineering
Current Plan=p01
Default Exp/Contr=0.3,0.1
English Units
Geom File=g01
Flow File=f01
Plan File=p01
BEGIN DESCRIPTION:
UNT 086 IN DRY CR WATERSHED
END DESCRIPTION:

--- UNT 086 IN DRY CR WATERSHED.p01 (plan) ---

Plan Title=Multiple Run
Short Identifier=Multiple
Geom File=g01
Flow File=f01
Subcritical Flow
K Sum by GR= 0
Std Step Tol= 0.01
Critical Tol= 0.01
Num of Std Step Trials= 20
Max Error Tol= 0.3
Flow Tol Ratio= 0.001
Split Flow NTrial= 30
Split Flow Tol= 0.02
Split Flow Ratio= 0.02
Log Output Level= 0
Friction Slope Method= 1
Unsteady Friction Slope Method= 2
Unsteady Bridges Friction Slope Method= 1
Parabolic Critical Depth
Global Vel Dist=  1 , 1 , 1
Global Log Level= 0
CheckData=True
Encroach Param= -1, 0, 0, 0
BEGIN DESCRIPTION:
Multiple Run
END DESCRIPTION:

--- UNT 086 IN DRY CR WATERSHED.f01 (steady flow) ---

Flow Title=Multiple
Number of Profiles=7
Profile Names=10-year,25-year,50-year,1pct_min,100-year,1pct_plu,500-year
River Rch & RM= UNT 086 IN DRY C,Reach-1,2433
     158     196     224     129     257     513     337
Boundary for River Rch & Prof#=UNT 086 IN DRY C,Reach-1,1
Up Type=0
Dn Type=3
Dn Slope=0.005
Boundary for River Rch & Prof#=UNT 086 IN DRY C,Reach-1,2
Up Type=0
Dn Type=3
Dn Slope=0.005
Boundary for River Rch & Prof#=UNT 086 IN DRY C,Reach-1,3
Up Type=0
Dn Type=3
Dn Slope=0.005
Boundary for River Rch & Prof#=UNT 086 IN DRY C,Reach-1,4
Up Type=0
Dn Type=3
Dn Slope=0.005
Boundary for River Rch & Prof#=UNT 086 IN DRY C,Reach-1,5
Up Type=0
Dn Type=3
Dn Slope=0.005
Boundary for River Rch & Prof#=UNT 086 IN DRY C,Reach-1,6
Up Type=0
Dn Type=3
Dn Slope=0.005
Boundary for River Rch & Prof#=UNT 086 IN DRY C,Reach-1,7
Up Type=0
Dn Type=3
Dn Slope=0.005

--- UNT 086 IN DRY CR WATERSHED.g01 (geometry) ---

Geom Title=Existing Conditions

River Reach=UNT 086 IN DRY C,Reach-1
Reach XY= 30
      2885539.96      6971576.01      2885709.46      6971604.26
      2885808.33      6971586.10      2885860.80      6971477.14
      2885860.80      6971386.33      2885913.26      6971307.64
      2886002.07      6971248.87      2886193.04      6971189.84
      2886547.62      6971151.87      2886576.83      6971167.06
      2886623.30      6971174.99      2886659.68      6971213.01
      2886686.27      6971219.17      2886781.01      6971170.53
      2886804.45      6971165.46      2886834.49      6971204.89
      2886869.27      6971232.67      2886885.54      6971237.97
      2886929.82      6971232.94      2886954.88      6971242.17
      2886989.66      6971264.69      2887040.06      6971318.00
      2887092.23      6971442.10      2887100.61      6971493.34
      2887123.19      6971536.70      2887127.44      6971644.94
      2887152.18      6971712.12      2887169.14      6971799.24
      2887305.61      6971941.21      2887325.59      6971970.71

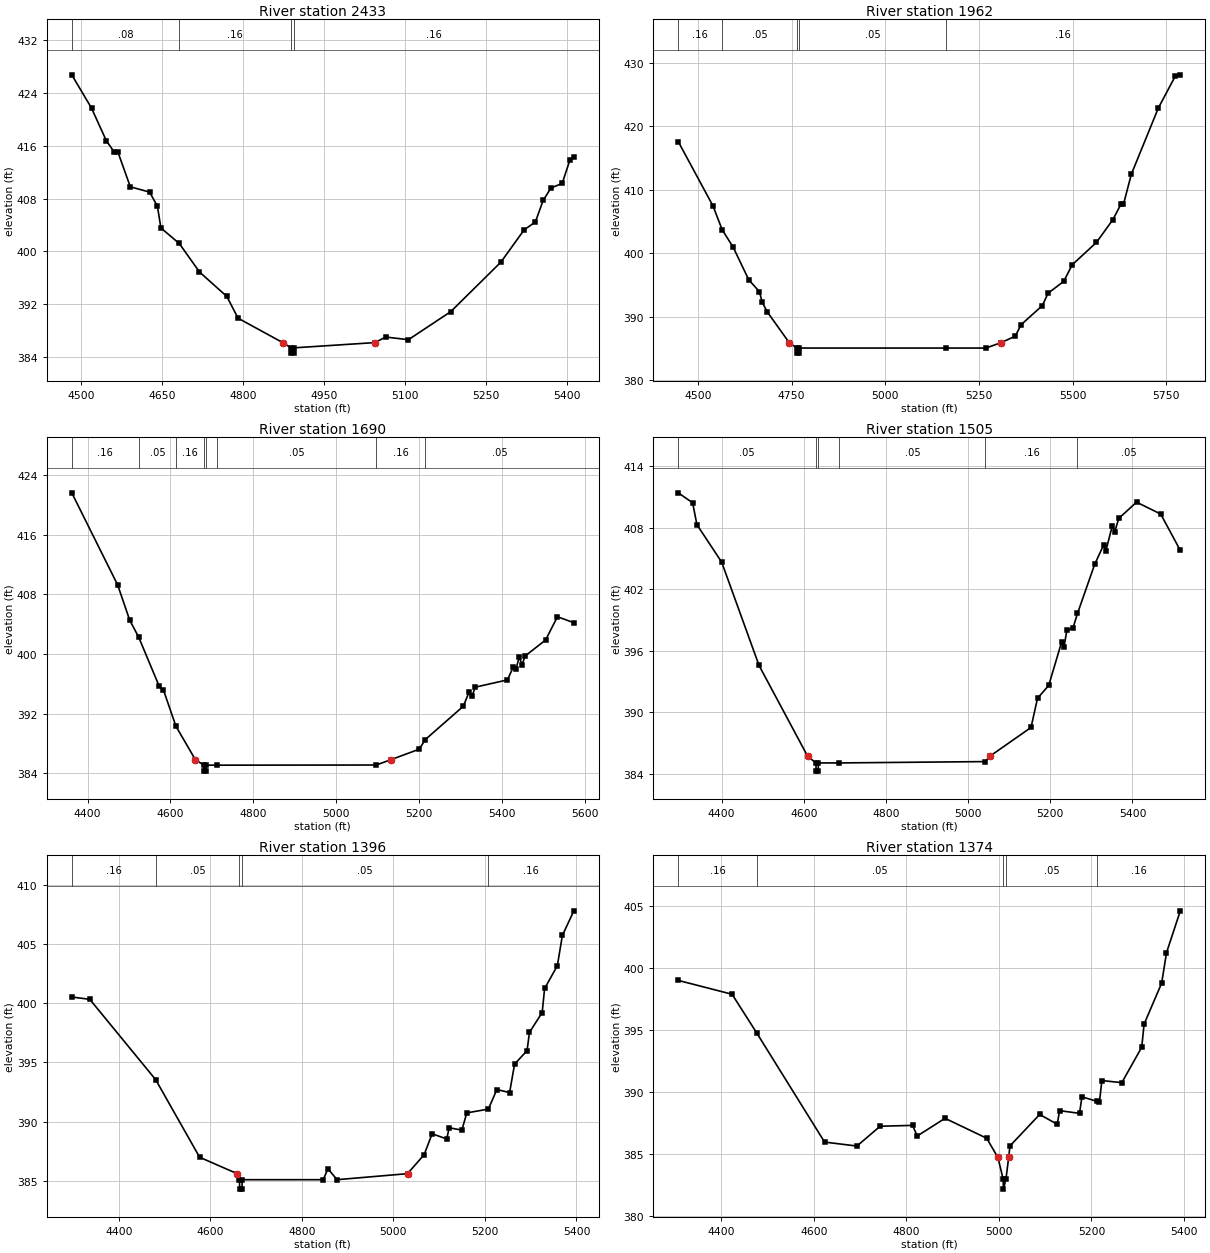
Type RM Length L Ch R = 1,2433,471,471,471
BEGIN DESCRIPTION:
UNT 086 IN DRY CR WATERSHED 5.0
END DESCRIPTION:
XS GIS Cut Line= 3
      2885974.99      6972024.99      2885625.00      6971525.00
      2885374.98      6971324.98
#Sta/Elev= 30
  4483.0  426.69  4519.6  421.66  4547.1  416.72  4561.9  415.01  4568.4  415.05
  4591.5  409.77  4627.3  408.97  4641.7  406.84  4648.2  403.55  4682.2  401.21
  4719.7  396.90  4770.3  393.21  4791.2  389.92  4874.0  386.23  4889.3  385.44
  4889.8  384.64  4894.8  384.64  4895.3  385.44  5044.5  386.23  5065.0  387.07
  5106.9  386.67  5185.4  390.91  5278.2  398.38  5321.4  403.27  5342.2  404.46
  5356.6  407.71  5371.0  409.58  5391.9  410.29  5406.3  413.84  5413.5  414.34
#Mann=4,-1,0
  4483.0    0.08       0  4682.2    0.16       0  4889.3    0.07       0
  4895.3    0.16       0
Bank Sta=4874,5044.5
Exp/Cntr=0.3,0.1

Type RM Length L Ch R = 1,1962,272,272,272
BEGIN DESCRIPTION:
UNT 086 IN DRY CR WATERSHED 4.0
END DESCRIPTION:
XS GIS Cut Line= 3
      2886074.99      6971824.95      2885925.00      6971225.00
      2885325.02      6970825.02
#Sta/Elev= 30
  4447.8  417.58  4540.5  407.45  4564.8  403.73  4594.6  400.92  4635.9  395.82
  4664.2  393.96  4671.9  392.29  4684.8  390.81  4744.1  385.90  4764.3  385.07
  4764.8  384.27  4769.8  384.27  4770.3  385.07  5161.1  385.07  5269.0  385.07
  5308.0  385.90  5347.2  386.94  5362.2  388.73  5419.3  391.76  5434.3  393.69
  5476.4  395.58  5498.9  398.18  5563.5  401.70  5607.1  405.26  5629.6  407.80
  5635.6  407.69  5656.6  412.43  5728.7  422.87  5773.8  427.87  5787.3  428.09
#Mann=5,-1,0
  4447.8    0.16       0  4564.8    0.05       0  4764.3   0.033       0
  4770.3    0.05       0  5161.1    0.16       0
Bank Sta=4744.1,5308
Exp/Cntr=0.3,0.1

Type RM Length L Ch R = 1,1690,185,185,185
BEGIN DESCRIPTION:
UNT 086 IN DRY CR WATERSHED 3.0
END DESCRIPTION:
XS GIS Cut Line= 3
      2886125.00      6971824.96      2886195.61      6971150.85
      2885844.12      6970749.89
#Sta/Elev= 30
  4361.9  421.64  4472.5  409.28  4501.7  404.53  4523.3  402.26  4573.0  395.64
  4583.1  395.15  4613.2  390.29  4660.0  385.81  4680.6  385.07  4681.1  384.27
  4686.1  384.27  4686.6  385.07  4711.3  385.07  5096.1  385.09  5131.8  385.81
  5200.2  387.22  5214.1  388.48  5306.4  392.99  5320.7  394.95  5327.3  394.31
  5334.9  395.54  5412.7  396.52  5427.0  398.27  5433.6  398.04  5441.2  399.59
  5447.8  398.55  5455.4  399.73  5504.8  401.88  5533.3  405.00  5572.9  404.20
#Mann=8,-1,0
  4361.9    0.16       0  4523.3    0.05       0  4613.2    0.16       0
  4680.6   0.033       0  4686.6    0.16       0  4711.3    0.05       0
  5096.1    0.16       0  5214.1    0.05       0
Bank Sta=4660,5131.8
Exp/Cntr=0.3,0.1

Type RM Length L Ch R = 1,1505,109,109,109
BEGIN DESCRIPTION:
Mapping XS 8780abdf
END DESCRIPTION:
XS GIS Cut Line= 3
      2886284.15      6971869.61      2886383.11      6971184.70
      2886117.46      6970726.33
#Sta/Elev= 30
  4294.6  411.42  4329.6  410.45  4340.1  408.31  4400.3  404.66  4491.2  394.58
  4609.5  385.72  4629.7  385.07  4630.2  384.27  4635.2  384.27  4635.7  385.07
  4686.6  385.07  5041.9  385.20  5052.8  385.72  5153.1  388.53  5168.9  391.38
  5196.2  392.63  5227.7  396.88  5233.5  396.42  5240.5  398.03  5255.0  398.21
  5266.2  399.65  5308.0  404.44  5329.5  406.31  5335.3  405.78  5351.1  408.23
  5356.8  407.64  5366.8  408.93  5409.9  410.51  5468.7  409.35  5516.4  405.80
#Mann=6,-1,0
  4294.6    0.05       0  4629.7    0.03       0  4635.7    0.05       0
  4686.6    0.05       0  5041.9    0.16       0  5266.2    0.05       0
Bank Sta=4609.5,5052.8
Exp/Cntr=0.3,0.1

Type RM Length L Ch R = 1,1396,22,22,22
BEGIN DESCRIPTION:
Mapping XS 1661ed09
END DESCRIPTION:
XS GIS Cut Line= 4
      2886495.09      6971864.41      2886500.30      6971416.47
      2886479.46      6971075.33      2886390.91      6970781.01
#Sta/Elev= 30
  4297.2  400.55  4336.6  400.35  4480.6  393.54  4576.6  386.97  4658.6  385.58
  4663.6  385.07  4664.1  384.27  4669.1  384.27  4669.6  385.07  4846.8  385.07
  4856.8  386.00  4876.9  385.07  5030.9  385.58  5067.2  387.19  5084.6  388.96
  5116.6  388.52  5121.8  389.47  5149.6  389.27  5160.4  390.73  5207.5  391.05
  5226.1  392.71  5253.9  392.45  5264.8  394.86  5292.1  396.01  5297.3  397.55
  5325.1  399.23  5330.4  401.27  5358.2  403.19  5369.2  405.76  5394.3  407.85
#Mann=5,-1,0
  4297.2    0.16       0  4480.6    0.05       0  4663.6    0.03       0
  4669.6    0.05       0  5207.5    0.16       0
Bank Sta=4658.6,5030.9
Exp/Cntr=0.3,0.1

Type RM Length L Ch R = 1,1374,27,27,27
BEGIN DESCRIPTION:
Mapping XS cdb0e0c5
END DESCRIPTION:
XS GIS Cut Line= 4
      2886534.15      6971851.32      2886523.73      6971442.52
      2886505.50      6971143.04      2886422.17      6970775.85
#Sta/Elev= 30
  4306.6  399.01  4423.0  397.89  4476.2  394.77  4623.0  385.95  4693.0  385.63
  4743.1  387.23  4813.2  387.30  4823.3  386.44  4883.4  387.87  4973.5  386.26
  4997.7  384.71  5009.1  382.95  5009.6  382.15  5015.1  382.95  5021.0  384.71
  5023.8  385.64  5088.0  388.18  5126.0  387.39  5131.1  388.49  5174.2  388.27
  5179.4  389.61  5212.7  389.23  5217.3  389.18  5222.5  390.92  5265.6  390.75
  5308.7  393.61  5313.8  395.48  5351.8  398.79  5362.2  401.24  5392.1  404.63
#Mann=5,-1,0
  4306.6    0.16       0  4476.2    0.05       0  5009.1    0.03       0
  5015.1    0.05       0  5212.7    0.16       0
Bank Sta=4997.7,5021
Exp/Cntr=0.3,0.1

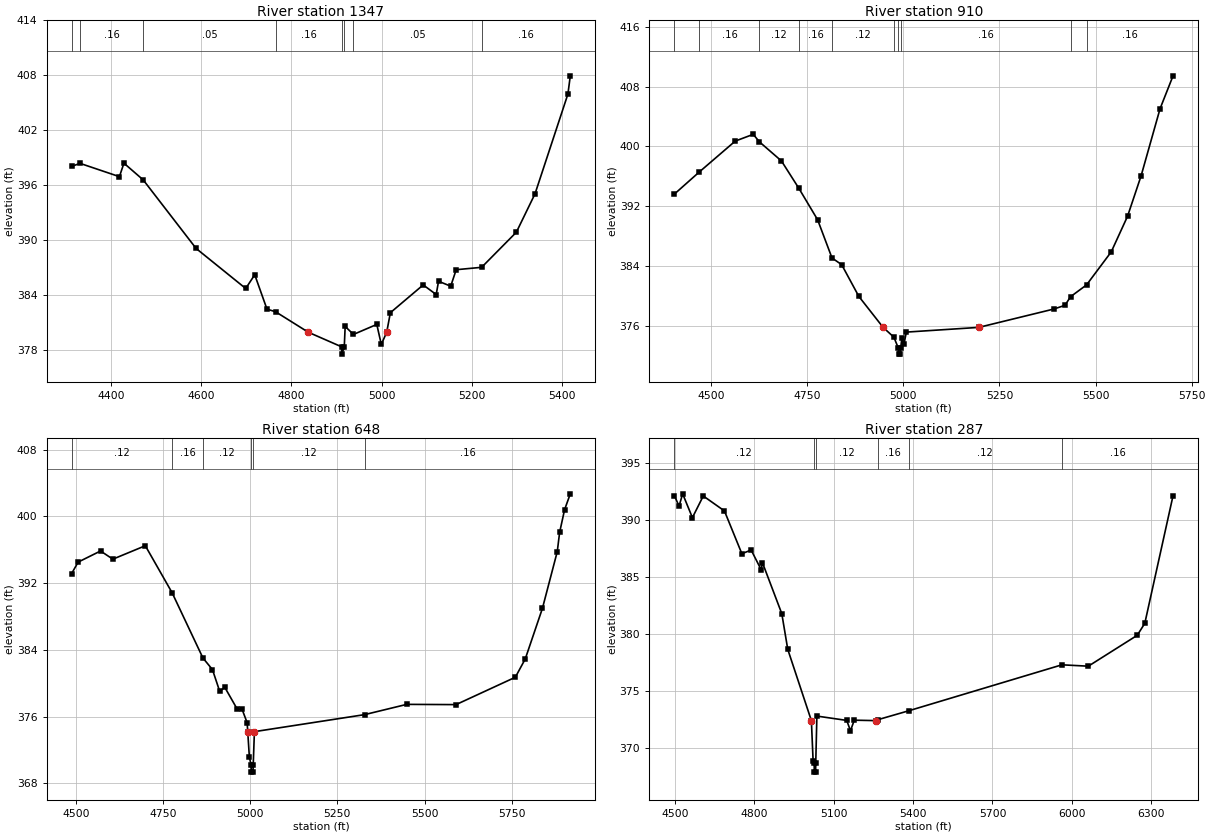
Type RM Length L Ch R = 1,1347,437,437,437
BEGIN DESCRIPTION:
Mapping XS 81609bab
END DESCRIPTION:
XS GIS Cut Line= 4
      2886552.38      6971840.95      2886549.77      6971364.39
      2886528.94      6971098.77      2886430.02      6970749.93
#Sta/Elev= 30
  4312.6  398.06  4331.3  398.39  4418.6  396.94  4428.6  398.41  4471.3  396.59
  4588.6  389.11  4698.6  384.74  4718.6  386.24  4745.7  382.49  4764.9  382.20
  4837.3  379.97  4911.1  378.38  4911.6  377.58  4917.1  378.38  4919.1  380.60
  4937.5  379.73  4989.2  380.82  4999.2  378.64  5011.2  379.97  5019.3  382.10
  5092.1  385.13  5120.9  384.08  5126.1  385.53  5153.1  384.99  5165.2  386.79
  5221.6  387.05  5298.6  390.88  5340.0  395.07  5412.9  405.95  5418.2  407.94
#Mann=8,-1,0
  4312.6    0.12       0  4331.3    0.16       0  4471.3    0.05       0
  4764.9    0.16       0  4911.1    0.03       0  4917.1    0.16       0
  4937.5    0.05       0  5221.6    0.16       0
Bank Sta=4837.3,5011.2
Exp/Cntr=0.3,0.1

Type RM Length L Ch R = 1,910,262,262,262
BEGIN DESCRIPTION:
Mapping XS 97f25a80
END DESCRIPTION:
XS GIS Cut Line= 3
      2886708.64      6971799.26      2886903.94      6971226.37
      2886433.28      6970719.31
#Sta/Elev= 30
  4404.5  393.64  4469.5  396.60  4562.9  400.72  4609.7  401.62  4625.9  400.61
  4683.0  398.07  4728.4  394.41  4777.1  390.22  4814.5  385.12  4839.7  384.22
  4884.4  379.98  4947.5  375.85  4975.5  374.54  4987.1  373.08  4987.6  372.28
  4992.6  372.28  4993.1  373.08  4996.5  374.49  5001.7  373.60  5007.9  375.22
  5196.3  375.85  5392.3  378.31  5420.6  378.80  5434.9  379.94  5476.6  381.52
  5540.8  385.93  5583.3  390.69  5618.5  396.08  5667.8  405.04  5701.6  409.43
#Mann=10,-1,0
  4404.5    0.12       0  4469.5    0.16       0  4625.9    0.12       0
  4728.4    0.16       0  4814.5    0.12       0  4975.5    0.16       0
  4987.1    0.07       0  4993.1    0.16       0  5434.9    0.05       0
  5476.6    0.16       0
Bank Sta=4947.5,5196.3
Exp/Cntr=0.3,0.1

Type RM Length L Ch R = 1,648,361,361,361
BEGIN DESCRIPTION:
Mapping XS f8f44dfb
END DESCRIPTION:
XS GIS Cut Line= 4
      2886758.11      6971804.50      2887099.25      6971369.60
      2887073.21      6971304.49      2886526.32      6970710.73
#Sta/Elev= 30
  4487.9  393.13  4506.7  394.51  4570.9  395.84  4606.2  394.86  4699.3  396.47
  4776.2  390.83  4864.6  383.01  4891.8  381.63  4912.6  379.02  4927.1  379.51
  4962.4  376.92  4976.8  376.87  4991.3  375.26  4993.0  374.18  4997.6  371.20
  5002.7  370.14  5003.2  369.34  5008.2  369.34  5008.7  370.14  5012.1  374.19
  5328.1  376.23  5449.1  377.46  5590.3  377.43  5760.4  380.71  5788.8  382.90
  5838.1  388.97  5880.6  395.76  5887.4  398.07  5901.6  400.79  5918.0  402.69
#Mann=6,-1,0
  4487.9    0.12       0  4776.2    0.16       0  4864.6    0.12       0
  5002.7    0.07       0  5008.7    0.12       0  5328.1    0.16       0
Bank Sta=4993,5012.1
Exp/Cntr=0.3,0.1

Type RM Length L Ch R = 1,287,0,0,0
BEGIN DESCRIPTION:
UNT 086 IN DRY CR WATERSHED 1.0
END DESCRIPTION:
XS GIS Cut Line= 4
      2886677.41      6971853.97      2887104.46      6971796.68
      2887323.21      6971590.95      2886583.65      6970705.56
#Sta/Elev= 30
  4497.7  392.14  4515.4  391.21  4529.1  392.29  4565.9  390.20  4607.0  392.10
  4687.0  390.79  4752.9  387.03  4787.9  387.36  4825.8  385.63  4830.8  386.24
  4903.8  381.77  4926.3  378.64  5015.6  372.38  5022.2  368.80  5026.1  368.66
  5026.6  367.86  5031.6  367.86  5032.1  368.66  5036.4  372.78  5149.2  372.40
  5163.4  371.49  5177.6  372.42  5261.4  372.38  5267.8  372.47  5382.7  373.24
  5962.5  377.28  6062.3  377.16  6247.1  379.87  6275.7  380.92  6382.5  392.13
#Mann=6,-1,0
  4497.7    0.12       0  5026.1    0.07       0  5032.1    0.12       0
  5267.8    0.16       0  5382.7    0.12       0  5962.5    0.16       0
Bank Sta=5015.6,5261.4
Exp/Cntr=0.3,0.1

Chan Stop Cuts=-1