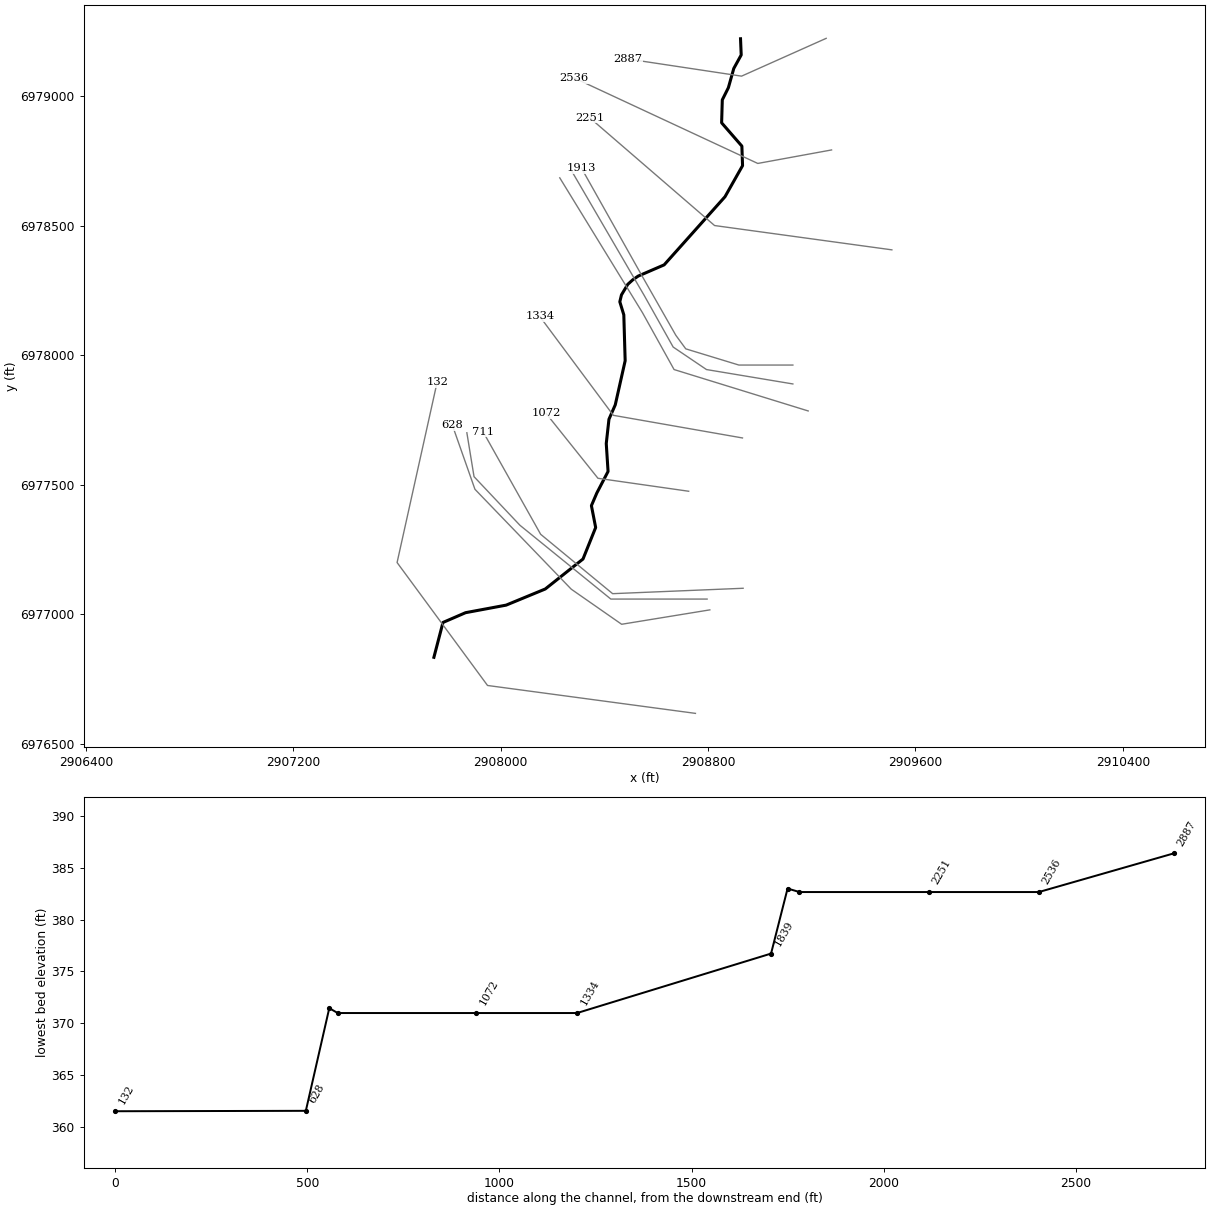
--- UNT 087 IN DRY CR WATERSHED.prj (project) ---

Proj Title=UNT 087 IN DRY CR WATERSHED Base Level Engineering
Current Plan=p01
Default Exp/Contr=0.3,0.1
English Units
Geom File=g01
Flow File=f01
Plan File=p01
BEGIN DESCRIPTION:
UNT 087 IN DRY CR WATERSHED
END DESCRIPTION:

--- UNT 087 IN DRY CR WATERSHED.p01 (plan) ---

Plan Title=Multiple Run
Short Identifier=Multiple
Geom File=g01
Flow File=f01
Subcritical Flow
K Sum by GR= 0
Std Step Tol= 0.01
Critical Tol= 0.01
Num of Std Step Trials= 20
Max Error Tol= 0.3
Flow Tol Ratio= 0.001
Split Flow NTrial= 30
Split Flow Tol= 0.02
Split Flow Ratio= 0.02
Log Output Level= 0
Friction Slope Method= 1
Unsteady Friction Slope Method= 2
Unsteady Bridges Friction Slope Method= 1
Parabolic Critical Depth
Global Vel Dist=  1 , 1 , 1
Global Log Level= 0
CheckData=True
Encroach Param= -1, 0, 0, 0
BEGIN DESCRIPTION:
Multiple Run
END DESCRIPTION:

--- UNT 087 IN DRY CR WATERSHED.f01 (steady flow) ---

Flow Title=Multiple
Number of Profiles=7
Profile Names=10-year,25-year,50-year,1pct_min,100-year,1pct_plu,500-year
River Rch & RM= UNT 087 IN DRY C,Reach-1,2887
     169     210     240     138     275     548     358
Boundary for River Rch & Prof#=UNT 087 IN DRY C,Reach-1,1
Up Type=0
Dn Type=3
Dn Slope=0.005
Boundary for River Rch & Prof#=UNT 087 IN DRY C,Reach-1,2
Up Type=0
Dn Type=3
Dn Slope=0.005
Boundary for River Rch & Prof#=UNT 087 IN DRY C,Reach-1,3
Up Type=0
Dn Type=3
Dn Slope=0.005
Boundary for River Rch & Prof#=UNT 087 IN DRY C,Reach-1,4
Up Type=0
Dn Type=3
Dn Slope=0.005
Boundary for River Rch & Prof#=UNT 087 IN DRY C,Reach-1,5
Up Type=0
Dn Type=3
Dn Slope=0.005
Boundary for River Rch & Prof#=UNT 087 IN DRY C,Reach-1,6
Up Type=0
Dn Type=3
Dn Slope=0.005
Boundary for River Rch & Prof#=UNT 087 IN DRY C,Reach-1,7
Up Type=0
Dn Type=3
Dn Slope=0.005

--- UNT 087 IN DRY CR WATERSHED.g01 (geometry) ---

Geom Title=Existing Conditions

River Reach=UNT 087 IN DRY C,Reach-1
Reach XY= 30
      2908924.97      6979220.64      2908927.57      6979158.14
      2908898.93      6979106.06      2908878.10      6979031.84
      2908854.66      6978984.96      2908852.05      6978896.42
      2908930.18      6978806.58      2908932.78      6978731.06
      2908865.07      6978611.27      2908630.29      6978348.41
      2908530.17      6978305.11      2908509.61      6978291.00
      2908490.05      6978273.38      2908465.64      6978232.53
      2908459.29      6978205.92      2908474.68      6978155.65
      2908479.90      6977978.51      2908441.71      6977808.37
      2908417.40      6977752.81      2908406.99      6977659.06
      2908413.93      6977551.42      2908370.53      6977468.09
      2908349.69      6977419.48      2908366.10      6977335.11
      2908317.27      6977213.59      2908171.74      6977097.97
      2908020.76      6977035.69      2907864.08      6977006.52
      2907777.07      6976968.81      2907742.05      6976834.41

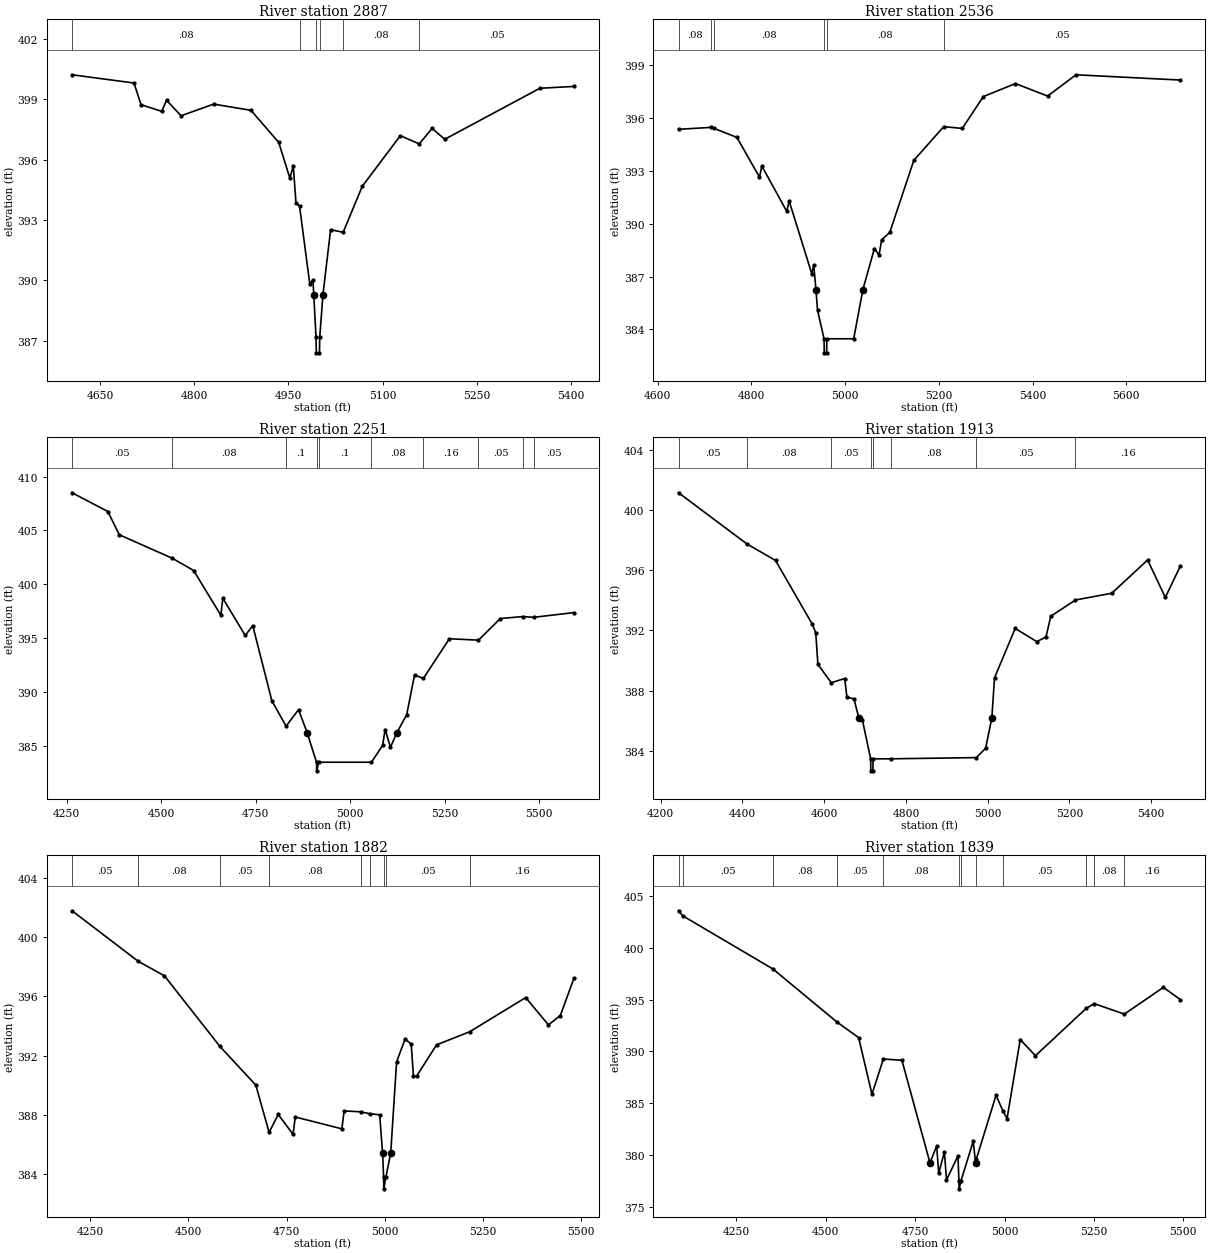
Type RM Length L Ch R = 1,2887,351,351,351
BEGIN DESCRIPTION:
UNT 087 IN DRY CR WATERSHED 5.0
END DESCRIPTION:
XS GIS Cut Line= 3
      2909255.44      6979222.33      2908929.01      6979076.47
      2908491.49      6979142.45
#Sta/Elev= 30
  4605.0  400.23  4703.7  399.82  4715.0  398.74  4747.9  398.41  4755.6  398.96
  4778.8  398.19  4830.7  398.77  4890.3  398.46  4934.5  396.86  4952.2  395.09
  4957.7  395.69  4962.0  393.84  4967.6  393.71  4984.0  389.81  4989.0  390.03
  4990.3  389.29  4993.9  387.19  4994.4  386.39  4999.4  386.39  4999.9  387.19
  5005.0  389.29  5017.2  392.52  5037.2  392.39  5067.7  394.68  5128.4  397.20
  5158.5  396.79  5179.0  397.56  5199.2  397.02  5350.9  399.56  5405.0  399.65
#Mann=6,-1,0
  4605.0    0.08       0  4967.6    0.16       0  4993.9    0.07       0
  4999.9    0.16       0  5037.2    0.08       0  5158.5    0.05       0
Bank Sta=4990.3,5005
Exp/Cntr=0.3,0.1

Type RM Length L Ch R = 1,2536,285,285,285
BEGIN DESCRIPTION:
Mapping XS 69a67a7f
END DESCRIPTION:
XS GIS Cut Line= 3
      2909276.21      6978791.75      2908991.51      6978739.67
      2908283.18      6979069.53
#Sta/Elev= 30
  4644.4  395.37  4714.4  395.48  4720.5  395.42  4769.0  394.91  4817.1  392.65
  4822.2  393.28  4875.4  390.70  4880.5  391.29  4928.6  387.17  4932.9  387.64
  4937.7  386.25  4941.0  385.08  4954.9  383.46  4955.4  382.66  4960.4  382.66
  4960.9  383.46  5018.2  383.46  5037.7  386.25  5062.4  388.59  5072.3  388.22
  5077.8  389.08  5095.2  389.51  5146.4  393.60  5210.2  395.52  5249.9  395.42
  5294.7  397.23  5363.4  397.97  5432.0  397.26  5492.6  398.47  5715.2  398.17
#Mann=6,-1,0
  4644.4    0.08       0  4714.4    0.05       0  4720.5    0.08       0
  4954.9    0.07       0  4960.9    0.08       0  5210.2    0.05       0
Bank Sta=4937.7,5037.7
Exp/Cntr=0.3,0.1

Type RM Length L Ch R = 1,2251,338,338,338
BEGIN DESCRIPTION:
Mapping XS 684b169c
END DESCRIPTION:
XS GIS Cut Line= 3
      2909508.86      6978406.34      2908824.85      6978500.09
      2908342.22      6978916.74
#Sta/Elev= 30
  4264.1  408.49  4358.8  406.75  4389.1  404.59  4529.7  402.40  4585.8  401.27
  4657.9  397.11  4663.0  398.70  4722.2  395.24  4742.4  396.14  4792.9  389.16
  4830.5  386.81  4863.5  388.34  4886.3  386.20  4911.0  383.46  4911.5  382.66
  4917.0  383.46  5056.5  383.46  5086.0  385.03  5092.6  386.50  5106.8  384.85
  5123.6  386.20  5149.6  387.86  5170.5  391.57  5193.8  391.24  5262.6  394.93
  5339.7  394.80  5397.5  396.81  5456.9  396.99  5485.5  396.92  5592.1  397.36
#Mann=10,-1,0
  4264.1    0.05       0  4529.7    0.08       0  4830.5     0.1       0
  4911.0    0.07       0  4917.0     0.1       0  5056.5    0.08       0
  5193.8    0.16       0  5339.7    0.05       0  5456.9    0.16       0
  5485.5    0.05       0
Bank Sta=4886.3,5123.6
Exp/Cntr=0.3,0.1

Type RM Length L Ch R = 1,1913,31,31,31
BEGIN DESCRIPTION:
Mapping XS 09578bbd
END DESCRIPTION:
XS GIS Cut Line= 6
      2909126.97      6977961.89      2908918.60      6977961.89
      2908713.73      6978024.39      2908675.54      6978076.47
      2908547.07      6978302.17      2908311.58      6978721.19
#Sta/Elev= 30
  4243.7  401.15  4410.9  397.75  4480.9  396.65  4570.8  392.42  4579.4  391.84
  4584.6  389.74  4617.3  388.52  4650.2  388.80  4655.5  387.57  4672.9  387.44
  4684.8  386.18  4693.7  386.02  4713.6  383.46  4714.1  382.66  4719.1  382.66
  4719.6  383.46  4763.6  383.46  4972.3  383.54  4995.0  384.17  5010.1  386.18
  5016.7  388.85  5067.3  392.13  5120.0  391.25  5142.5  391.56  5154.4  392.94
  5214.6  394.02  5303.5  394.47  5391.2  396.68  5434.5  394.19  5471.2  396.27
#Mann=8,-1,0
  4243.7    0.05       0  4410.9    0.08       0  4617.3    0.05       0
  4713.6    0.04       0  4719.6    0.05       0  4763.6    0.08       0
  4972.3    0.05       0  5214.6    0.16       0
Bank Sta=4684.8,5010.1
Exp/Cntr=0.3,0.1

Type RM Length L Ch R = 1,1882,43,43,43
BEGIN DESCRIPTION:
Mapping XS ed18aee8
END DESCRIPTION:
XS GIS Cut Line= 5
      2909126.90      6977888.98      2908793.60      6977944.53
      2908665.12      6978031.34      2908554.01      6978229.25
      2908273.33      6978710.92
#Sta/Elev= 30
  4204.1  401.77  4372.5  398.36  4439.2  397.38  4580.6  392.61  4671.9  390.00
  4705.7  386.81  4728.9  388.02  4766.6  386.68  4772.3  387.85  4890.9  387.05
  4896.7  388.26  4938.7  388.20  4962.5  388.07  4987.2  388.00  4994.6  385.41
  4997.1  383.80  4997.6  383.00  5003.1  383.80  5015.3  385.42  5030.2  391.57
  5051.7  393.10  5067.4  392.78  5073.2  390.59  5081.1  390.60  5131.9  392.72
  5216.1  393.60  5358.9  395.91  5416.8  394.07  5447.1  394.70  5481.5  397.20
#Mann=9,-1,0
  4204.1    0.05       0  4372.5    0.08       0  4580.6    0.05       0
  4705.7    0.08       0  4938.7    0.16       0  4962.5    0.05       0
  4997.1    0.04       0  5003.1    0.05       0  5216.1    0.16       0
Bank Sta=4994.6,5015.3
Exp/Cntr=0.3,0.1

Type RM Length L Ch R = 1,1839,505,505,505
BEGIN DESCRIPTION:
Mapping XS 95d0c614
END DESCRIPTION:
XS GIS Cut Line= 4
      2909185.95      6977784.81      2908668.60      6977944.53
      2908547.07      6978163.28      2908227.62      6978684.12
#Sta/Elev= 30
  4088.8  403.58  4100.2  403.10  4352.6  397.96  4531.7  392.83  4592.2  391.33
  4629.5  385.86  4661.4  389.26  4713.2  389.14  4791.6  379.24  4810.4  380.85
  4816.1  378.23  4832.1  380.29  4837.8  377.57  4869.9  379.91  4872.6  377.52
  4873.1  376.72  4878.6  377.52  4912.5  381.30  4919.2  379.24  4921.4  379.61
  4976.4  385.76  4995.6  384.24  5007.2  383.50  5044.0  391.14  5086.5  389.58
  5228.3  394.15  5250.5  394.61  5335.1  393.60  5444.2  396.18  5491.5  395.00
#Mann=12,-1,0
  4088.8    0.08       0  4100.2    0.05       0  4352.6    0.08       0
  4531.7    0.05       0  4661.4    0.08       0  4872.6    0.04       0
  4878.6    0.08       0  4921.4    0.16       0  4995.6    0.05       0
  5228.3    0.16       0  5250.5    0.08       0  5335.1    0.16       0
Bank Sta=4791.6,4919.2
Exp/Cntr=0.3,0.1

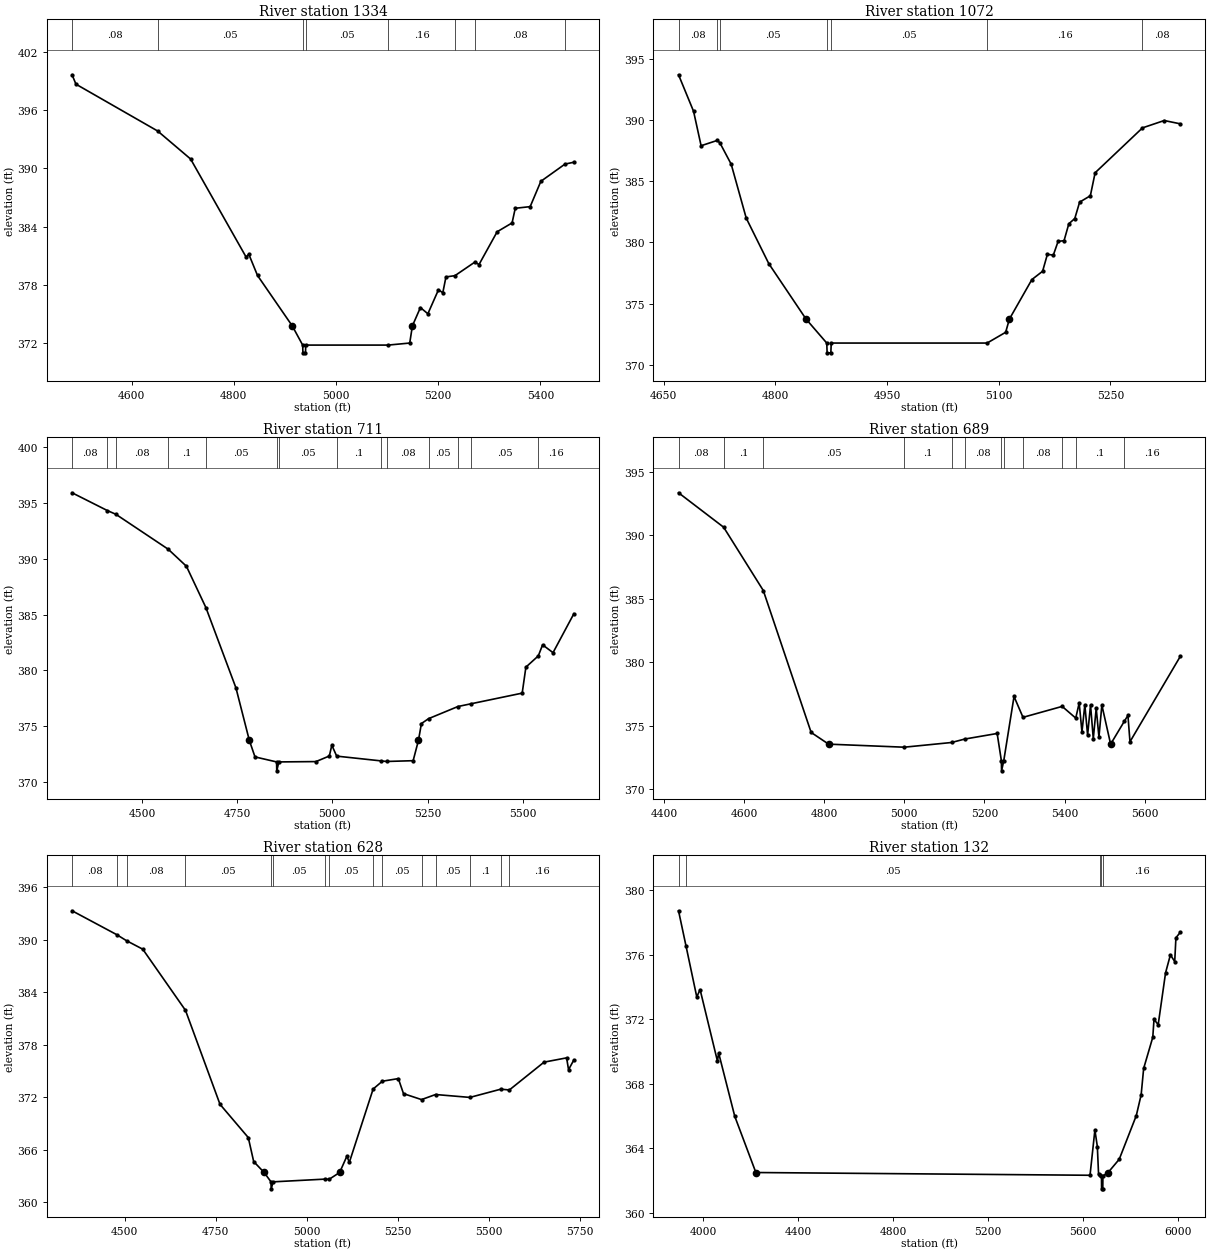
Type RM Length L Ch R = 1,1334,262,262,262
BEGIN DESCRIPTION:
UNT 087 IN DRY CR WATERSHED 3.0
END DESCRIPTION:
XS GIS Cut Line= 3
      2908932.48      6977680.64      2908434.18      6977767.97
      2908150.02      6978149.98
#Sta/Elev= 30
  4483.4  399.66  4491.0  398.69  4650.9  393.86  4715.4  390.97  4824.1  380.85
  4829.2  381.16  4846.3  378.96  4914.3  373.76  4934.7  371.78  4935.2  370.98
  4940.2  370.98  4940.7  371.78  5102.1  371.78  5144.2  371.99  5149.4  373.76
  5165.1  375.65  5179.7  375.01  5200.5  377.49  5208.9  377.17  5215.1  378.81
  5232.7  378.94  5271.4  380.33  5279.8  380.09  5315.3  383.47  5344.5  384.38
  5350.7  385.89  5379.9  386.06  5400.8  388.67  5448.1  390.45  5465.4  390.64
#Mann=8,-1,0
  4483.4    0.08       0  4650.9    0.05       0  4934.7   0.033       0
  4940.7    0.05       0  5102.1    0.16       0  5232.7    0.05       0
  5271.4    0.08       0  5448.1    0.05       0
Bank Sta=4914.3,5149.4
Exp/Cntr=0.3,0.1

Type RM Length L Ch R = 1,1072,361,361,361
BEGIN DESCRIPTION:
UNT 087 IN DRY CR WATERSHED 2.0
END DESCRIPTION:
XS GIS Cut Line= 3
      2908725.01      6977475.00      2908375.00      6977525.00
      2908175.01      6977774.99
#Sta/Elev= 30
  4670.1  393.71  4690.3  390.72  4700.4  387.91  4721.9  388.34  4725.5  388.16
  4740.8  386.40  4761.0  381.99  4791.3  378.27  4841.3  373.74  4869.1  371.78
  4869.6  370.98  4874.6  370.98  4875.1  371.78  5084.4  371.78  5109.3  372.66
  5114.3  373.74  5144.5  376.97  5158.9  377.65  5165.3  379.03  5173.3  378.97
  5179.7  380.09  5187.7  380.15  5194.1  381.53  5202.1  381.96  5208.6  383.30
  5223.0  383.82  5229.4  385.70  5293.0  389.37  5322.2  389.97  5343.8  389.70
#Mann=7,-1,0
  4670.1    0.08       0  4721.9    0.16       0  4725.5    0.05       0
  4869.1   0.033       0  4875.1    0.05       0  5084.4    0.16       0
  5293.0    0.08       0
Bank Sta=4841.3,5114.3
Exp/Cntr=0.3,0.1

Type RM Length L Ch R = 1,711,22,22,22
BEGIN DESCRIPTION:
Mapping XS 69549c3f
END DESCRIPTION:
XS GIS Cut Line= 4
      2908935.03      6977100.72      2908431.59      6977079.89
      2908153.81      6977309.06      2907931.60      6977704.86
#Sta/Elev= 30
  4316.4  395.92  4408.8  394.33  4431.5  393.99  4568.8  390.86  4616.7  389.33
  4667.8  385.63  4746.8  378.42  4781.9  373.72  4796.8  372.23  4853.5  371.78
  4854.0  370.98  4859.5  371.78  4956.9  371.81  4992.1  372.31  4998.6  373.28
  5011.4  372.30  5128.5  371.87  5142.3  371.82  5212.2  371.89  5226.2  373.72
  5233.9  375.22  5252.7  375.66  5329.9  376.75  5363.5  376.99  5498.6  377.95
  5508.3  380.28  5540.9  381.29  5552.2  382.28  5579.6  381.58  5634.3  385.07
#Mann=14,-1,0
  4316.4    0.08       0  4408.8    0.05       0  4431.5    0.08       0
  4568.8     0.1       0  4667.8    0.05       0  4853.5   0.033       0
  4859.5    0.05       0  5011.4     0.1       0  5128.5    0.05       0
  5142.3    0.08       0  5252.7    0.05       0  5329.9    0.08       0
  5363.5    0.05       0  5540.9    0.16       0
Bank Sta=4781.9,5226.2
Exp/Cntr=0.3,0.1

Type RM Length L Ch R = 1,689,61,61,61
BEGIN DESCRIPTION:
Mapping XS 3eb9bbb2
END DESCRIPTION:
XS GIS Cut Line= 5
      2908796.13      6977059.06      2908424.64      6977059.06
      2908073.95      6977343.78      2907896.87      6977531.28
      2907869.20      6977700.72
#Sta/Elev= 30
  4436.2  393.33  4548.8  390.62  4647.8  385.64  4767.3  374.47  4810.9  373.55
  4999.7  373.31  5117.8  373.68  5150.6  373.95  5231.7  374.39  5242.2  372.25
  5242.7  371.45  5248.2  372.25  5273.8  377.30  5296.2  375.66  5394.0  376.52
  5427.9  375.60  5436.5  376.79  5443.4  374.51  5450.6  376.65  5457.5  374.26
  5464.8  376.63  5471.7  373.98  5479.0  376.38  5485.8  374.10  5493.1  376.62
  5515.0  373.55  5549.0  375.34  5558.2  375.81  5563.3  373.74  5689.0  380.46
#Mann=12,-1,0
  4436.2    0.08       0  4548.8     0.1       0  4647.8    0.05       0
  4999.7     0.1       0  5117.8    0.05       0  5150.6    0.08       0
  5242.2    0.07       0  5248.2    0.08       0  5296.2    0.08       0
  5394.0    0.05       0  5427.9     0.1       0  5549.0    0.16       0
Bank Sta=4810.9,5515
Exp/Cntr=0.3,0.1

Type RM Length L Ch R = 1,628,496,496,496
BEGIN DESCRIPTION:
Mapping XS b596df6a
END DESCRIPTION:
XS GIS Cut Line= 5
      2908806.62      6977017.39      2908466.31      6976961.83
      2908271.87      6977097.25      2907900.34      6977482.67
      2907813.52      6977729.23
#Sta/Elev= 30
  4355.1  393.32  4478.3  390.58  4504.7  389.90  4549.3  388.93  4666.7  381.94
  4761.5  371.20  4839.2  367.40  4854.0  364.66  4882.7  363.41  4901.6  362.34
  4902.1  361.54  4907.6  362.34  5049.3  362.65  5061.3  362.63  5090.2  363.41
  5109.9  365.26  5116.9  364.58  5182.2  372.95  5207.5  373.84  5251.4  374.14
  5265.6  372.42  5315.1  371.74  5353.7  372.32  5448.0  371.99  5532.8  372.93
  5556.4  372.84  5651.7  376.02  5713.7  376.51  5719.0  375.16  5733.6  376.27
#Mann=15,-1,0
  4355.1    0.08       0  4478.3     0.1       0  4504.7    0.08       0
  4666.7    0.05       0  4901.6    0.04       0  4907.6    0.05       0
  5049.3     0.1       0  5061.3    0.05       0  5182.2    0.08       0
  5207.5    0.05       0  5315.1    0.08       0  5353.7    0.05       0
  5448.0     0.1       0  5532.8    0.05       0  5556.4    0.16       0
Bank Sta=4882.7,5090.2
Exp/Cntr=0.3,0.1

Type RM Length L Ch R = 1,132,0,0,0
BEGIN DESCRIPTION:
UNT 087 IN DRY CR WATERSHED 1.0
END DESCRIPTION:
XS GIS Cut Line= 4
      2908751.05      6976618.08      2907948.95      6976725.72
      2907600.00      6977200.00      2907754.50      6977895.85
#Sta/Elev= 30
  3897.6  378.71  3929.5  376.50  3974.3  373.38  3988.3  373.83  4061.2  369.41
  4066.3  369.91  4134.1  365.99  4222.9  362.51  5628.6  362.34  5649.1  365.14
  5659.4  364.12  5664.6  362.39  5671.8  362.35  5676.8  362.30  5677.3  361.50
  5682.3  361.50  5682.8  362.30  5704.6  362.51  5751.5  363.33  5823.2  366.03
  5843.7  367.32  5854.2  368.95  5892.6  370.88  5897.8  371.99  5915.4  371.66
  5946.4  374.87  5966.7  375.98  5984.9  375.57  5990.0  377.04  6008.5  377.38
#Mann=5,-1,0
  3897.6    0.08       0  3929.5    0.05       0  5671.8    0.16       0
  5676.8   0.033       0  5682.8    0.16       0
Bank Sta=4222.9,5704.6
Exp/Cntr=0.3,0.1

Chan Stop Cuts=-1