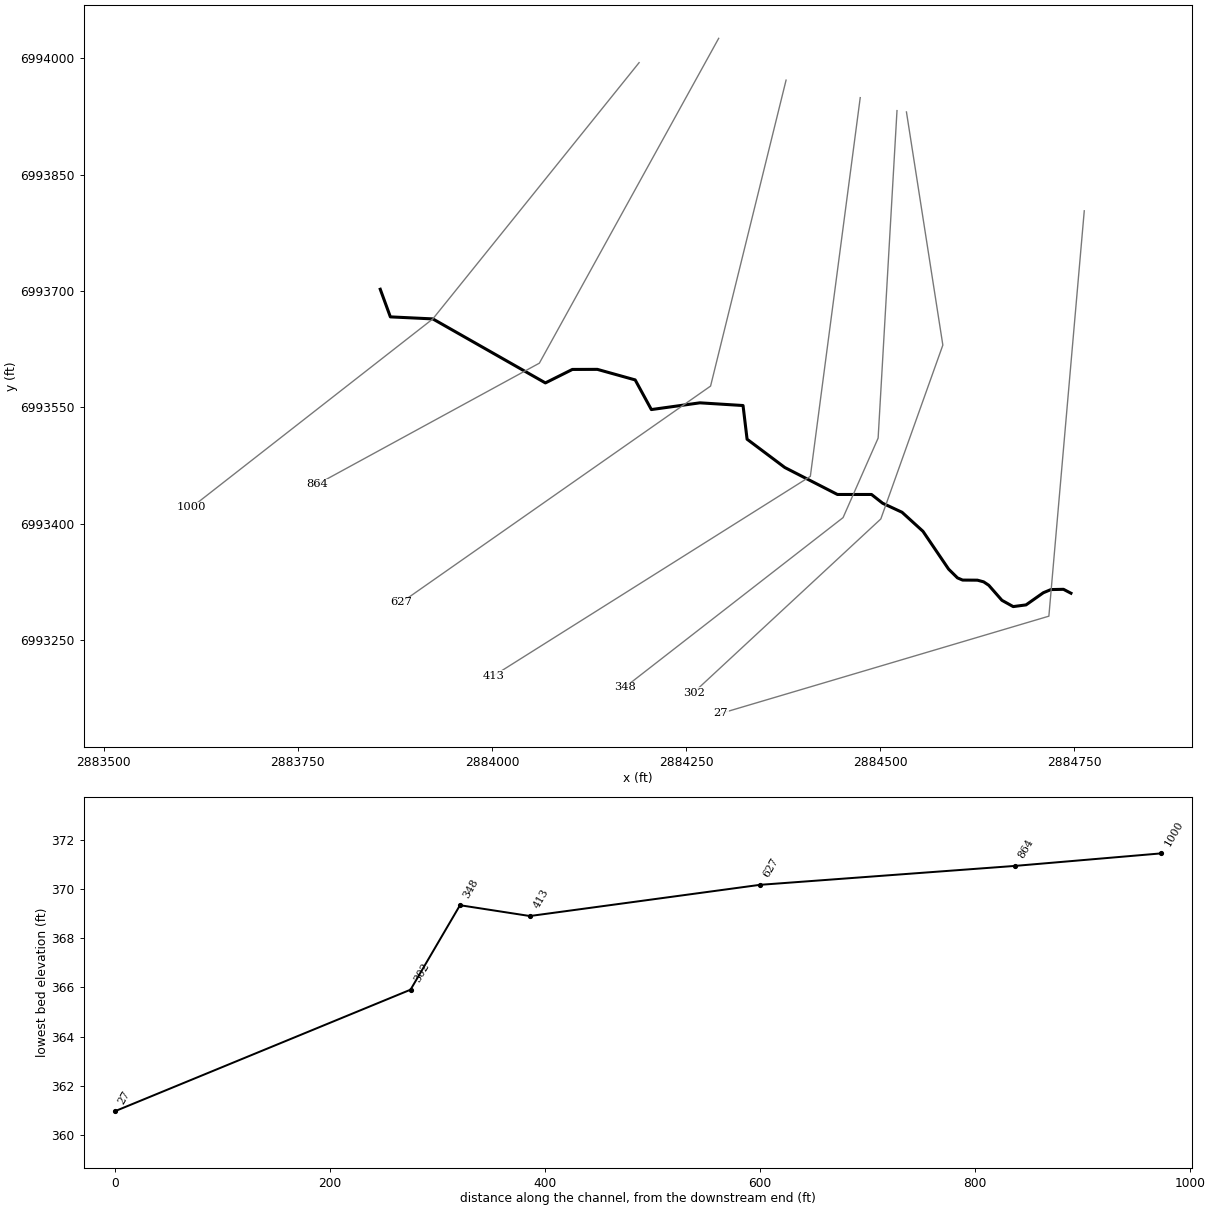
--- UNT 088 IN DRY CR WATERSHED.prj (project) ---

Proj Title=UNT 088 IN DRY CR WATERSHED Base Level Engineering
Current Plan=p01
Default Exp/Contr=0.3,0.1
English Units
Geom File=g01
Flow File=f01
Plan File=p01
BEGIN DESCRIPTION:
UNT 088 IN DRY CR WATERSHED
END DESCRIPTION:

--- UNT 088 IN DRY CR WATERSHED.p01 (plan) ---

Plan Title=Multiple Run
Short Identifier=Multiple
Geom File=g01
Flow File=f01
Subcritical Flow
K Sum by GR= 0
Std Step Tol= 0.01
Critical Tol= 0.01
Num of Std Step Trials= 20
Max Error Tol= 0.3
Flow Tol Ratio= 0.001
Split Flow NTrial= 30
Split Flow Tol= 0.02
Split Flow Ratio= 0.02
Log Output Level= 0
Friction Slope Method= 1
Unsteady Friction Slope Method= 2
Unsteady Bridges Friction Slope Method= 1
Parabolic Critical Depth
Global Vel Dist=  1 , 1 , 1
Global Log Level= 0
CheckData=True
Encroach Param= -1, 0, 0, 0
BEGIN DESCRIPTION:
Multiple Run
END DESCRIPTION:

--- UNT 088 IN DRY CR WATERSHED.f01 (steady flow) ---

Flow Title=Multiple
Number of Profiles=7
Profile Names=10-year,25-year,50-year,1pct_min,100-year,1pct_plu,500-year
River Rch & RM= UNT 088 IN DRY C,Reach-1,1000
     352     460     546     323     645    1287     900
Boundary for River Rch & Prof#=UNT 088 IN DRY C,Reach-1,1
Up Type=0
Dn Type=3
Dn Slope=0.005
Boundary for River Rch & Prof#=UNT 088 IN DRY C,Reach-1,2
Up Type=0
Dn Type=3
Dn Slope=0.005
Boundary for River Rch & Prof#=UNT 088 IN DRY C,Reach-1,3
Up Type=0
Dn Type=3
Dn Slope=0.005
Boundary for River Rch & Prof#=UNT 088 IN DRY C,Reach-1,4
Up Type=0
Dn Type=3
Dn Slope=0.005
Boundary for River Rch & Prof#=UNT 088 IN DRY C,Reach-1,5
Up Type=0
Dn Type=3
Dn Slope=0.005
Boundary for River Rch & Prof#=UNT 088 IN DRY C,Reach-1,6
Up Type=0
Dn Type=3
Dn Slope=0.005
Boundary for River Rch & Prof#=UNT 088 IN DRY C,Reach-1,7
Up Type=0
Dn Type=3
Dn Slope=0.005

--- UNT 088 IN DRY CR WATERSHED.g01 (geometry) ---

Geom Title=Existing Conditions

River Reach=UNT 088 IN DRY C,Reach-1
Reach XY= 30
      2883856.14      6993702.28      2883869.16      6993666.69
      2883923.85      6993664.08      2884068.81      6993581.62
      2884103.53      6993598.98      2884135.70      6993599.08
      2884184.42      6993585.49      2884205.25      6993547.29
      2884267.75      6993555.97      2884323.31      6993552.50
      2884328.52      6993509.10      2884377.13      6993472.64
      2884444.84      6993437.92      2884488.76      6993437.92
      2884503.14      6993426.59      2884528.06      6993414.99
      2884555.01      6993390.47      2884588.03      6993341.75
      2884599.45      6993330.46      2884606.07      6993327.65
      2884625.16      6993327.52      2884633.18      6993325.35
      2884639.74      6993320.95      2884656.67      6993301.59
      2884671.20      6993293.49      2884687.76      6993295.69
      2884710.02      6993311.36      2884719.82      6993315.42
      2884735.96      6993315.74      2884745.59      6993310.71

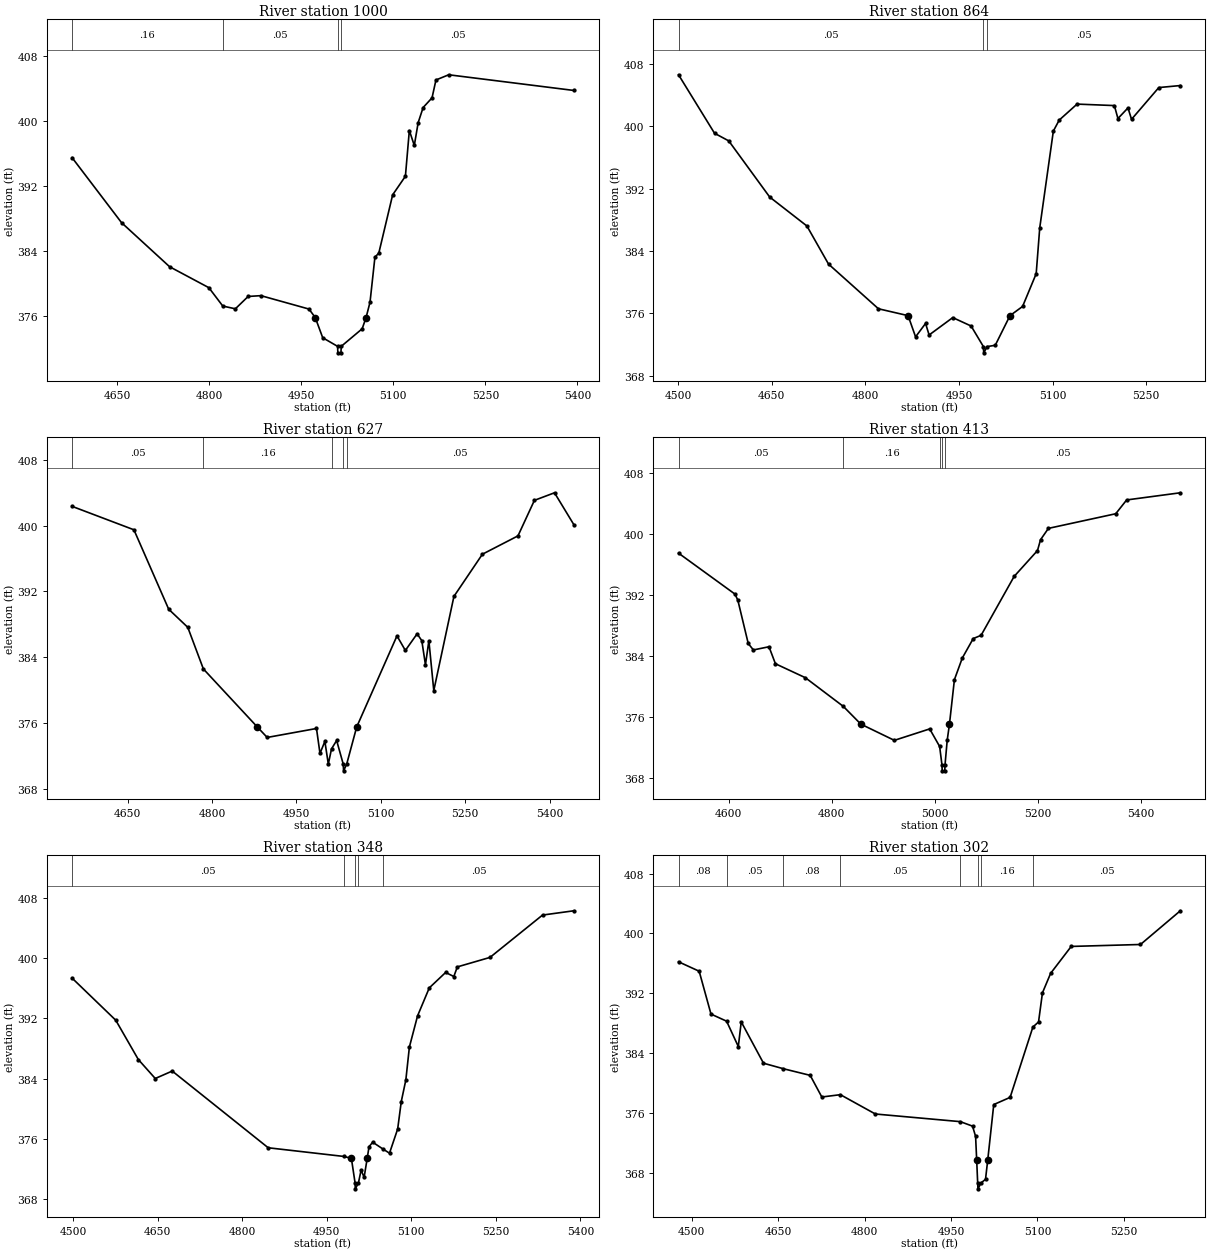
Type RM Length L Ch R = 1,1000,136,136,136
BEGIN DESCRIPTION:
UNT 088 IN DRY CR WATERSHED 2.0
END DESCRIPTION:
XS GIS Cut Line= 3
      2884189.47      6993994.18      2883923.85      6993664.08
      2883613.14      6993421.32
#Sta/Elev= 30
  4576.3  395.49  4656.9  387.49  4735.3  382.06  4799.3  379.48  4822.0  377.22
  4842.5  376.88  4863.3  378.40  4884.1  378.50  4962.5  376.85  4972.7  375.81
  4984.9  373.32  5009.1  372.26  5009.6  371.46  5014.6  371.46  5015.1  372.26
  5049.2  374.42  5055.6  375.81  5062.0  377.69  5070.0  383.24  5076.3  383.73
  5098.9  390.91  5119.7  393.20  5126.1  398.83  5134.2  396.99  5140.5  399.80
  5148.6  401.66  5163.1  402.85  5169.5  405.05  5190.3  405.69  5394.3  403.76
#Mann=4,-1,0
  4576.3    0.16       0  4822.0    0.05       0  5009.1    0.03       0
  5015.1    0.05       0
Bank Sta=4972.7,5055.6
Exp/Cntr=0.3,0.1

Type RM Length L Ch R = 1,864,237,237,237
BEGIN DESCRIPTION:
Mapping XS a963888c
END DESCRIPTION:
XS GIS Cut Line= 3
      2884291.94      6994025.49      2884061.02      6993607.06
      2883774.58      6993450.82
#Sta/Elev= 30
  4500.6  406.61  4558.3  399.11  4581.1  398.13  4646.7  390.93  4706.3  387.22
  4741.0  382.33  4821.0  376.60  4868.5  375.72  4880.5  373.00  4896.5  374.72
  4902.2  373.24  4940.1  375.47  4969.5  374.39  4989.2  371.75  4989.7  370.95
  4995.2  371.75  5008.2  371.92  5031.8  375.72  5052.0  376.90  5073.8  381.10
  5079.5  386.99  5101.3  399.39  5110.7  400.80  5139.3  402.85  5199.1  402.66
  5204.8  401.00  5220.9  402.36  5226.6  400.90  5270.3  404.97  5304.8  405.23
#Mann=3,-1,0
  4500.6    0.05       0  4989.2    0.03       0  4995.2    0.05       0
Bank Sta=4868.5,5031.8
Exp/Cntr=0.3,0.1

Type RM Length L Ch R = 1,627,214,214,214
BEGIN DESCRIPTION:
Mapping XS 03284384
END DESCRIPTION:
XS GIS Cut Line= 3
      2884378.73      6993971.66      2884281.51      6993577.55
      2883883.63      6993299.03
#Sta/Elev= 30
  4551.3  402.34  4661.2  399.49  4723.0  389.83  4756.9  387.63  4784.6  382.57
  4880.5  375.51  4898.0  374.24  4985.6  375.33  4991.8  372.30  5000.5  373.76
  5006.6  371.01  5012.3  372.85  5021.4  373.87  5033.2  370.98  5033.7  370.18
  5039.2  370.98  5057.0  375.51  5128.6  386.59  5143.5  384.82  5164.4  386.84
  5172.7  386.01  5179.2  383.08  5185.3  386.00  5194.0  379.94  5229.8  391.39
  5280.4  396.52  5343.6  398.75  5372.8  403.07  5408.5  403.99  5442.9  400.11
#Mann=5,-1,0
  4551.3    0.05       0  4784.6    0.16       0  5012.3    0.05       0
  5033.2    0.07       0  5039.2    0.05       0
Bank Sta=4880.5,5057
Exp/Cntr=0.3,0.1

Type RM Length L Ch R = 1,413,65,65,65
BEGIN DESCRIPTION:
Mapping XS 5884db64
END DESCRIPTION:
XS GIS Cut Line= 3
      2884474.22      6993949.10      2884409.98      6993461.23
      2884002.02      6993204.30
#Sta/Elev= 30
  4502.3  397.47  4611.8  392.10  4617.4  391.31  4637.6  385.62  4647.6  384.77
  4677.9  385.19  4690.4  382.96  4748.5  381.13  4822.3  377.36  4856.2  375.04
  4921.3  372.91  4989.9  374.41  5009.2  372.11  5013.7  369.71  5014.2  368.91
  5019.2  368.91  5019.7  369.71  5023.9  372.92  5028.3  375.04  5037.9  380.87
  5053.2  383.71  5074.4  386.26  5089.7  386.69  5153.9  394.42  5199.2  397.81
  5205.1  399.23  5220.4  400.72  5351.1  402.64  5372.3  404.45  5476.5  405.39
#Mann=5,-1,0
  4502.3    0.05       0  4822.3    0.16       0  5009.2    0.05       0
  5013.7    0.07       0  5019.7    0.05       0
Bank Sta=4856.2,5028.3
Exp/Cntr=0.3,0.1

Type RM Length L Ch R = 1,348,46,46,46
BEGIN DESCRIPTION:
Mapping XS dd0ee482
END DESCRIPTION:
XS GIS Cut Line= 4
      2884521.57      6993932.38      2884497.27      6993510.55
      2884452.13      6993408.12      2884171.25      6993189.66
#Sta/Elev= 30
  4498.1  397.37  4575.6  391.77  4615.7  386.54  4645.7  384.02  4675.8  385.01
  4846.1  374.81  4981.2  373.65  4993.7  373.39  5000.2  370.15  5000.7  369.35
  5006.2  370.15  5010.9  371.83  5016.3  370.89  5021.7  373.39  5025.0  374.95
  5031.5  375.55  5050.6  374.60  5061.3  374.09  5075.8  377.31  5082.2  380.96
  5090.3  383.83  5096.6  388.21  5111.1  392.35  5131.9  396.07  5160.9  398.12
  5175.4  397.58  5181.7  398.86  5239.6  400.12  5332.8  405.75  5388.4  406.32
#Mann=5,-1,0
  4498.1    0.05       0  4981.2    0.16       0  5000.2    0.07       0
  5006.2    0.16       0  5050.6    0.05       0
Bank Sta=4993.7,5021.7
Exp/Cntr=0.3,0.1

Type RM Length L Ch R = 1,302,275,275,275
BEGIN DESCRIPTION:
Mapping XS 6e975fcd
END DESCRIPTION:
XS GIS Cut Line= 4
      2884533.73      6993930.67      2884580.60      6993630.34
      2884500.74      6993406.38      2884259.69      6993182.68
#Sta/Elev= 30
  4477.3  396.22  4513.1  394.96  4533.6  389.24  4560.7  388.29  4581.0  384.91
  4586.1  388.20  4624.7  382.68  4659.4  381.94  4705.7  381.06  4725.9  378.17
  4758.1  378.48  4818.8  375.90  4966.2  374.88  4987.4  374.28  4992.7  372.91
  4994.6  369.72  4996.3  366.71  4996.8  365.91  5002.3  366.71  5009.9  367.18
  5013.7  369.72  5024.2  377.16  5052.6  378.12  5092.1  387.51  5101.9  388.19
  5108.7  392.08  5122.9  394.68  5158.6  398.27  5278.8  398.53  5347.9  403.03
#Mann=8,-1,0
  4477.3    0.08       0  4560.7    0.05       0  4659.4    0.08       0
  4758.1    0.05       0  4966.2    0.16       0  4996.3    0.07       0
  5002.3    0.16       0  5092.1    0.05       0
Bank Sta=4994.6,5013.7
Exp/Cntr=0.3,0.1

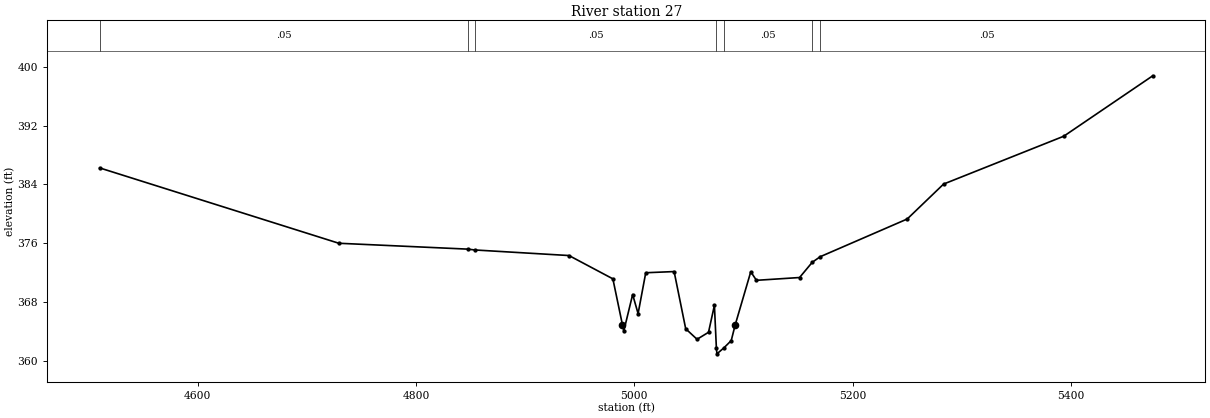
Type RM Length L Ch R = 1,27,0,0,0
BEGIN DESCRIPTION:
UNT 088 IN DRY CR WATERSHED 1.0
END DESCRIPTION:
XS GIS Cut Line= 3
      2884762.72      6993803.32      2884717.14      6993281.15
      2884294.87      6993155.94
#Sta/Elev= 30
  4510.3  386.25  4729.4  376.00  4847.7  375.20  4853.7  375.09  4940.2  374.33
  4980.4  371.16  4989.2  364.88  4990.4  364.06  4998.5  369.03  5003.5  366.43
  5010.5  371.99  5036.5  372.15  5047.1  364.37  5057.5  362.94  5068.0  363.89
  5073.4  367.56  5075.2  361.76  5075.7  360.96  5082.0  361.76  5088.8  362.76
  5092.4  364.88  5106.7  372.12  5111.9  370.96  5151.4  371.34  5163.0  373.41
  5170.3  374.17  5250.0  379.30  5283.3  384.05  5393.4  390.56  5474.9  398.78
#Mann=7,-1,0
  4510.3    0.05       0  4847.7    0.08       0  4853.7    0.05       0
  5075.2    0.03       0  5082.0    0.05       0  5163.0    0.16       0
  5170.3    0.05       0
Bank Sta=4989.2,5092.4
Exp/Cntr=0.3,0.1

Chan Stop Cuts=-1