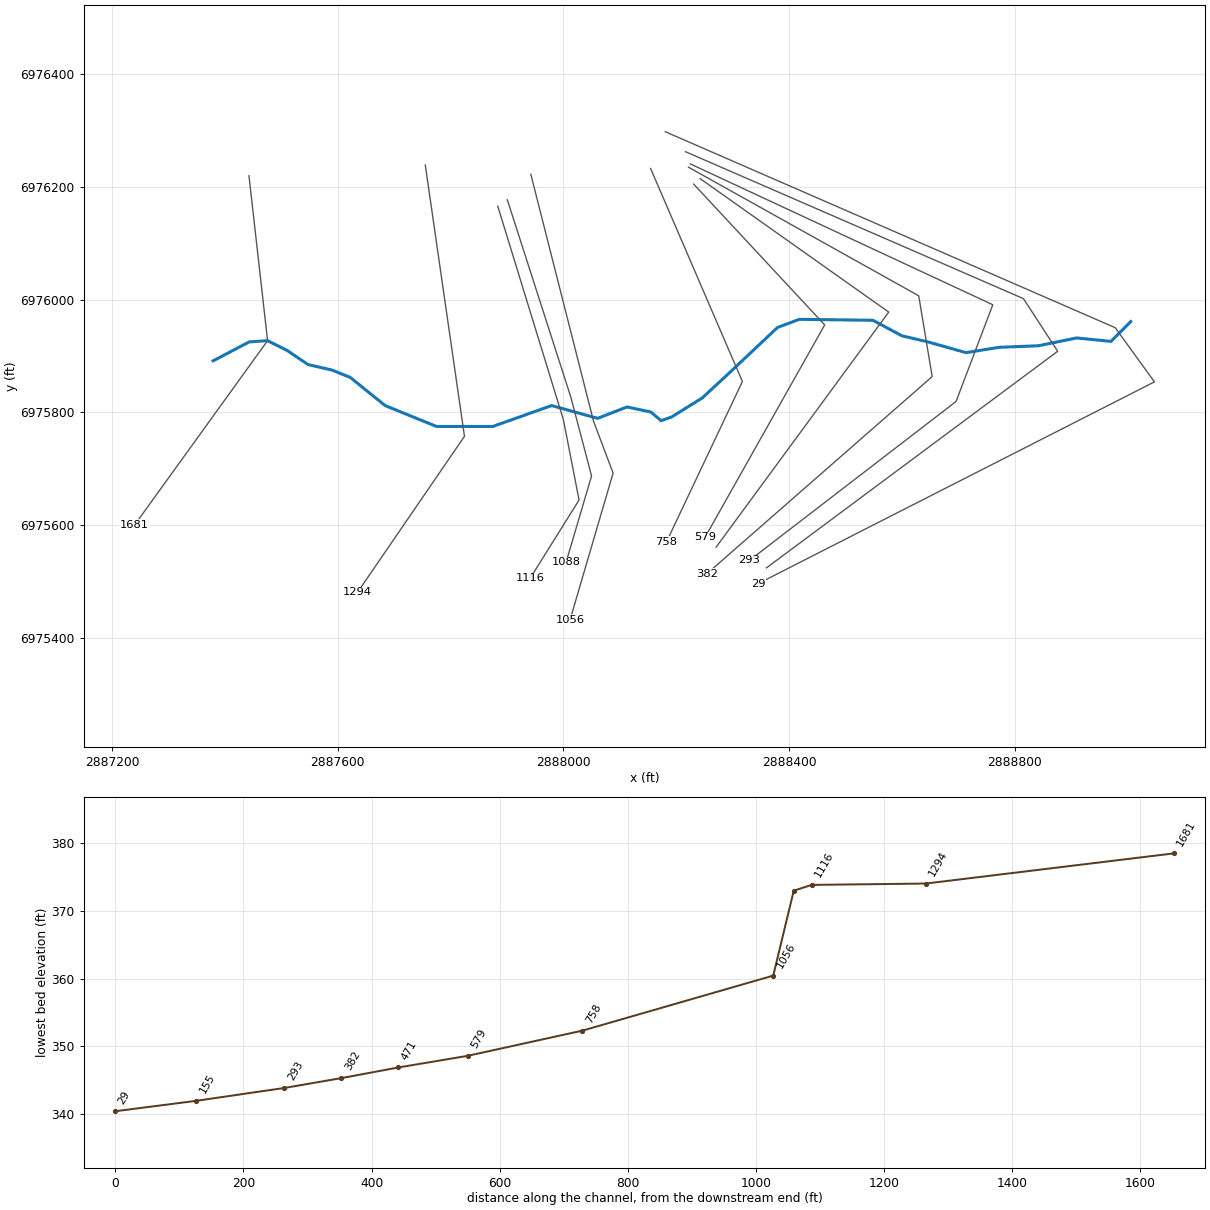
--- UNT 089 IN DRY CR WATERSHED.prj (project) ---

Proj Title=UNT 089 IN DRY CR WATERSHED Base Level Engineering
Current Plan=p01
Default Exp/Contr=0.3,0.1
English Units
Geom File=g01
Flow File=f01
Plan File=p01
BEGIN DESCRIPTION:
UNT 089 IN DRY CR WATERSHED
END DESCRIPTION:

--- UNT 089 IN DRY CR WATERSHED.p01 (plan) ---

Plan Title=Multiple Run
Short Identifier=Multiple
Geom File=g01
Flow File=f01
Subcritical Flow
K Sum by GR= 0
Std Step Tol= 0.01
Critical Tol= 0.01
Num of Std Step Trials= 20
Max Error Tol= 0.3
Flow Tol Ratio= 0.001
Split Flow NTrial= 30
Split Flow Tol= 0.02
Split Flow Ratio= 0.02
Log Output Level= 0
Friction Slope Method= 1
Unsteady Friction Slope Method= 2
Unsteady Bridges Friction Slope Method= 1
Parabolic Critical Depth
Global Vel Dist=  1 , 1 , 1
Global Log Level= 0
CheckData=True
Encroach Param= -1, 0, 0, 0
BEGIN DESCRIPTION:
Multiple Run
END DESCRIPTION:

--- UNT 089 IN DRY CR WATERSHED.f01 (steady flow) ---

Flow Title=Multiple
Number of Profiles=7
Profile Names=10-year,25-year,50-year,1pct_min,100-year,1pct_plu,500-year
River Rch & RM= UNT 089 IN DRY C,Reach-1,1681
      68      79      86      48      95     190     114
Boundary for River Rch & Prof#=UNT 089 IN DRY C,Reach-1,1
Up Type=0
Dn Type=3
Dn Slope=0.005
Boundary for River Rch & Prof#=UNT 089 IN DRY C,Reach-1,2
Up Type=0
Dn Type=3
Dn Slope=0.005
Boundary for River Rch & Prof#=UNT 089 IN DRY C,Reach-1,3
Up Type=0
Dn Type=3
Dn Slope=0.005
Boundary for River Rch & Prof#=UNT 089 IN DRY C,Reach-1,4
Up Type=0
Dn Type=3
Dn Slope=0.005
Boundary for River Rch & Prof#=UNT 089 IN DRY C,Reach-1,5
Up Type=0
Dn Type=3
Dn Slope=0.005
Boundary for River Rch & Prof#=UNT 089 IN DRY C,Reach-1,6
Up Type=0
Dn Type=3
Dn Slope=0.005
Boundary for River Rch & Prof#=UNT 089 IN DRY C,Reach-1,7
Up Type=0
Dn Type=3
Dn Slope=0.005

--- UNT 089 IN DRY CR WATERSHED.g01 (geometry) ---

Geom Title=Existing Conditions

River Reach=UNT 089 IN DRY C,Reach-1
Reach XY= 29
      2887379.11      6975891.23      2887443.13      6975924.87
      2887475.68      6975927.04      2887510.40      6975909.68
      2887547.30      6975884.72      2887589.61      6975875.00
      2887622.17      6975861.94      2887684.01      6975812.02
      2887775.00      6975775.00      2887875.00      6975775.00
      2887979.15      6975812.02      2888060.65      6975789.35
      2888112.75      6975809.55      2888155.11      6975800.52
      2888173.16      6975785.24      2888191.70      6975791.70
      2888246.08      6975825.52      2888286.99      6975863.31
      2888379.49      6975950.42      2888418.38      6975964.87
      2888548.59      6975963.14      2888599.98      6975935.64
      2888645.81      6975924.94      2888713.52      6975905.84
      2888772.77      6975915.29      2888841.99      6975918.00
      2888909.70      6975931.88      2888970.59      6975925.71
      2889005.66      6975960.99

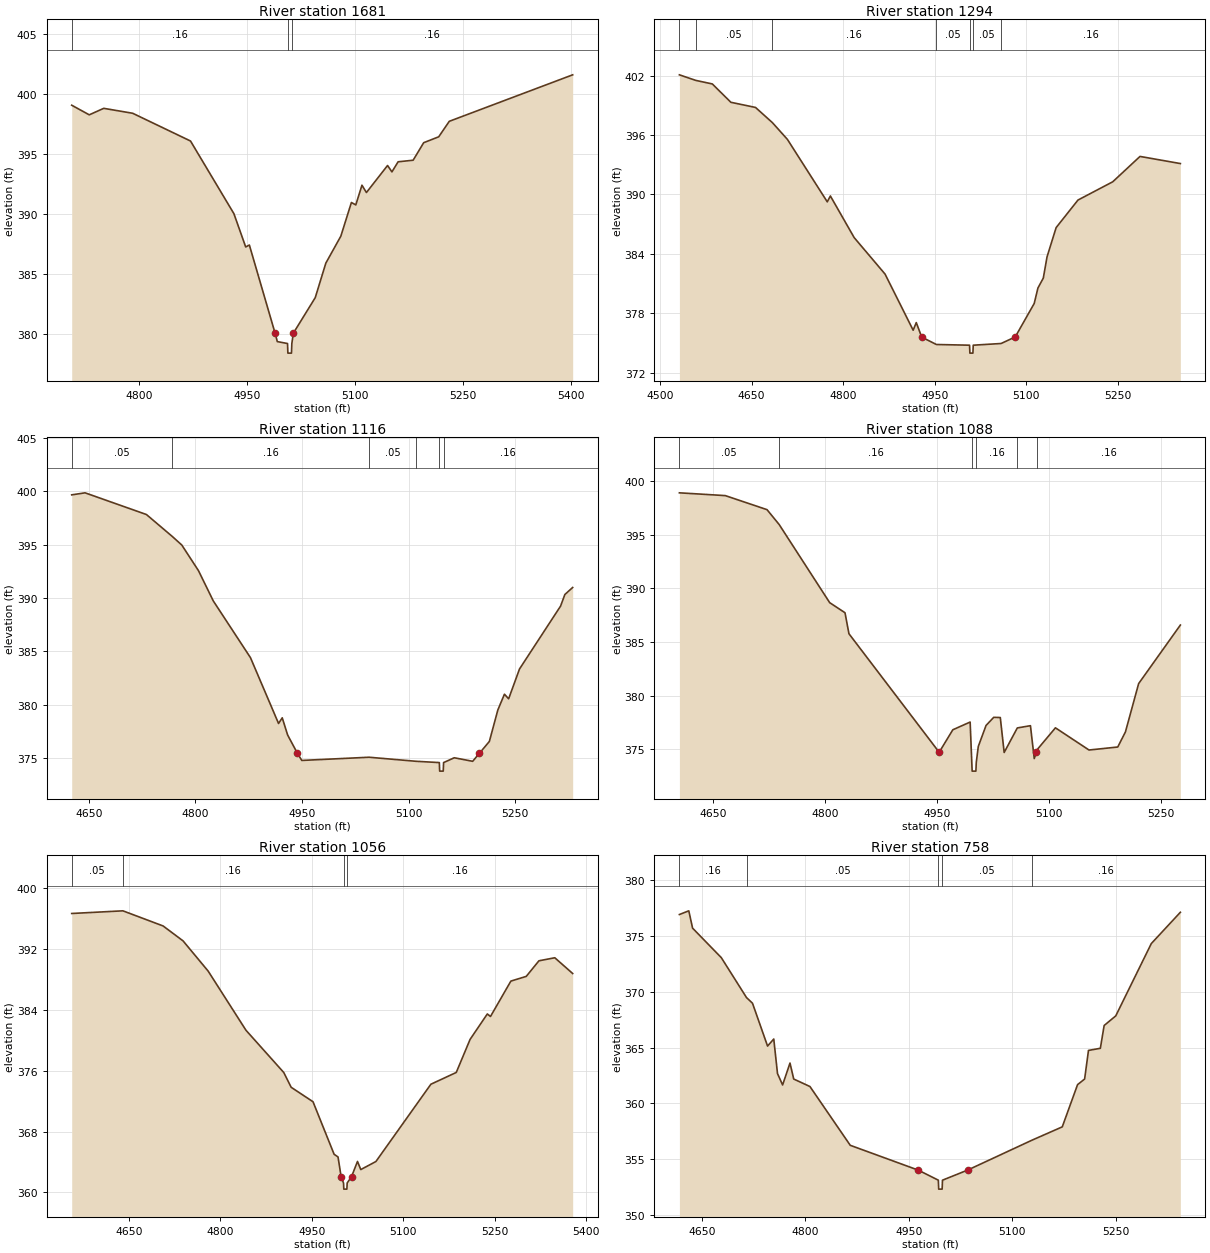
Type RM Length L Ch R = 1,1681,387,387,387
BEGIN DESCRIPTION:
UNT 089 IN DRY CR WATERSHED 2.0
END DESCRIPTION:
XS GIS Cut Line= 3
      2887442.69      6976219.29      2887475.68      6975927.04
      2887239.88      6975600.23
#Sta/Elev= 30
  4705.9  399.08  4730.3  398.28  4750.5  398.82  4790.7  398.41  4871.2  396.10
  4931.6  390.05  4948.0  387.28  4953.1  387.44  4988.9  380.10  4992.0  379.40
  5006.2  379.24  5006.7  378.44  5011.7  378.44  5012.2  379.24  5014.3  380.10
  5044.8  383.06  5059.5  385.93  5080.4  388.18  5095.1  390.98  5101.2  390.78
  5109.8  392.42  5116.0  391.81  5145.4  394.06  5151.5  393.53  5160.1  394.37
  5181.0  394.50  5195.7  395.96  5216.6  396.45  5231.3  397.74  5403.0  401.61
#Mann=3,-1,0
  4705.9    0.16       0  5006.2    0.07       0  5012.2    0.16       0
Bank Sta=4988.9,5014.3
Exp/Cntr=0.3,0.1

Type RM Length L Ch R = 1,1294,178,178,178
BEGIN DESCRIPTION:
Mapping XS c5bb39c0
END DESCRIPTION:
XS GIS Cut Line= 3
      2887755.19      6976238.39      2887824.64      6975757.46
      2887635.40      6975481.42
#Sta/Elev= 30
  4531.8  402.07  4558.5  401.51  4585.7  401.15  4616.1  399.30  4656.5  398.78
  4684.1  397.25  4708.7  395.56  4774.0  389.26  4779.1  389.85  4818.1  385.65
  4868.7  381.97  4914.7  376.31  4919.8  377.08  4928.7  375.62  4952.7  374.87
  5007.1  374.80  5007.6  374.00  5012.6  374.00  5013.1  374.80  5058.7  374.97
  5081.9  375.63  5113.0  379.01  5119.1  380.57  5127.9  381.57  5134.0  383.71
  5148.9  386.66  5184.7  389.44  5241.6  391.28  5286.3  393.84  5352.4  393.12
#Mann=7,-1,0
  4531.8    0.16       0  4558.5    0.05       0  4684.1    0.16       0
  4952.7    0.05       0  5007.1   0.033       0  5013.1    0.05       0
  5058.7    0.16       0
Bank Sta=4928.7,5081.9
Exp/Cntr=0.3,0.1

Type RM Length L Ch R = 1,1116,28,28,28
BEGIN DESCRIPTION:
Mapping XS a48b30b1
END DESCRIPTION:
XS GIS Cut Line= 4
      2887883.67      6976165.43      2887999.99      6975786.97
      2888027.77      6975644.61      2887940.94      6975505.69
#Sta/Elev= 30
  4626.1  399.66  4644.9  399.85  4731.2  397.82  4767.7  395.76  4781.0  394.96
  4804.4  392.57  4825.3  389.73  4877.6  384.42  4917.1  378.26  4922.3  378.79
  4929.9  377.18  4943.7  375.46  4949.8  374.80  5044.4  375.10  5110.7  374.72
  5143.3  374.60  5143.8  373.80  5148.8  373.80  5149.3  374.60  5164.3  375.05
  5190.2  374.72  5199.6  375.46  5213.7  376.58  5225.6  379.52  5234.9  381.00
  5240.8  380.57  5256.1  383.36  5313.9  389.25  5319.9  390.33  5330.9  390.99
#Mann=6,-1,0
  4626.1    0.05       0  4767.7    0.16       0  5044.4    0.05       0
  5110.7    0.16       0  5143.3    0.07       0  5149.3    0.16       0
Bank Sta=4943.7,5199.6
Exp/Cntr=0.3,0.1

Type RM Length L Ch R = 1,1088,32,32,32
BEGIN DESCRIPTION:
Mapping XS 25ffbd8b
END DESCRIPTION:
XS GIS Cut Line= 4
      2887900.59      6976176.76      2888013.44      6975826.04
      2888049.90      6975687.15      2888004.77      6975534.40
#Sta/Elev= 30
  4605.3  398.92  4666.8  398.66  4722.7  397.35  4739.0  395.96  4806.7  388.67
  4827.2  387.73  4832.5  385.77  4953.4  374.71  4971.7  376.81  4994.9  377.53
  4997.1  373.75  4997.6  372.95  5002.6  372.95  5003.1  373.75  5005.8  375.25
  5016.2  377.21  5026.5  377.97  5035.3  377.95  5040.5  374.69  5058.1  376.98
  5075.7  377.19  5080.8  374.12  5083.7  374.71  5085.1  374.99  5109.2  376.99
  5154.2  374.92  5192.7  375.20  5203.0  376.61  5220.7  381.12  5276.6  386.58
#Mann=6,-1,0
  4605.3    0.05       0  4739.0    0.16       0  4997.1    0.07       0
  5003.1    0.16       0  5058.1    0.05       0  5085.1    0.16       0
Bank Sta=4953.4,5083.7
Exp/Cntr=0.3,0.1

Type RM Length L Ch R = 1,1056,298,298,298
BEGIN DESCRIPTION:
Mapping XS a4f2f55d
END DESCRIPTION:
XS GIS Cut Line= 4
      2887942.26      6976221.86      2888053.37      6975784.37
      2888088.10      6975692.35      2888011.71      6975431.95
#Sta/Elev= 30
  4556.4  396.68  4640.3  397.03  4706.2  395.04  4738.9  393.08  4780.1  389.10
  4842.0  381.33  4904.0  375.77  4916.1  373.83  4951.9  371.93  4986.5  365.02
  4992.9  364.67  4998.0  362.07  5001.9  361.24  5002.4  360.44  5007.4  360.44
  5007.9  361.24  5015.1  362.09  5024.8  364.08  5030.2  363.01  5055.0  364.07
  5145.1  374.23  5186.7  375.78  5209.4  380.13  5237.6  383.47  5242.8  383.14
  5276.2  387.79  5301.4  388.41  5322.2  390.46  5348.2  390.86  5377.5  388.79
#Mann=4,-1,0
  4556.4    0.05       0  4640.3    0.16       0  5001.9    0.07       0
  5007.9    0.16       0
Bank Sta=4998,5015.1
Exp/Cntr=0.3,0.1

Type RM Length L Ch R = 1,758,179,179,179
BEGIN DESCRIPTION:
Mapping XS 780552c8
END DESCRIPTION:
XS GIS Cut Line= 3
      2888154.51      6976232.26      2888317.26      6975854.68
      2888182.71      6975570.38
#Sta/Elev= 30
  4617.6  376.90  4631.2  377.23  4636.7  375.68  4678.3  373.04  4714.8  369.47
  4723.5  368.96  4745.3  365.13  4754.3  365.76  4759.7  362.67  4767.1  361.65
  4777.8  363.61  4783.2  362.18  4806.7  361.51  4865.1  356.25  4963.6  354.03
  4992.7  353.13  4993.2  352.33  4998.2  352.33  4998.7  353.13  5035.0  354.03
  5128.4  356.71  5172.2  357.90  5194.4  361.68  5204.6  362.18  5210.2  364.74
  5227.4  364.93  5232.9  366.97  5249.7  367.83  5301.2  374.30  5343.3  377.10
#Mann=5,-1,0
  4617.6    0.16       0  4714.8    0.05       0  4992.7    0.03       0
  4998.7    0.05       0  5128.4    0.16       0
Bank Sta=4963.6,5035
Exp/Cntr=0.3,0.1

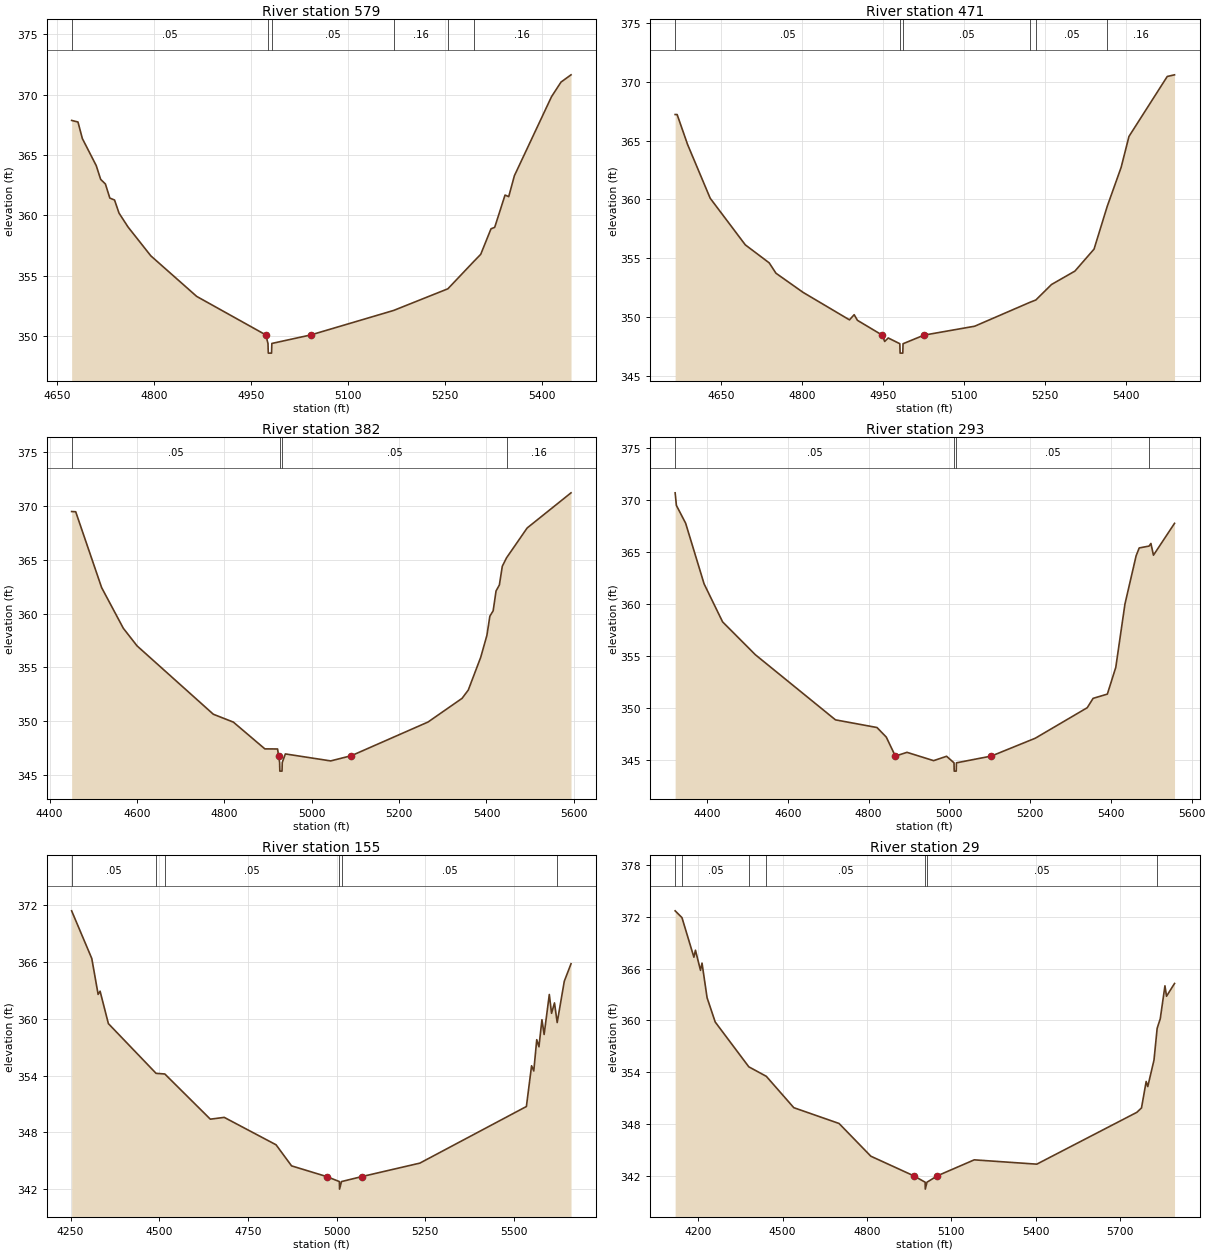
Type RM Length L Ch R = 1,579,108,108,108
BEGIN DESCRIPTION:
Mapping XS 2769c3f2
END DESCRIPTION:
XS GIS Cut Line= 3
      2888230.90      6976204.52      2888463.10      6975954.97
      2888251.18      6975578.71
#Sta/Elev= 30
  4672.0  367.86  4681.8  367.73  4688.6  366.36  4710.1  364.12  4716.9  362.99
  4724.3  362.60  4731.1  361.44  4738.4  361.28  4745.3  360.20  4759.4  359.04
  4794.6  356.66  4865.5  353.31  4972.3  350.13  4975.8  349.42  4976.3  348.62
  4981.3  348.62  4981.8  349.42  5042.5  350.13  5170.3  352.15  5254.2  353.94
  5294.1  356.19  5305.0  356.79  5320.9  358.90  5326.6  359.02  5342.6  361.69
  5348.3  361.56  5357.1  363.29  5414.5  369.82  5429.2  371.03  5444.7  371.63
#Mann=6,-1,0
  4672.0    0.05       0  4975.8    0.03       0  4981.8    0.05       0
  5170.3    0.16       0  5254.2    0.05       0  5294.1    0.16       0
Bank Sta=4972.3,5042.5
Exp/Cntr=0.3,0.1

Type RM Length L Ch R = 1,471,89,89,89
BEGIN DESCRIPTION:
Mapping XS d16d5a09
END DESCRIPTION:
XS GIS Cut Line= 3
      2888242.36      6976214.26      2888576.60      6975977.68
      2888270.64      6975561.05
#Sta/Elev= 30
  4564.2  367.21  4567.9  367.21  4587.3  364.66  4629.2  360.09  4694.4  356.12
  4738.7  354.59  4751.2  353.71  4801.5  352.08  4887.6  349.74  4896.3  350.18
  4902.4  349.70  4948.4  348.44  4952.9  347.90  4959.5  348.20  4981.0  347.71
  4981.5  346.91  4986.5  346.91  4987.0  347.71  5025.8  348.44  5119.9  349.20
  5222.7  351.24  5233.3  351.43  5262.4  352.75  5305.8  353.89  5341.3  355.76
  5365.6  359.38  5391.5  362.71  5406.1  365.35  5477.1  370.45  5490.6  370.59
#Mann=6,-1,0
  4564.2    0.05       0  4981.0    0.03       0  4987.0    0.05       0
  5222.7    0.16       0  5233.3    0.05       0  5365.6    0.16       0
Bank Sta=4948.4,5025.8
Exp/Cntr=0.3,0.1

Type RM Length L Ch R = 1,382,89,89,89
BEGIN DESCRIPTION:
Mapping XS a4799c53
END DESCRIPTION:
XS GIS Cut Line= 4
      2888221.76      6976234.46      2888629.76      6976006.59
      2888653.63      6975863.36      2888254.34      6975513.98
#Sta/Elev= 30
  4450.5  369.49  4459.8  369.47  4519.2  362.41  4568.8  358.63  4600.3  356.99
  4774.9  350.63  4820.7  349.90  4892.8  347.41  4921.9  347.40  4924.2  346.78
  4926.6  346.14  4927.1  345.34  4932.1  345.34  4932.6  346.14  4939.7  346.94
  5043.5  346.29  5091.1  346.78  5266.4  349.91  5344.2  352.11  5358.4  352.88
  5386.9  355.93  5401.1  357.98  5407.8  359.75  5415.4  360.26  5422.0  362.10
  5429.6  362.66  5436.3  364.40  5446.1  365.19  5493.2  367.96  5593.6  371.23
#Mann=4,-1,0
  4450.5    0.05       0  4926.6    0.03       0  4932.6    0.05       0
  5446.1    0.16       0
Bank Sta=4924.2,5091.1
Exp/Cntr=0.3,0.1

Type RM Length L Ch R = 1,293,138,138,138
BEGIN DESCRIPTION:
Mapping XS eda33bd7
END DESCRIPTION:
XS GIS Cut Line= 4
      2888225.01      6976240.28      2888761.07      6975990.70
      2888695.96      6975819.26      2888329.60      6975537.45
#Sta/Elev= 30
  4320.7  370.70  4323.8  369.49  4346.7  367.77  4392.4  361.93  4438.2  358.27
  4519.2  355.11  4717.8  348.83  4820.7  348.09  4843.6  347.17  4866.1  345.34
  4894.9  345.70  4960.9  344.90  4993.0  345.32  5011.4  344.69  5011.9  343.89
  5016.9  343.89  5017.4  344.69  5103.8  345.34  5212.7  347.06  5341.4  350.00
  5355.9  350.90  5391.2  351.31  5412.1  353.89  5434.8  359.99  5462.5  364.64
  5470.1  365.39  5494.5  365.57  5499.1  365.82  5505.4  364.69  5557.6  367.76
#Mann=4,-1,0
  4320.7    0.05       0  5011.4    0.03       0  5017.4    0.05       0
  5494.5    0.16       0
Bank Sta=4866.1,5103.8
Exp/Cntr=0.3,0.1

Type RM Length L Ch R = 1,155,126,126,126
BEGIN DESCRIPTION:
Mapping XS f0e6b568
END DESCRIPTION:
XS GIS Cut Line= 4
      2888216.40      6976261.95      2888815.32      6976001.55
      2888876.08      6975908.24      2888359.83      6975524.30
#Sta/Elev= 30
  4253.2  371.43  4310.0  366.39  4327.9  362.59  4333.4  362.93  4356.8  359.50
  4491.2  354.24  4515.9  354.17  4644.2  349.39  4683.4  349.58  4829.5  346.68
  4873.2  344.45  4972.1  343.32  5008.0  342.79  5008.5  341.99  5014.0  342.79
  5071.7  343.32  5234.8  344.74  5535.2  350.73  5549.8  355.04  5556.0  354.49
  5564.4  357.80  5570.6  357.05  5579.0  359.91  5585.2  358.35  5599.8  362.58
  5606.1  360.59  5614.4  361.69  5622.0  359.61  5642.1  363.99  5661.0  365.83
#Mann=6,-1,0
  4253.2    0.05       0  4491.2    0.16       0  4515.9    0.05       0
  5008.0    0.03       0  5014.0    0.05       0  5622.0    0.16       0
Bank Sta=4972.1,5071.7
Exp/Cntr=0.3,0.1

Type RM Length L Ch R = 1,29,0,0,0
BEGIN DESCRIPTION:
UNT 089 IN DRY CR WATERSHED 1.0
END DESCRIPTION:
XS GIS Cut Line= 4
      2888180.52      6976297.40      2888978.08      6975950.00
      2889047.52      6975853.99      2888345.48      6975496.61
#Sta/Elev= 30
  4118.1  372.68  4142.4  371.89  4184.8  367.31  4190.3  368.12  4208.3  365.79
  4213.7  366.63  4231.7  362.62  4260.6  359.81  4380.1  354.62  4442.4  353.52
  4540.1  349.89  4701.1  348.06  4814.2  344.27  4966.8  342.00  5007.3  341.26
  5007.8  340.46  5013.8  341.26  5050.6  342.00  5181.9  343.85  5404.3  343.35
  5760.2  349.35  5776.8  349.86  5793.4  352.92  5799.1  352.33  5821.3  355.41
  5832.5  359.08  5843.5  360.18  5860.2  364.00  5865.8  362.79  5894.3  364.27
#Mann=7,-1,0
  4118.1    0.16       0  4142.4    0.05       0  4380.1    0.16       0
  4442.4    0.05       0  5007.3    0.03       0  5013.8    0.05       0
  5832.5    0.16       0
Bank Sta=4966.8,5050.6
Exp/Cntr=0.3,0.1

Chan Stop Cuts=-1