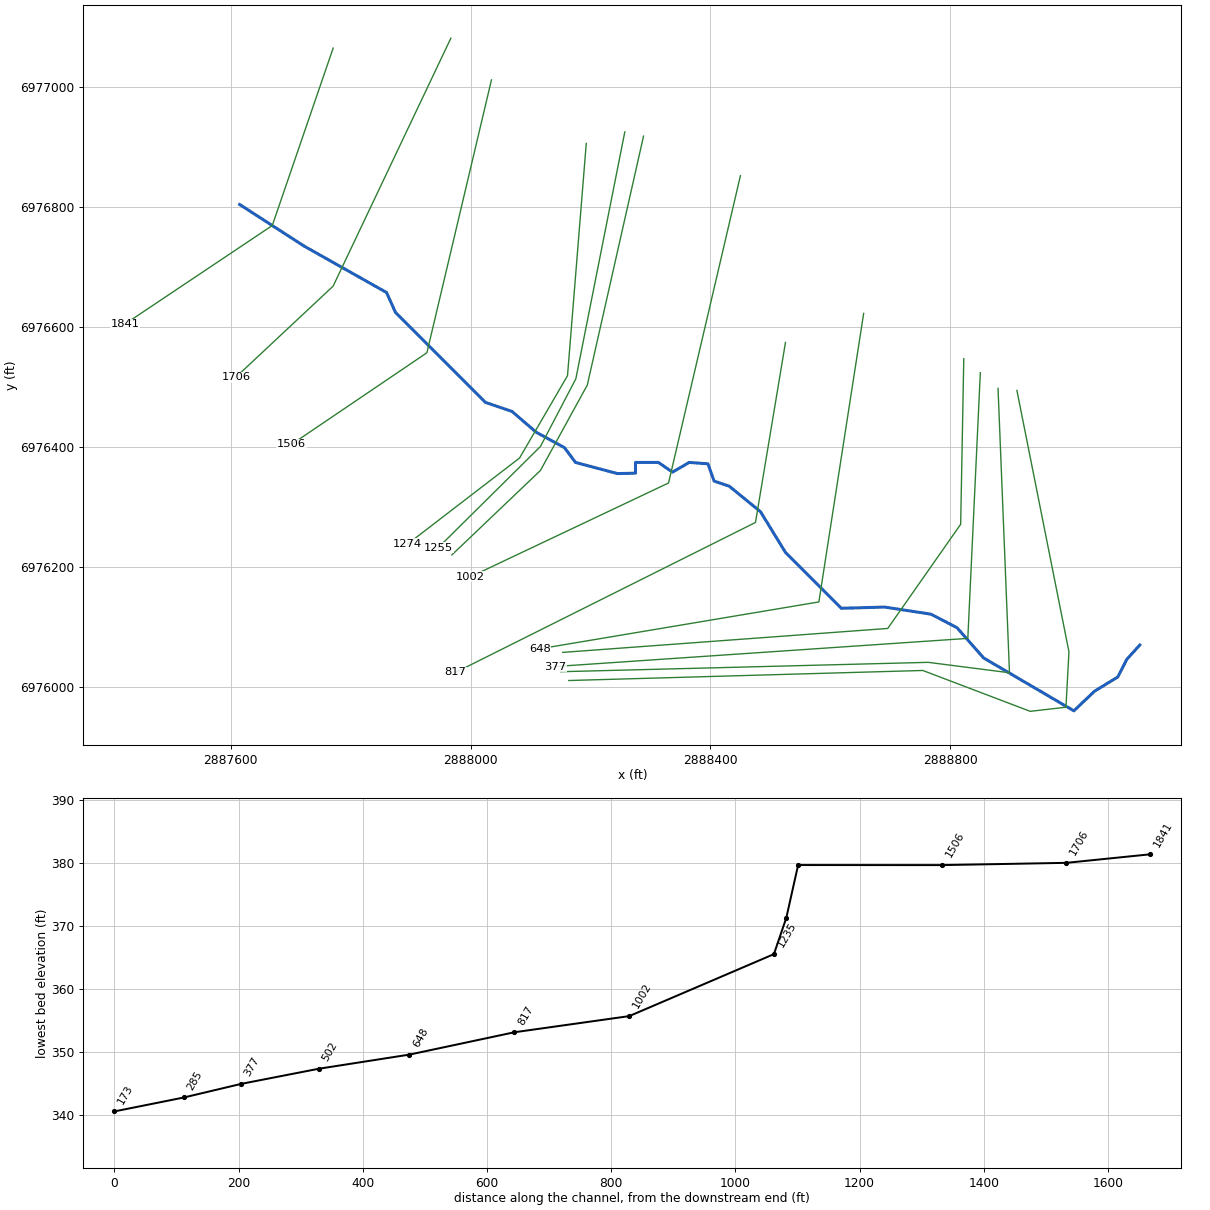
--- UNT 090 IN DRY CR WATERSHED.prj (project) ---

Proj Title=UNT 090 IN DRY CR WATERSHED Base Level Engineering
Current Plan=p01
Default Exp/Contr=0.3,0.1
English Units
Geom File=g01
Flow File=f01
Plan File=p01
BEGIN DESCRIPTION:
UNT 090 IN DRY CR WATERSHED
END DESCRIPTION:

--- UNT 090 IN DRY CR WATERSHED.p01 (plan) ---

Plan Title=Multiple Run
Short Identifier=Multiple
Geom File=g01
Flow File=f01
Subcritical Flow
K Sum by GR= 0
Std Step Tol= 0.01
Critical Tol= 0.01
Num of Std Step Trials= 20
Max Error Tol= 0.3
Flow Tol Ratio= 0.001
Split Flow NTrial= 30
Split Flow Tol= 0.02
Split Flow Ratio= 0.02
Log Output Level= 0
Friction Slope Method= 1
Unsteady Friction Slope Method= 2
Unsteady Bridges Friction Slope Method= 1
Parabolic Critical Depth
Global Vel Dist=  1 , 1 , 1
Global Log Level= 0
CheckData=True
Encroach Param= -1, 0, 0, 0
BEGIN DESCRIPTION:
Multiple Run
END DESCRIPTION:

--- UNT 090 IN DRY CR WATERSHED.f01 (steady flow) ---

Flow Title=Multiple
Number of Profiles=7
Profile Names=10-year,25-year,50-year,1pct_min,100-year,1pct_plu,500-year
River Rch & RM= UNT 090 IN DRY C,Reach-1,1841
      85     101     112      63     125     250     155
Boundary for River Rch & Prof#=UNT 090 IN DRY C,Reach-1,1
Up Type=0
Dn Type=3
Dn Slope=0.005
Boundary for River Rch & Prof#=UNT 090 IN DRY C,Reach-1,2
Up Type=0
Dn Type=3
Dn Slope=0.005
Boundary for River Rch & Prof#=UNT 090 IN DRY C,Reach-1,3
Up Type=0
Dn Type=3
Dn Slope=0.005
Boundary for River Rch & Prof#=UNT 090 IN DRY C,Reach-1,4
Up Type=0
Dn Type=3
Dn Slope=0.005
Boundary for River Rch & Prof#=UNT 090 IN DRY C,Reach-1,5
Up Type=0
Dn Type=3
Dn Slope=0.005
Boundary for River Rch & Prof#=UNT 090 IN DRY C,Reach-1,6
Up Type=0
Dn Type=3
Dn Slope=0.005
Boundary for River Rch & Prof#=UNT 090 IN DRY C,Reach-1,7
Up Type=0
Dn Type=3
Dn Slope=0.005

--- UNT 090 IN DRY CR WATERSHED.g01 (geometry) ---

Geom Title=Existing Conditions

River Reach=UNT 090 IN DRY C,Reach-1
Reach XY= 30
      2887615.29      6976804.91      2887722.93      6976735.46
      2887860.09      6976658.21      2887875.00      6976625.00
      2888025.00      6976475.00      2888069.15      6976460.08
      2888109.43      6976425.36      2888156.65      6976399.66
      2888175.00      6976375.00      2888244.83      6976356.45
      2888275.04      6976357.10      2888275.00      6976375.00
      2888313.24      6976375.00      2888336.67      6976358.84
      2888364.45      6976375.00      2888395.70      6976372.73
      2888406.02      6976343.98      2888431.29      6976335.40
      2888483.38      6976292.87      2888525.00      6976225.00
      2888618.07      6976131.93      2888690.39      6976133.93
      2888767.47      6976122.13      2888810.87      6976099.56
      2888855.14      6976049.21      2889005.66      6975960.99
      2889040.13      6975993.72      2889078.82      6976017.37
      2889094.09      6976047.06      2889115.59      6976070.71

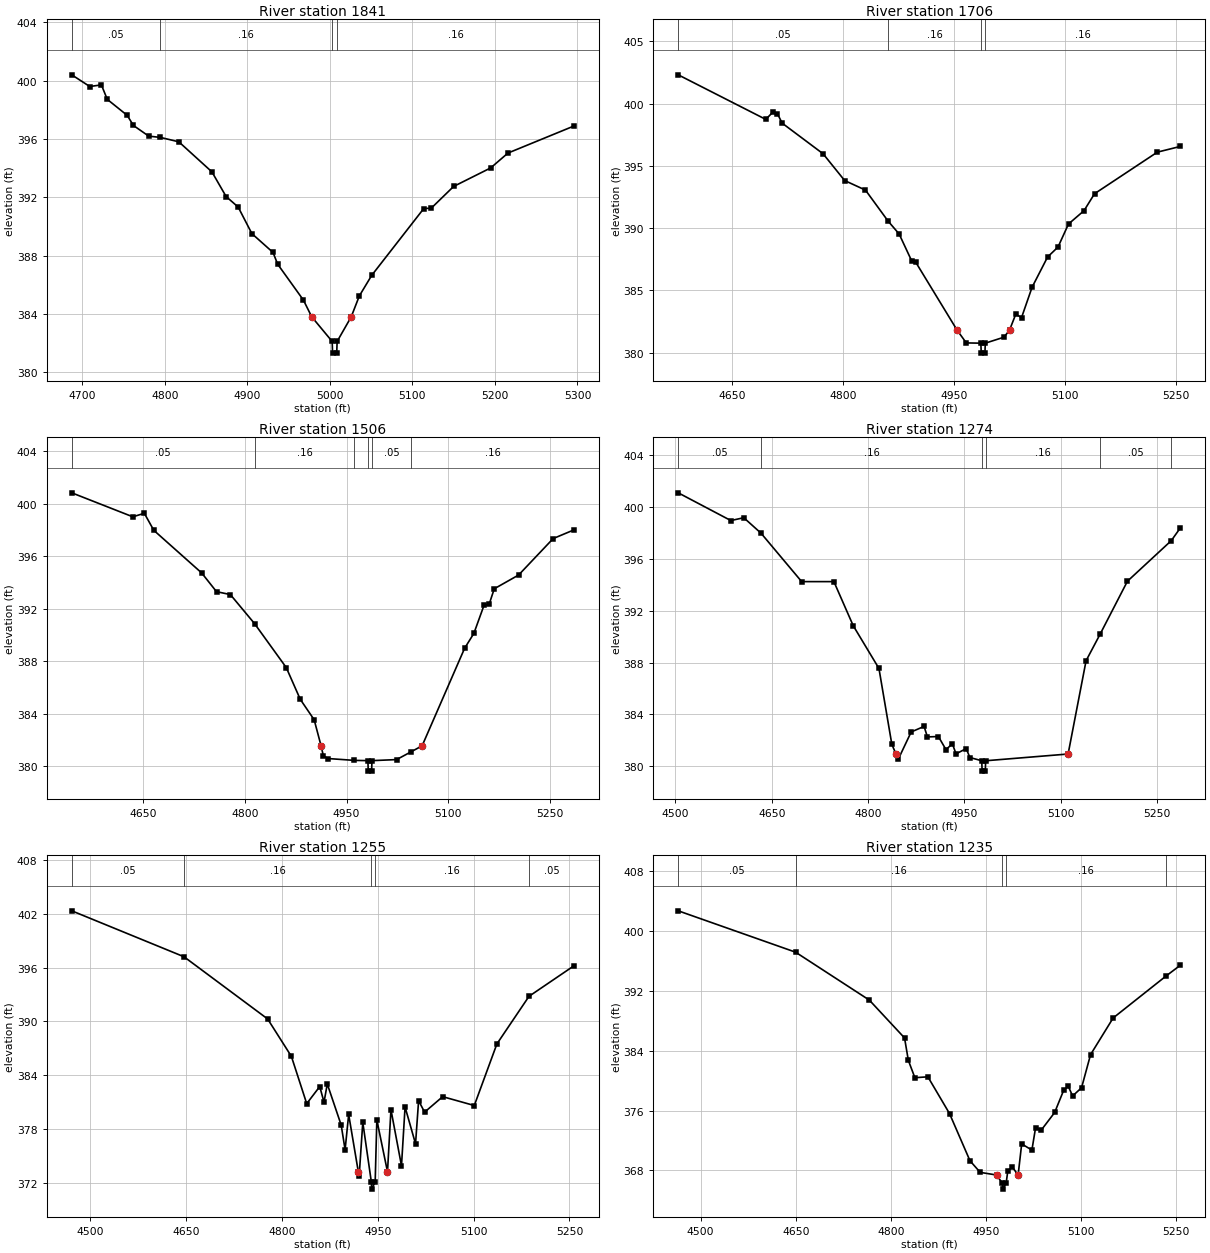
Type RM Length L Ch R = 1,1841,135,135,135
BEGIN DESCRIPTION:
UNT 090 IN DRY CR WATERSHED 4.0
END DESCRIPTION:
XS GIS Cut Line= 3
      2887771.08      6977065.65      2887669.60      6976769.87
      2887423.88      6976605.55
#Sta/Elev= 30
  4687.3  400.39  4709.1  399.59  4723.2  399.70  4730.3  398.71  4754.5  397.61
  4762.0  396.92  4780.5  396.19  4794.8  396.10  4817.0  395.80  4857.1  393.74
  4874.3  392.05  4888.9  391.33  4905.5  389.51  4931.1  388.22  4936.8  387.41
  4968.0  384.95  4978.0  383.81  5002.8  382.12  5003.3  381.32  5008.3  381.32
  5008.8  382.12  5025.9  383.81  5035.7  385.24  5050.7  386.65  5113.8  391.23
  5122.8  391.25  5149.9  392.74  5194.8  394.01  5215.8  395.03  5295.6  396.88
#Mann=4,-1,0
  4687.3    0.05       0  4794.8    0.16       0  5002.8    0.07       0
  5008.8    0.16       0
Bank Sta=4978,5025.9
Exp/Cntr=0.3,0.1

Type RM Length L Ch R = 1,1706,200,200,200
BEGIN DESCRIPTION:
Mapping XS 6ac1ec67
END DESCRIPTION:
XS GIS Cut Line= 3
      2887967.23      6977082.05      2887771.07      6976668.90
      2887608.97      6976517.15
#Sta/Elev= 30
  4577.1  402.32  4695.6  398.74  4705.8  399.37  4711.4  399.19  4717.7  398.44
  4773.1  395.98  4802.3  393.83  4830.5  393.06  4861.1  390.57  4876.0  389.54
  4893.2  387.35  4898.7  387.25  4954.4  381.82  4966.9  380.79  4986.6  380.77
  4987.1  379.97  4992.1  379.97  4992.6  380.77  5017.9  381.25  5025.4  381.82
  5033.8  383.09  5041.7  382.83  5055.9  385.26  5076.9  387.69  5091.0  388.49
  5105.2  390.34  5126.2  391.41  5140.4  392.77  5225.4  396.11  5256.5  396.57
#Mann=4,-1,0
  4577.1    0.05       0  4861.1    0.16       0  4986.6    0.07       0
  4992.6    0.16       0
Bank Sta=4954.4,5025.4
Exp/Cntr=0.3,0.1

Type RM Length L Ch R = 1,1506,232,232,232
BEGIN DESCRIPTION:
Mapping XS 1761d376
END DESCRIPTION:
XS GIS Cut Line= 3
      2888034.94      6977012.61      2887927.32      6976557.79
      2887701.64      6976405.02
#Sta/Elev= 30
  4545.0  400.84  4635.0  399.01  4651.9  399.28  4665.9  397.98  4736.4  394.73
  4758.3  393.30  4778.7  393.08  4814.4  390.86  4861.1  387.51  4881.7  385.09
  4902.2  383.53  4912.4  381.54  4915.7  380.78  4922.8  380.57  4961.2  380.43
  4981.4  380.41  4981.9  379.61  4986.9  379.61  4987.4  380.41  5023.7  380.49
  5045.6  381.10  5061.3  381.54  5123.9  388.98  5137.6  390.12  5152.6  392.27
  5160.1  392.34  5167.6  393.52  5203.5  394.57  5254.4  397.35  5284.9  398.01
#Mann=6,-1,0
  4545.0    0.05       0  4814.4    0.16       0  4961.2    0.05       0
  4981.4   0.033       0  4987.4    0.05       0  5045.6    0.16       0
Bank Sta=4912.4,5061.3
Exp/Cntr=0.3,0.1

Type RM Length L Ch R = 1,1274,19,19,19
BEGIN DESCRIPTION:
Mapping XS 2e76f869
END DESCRIPTION:
XS GIS Cut Line= 4
      2888192.94      6976906.72      2888161.69      6976519.59
      2888081.83      6976382.44      2887895.41      6976239.18
#Sta/Elev= 30
  4504.3  401.09  4586.3  398.95  4606.4  399.17  4633.2  397.98  4696.6  394.24
  4746.8  394.24  4776.9  390.84  4817.0  387.54  4837.1  381.68  4843.6  380.94
  4847.1  380.54  4867.2  382.64  4887.3  383.07  4892.5  382.26  4909.6  382.29
  4921.4  381.28  4931.4  381.73  4937.1  380.95  4952.9  381.36  4958.7  380.67
  4977.2  380.42  4977.7  379.62  4982.7  379.62  4983.2  380.42  5111.7  380.94
  5139.7  388.14  5161.6  390.19  5204.1  394.27  5272.4  397.40  5286.5  398.38
#Mann=6,-1,0
  4504.3    0.05       0  4633.2    0.16       0  4977.2    0.07       0
  4983.2    0.16       0  5161.6    0.05       0  5272.4    0.16       0
Bank Sta=4843.6,5111.7
Exp/Cntr=0.3,0.1

Type RM Length L Ch R = 1,1255,20,20,20
BEGIN DESCRIPTION:
Mapping XS 1cd20cc5
END DESCRIPTION:
XS GIS Cut Line= 4
      2888257.18      6976925.84      2888175.58      6976514.39
      2888116.55      6976401.54      2887946.42      6976233.14
#Sta/Elev= 30
  4470.7  402.35  4646.4  397.22  4777.4  390.27  4814.6  386.09  4838.6  380.81
  4859.0  382.72  4865.7  380.97  4870.8  383.01  4892.6  378.41  4898.7  375.66
  4904.3  379.60  4919.4  373.20  4920.7  372.70  4926.4  378.72  4939.8  372.06
  4940.3  371.26  4945.8  372.06  4948.4  378.99  4965.1  373.20  4970.5  380.14
  4987.0  373.87  4992.6  380.44  5009.0  376.32  5013.8  381.14  5023.2  379.86
  5051.5  381.59  5101.0  380.60  5136.4  387.48  5186.7  392.80  5256.9  396.20
#Mann=5,-1,0
  4470.7    0.05       0  4646.4    0.16       0  4939.8    0.07       0
  4945.8    0.16       0  5186.7    0.05       0
Bank Sta=4919.4,4965.1
Exp/Cntr=0.3,0.1

Type RM Length L Ch R = 1,1235,233,233,233
BEGIN DESCRIPTION:
Mapping XS 1b99cf30
END DESCRIPTION:
XS GIS Cut Line= 4
      2888288.43      6976918.91      2888194.68      6976503.97
      2888116.55      6976361.61      2887969.05      6976220.97
#Sta/Elev= 30
  4464.8  402.72  4649.8  397.19  4766.1  390.78  4821.6  385.72  4827.6  382.72
  4837.9  380.40  4858.4  380.52  4892.5  375.61  4924.8  369.29  4940.9  367.74
  4966.6  367.39  4975.8  366.30  4976.3  365.50  4981.8  366.30  4984.5  367.98
  4991.7  368.43  5000.7  367.39  5006.3  371.55  5022.4  370.72  5028.1  373.66
  5037.3  373.41  5058.3  375.75  5072.4  378.70  5079.7  379.27  5086.6  377.96
  5100.7  379.06  5114.9  383.49  5150.5  388.39  5233.6  393.98  5256.4  395.44
#Mann=5,-1,0
  4464.8    0.05       0  4649.8    0.16       0  4975.8    0.07       0
  4981.8    0.16       0  5233.6    0.05       0
Bank Sta=4966.6,5000.7
Exp/Cntr=0.3,0.1

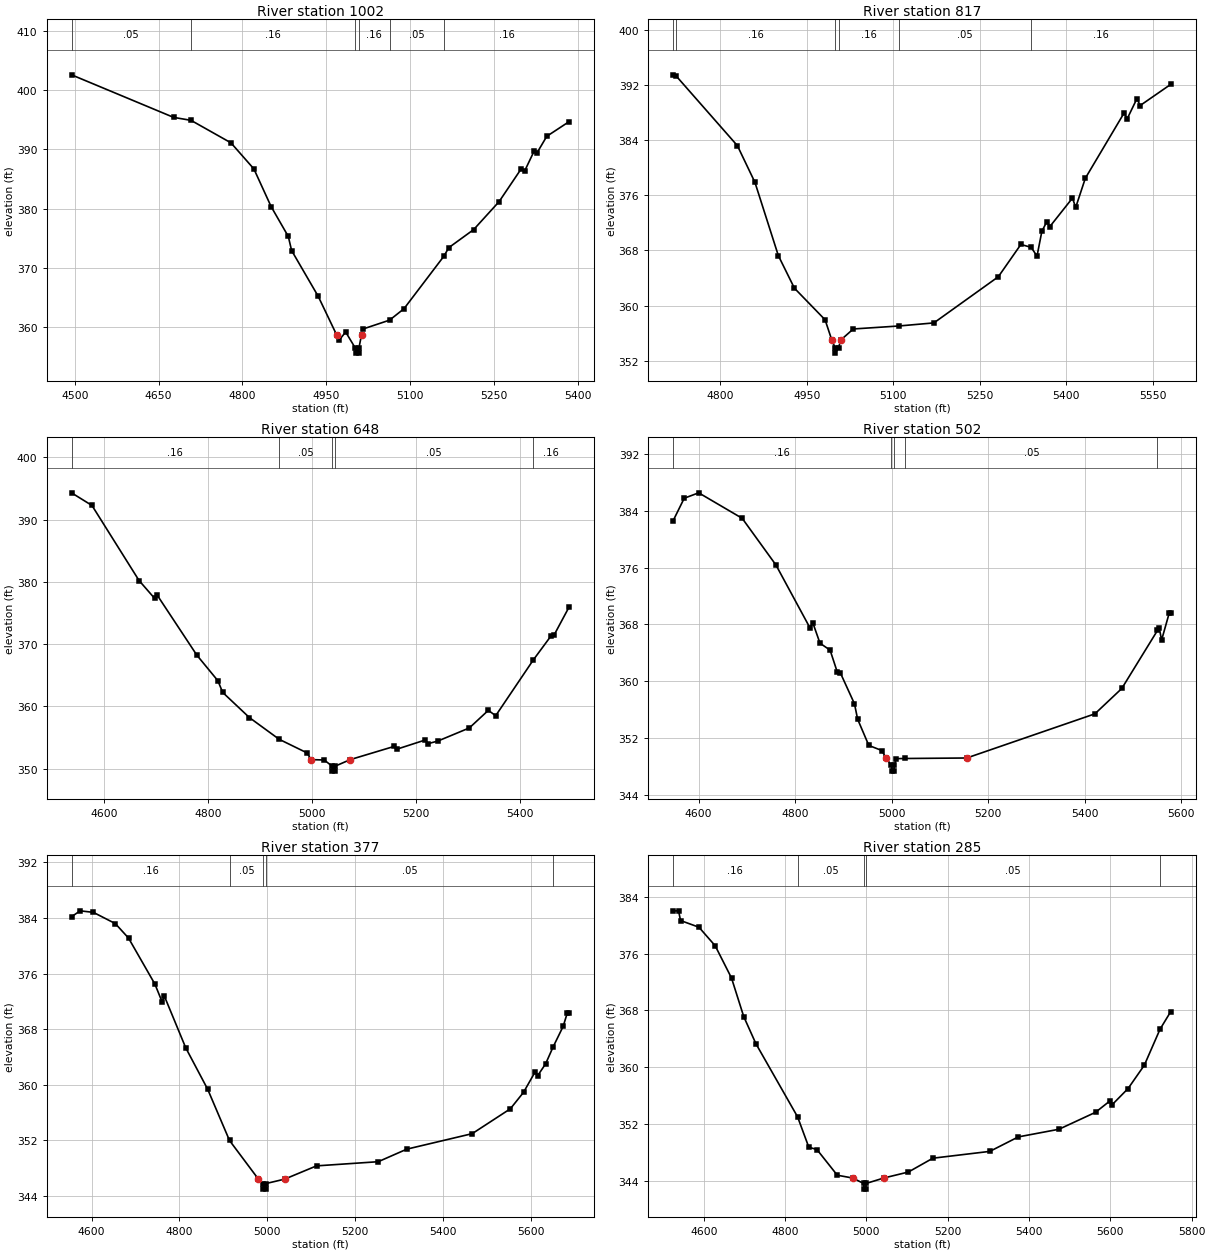
Type RM Length L Ch R = 1,1002,185,185,185
BEGIN DESCRIPTION:
Mapping XS a7304647
END DESCRIPTION:
XS GIS Cut Line= 3
      2888449.89      6976852.94      2888330.09      6976340.78
      2888000.22      6976184.52
#Sta/Elev= 30
  4494.0  402.58  4676.7  395.41  4707.9  394.91  4779.4  391.12  4820.5  386.72
  4851.3  380.38  4882.1  375.34  4888.0  372.97  4935.6  365.26  4968.6  358.76
  4973.0  357.86  4984.8  359.24  5002.4  356.48  5002.9  355.68  5007.9  355.68
  5008.4  356.48  5013.2  358.76  5015.3  359.73  5063.4  361.24  5089.2  363.16
  5160.7  372.02  5169.5  373.46  5214.0  376.50  5259.5  381.21  5299.4  386.78
  5305.0  386.32  5322.2  389.72  5327.7  389.48  5344.9  392.22  5385.0  394.70
#Mann=6,-1,0
  4494.0    0.05       0  4707.9    0.16       0  5002.4    0.07       0
  5008.4    0.16       0  5063.4    0.05       0  5160.7    0.16       0
Bank Sta=4968.6,5013.2
Exp/Cntr=0.3,0.1

Type RM Length L Ch R = 1,817,169,169,169
BEGIN DESCRIPTION:
UNT 090 IN DRY CR WATERSHED 2.0
END DESCRIPTION:
XS GIS Cut Line= 3
      2888525.00      6976575.01      2888475.00      6976275.00
      2887974.97      6976024.98
#Sta/Elev= 30
  4717.9  393.45  4723.4  393.26  4829.4  383.18  4859.8  377.87  4900.4  367.25
  4928.3  362.53  4981.5  357.95  4993.1  355.02  4998.8  353.92  4999.3  353.12
  5004.8  353.92  5008.7  355.02  5030.4  356.62  5109.0  357.05  5170.2  357.50
  5282.0  364.19  5321.1  368.87  5338.9  368.45  5349.1  367.18  5357.5  370.77
  5365.8  372.12  5371.4  371.46  5410.6  375.59  5416.2  374.23  5432.9  378.46
  5500.0  387.90  5505.6  387.09  5522.4  390.00  5528.0  389.00  5581.1  392.07
#Mann=6,-1,0
  4717.9    0.05       0  4723.4    0.16       0  4998.8    0.07       0
  5004.8    0.16       0  5109.0    0.05       0  5338.9    0.16       0
Bank Sta=4993.1,5008.7
Exp/Cntr=0.3,0.1

Type RM Length L Ch R = 1,648,146,146,146
BEGIN DESCRIPTION:
Mapping XS 8df2dfa0
END DESCRIPTION:
XS GIS Cut Line= 3
      2888655.32      6976623.46      2888580.66      6976142.51
      2888115.38      6976064.39
#Sta/Elev= 30
  4536.8  394.30  4576.1  392.27  4666.8  380.21  4697.0  377.32  4702.0  377.83
  4778.1  368.22  4818.6  364.11  4827.9  362.23  4879.3  358.19  4936.6  354.70
  4990.6  352.50  4998.0  351.43  5023.5  351.37  5038.6  350.38  5039.1  349.58
  5044.1  349.58  5044.6  350.38  5073.6  351.43  5157.7  353.54  5162.8  353.09
  5218.3  354.59  5223.4  353.99  5242.2  354.41  5303.0  356.52  5339.6  359.35
  5353.7  358.48  5426.3  367.46  5460.8  371.36  5465.9  371.40  5495.3  375.98
#Mann=5,-1,0
  4536.8    0.16       0  4936.6    0.05       0  5038.6    0.03       0
  5044.6    0.05       0  5426.3    0.16       0
Bank Sta=4998,5073.6
Exp/Cntr=0.3,0.1

Type RM Length L Ch R = 1,502,125,125,125
BEGIN DESCRIPTION:
Mapping XS a207cd38
END DESCRIPTION:
XS GIS Cut Line= 4
      2888822.19      6976548.03      2888816.99      6976271.94
      2888695.46      6976098.33      2888153.79      6976058.40
#Sta/Elev= 30
  4547.4  382.61  4570.4  385.78  4600.4  386.54  4690.5  382.95  4760.5  376.37
  4830.8  367.54  4836.9  368.23  4851.7  365.36  4872.7  364.38  4887.5  361.30
  4893.6  361.23  4923.2  356.82  4929.7  354.66  4952.9  350.96  4979.9  350.24
  4988.5  349.19  4999.9  348.14  5000.4  347.34  5005.4  347.34  5005.9  348.14
  5009.6  349.10  5028.6  349.12  5155.8  349.19  5421.4  355.41  5477.1  358.98
  5551.1  367.16  5554.6  367.57  5559.6  365.79  5575.5  369.63  5578.6  369.63
#Mann=5,-1,0
  4547.4    0.16       0  4999.9    0.07       0  5005.9    0.16       0
  5028.6    0.05       0  5551.1    0.16       0
Bank Sta=4988.5,5155.8
Exp/Cntr=0.3,0.1

Type RM Length L Ch R = 1,377,92,92,92
BEGIN DESCRIPTION:
Mapping XS 58fdc581
END DESCRIPTION:
XS GIS Cut Line= 3
      2888849.76      6976524.50      2888828.92      6976081.75
      2888141.46      6976034.87
#Sta/Elev= 30
  4554.5  384.18  4574.0  385.03  4604.1  384.81  4654.1  383.19  4684.1  381.11
  4744.2  374.47  4760.6  371.91  4765.6  372.76  4814.3  365.30  4864.3  359.32
  4913.9  351.95  4979.7  346.38  4990.6  345.74  4991.1  344.94  4996.1  344.94
  4996.6  345.74  5039.4  346.38  5111.9  348.29  5252.3  348.89  5317.4  350.70
  5466.1  352.93  5552.9  356.51  5583.0  358.89  5609.8  361.88  5614.8  361.26
  5633.1  362.98  5650.2  365.42  5673.2  368.40  5682.5  370.32  5686.8  370.32
#Mann=5,-1,0
  4554.5    0.16       0  4913.9    0.05       0  4990.6    0.03       0
  4996.6    0.05       0  5650.2    0.16       0
Bank Sta=4979.7,5039.4
Exp/Cntr=0.3,0.1

Type RM Length L Ch R = 1,285,112,112,112
BEGIN DESCRIPTION:
Mapping XS 2884526b
END DESCRIPTION:
XS GIS Cut Line= 4
      2888879.27      6976498.45      2888898.36      6976024.46
      2888762.95      6976041.82      2888150.05      6976026.19
#Sta/Elev= 30
  4524.6  382.01  4537.9  382.02  4542.9  380.65  4588.1  379.71  4628.1  377.09
  4668.2  372.55  4698.2  367.12  4728.2  363.29  4830.7  352.98  4858.3  348.70
  4878.3  348.37  4928.4  344.75  4965.9  344.36  4993.2  343.59  4993.7  342.79
  4998.7  342.79  4999.2  343.59  5043.0  344.36  5103.2  345.20  5163.5  347.15
  5303.5  348.11  5373.5  350.15  5473.6  351.23  5563.6  353.62  5598.9  355.22
  5603.9  354.66  5643.6  356.97  5683.6  360.26  5722.2  365.33  5748.6  367.82
#Mann=5,-1,0
  4524.6    0.16       0  4830.7    0.05       0  4993.2    0.03       0
  4999.2    0.05       0  5722.2    0.16       0
Bank Sta=4965.9,5043
Exp/Cntr=0.3,0.1

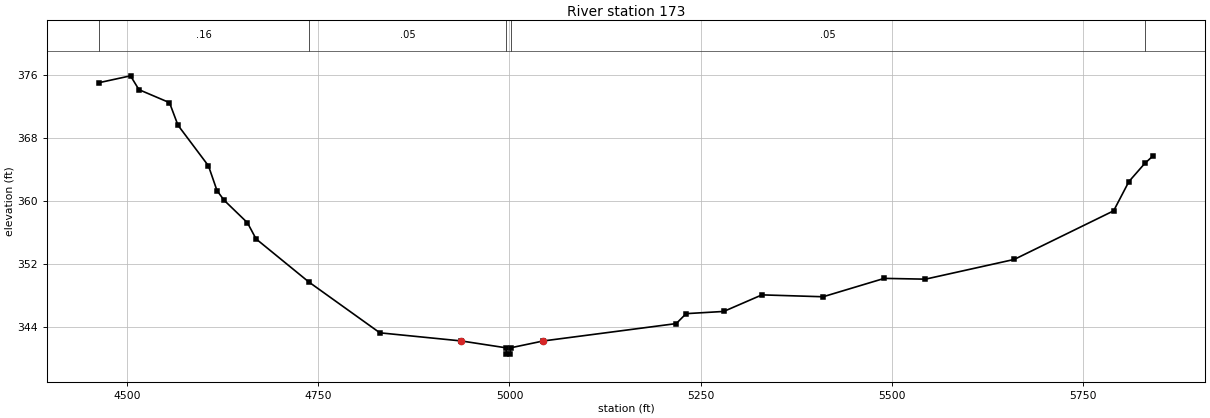
Type RM Length L Ch R = 1,173,0,0,0
BEGIN DESCRIPTION:
UNT 090 IN DRY CR WATERSHED 1.0
END DESCRIPTION:
XS GIS Cut Line= 6
      2888910.73      6976495.03      2888997.49      6976059.34
      2888992.46      6975967.02      2888932.90      6975960.17
      2888753.87      6976028.27      2888163.81      6976011.52
#Sta/Elev= 30
  4463.3  374.99  4504.1  375.85  4515.1  374.10  4555.1  372.45  4566.2  369.59
  4606.1  364.44  4617.3  361.30  4626.5  360.09  4657.1  357.23  4668.4  355.18
  4737.5  349.72  4830.4  343.28  4937.0  342.25  4995.5  341.38  4996.0  340.58
  5001.0  340.58  5001.5  341.38  5044.3  342.25  5218.2  344.45  5231.2  345.71
  5280.4  345.99  5330.4  348.09  5410.4  347.85  5490.5  350.18  5544.3  350.08
  5660.5  352.58  5790.6  358.74  5810.6  362.45  5831.3  364.74  5841.8  365.67
#Mann=5,-1,0
  4463.3    0.16       0  4737.5    0.05       0  4995.5    0.03       0
  5001.5    0.05       0  5831.3    0.16       0
Bank Sta=4937,5044.3
Exp/Cntr=0.3,0.1

Chan Stop Cuts=-1