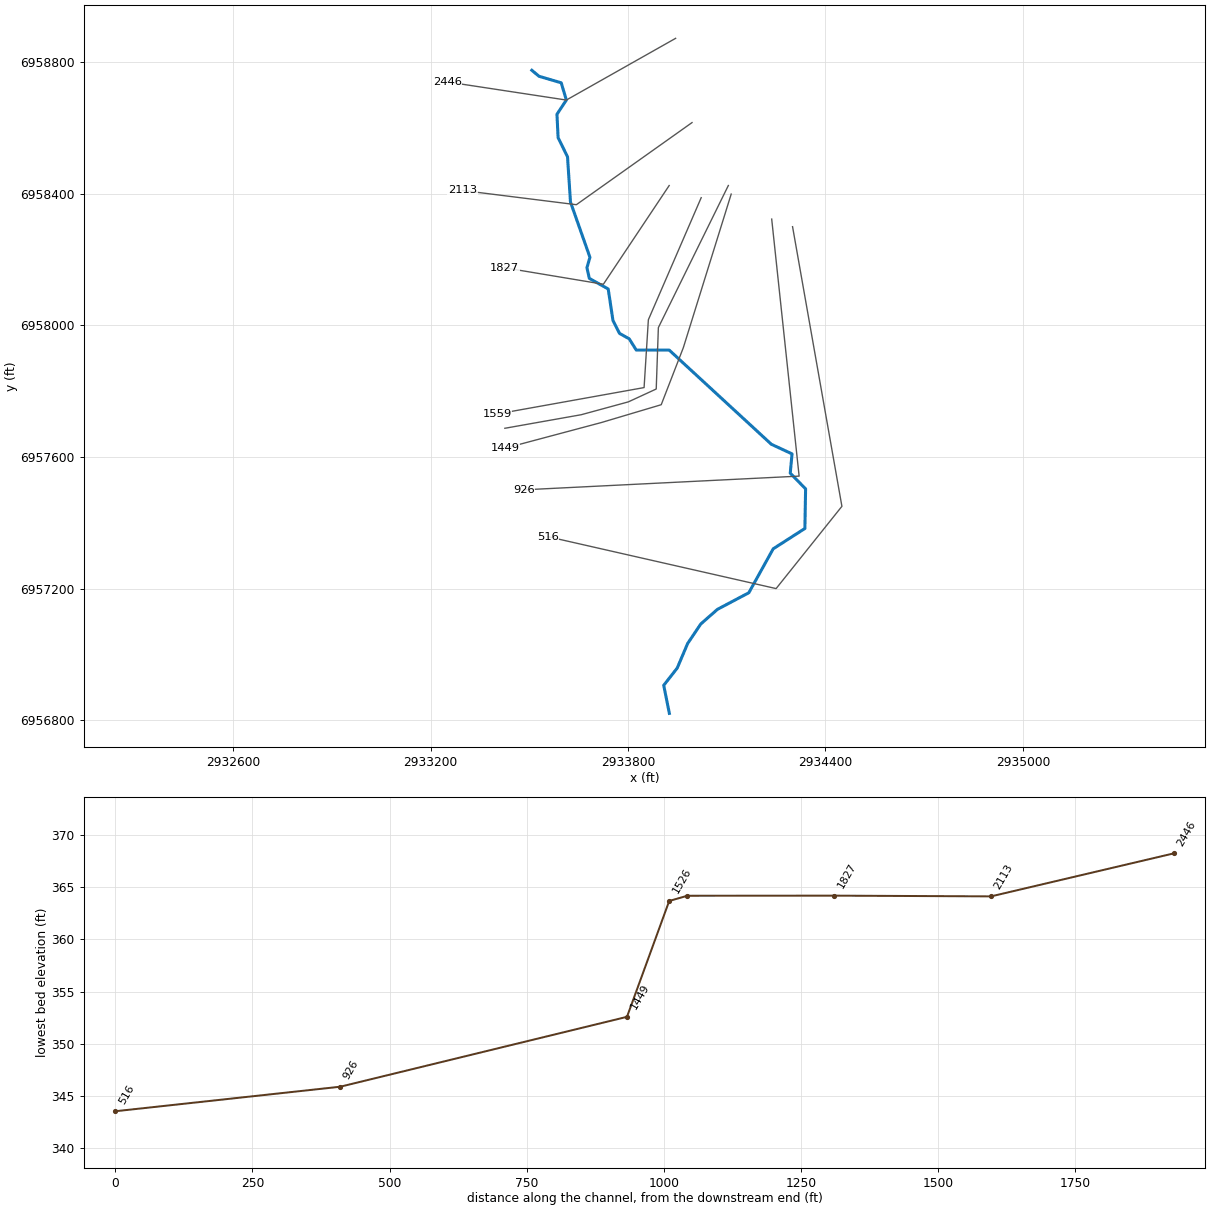
--- UNT 091 IN DRY CR WATERSHED.prj (project) ---

Proj Title=UNT 091 IN DRY CR WATERSHED Base Level Engineering
Current Plan=p01
Default Exp/Contr=0.3,0.1
English Units
Geom File=g01
Flow File=f01
Plan File=p01
BEGIN DESCRIPTION:
UNT 091 IN DRY CR WATERSHED
END DESCRIPTION:

--- UNT 091 IN DRY CR WATERSHED.p01 (plan) ---

Plan Title=Multiple Run
Short Identifier=Multiple
Geom File=g01
Flow File=f01
Subcritical Flow
K Sum by GR= 0
Std Step Tol= 0.01
Critical Tol= 0.01
Num of Std Step Trials= 20
Max Error Tol= 0.3
Flow Tol Ratio= 0.001
Split Flow NTrial= 30
Split Flow Tol= 0.02
Split Flow Ratio= 0.02
Log Output Level= 0
Friction Slope Method= 1
Unsteady Friction Slope Method= 2
Unsteady Bridges Friction Slope Method= 1
Parabolic Critical Depth
Global Vel Dist=  1 , 1 , 1
Global Log Level= 0
CheckData=True
Encroach Param= -1, 0, 0, 0
BEGIN DESCRIPTION:
Multiple Run
END DESCRIPTION:

--- UNT 091 IN DRY CR WATERSHED.f01 (steady flow) ---

Flow Title=Multiple
Number of Profiles=7
Profile Names=10-year,25-year,50-year,1pct_min,100-year,1pct_plu,500-year
River Rch & RM= UNT 091 IN DRY C,Reach-1,2446
     124     151     170      96     192     382     243
Boundary for River Rch & Prof#=UNT 091 IN DRY C,Reach-1,1
Up Type=0
Dn Type=3
Dn Slope=0.005
Boundary for River Rch & Prof#=UNT 091 IN DRY C,Reach-1,2
Up Type=0
Dn Type=3
Dn Slope=0.005
Boundary for River Rch & Prof#=UNT 091 IN DRY C,Reach-1,3
Up Type=0
Dn Type=3
Dn Slope=0.005
Boundary for River Rch & Prof#=UNT 091 IN DRY C,Reach-1,4
Up Type=0
Dn Type=3
Dn Slope=0.005
Boundary for River Rch & Prof#=UNT 091 IN DRY C,Reach-1,5
Up Type=0
Dn Type=3
Dn Slope=0.005
Boundary for River Rch & Prof#=UNT 091 IN DRY C,Reach-1,6
Up Type=0
Dn Type=3
Dn Slope=0.005
Boundary for River Rch & Prof#=UNT 091 IN DRY C,Reach-1,7
Up Type=0
Dn Type=3
Dn Slope=0.005

--- UNT 091 IN DRY CR WATERSHED.g01 (geometry) ---

Geom Title=Existing Conditions

River Reach=UNT 091 IN DRY C,Reach-1
Reach XY= 30
      2933507.52      6958775.43      2933529.22      6958757.20
      2933596.93      6958737.24      2933612.47      6958684.87
      2933583.91      6958641.75      2933587.38      6958570.57
      2933616.03      6958512.41      2933625.00      6958375.00
      2933684.14      6958206.97      2933675.00      6958175.00
      2933682.41      6958142.74      2933739.70      6958110.62
      2933754.19      6958014.61      2933774.16      6957975.55
      2933803.67      6957959.05      2933825.00      6957925.00
      2933925.00      6957925.00      2934235.48      6957638.69
      2934298.42      6957609.40      2934292.99      6957550.80
      2934339.65      6957503.06      2934337.48      6957382.62
      2934241.21      6957320.94      2934167.11      6957187.34
      2934071.82      6957136.94      2934020.99      6957092.35
      2933981.18      6957033.14      2933949.48      6956958.47
      2933908.38      6956905.96      2933925.59      6956820.71

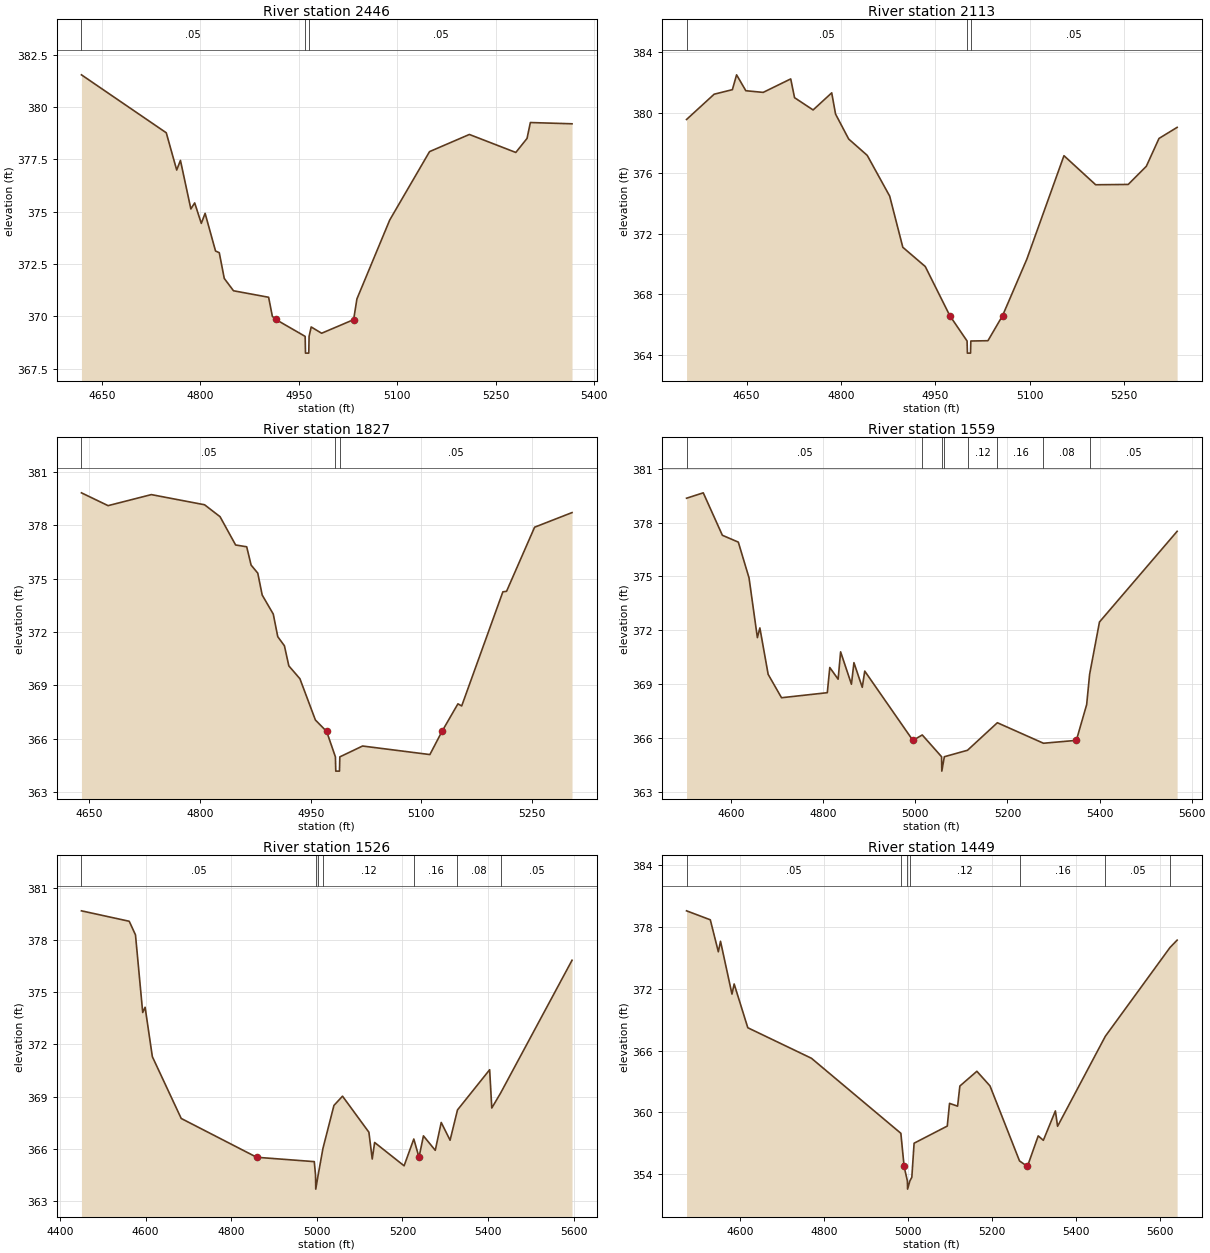
Type RM Length L Ch R = 1,2446,333,333,333
BEGIN DESCRIPTION:
UNT 091 IN DRY CR WATERSHED 3.0
END DESCRIPTION:
XS GIS Cut Line= 3
      2933944.56      6958872.45      2933612.47      6958684.87
      2933250.24      6958740.02
#Sta/Elev= 30
  4618.6  381.54  4747.9  378.77  4763.8  376.99  4769.5  377.45  4785.4  375.13
  4791.2  375.42  4801.3  374.44  4807.1  374.92  4823.0  373.12  4828.7  373.04
  4836.3  371.81  4850.4  371.22  4903.9  370.91  4909.6  370.00  4914.8  369.85
  4959.6  369.04  4960.1  368.24  4965.1  368.24  4965.6  369.04  4968.8  369.49
  4984.7  369.19  5033.5  369.84  5038.5  370.83  5088.5  374.60  5149.2  377.87
  5209.9  378.69  5280.7  377.83  5297.8  378.50  5302.9  379.26  5366.4  379.20
#Mann=3,-1,0
  4618.6    0.05       0  4959.6    0.03       0  4965.6    0.05       0
Bank Sta=4914.8,5033.5
Exp/Cntr=0.3,0.1

Type RM Length L Ch R = 1,2113,286,286,286
BEGIN DESCRIPTION:
Mapping XS 6dafb13a
END DESCRIPTION:
XS GIS Cut Line= 3
      2933994.44      6958616.36      2933642.87      6958366.78
      2933296.41      6958410.09
#Sta/Elev= 30
  4554.4  379.55  4598.3  381.22  4627.3  381.52  4634.0  382.50  4648.7  381.45
  4676.3  381.34  4720.1  382.23  4726.2  380.99  4755.7  380.18  4785.3  381.31
  4791.4  379.91  4812.3  378.26  4841.8  377.18  4877.5  374.49  4898.4  371.11
  4934.1  369.84  4973.2  366.59  5000.6  364.92  5001.1  364.12  5006.1  364.12
  5006.6  364.92  5033.8  364.94  5057.0  366.59  5095.7  370.33  5154.7  377.16
  5205.1  375.24  5256.9  375.26  5285.7  376.46  5305.9  378.30  5334.7  379.03
#Mann=3,-1,0
  4554.4    0.05       0  5000.6    0.03       0  5006.6    0.05       0
Bank Sta=4973.2,5057
Exp/Cntr=0.3,0.1

Type RM Length L Ch R = 1,1827,268,268,268
BEGIN DESCRIPTION:
UNT 091 IN DRY CR WATERSHED 2.0
END DESCRIPTION:
XS GIS Cut Line= 3
      2933925.02      6958425.04      2933725.00      6958125.00
      2933425.04      6958174.99
#Sta/Elev= 30
  4639.4  379.82  4675.5  379.10  4734.1  379.72  4806.2  379.15  4827.2  378.48
  4848.3  376.89  4863.3  376.79  4869.3  375.76  4878.3  375.31  4884.3  374.08
  4899.3  373.01  4905.4  371.74  4914.4  371.23  4920.4  370.10  4935.4  369.38
  4956.4  367.06  4971.6  366.42  4983.5  364.99  4984.0  364.19  4989.0  364.19
  4989.5  364.99  5020.3  365.60  5111.5  365.12  5127.9  366.42  5149.5  367.97
  5154.6  367.85  5210.4  374.26  5215.4  374.29  5253.4  377.89  5304.1  378.71
#Mann=3,-1,0
  4639.4    0.05       0  4983.5    0.03       0  4989.5    0.05       0
Bank Sta=4971.6,5127.9
Exp/Cntr=0.3,0.1

Type RM Length L Ch R = 1,1559,33,33,33
BEGIN DESCRIPTION:
Mapping XS 4d5b8741
END DESCRIPTION:
XS GIS Cut Line= 5
      2934022.34      6958388.16      2933861.76      6958017.10
      2933848.74      6957810.94      2933655.60      6957776.22
      2933401.68      6957730.64
#Sta/Elev= 30
  4503.4  379.35  4539.7  379.65  4581.2  377.29  4615.8  376.91  4639.1  374.92
  4657.2  371.60  4662.6  372.14  4680.6  369.56  4709.6  368.26  4809.0  368.54
  4814.4  369.94  4832.5  369.29  4837.9  370.81  4861.4  369.01  4866.8  370.21
  4884.9  368.84  4890.3  369.74  4994.8  365.89  5015.2  366.19  5057.1  364.98
  5057.6  364.18  5063.1  364.98  5113.4  365.34  5178.2  366.87  5278.3  365.73
  5349.7  365.89  5372.1  367.88  5378.5  369.56  5399.9  372.47  5568.5  377.51
#Mann=8,-1,0
  4503.4    0.05       0  5015.2    0.16       0  5057.1    0.03       0
  5063.1    0.16       0  5113.4    0.12       0  5178.2    0.16       0
  5278.3    0.08       0  5378.5    0.05       0
Bank Sta=4994.8,5349.7
Exp/Cntr=0.3,0.1

Type RM Length L Ch R = 1,1526,77,77,77
BEGIN DESCRIPTION:
Mapping XS c3818ba4
END DESCRIPTION:
XS GIS Cut Line= 6
      2934104.84      6958425.13      2933892.15      6957993.23
      2933885.64      6957806.60      2933801.00      6957767.54
      2933657.77      6957728.47      2933425.55      6957687.24
#Sta/Elev= 30
  4450.3  379.67  4561.9  379.07  4576.5  378.29  4593.4  373.83  4599.0  374.13
  4615.9  371.29  4683.3  367.74  4859.6  365.51  4994.1  365.26  4997.0  364.48
  4997.5  363.68  5003.0  364.48  5014.4  366.03  5040.0  368.49  5060.0  369.02
  5121.6  366.95  5129.4  365.41  5135.0  366.36  5203.8  365.02  5226.5  366.56
  5238.6  365.51  5249.0  366.74  5276.6  365.91  5290.5  367.51  5311.2  366.49
  5328.5  368.23  5403.6  370.54  5408.6  368.34  5429.2  369.20  5596.0  376.83
#Mann=7,-1,0
  4450.3    0.05       0  4997.0    0.03       0  5003.0    0.05       0
  5014.4    0.12       0  5226.5    0.16       0  5328.5    0.08       0
  5429.2    0.05       0
Bank Sta=4859.6,5238.6
Exp/Cntr=0.3,0.1

Type RM Length L Ch R = 1,1449,523,523,523
BEGIN DESCRIPTION:
Mapping XS 34db36e9
END DESCRIPTION:
XS GIS Cut Line= 5
      2934113.50      6958399.05      2933968.10      6957932.47
      2933900.83      6957758.86      2933718.53      6957704.60
      2933425.57      6957626.48
#Sta/Elev= 30
  4472.2  379.54  4528.8  378.67  4547.9  375.57  4553.1  376.59  4580.4  371.47
  4585.6  372.45  4618.1  368.21  4769.7  365.25  4982.6  357.98  4990.3  354.77
  4998.1  353.37  4998.6  352.57  5004.1  353.37  5008.7  353.72  5014.1  357.02
  5093.1  358.68  5098.5  360.88  5117.7  360.61  5123.1  362.56  5163.6  363.99
  5194.9  362.57  5265.2  355.30  5284.0  354.77  5309.7  357.73  5321.9  357.30
  5350.6  360.15  5355.8  358.66  5469.5  367.38  5623.4  375.98  5640.5  376.70
#Mann=7,-1,0
  4472.2    0.05       0  4982.6    0.12       0  4998.1    0.07       0
  5004.1    0.12       0  5265.2    0.16       0  5469.5    0.05       0
  5623.4    0.16       0
Bank Sta=4990.3,5284
Exp/Cntr=0.3,0.1

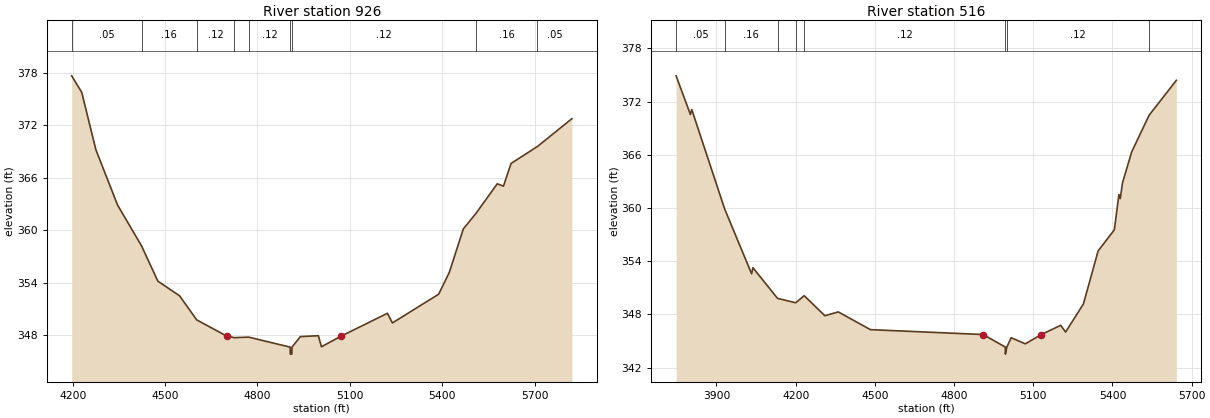
Type RM Length L Ch R = 1,926,410,410,410
BEGIN DESCRIPTION:
Mapping XS a327b4d0
END DESCRIPTION:
XS GIS Cut Line= 3
      2934236.61      6958323.13      2934319.95      6957541.84
      2933483.11      6957500.17
#Sta/Elev= 30
  4196.9  377.63  4229.5  375.75  4275.5  369.19  4345.9  362.88  4423.7  358.22
  4476.6  354.20  4547.0  352.53  4602.7  349.78  4701.1  347.91  4725.2  347.75
  4771.3  347.81  4906.0  346.67  4906.5  345.87  4911.5  345.87  4912.0  346.67
  4939.2  347.87  4997.6  347.97  5007.6  346.71  5070.7  347.91  5221.8  350.53
  5237.9  349.43  5388.1  352.71  5422.5  355.19  5468.2  360.17  5507.6  361.86
  5578.3  365.31  5598.3  365.04  5623.1  367.63  5708.8  369.57  5820.5  372.74
#Mann=9,-1,0
  4196.9    0.05       0  4423.7    0.16       0  4602.7    0.12       0
  4725.2    0.16       0  4771.3    0.12       0  4906.0    0.07       0
  4912.0    0.12       0  5507.6    0.16       0  5708.8    0.05       0
Bank Sta=4701.1,5070.7
Exp/Cntr=0.3,0.1

Type RM Length L Ch R = 1,516,0,0,0
BEGIN DESCRIPTION:
UNT 091 IN DRY CR WATERSHED 1.0
END DESCRIPTION:
XS GIS Cut Line= 4
      2934299.99      6958300.03      2934450.00      6957450.00
      2934250.00      6957200.00      2933556.04      6957357.82
#Sta/Elev= 30
  3747.0  374.90  3801.2  370.54  3806.3  371.10  3930.8  359.90  4033.0  352.58
  4038.1  353.26  4131.2  349.81  4200.2  349.31  4232.2  350.11  4310.6  347.85
  4361.4  348.28  4483.2  346.28  4910.0  345.73  4994.0  344.32  4994.5  343.52
  5000.0  344.32  5016.4  345.37  5069.7  344.68  5130.7  345.73  5204.0  346.77
  5222.6  346.01  5290.2  349.19  5345.7  355.16  5407.2  357.54  5424.5  361.51
  5429.6  361.06  5438.0  362.82  5472.7  366.31  5538.9  370.46  5642.0  374.39
#Mann=8,-1,0
  3747.0    0.05       0  3930.8    0.16       0  4131.2    0.12       0
  4200.2    0.16       0  4232.2    0.12       0  4994.0    0.07       0
  5000.0    0.12       0  5538.9    0.05       0
Bank Sta=4910,5130.7
Exp/Cntr=0.3,0.1

Chan Stop Cuts=-1