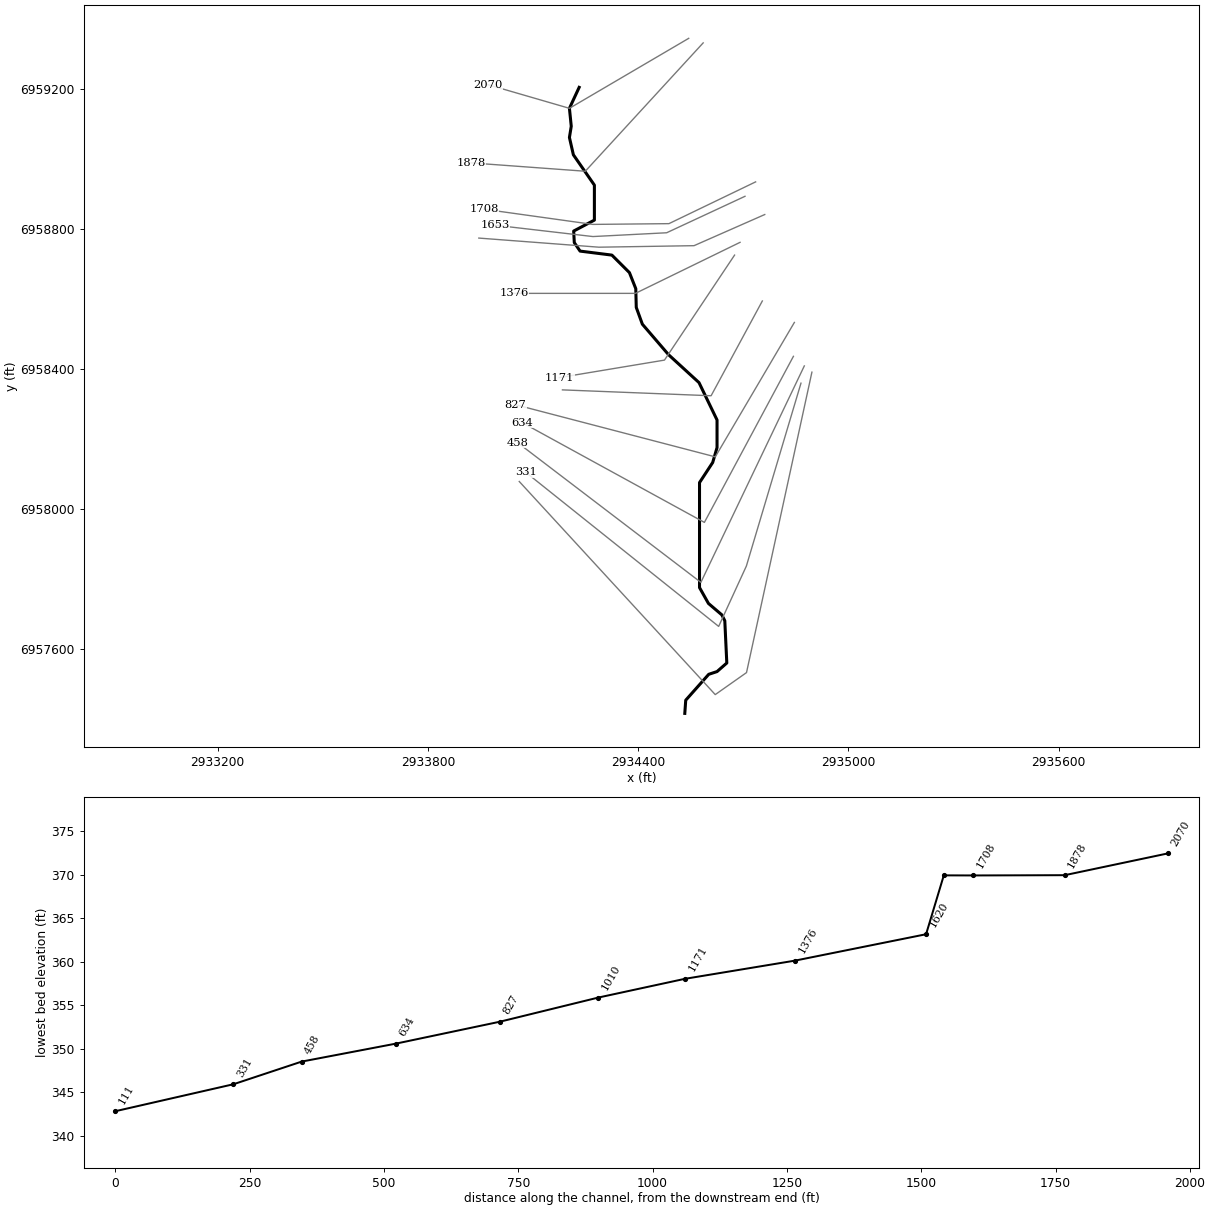
--- UNT 092 IN DRY CR WATERSHED.prj (project) ---

Proj Title=UNT 092 IN DRY CR WATERSHED Base Level Engineering
Current Plan=p01
Default Exp/Contr=0.3,0.1
English Units
Geom File=g01
Flow File=f01
Plan File=p01
BEGIN DESCRIPTION:
UNT 092 IN DRY CR WATERSHED
END DESCRIPTION:

--- UNT 092 IN DRY CR WATERSHED.p01 (plan) ---

Plan Title=Multiple Run
Short Identifier=Multiple
Geom File=g01
Flow File=f01
Subcritical Flow
K Sum by GR= 0
Std Step Tol= 0.01
Critical Tol= 0.01
Num of Std Step Trials= 20
Max Error Tol= 0.3
Flow Tol Ratio= 0.001
Split Flow NTrial= 30
Split Flow Tol= 0.02
Split Flow Ratio= 0.02
Log Output Level= 0
Friction Slope Method= 1
Unsteady Friction Slope Method= 2
Unsteady Bridges Friction Slope Method= 1
Parabolic Critical Depth
Global Vel Dist=  1 , 1 , 1
Global Log Level= 0
CheckData=True
Encroach Param= -1, 0, 0, 0
BEGIN DESCRIPTION:
Multiple Run
END DESCRIPTION:

--- UNT 092 IN DRY CR WATERSHED.f01 (steady flow) ---

Flow Title=Multiple
Number of Profiles=7
Profile Names=10-year,25-year,50-year,1pct_min,100-year,1pct_plu,500-year
River Rch & RM= UNT 092 IN DRY C,Reach-1,2070
      85     100     110      61     122     243     148
Boundary for River Rch & Prof#=UNT 092 IN DRY C,Reach-1,1
Up Type=0
Dn Type=3
Dn Slope=0.005
Boundary for River Rch & Prof#=UNT 092 IN DRY C,Reach-1,2
Up Type=0
Dn Type=3
Dn Slope=0.005
Boundary for River Rch & Prof#=UNT 092 IN DRY C,Reach-1,3
Up Type=0
Dn Type=3
Dn Slope=0.005
Boundary for River Rch & Prof#=UNT 092 IN DRY C,Reach-1,4
Up Type=0
Dn Type=3
Dn Slope=0.005
Boundary for River Rch & Prof#=UNT 092 IN DRY C,Reach-1,5
Up Type=0
Dn Type=3
Dn Slope=0.005
Boundary for River Rch & Prof#=UNT 092 IN DRY C,Reach-1,6
Up Type=0
Dn Type=3
Dn Slope=0.005
Boundary for River Rch & Prof#=UNT 092 IN DRY C,Reach-1,7
Up Type=0
Dn Type=3
Dn Slope=0.005

--- UNT 092 IN DRY CR WATERSHED.g01 (geometry) ---

Geom Title=Existing Conditions

River Reach=UNT 092 IN DRY C,Reach-1
Reach XY= 30
      2934231.55      6959204.35      2934203.77      6959144.45
      2934208.98      6959093.24      2934203.77      6959061.12
      2934215.06      6959011.64      2934275.00      6958925.00
      2934275.00      6958825.00      2934215.92      6958793.76
      2934217.66      6958760.77      2934234.15      6958736.47
      2934325.00      6958725.00      2934375.00      6958675.00
      2934393.12      6958629.08      2934394.50      6958575.61
      2934411.87      6958527.69      2934486.87      6958440.19
      2934573.53      6958360.70      2934625.00      6958253.92
      2934625.00      6958175.00      2934612.59      6958132.40
      2934575.00      6958075.00      2934575.00      6957775.00
      2934600.44      6957729.72      2934638.64      6957697.08
      2934647.13      6957680.30      2934652.86      6957559.47
      2934625.00      6957534.99      2934601.30      6957527.18
      2934535.67      6957453.22      2934532.99      6957415.54

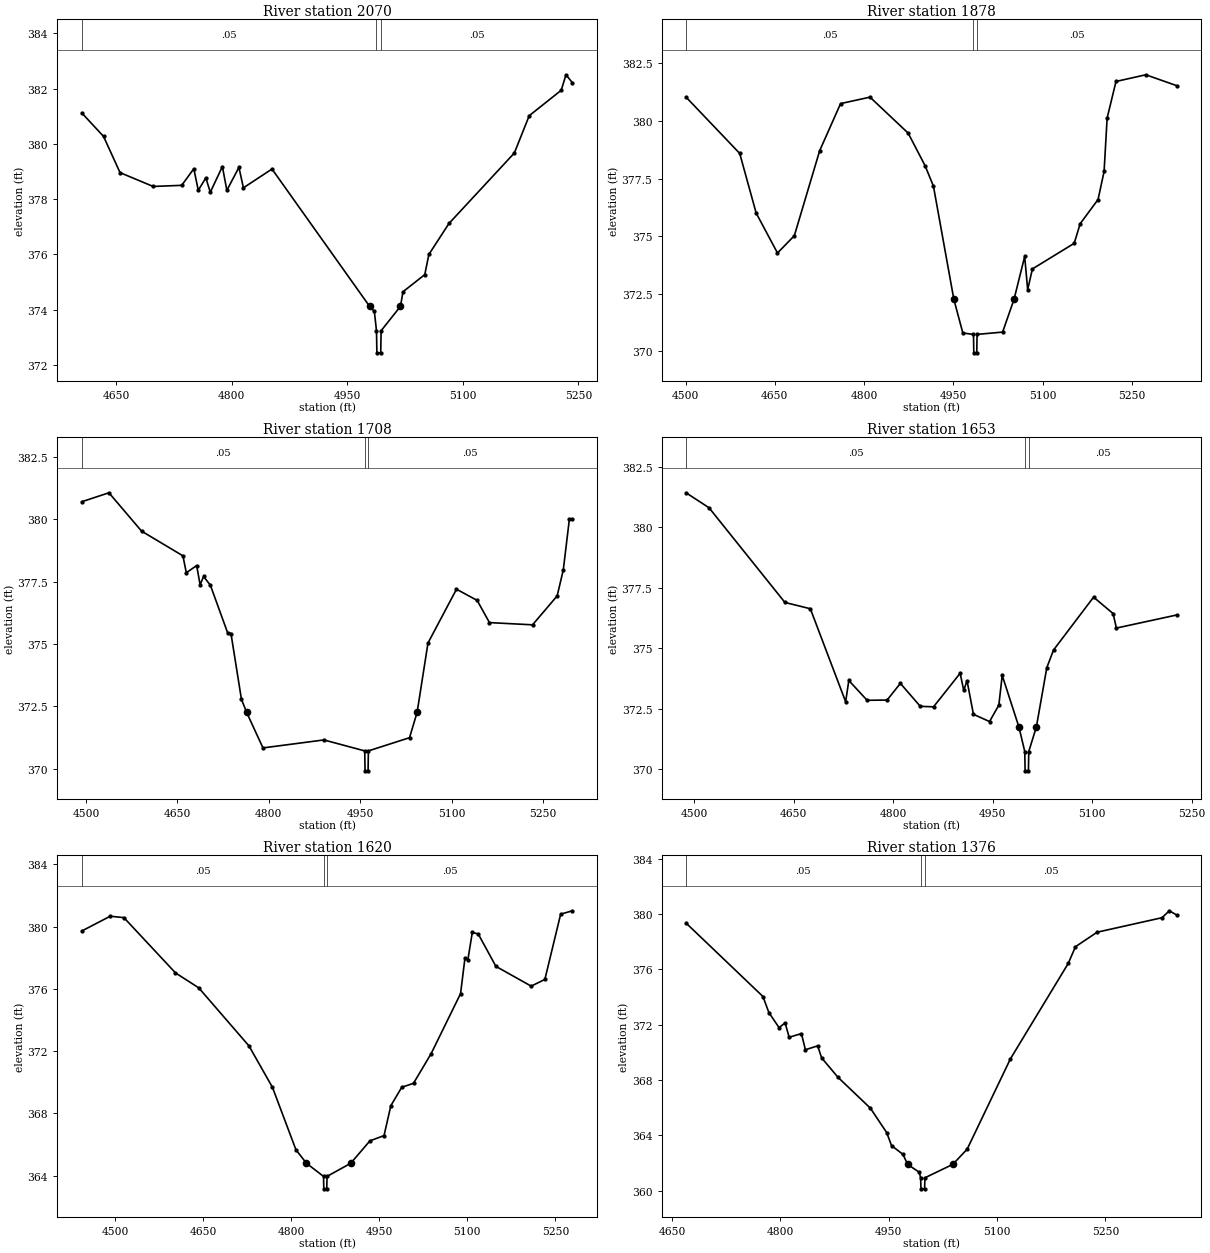
Type RM Length L Ch R = 1,2070,192,192,192
BEGIN DESCRIPTION:
UNT 092 IN DRY CR WATERSHED 4.0
END DESCRIPTION:
XS GIS Cut Line= 3
      2934544.18      6959344.43      2934203.77      6959144.45
      2933971.30      6959212.03
#Sta/Elev= 30
  4605.2  381.12  4633.5  380.27  4654.9  378.96  4697.9  378.46  4735.0  378.50
  4750.7  379.10  4756.5  378.32  4766.3  378.77  4772.1  378.25  4787.8  379.18
  4793.6  378.32  4809.3  379.15  4815.1  378.41  4852.2  379.09  4979.0  374.12
  4985.1  373.94  4987.9  373.24  4988.4  372.44  4993.4  372.44  4993.9  373.24
  5019.0  374.12  5022.3  374.65  5050.6  375.27  5055.9  376.00  5082.0  377.12
  5166.9  379.67  5186.2  381.02  5227.8  381.94  5233.9  382.50  5242.1  382.22
#Mann=3,-1,0
  4605.2    0.05       0  4987.9    0.03       0  4993.9    0.05       0
Bank Sta=4979,5019
Exp/Cntr=0.3,0.1

Type RM Length L Ch R = 1,1878,170,170,170
BEGIN DESCRIPTION:
Mapping XS 39fe7033
END DESCRIPTION:
XS GIS Cut Line= 3
      2934585.42      6959331.42      2934249.03      6958964.65
      2933923.48      6958988.52
#Sta/Elev= 30
  4500.8  381.03  4590.9  378.59  4618.6  376.00  4654.4  374.27  4682.7  375.02
  4725.3  378.71  4760.4  380.75  4809.8  381.03  4873.9  379.47  4902.3  378.06
  4916.4  377.17  4950.7  372.26  4965.8  370.80  4983.7  370.74  4984.2  369.94
  4989.2  369.94  4989.7  370.74  5032.6  370.84  5051.8  372.26  5069.7  374.12
  5074.7  372.68  5082.7  373.58  5152.9  374.69  5162.9  375.54  5193.0  376.59
  5203.1  377.81  5208.2  380.12  5223.1  381.71  5273.2  382.00  5324.9  381.53
#Mann=3,-1,0
  4500.8    0.05       0  4983.7    0.03       0  4989.7    0.05       0
Bank Sta=4950.7,5051.8
Exp/Cntr=0.3,0.1

Type RM Length L Ch R = 1,1708,55,55,55
BEGIN DESCRIPTION:
Mapping XS 8c1d628a
END DESCRIPTION:
XS GIS Cut Line= 4
      2934735.13      6958934.26      2934487.74      6958814.91
      2934270.73      6958812.74      2933960.44      6958856.13
#Sta/Elev= 30
  4493.2  380.71  4537.8  381.07  4591.4  379.53  4659.2  378.54  4664.8  377.86
  4681.8  378.15  4687.4  377.38  4693.2  377.71  4704.3  377.36  4732.6  375.45
  4738.1  375.42  4755.2  372.79  4763.7  372.26  4790.6  370.83  4890.6  371.15
  4957.6  370.71  4958.1  369.91  4963.1  369.91  4963.6  370.71  5031.1  371.24
  5043.6  372.26  5061.4  375.04  5108.2  377.20  5142.1  376.75  5162.3  375.86
  5233.0  375.77  5273.4  376.93  5283.5  377.98  5293.4  380.00  5298.2  380.00
#Mann=3,-1,0
  4493.2    0.05       0  4957.6    0.03       0  4963.6    0.05       0
Bank Sta=4763.7,5043.6
Exp/Cntr=0.3,0.1

Type RM Length L Ch R = 1,1653,33,33,33
BEGIN DESCRIPTION:
Mapping XS 7577bd9d
END DESCRIPTION:
XS GIS Cut Line= 4
      2934704.79      6958893.05      2934481.23      6958788.87
      2934270.73      6958778.02      2933990.74      6958810.57
#Sta/Elev= 30
  4487.9  381.43  4522.5  380.81  4636.9  376.89  4675.2  376.63  4728.4  372.78
  4733.2  373.66  4760.8  372.84  4790.9  372.85  4810.9  373.54  4840.9  372.59
  4860.9  372.57  4901.0  373.96  4906.4  373.25  4911.4  373.65  4921.0  372.26
  4945.3  371.96  4959.3  372.64  4964.4  373.87  4989.5  371.74  4998.4  370.72
  4998.9  369.92  5003.9  369.92  5004.4  370.72  5015.9  371.74  5031.6  374.19
  5041.7  374.92  5102.1  377.11  5131.5  376.43  5136.5  375.83  5227.2  376.37
#Mann=3,-1,0
  4487.9    0.05       0  4998.4    0.03       0  5004.4    0.05       0
Bank Sta=4989.5,5015.9
Exp/Cntr=0.3,0.1

Type RM Length L Ch R = 1,1620,244,244,244
BEGIN DESCRIPTION:
Mapping XS ec50601e
END DESCRIPTION:
XS GIS Cut Line= 4
      2934761.17      6958840.95      2934559.36      6958751.97
      2934288.09      6958747.63      2933945.23      6958773.67
#Sta/Elev= 30
  4443.1  379.72  4491.6  380.67  4514.9  380.58  4602.8  377.03  4642.4  376.07
  4728.0  372.34  4768.0  369.68  4808.0  365.67  4826.0  364.80  4855.0  363.96
  4855.5  363.16  4860.5  363.16  4861.0  363.96  4901.3  364.80  4934.0  366.24
  4958.1  366.58  4969.7  368.50  4988.2  369.68  5008.3  369.94  5038.3  371.84
  5088.5  375.70  5095.9  377.96  5100.9  377.87  5108.5  379.63  5118.6  379.53
  5148.7  377.45  5208.8  376.18  5232.1  376.61  5259.0  380.80  5278.8  381.02
#Mann=3,-1,0
  4443.1    0.05       0  4855.0    0.03       0  4861.0    0.05       0
Bank Sta=4826,4901.3
Exp/Cntr=0.3,0.1

Type RM Length L Ch R = 1,1376,205,205,205
BEGIN DESCRIPTION:
Mapping XS b206e1e1
END DESCRIPTION:
XS GIS Cut Line= 3
      2934690.69      6958761.51      2934392.11      6958615.69
      2934044.90      6958615.69
#Sta/Elev= 30
  4669.2  379.35  4775.7  374.04  4783.9  372.88  4798.0  371.79  4806.4  372.13
  4812.0  371.09  4829.0  371.36  4834.5  370.19  4851.5  370.47  4857.0  369.60
  4879.6  368.20  4924.6  365.96  4947.1  364.20  4953.8  363.26  4969.7  362.62
  4976.1  361.90  4992.2  361.33  4994.1  360.93  4994.6  360.13  4999.6  360.13
  5000.1  360.93  5038.7  361.90  5058.6  363.00  5118.6  369.54  5198.6  376.43
  5208.6  377.64  5238.6  378.69  5328.6  379.74  5338.6  380.24  5348.7  379.94
#Mann=3,-1,0
  4669.2    0.05       0  4994.1    0.03       0  5000.1    0.05       0
Bank Sta=4976.1,5038.7
Exp/Cntr=0.3,0.1

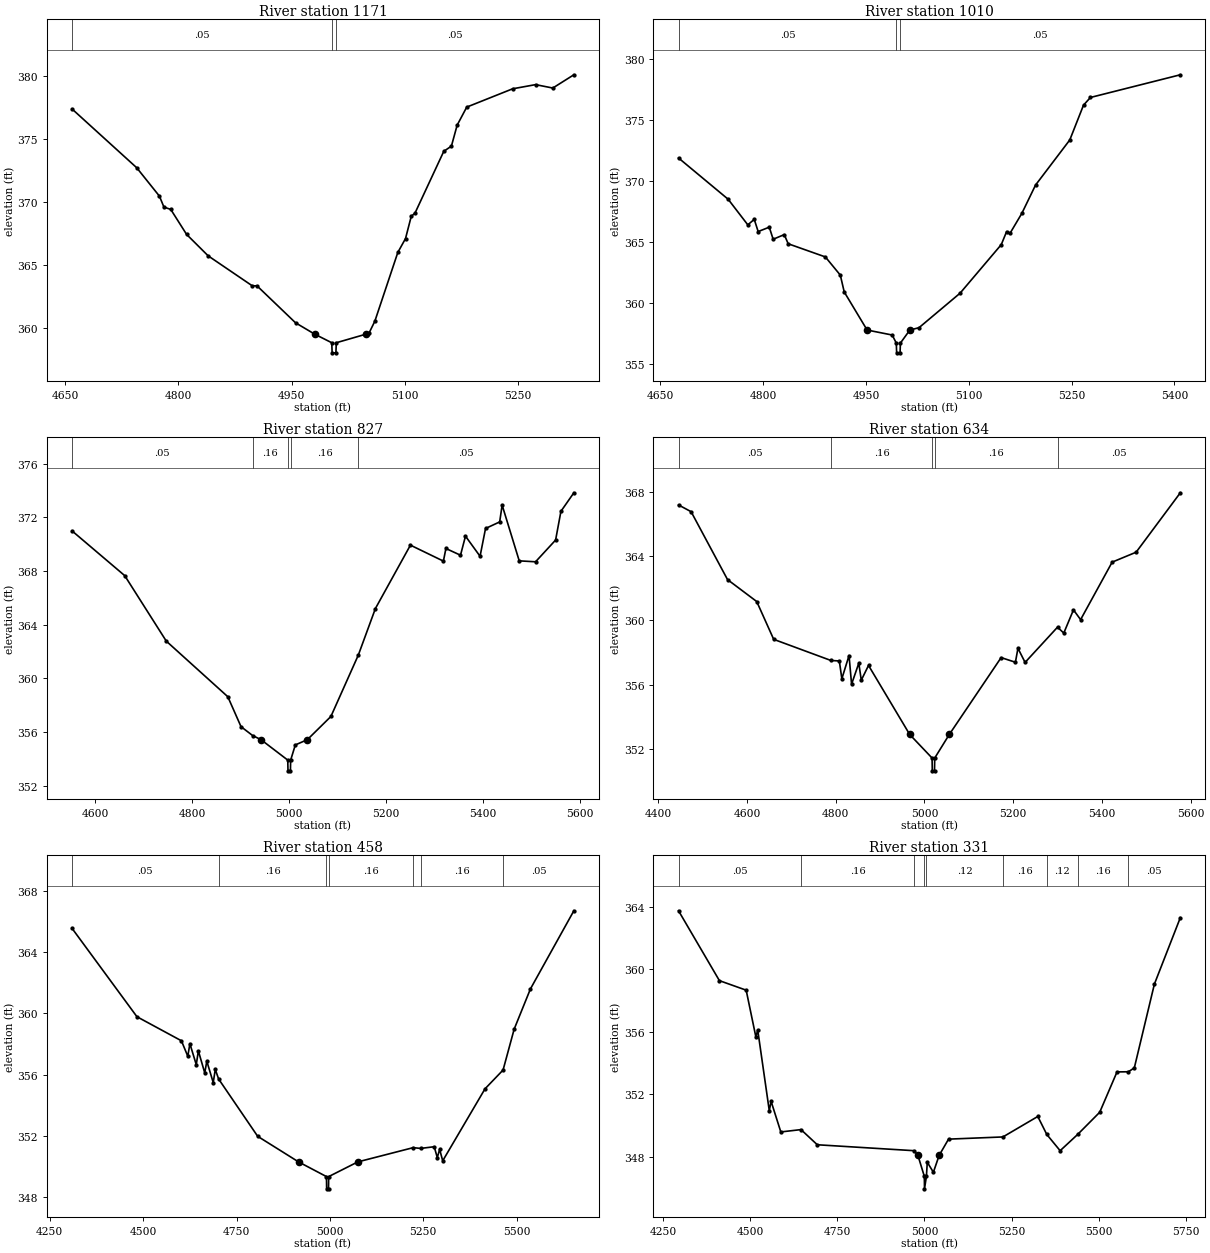
Type RM Length L Ch R = 1,1171,161,161,161
BEGIN DESCRIPTION:
UNT 092 IN DRY CR WATERSHED 2.0
END DESCRIPTION:
XS GIS Cut Line= 3
      2934675.00      6958725.01      2934475.00      6958425.00
      2934175.00      6958375.00
#Sta/Elev= 30
  4659.1  377.35  4744.7  372.70  4774.8  370.45  4780.8  369.58  4789.8  369.40
  4810.8  367.42  4839.4  365.72  4898.0  363.34  4904.0  363.35  4955.1  360.42
  4980.5  359.52  5003.1  358.84  5003.6  358.04  5008.6  358.04  5009.1  358.84
  5048.5  359.52  5052.6  359.62  5060.2  360.55  5090.6  365.99  5100.8  367.09
  5108.4  368.85  5113.4  369.11  5151.5  374.00  5161.6  374.41  5169.2  376.07
  5181.9  377.50  5242.7  378.95  5273.1  379.28  5295.9  379.01  5323.8  380.06
#Mann=3,-1,0
  4659.1    0.05       0  5003.1    0.03       0  5009.1    0.05       0
Bank Sta=4980.5,5048.5
Exp/Cntr=0.3,0.1

Type RM Length L Ch R = 1,1010,183,183,183
BEGIN DESCRIPTION:
Mapping XS dad77fe5
END DESCRIPTION:
XS GIS Cut Line= 3
      2934754.26      6958593.94      2934608.07      6958323.13
      2934183.86      6958339.90
#Sta/Elev= 30
  4676.4  371.86  4748.8  368.48  4777.5  366.38  4786.9  366.83  4792.6  365.83
  4808.8  366.19  4814.5  365.20  4830.7  365.58  4836.4  364.83  4890.7  363.75
  4912.5  362.26  4918.2  360.88  4951.6  357.76  4988.2  357.35  4994.2  356.69
  4994.7  355.89  4999.7  355.89  5000.2  356.69  5014.0  357.76  5027.3  357.95
  5087.3  360.78  5147.4  364.76  5155.2  365.83  5160.2  365.69  5177.4  367.32
  5197.4  369.64  5247.4  373.34  5267.4  376.19  5277.5  376.82  5408.7  378.68
#Mann=3,-1,0
  4676.4    0.05       0  4994.2    0.03       0  5000.2    0.05       0
Bank Sta=4951.6,5014
Exp/Cntr=0.3,0.1

Type RM Length L Ch R = 1,827,193,193,193
BEGIN DESCRIPTION:
Mapping XS 64e6c07f
END DESCRIPTION:
XS GIS Cut Line= 3
      2934845.68      6958532.65      2934619.98      6958148.53
      2934048.50      6958297.89
#Sta/Elev= 30
  4551.9  370.99  4660.6  367.66  4746.5  362.78  4873.5  358.64  4900.8  356.41
  4924.7  355.75  4942.1  355.44  4997.3  353.92  4997.8  353.12  5002.8  353.12
  5003.3  353.92  5012.9  355.05  5037.7  355.44  5086.4  357.17  5143.0  361.74
  5178.3  365.21  5250.6  369.93  5318.7  368.74  5323.9  369.68  5354.0  369.18
  5364.3  370.60  5394.4  369.10  5405.7  371.17  5434.9  371.66  5440.0  372.91
  5475.3  368.76  5509.0  368.69  5550.4  370.31  5561.4  372.45  5588.1  373.83
#Mann=5,-1,0
  4551.9    0.05       0  4924.7    0.16       0  4997.3    0.07       0
  5003.3    0.16       0  5143.0    0.05       0
Bank Sta=4942.1,5037.7
Exp/Cntr=0.3,0.1

Type RM Length L Ch R = 1,634,176,176,176
BEGIN DESCRIPTION:
Mapping XS 8fe443f2
END DESCRIPTION:
XS GIS Cut Line= 3
      2934842.94      6958435.76      2934588.89      6957961.23
      2934069.43      6958246.09
#Sta/Elev= 30
  4445.9  367.21  4474.2  366.79  4556.3  362.55  4622.1  361.18  4660.3  358.82
  4789.3  357.50  4808.2  357.47  4813.9  356.36  4830.1  357.81  4835.8  356.02
  4852.1  357.33  4857.7  356.27  4874.0  357.19  4966.8  352.88  5017.2  351.41
  5017.7  350.61  5022.7  350.61  5023.2  351.41  5056.0  352.88  5172.8  357.68
  5205.0  357.39  5210.7  358.26  5226.8  357.38  5299.9  359.58  5314.0  359.21
  5335.8  360.66  5351.9  360.05  5423.0  363.64  5477.0  364.26  5576.6  367.97
#Mann=5,-1,0
  4445.9    0.05       0  4789.3    0.16       0  5017.2    0.07       0
  5023.2    0.16       0  5299.9    0.05       0
Bank Sta=4966.8,5056
Exp/Cntr=0.3,0.1

Type RM Length L Ch R = 1,458,127,127,127
BEGIN DESCRIPTION:
Mapping XS b3543d02
END DESCRIPTION:
XS GIS Cut Line= 3
      2934874.03      6958408.38      2934578.89      6957789.88
      2934055.90      6958189.17
#Sta/Elev= 30
  4309.8  365.55  4483.5  359.78  4602.5  358.21  4619.6  357.20  4625.2  358.02
  4642.3  356.65  4647.9  357.55  4665.0  356.11  4670.5  356.88  4687.7  355.48
  4693.2  356.34  4702.2  355.71  4806.7  351.97  4916.1  350.30  4990.8  349.34
  4991.3  348.54  4996.3  348.54  4996.8  349.34  5074.8  350.30  5223.0  351.23
  5242.9  351.18  5279.3  351.29  5287.5  350.58  5293.8  351.12  5302.0  350.37
  5415.2  355.07  5463.6  356.30  5493.3  358.97  5536.9  361.60  5653.1  366.70
#Mann=7,-1,0
  4309.8    0.05       0  4702.2    0.16       0  4990.8    0.07       0
  4996.8    0.16       0  5223.0    0.12       0  5242.9    0.16       0
  5463.6    0.05       0
Bank Sta=4916.1,5074.8
Exp/Cntr=0.3,0.1

Type RM Length L Ch R = 1,331,220,220,220
BEGIN DESCRIPTION:
Mapping XS 44f0407f
END DESCRIPTION:
XS GIS Cut Line= 4
      2934864.52      6958359.08      2934708.73      6957836.60
      2934629.64      6957664.03      2934079.24      6958104.36
#Sta/Elev= 30
  4294.3  363.73  4411.6  359.26  4488.4  358.65  4516.3  355.65  4521.5  356.11
  4554.7  350.94  4559.9  351.54  4587.8  349.58  4645.7  349.73  4692.5  348.76
  4970.5  348.38  4981.2  348.08  4999.6  346.74  5000.1  345.94  5005.6  346.74
  5008.1  347.64  5025.6  347.00  5042.1  348.08  5069.1  349.12  5225.1  349.26
  5325.2  350.57  5351.0  349.42  5389.3  348.38  5439.6  349.42  5502.9  350.84
  5552.5  353.42  5585.2  353.43  5602.2  353.68  5659.8  359.04  5734.2  363.29
#Mann=9,-1,0
  4294.3    0.05       0  4645.7    0.16       0  4970.5    0.12       0
  4999.6    0.07       0  5005.6    0.12       0  5225.1    0.16       0
  5351.0    0.12       0  5439.6    0.16       0  5585.2    0.05       0
Bank Sta=4981.2,5042.1
Exp/Cntr=0.3,0.1

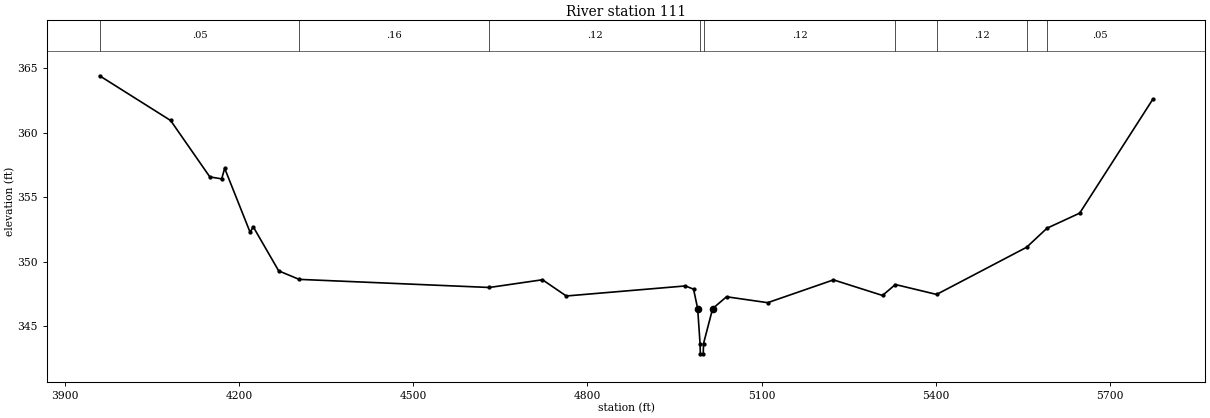
Type RM Length L Ch R = 1,111,0,0,0
BEGIN DESCRIPTION:
UNT 092 IN DRY CR WATERSHED 1.0
END DESCRIPTION:
XS GIS Cut Line= 4
      2934895.74      6958390.61      2934709.10      6957532.07
      2934619.87      6957469.19      2934060.63      6958078.10
#Sta/Elev= 30
  3959.6  364.42  4081.9  360.95  4149.5  356.57  4169.9  356.42  4175.0  357.24
  4219.0  352.26  4224.1  352.71  4268.1  349.28  4303.3  348.62  4631.0  347.99
  4722.6  348.59  4763.6  347.33  4968.8  348.11  4982.9  347.86  4990.0  346.35
  4994.1  343.64  4994.6  342.84  4999.6  342.84  5000.1  343.64  5015.8  346.35
  5039.7  347.27  5110.6  346.81  5224.0  348.58  5308.5  347.37  5330.6  348.22
  5401.7  347.45  5556.7  351.11  5591.9  352.59  5648.2  353.76  5774.1  362.59
#Mann=9,-1,0
  3959.6    0.05       0  4303.3    0.16       0  4631.0    0.12       0
  4994.1    0.07       0  5000.1    0.12       0  5330.6    0.16       0
  5401.7    0.12       0  5556.7    0.16       0  5591.9    0.05       0
Bank Sta=4990,5015.8
Exp/Cntr=0.3,0.1

Chan Stop Cuts=-1