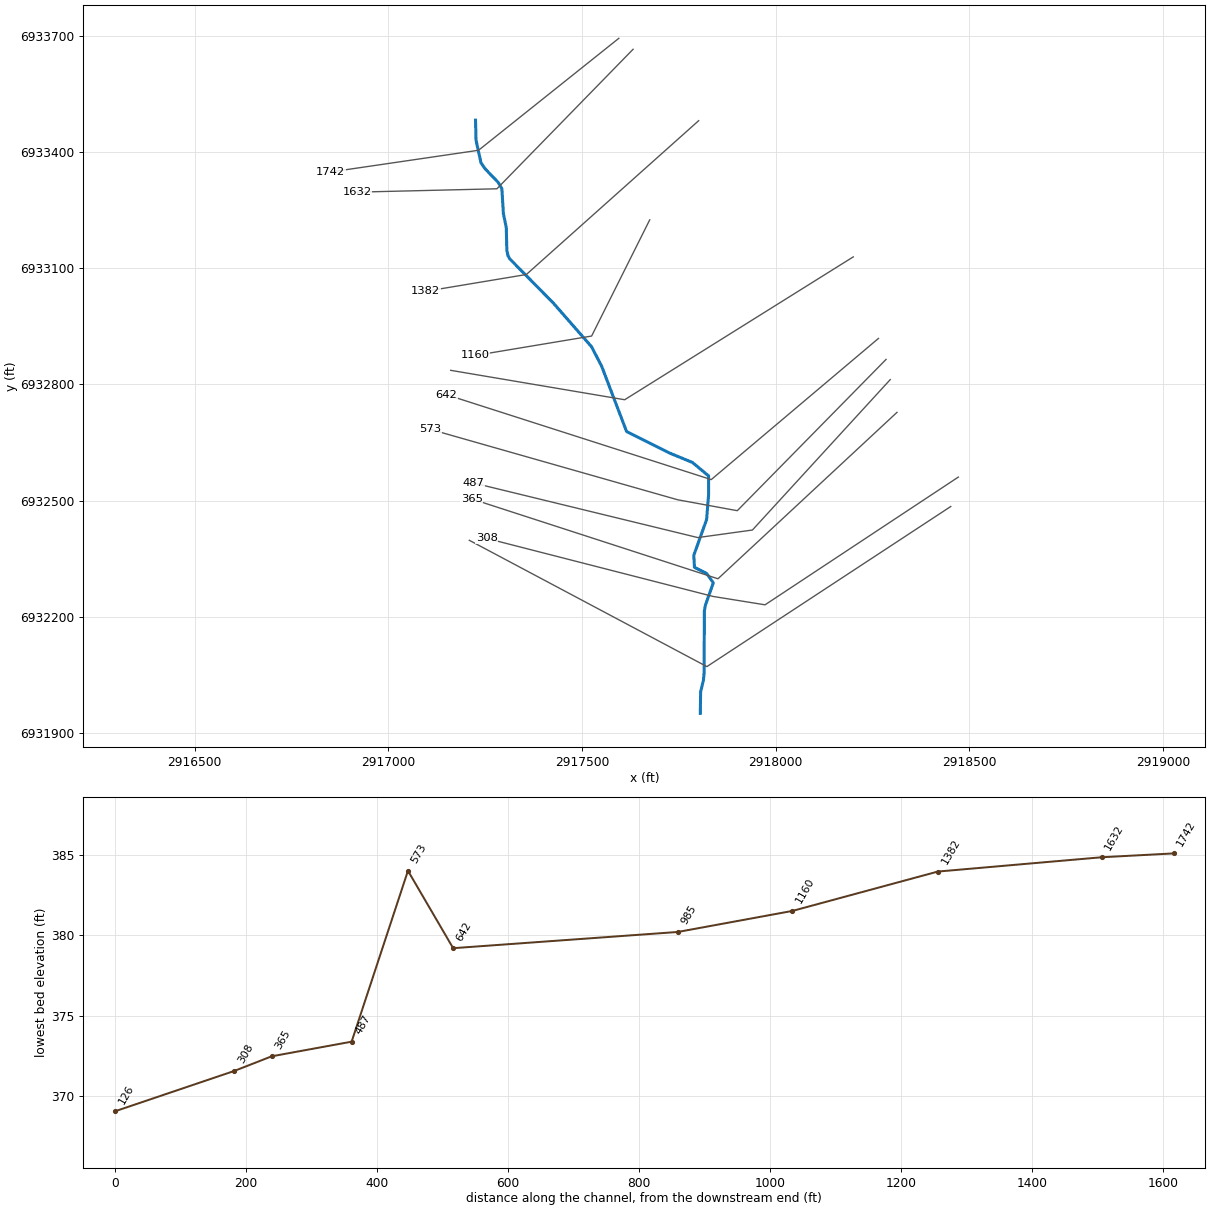
--- UNT 093 IN DRY CR WATERSHED.prj (project) ---

Proj Title=UNT 093 IN DRY CR WATERSHED Base Level Engineering
Current Plan=p01
Default Exp/Contr=0.3,0.1
English Units
Geom File=g01
Flow File=f01
Plan File=p01
BEGIN DESCRIPTION:
UNT 093 IN DRY CR WATERSHED
END DESCRIPTION:

--- UNT 093 IN DRY CR WATERSHED.p01 (plan) ---

Plan Title=Multiple Run
Short Identifier=Multiple
Geom File=g01
Flow File=f01
Subcritical Flow
K Sum by GR= 0
Std Step Tol= 0.01
Critical Tol= 0.01
Num of Std Step Trials= 20
Max Error Tol= 0.3
Flow Tol Ratio= 0.001
Split Flow NTrial= 30
Split Flow Tol= 0.02
Split Flow Ratio= 0.02
Log Output Level= 0
Friction Slope Method= 1
Unsteady Friction Slope Method= 2
Unsteady Bridges Friction Slope Method= 1
Parabolic Critical Depth
Global Vel Dist=  1 , 1 , 1
Global Log Level= 0
CheckData=True
Encroach Param= -1, 0, 0, 0
BEGIN DESCRIPTION:
Multiple Run
END DESCRIPTION:

--- UNT 093 IN DRY CR WATERSHED.f01 (steady flow) ---

Flow Title=Multiple
Number of Profiles=7
Profile Names=10-year,25-year,50-year,1pct_min,100-year,1pct_plu,500-year
River Rch & RM= UNT 093 IN DRY C,Reach-1,1742
     348     455     541     321     640    1278     896
Boundary for River Rch & Prof#=UNT 093 IN DRY C,Reach-1,1
Up Type=0
Dn Type=3
Dn Slope=0.005
Boundary for River Rch & Prof#=UNT 093 IN DRY C,Reach-1,2
Up Type=0
Dn Type=3
Dn Slope=0.005
Boundary for River Rch & Prof#=UNT 093 IN DRY C,Reach-1,3
Up Type=0
Dn Type=3
Dn Slope=0.005
Boundary for River Rch & Prof#=UNT 093 IN DRY C,Reach-1,4
Up Type=0
Dn Type=3
Dn Slope=0.005
Boundary for River Rch & Prof#=UNT 093 IN DRY C,Reach-1,5
Up Type=0
Dn Type=3
Dn Slope=0.005
Boundary for River Rch & Prof#=UNT 093 IN DRY C,Reach-1,6
Up Type=0
Dn Type=3
Dn Slope=0.005
Boundary for River Rch & Prof#=UNT 093 IN DRY C,Reach-1,7
Up Type=0
Dn Type=3
Dn Slope=0.005

--- UNT 093 IN DRY CR WATERSHED.g01 (geometry) ---

Geom Title=Existing Conditions

River Reach=UNT 093 IN DRY C,Reach-1
Reach XY= 30
      2917225.20      6933482.35      2917226.52      6933430.69
      2917239.36      6933372.28      2917250.08      6933356.75
      2917284.34      6933321.02      2917293.26      6933305.04
      2917297.17      6933240.77      2917304.63      6933205.31
      2917306.06      6933145.90      2917309.18      6933132.20
      2917313.74      6933124.10      2917425.59      6933010.71
      2917524.95      6932897.19      2917550.99      6932846.84
      2917615.23      6932678.44      2917726.34      6932622.88
      2917785.36      6932598.57      2917827.03      6932563.85
      2917827.03      6932515.24      2917821.82      6932451.00
      2917788.84      6932358.99      2917790.57      6932327.74
      2917821.82      6932312.12      2917839.18      6932287.81
      2917818.60      6932229.58      2917816.13      6932215.55
      2917815.44      6932055.77      2917813.71      6932036.49
      2917806.44      6932006.35      2917805.59      6931950.71

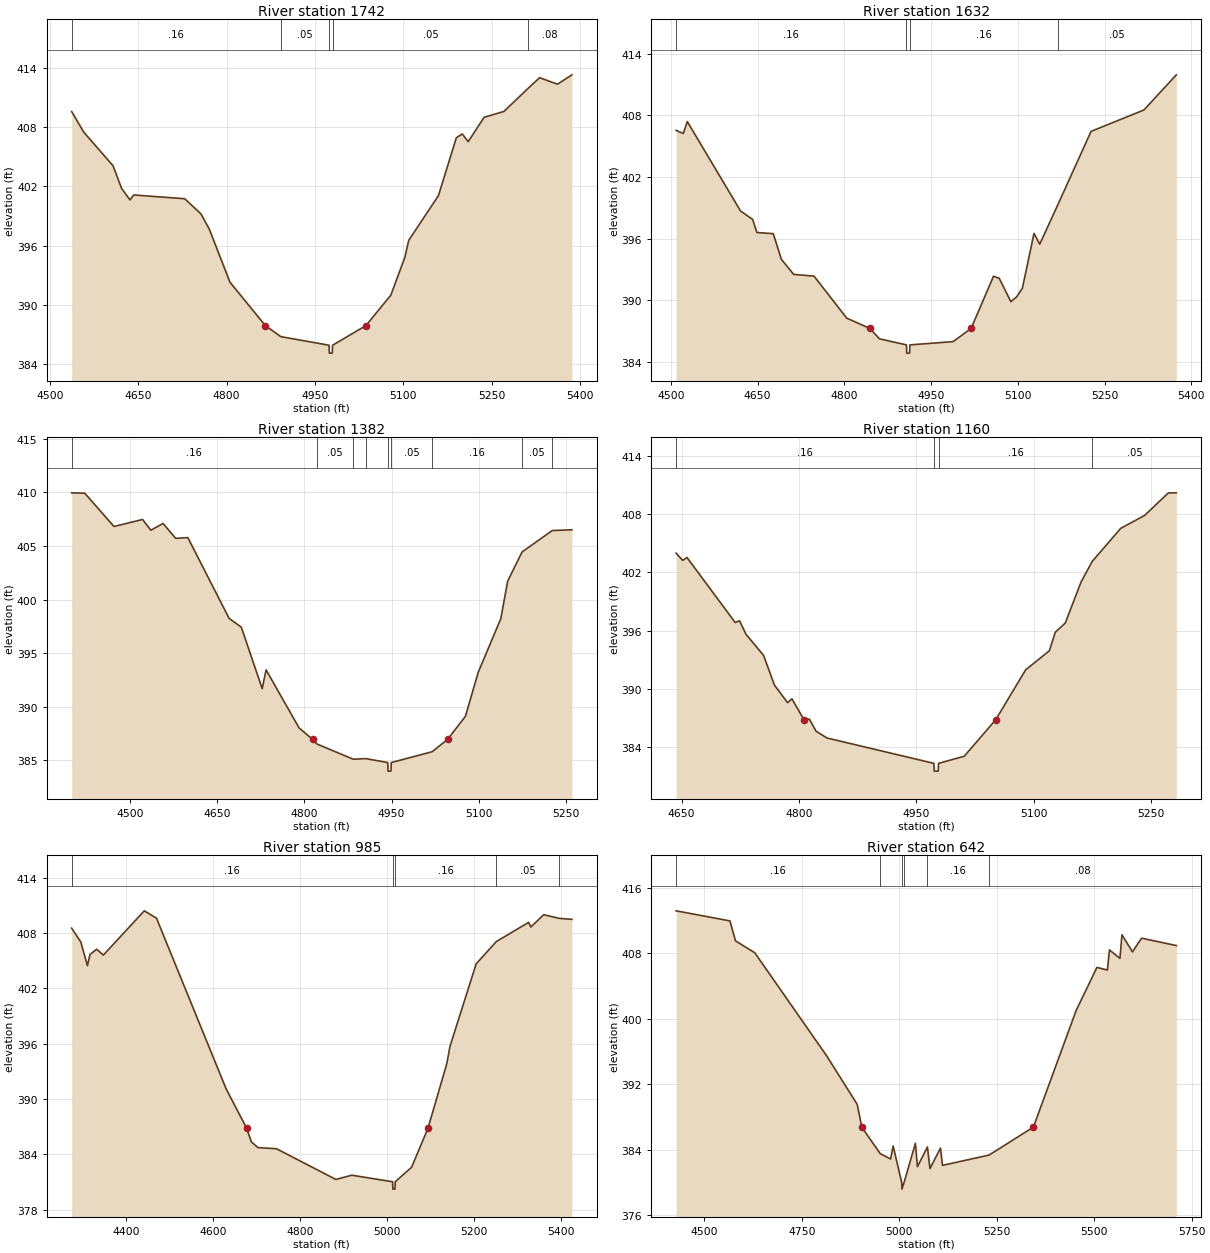
Type RM Length L Ch R = 1,1742,110,110,110
BEGIN DESCRIPTION:
UNT 093 IN DRY CR WATERSHED 3.0
END DESCRIPTION:
XS GIS Cut Line= 3
      2917595.16      6933693.69      2917233.05      6933404.69
      2916850.74      6933348.61
#Sta/Elev= 30
  4536.7  409.58  4557.4  407.48  4607.0  404.09  4621.4  401.80  4635.8  400.63
  4642.2  401.13  4728.7  400.75  4755.9  399.24  4770.3  397.70  4805.6  392.29
  4865.7  387.90  4892.0  386.78  4973.9  385.91  4974.4  385.11  4979.4  385.11
  4979.9  385.91  5036.6  387.90  5078.9  390.99  5102.7  394.82  5109.2  396.53
  5159.7  401.06  5190.1  406.93  5200.2  407.31  5210.3  406.53  5237.3  409.00
  5270.9  409.59  5312.4  411.95  5331.6  413.01  5361.9  412.35  5386.4  413.30
#Mann=5,-1,0
  4536.7    0.16       0  4892.0    0.05       0  4973.9    0.03       0
  4979.9    0.05       0  5312.4    0.08       0
Bank Sta=4865.7,5036.6
Exp/Cntr=0.3,0.1

Type RM Length L Ch R = 1,1632,250,250,250
BEGIN DESCRIPTION:
Mapping XS 7c2d27fb
END DESCRIPTION:
XS GIS Cut Line= 3
      2917632.00      6933665.43      2917280.46      6933305.21
      2916918.98      6933296.56
#Sta/Elev= 30
  4509.2  406.54  4521.6  406.24  4528.6  407.39  4620.6  398.70  4641.7  397.87
  4648.9  396.60  4677.2  396.49  4691.3  393.99  4712.5  392.53  4747.7  392.36
  4804.3  388.27  4844.0  387.28  4860.9  386.26  4907.5  385.67  4908.0  384.87
  4913.0  384.87  4913.5  385.67  4988.2  385.99  5019.4  387.28  5058.0  392.35
  5068.0  392.14  5088.0  389.88  5098.0  390.34  5108.0  391.19  5128.0  396.52
  5138.0  395.47  5169.7  399.36  5226.7  406.44  5318.1  408.52  5374.1  411.94
#Mann=4,-1,0
  4509.2    0.16       0  4907.5    0.07       0  4913.5    0.16       0
  5169.7    0.05       0
Bank Sta=4844,5019.4
Exp/Cntr=0.3,0.1

Type RM Length L Ch R = 1,1382,222,222,222
BEGIN DESCRIPTION:
Mapping XS 793e69c2
END DESCRIPTION:
XS GIS Cut Line= 3
      2917801.32      6933481.01      2917356.42      6933083.86
      2917095.99      6933040.46
#Sta/Elev= 30
  4399.8  409.96  4422.4  409.92  4472.5  406.82  4521.8  407.47  4536.0  406.47
  4557.0  407.10  4578.7  405.71  4599.6  405.78  4670.6  398.24  4691.6  397.42
  4727.5  391.68  4734.2  393.43  4791.0  388.01  4814.3  386.94  4821.8  386.51
  4884.2  385.09  4905.5  385.15  4943.5  384.78  4944.0  383.98  4949.0  383.98
  4949.5  384.78  5019.7  385.79  5046.4  386.94  5077.1  389.10  5099.0  393.19
  5137.9  398.21  5149.7  401.71  5174.5  404.44  5226.5  406.44  5260.2  406.51
#Mann=9,-1,0
  4399.8    0.16       0  4821.8    0.05       0  4884.2     0.1       0
  4905.5    0.05       0  4943.5    0.03       0  4949.5    0.05       0
  5019.7    0.16       0  5174.5    0.05       0  5226.5    0.16       0
Bank Sta=4814.3,5046.4
Exp/Cntr=0.3,0.1

Type RM Length L Ch R = 1,1160,175,175,175
BEGIN DESCRIPTION:
UNT 093 IN DRY CR WATERSHED 2.0
END DESCRIPTION:
XS GIS Cut Line= 3
      2917675.00      6933225.00      2917525.00      6932925.00
      2917224.95      6932874.99
#Sta/Elev= 30
  4643.0  403.96  4651.4  403.22  4657.0  403.51  4718.5  396.83  4724.1  397.00
  4732.4  395.61  4754.8  393.45  4768.8  390.38  4785.6  388.57  4791.1  388.97
  4806.5  386.82  4813.5  386.88  4821.9  385.64  4835.9  384.94  4972.6  382.33
  4973.1  381.53  4978.1  381.53  4978.6  382.33  5011.4  383.06  5051.7  386.82
  5089.9  391.95  5120.3  393.92  5127.9  395.83  5140.6  396.77  5160.9  401.01
  5175.2  403.13  5211.6  406.52  5242.0  407.84  5272.4  410.16  5282.6  410.17
#Mann=4,-1,0
  4643.0    0.16       0  4972.6    0.07       0  4978.6    0.16       0
  5175.2    0.05       0
Bank Sta=4806.5,5051.7
Exp/Cntr=0.3,0.1

Type RM Length L Ch R = 1,985,343,343,343
BEGIN DESCRIPTION:
Mapping XS 428e14e7
END DESCRIPTION:
XS GIS Cut Line= 3
      2918200.58      6933129.42      2917610.32      6932760.51
      2917161.06      6932836.47
#Sta/Elev= 30
  4274.1  408.51  4295.1  407.01  4310.4  404.45  4316.3  405.66  4331.7  406.23
  4347.0  405.59  4441.3  410.39  4469.4  409.59  4630.0  391.06  4677.2  386.80
  4687.8  385.34  4703.1  384.72  4745.6  384.60  4882.4  381.27  4918.9  381.73
  5013.1  381.02  5013.6  380.22  5018.6  380.22  5019.1  381.02  5056.7  382.59
  5094.3  386.80  5137.8  393.82  5145.0  395.68  5205.4  404.64  5251.6  407.05
  5326.2  409.14  5331.3  408.63  5360.9  409.97  5396.9  409.57  5425.8  409.47
#Mann=5,-1,0
  4274.1    0.16       0  5013.1    0.07       0  5019.1    0.16       0
  5251.6    0.05       0  5396.9    0.08       0
Bank Sta=4677.2,5094.3
Exp/Cntr=0.3,0.1

Type RM Length L Ch R = 1,642,69,69,69
BEGIN DESCRIPTION:
Mapping XS b55ddc35
END DESCRIPTION:
XS GIS Cut Line= 3
      2918265.68      6932918.91      2917833.85      6932554.35
      2917150.27      6932773.53
#Sta/Elev= 30
  4427.7  413.19  4565.8  411.96  4580.1  409.52  4629.5  408.07  4814.1  395.47
  4892.1  389.57  4904.1  386.77  4951.3  383.54  4977.9  382.89  4984.4  384.48
  5006.4  380.01  5006.9  379.21  5012.4  380.01  5041.5  384.80  5046.7  381.95
  5072.3  384.36  5078.9  381.72  5105.8  384.22  5111.0  382.11  5230.5  383.37
  5344.1  386.78  5453.7  401.01  5507.0  406.28  5533.9  405.96  5539.2  408.42
  5566.1  407.39  5571.3  410.27  5598.2  408.18  5621.7  409.85  5710.7  408.95
#Mann=6,-1,0
  4427.7    0.16       0  4951.3    0.08       0  5006.4    0.07       0
  5012.4    0.08       0  5072.3    0.16       0  5230.5    0.08       0
Bank Sta=4904.1,5344.1
Exp/Cntr=0.3,0.1

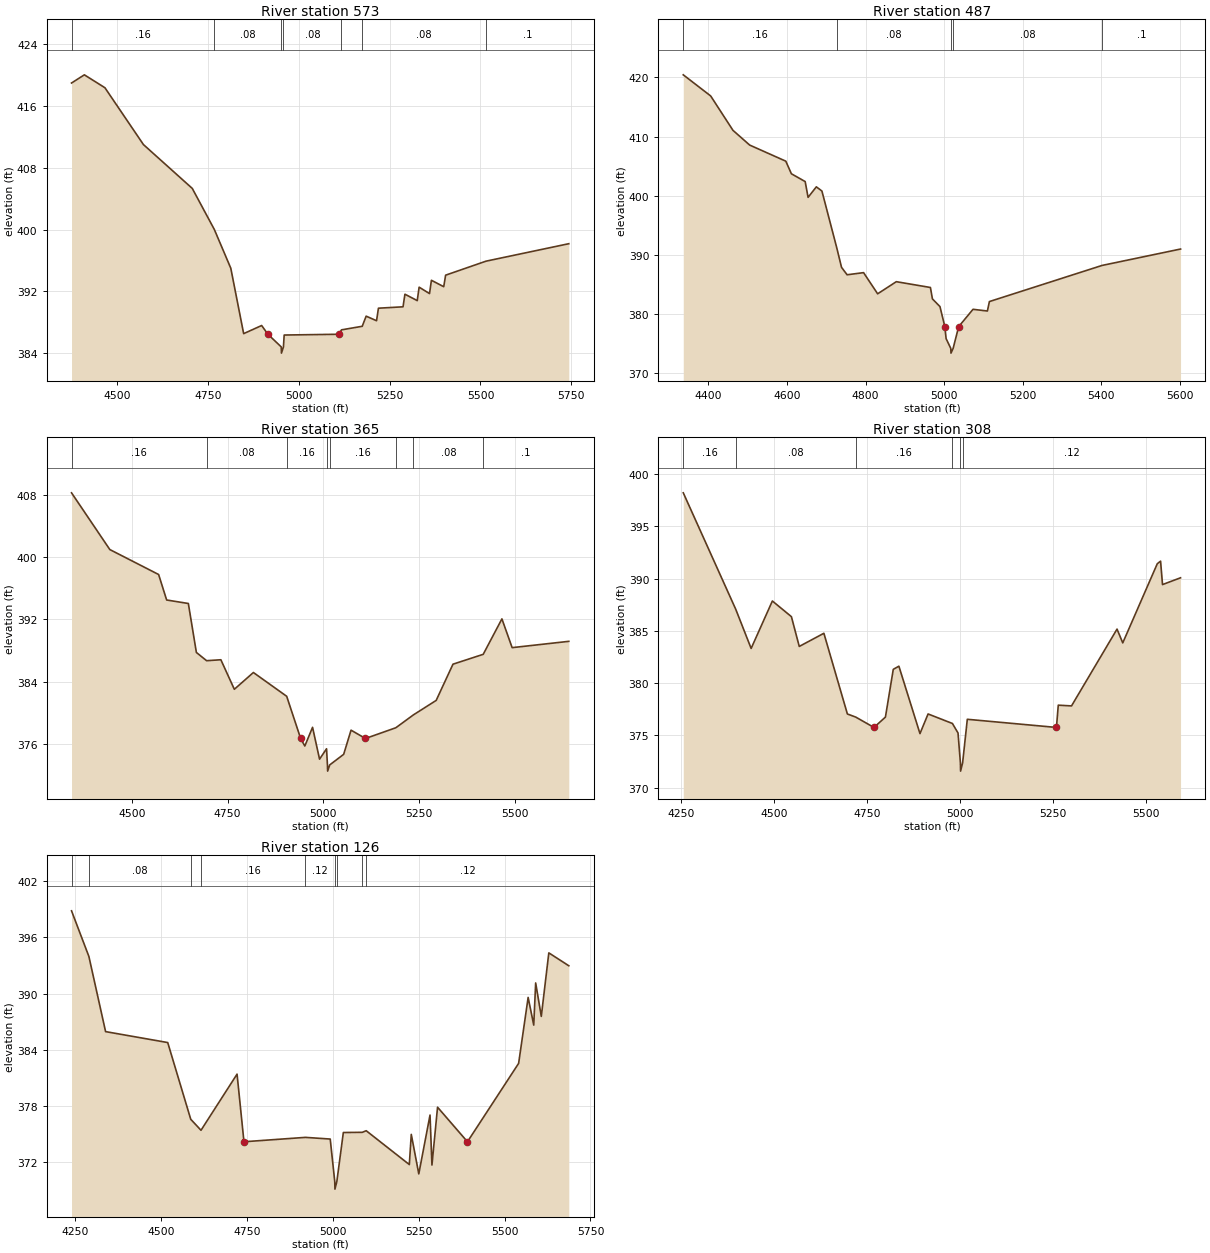
Type RM Length L Ch R = 1,573,86,86,86
BEGIN DESCRIPTION:
Mapping XS e647e8f9
END DESCRIPTION:
XS GIS Cut Line= 4
      2918285.23      6932864.67      2917901.12      6932474.05
      2917747.04      6932502.26      2917108.40      6932684.11
#Sta/Elev= 30
  4374.6  418.96  4409.9  420.02  4466.5  418.35  4572.5  411.00  4706.9  405.33
  4767.6  400.02  4812.9  395.01  4848.3  386.55  4897.8  387.60  4915.1  386.47
  4951.8  384.83  4952.3  384.03  4957.8  384.83  4959.8  386.37  5109.8  386.47
  5117.5  387.04  5174.6  387.50  5185.4  388.81  5214.0  388.22  5219.2  389.84
  5286.9  390.02  5292.1  391.65  5326.0  390.82  5331.2  392.56  5359.8  391.73
  5365.0  393.45  5398.9  392.62  5404.1  394.11  5515.1  395.92  5743.1  398.18
#Mann=7,-1,0
  4374.6    0.16       0  4767.6    0.08       0  4951.8    0.07       0
  4957.8    0.08       0  5117.5     0.1       0  5174.6    0.08       0
  5515.1     0.1       0
Bank Sta=4915.1,5109.8
Exp/Cntr=0.3,0.1

Type RM Length L Ch R = 1,487,122,122,122
BEGIN DESCRIPTION:
Mapping XS 340848fb
END DESCRIPTION:
XS GIS Cut Line= 4
      2918296.06      6932812.56      2917940.19      6932424.14
      2917799.13      6932404.61      2917219.85      6932545.63
#Sta/Elev= 30
  4336.0  420.45  4405.7  416.88  4462.5  411.06  4505.0  408.57  4596.9  405.85
  4611.1  403.72  4646.2  402.40  4653.6  399.73  4674.6  401.51  4688.8  400.80
  4726.2  391.30  4738.7  387.90  4752.9  386.64  4794.8  387.00  4830.6  383.42
  4878.1  385.47  4964.9  384.49  4970.0  382.56  4989.2  381.26  5001.6  377.87
  5004.8  375.85  5016.7  374.19  5017.2  373.39  5022.7  374.19  5036.8  377.87
  5073.3  380.80  5109.9  380.51  5115.0  382.11  5401.8  388.22  5601.4  390.99
#Mann=5,-1,0
  4336.0    0.16       0  4726.2    0.08       0  5016.7    0.07       0
  5022.7    0.08       0  5401.8     0.1       0
Bank Sta=5001.6,5036.8
Exp/Cntr=0.3,0.1

Type RM Length L Ch R = 1,365,57,57,57
BEGIN DESCRIPTION:
Mapping XS 7103861d
END DESCRIPTION:
XS GIS Cut Line= 3
      2918313.46      6932727.97      2917851.21      6932298.27
      2917215.32      6932504.44
#Sta/Elev= 30
  4342.2  408.29  4442.3  400.99  4569.8  397.78  4590.8  394.50  4647.5  394.05
  4668.5  387.75  4695.2  386.69  4732.5  386.81  4767.7  383.01  4817.5  385.17
  4904.5  382.11  4941.0  376.68  4951.9  375.71  4972.1  378.12  4990.4  374.02
  5008.7  375.36  5011.0  373.28  5011.5  372.48  5017.0  373.28  5053.4  374.64
  5072.7  377.75  5110.4  376.68  5189.7  378.06  5235.8  379.72  5295.2  381.58
  5339.1  386.24  5418.1  387.51  5467.0  392.07  5493.7  388.37  5641.8  389.18
#Mann=8,-1,0
  4342.2    0.16       0  4695.2    0.08       0  4904.5    0.16       0
  5011.0    0.07       0  5017.0    0.16       0  5189.7    0.12       0
  5235.8    0.08       0  5418.1     0.1       0
Bank Sta=4941,5110.4
Exp/Cntr=0.3,0.1

Type RM Length L Ch R = 1,308,182,182,182
BEGIN DESCRIPTION:
Mapping XS 24ea7d34
END DESCRIPTION:
XS GIS Cut Line= 4
      2918471.86      6932560.85      2917972.74      6932231.00
      2917838.19      6932252.70      2917254.44      6932402.43
#Sta/Elev= 30
  4255.7  398.20  4396.9  387.05  4438.2  383.31  4495.3  387.85  4546.5  386.35
  4567.6  383.50  4633.8  384.76  4697.0  377.04  4719.5  376.74  4768.5  375.75
  4799.3  376.74  4820.4  381.31  4835.5  381.61  4892.2  375.16  4914.0  377.04
  4979.4  376.13  4994.5  375.22  5000.9  372.37  5001.4  371.57  5006.9  372.37
  5019.5  376.53  5259.2  375.75  5264.1  377.88  5299.7  377.81  5422.1  385.16
  5437.5  383.84  5530.4  391.42  5539.2  391.66  5544.4  389.42  5592.9  390.07
#Mann=6,-1,0
  4255.7    0.16       0  4396.9    0.08       0  4719.5    0.16       0
  4979.4    0.12       0  5000.9    0.07       0  5006.9    0.12       0
Bank Sta=4768.5,5259.2
Exp/Cntr=0.3,0.1

Type RM Length L Ch R = 1,126,0,0,0
BEGIN DESCRIPTION:
UNT 093 IN DRY CR WATERSHED 1.0
END DESCRIPTION:
XS GIS Cut Line= 3
      2918452.31      6932484.89      2917822.61      6932071.49
      2917209.18      6932397.60
#Sta/Elev= 30
  4238.9  398.85  4289.5  393.96  4338.1  385.92  4519.0  384.75  4586.0  376.54
  4615.9  375.36  4720.9  381.37  4741.0  374.13  4920.0  374.60  4992.2  374.42
  5005.4  369.86  5005.9  369.06  5011.4  369.86  5030.4  375.12  5085.5  375.14
  5097.0  375.31  5222.5  371.69  5228.2  374.92  5250.1  370.69  5282.8  376.99
  5288.4  371.64  5304.7  377.83  5391.8  374.13  5540.8  382.52  5568.5  389.58
  5584.8  386.62  5590.4  391.13  5606.8  387.55  5628.7  394.35  5686.9  392.97
#Mann=9,-1,0
  4238.9    0.16       0  4289.5    0.08       0  4586.0    0.12       0
  4615.9    0.16       0  4920.0    0.12       0  5005.4    0.07       0
  5011.4    0.12       0  5085.5    0.16       0  5097.0    0.12       0
Bank Sta=4741,5391.8
Exp/Cntr=0.3,0.1

Chan Stop Cuts=-1