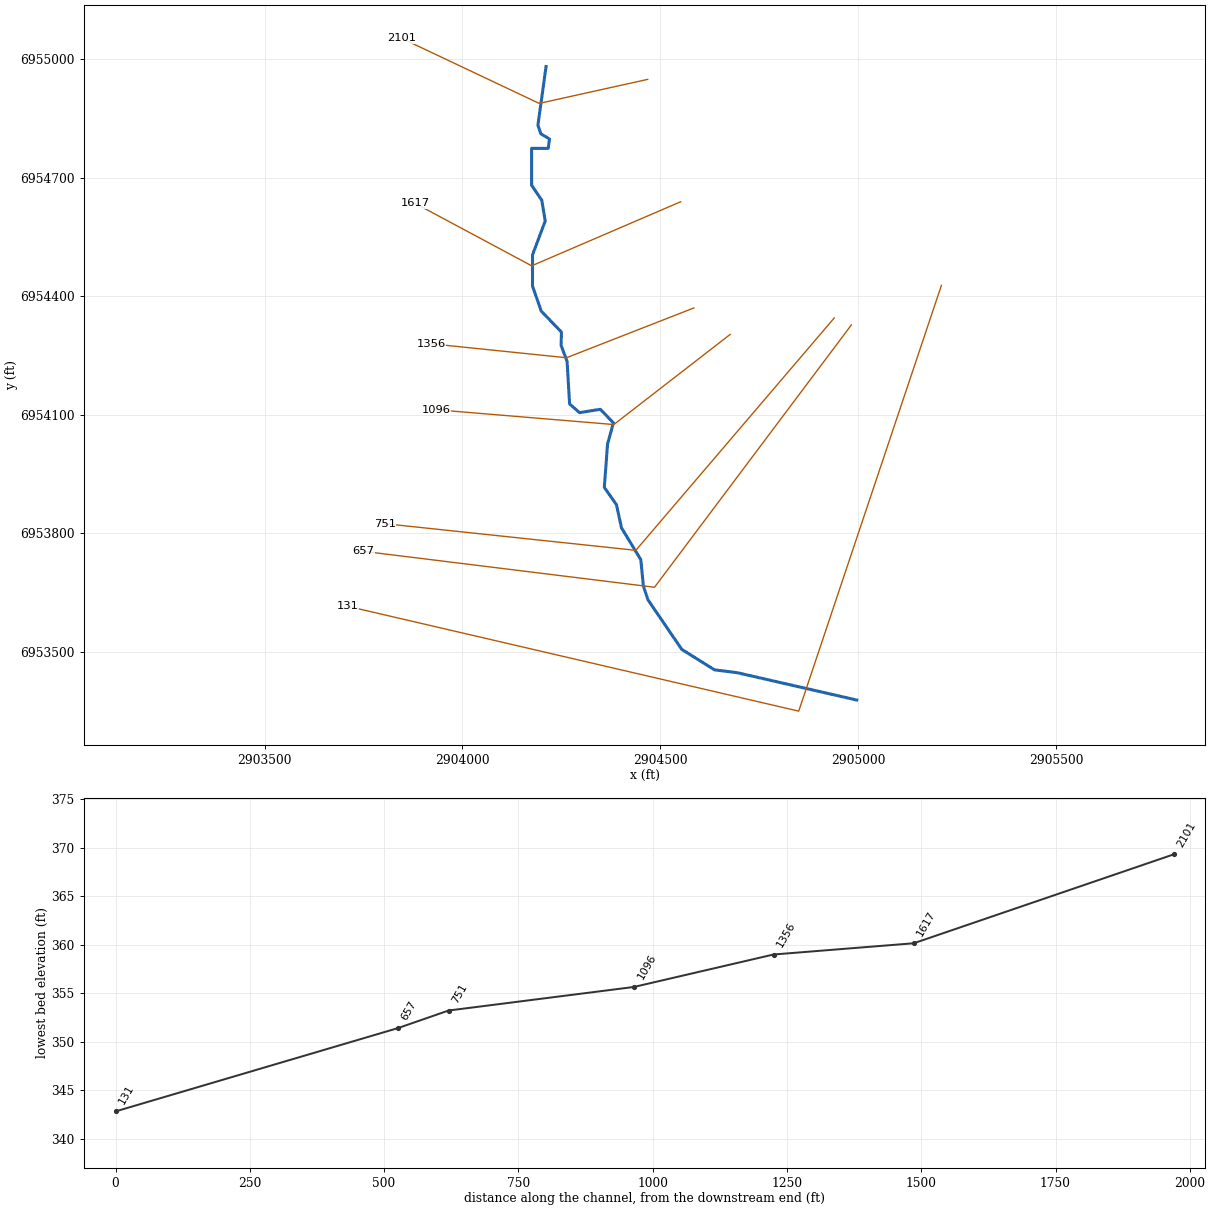
--- UNT 094 IN DRY CR WATERSHED.prj (project) ---

Proj Title=UNT 094 IN DRY CR WATERSHED Base Level Engineering
Current Plan=p01
Default Exp/Contr=0.3,0.1
English Units
Geom File=g01
Flow File=f01
Plan File=p01
BEGIN DESCRIPTION:
UNT 094 IN DRY CR WATERSHED
END DESCRIPTION:

--- UNT 094 IN DRY CR WATERSHED.p01 (plan) ---

Plan Title=Multiple Run
Short Identifier=Multiple
Geom File=g01
Flow File=f01
Subcritical Flow
K Sum by GR= 0
Std Step Tol= 0.01
Critical Tol= 0.01
Num of Std Step Trials= 20
Max Error Tol= 0.3
Flow Tol Ratio= 0.001
Split Flow NTrial= 30
Split Flow Tol= 0.02
Split Flow Ratio= 0.02
Log Output Level= 0
Friction Slope Method= 1
Unsteady Friction Slope Method= 2
Unsteady Bridges Friction Slope Method= 1
Parabolic Critical Depth
Global Vel Dist=  1 , 1 , 1
Global Log Level= 0
CheckData=True
Encroach Param= -1, 0, 0, 0
BEGIN DESCRIPTION:
Multiple Run
END DESCRIPTION:

--- UNT 094 IN DRY CR WATERSHED.f01 (steady flow) ---

Flow Title=Multiple
Number of Profiles=7
Profile Names=10-year,25-year,50-year,1pct_min,100-year,1pct_plu,500-year
River Rch & RM= UNT 094 IN DRY C,Reach-1,2101
     140     171     195     111     222     442     285
Boundary for River Rch & Prof#=UNT 094 IN DRY C,Reach-1,1
Up Type=0
Dn Type=3
Dn Slope=0.005
Boundary for River Rch & Prof#=UNT 094 IN DRY C,Reach-1,2
Up Type=0
Dn Type=3
Dn Slope=0.005
Boundary for River Rch & Prof#=UNT 094 IN DRY C,Reach-1,3
Up Type=0
Dn Type=3
Dn Slope=0.005
Boundary for River Rch & Prof#=UNT 094 IN DRY C,Reach-1,4
Up Type=0
Dn Type=3
Dn Slope=0.005
Boundary for River Rch & Prof#=UNT 094 IN DRY C,Reach-1,5
Up Type=0
Dn Type=3
Dn Slope=0.005
Boundary for River Rch & Prof#=UNT 094 IN DRY C,Reach-1,6
Up Type=0
Dn Type=3
Dn Slope=0.005
Boundary for River Rch & Prof#=UNT 094 IN DRY C,Reach-1,7
Up Type=0
Dn Type=3
Dn Slope=0.005

--- UNT 094 IN DRY CR WATERSHED.g01 (geometry) ---

Geom Title=Existing Conditions

River Reach=UNT 094 IN DRY C,Reach-1
Reach XY= 30
      2904211.54      6954982.06      2904190.92      6954833.40
      2904198.52      6954811.70      2904220.22      6954798.68
      2904216.96      6954774.81      2904175.00      6954775.00
      2904175.06      6954681.42      2904200.64      6954643.78
      2904209.36      6954590.79      2904177.32      6954505.22
      2904177.27      6954426.17      2904199.32      6954362.83
      2904250.40      6954309.72      2904249.56      6954275.79
      2904264.67      6954235.42      2904271.00      6954127.63
      2904296.24      6954105.69      2904348.73      6954114.29
      2904381.71      6954079.91      2904366.90      6954026.17
      2904358.72      6953916.36      2904389.32      6953872.91
      2904402.18      6953814.02      2904450.96      6953733.50
      2904457.49      6953666.42      2904468.97      6953631.95
      2904554.43      6953506.39      2904637.18      6953454.59
      2904694.24      6953447.45      2904996.56      6953378.13

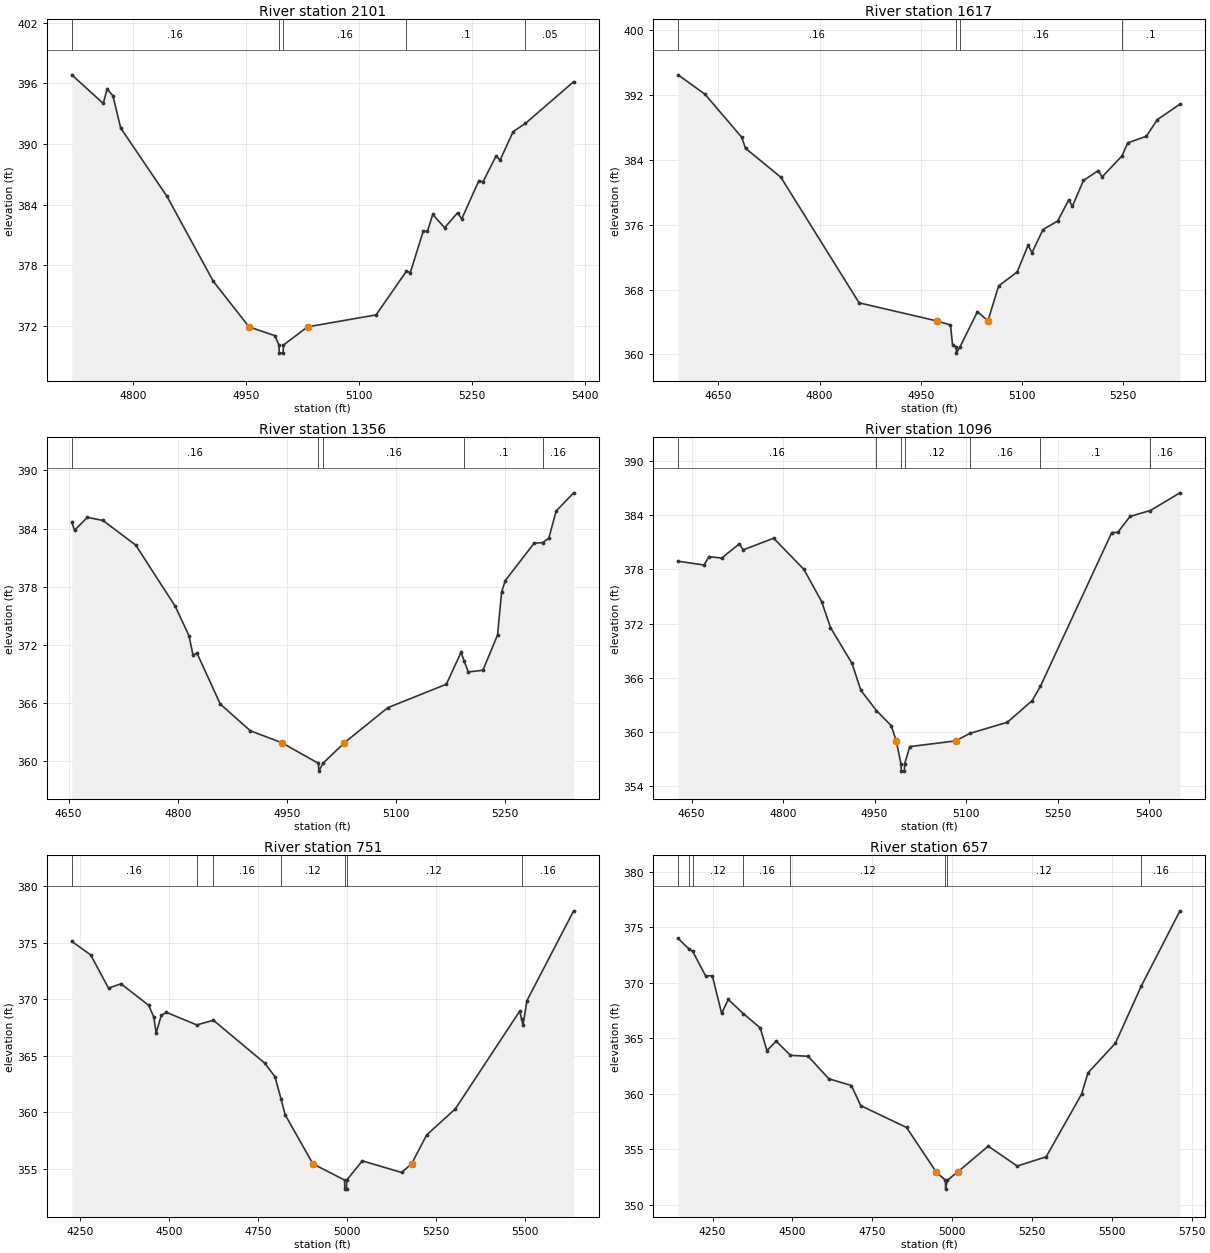
Type RM Length L Ch R = 1,2101,484,484,484
BEGIN DESCRIPTION:
UNT 094 IN DRY CR WATERSHED 6.0
END DESCRIPTION:
XS GIS Cut Line= 3
      2904468.40      6954949.61      2904194.18      6954888.74
      2903846.00      6955053.75
#Sta/Elev= 30
  4719.1  396.84  4760.9  394.01  4766.1  395.45  4773.8  394.76  4784.0  391.59
  4845.5  384.82  4907.0  376.42  4954.4  371.92  4988.9  371.04  4994.1  370.12
  4994.6  369.32  4999.6  369.32  5000.1  370.12  5032.1  371.92  5123.0  373.10
  5163.3  377.42  5168.5  377.29  5185.7  381.39  5191.2  381.38  5198.3  383.03
  5214.0  381.72  5231.2  383.20  5236.7  382.59  5259.5  386.38  5265.0  386.26
  5282.2  388.80  5287.7  388.42  5305.0  391.23  5321.2  392.03  5385.3  396.16
#Mann=5,-1,0
  4719.1    0.16       0  4994.1    0.07       0  5000.1    0.16       0
  5163.3     0.1       0  5321.2    0.05       0
Bank Sta=4954.4,5032.1
Exp/Cntr=0.3,0.1

Type RM Length L Ch R = 1,1617,261,261,261
BEGIN DESCRIPTION:
UNT 094 IN DRY CR WATERSHED 5.0
END DESCRIPTION:
XS GIS Cut Line= 3
      2904551.68      6954639.70      2904175.22      6954477.53
      2903880.26      6954635.72
#Sta/Elev= 30
  4590.1  394.51  4630.0  392.12  4684.5  386.81  4690.2  385.44  4742.7  381.86
  4858.7  366.36  4973.7  364.13  4994.3  363.62  4997.4  361.14  5002.6  360.95
  5003.1  360.15  5008.6  360.95  5034.3  365.27  5049.8  364.13  5065.7  368.44
  5093.3  370.18  5109.5  373.48  5115.2  372.55  5131.5  375.40  5153.4  376.47
  5169.6  379.04  5175.3  378.31  5191.6  381.47  5213.5  382.68  5219.2  381.90
  5248.7  384.50  5257.3  386.11  5284.9  386.93  5301.2  388.98  5334.7  390.88
#Mann=4,-1,0
  4590.1    0.16       0  5002.6    0.07       0  5008.6    0.16       0
  5248.7     0.1       0
Bank Sta=4973.7,5049.8
Exp/Cntr=0.3,0.1

Type RM Length L Ch R = 1,1356,260,260,260
BEGIN DESCRIPTION:
UNT 094 IN DRY CR WATERSHED 4.0
END DESCRIPTION:
XS GIS Cut Line= 3
      2904584.97      6954370.83      2904263.07      6954244.78
      2903920.99      6954280.11
#Sta/Elev= 30
  4654.3  384.67  4658.1  383.81  4675.7  385.15  4697.2  384.83  4742.2  382.29
  4796.5  375.98  4815.4  372.94  4820.9  370.95  4826.3  371.16  4858.3  365.91
  4899.6  363.15  4942.9  361.92  4993.3  359.79  4993.8  358.99  4999.3  359.79
  5029.0  361.92  5088.5  365.53  5169.0  367.95  5189.1  371.23  5193.4  370.36
  5199.1  369.21  5219.2  369.39  5239.3  373.02  5244.9  377.46  5250.0  378.64
  5289.6  382.49  5301.2  382.55  5309.7  382.99  5319.8  385.80  5343.9  387.68
#Mann=5,-1,0
  4654.3    0.16       0  4993.3    0.07       0  4999.3    0.16       0
  5193.4     0.1       0  5301.2    0.16       0
Bank Sta=4942.9,5029
Exp/Cntr=0.3,0.1

Type RM Length L Ch R = 1,1096,345,345,345
BEGIN DESCRIPTION:
UNT 094 IN DRY CR WATERSHED 3.0
END DESCRIPTION:
XS GIS Cut Line= 3
      2904676.70      6954303.77      2904382.73      6954075.65
      2903933.59      6954113.13
#Sta/Elev= 30
  4627.9  378.91  4670.5  378.49  4678.7  379.42  4699.5  379.26  4728.4  380.84
  4734.8  380.17  4784.6  381.46  4834.3  378.00  4863.3  374.44  4877.8  371.56
  4913.1  367.58  4927.6  364.60  4953.2  362.35  4977.4  360.68  4985.7  358.99
  4993.4  356.44  4993.9  355.64  4998.9  355.64  4999.4  356.44  5007.8  358.36
  5083.0  358.99  5106.2  359.82  5167.9  361.06  5208.4  363.45  5222.0  365.05
  5338.9  382.08  5348.9  382.11  5369.0  383.88  5402.2  384.53  5450.7  386.49
#Mann=7,-1,0
  4627.9    0.16       0  4953.2    0.12       0  4993.4    0.07       0
  4999.4    0.12       0  5106.2    0.16       0  5222.0     0.1       0
  5402.2    0.16       0
Bank Sta=4985.7,5083
Exp/Cntr=0.3,0.1

Type RM Length L Ch R = 1,751,94,94,94
BEGIN DESCRIPTION:
UNT 094 IN DRY CR WATERSHED 2.0
END DESCRIPTION:
XS GIS Cut Line= 3
      2904939.72      6954345.44      2904438.41      6953757.16
      2903804.29      6953824.60
#Sta/Elev= 30
  4227.1  375.10  4280.2  373.91  4330.4  370.97  4365.5  371.35  4443.5  369.45
  4457.8  368.40  4464.3  367.00  4478.6  368.56  4492.9  368.83  4578.4  367.72
  4625.2  368.13  4769.6  364.34  4798.2  363.14  4815.3  361.18  4826.7  359.79
  4904.7  355.45  4993.9  354.01  4994.4  353.21  4999.4  353.21  4999.9  354.01
  5043.7  355.71  5154.3  354.68  5182.1  355.45  5224.7  358.00  5305.1  360.30
  5486.1  368.94  5491.2  368.25  5495.4  367.69  5506.3  369.86  5637.7  377.80
#Mann=7,-1,0
  4227.1    0.16       0  4578.4    0.12       0  4625.2    0.16       0
  4815.3    0.12       0  4993.9    0.07       0  4999.9    0.12       0
  5491.2    0.16       0
Bank Sta=4904.7,5182.1
Exp/Cntr=0.3,0.1

Type RM Length L Ch R = 1,657,526,526,526
BEGIN DESCRIPTION:
Mapping XS bddd638b
END DESCRIPTION:
XS GIS Cut Line= 3
      2904982.98      6954327.74      2904485.59      6953663.69
      2903749.27      6953754.75
#Sta/Elev= 30
  4141.9  373.98  4175.0  373.06  4187.9  372.81  4228.4  370.59  4249.2  370.62
  4278.4  367.23  4299.2  368.48  4346.1  367.21  4399.3  365.92  4420.2  363.88
  4449.3  364.72  4494.0  363.45  4549.3  363.36  4613.9  361.34  4684.7  360.73
  4713.9  358.92  4857.5  356.95  4950.4  352.94  4979.2  352.20  4979.7  351.40
  4985.2  352.20  5017.4  352.94  5113.2  355.27  5203.9  353.48  5294.6  354.31
  5405.4  359.95  5425.5  361.87  5511.5  364.54  5592.0  369.66  5713.5  376.46
#Mann=8,-1,0
  4141.9    0.12       0  4175.0    0.16       0  4187.9    0.12       0
  4346.1    0.16       0  4494.0    0.12       0  4979.2    0.07       0
  4985.2    0.12       0  5592.0    0.16       0
Bank Sta=4950.4,5017.4
Exp/Cntr=0.3,0.1

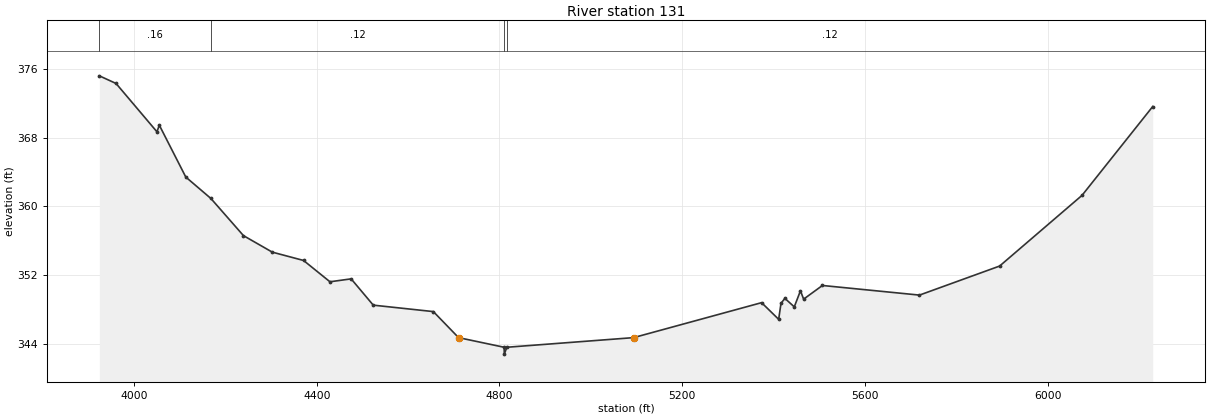
Type RM Length L Ch R = 1,131,0,0,0
BEGIN DESCRIPTION:
UNT 094 IN DRY CR WATERSHED 1.0
END DESCRIPTION:
XS GIS Cut Line= 3
      2905210.56      6954427.92      2904850.00      6953350.00
      2903710.53      6953615.40
#Sta/Elev= 30
  3923.8  375.19  3960.4  374.30  4049.9  368.68  4055.2  369.44  4113.1  363.41
  4168.0  360.92  4239.4  356.59  4302.5  354.67  4371.0  353.70  4428.8  351.22
  4475.2  351.56  4523.6  348.50  4655.2  347.75  4710.4  344.72  4810.1  343.60
  4810.6  342.80  4816.1  343.60  5093.6  344.72  5373.9  348.79  5411.3  346.85
  5416.4  348.71  5424.9  349.29  5445.5  348.30  5459.0  350.17  5466.0  349.20
  5507.1  350.79  5719.6  349.67  5895.1  353.05  6075.6  361.28  6230.4  371.62
#Mann=4,-1,0
  3923.8    0.16       0  4168.0    0.12       0  4810.1    0.07       0
  4816.1    0.12       0
Bank Sta=4710.4,5093.6
Exp/Cntr=0.3,0.1

Chan Stop Cuts=-1