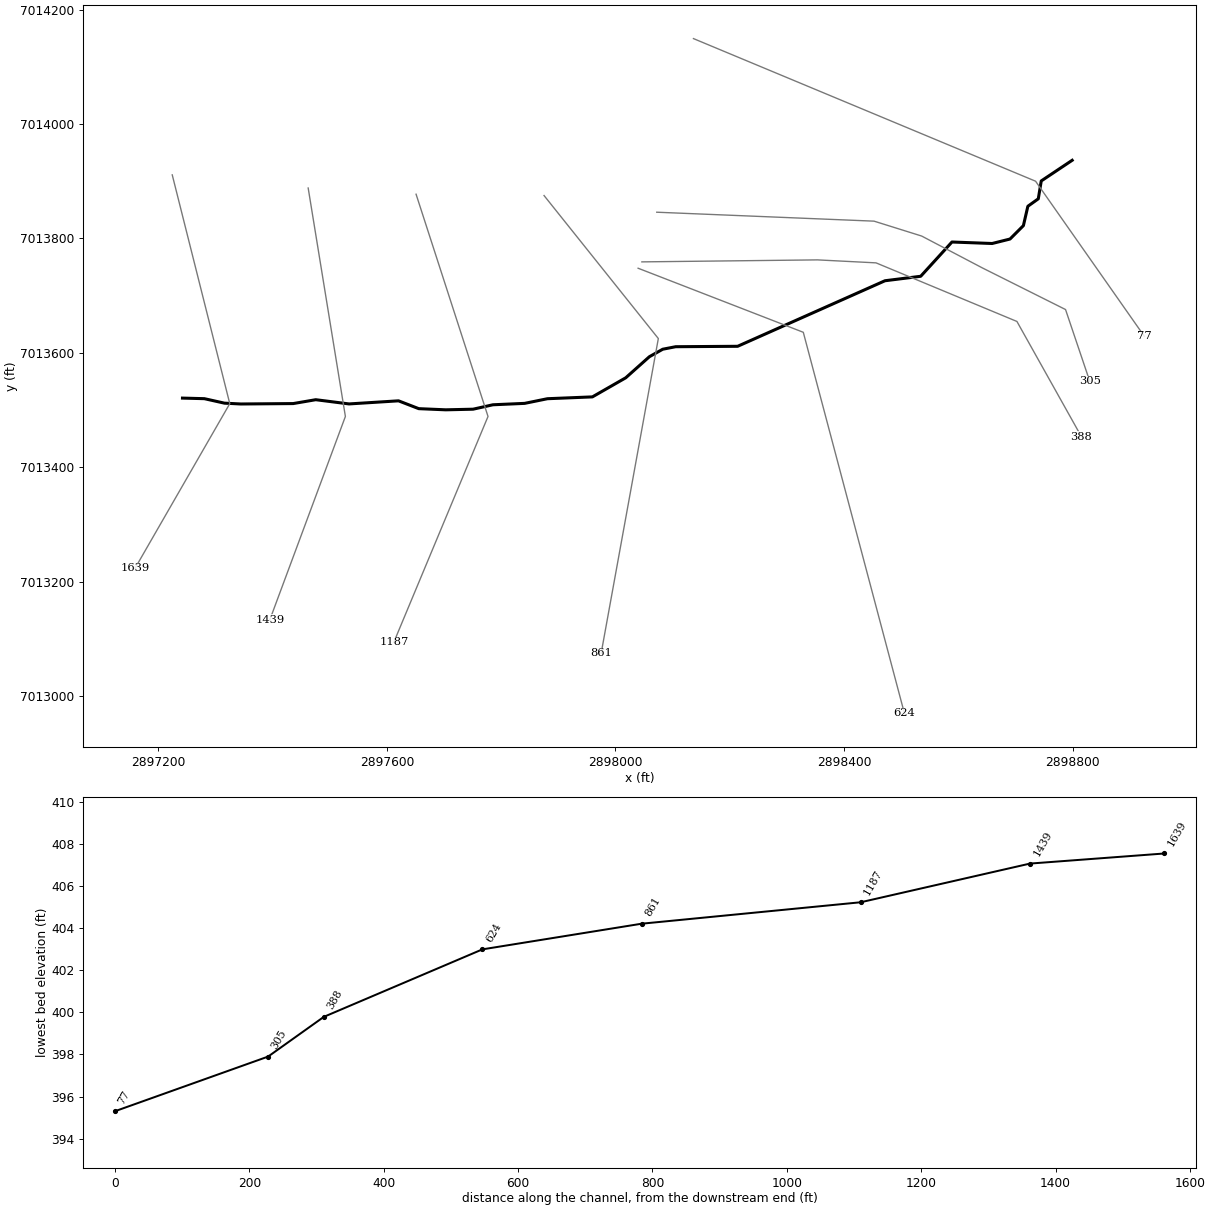
--- UNT 095 IN DRY CR WATERSHED.prj (project) ---

Proj Title=UNT 095 IN DRY CR WATERSHED Base Level Engineering
Current Plan=p01
Default Exp/Contr=0.3,0.1
English Units
Geom File=g01
Flow File=f01
Plan File=p01
BEGIN DESCRIPTION:
UNT 095 IN DRY CR WATERSHED
END DESCRIPTION:

--- UNT 095 IN DRY CR WATERSHED.p01 (plan) ---

Plan Title=Multiple Run
Short Identifier=Multiple
Geom File=g01
Flow File=f01
Subcritical Flow
K Sum by GR= 0
Std Step Tol= 0.01
Critical Tol= 0.01
Num of Std Step Trials= 20
Max Error Tol= 0.3
Flow Tol Ratio= 0.001
Split Flow NTrial= 30
Split Flow Tol= 0.02
Split Flow Ratio= 0.02
Log Output Level= 0
Friction Slope Method= 1
Unsteady Friction Slope Method= 2
Unsteady Bridges Friction Slope Method= 1
Parabolic Critical Depth
Global Vel Dist=  1 , 1 , 1
Global Log Level= 0
CheckData=True
Encroach Param= -1, 0, 0, 0
BEGIN DESCRIPTION:
Multiple Run
END DESCRIPTION:

--- UNT 095 IN DRY CR WATERSHED.f01 (steady flow) ---

Flow Title=Multiple
Number of Profiles=7
Profile Names=10-year,25-year,50-year,1pct_min,100-year,1pct_plu,500-year
River Rch & RM= UNT 095 IN DRY C,Reach-1,1639
     419     550     655     388     774    1544    1082
Boundary for River Rch & Prof#=UNT 095 IN DRY C,Reach-1,1
Up Type=0
Dn Type=3
Dn Slope=0.005
Boundary for River Rch & Prof#=UNT 095 IN DRY C,Reach-1,2
Up Type=0
Dn Type=3
Dn Slope=0.005
Boundary for River Rch & Prof#=UNT 095 IN DRY C,Reach-1,3
Up Type=0
Dn Type=3
Dn Slope=0.005
Boundary for River Rch & Prof#=UNT 095 IN DRY C,Reach-1,4
Up Type=0
Dn Type=3
Dn Slope=0.005
Boundary for River Rch & Prof#=UNT 095 IN DRY C,Reach-1,5
Up Type=0
Dn Type=3
Dn Slope=0.005
Boundary for River Rch & Prof#=UNT 095 IN DRY C,Reach-1,6
Up Type=0
Dn Type=3
Dn Slope=0.005
Boundary for River Rch & Prof#=UNT 095 IN DRY C,Reach-1,7
Up Type=0
Dn Type=3
Dn Slope=0.005

--- UNT 095 IN DRY CR WATERSHED.g01 (geometry) ---

Geom Title=Existing Conditions

River Reach=UNT 095 IN DRY C,Reach-1
Reach XY= 30
      2897242.40      7013520.89      2897280.72      7013519.88
      2897315.83      7013512.05      2897344.27      7013510.60
      2897436.09      7013511.32      2897475.59      7013518.08
      2897533.84      7013510.69      2897620.38      7013516.12
      2897655.81      7013502.43      2897703.13      7013500.40
      2897750.83      7013501.49      2897785.61      7013509.22
      2897841.07      7013511.67      2897880.96      7013519.81
      2897959.64      7013523.01      2898017.95      7013556.38
      2898059.28      7013593.18      2898082.69      7013606.32
      2898105.37      7013610.71      2898213.76      7013611.44
      2898471.58      7013726.02      2898534.08      7013733.83
      2898588.76      7013793.73      2898659.08      7013791.13
      2898690.33      7013798.94      2898713.76      7013822.38
      2898721.58      7013856.23      2898739.81      7013869.25
      2898745.01      7013900.50      2898799.11      7013936.58

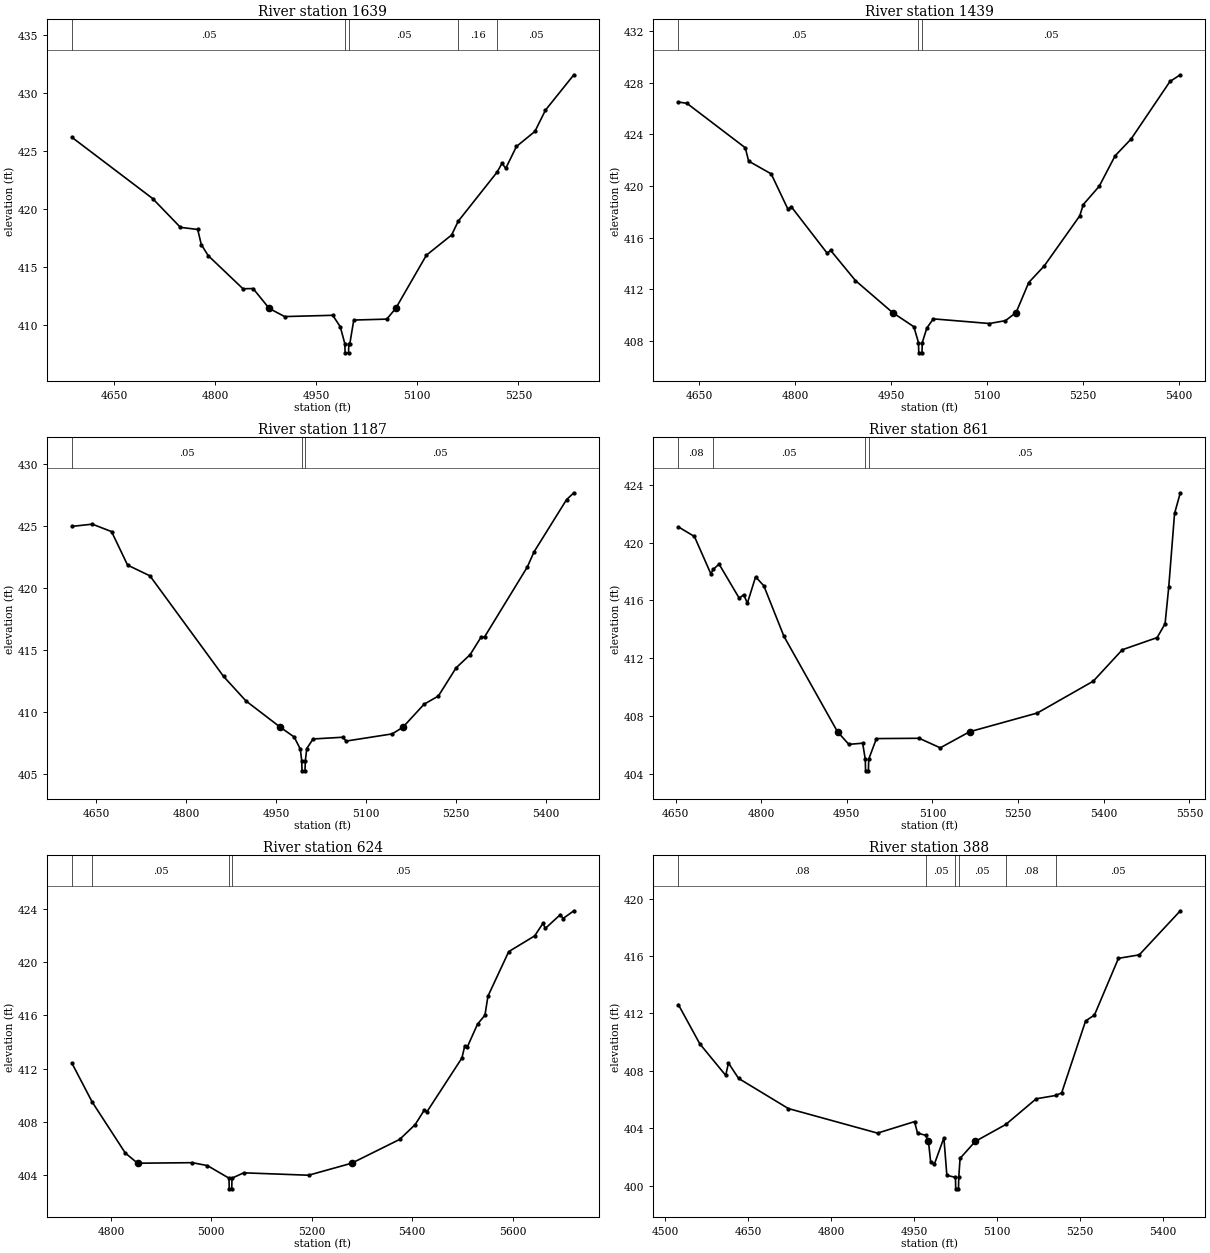
Type RM Length L Ch R = 1,1639,200,200,200
BEGIN DESCRIPTION:
UNT 095 IN DRY CR WATERSHED 3.0
END DESCRIPTION:
XS GIS Cut Line= 3
      2897224.48      7013911.11      2897325.15      7013511.18
      2897159.25      7013223.14
#Sta/Elev= 30
  4587.6  426.16  4707.3  420.88  4748.6  418.39  4774.2  418.21  4779.5  416.91
  4789.8  415.95  4841.4  413.09  4856.4  413.11  4880.4  411.39  4903.3  410.69
  4974.6  410.80  4985.8  409.81  4992.5  408.36  4993.0  407.56  4998.0  407.56
  4998.5  408.36  5000.0  408.36  5005.8  410.39  5054.7  410.47  5068.0  411.39
  5113.6  415.99  5151.0  417.73  5160.8  418.92  5218.4  423.15  5225.7  423.91
  5231.4  423.49  5247.2  425.37  5274.6  426.67  5290.3  428.51  5332.4  431.56
#Mann=5,-1,0
  4587.6    0.05       0  4992.5    0.03       0  4998.5    0.05       0
  5160.8    0.16       0  5218.4    0.05       0
Bank Sta=4880.4,5068
Exp/Cntr=0.3,0.1

Type RM Length L Ch R = 1,1439,252,252,252
BEGIN DESCRIPTION:
Mapping XS 1c2dafb0
END DESCRIPTION:
XS GIS Cut Line= 3
      2897462.33      7013888.12      2897527.44      7013488.79
      2897395.07      7013132.92
#Sta/Elev= 30
  4617.8  426.49  4631.1  426.39  4722.3  422.95  4727.5  421.92  4762.8  420.93
  4789.0  418.19  4794.0  418.40  4850.4  414.78  4855.5  415.02  4894.5  412.67
  4952.4  410.20  4985.7  409.10  4992.9  407.88  4993.4  407.08  4998.4  407.08
  4998.9  407.88  5006.0  409.00  5016.1  409.71  5103.8  409.35  5128.8  409.57
  5145.5  410.20  5165.2  412.52  5189.5  413.81  5244.9  417.68  5250.5  418.56
  5275.2  419.96  5300.2  422.33  5325.2  423.63  5385.9  428.08  5402.1  428.60
#Mann=3,-1,0
  4617.8    0.05       0  4992.9    0.03       0  4998.9    0.05       0
Bank Sta=4952.4,5145.5
Exp/Cntr=0.3,0.1

Type RM Length L Ch R = 1,1187,326,326,326
BEGIN DESCRIPTION:
Mapping XS a0786c91
END DESCRIPTION:
XS GIS Cut Line= 3
      2897651.12      7013877.28      2897777.00      7013488.79
      2897612.07      7013093.82
#Sta/Elev= 30
  4609.6  424.95  4643.6  425.13  4675.6  424.53  4702.3  421.83  4739.6  420.96
  4862.3  412.85  4899.5  410.88  4957.0  408.75  4979.9  407.97  4990.2  406.99
  4992.5  406.04  4993.0  405.24  4998.0  405.24  4998.5  406.04  5000.9  407.04
  5011.5  407.81  5061.1  407.95  5066.5  407.64  5143.3  408.22  5161.0  408.75
  5196.4  410.61  5220.2  411.27  5249.7  413.54  5273.2  414.61  5291.6  416.04
  5297.1  416.03  5368.5  421.68  5379.7  422.90  5433.9  427.11  5446.0  427.66
#Mann=3,-1,0
  4609.6    0.05       0  4992.5    0.03       0  4998.5    0.05       0
Bank Sta=4957,5161
Exp/Cntr=0.3,0.1

Type RM Length L Ch R = 1,861,237,237,237
BEGIN DESCRIPTION:
UNT 095 IN DRY CR WATERSHED 2.0
END DESCRIPTION:
XS GIS Cut Line= 3
      2897875.03      7013874.96      2898075.00      7013625.00
      2897975.00      7013075.03
#Sta/Elev= 30
  4655.0  421.08  4683.0  420.42  4711.8  417.84  4715.9  418.14  4726.2  418.51
  4761.4  416.16  4769.4  416.39  4775.8  415.81  4790.2  417.63  4804.6  417.01
  4839.8  413.52  4933.7  406.92  4953.5  406.05  4977.7  406.13  4982.3  405.02
  4982.8  404.22  4987.8  404.22  4988.3  405.02  5001.8  406.45  5076.7  406.47
  5113.6  405.81  5164.9  406.92  5283.8  408.22  5381.7  410.42  5432.5  412.59
  5493.5  413.43  5507.4  414.39  5513.8  416.91  5524.0  422.01  5534.1  423.44
#Mann=4,-1,0
  4655.0    0.08       0  4715.9    0.05       0  4982.3    0.03       0
  4988.3    0.05       0
Bank Sta=4933.7,5164.9
Exp/Cntr=0.3,0.1

Type RM Length L Ch R = 1,624,236,236,236
BEGIN DESCRIPTION:
Mapping XS 98c1e125
END DESCRIPTION:
XS GIS Cut Line= 3
      2898039.61      7013747.90      2898328.65      7013635.92
      2898505.64      7012969.61
#Sta/Elev= 30
  4722.4  412.41  4762.6  409.51  4828.7  405.68  4853.1  404.92  4962.2  404.96
  4992.2  404.74  5035.1  403.80  5035.6  403.00  5040.6  403.00  5041.1  403.80
  5064.4  404.20  5193.6  404.02  5279.4  404.92  5374.8  406.70  5405.8  407.81
  5424.2  408.91  5429.4  408.78  5498.9  412.80  5504.6  413.71  5509.8  413.64
  5530.0  415.34  5544.8  416.01  5550.7  417.43  5592.1  420.77  5643.8  421.95
  5660.1  422.88  5665.3  422.52  5695.1  423.55  5700.3  423.25  5721.8  423.83
#Mann=4,-1,0
  4722.4    0.08       0  4762.6    0.05       0  5035.1    0.03       0
  5041.1    0.05       0
Bank Sta=4853.1,5279.4
Exp/Cntr=0.3,0.1

Type RM Length L Ch R = 1,388,83,83,83
BEGIN DESCRIPTION:
Mapping XS b87ba6f6
END DESCRIPTION:
XS GIS Cut Line= 5
      2898046.21      7013759.01      2898353.48      7013762.49
      2898455.91      7013757.28      2898702.44      7013654.85
      2898815.30      7013453.43
#Sta/Elev= 30
  4523.6  412.61  4562.4  409.88  4609.1  407.69  4614.1  408.55  4632.4  407.48
  4722.4  405.38  4883.7  403.67  4950.6  404.47  4956.0  403.67  4970.6  403.52
  4975.8  403.09  4979.8  401.66  4986.6  401.52  5003.7  403.34  5009.1  400.73
  5024.6  400.59  5025.1  399.79  5030.1  399.79  5030.6  400.59  5033.0  401.91
  5060.4  403.09  5115.6  404.27  5170.7  406.06  5205.8  406.29  5216.7  406.47
  5260.0  411.48  5276.0  411.89  5319.4  415.84  5357.0  416.08  5431.3  419.15
#Mann=6,-1,0
  4523.6    0.08       0  4970.6    0.05       0  5024.6    0.03       0
  5030.6    0.05       0  5115.6    0.08       0  5205.8    0.05       0
Bank Sta=4975.8,5060.4
Exp/Cntr=0.3,0.1

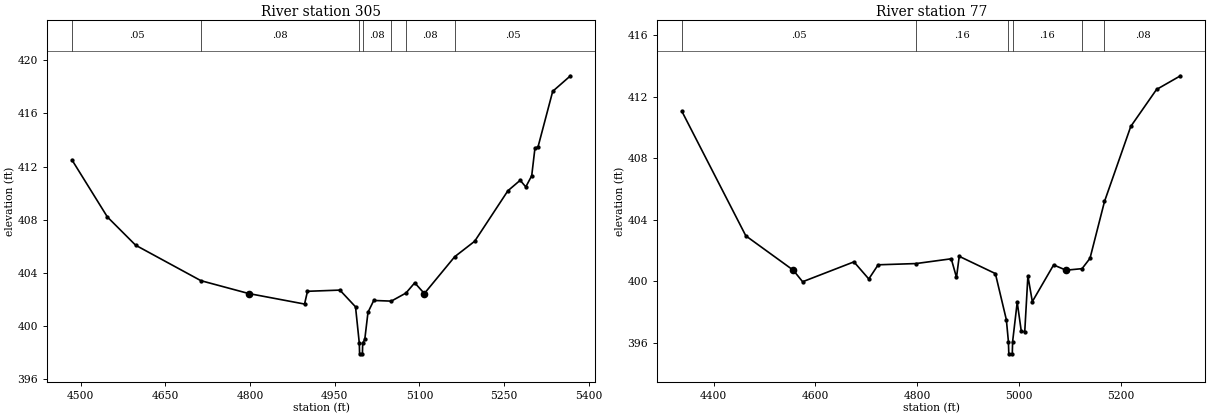
Type RM Length L Ch R = 1,305,228,228,228
BEGIN DESCRIPTION:
Mapping XS fbf7df6e
END DESCRIPTION:
XS GIS Cut Line= 6
      2898072.23      7013845.82      2898452.44      7013830.19
      2898535.77      7013804.15      2898641.67      7013748.60
      2898787.51      7013675.68      2898829.99      7013549.94
#Sta/Elev= 30
  4484.4  412.51  4547.2  408.21  4597.3  406.08  4712.9  403.41  4797.7  402.44
  4896.5  401.65  4901.7  402.61  4959.1  402.70  4986.8  401.44  4993.5  398.70
  4994.0  397.90  4999.0  397.90  4999.5  398.70  5003.2  398.99  5008.9  401.03
  5019.1  401.92  5050.2  401.87  5076.2  402.48  5091.7  403.25  5108.7  402.44
  5162.4  405.21  5197.9  406.38  5256.7  410.18  5278.5  410.97  5288.4  410.47
  5298.9  411.31  5304.7  413.41  5310.0  413.47  5336.1  417.67  5367.6  418.84
#Mann=7,-1,0
  4484.4    0.05       0  4712.9    0.08       0  4993.5    0.07       0
  4999.5    0.08       0  5050.2    0.16       0  5076.2    0.08       0
  5162.4    0.05       0
Bank Sta=4797.7,5108.7
Exp/Cntr=0.3,0.1

Type RM Length L Ch R = 1,77,0,0,0
BEGIN DESCRIPTION:
UNT 095 IN DRY CR WATERSHED 1.0
END DESCRIPTION:
XS GIS Cut Line= 3
      2898136.47      7014149.30      2898735.08      7013900.00
      2898925.34      7013628.95
#Sta/Elev= 30
  4337.7  411.04  4463.3  402.96  4556.5  400.73  4574.9  399.98  4675.7  401.27
  4704.9  400.16  4723.3  401.08  4797.6  401.16  4866.9  401.47  4877.2  400.26
  4882.6  401.63  4953.6  400.51  4975.2  397.51  4979.2  396.10  4980.0  395.30
  4986.8  395.30  4987.5  396.10  4996.5  398.65  5004.5  396.77  5011.3  396.73
  5017.5  400.36  5026.2  398.69  5068.0  401.07  5092.5  400.73  5123.9  400.83
  5139.5  401.50  5168.0  405.19  5219.6  410.06  5270.2  412.46  5317.3  413.35
#Mann=6,-1,0
  4337.7    0.05       0  4797.6    0.16       0  4979.2    0.07       0
  4987.5    0.16       0  5123.9    0.05       0  5168.0    0.08       0
Bank Sta=4556.5,5092.5
Exp/Cntr=0.3,0.1

Chan Stop Cuts=-1