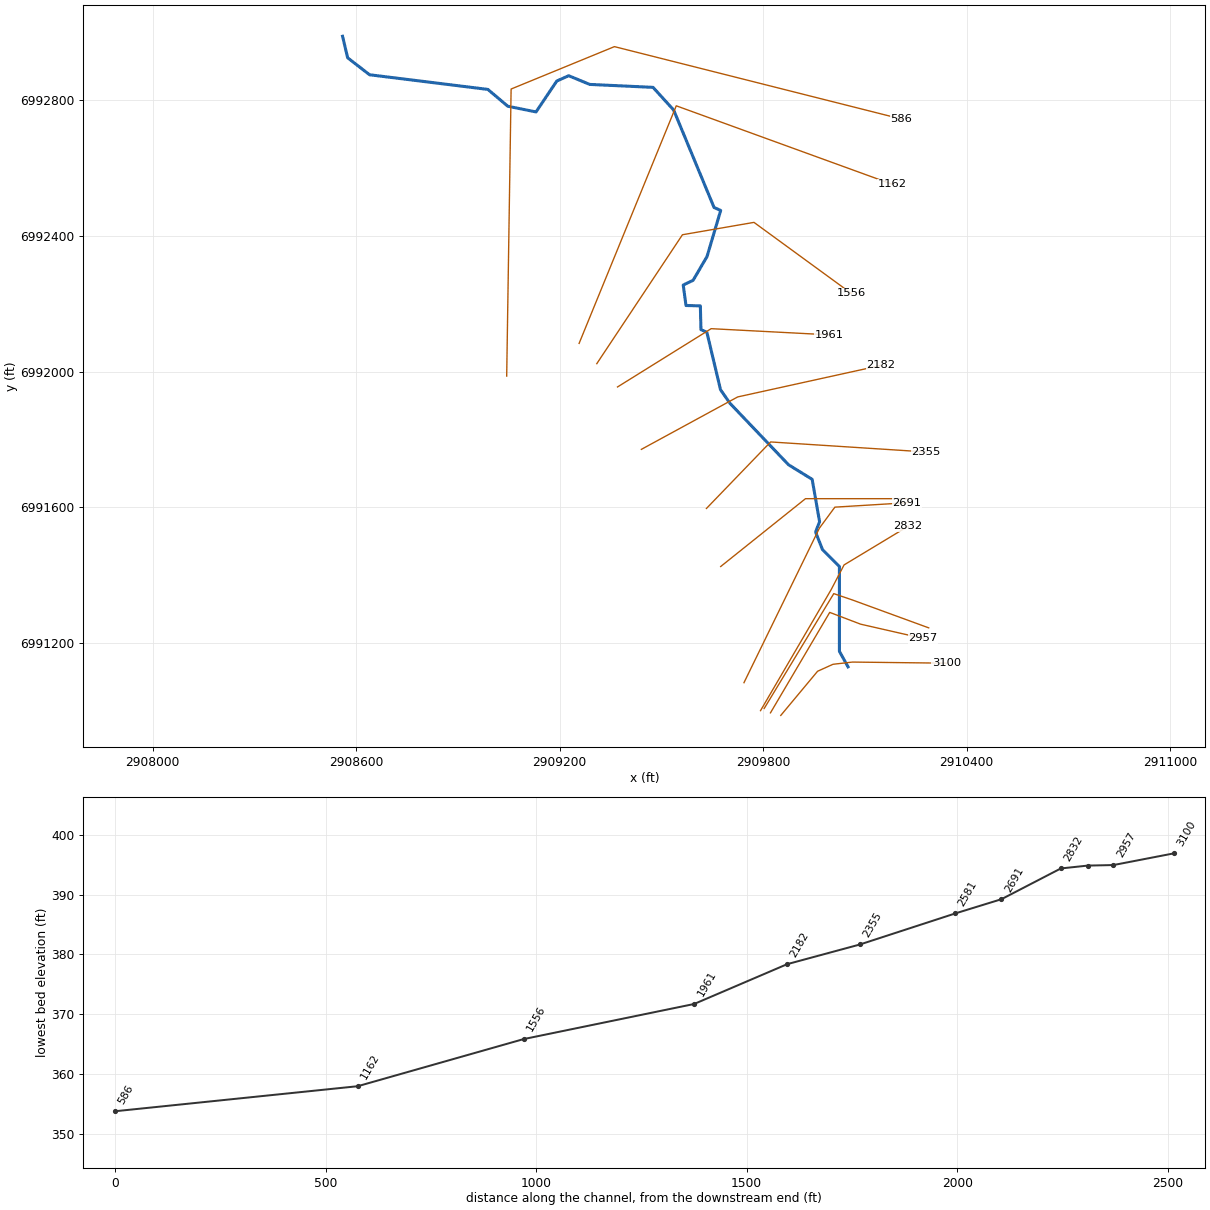
--- UNT 096 IN DRY CR WATERSHED.prj (project) ---

Proj Title=UNT 096 IN DRY CR WATERSHED Base Level Engineering
Current Plan=p01
Default Exp/Contr=0.3,0.1
English Units
Geom File=g01
Flow File=f01
Plan File=p01
BEGIN DESCRIPTION:
UNT 096 IN DRY CR WATERSHED
END DESCRIPTION:

--- UNT 096 IN DRY CR WATERSHED.p01 (plan) ---

Plan Title=Multiple Run
Short Identifier=Multiple
Geom File=g01
Flow File=f01
Subcritical Flow
K Sum by GR= 0
Std Step Tol= 0.01
Critical Tol= 0.01
Num of Std Step Trials= 20
Max Error Tol= 0.3
Flow Tol Ratio= 0.001
Split Flow NTrial= 30
Split Flow Tol= 0.02
Split Flow Ratio= 0.02
Log Output Level= 0
Friction Slope Method= 1
Unsteady Friction Slope Method= 2
Unsteady Bridges Friction Slope Method= 1
Parabolic Critical Depth
Global Vel Dist=  1 , 1 , 1
Global Log Level= 0
CheckData=True
Encroach Param= -1, 0, 0, 0
BEGIN DESCRIPTION:
Multiple Run
END DESCRIPTION:

--- UNT 096 IN DRY CR WATERSHED.f01 (steady flow) ---

Flow Title=Multiple
Number of Profiles=7
Profile Names=10-year,25-year,50-year,1pct_min,100-year,1pct_plu,500-year
River Rch & RM= UNT 096 IN DRY C,Reach-1,3100
      95     112     125      70     139     278     172
Boundary for River Rch & Prof#=UNT 096 IN DRY C,Reach-1,1
Up Type=0
Dn Type=3
Dn Slope=0.005
Boundary for River Rch & Prof#=UNT 096 IN DRY C,Reach-1,2
Up Type=0
Dn Type=3
Dn Slope=0.005
Boundary for River Rch & Prof#=UNT 096 IN DRY C,Reach-1,3
Up Type=0
Dn Type=3
Dn Slope=0.005
Boundary for River Rch & Prof#=UNT 096 IN DRY C,Reach-1,4
Up Type=0
Dn Type=3
Dn Slope=0.005
Boundary for River Rch & Prof#=UNT 096 IN DRY C,Reach-1,5
Up Type=0
Dn Type=3
Dn Slope=0.005
Boundary for River Rch & Prof#=UNT 096 IN DRY C,Reach-1,6
Up Type=0
Dn Type=3
Dn Slope=0.005
Boundary for River Rch & Prof#=UNT 096 IN DRY C,Reach-1,7
Up Type=0
Dn Type=3
Dn Slope=0.005

--- UNT 096 IN DRY CR WATERSHED.g01 (geometry) ---

Geom Title=Existing Conditions

River Reach=UNT 096 IN DRY C,Reach-1
Reach XY= 30
      2910050.33      6991129.23      2910025.00      6991175.00
      2910025.00      6991425.00      2909975.00      6991475.00
      2909954.80      6991526.68      2909966.54      6991557.07
      2909944.67      6991682.07      2909875.00      6991725.00
      2909702.05      6991906.52      2909674.44      6991946.36
      2909634.16      6992115.84      2909616.74      6992123.42
      2909615.00      6992193.56      2909572.64      6992194.60
      2909564.50      6992255.02      2909593.66      6992268.91
      2909634.63      6992339.05      2909675.00      6992475.00
      2909655.47      6992483.49      2909536.25      6992771.01
      2909475.48      6992837.85      2909288.85      6992846.53
      2909226.79      6992872.14      2909191.63      6992856.51
      2909130.43      6992765.37      2909047.10      6992782.29
      2908988.50      6992831.77      2908639.55      6992875.00
      2908575.00      6992925.00      2908559.92      6992988.49

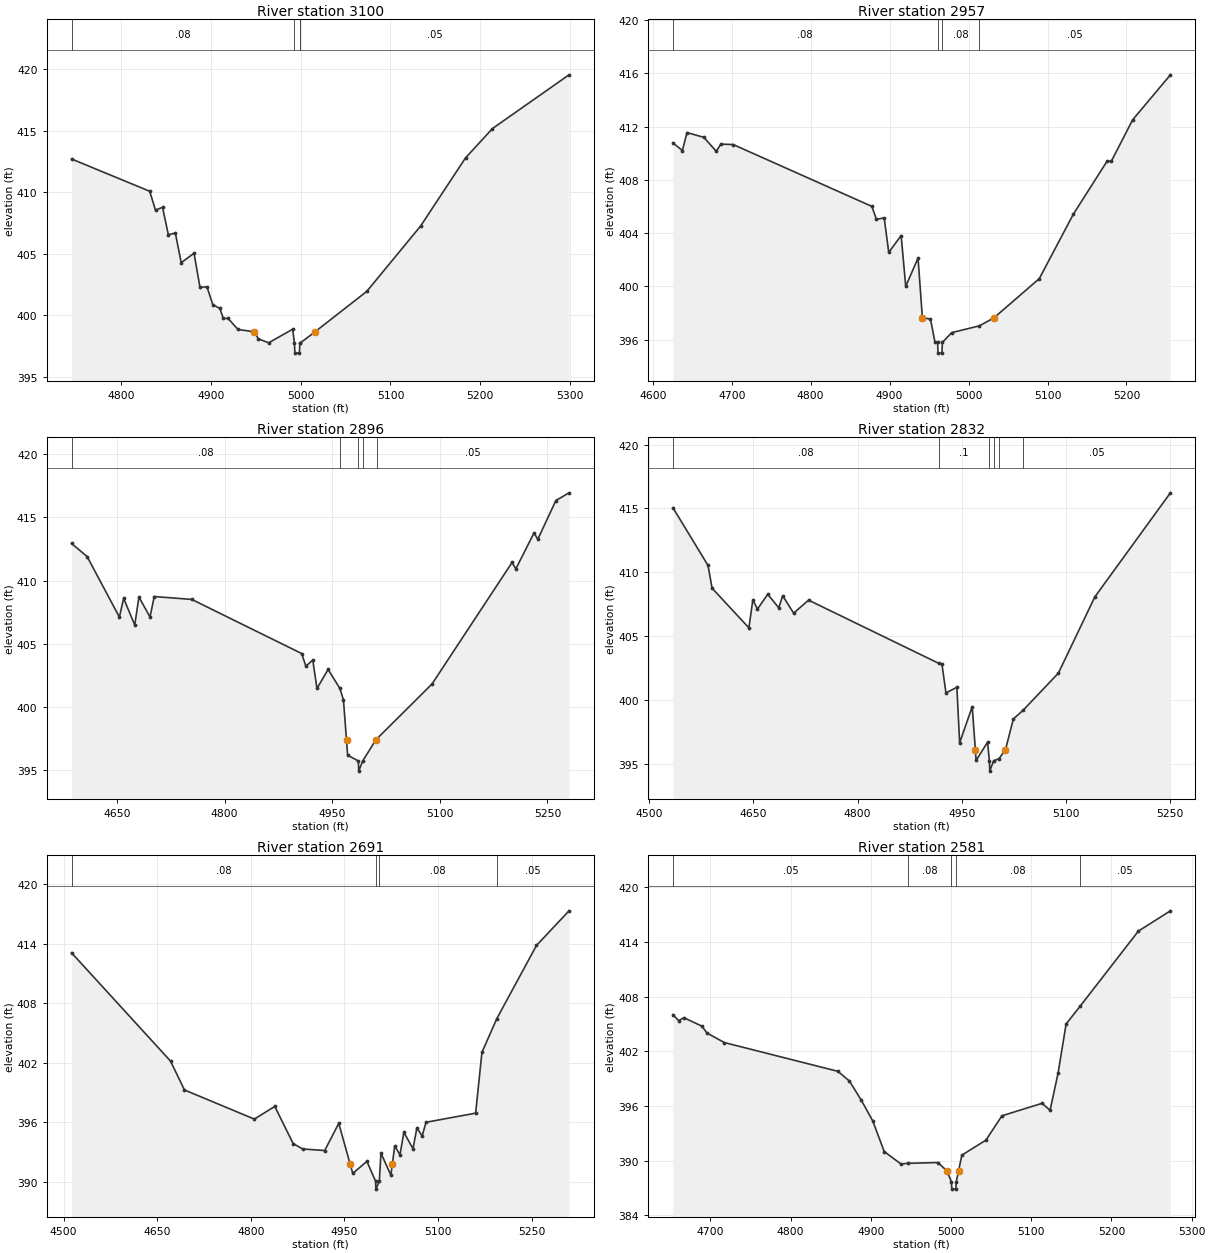
Type RM Length L Ch R = 1,3100,143,143,143
BEGIN DESCRIPTION:
UNT 096 IN DRY CR WATERSHED 4.0
END DESCRIPTION:
XS GIS Cut Line= 5
      2909852.09      6990985.85      2909960.62      6991116.08
      2910006.19      6991136.70      2910063.70      6991143.21
      2910340.17      6991139.95
#Sta/Elev= 30
  4744.9  412.69  4831.9  410.07  4838.4  408.53  4846.2  408.77  4852.7  406.54
  4860.5  406.68  4867.0  404.27  4881.3  405.04  4887.9  402.28  4895.7  402.31
  4902.2  400.86  4910.0  400.56  4913.9  399.75  4919.2  399.75  4930.2  398.85
  4948.6  398.66  4952.9  398.09  4964.4  397.77  4991.1  398.87  4993.1  397.73
  4993.6  396.93  4998.6  396.93  4999.1  397.73  4999.3  397.74  5016.0  398.66
  5073.6  401.94  5133.6  407.25  5183.6  412.78  5213.6  415.16  5298.8  419.52
#Mann=4,-1,0
  4744.9    0.08       0  4993.1    0.03       0  4999.1    0.08       0
  4999.3    0.05       0
Bank Sta=4948.6,5016
Exp/Cntr=0.3,0.1

Type RM Length L Ch R = 1,2957,61,61,61
BEGIN DESCRIPTION:
Mapping XS 07530856
END DESCRIPTION:
XS GIS Cut Line= 4
      2909821.72      6990993.45      2909996.43      6991289.69
      2910087.57      6991254.97      2910271.59      6991213.00
#Sta/Elev= 30
  4625.5  410.78  4637.5  410.21  4643.3  411.56  4664.7  411.20  4680.4  410.15
  4686.2  410.69  4701.8  410.66  4877.5  406.01  4883.3  405.03  4893.1  405.15
  4898.9  402.55  4914.6  403.82  4920.4  400.00  4936.0  402.13  4941.5  397.63
  4951.7  397.55  4957.5  395.79  4960.8  395.78  4961.3  394.98  4966.3  394.98
  4966.8  395.78  4978.6  396.52  5013.7  397.03  5032.1  397.63  5089.6  400.58
  5132.6  405.41  5175.6  409.42  5180.8  409.40  5207.9  412.52  5255.7  415.90
#Mann=4,-1,0
  4625.5    0.08       0  4960.8    0.07       0  4966.8    0.08       0
  5013.7    0.05       0
Bank Sta=4941.5,5032.1
Exp/Cntr=0.3,0.1

Type RM Length L Ch R = 1,2896,64,64,64
BEGIN DESCRIPTION:
Mapping XS ba17606f
END DESCRIPTION:
XS GIS Cut Line= 4
      2909803.28      6991006.48      2910008.36      6991345.03
      2910062.62      6991326.58      2910288.29      6991244.12
#Sta/Elev= 30
  4586.6  412.94  4608.3  411.90  4653.3  407.10  4659.2  408.59  4674.7  406.47
  4680.5  408.69  4696.0  407.11  4701.9  408.73  4754.2  408.50  4907.4  404.21
  4913.2  403.21  4922.9  403.69  4928.7  401.44  4944.2  402.95  4960.6  401.45
  4965.6  400.54  4969.9  397.33  4971.4  396.16  4986.4  395.69  4986.9  394.89
  4992.4  395.69  5010.3  397.33  5012.0  397.44  5089.1  401.80  5200.6  411.43
  5205.9  410.92  5231.2  413.77  5236.5  413.27  5261.7  416.34  5280.0  416.95
#Mann=5,-1,0
  4586.6    0.08       0  4960.6     0.1       0  4986.4    0.07       0
  4992.4     0.1       0  5012.0    0.05       0
Bank Sta=4969.9,5010.3
Exp/Cntr=0.3,0.1

Type RM Length L Ch R = 1,2832,141,141,141
BEGIN DESCRIPTION:
Mapping XS 1dae2b87
END DESCRIPTION:
XS GIS Cut Line= 4
      2909792.42      6990999.95      2910000.77      6991356.97
      2910038.74      6991429.66      2910227.55      6991543.60
#Sta/Elev= 30
  4534.3  415.05  4584.8  410.53  4590.6  408.75  4643.6  405.64  4649.3  407.83
  4655.9  407.11  4670.8  408.27  4686.5  407.21  4692.3  408.15  4708.0  406.79
  4729.5  407.81  4917.1  402.85  4921.4  402.80  4927.2  400.54  4942.9  400.98
  4946.9  396.63  4965.0  399.46  4969.5  396.08  4970.6  395.25  4987.1  396.68
  4989.7  395.21  4990.2  394.41  4995.7  395.21  5003.6  395.39  5012.8  396.08
  5024.2  398.50  5038.4  399.19  5089.0  402.09  5141.4  408.06  5250.2  416.22
#Mann=6,-1,0
  4534.3    0.08       0  4917.1     0.1       0  4989.7    0.07       0
  4995.7     0.1       0  5003.6    0.08       0  5038.4    0.05       0
Bank Sta=4969.5,5012.8
Exp/Cntr=0.3,0.1

Type RM Length L Ch R = 1,2691,110,110,110
BEGIN DESCRIPTION:
Mapping XS 18b4518b
END DESCRIPTION:
XS GIS Cut Line= 4
      2909743.60      6991082.44      2909966.04      6991538.17
      2910011.62      6991600.02      2910224.27      6991613.04
#Sta/Elev= 30
  4512.8  413.09  4671.4  402.17  4693.7  399.26  4805.7  396.32  4838.4  397.60
  4867.8  393.86  4882.9  393.31  4918.4  393.15  4940.9  395.89  4959.3  391.76
  4963.4  390.85  4986.0  392.06  4999.9  390.06  5000.4  389.26  5005.9  390.06
  5008.5  392.89  5024.4  390.68  5026.7  391.76  5030.6  393.62  5039.0  392.72
  5045.2  394.99  5059.9  393.33  5066.1  395.45  5074.5  394.61  5080.7  396.00
  5160.2  396.92  5170.3  403.05  5194.2  406.46  5257.7  413.83  5309.8  417.32
#Mann=4,-1,0
  4512.8    0.08       0  4999.9    0.07       0  5005.9    0.08       0
  5194.2    0.05       0
Bank Sta=4959.3,5026.7
Exp/Cntr=0.3,0.1

Type RM Length L Ch R = 1,2581,226,226,226
BEGIN DESCRIPTION:
UNT 096 IN DRY CR WATERSHED 3.0
END DESCRIPTION:
XS GIS Cut Line= 3
      2909674.97      6991424.98      2909925.00      6991625.00
      2910225.00      6991625.00
#Sta/Elev= 30
  4653.3  406.02  4660.5  405.36  4666.9  405.69  4689.4  404.76  4695.8  404.00
  4717.4  402.96  4859.0  399.80  4873.4  398.73  4887.9  396.67  4902.3  394.38
  4916.7  391.00  4937.5  389.63  4946.0  389.70  4983.5  389.79  4994.9  388.88
  5000.5  387.67  5001.0  386.87  5006.0  386.87  5006.5  387.67  5009.4  388.88
  5013.5  390.60  5043.5  392.25  5063.5  394.92  5113.5  396.29  5123.5  395.52
  5133.5  399.63  5143.5  405.00  5160.8  406.93  5233.5  415.19  5273.5  417.42
#Mann=5,-1,0
  4653.3    0.05       0  4946.0    0.08       0  5000.5    0.07       0
  5006.5    0.08       0  5160.8    0.05       0
Bank Sta=4994.9,5009.4
Exp/Cntr=0.3,0.1

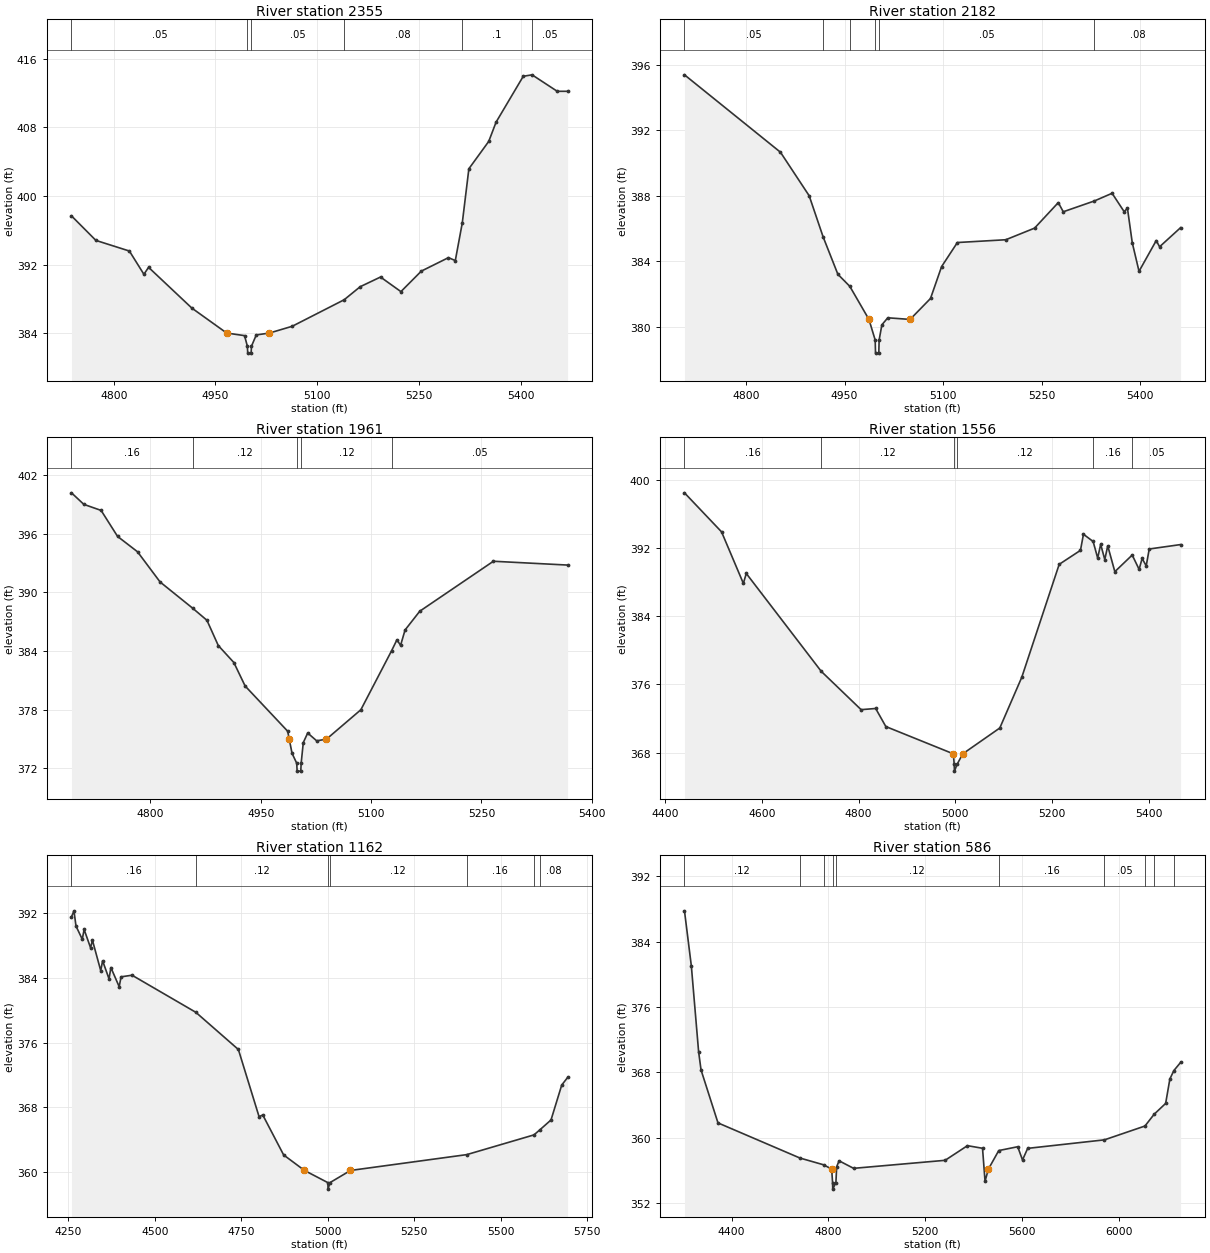
Type RM Length L Ch R = 1,2355,173,173,173
BEGIN DESCRIPTION:
Mapping XS 56a6786b
END DESCRIPTION:
XS GIS Cut Line= 3
      2909632.96      6991596.15      2909822.16      6991792.30
      2910280.29      6991762.79
#Sta/Elev= 30
  4737.7  397.68  4773.7  394.82  4823.1  393.58  4844.5  390.87  4851.4  391.68
  4915.2  386.93  4966.6  384.02  4992.9  383.72  4997.1  382.48  4997.6  381.68
  5002.6  381.68  5003.1  382.48  5010.2  383.80  5029.6  384.02  5063.2  384.81
  5139.8  387.90  5163.4  389.42  5193.4  390.55  5223.5  388.85  5253.6  391.24
  5293.6  392.81  5303.7  392.47  5314.0  396.86  5323.7  403.17  5353.0  406.36
  5363.8  408.60  5403.9  413.95  5416.9  414.12  5454.0  412.20  5469.3  412.20
#Mann=6,-1,0
  4737.7    0.05       0  4997.1    0.03       0  5003.1    0.05       0
  5139.8    0.08       0  5314.0     0.1       0  5416.9    0.05       0
Bank Sta=4966.6,5029.6
Exp/Cntr=0.3,0.1

Type RM Length L Ch R = 1,2182,221,221,221
BEGIN DESCRIPTION:
UNT 096 IN DRY CR WATERSHED 2.0
END DESCRIPTION:
XS GIS Cut Line= 3
      2909441.08      6991770.44      2909725.00      6991925.00
      2910146.84      6992017.85
#Sta/Elev= 30
  4706.3  395.39  4852.4  390.66  4896.1  388.00  4917.3  385.49  4939.8  383.20
  4958.0  382.46  4987.1  380.44  4996.6  379.18  4997.1  378.38  5002.1  378.38
  5002.6  379.18  5006.8  380.11  5015.8  380.54  5049.7  380.44  5080.8  381.72
  5097.7  383.67  5121.7  385.14  5195.4  385.31  5239.2  386.02  5275.3  387.58
  5282.9  387.02  5330.2  387.68  5357.2  388.15  5375.5  387.03  5380.6  387.23
  5387.9  385.13  5398.2  383.38  5424.4  385.26  5429.5  384.88  5461.5  386.05
#Mann=6,-1,0
  4706.3    0.05       0  4917.3    0.12       0  4958.0    0.05       0
  4996.6    0.03       0  5002.6    0.05       0  5330.2    0.08       0
Bank Sta=4987.1,5049.7
Exp/Cntr=0.3,0.1

Type RM Length L Ch R = 1,1961,405,405,405
BEGIN DESCRIPTION:
Mapping XS 31b275d7
END DESCRIPTION:
XS GIS Cut Line= 3
      2909370.75      6991954.43      2909646.82      6992126.32
      2909995.74      6992108.10
#Sta/Elev= 30
  4692.6  400.18  4709.4  399.00  4732.9  398.38  4755.3  395.72  4782.4  394.15
  4813.1  391.06  4857.5  388.37  4876.8  387.14  4892.2  384.56  4913.4  382.82
  4928.7  380.42  4986.6  375.79  4988.7  374.98  4992.5  373.54  4998.9  372.51
  4999.4  371.71  5004.4  371.71  5004.9  372.51  5007.8  374.63  5013.8  375.61
  5026.0  374.81  5039.3  374.98  5086.1  377.99  5127.9  384.03  5135.1  385.14
  5140.1  384.58  5146.2  386.15  5166.2  388.07  5266.3  393.18  5367.2  392.79
#Mann=5,-1,0
  4692.6    0.16       0  4857.5    0.12       0  4998.9    0.07       0
  5004.9    0.12       0  5127.9    0.05       0
Bank Sta=4988.7,5039.3
Exp/Cntr=0.3,0.1

Type RM Length L Ch R = 1,1556,394,394,394
BEGIN DESCRIPTION:
Mapping XS acb410c0
END DESCRIPTION:
XS GIS Cut Line= 4
      2909309.60      6992023.09      2909562.18      6992403.26
      2909773.12      6992439.72      2910060.29      6992230.16
#Sta/Elev= 30
  4439.9  398.48  4516.6  393.90  4561.7  387.85  4567.7  389.02  4722.7  377.54
  4805.2  373.04  4835.3  373.18  4856.3  371.06  4995.9  367.86  4997.7  366.63
  4998.2  365.83  5003.7  366.63  5015.4  367.86  5092.0  370.89  5137.5  376.85
  5214.8  390.09  5258.8  391.73  5265.0  393.62  5285.0  392.77  5294.4  390.83
  5300.6  392.44  5309.1  390.65  5315.2  392.26  5329.9  389.23  5365.8  391.18
  5380.1  389.50  5386.3  390.78  5394.8  389.91  5401.0  391.89  5465.9  392.41
#Mann=6,-1,0
  4439.9    0.16       0  4722.7    0.12       0  4997.7    0.07       0
  5003.7    0.12       0  5285.0    0.16       0  5365.8    0.05       0
Bank Sta=4995.9,5015.4
Exp/Cntr=0.3,0.1

Type RM Length L Ch R = 1,1162,576,576,576
BEGIN DESCRIPTION:
Mapping XS d4cf9a53
END DESCRIPTION:
XS GIS Cut Line= 3
      2909257.48      6992082.91      2909543.95      6992783.47
      2910180.96      6992552.07
#Sta/Elev= 30
  4259.0  391.47  4266.2  392.22  4272.1  390.34  4290.2  388.72  4295.6  389.92
  4314.2  387.67  4319.6  388.60  4343.6  384.85  4349.0  386.07  4367.6  383.84
  4373.0  385.23  4397.0  382.87  4402.4  384.09  4434.1  384.29  4618.6  379.72
  4741.6  375.14  4801.4  366.87  4812.2  367.07  4872.5  362.15  4932.8  360.24
  5000.4  358.74  5000.9  357.94  5006.4  358.74  5065.8  360.24  5402.0  362.19
  5596.3  364.62  5613.8  365.26  5645.6  366.46  5676.6  370.76  5693.6  371.69
#Mann=7,-1,0
  4259.0    0.16       0  4618.6    0.12       0  5000.4    0.07       0
  5006.4    0.12       0  5402.0    0.16       0  5596.3    0.05       0
  5613.8    0.08       0
Bank Sta=4932.8,5065.8
Exp/Cntr=0.3,0.1

Type RM Length L Ch R = 1,586,0,0,0
BEGIN DESCRIPTION:
UNT 096 IN DRY CR WATERSHED 1.0
END DESCRIPTION:
XS GIS Cut Line= 4
      2909043.95      6991986.64      2909056.97      6992832.95
      2909361.66      6992957.95      2910208.00      6992744.41
#Sta/Elev= 30
  4205.8  387.75  4234.2  381.01  4264.2  370.53  4274.2  368.31  4344.2  361.84
  4682.5  357.55  4780.4  356.72  4813.6  356.20  4817.3  354.55  4818.1  353.75
  4831.1  354.55  4834.2  356.48  4844.2  357.21  4904.2  356.29  5282.0  357.27
  5374.3  359.06  5436.5  358.74  5446.9  354.71  5460.8  356.20  5503.5  358.46
  5581.8  358.93  5601.6  357.31  5622.9  358.73  5939.8  359.77  6107.2  361.46
  6145.2  362.90  6192.6  364.22  6210.1  367.21  6226.7  368.24  6254.4  369.23
#Mann=10,-1,0
  4205.8    0.12       0  4682.5    0.16       0  4780.4    0.12       0
  4817.3    0.07       0  4831.1    0.12       0  5503.5    0.16       0
  5939.8    0.05       0  6107.2    0.16       0  6145.2    0.08       0
  6226.7    0.05       0
Bank Sta=4813.6,5460.8
Exp/Cntr=0.3,0.1

Chan Stop Cuts=-1