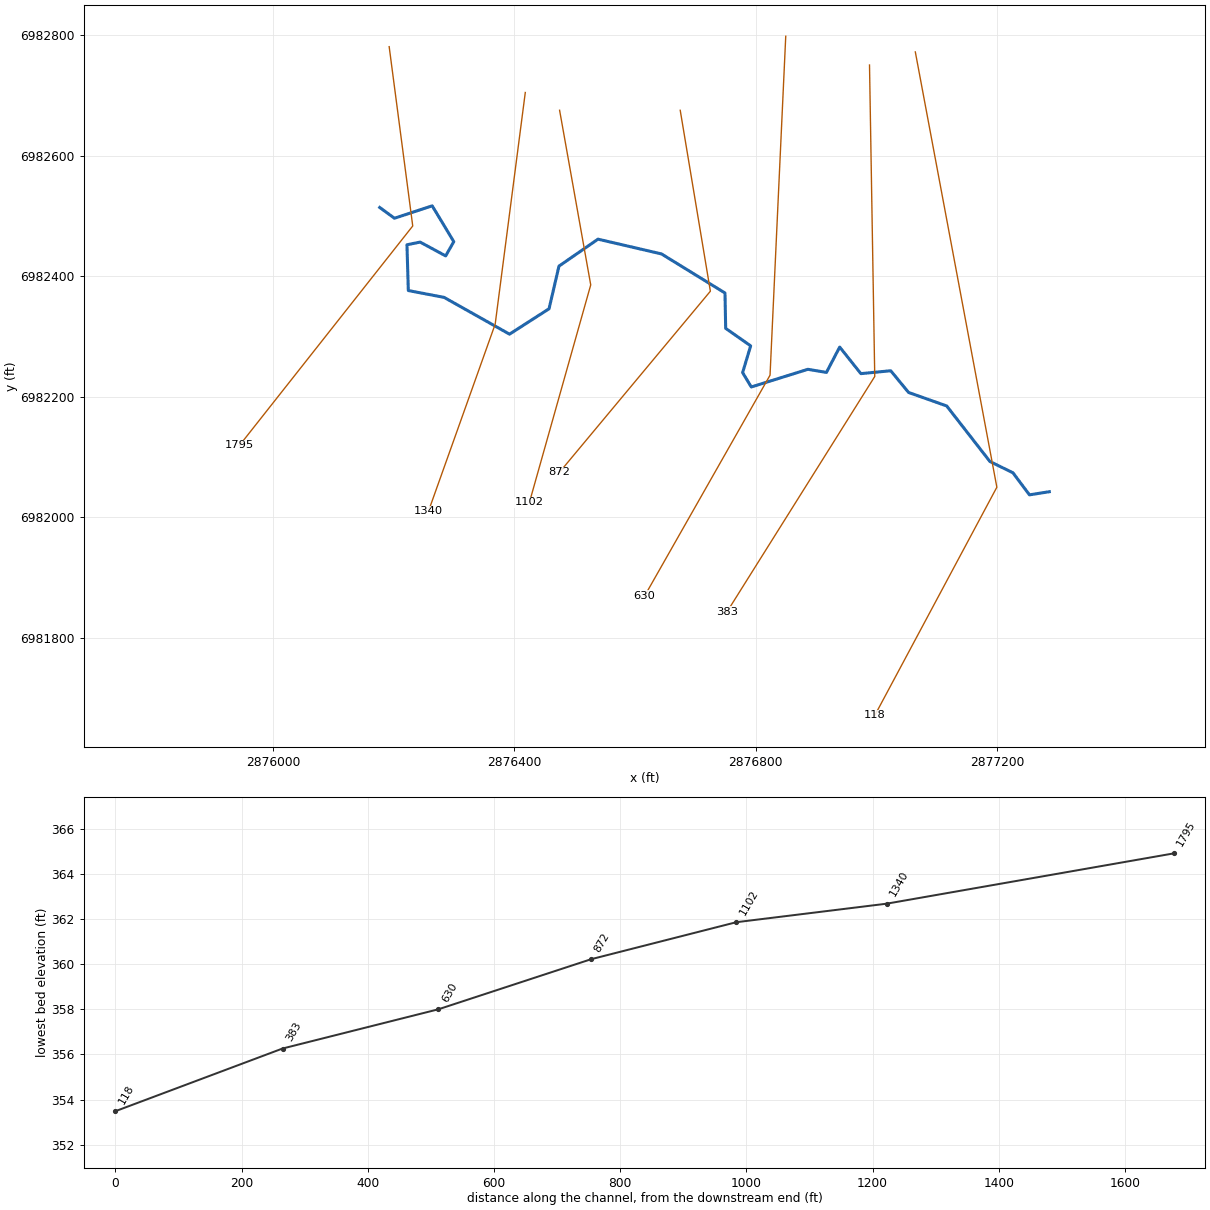
--- UNT 097 IN DRY CR WATERSHED.prj (project) ---

Proj Title=UNT 097 IN DRY CR WATERSHED Base Level Engineering
Current Plan=p01
Default Exp/Contr=0.3,0.1
English Units
Geom File=g01
Flow File=f01
Plan File=p01
BEGIN DESCRIPTION:
UNT 097 IN DRY CR WATERSHED
END DESCRIPTION:

--- UNT 097 IN DRY CR WATERSHED.p01 (plan) ---

Plan Title=Multiple Run
Short Identifier=Multiple
Geom File=g01
Flow File=f01
Subcritical Flow
K Sum by GR= 0
Std Step Tol= 0.01
Critical Tol= 0.01
Num of Std Step Trials= 20
Max Error Tol= 0.3
Flow Tol Ratio= 0.001
Split Flow NTrial= 30
Split Flow Tol= 0.02
Split Flow Ratio= 0.02
Log Output Level= 0
Friction Slope Method= 1
Unsteady Friction Slope Method= 2
Unsteady Bridges Friction Slope Method= 1
Parabolic Critical Depth
Global Vel Dist=  1 , 1 , 1
Global Log Level= 0
CheckData=True
Encroach Param= -1, 0, 0, 0
BEGIN DESCRIPTION:
Multiple Run
END DESCRIPTION:

--- UNT 097 IN DRY CR WATERSHED.f01 (steady flow) ---

Flow Title=Multiple
Number of Profiles=7
Profile Names=10-year,25-year,50-year,1pct_min,100-year,1pct_plu,500-year
River Rch & RM= UNT 097 IN DRY C,Reach-1,1795
     407     539     645     386     769    1535    1093
Boundary for River Rch & Prof#=UNT 097 IN DRY C,Reach-1,1
Up Type=0
Dn Type=3
Dn Slope=0.005
Boundary for River Rch & Prof#=UNT 097 IN DRY C,Reach-1,2
Up Type=0
Dn Type=3
Dn Slope=0.005
Boundary for River Rch & Prof#=UNT 097 IN DRY C,Reach-1,3
Up Type=0
Dn Type=3
Dn Slope=0.005
Boundary for River Rch & Prof#=UNT 097 IN DRY C,Reach-1,4
Up Type=0
Dn Type=3
Dn Slope=0.005
Boundary for River Rch & Prof#=UNT 097 IN DRY C,Reach-1,5
Up Type=0
Dn Type=3
Dn Slope=0.005
Boundary for River Rch & Prof#=UNT 097 IN DRY C,Reach-1,6
Up Type=0
Dn Type=3
Dn Slope=0.005
Boundary for River Rch & Prof#=UNT 097 IN DRY C,Reach-1,7
Up Type=0
Dn Type=3
Dn Slope=0.005

--- UNT 097 IN DRY CR WATERSHED.g01 (geometry) ---

Geom Title=Existing Conditions

River Reach=UNT 097 IN DRY C,Reach-1
Reach XY= 30
      2876176.75      6982513.83      2876201.18      6982495.99
      2876263.76      6982516.54      2876299.57      6982457.11
      2876286.07      6982433.54      2876243.74      6982456.44
      2876221.91      6982451.98      2876224.18      6982376.09
      2876283.45      6982364.77      2876391.91      6982303.77
      2876457.50      6982345.85      2876473.96      6982416.56
      2876538.69      6982461.30      2876643.95      6982436.80
      2876749.22      6982372.05      2876750.38      6982313.41
      2876791.79      6982284.39      2876778.47      6982240.06
      2876792.81      6982216.22      2876886.70      6982245.51
      2876917.43      6982240.33      2876939.42      6982282.37
      2876974.53      6982238.34      2877024.04      6982243.12
      2877053.63      6982207.11      2877116.83      6982184.73
      2877188.53      6982092.65      2877226.67      6982073.93
      2877254.06      6982037.37      2877286.97      6982042.53

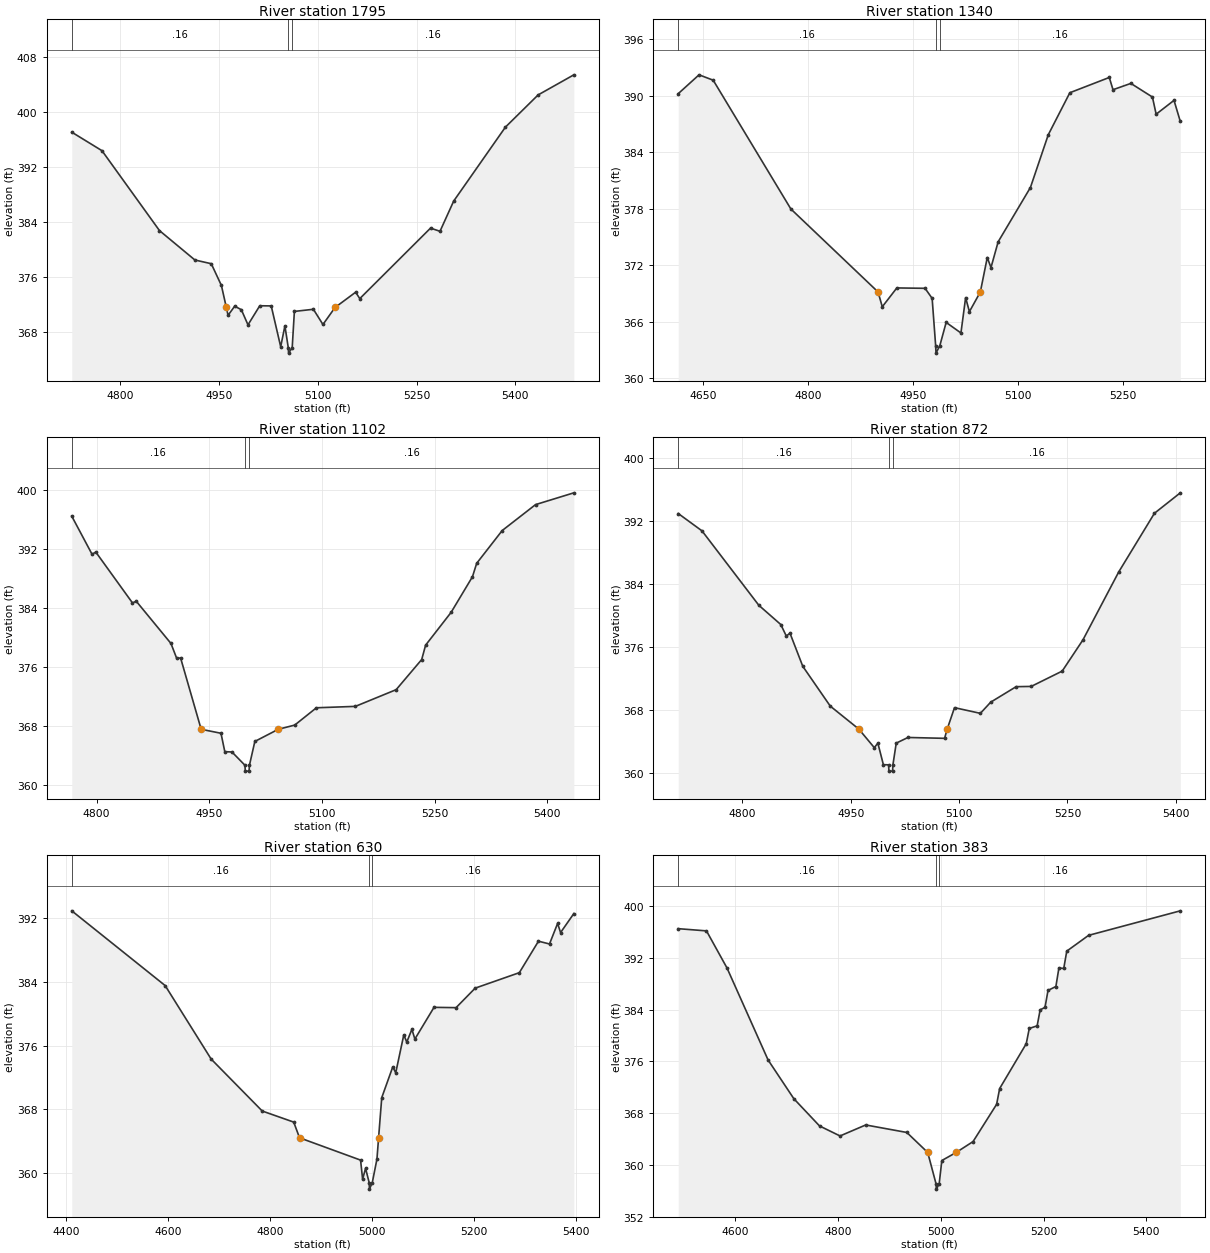
Type RM Length L Ch R = 1,1795,455,455,455
BEGIN DESCRIPTION:
UNT 097 IN DRY CR WATERSHED 4.0
END DESCRIPTION:
XS GIS Cut Line= 3
      2876192.42      6982780.48      2876231.49      6982483.14
      2875944.51      6982119.67
#Sta/Elev= 30
  4726.1  397.01  4772.0  394.32  4859.4  382.71  4913.2  378.44  4938.1  377.90
  4953.5  374.74  4961.0  371.54  4963.6  370.40  4973.7  371.73  4983.8  371.22
  4993.9  369.02  5011.8  371.79  5029.2  371.77  5043.6  365.84  5050.0  368.87
  5055.1  365.71  5055.6  364.91  5061.1  365.71  5064.4  370.97  5093.3  371.28
  5107.8  369.07  5126.2  371.54  5157.5  373.76  5163.8  372.83  5271.3  383.07
  5285.7  382.61  5306.5  387.00  5385.1  397.74  5434.8  402.42  5489.1  405.34
#Mann=3,-1,0
  4726.1    0.16       0  5055.1    0.07       0  5061.1    0.16       0
Bank Sta=4961,5126.2
Exp/Cntr=0.3,0.1

Type RM Length L Ch R = 1,1340,238,238,238
BEGIN DESCRIPTION:
Mapping XS 2db3b242
END DESCRIPTION:
XS GIS Cut Line= 3
      2876418.11      6982704.46      2876368.20      6982320.38
      2876257.52      6982010.04
#Sta/Elev= 30
  4614.5  390.22  4644.2  392.22  4664.4  391.65  4775.3  377.98  4899.8  369.17
  4905.8  367.60  4926.6  369.60  4966.9  369.56  4977.0  368.49  4982.0  363.48
  4982.5  362.68  4988.0  363.48  4997.0  365.94  5018.1  364.82  5024.8  368.57
  5030.2  367.08  5045.8  369.17  5055.7  372.83  5061.0  371.76  5071.2  374.49
  5117.3  380.26  5142.8  385.86  5173.6  390.32  5229.9  391.94  5235.2  390.64
  5260.7  391.31  5291.5  389.86  5296.8  388.04  5322.3  389.51  5331.3  387.27
#Mann=3,-1,0
  4614.5    0.16       0  4982.0    0.07       0  4988.0    0.16       0
Bank Sta=4899.8,5045.8
Exp/Cntr=0.3,0.1

Type RM Length L Ch R = 1,1102,230,230,230
BEGIN DESCRIPTION:
UNT 097 IN DRY CR WATERSHED 3.0
END DESCRIPTION:
XS GIS Cut Line= 3
      2876475.00      6982675.02      2876526.62      6982385.48
      2876425.01      6982025.03
#Sta/Elev= 30
  4766.9  396.47  4793.9  391.30  4798.9  391.60  4847.7  384.70  4852.8  384.92
  4899.0  379.19  4906.7  377.15  4911.8  377.23  4939.2  367.54  4965.6  367.00
  4970.7  364.50  4980.2  364.46  4997.5  362.66  4998.0  361.86  5003.0  361.86
  5003.5  362.66  5010.7  365.89  5041.9  367.54  5063.8  368.11  5092.7  370.46
  5144.6  370.65  5198.9  372.92  5232.9  377.01  5238.1  378.96  5272.1  383.42
  5300.5  388.25  5306.1  390.07  5340.1  394.52  5384.5  398.04  5435.5  399.64
#Mann=3,-1,0
  4766.9    0.16       0  4997.5    0.07       0  5003.5    0.16       0
Bank Sta=4939.2,5041.9
Exp/Cntr=0.3,0.1

Type RM Length L Ch R = 1,872,242,242,242
BEGIN DESCRIPTION:
UNT 097 IN DRY CR WATERSHED 2.0
END DESCRIPTION:
XS GIS Cut Line= 3
      2876675.01      6982674.96      2876725.00      6982375.00
      2876475.01      6982075.01
#Sta/Elev= 30
  4711.5  392.98  4744.4  390.77  4823.0  381.31  4853.4  378.86  4861.0  377.40
  4866.1  377.76  4883.8  373.55  4921.8  368.49  4961.3  365.57  4982.7  363.21
  4987.7  363.77  4995.3  361.04  5002.5  361.02  5003.0  360.22  5008.0  360.22
  5008.5  361.02  5013.1  363.78  5029.3  364.50  5080.0  364.39  5083.6  365.57
  5093.7  368.29  5129.5  367.57  5143.8  368.99  5179.0  370.96  5199.8  370.99
  5242.7  372.94  5271.4  376.91  5320.9  385.55  5370.3  393.01  5406.1  395.61
#Mann=3,-1,0
  4711.5    0.16       0  5002.5    0.07       0  5008.5    0.16       0
Bank Sta=4961.3,5083.6
Exp/Cntr=0.3,0.1

Type RM Length L Ch R = 1,630,247,247,247
BEGIN DESCRIPTION:
Mapping XS d31e89fb
END DESCRIPTION:
XS GIS Cut Line= 3
      2876849.97      6982797.76      2876823.93      6982235.74
      2876615.90      6981869.52
#Sta/Elev= 30
  4411.5  392.92  4594.5  383.54  4684.6  374.32  4784.7  367.80  4846.4  366.41
  4857.8  364.44  4977.4  361.64  4981.4  359.25  4987.2  360.61  4994.3  358.80
  4994.8  358.00  5000.3  358.80  5009.5  361.78  5012.7  364.44  5018.9  369.48
  5040.5  373.34  5046.3  372.60  5062.1  377.36  5067.9  376.45  5078.0  378.05
  5083.8  376.83  5121.3  380.81  5164.5  380.77  5202.0  383.22  5288.5  385.16
  5326.0  389.11  5347.6  388.76  5363.5  391.34  5369.3  390.19  5395.3  392.58
#Mann=3,-1,0
  4411.5    0.16       0  4994.3    0.07       0  5000.3    0.16       0
Bank Sta=4857.8,5012.7
Exp/Cntr=0.3,0.1

Type RM Length L Ch R = 1,383,265,265,265
BEGIN DESCRIPTION:
Mapping XS 77860d82
END DESCRIPTION:
XS GIS Cut Line= 3
      2876988.86      6982750.02      2876997.54      6982233.57
      2876752.34      6981842.98
#Sta/Elev= 30
  4488.5  396.52  4543.5  396.18  4583.5  390.44  4663.5  376.22  4713.6  370.24
  4763.6  366.03  4803.6  364.48  4853.6  366.18  4933.6  365.02  4974.3  361.93
  4990.6  357.06  4991.1  356.26  4996.6  357.06  5001.8  360.68  5029.8  361.93
  5062.6  363.61  5108.5  369.37  5114.4  371.81  5166.2  378.74  5172.1  381.10
  5187.4  381.50  5193.3  383.98  5202.7  384.35  5208.6  386.98  5223.9  387.58
  5229.8  390.45  5239.2  390.37  5245.1  393.05  5287.6  395.49  5466.2  399.28
#Mann=3,-1,0
  4488.5    0.16       0  4990.6    0.07       0  4996.6    0.16       0
Bank Sta=4974.3,5029.8
Exp/Cntr=0.3,0.1

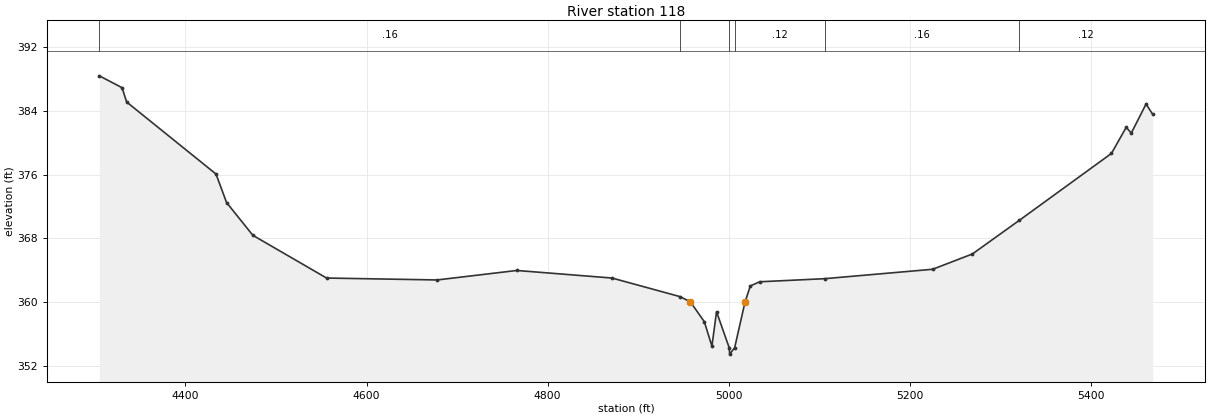
Type RM Length L Ch R = 1,118,0,0,0
BEGIN DESCRIPTION:
UNT 097 IN DRY CR WATERSHED 1.0
END DESCRIPTION:
XS GIS Cut Line= 3
      2877064.82      6982771.74      2877200.00      6982050.00
      2876997.56      6981671.53
#Sta/Elev= 30
  4304.9  388.41  4330.0  386.92  4335.1  385.12  4433.8  376.08  4445.4  372.51
  4474.5  368.39  4555.9  363.03  4678.0  362.79  4766.0  363.98  4871.2  363.03
  4946.5  360.69  4957.8  360.03  4973.1  357.55  4981.5  354.48  4986.6  358.80
  5000.6  354.28  5001.1  353.48  5006.6  354.28  5018.1  360.03  5023.9  362.03
  5034.1  362.56  5106.2  362.95  5225.3  364.13  5269.2  366.05  5321.0  370.27
  5422.8  378.67  5439.1  381.95  5444.7  381.22  5461.0  384.87  5468.4  383.57
#Mann=6,-1,0
  4304.9    0.16       0  4946.5    0.12       0  5000.6    0.07       0
  5006.6    0.12       0  5106.2    0.16       0  5321.0    0.12       0
Bank Sta=4957.8,5018.1
Exp/Cntr=0.3,0.1

Chan Stop Cuts=-1