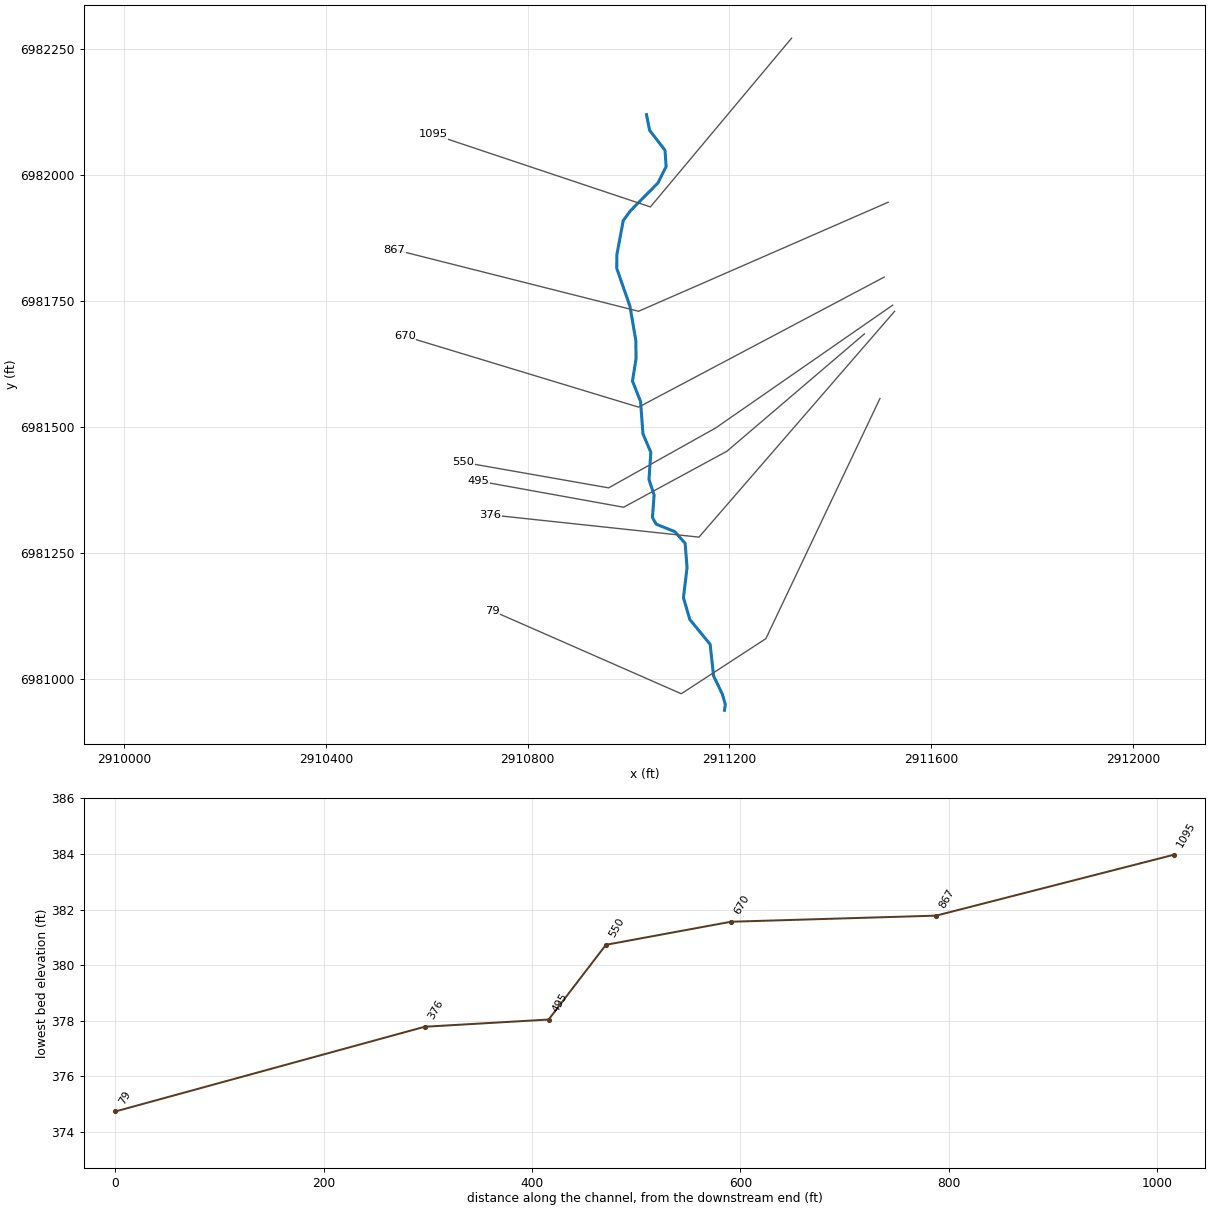
--- UNT 098 IN DRY CR WATERSHED.prj (project) ---

Proj Title=UNT 098 IN DRY CR WATERSHED Base Level Engineering
Current Plan=p01
Default Exp/Contr=0.3,0.1
English Units
Geom File=g01
Flow File=f01
Plan File=p01
BEGIN DESCRIPTION:
UNT 098 IN DRY CR WATERSHED
END DESCRIPTION:

--- UNT 098 IN DRY CR WATERSHED.p01 (plan) ---

Plan Title=Multiple Run
Short Identifier=Multiple
Geom File=g01
Flow File=f01
Subcritical Flow
K Sum by GR= 0
Std Step Tol= 0.01
Critical Tol= 0.01
Num of Std Step Trials= 20
Max Error Tol= 0.3
Flow Tol Ratio= 0.001
Split Flow NTrial= 30
Split Flow Tol= 0.02
Split Flow Ratio= 0.02
Log Output Level= 0
Friction Slope Method= 1
Unsteady Friction Slope Method= 2
Unsteady Bridges Friction Slope Method= 1
Parabolic Critical Depth
Global Vel Dist=  1 , 1 , 1
Global Log Level= 0
CheckData=True
Encroach Param= -1, 0, 0, 0
BEGIN DESCRIPTION:
Multiple Run
END DESCRIPTION:

--- UNT 098 IN DRY CR WATERSHED.f01 (steady flow) ---

Flow Title=Multiple
Number of Profiles=7
Profile Names=10-year,25-year,50-year,1pct_min,100-year,1pct_plu,500-year
River Rch & RM= UNT 098 IN DRY C,Reach-1,1095
     342     445     526     311     620    1236     859
Boundary for River Rch & Prof#=UNT 098 IN DRY C,Reach-1,1
Up Type=0
Dn Type=3
Dn Slope=0.005
Boundary for River Rch & Prof#=UNT 098 IN DRY C,Reach-1,2
Up Type=0
Dn Type=3
Dn Slope=0.005
Boundary for River Rch & Prof#=UNT 098 IN DRY C,Reach-1,3
Up Type=0
Dn Type=3
Dn Slope=0.005
Boundary for River Rch & Prof#=UNT 098 IN DRY C,Reach-1,4
Up Type=0
Dn Type=3
Dn Slope=0.005
Boundary for River Rch & Prof#=UNT 098 IN DRY C,Reach-1,5
Up Type=0
Dn Type=3
Dn Slope=0.005
Boundary for River Rch & Prof#=UNT 098 IN DRY C,Reach-1,6
Up Type=0
Dn Type=3
Dn Slope=0.005
Boundary for River Rch & Prof#=UNT 098 IN DRY C,Reach-1,7
Up Type=0
Dn Type=3
Dn Slope=0.005

--- UNT 098 IN DRY CR WATERSHED.g01 (geometry) ---

Geom Title=Existing Conditions

River Reach=UNT 098 IN DRY C,Reach-1
Reach XY= 30
      2911035.44      6982119.43      2911041.58      6982088.40
      2911072.08      6982048.92      2911074.33      6982016.54
      2911058.14      6981984.12      2911002.87      6981928.14
      2910989.26      6981909.16      2910976.51      6981841.00
      2910976.38      6981814.79      2911002.64      6981739.49
      2911014.37      6981670.86      2911014.62      6981634.90
      2911007.60      6981591.18      2911023.68      6981550.59
      2911028.36      6981486.51      2911043.99      6981449.94
      2911040.35      6981395.86      2911050.53      6981365.27
      2911047.23      6981320.46      2911054.67      6981307.34
      2911091.64      6981292.45      2911112.07      6981269.41
      2911115.82      6981220.91      2911108.69      6981161.63
      2911121.26      6981118.43      2911161.66      6981069.08
      2911168.48      6981006.44      2911185.76      6980970.46
      2911191.71      6980949.98      2911190.06      6980938.38

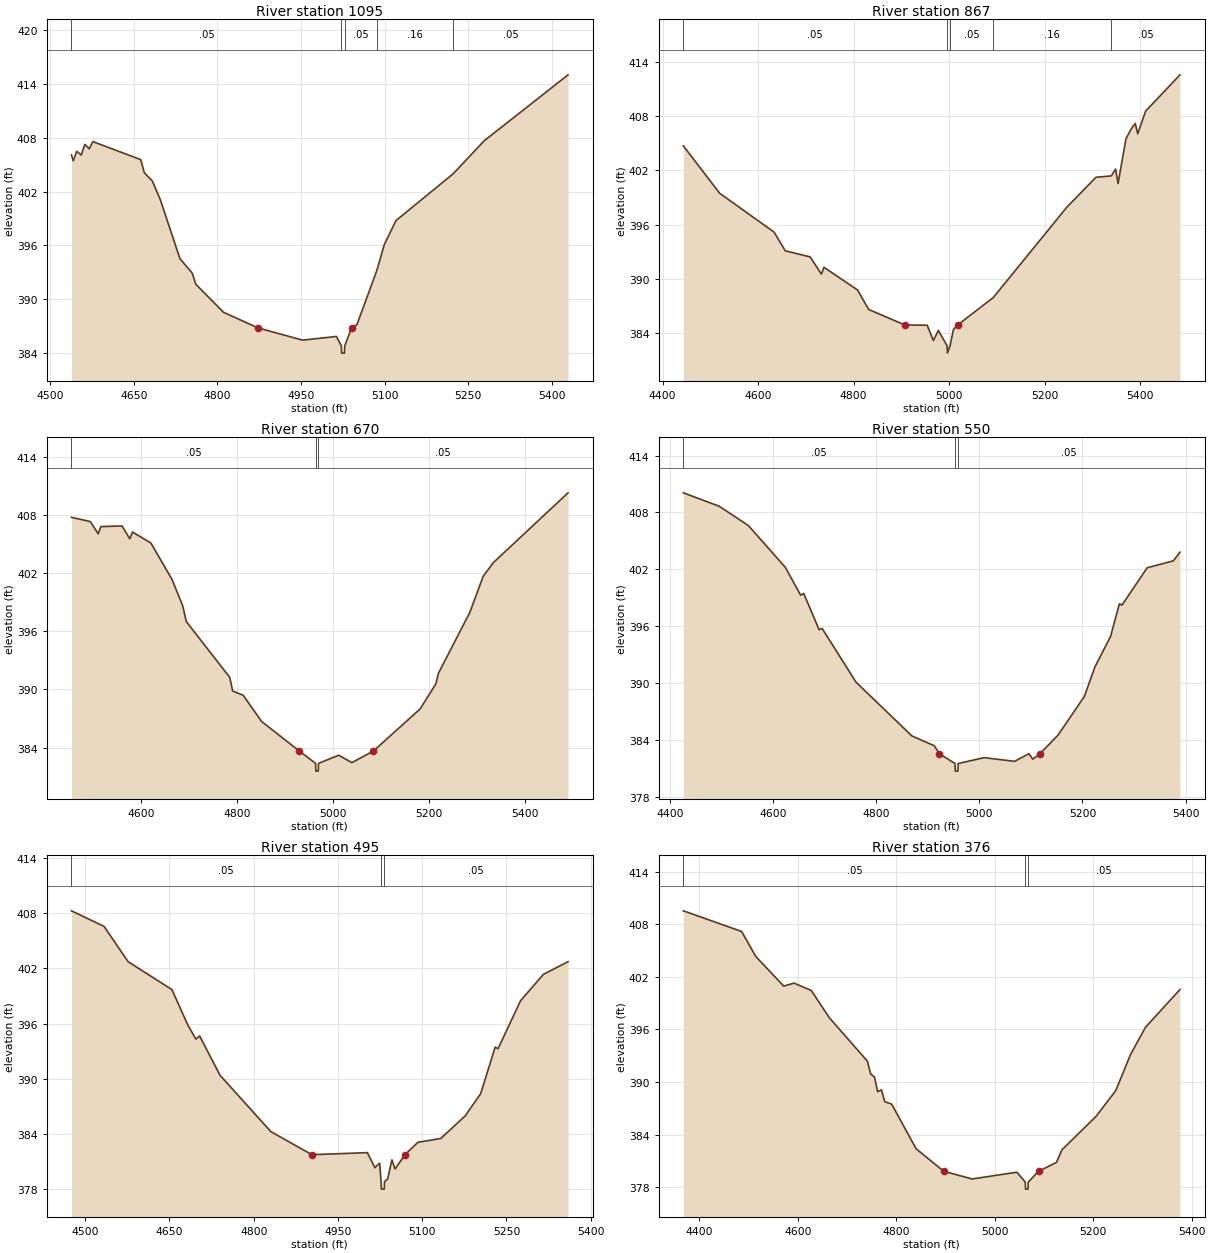
Type RM Length L Ch R = 1,1095,228,228,228
BEGIN DESCRIPTION:
UNT 098 IN DRY CR WATERSHED 2.0
END DESCRIPTION:
XS GIS Cut Line= 3
      2911323.09      6982271.11      2911043.14      6981936.48
      2910612.37      6982080.50
#Sta/Elev= 30
  4538.4  406.08  4541.5  405.43  4548.0  406.49  4555.8  406.07  4562.4  407.26
  4570.2  406.76  4576.7  407.57  4662.5  405.56  4669.1  404.08  4683.4  403.18
  4697.7  401.09  4732.8  394.52  4754.9  392.90  4761.4  391.65  4810.9  388.53
  4873.1  386.78  4952.7  385.42  5013.5  385.83  5022.4  384.77  5022.9  383.97
  5027.9  383.97  5028.4  384.77  5040.6  386.78  5050.3  387.15  5085.8  393.16
  5099.3  396.07  5120.3  398.76  5222.9  403.98  5278.5  407.66  5428.9  415.02
#Mann=5,-1,0
  4538.4    0.05       0  5022.4    0.03       0  5028.4    0.05       0
  5085.8    0.16       0  5222.9    0.05       0
Bank Sta=4873.1,5040.6
Exp/Cntr=0.3,0.1

Type RM Length L Ch R = 1,867,197,197,197
BEGIN DESCRIPTION:
Mapping XS a81c5c87
END DESCRIPTION:
XS GIS Cut Line= 3
      2911514.54      6981945.74      2911019.70      6981729.58
      2910535.32      6981851.97
#Sta/Elev= 30
  4443.7  404.72  4519.6  399.48  4633.5  395.18  4656.9  393.11  4709.2  392.43
  4732.6  390.52  4738.1  391.28  4808.3  388.77  4831.7  386.61  4907.6  384.89
  4954.1  384.87  4967.0  383.17  4977.5  384.29  4995.9  382.58  4996.4  381.78
  5001.9  382.58  5009.2  384.41  5017.8  384.89  5092.4  387.93  5246.4  397.93
  5307.5  401.25  5339.7  401.40  5348.6  402.16  5353.7  400.55  5370.2  405.50
  5380.5  406.54  5389.6  407.21  5394.8  406.06  5411.4  408.57  5483.3  412.59
#Mann=5,-1,0
  4443.7    0.05       0  4995.9    0.03       0  5001.9    0.05       0
  5092.4    0.16       0  5339.7    0.05       0
Bank Sta=4907.6,5017.8
Exp/Cntr=0.3,0.1

Type RM Length L Ch R = 1,670,120,120,120
BEGIN DESCRIPTION:
Mapping XS c1772bf5
END DESCRIPTION:
XS GIS Cut Line= 3
      2911506.68      6981797.28      2911019.70      6981539.47
      2910556.36      6981680.04
#Sta/Elev= 30
  4454.7  407.78  4493.9  407.34  4510.3  406.08  4515.9  406.82  4559.9  406.89
  4576.3  405.56  4581.9  406.26  4620.3  405.12  4664.3  401.36  4686.3  398.67
  4694.2  397.00  4784.7  391.24  4790.6  389.84  4812.6  389.40  4851.0  386.69
  4929.6  383.64  4963.6  382.36  4964.1  381.56  4969.1  381.56  4969.6  382.36
  5011.7  383.20  5039.4  382.44  5084.2  383.64  5181.4  387.98  5214.3  390.57
  5219.6  391.66  5285.3  397.98  5313.0  401.69  5334.6  403.12  5489.9  410.31
#Mann=3,-1,0
  4454.7    0.05       0  4963.6    0.03       0  4969.6    0.05       0
Bank Sta=4929.6,5084.2
Exp/Cntr=0.3,0.1

Type RM Length L Ch R = 1,550,55,55,55
BEGIN DESCRIPTION:
Mapping XS 968d7267
END DESCRIPTION:
XS GIS Cut Line= 4
      2911523.68      6981741.72      2911172.41      6981498.05
      2910960.37      6981379.37      2910672.39      6981430.00
#Sta/Elev= 30
  4426.3  410.07  4495.6  408.66  4552.3  406.62  4623.9  402.22  4653.6  399.28
  4659.7  399.45  4689.4  395.65  4695.5  395.76  4761.0  390.11  4869.2  384.45
  4912.6  383.41  4922.7  382.57  4953.0  381.53  4953.5  380.73  4958.5  380.73
  4959.0  381.53  5009.6  382.15  5068.6  381.76  5096.2  382.57  5103.9  381.99
  5118.0  382.57  5153.0  384.54  5203.8  388.60  5224.1  391.69  5254.6  394.93
  5271.7  398.37  5276.8  398.23  5325.6  402.17  5376.4  402.90  5389.2  403.81
#Mann=3,-1,0
  4426.3    0.05       0  4953.0    0.03       0  4959.0    0.05       0
Bank Sta=4922.7,5118
Exp/Cntr=0.3,0.1

Type RM Length L Ch R = 1,495,119,119,119
BEGIN DESCRIPTION:
Mapping XS e27811c2
END DESCRIPTION:
XS GIS Cut Line= 4
      2911467.54      6981684.71      2911194.94      6981452.04
      2910990.08      6981340.93      2910701.89      6981393.01
#Sta/Elev= 30
  4475.5  408.25  4533.5  406.56  4576.3  402.73  4654.3  399.70  4682.8  395.84
  4697.1  394.32  4703.7  394.67  4739.9  390.41  4830.6  384.28  4903.6  381.78
  5002.4  382.00  5015.8  380.37  5024.2  380.86  5026.9  378.84  5027.4  378.04
  5032.4  378.04  5032.9  378.84  5038.6  379.15  5046.1  381.22  5051.8  380.23
  5069.4  381.78  5092.4  383.12  5133.1  383.54  5176.5  385.98  5204.2  388.40
  5230.0  393.46  5235.1  393.28  5275.3  398.50  5316.0  401.36  5359.8  402.73
#Mann=3,-1,0
  4475.5    0.05       0  5026.9    0.03       0  5032.9    0.05       0
Bank Sta=4903.6,5069.4
Exp/Cntr=0.3,0.1

Type RM Length L Ch R = 1,376,297,297,297
BEGIN DESCRIPTION:
Mapping XS 08df8e98
END DESCRIPTION:
XS GIS Cut Line= 3
      2911527.51      6981729.57      2911139.49      6981281.66
      2910725.46      6981325.93
#Sta/Elev= 30
  4367.3  409.54  4485.7  407.18  4514.2  404.34  4571.2  400.95  4592.1  401.29
  4627.2  400.45  4663.4  397.37  4741.2  392.38  4747.9  390.91  4755.5  390.58
  4762.1  388.90  4769.8  389.11  4776.4  387.76  4790.6  387.48  4840.0  382.40
  4896.2  379.82  4954.0  378.94  5044.9  379.71  5062.0  378.58  5062.5  377.78
  5067.5  377.78  5068.0  378.58  5089.0  379.82  5125.3  380.82  5136.4  382.26
  5205.8  386.08  5246.0  389.04  5276.2  393.19  5306.4  396.26  5376.3  400.56
#Mann=3,-1,0
  4367.3    0.05       0  5062.0    0.03       0  5068.0    0.05       0
Bank Sta=4896.2,5089
Exp/Cntr=0.3,0.1

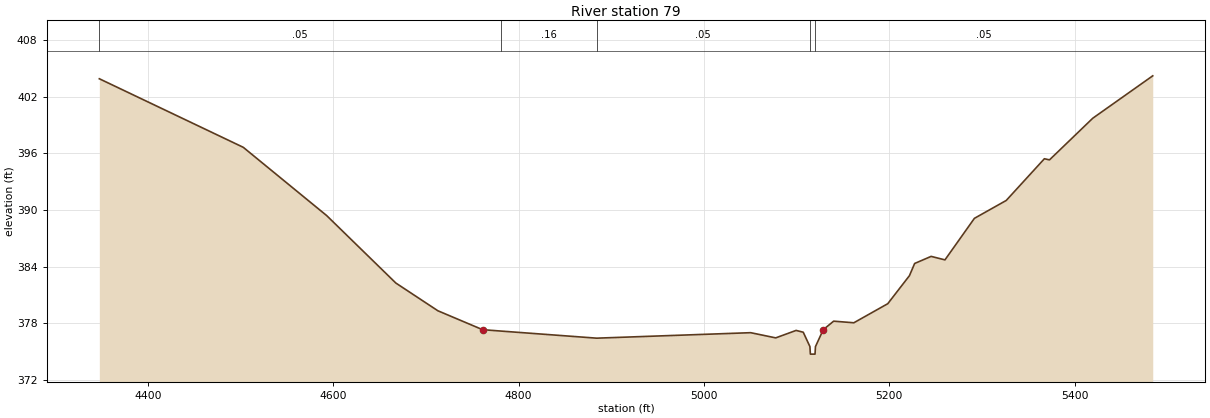
Type RM Length L Ch R = 1,79,0,0,0
BEGIN DESCRIPTION:
UNT 098 IN DRY CR WATERSHED 1.0
END DESCRIPTION:
XS GIS Cut Line= 4
      2911498.38      6981556.60      2911272.10      6981080.30
      2911104.37      6980971.11      2910729.71      6981135.51
#Sta/Elev= 30
  4347.7  403.89  4503.0  396.63  4593.0  389.40  4667.6  382.26  4713.0  379.32
  4761.2  377.32  4781.2  377.17  4884.3  376.42  5050.5  377.00  5077.5  376.45
  5099.5  377.24  5107.2  377.05  5114.4  375.53  5114.9  374.73  5119.9  374.73
  5120.4  375.53  5128.8  377.32  5140.0  378.22  5161.8  378.05  5198.4  380.07
  5221.8  383.04  5227.4  384.33  5245.2  385.08  5260.1  384.71  5291.9  389.11
  5326.2  391.00  5367.4  395.42  5372.9  395.30  5419.6  399.71  5484.3  404.20
#Mann=5,-1,0
  4347.7    0.05       0  4781.2    0.16       0  4884.3    0.05       0
  5114.4    0.03       0  5120.4    0.05       0
Bank Sta=4761.2,5128.8
Exp/Cntr=0.3,0.1

Chan Stop Cuts=-1