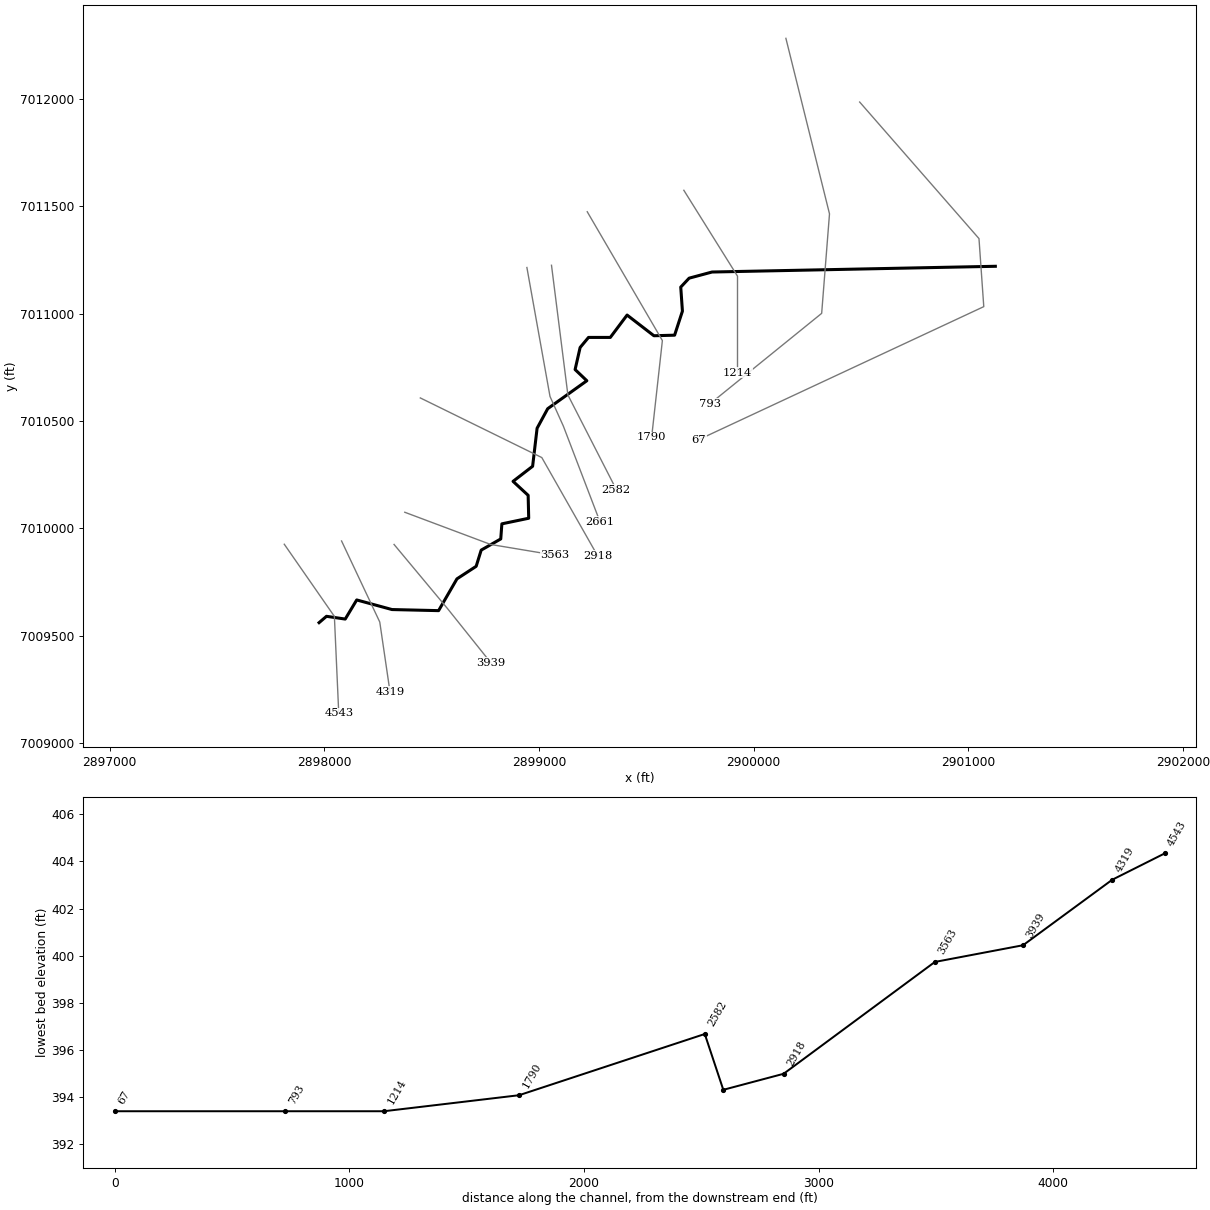
--- UNT 099 IN DRY CR WATERSHED.prj (project) ---

Proj Title=UNT 099 IN DRY CR WATERSHED Base Level Engineering
Current Plan=p01
Default Exp/Contr=0.3,0.1
English Units
Geom File=g01
Flow File=f01
Plan File=p01
BEGIN DESCRIPTION:
UNT 099 IN DRY CR WATERSHED
END DESCRIPTION:

--- UNT 099 IN DRY CR WATERSHED.p01 (plan) ---

Plan Title=Multiple Run
Short Identifier=Multiple
Geom File=g01
Flow File=f01
Subcritical Flow
K Sum by GR= 0
Std Step Tol= 0.01
Critical Tol= 0.01
Num of Std Step Trials= 20
Max Error Tol= 0.3
Flow Tol Ratio= 0.001
Split Flow NTrial= 30
Split Flow Tol= 0.02
Split Flow Ratio= 0.02
Log Output Level= 0
Friction Slope Method= 1
Unsteady Friction Slope Method= 2
Unsteady Bridges Friction Slope Method= 1
Parabolic Critical Depth
Global Vel Dist=  1 , 1 , 1
Global Log Level= 0
CheckData=True
Encroach Param= -1, 0, 0, 0
BEGIN DESCRIPTION:
Multiple Run
END DESCRIPTION:

--- UNT 099 IN DRY CR WATERSHED.f01 (steady flow) ---

Flow Title=Multiple
Number of Profiles=7
Profile Names=10-year,25-year,50-year,1pct_min,100-year,1pct_plu,500-year
River Rch & RM= UNT 099 IN DRY C,Reach-1,4543
     648     883    1078     654    1306    2605    1919
River Rch & RM= UNT 099 IN DRY C,Reach-1,4319
     721     984    1201     729    1454    2901    2136
Boundary for River Rch & Prof#=UNT 099 IN DRY C,Reach-1,1
Up Type=0
Dn Type=3
Dn Slope=0.005
Boundary for River Rch & Prof#=UNT 099 IN DRY C,Reach-1,2
Up Type=0
Dn Type=3
Dn Slope=0.005
Boundary for River Rch & Prof#=UNT 099 IN DRY C,Reach-1,3
Up Type=0
Dn Type=3
Dn Slope=0.005
Boundary for River Rch & Prof#=UNT 099 IN DRY C,Reach-1,4
Up Type=0
Dn Type=3
Dn Slope=0.005
Boundary for River Rch & Prof#=UNT 099 IN DRY C,Reach-1,5
Up Type=0
Dn Type=3
Dn Slope=0.005
Boundary for River Rch & Prof#=UNT 099 IN DRY C,Reach-1,6
Up Type=0
Dn Type=3
Dn Slope=0.005
Boundary for River Rch & Prof#=UNT 099 IN DRY C,Reach-1,7
Up Type=0
Dn Type=3
Dn Slope=0.005

--- UNT 099 IN DRY CR WATERSHED.g01 (geometry) ---

Geom Title=Existing Conditions

River Reach=UNT 099 IN DRY C,Reach-1
Reach XY= 30
      2897975.59      7009560.71      2898010.11      7009590.30
      2898097.50      7009577.45      2898150.98      7009666.53
      2898315.38      7009621.78      2898532.41      7009616.71
      2898617.93      7009764.74      2898707.46      7009823.18
      2898730.90      7009898.70      2898822.04      7009950.78
      2898827.25      7010021.10      2898952.25      7010047.14
      2898949.65      7010153.91      2898879.33      7010219.01
      2898970.48      7010289.32      2898991.31      7010466.41
      2899040.79      7010557.55      2899223.08      7010687.76
      2899168.39      7010739.85      2899191.83      7010842.71
      2899230.90      7010889.58      2899332.46      7010889.58
      2899410.58      7010993.75      2899535.58      7010897.40
      2899631.94      7010900.00      2899668.39      7011011.98
      2899660.58      7011123.96      2899699.65      7011165.63
      2899806.42      7011194.27      2901126.23      7011220.99

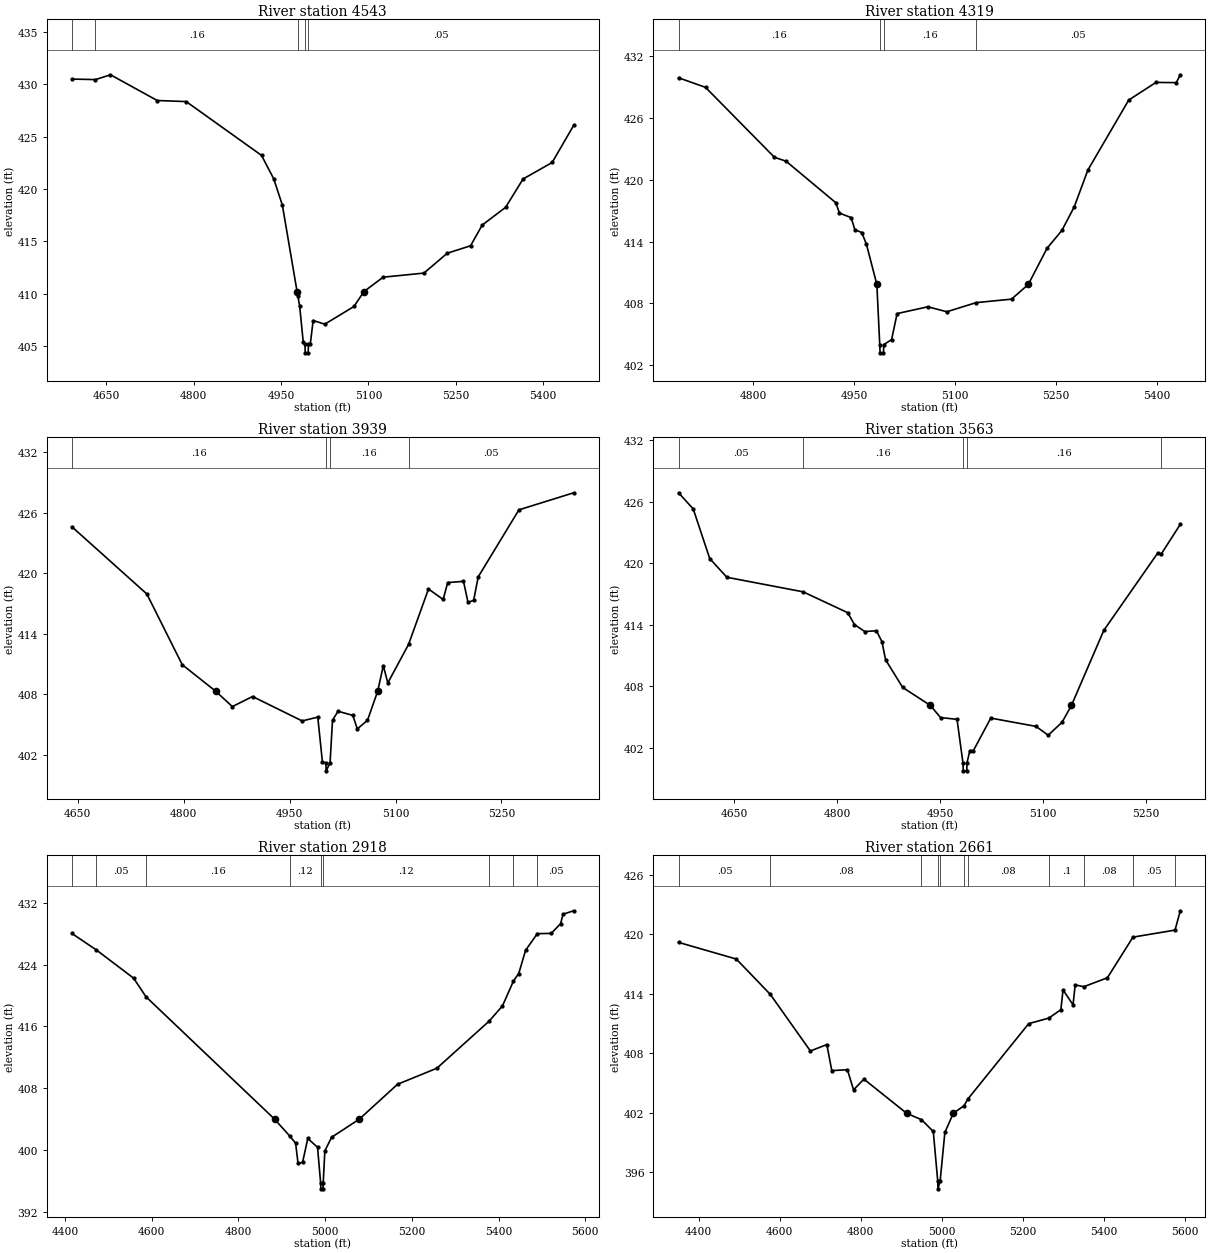
Type RM Length L Ch R = 1,4543,224,224,224
BEGIN DESCRIPTION:
UNT 099 IN DRY CR WATERSHED 8.0
END DESCRIPTION:
XS GIS Cut Line= 3
      2897813.47      7009926.10      2898046.92      7009590.02
      2898067.31      7009138.08
#Sta/Elev= 30
  4590.8  430.50  4631.2  430.45  4657.0  430.91  4737.3  428.45  4787.0  428.35
  4916.3  423.21  4937.2  420.98  4952.1  418.46  4977.4  410.19  4978.8  409.75
  4981.8  408.82  4987.9  405.42  4990.9  405.14  4991.4  404.34  4996.4  404.34
  4996.9  405.14  5000.0  405.14  5005.0  407.43  5025.0  407.08  5075.1  408.77
  5092.1  410.19  5125.2  411.57  5195.2  411.96  5235.3  413.86  5275.3  414.57
  5295.3  416.55  5335.4  418.24  5365.4  420.95  5415.4  422.53  5452.4  426.08
#Mann=5,-1,0
  4590.8    0.05       0  4631.2    0.16       0  4978.8    0.05       0
  4990.9    0.03       0  4996.9    0.05       0
Bank Sta=4977.4,5092.1
Exp/Cntr=0.3,0.1

Type RM Length L Ch R = 1,4319,380,380,380
BEGIN DESCRIPTION:
Mapping XS efb102fb
END DESCRIPTION:
XS GIS Cut Line= 3
      2898080.41      7009941.27      2898258.37      7009563.65
      2898305.97      7009239.07
#Sta/Elev= 30
  4689.1  429.86  4729.2  428.93  4831.5  422.16  4848.8  421.78  4922.7  417.76
  4928.2  416.75  4945.5  416.32  4951.0  415.15  4961.3  414.87  4968.3  413.72
  4983.7  409.84  4988.0  404.02  4988.5  403.22  4993.5  403.22  4994.0  404.02
  5005.6  404.50  5013.8  407.02  5059.4  407.68  5087.7  407.20  5131.1  408.08
  5183.8  408.42  5208.7  409.84  5236.6  413.35  5258.7  415.08  5277.0  417.36
  5297.2  420.92  5357.9  427.70  5398.4  429.41  5428.6  429.39  5434.6  430.15
#Mann=4,-1,0
  4689.1    0.16       0  4988.0    0.07       0  4994.0    0.16       0
  5131.1    0.05       0
Bank Sta=4983.7,5208.7
Exp/Cntr=0.3,0.1

Type RM Length L Ch R = 1,3939,376,376,376
BEGIN DESCRIPTION:
UNT 099 IN DRY CR WATERSHED 7.0
END DESCRIPTION:
XS GIS Cut Line= 3
      2898324.97      7009925.03      2898575.00      7009625.00
      2898774.99      7009375.01
#Sta/Elev= 30
  4641.6  424.60  4747.7  417.95  4797.8  410.95  4845.1  408.33  4868.8  406.80
  4897.4  407.80  4967.7  405.38  4989.8  405.76  4996.4  401.31  5001.2  401.24
  5001.7  400.44  5007.2  401.24  5010.7  405.45  5018.5  406.34  5039.4  405.93
  5045.8  404.59  5060.2  405.44  5074.7  408.33  5082.6  410.85  5089.0  409.14
  5118.4  412.96  5146.6  418.44  5167.4  417.41  5173.8  419.08  5196.2  419.20
  5202.6  417.12  5210.6  417.32  5217.0  419.64  5274.7  426.28  5352.3  427.97
#Mann=4,-1,0
  4641.6    0.16       0  5001.2    0.07       0  5007.2    0.16       0
  5118.4    0.05       0
Bank Sta=4845.1,5074.7
Exp/Cntr=0.3,0.1

Type RM Length L Ch R = 1,3563,645,645,645
BEGIN DESCRIPTION:
UNT 099 IN DRY CR WATERSHED 6.0
END DESCRIPTION:
XS GIS Cut Line= 3
      2898374.96      7010075.01      2898775.00      7009925.00
      2899075.02      7009875.00
#Sta/Elev= 30
  4568.9  426.88  4590.3  425.30  4614.3  420.46  4639.3  418.63  4750.4  417.21
  4815.5  415.17  4825.3  414.01  4840.4  413.33  4857.3  413.41  4865.3  412.35
  4870.7  410.57  4895.6  407.87  4935.9  406.12  4950.8  404.93  4974.8  404.76
  4983.4  400.53  4983.9  399.73  4988.9  399.73  4989.4  400.53  4993.5  401.71
  4998.7  401.71  5024.0  404.88  5089.9  404.07  5107.7  403.21  5127.9  404.47
  5141.6  406.12  5188.8  413.45  5267.3  420.99  5272.3  420.88  5300.3  423.80
#Mann=5,-1,0
  4568.9    0.05       0  4750.4    0.16       0  4983.4    0.07       0
  4989.4    0.16       0  5272.3    0.05       0
Bank Sta=4935.9,5141.6
Exp/Cntr=0.3,0.1

Type RM Length L Ch R = 1,2918,257,257,257
BEGIN DESCRIPTION:
Mapping XS d431eb8f
END DESCRIPTION:
XS GIS Cut Line= 3
      2898447.31      7010607.64      2899013.29      7010329.85
      2899273.70      7009871.54
#Sta/Elev= 30
  4415.9  428.03  4472.5  425.89  4558.1  422.25  4586.9  419.83  4883.4  404.00
  4918.9  401.78  4931.9  400.89  4937.5  398.29  4948.0  398.41  4960.0  401.50
  4982.5  400.36  4989.6  395.78  4990.1  394.98  4995.1  394.98  4995.6  395.78
  4999.4  399.89  5014.9  401.65  5078.9  404.00  5167.0  408.51  5257.8  410.59
  5378.5  416.69  5409.2  418.66  5434.6  421.89  5446.7  422.85  5462.5  425.86
  5489.6  428.01  5521.6  428.04  5543.3  429.31  5549.0  430.53  5573.5  430.97
#Mann=9,-1,0
  4415.9    0.16       0  4472.5    0.05       0  4586.9    0.16       0
  4918.9    0.12       0  4989.6    0.07       0  4995.6    0.12       0
  5378.5    0.05       0  5434.6    0.12       0  5489.6    0.05       0
Bank Sta=4883.4,5078.9
Exp/Cntr=0.3,0.1

Type RM Length L Ch R = 1,2661,79,79,79
BEGIN DESCRIPTION:
Mapping XS 599006dd
END DESCRIPTION:
XS GIS Cut Line= 4
      2898943.84      7011215.30      2899051.48      7010614.58
      2899113.98      7010475.69      2899284.13      7010031.23
#Sta/Elev= 30
  4350.4  419.17  4492.9  417.49  4576.9  413.92  4675.8  408.21  4716.4  408.86
  4728.6  406.23  4767.2  406.32  4782.3  404.29  4807.9  405.37  4913.5  401.92
  4950.0  401.28  4979.1  400.09  4990.1  395.10  4990.6  394.30  4996.1  395.10
  5007.7  399.99  5028.6  401.92  5055.4  402.70  5063.8  403.33  5214.6  410.97
  5264.3  411.53  5294.0  412.38  5299.4  414.37  5324.1  412.87  5329.4  414.88
  5350.8  414.70  5408.9  415.60  5472.0  419.70  5575.8  420.41  5588.9  422.36
#Mann=11,-1,0
  4350.4    0.05       0  4576.9    0.08       0  4950.0    0.16       0
  4990.1    0.07       0  4996.1    0.16       0  5055.4    0.12       0
  5063.8    0.08       0  5264.3     0.1       0  5350.8    0.08       0
  5472.0    0.05       0  5575.8    0.12       0
Bank Sta=4913.5,5028.6
Exp/Cntr=0.3,0.1

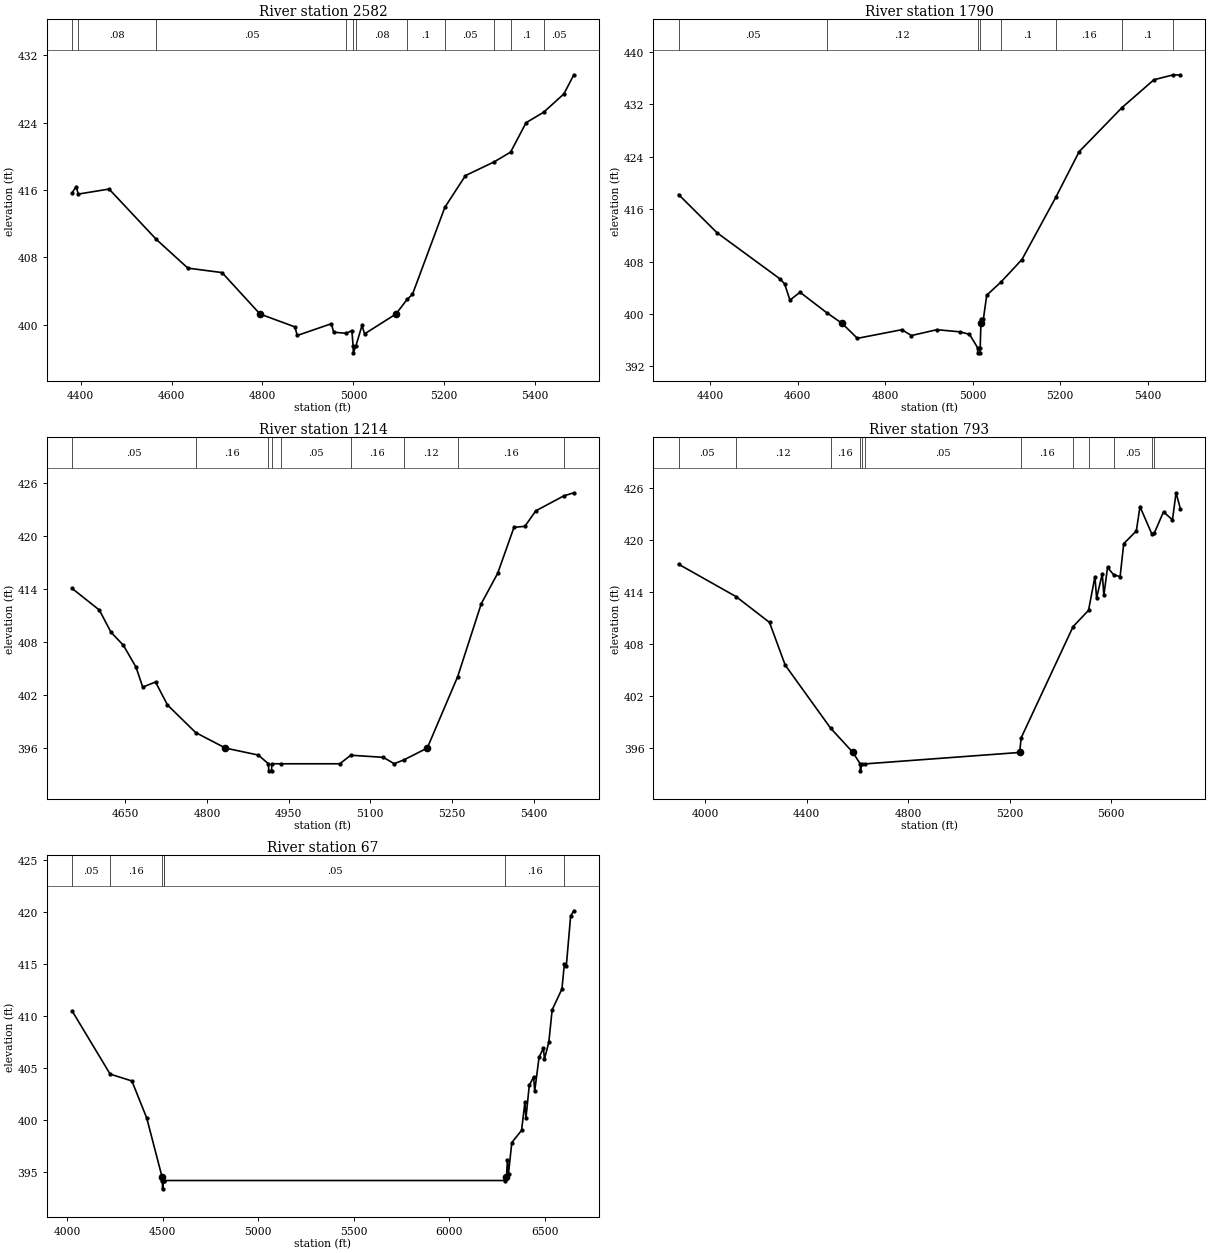
Type RM Length L Ch R = 1,2582,792,792,792
BEGIN DESCRIPTION:
Mapping XS 4bc61ca9
END DESCRIPTION:
XS GIS Cut Line= 3
      2899058.42      7011225.71      2899134.82      7010621.52
      2899360.25      7010181.06
#Sta/Elev= 30
  4381.2  415.67  4390.4  416.42  4394.6  415.52  4462.6  416.12  4566.7  410.13
  4635.9  406.73  4711.1  406.20  4794.6  401.28  4871.4  399.75  4876.5  398.73
  4951.6  400.13  4956.6  399.12  4984.6  398.99  4996.7  399.32  4999.4  397.47
  4999.9  396.67  5005.4  397.47  5019.0  399.92  5024.6  398.92  5093.6  401.28
  5118.2  403.01  5130.0  403.62  5201.2  413.95  5246.6  417.72  5309.8  419.35
  5345.9  420.51  5379.9  424.00  5418.5  425.24  5463.1  427.42  5485.0  429.69
#Mann=11,-1,0
  4381.2    0.05       0  4394.6    0.08       0  4566.7    0.05       0
  4984.6    0.08       0  4999.4    0.07       0  5005.4    0.08       0
  5118.2     0.1       0  5201.2    0.05       0  5309.8    0.08       0
  5345.9     0.1       0  5418.5    0.05       0
Bank Sta=4794.6,5093.6
Exp/Cntr=0.3,0.1

Type RM Length L Ch R = 1,1790,576,576,576
BEGIN DESCRIPTION:
UNT 099 IN DRY CR WATERSHED 3.0
END DESCRIPTION:
XS GIS Cut Line= 3
      2899225.00      7011474.99      2899575.00      7010875.00
      2899525.00      7010424.99
#Sta/Elev= 30
  4327.2  418.22  4415.3  412.38  4560.0  405.31  4569.9  404.57  4581.9  402.11
  4605.0  403.31  4665.9  400.20  4701.3  398.56  4736.1  396.28  4837.8  397.60
  4859.7  396.71  4918.0  397.60  4971.0  397.27  4992.5  396.89  5010.9  394.87
  5011.4  394.07  5016.5  394.07  5017.0  394.87  5018.6  398.56  5018.9  399.24
  5024.3  399.24  5031.9  402.86  5064.1  404.84  5112.4  408.30  5189.8  417.79
  5243.2  424.75  5341.3  431.48  5414.2  435.72  5458.9  436.48  5474.6  436.43
#Mann=8,-1,0
  4327.2    0.05       0  4665.9    0.12       0  5010.9    0.07       0
  5017.0    0.12       0  5064.1     0.1       0  5189.8    0.16       0
  5341.3     0.1       0  5458.9    0.16       0
Bank Sta=4701.3,5018.6
Exp/Cntr=0.3,0.1

Type RM Length L Ch R = 1,1214,421,421,421
BEGIN DESCRIPTION:
UNT 099 IN DRY CR WATERSHED 2.0
END DESCRIPTION:
XS GIS Cut Line= 3
      2899674.98      7011575.03      2899925.00      7011175.00
      2899925.00      7010725.04
#Sta/Elev= 30
  4552.2  414.07  4602.4  411.61  4623.6  409.11  4646.6  407.61  4669.6  405.15
  4682.0  402.88  4705.5  403.46  4727.4  400.86  4779.2  397.73  4833.9  395.97
  4894.2  395.18  4912.9  394.19  4913.4  393.39  4918.6  393.39  4919.1  394.19
  4936.0  394.19  5043.9  394.19  5064.2  395.16  5123.9  394.92  5143.9  394.20
  5162.0  394.64  5204.6  395.97  5260.5  404.07  5303.9  412.35  5333.9  415.77
  5363.9  420.99  5383.9  421.11  5403.9  422.86  5455.5  424.56  5473.9  424.91
#Mann=9,-1,0
  4552.2    0.05       0  4779.2    0.16       0  4912.9   0.035       0
  4919.1    0.16       0  4936.0    0.05       0  5064.2    0.16       0
  5162.0    0.12       0  5260.5    0.16       0  5455.5    0.05       0
Bank Sta=4833.9,5204.6
Exp/Cntr=0.3,0.1

Type RM Length L Ch R = 1,793,726,726,726
BEGIN DESCRIPTION:
Mapping XS 0e89bfc9
END DESCRIPTION:
XS GIS Cut Line= 4
      2900150.45      7012282.95      2900353.57      7011465.27
      2900317.11      7011001.73      2899796.40      7010579.95
#Sta/Elev= 30
  3895.6  417.21  4122.5  413.47  4254.1  410.50  4315.9  405.58  4494.9  398.31
  4582.9  395.51  4611.7  394.19  4612.2  393.39  4617.9  394.19  4630.3  394.19
  5240.2  395.51  5245.7  397.18  5450.7  410.02  5511.4  411.89  5536.7  415.77
  5543.2  413.31  5565.5  416.09  5571.9  413.64  5586.3  416.84  5610.7  415.98
  5635.9  415.78  5650.2  419.58  5699.8  421.04  5714.2  423.84  5761.6  420.65
  5770.8  420.81  5806.9  423.24  5842.1  422.32  5856.5  425.44  5873.2  423.62
#Mann=12,-1,0
  3895.6    0.05       0  4122.5    0.12       0  4494.9    0.16       0
  4611.7   0.033       0  4617.9    0.16       0  4630.3    0.05       0
  5245.7    0.16       0  5450.7    0.05       0  5511.4    0.08       0
  5610.7    0.05       0  5761.6    0.16       0  5770.8    0.08       0
Bank Sta=4582.9,5240.2
Exp/Cntr=0.3,0.1

Type RM Length L Ch R = 1,67,0,0,0
BEGIN DESCRIPTION:
UNT 099 IN DRY CR WATERSHED 1.0
END DESCRIPTION:
XS GIS Cut Line= 4
      2900494.17      7011986.13      2901050.00      7011350.00
      2901072.32      7011032.98      2899744.18      7010413.18
#Sta/Elev= 30
  4024.5  410.50  4223.9  404.42  4337.7  403.76  4415.5  400.20  4495.6  394.55
  4497.9  394.19  4498.4  393.39  4504.1  394.19  4504.7  394.19  6292.2  394.19
  6299.8  394.55  6304.8  396.20  6310.4  394.85  6327.7  397.84  6378.9  399.01
  6396.3  401.71  6401.8  400.19  6419.1  403.33  6442.0  404.15  6447.5  402.77
  6470.4  406.04  6493.2  406.91  6498.8  405.88  6521.6  407.49  6539.0  410.60
  6590.2  412.60  6603.2  415.04  6613.0  414.78  6635.9  419.63  6652.7  420.12
#Mann=7,-1,0
  4024.5    0.05       0  4223.9    0.16       0  4497.9   0.033       0
  4504.1    0.16       0  4504.7    0.05       0  6292.2    0.16       0
  6603.2    0.08       0
Bank Sta=4495.6,6299.8
Exp/Cntr=0.3,0.1

Chan Stop Cuts=-1