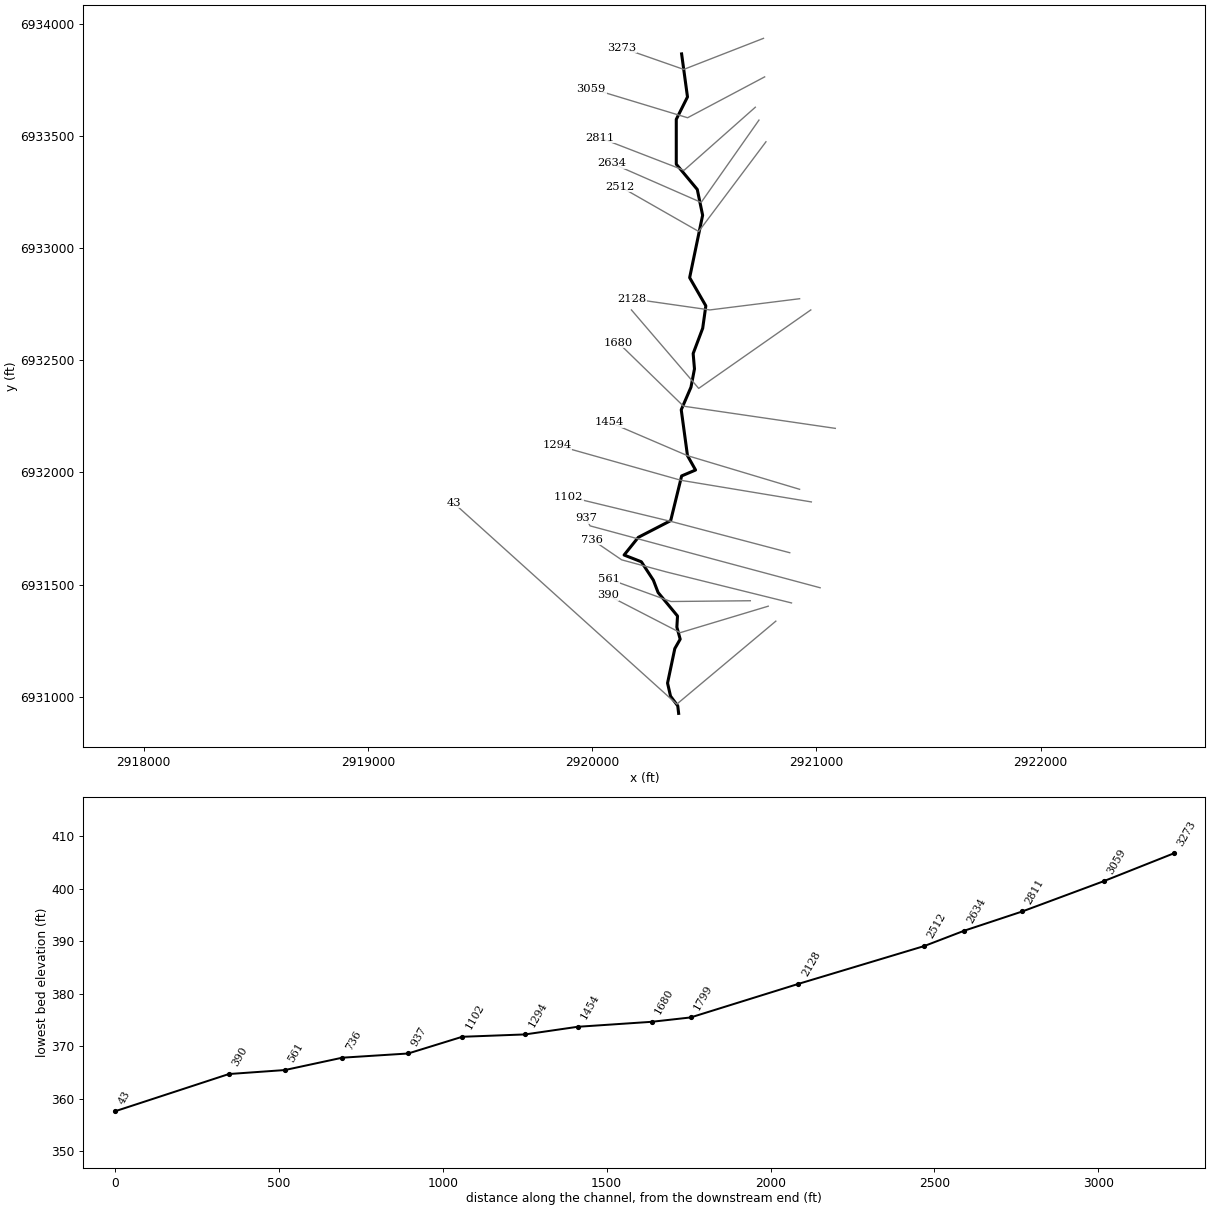
--- UNT 100 IN DRY CR WATERSHED.prj (project) ---

Proj Title=UNT 100 IN DRY CR WATERSHED Base Level Engineering
Current Plan=p01
Default Exp/Contr=0.3,0.1
English Units
Geom File=g01
Flow File=f01
Plan File=p01
BEGIN DESCRIPTION:
UNT 100 IN DRY CR WATERSHED
END DESCRIPTION:

--- UNT 100 IN DRY CR WATERSHED.p01 (plan) ---

Plan Title=Multiple Run
Short Identifier=Multiple
Geom File=g01
Flow File=f01
Subcritical Flow
K Sum by GR= 0
Std Step Tol= 0.01
Critical Tol= 0.01
Num of Std Step Trials= 20
Max Error Tol= 0.3
Flow Tol Ratio= 0.001
Split Flow NTrial= 30
Split Flow Tol= 0.02
Split Flow Ratio= 0.02
Log Output Level= 0
Friction Slope Method= 1
Unsteady Friction Slope Method= 2
Unsteady Bridges Friction Slope Method= 1
Parabolic Critical Depth
Global Vel Dist=  1 , 1 , 1
Global Log Level= 0
CheckData=True
Encroach Param= -1, 0, 0, 0
BEGIN DESCRIPTION:
Multiple Run
END DESCRIPTION:

--- UNT 100 IN DRY CR WATERSHED.f01 (steady flow) ---

Flow Title=Multiple
Number of Profiles=7
Profile Names=10-year,25-year,50-year,1pct_min,100-year,1pct_plu,500-year
River Rch & RM= UNT 100 IN DRY C,Reach-1,3273
     268     346     408     241     480     958     663
Boundary for River Rch & Prof#=UNT 100 IN DRY C,Reach-1,1
Up Type=0
Dn Type=3
Dn Slope=0.005
Boundary for River Rch & Prof#=UNT 100 IN DRY C,Reach-1,2
Up Type=0
Dn Type=3
Dn Slope=0.005
Boundary for River Rch & Prof#=UNT 100 IN DRY C,Reach-1,3
Up Type=0
Dn Type=3
Dn Slope=0.005
Boundary for River Rch & Prof#=UNT 100 IN DRY C,Reach-1,4
Up Type=0
Dn Type=3
Dn Slope=0.005
Boundary for River Rch & Prof#=UNT 100 IN DRY C,Reach-1,5
Up Type=0
Dn Type=3
Dn Slope=0.005
Boundary for River Rch & Prof#=UNT 100 IN DRY C,Reach-1,6
Up Type=0
Dn Type=3
Dn Slope=0.005
Boundary for River Rch & Prof#=UNT 100 IN DRY C,Reach-1,7
Up Type=0
Dn Type=3
Dn Slope=0.005

--- UNT 100 IN DRY CR WATERSHED.g01 (geometry) ---

Geom Title=Existing Conditions

River Reach=UNT 100 IN DRY C,Reach-1
Reach XY= 30
      2920398.79      6933866.92      2920425.00      6933675.00
      2920375.00      6933575.00      2920375.00      6933375.00
      2920468.67      6933262.32      2920492.54      6933147.31
      2920434.64      6932868.95      2920506.81      6932743.19
      2920492.80      6932643.13      2920450.27      6932530.41
      2920456.17      6932462.00      2920440.55      6932380.41
      2920397.14      6932279.71      2920425.00      6932075.00
      2920461.00      6932011.00      2920398.88      6931984.57
      2920350.09      6931785.27      2920205.59      6931710.71
      2920142.27      6931631.81      2920219.24      6931601.69
      2920272.82      6931519.59      2920293.88      6931464.71
      2920380.54      6931359.68      2920377.66      6931310.25
      2920392.39      6931256.48      2920368.48      6931214.64
      2920336.07      6931060.65      2920349.37      6931002.33
      2920381.60      6930959.03      2920385.54      6930925.56

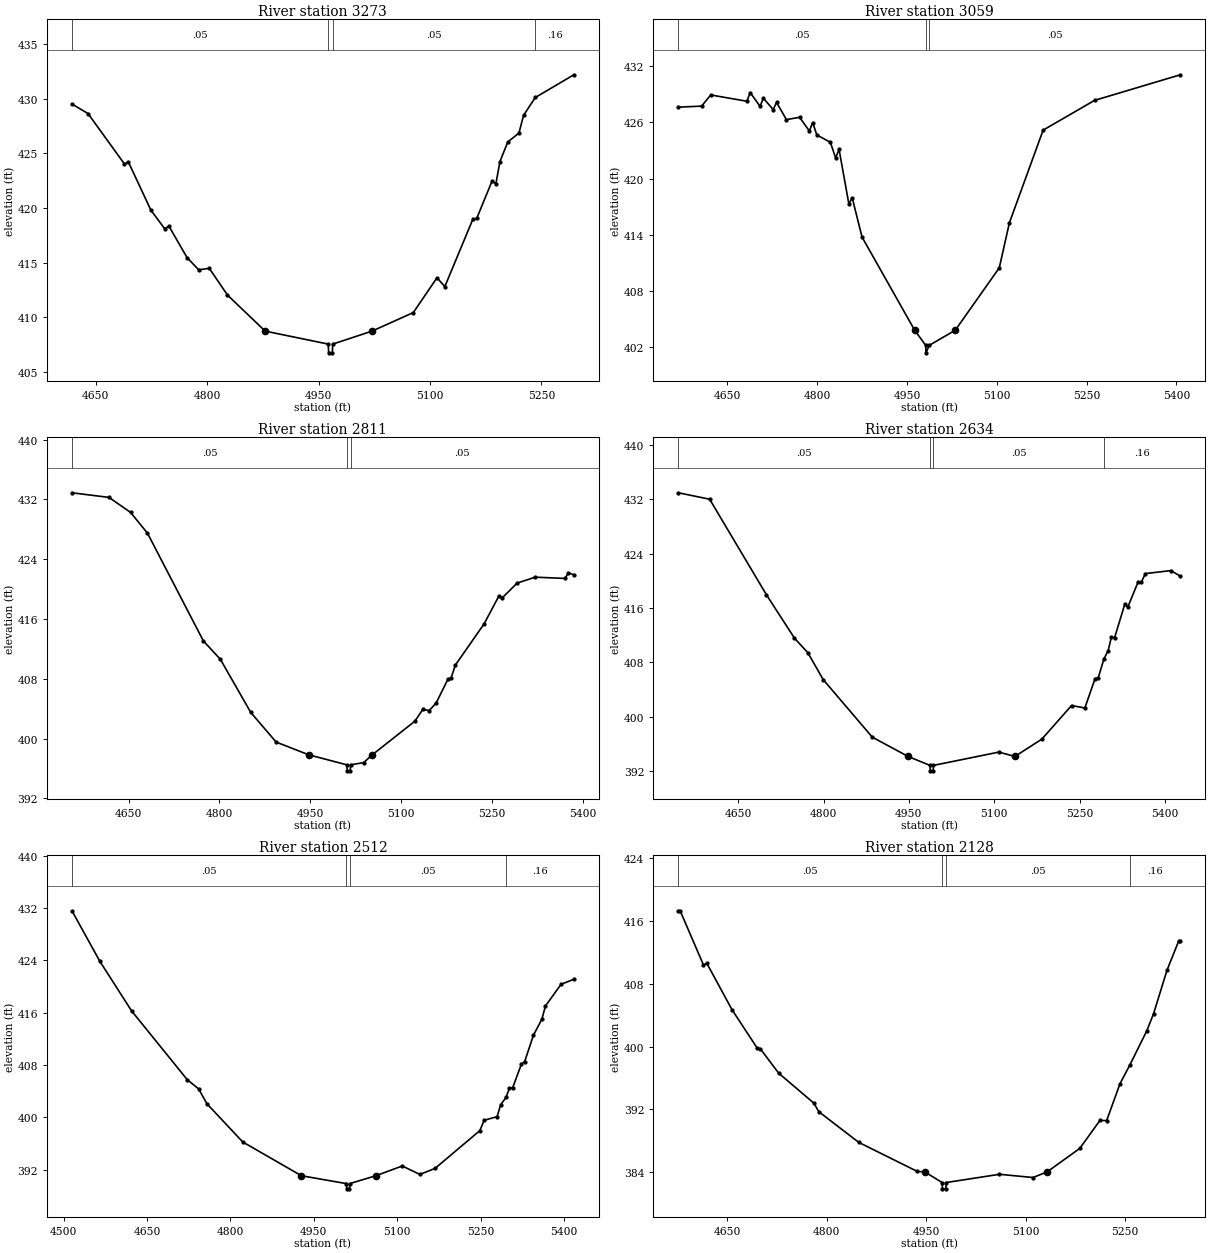
Type RM Length L Ch R = 1,3273,214,214,214
BEGIN DESCRIPTION:
UNT 100 IN DRY CR WATERSHED 7.0
END DESCRIPTION:
XS GIS Cut Line= 3
      2920763.99      6933936.37      2920408.24      6933797.77
      2920131.10      6933894.70
#Sta/Elev= 30
  4618.2  429.51  4639.8  428.64  4688.9  424.02  4694.2  424.20  4724.4  419.80
  4743.2  418.07  4748.6  418.34  4773.1  415.45  4788.8  414.33  4803.0  414.47
  4827.5  412.02  4878.2  408.72  4963.1  407.53  4963.6  406.73  4968.6  406.73
  4969.1  407.53  5022.1  408.72  5077.6  410.42  5109.4  413.60  5120.0  412.80
  5157.6  418.95  5162.9  419.04  5183.4  422.44  5188.7  422.21  5194.1  424.24
  5204.7  426.04  5219.7  426.85  5225.9  428.47  5241.7  430.11  5293.6  432.19
#Mann=4,-1,0
  4618.2    0.05       0  4963.1    0.03       0  4969.1    0.05       0
  5241.7    0.16       0
Bank Sta=4878.2,5022.1
Exp/Cntr=0.3,0.1

Type RM Length L Ch R = 1,3059,248,248,248
BEGIN DESCRIPTION:
Mapping XS e77e30af
END DESCRIPTION:
XS GIS Cut Line= 3
      2920769.18      6933764.49      2920425.41      6933582.19
      2919995.72      6933712.40
#Sta/Elev= 30
  4568.4  427.61  4607.1  427.72  4622.4  428.91  4682.7  428.24  4688.3  429.16
  4704.7  427.70  4710.3  428.56  4726.7  427.35  4732.3  428.12  4748.7  426.28
  4770.7  426.53  4787.0  425.07  4792.6  425.97  4799.5  424.65  4822.2  423.86
  4831.0  422.18  4836.6  423.13  4853.0  417.30  4858.6  417.95  4875.0  413.77
  4962.9  403.84  4981.3  402.23  4981.8  401.43  4987.3  402.23  5030.7  403.84
  5104.2  410.49  5121.1  415.29  5177.4  425.16  5263.2  428.33  5406.5  431.06
#Mann=3,-1,0
  4568.4    0.05       0  4981.3    0.03       0  4987.3    0.05       0
Bank Sta=4962.9,5030.7
Exp/Cntr=0.3,0.1

Type RM Length L Ch R = 1,2811,177,177,177
BEGIN DESCRIPTION:
Mapping XS a1332647
END DESCRIPTION:
XS GIS Cut Line= 3
      2920727.53      6933629.10      2920409.79      6933347.81
      2920032.22      6933493.63
#Sta/Elev= 30
  4556.4  432.88  4617.6  432.26  4653.3  430.25  4681.2  427.47  4773.5  413.06
  4801.6  410.60  4851.8  403.49  4893.7  399.53  4947.4  397.83  5010.6  396.48
  5011.1  395.68  5016.1  395.68  5016.6  396.48  5038.2  396.78  5052.6  397.83
  5122.7  402.31  5136.0  403.89  5146.7  403.75  5158.1  404.77  5177.3  407.91
  5182.7  408.08  5189.6  409.81  5237.2  415.34  5261.8  419.09  5267.2  418.82
  5291.8  420.80  5321.7  421.59  5370.9  421.42  5376.3  422.15  5385.5  421.92
#Mann=3,-1,0
  4556.4    0.05       0  5010.6    0.03       0  5016.6    0.05       0
Bank Sta=4947.4,5052.6
Exp/Cntr=0.3,0.1

Type RM Length L Ch R = 1,2634,122,122,122
BEGIN DESCRIPTION:
Mapping XS d8f52793
END DESCRIPTION:
XS GIS Cut Line= 3
      2920743.84      6933571.71      2920486.01      6933204.50
      2920088.81      6933378.44
#Sta/Elev= 30
  4544.9  432.97  4599.8  432.02  4699.7  417.94  4748.9  411.56  4772.4  409.42
  4799.4  405.46  4885.7  396.98  4948.6  394.14  4987.2  392.82  4987.7  392.02
  4992.7  392.02  4993.2  392.82  5108.2  394.78  5136.4  394.14  5183.8  396.69
  5236.0  401.64  5259.4  401.28  5277.3  405.60  5282.8  405.69  5292.9  408.50
  5300.4  409.73  5306.1  411.75  5311.6  411.62  5329.5  416.54  5335.0  416.16
  5352.9  419.82  5358.4  419.77  5365.9  421.07  5410.6  421.51  5427.2  420.69
#Mann=4,-1,0
  4544.9    0.05       0  4987.2    0.03       0  4993.2    0.05       0
  5292.9    0.16       0
Bank Sta=4948.6,5136.4
Exp/Cntr=0.3,0.1

Type RM Length L Ch R = 1,2512,384,384,384
BEGIN DESCRIPTION:
UNT 100 IN DRY CR WATERSHED 6.0
END DESCRIPTION:
XS GIS Cut Line= 3
      2920774.99      6933474.98      2920475.00      6933075.00
      2920124.99      6933275.00
#Sta/Elev= 30
  4514.8  431.57  4564.8  423.88  4622.1  416.28  4722.1  405.79  4742.9  404.35
  4757.5  402.11  4822.1  396.26  4927.7  391.10  5008.7  389.90  5009.2  389.10
  5014.2  389.10  5014.7  389.90  5061.6  391.10  5109.1  392.59  5140.8  391.30
  5168.1  392.22  5248.7  397.99  5256.6  399.58  5279.7  400.12  5286.2  401.94
  5295.9  403.07  5302.0  404.50  5307.8  404.54  5323.6  408.16  5329.4  408.54
  5345.2  412.57  5360.3  414.99  5366.8  417.03  5394.9  420.34  5417.9  421.11
#Mann=4,-1,0
  4514.8    0.05       0  5008.7    0.03       0  5014.7    0.05       0
  5295.9    0.16       0
Bank Sta=4927.7,5061.6
Exp/Cntr=0.3,0.1

Type RM Length L Ch R = 1,2128,329,329,329
BEGIN DESCRIPTION:
UNT 100 IN DRY CR WATERSHED 5.0
END DESCRIPTION:
XS GIS Cut Line= 3
      2920925.05      6932775.01      2920525.00      6932725.00
      2920175.01      6932775.00
#Sta/Elev= 30
  4576.3  417.27  4578.9  417.27  4614.1  410.37  4619.2  410.58  4657.0  404.70
  4694.8  399.84  4699.8  399.71  4727.5  396.61  4780.4  392.81  4788.0  391.71
  4848.4  387.80  4936.6  384.11  4947.9  384.05  4973.9  382.70  4974.4  381.90
  4979.4  381.90  4979.9  382.70  5060.3  383.75  5110.8  383.34  5132.1  384.05
  5181.5  387.05  5211.8  390.60  5221.9  390.58  5242.1  395.28  5257.0  397.67
  5282.5  402.01  5292.6  404.16  5312.8  409.68  5330.5  413.41  5333.0  413.41
#Mann=4,-1,0
  4576.3    0.05       0  4973.9    0.03       0  4979.9    0.05       0
  5257.0    0.16       0
Bank Sta=4947.9,5132.1
Exp/Cntr=0.3,0.1

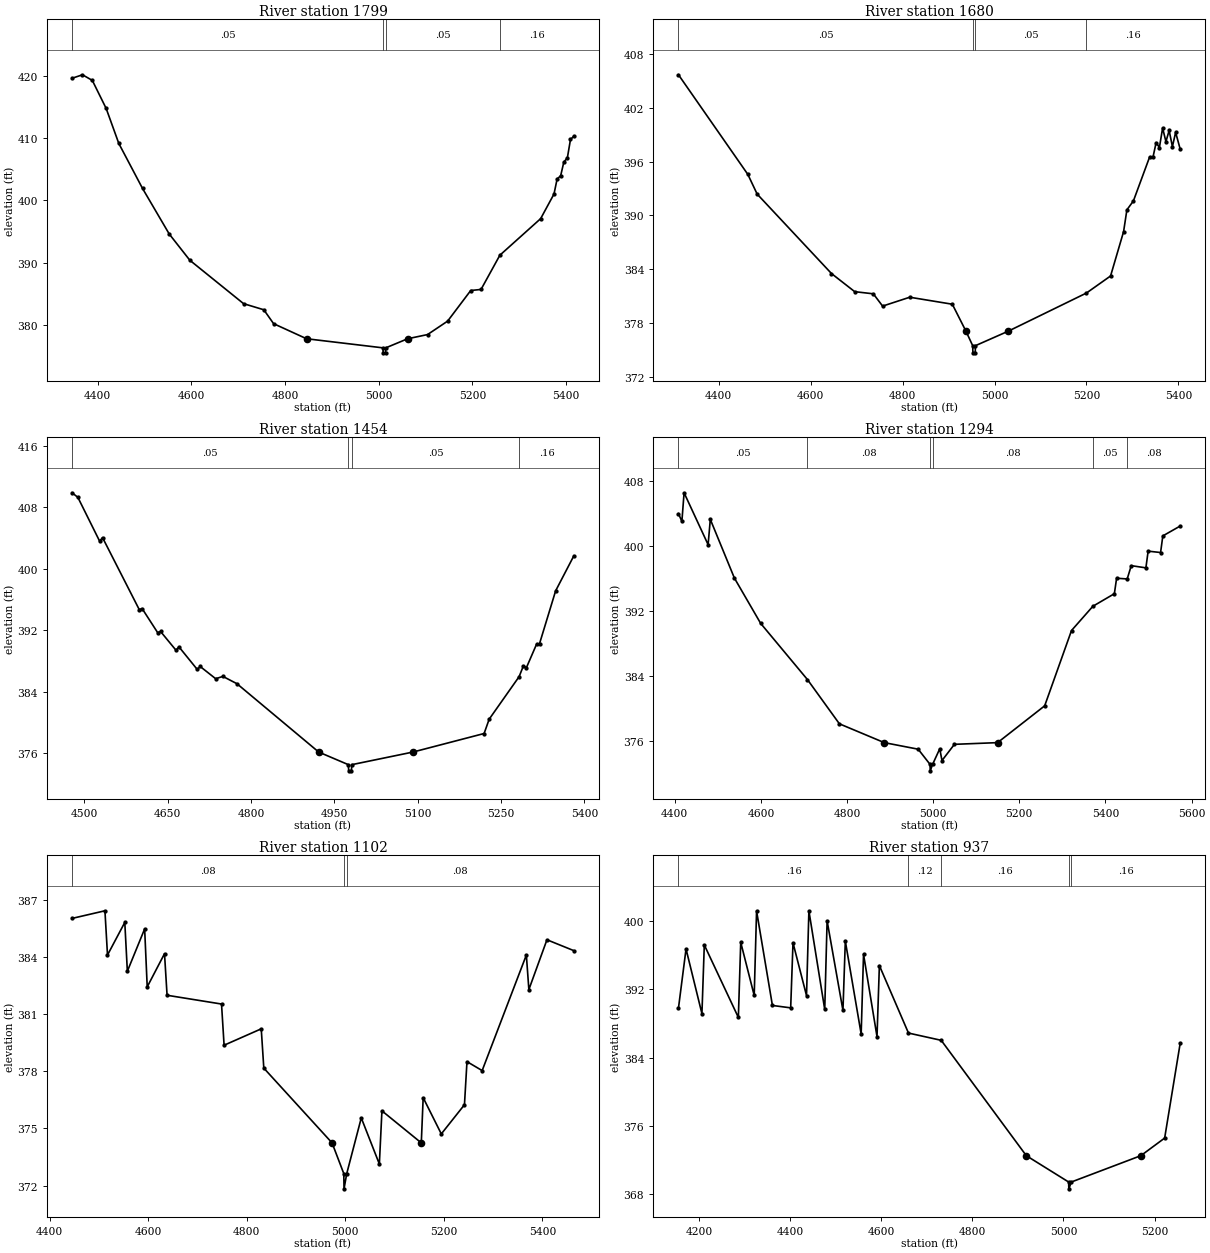
Type RM Length L Ch R = 1,1799,119,119,119
BEGIN DESCRIPTION:
UNT 100 IN DRY CR WATERSHED 4.0
END DESCRIPTION:
XS GIS Cut Line= 3
      2920975.00      6932725.00      2920475.00      6932375.00
      2920175.00      6932725.00
#Sta/Elev= 30
  4345.1  419.56  4367.3  420.12  4388.3  419.22  4417.9  414.72  4444.9  409.10
  4495.5  401.89  4552.6  394.57  4596.6  390.36  4711.3  383.40  4754.5  382.42
  4775.4  380.19  4845.8  377.77  5008.9  376.31  5009.4  375.51  5014.4  375.51
  5014.9  376.31  5061.6  377.77  5104.1  378.44  5147.0  380.60  5196.3  385.51
  5218.3  385.68  5258.5  391.17  5345.6  397.04  5374.1  400.99  5380.7  403.38
  5388.4  403.94  5395.0  406.09  5402.7  406.82  5409.3  409.74  5416.4  410.26
#Mann=4,-1,0
  4345.1    0.05       0  5008.9    0.03       0  5014.9    0.05       0
  5258.5    0.16       0
Bank Sta=4845.8,5061.6
Exp/Cntr=0.3,0.1

Type RM Length L Ch R = 1,1680,226,226,226
BEGIN DESCRIPTION:
Mapping XS d2a0d571
END DESCRIPTION:
XS GIS Cut Line= 3
      2921084.31      6932196.77      2920407.18      6932295.73
      2920115.52      6932579.58
#Sta/Elev= 30
  4312.6  405.68  4463.5  394.57  4483.7  392.38  4645.4  383.52  4695.9  381.50
  4736.4  381.26  4756.6  379.89  4815.6  380.88  4908.2  380.10  4937.8  377.10
  4952.5  375.48  4953.0  374.68  4958.0  374.68  4958.5  375.48  5030.1  377.10
  5200.0  381.35  5252.4  383.25  5280.7  388.19  5287.9  390.62  5302.1  391.62
  5337.3  396.51  5344.5  396.46  5351.5  398.12  5358.6  397.57  5365.6  399.74
  5372.8  398.23  5379.8  399.47  5386.9  397.67  5393.9  399.26  5403.9  397.38
#Mann=4,-1,0
  4312.6    0.05       0  4952.5    0.03       0  4958.5    0.05       0
  5200.0    0.16       0
Bank Sta=4937.8,5030.1
Exp/Cntr=0.3,0.1

Type RM Length L Ch R = 1,1454,160,160,160
BEGIN DESCRIPTION:
UNT 100 IN DRY CR WATERSHED 3.0
END DESCRIPTION:
XS GIS Cut Line= 3
      2920924.99      6931925.00      2920425.00      6932075.00
      2920074.99      6932225.00
#Sta/Elev= 30
  4478.0  409.86  4488.4  409.27  4527.6  403.57  4532.8  404.04  4598.9  394.68
  4604.1  394.81  4632.0  391.69  4637.2  391.84  4665.0  389.40  4670.3  389.84
  4703.3  386.90  4708.5  387.29  4736.4  385.70  4749.4  386.00  4774.7  385.05
  4921.8  376.17  4975.2  374.53  4975.7  373.73  4980.7  373.73  4981.2  374.53
  5091.3  376.17  5219.4  378.58  5228.5  380.44  5282.4  385.97  5290.1  387.37
  5295.6  387.15  5313.7  390.17  5319.1  390.25  5348.1  397.12  5380.8  401.66
#Mann=4,-1,0
  4478.0    0.05       0  4975.2    0.03       0  4981.2    0.05       0
  5282.4    0.16       0
Bank Sta=4921.8,5091.3
Exp/Cntr=0.3,0.1

Type RM Length L Ch R = 1,1294,192,192,192
BEGIN DESCRIPTION:
Mapping XS 04d55360
END DESCRIPTION:
XS GIS Cut Line= 3
      2920977.46      6931868.65      2920396.77      6931965.00
      2919842.08      6932121.25
#Sta/Elev= 30
  4408.7  404.00  4416.6  403.05  4421.7  406.58  4477.5  400.18  4482.6  403.30
  4538.5  396.06  4599.5  390.47  4708.1  383.54  4782.3  378.08  4886.5  375.76
  4965.2  374.95  4992.7  373.08  4993.2  372.28  4998.7  373.08  5015.3  375.00
  5020.5  373.55  5049.3  375.55  5149.6  375.76  5258.9  380.30  5321.2  389.59
  5370.8  392.58  5420.7  394.13  5425.9  396.04  5450.5  395.95  5459.9  397.59
  5493.9  397.32  5499.1  399.38  5528.0  399.21  5533.2  401.26  5573.6  402.48
#Mann=6,-1,0
  4408.7    0.05       0  4708.1    0.08       0  4992.7    0.07       0
  4998.7    0.08       0  5370.8    0.05       0  5450.5    0.08       0
Bank Sta=4886.5,5149.6
Exp/Cntr=0.3,0.1

Type RM Length L Ch R = 1,1102,165,165,165
BEGIN DESCRIPTION:
Mapping XS f02c8e81
END DESCRIPTION:
XS GIS Cut Line= 3
      2920881.13      6931642.09      2920357.70      6931780.11
      2919894.15      6931892.09
#Sta/Elev= 30
  4445.6  386.01  4512.3  386.41  4517.5  384.09  4552.6  385.80  4557.8  383.24
  4592.9  385.46  4598.1  382.42  4633.2  384.16  4638.4  381.98  4748.9  381.52
  4754.1  379.36  4829.5  380.22  4834.7  378.16  4973.2  374.24  4997.0  372.63
  4997.5  371.83  5003.0  372.63  5032.5  375.55  5069.2  373.13  5074.4  375.92
  5154.3  374.24  5158.1  376.61  5194.9  374.71  5241.9  376.24  5247.0  378.50
  5277.8  378.03  5367.5  384.09  5372.6  382.28  5409.3  384.89  5463.8  384.32
#Mann=3,-1,0
  4445.6    0.08       0  4997.0    0.07       0  5003.0    0.08       0
Bank Sta=4973.2,5154.3
Exp/Cntr=0.3,0.1

Type RM Length L Ch R = 1,937,201,201,201
BEGIN DESCRIPTION:
Mapping XS 5f1c4a61
END DESCRIPTION:
XS GIS Cut Line= 4
      2921016.59      6931485.83      2920443.64      6931639.48
      2919990.52      6931761.88      2919971.91      6931796.54
#Sta/Elev= 30
  4154.5  389.81  4171.1  396.72  4206.0  389.15  4211.2  397.19  4286.0  388.71
  4291.2  397.50  4320.8  391.28  4326.0  401.17  4360.8  390.11  4400.9  389.83
  4406.0  397.44  4435.7  391.26  4440.9  401.19  4475.7  389.64  4480.9  400.02
  4515.7  389.53  4520.9  397.64  4555.7  386.77  4560.9  396.10  4590.5  386.46
  4595.7  394.78  4659.6  386.88  4731.5  386.03  4918.4  372.53  5011.3  369.45
  5011.8  368.65  5017.3  369.45  5169.9  372.53  5222.2  374.59  5256.4  385.71
#Mann=5,-1,0
  4154.5    0.16       0  4659.6    0.12       0  4731.5    0.16       0
  5011.3    0.07       0  5017.3    0.16       0
Bank Sta=4918.4,5169.9
Exp/Cntr=0.3,0.1

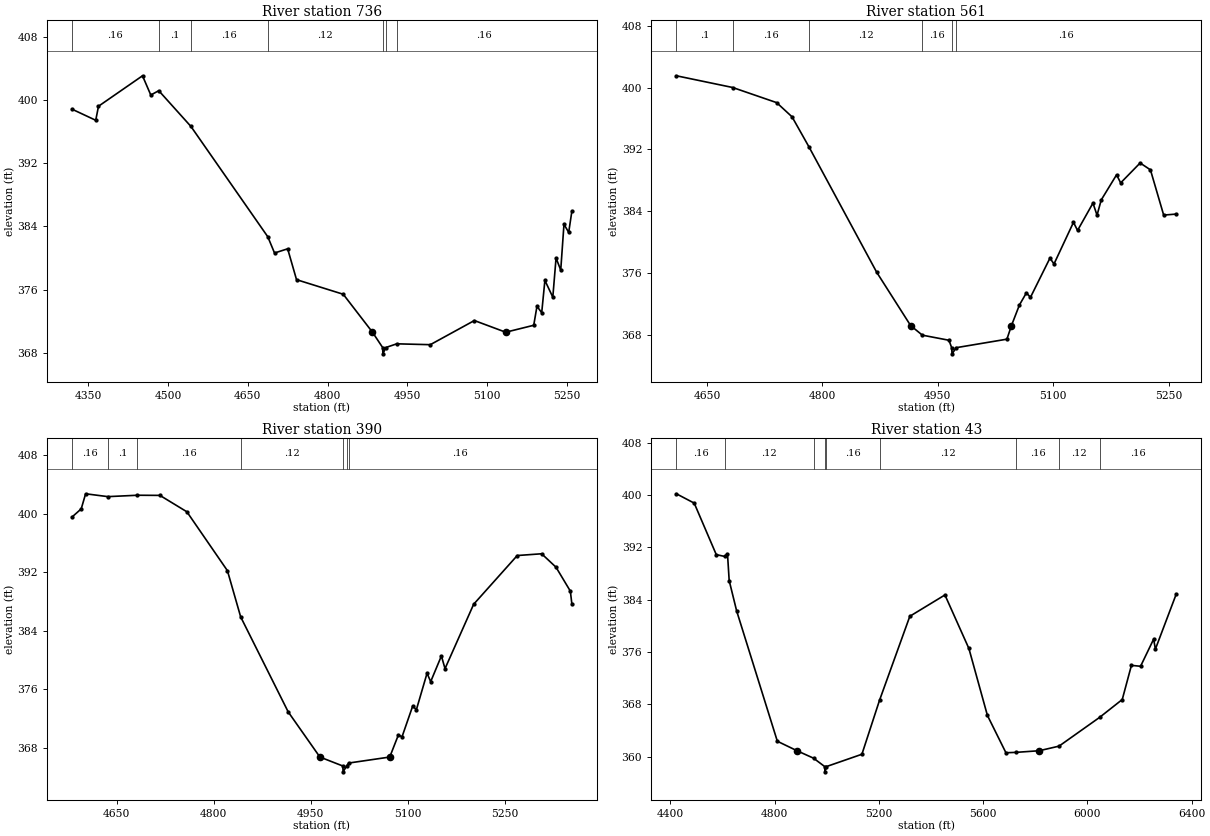
Type RM Length L Ch R = 1,736,175,175,175
BEGIN DESCRIPTION:
Mapping XS f1ca1bd9
END DESCRIPTION:
XS GIS Cut Line= 4
      2920888.91      6931418.14      2920331.66      6931556.15
      2920131.15      6931610.45      2920000.02      6931699.99
#Sta/Elev= 30
  4319.1  398.86  4363.8  397.45  4369.0  399.23  4451.8  403.09  4467.4  400.65
  4482.4  401.20  4542.9  396.67  4687.5  382.69  4700.2  380.63  4724.9  381.16
  4741.6  377.25  4829.5  375.40  4884.5  370.59  4903.6  368.65  4904.1  367.85
  4909.6  368.65  4930.2  369.12  4993.3  369.01  5076.2  372.07  5135.2  370.59
  5187.9  371.47  5194.0  373.88  5202.9  373.06  5208.9  377.16  5223.8  375.03
  5229.9  380.00  5238.7  378.46  5244.8  384.27  5253.7  383.24  5259.7  385.95
#Mann=7,-1,0
  4319.1    0.16       0  4482.4     0.1       0  4542.9    0.16       0
  4687.5    0.12       0  4903.6    0.07       0  4909.6    0.12       0
  4930.2    0.16       0
Bank Sta=4884.5,5135.2
Exp/Cntr=0.3,0.1

Type RM Length L Ch R = 1,561,171,171,171
BEGIN DESCRIPTION:
Mapping XS 2eb34dcd
END DESCRIPTION:
XS GIS Cut Line= 3
      2920705.27      6931427.94      2920351.12      6931424.46
      2920073.38      6931525.15
#Sta/Elev= 30
  4610.3  401.53  4683.5  400.01  4740.6  398.05  4760.6  396.21  4782.4  392.35
  4870.6  376.07  4914.7  369.16  4929.9  367.92  4964.5  367.26  4968.0  366.30
  4968.5  365.50  4974.0  366.30  5039.8  367.40  5045.7  369.16  5056.1  371.84
  5065.1  373.40  5070.4  372.82  5095.7  377.90  5101.0  377.15  5126.3  382.54
  5131.6  381.49  5151.6  385.03  5156.9  383.47  5162.4  385.45  5182.3  388.70
  5187.6  387.65  5212.9  390.23  5226.3  389.34  5243.5  383.48  5259.9  383.61
#Mann=6,-1,0
  4610.3     0.1       0  4683.5    0.16       0  4782.4    0.12       0
  4929.9    0.16       0  4968.0    0.07       0  4974.0    0.16       0
Bank Sta=4914.7,5045.7
Exp/Cntr=0.3,0.1

Type RM Length L Ch R = 1,390,347,347,347
BEGIN DESCRIPTION:
Mapping XS a6a1c355
END DESCRIPTION:
XS GIS Cut Line= 3
      2920785.19      6931403.64      2920392.78      6931285.58
      2920069.93      6931452.21
#Sta/Elev= 30
  4580.6  399.52  4594.9  400.64  4601.7  402.70  4636.1  402.31  4681.9  402.50
  4716.6  402.48  4758.3  400.24  4821.0  392.20  4841.5  385.89  4915.0  372.92
  4964.0  366.76  4999.4  365.54  4999.9  364.74  5005.4  365.54  5008.5  365.94
  5072.0  366.76  5085.4  369.78  5091.0  369.52  5107.5  373.72  5113.2  373.22
  5129.7  378.20  5135.3  377.05  5151.9  380.56  5157.5  378.83  5201.8  387.62
  5269.2  394.27  5306.9  394.51  5329.1  392.68  5351.3  389.41  5353.7  387.64
#Mann=7,-1,0
  4580.6    0.16       0  4636.1     0.1       0  4681.9    0.16       0
  4841.5    0.12       0  4999.4    0.07       0  5005.4    0.12       0
  5008.5    0.16       0
Bank Sta=4964,5072
Exp/Cntr=0.3,0.1

Type RM Length L Ch R = 1,43,0,0,0
BEGIN DESCRIPTION:
UNT 100 IN DRY CR WATERSHED 1.0
END DESCRIPTION:
XS GIS Cut Line= 3
      2920818.98      6931336.88      2920377.30      6930966.69
      2919381.48      6931864.66
#Sta/Elev= 30
  4423.7  400.20  4492.1  398.77  4576.7  390.89  4609.5  390.61  4619.7  391.02
  4626.2  386.92  4654.8  382.28  4810.9  362.34  4886.2  360.89  4949.7  359.75
  4992.7  358.46  4993.2  357.66  4998.7  358.46  5135.2  360.35  5202.7  368.60
  5319.0  381.46  5453.6  384.72  5545.5  376.53  5616.5  366.29  5687.5  360.58
  5726.2  360.64  5815.3  360.89  5891.1  361.59  6046.4  365.98  6133.6  368.72
  6168.8  373.95  6203.9  373.81  6254.0  377.96  6260.7  376.43  6340.9  384.88
#Mann=9,-1,0
  4423.7    0.16       0  4609.5    0.12       0  4949.7    0.16       0
  4992.7    0.07       0  4998.7    0.16       0  5202.7    0.12       0
  5726.2    0.16       0  5891.1    0.12       0  6046.4    0.16       0
Bank Sta=4886.2,5815.3
Exp/Cntr=0.3,0.1

Chan Stop Cuts=-1