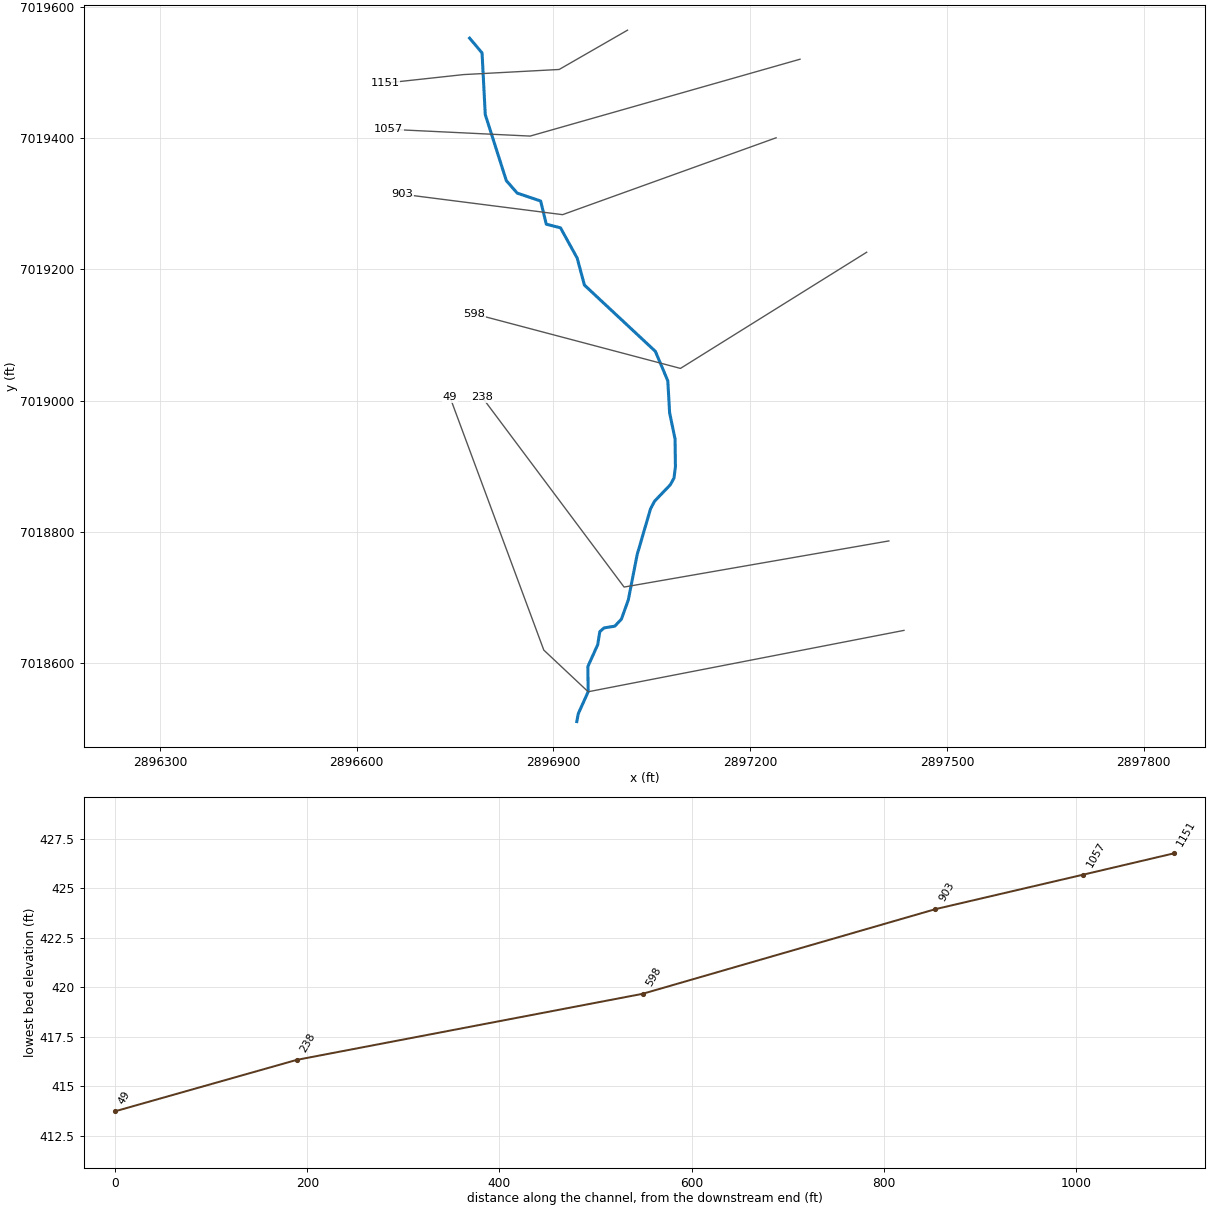
--- UNT 101 IN DRY CR WATERSHED.prj (project) ---

Proj Title=UNT 101 IN DRY CR WATERSHED Base Level Engineering
Current Plan=p01
Default Exp/Contr=0.3,0.1
English Units
Geom File=g01
Flow File=f01
Plan File=p01
BEGIN DESCRIPTION:
UNT 101 IN DRY CR WATERSHED
END DESCRIPTION:

--- UNT 101 IN DRY CR WATERSHED.p01 (plan) ---

Plan Title=Multiple Run
Short Identifier=Multiple
Geom File=g01
Flow File=f01
Subcritical Flow
K Sum by GR= 0
Std Step Tol= 0.01
Critical Tol= 0.01
Num of Std Step Trials= 20
Max Error Tol= 0.3
Flow Tol Ratio= 0.001
Split Flow NTrial= 30
Split Flow Tol= 0.02
Split Flow Ratio= 0.02
Log Output Level= 0
Friction Slope Method= 1
Unsteady Friction Slope Method= 2
Unsteady Bridges Friction Slope Method= 1
Parabolic Critical Depth
Global Vel Dist=  1 , 1 , 1
Global Log Level= 0
CheckData=True
Encroach Param= -1, 0, 0, 0
BEGIN DESCRIPTION:
Multiple Run
END DESCRIPTION:

--- UNT 101 IN DRY CR WATERSHED.f01 (steady flow) ---

Flow Title=Multiple
Number of Profiles=7
Profile Names=10-year,25-year,50-year,1pct_min,100-year,1pct_plu,500-year
River Rch & RM= UNT 101 IN DRY C,Reach-1,1151
     198     249     289     167     333     665     444
Boundary for River Rch & Prof#=UNT 101 IN DRY C,Reach-1,1
Up Type=0
Dn Type=3
Dn Slope=0.005
Boundary for River Rch & Prof#=UNT 101 IN DRY C,Reach-1,2
Up Type=0
Dn Type=3
Dn Slope=0.005
Boundary for River Rch & Prof#=UNT 101 IN DRY C,Reach-1,3
Up Type=0
Dn Type=3
Dn Slope=0.005
Boundary for River Rch & Prof#=UNT 101 IN DRY C,Reach-1,4
Up Type=0
Dn Type=3
Dn Slope=0.005
Boundary for River Rch & Prof#=UNT 101 IN DRY C,Reach-1,5
Up Type=0
Dn Type=3
Dn Slope=0.005
Boundary for River Rch & Prof#=UNT 101 IN DRY C,Reach-1,6
Up Type=0
Dn Type=3
Dn Slope=0.005
Boundary for River Rch & Prof#=UNT 101 IN DRY C,Reach-1,7
Up Type=0
Dn Type=3
Dn Slope=0.005

--- UNT 101 IN DRY CR WATERSHED.g01 (geometry) ---

Geom Title=Existing Conditions

River Reach=UNT 101 IN DRY C,Reach-1
Reach XY= 30
      2896772.23      7019552.51      2896791.15      7019530.07
      2896796.05      7019435.99      2896828.17      7019335.29
      2896844.71      7019316.35      2896880.43      7019304.27
      2896889.10      7019268.93      2896910.76      7019263.36
      2896936.13      7019217.30      2896947.26      7019176.05
      2897055.38      7019075.08      2897074.32      7019030.17
      2897077.11      7018981.28      2897085.40      7018941.41
      2897085.94      7018899.17      2897083.80      7018881.93
      2897078.22      7018871.73      2897054.10      7018846.60
      2897047.93      7018834.82      2897027.66      7018765.39
      2897014.08      7018695.99      2897003.64      7018666.92
      2896993.55      7018656.10      2896977.21      7018653.46
      2896970.67      7018647.79      2896967.46      7018627.86
      2896952.44      7018594.52      2896952.91      7018556.13
      2896937.85      7018522.67      2896935.59      7018510.71

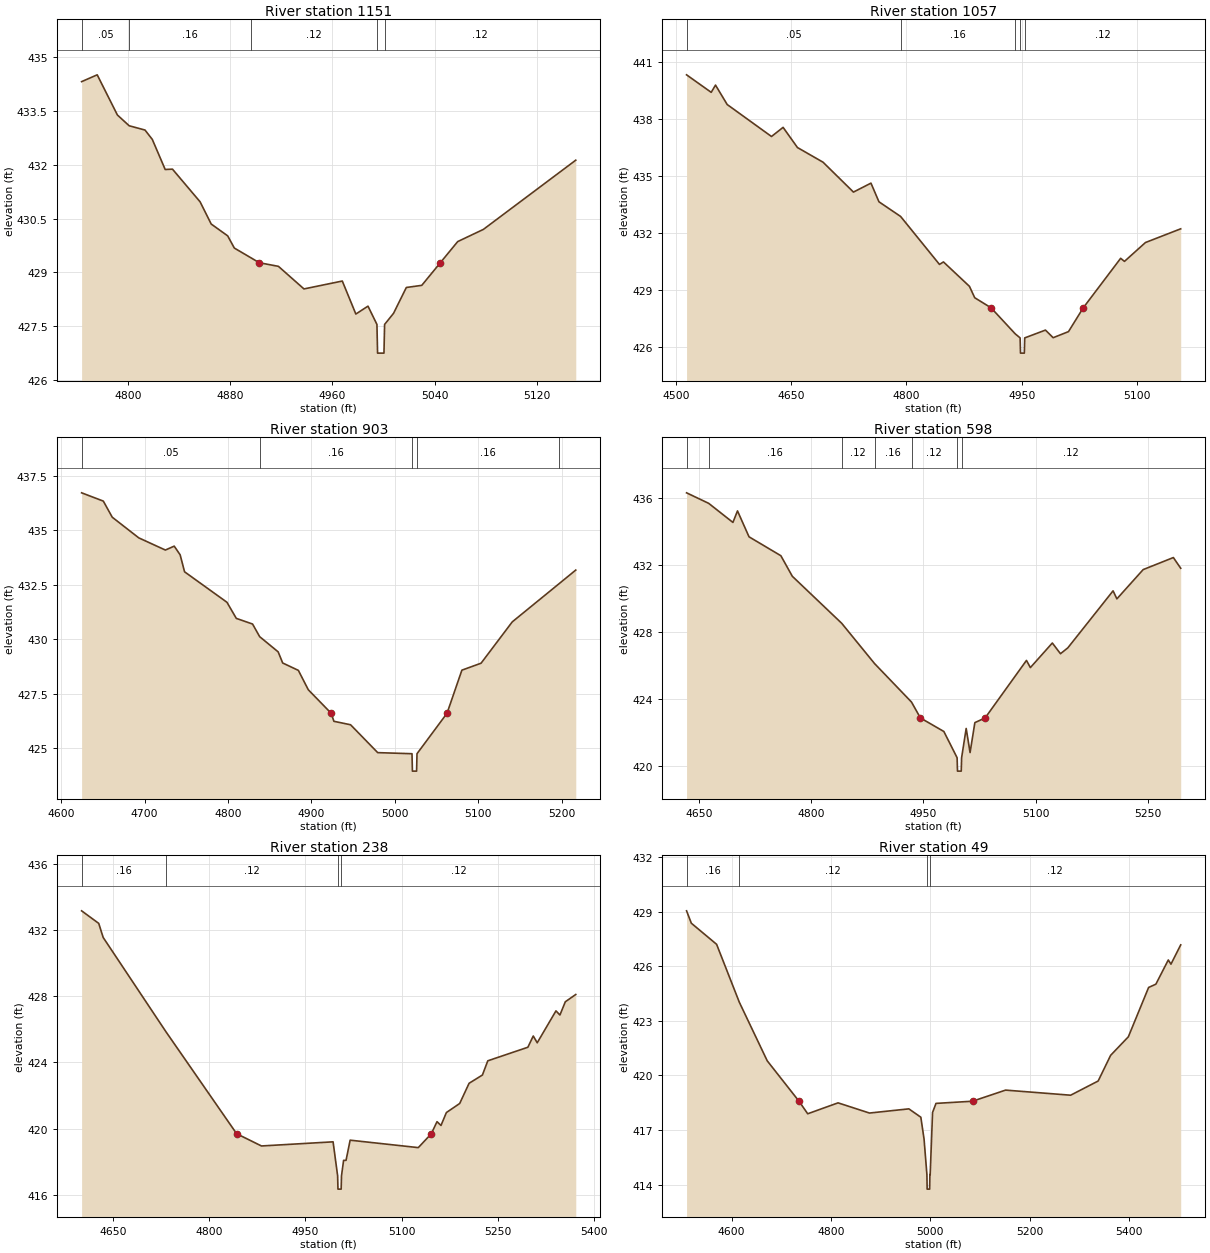
Type RM Length L Ch R = 1,1151,94,94,94
BEGIN DESCRIPTION:
UNT 101 2.0
END DESCRIPTION:
XS GIS Cut Line= 4
      2897012.92      7019564.73      2896908.72      7019504.81
      2896762.89      7019497.00      2896643.14      7019483.98
#Sta/Elev= 30
  4763.7  434.32  4775.9  434.51  4791.7  433.39  4800.9  433.09  4813.3  432.97
  4819.0  432.71  4829.1  431.87  4834.8  431.88  4856.4  430.97  4865.1  430.35
  4878.0  430.02  4883.2  429.68  4896.1  429.41  4902.8  429.27  4917.7  429.17
  4937.7  428.54  4967.7  428.76  4978.3  427.84  4987.8  428.06  4994.8  427.55
  4995.3  426.75  5000.3  426.75  5000.8  427.55  5007.8  427.86  5017.8  428.58
  5029.9  428.64  5044.4  429.27  5058.0  429.86  5078.1  430.20  5150.4  432.13
#Mann=5,-1,0
  4763.7    0.05       0  4800.9    0.16       0  4896.1    0.12       0
  4994.8    0.07       0  5000.8    0.12       0
Bank Sta=4902.8,5044.4
Exp/Cntr=0.3,0.1

Type RM Length L Ch R = 1,1057,154,154,154
BEGIN DESCRIPTION:
Mapping XS 89536e48
END DESCRIPTION:
XS GIS Cut Line= 3
      2897275.89      7019520.43      2896864.45      7019403.25
      2896649.10      7019413.63
#Sta/Elev= 30
  4513.7  440.30  4545.8  439.38  4551.4  439.76  4566.6  438.74  4624.3  437.06
  4639.4  437.54  4658.1  436.48  4691.4  435.71  4731.0  434.14  4753.8  434.61
  4764.2  433.63  4792.4  432.86  4843.0  430.34  4848.2  430.47  4882.0  429.19
  4888.9  428.59  4910.2  428.06  4941.7  426.69  4948.0  426.48  4948.5  425.68
  4953.5  425.68  4954.0  426.48  4981.0  426.89  4991.0  426.49  5011.0  426.81
  5030.2  428.06  5078.9  430.66  5083.9  430.50  5111.2  431.49  5157.1  432.21
#Mann=5,-1,0
  4513.7    0.05       0  4792.4    0.16       0  4941.7    0.12       0
  4948.0    0.07       0  4954.0    0.12       0
Bank Sta=4910.2,5030.2
Exp/Cntr=0.3,0.1

Type RM Length L Ch R = 1,903,305,305,305
BEGIN DESCRIPTION:
Mapping XS f93eebd4
END DESCRIPTION:
XS GIS Cut Line= 3
      2897239.43      7019400.64      2896913.93      7019283.46
      2896669.56      7019314.65
#Sta/Elev= 30
  4624.5  436.73  4650.5  436.35  4661.2  435.61  4693.0  434.66  4724.9  434.10
  4735.5  434.28  4742.6  433.88  4747.9  433.10  4798.7  431.70  4809.9  430.96
  4829.4  430.70  4837.9  430.12  4860.1  429.42  4865.5  428.91  4884.3  428.57
  4896.2  427.68  4923.6  426.60  4926.9  426.23  4946.9  426.07  4979.4  424.79
  5020.5  424.74  5021.0  423.94  5026.0  423.94  5026.5  424.74  5062.5  426.60
  5080.3  428.58  5103.3  428.90  5140.7  430.80  5197.0  432.56  5216.8  433.18
#Mann=5,-1,0
  4624.5    0.05       0  4837.9    0.16       0  5020.5    0.07       0
  5026.5    0.16       0  5197.0    0.12       0
Bank Sta=4923.6,5062.5
Exp/Cntr=0.3,0.1

Type RM Length L Ch R = 1,598,360,360,360
BEGIN DESCRIPTION:
Mapping XS 8386ed24
END DESCRIPTION:
XS GIS Cut Line= 3
      2897377.49      7019226.17      2897093.62      7019049.08
      2896779.30      7019132.21
#Sta/Elev= 30
  4633.8  436.31  4663.4  435.68  4695.7  434.54  4701.8  435.23  4717.2  433.68
  4759.7  432.55  4775.0  431.32  4840.9  428.51  4884.8  426.10  4934.1  423.80
  4946.0  422.85  4977.3  422.04  4995.0  420.47  4995.5  419.67  5000.5  419.67
  5001.0  420.47  5007.1  422.22  5012.3  420.78  5018.7  422.57  5032.4  422.85
  5087.6  426.29  5092.8  425.86  5122.1  427.33  5133.0  426.69  5142.8  427.04
  5203.2  430.45  5208.3  429.97  5243.4  431.72  5283.7  432.44  5293.5  431.80
#Mann=7,-1,0
  4633.8    0.12       0  4663.4    0.16       0  4840.9    0.12       0
  4884.8    0.16       0  4934.1    0.12       0  4995.0    0.07       0
  5001.0    0.12       0
Bank Sta=4946,5032.4
Exp/Cntr=0.3,0.1

Type RM Length L Ch R = 1,238,189,189,189
BEGIN DESCRIPTION:
Mapping XS d3b006a1
END DESCRIPTION:
XS GIS Cut Line= 3
      2897411.35      7018786.07      2897007.68      7018715.75
      2896791.53      7019004.82
#Sta/Elev= 30
  4601.0  433.17  4627.7  432.41  4634.6  431.56  4732.3  425.87  4842.8  419.69
  4881.5  418.95  4993.2  419.20  5000.3  417.14  5000.8  416.34  5005.8  416.34
  5006.3  417.14  5009.6  418.08  5013.4  418.08  5019.8  419.30  5126.1  418.85
  5146.4  419.69  5155.3  420.42  5161.5  420.19  5169.9  420.97  5190.7  421.52
  5205.3  422.74  5226.1  423.24  5234.5  424.10  5297.0  424.92  5305.4  425.60
  5311.6  425.19  5340.8  427.12  5347.0  426.87  5355.4  427.67  5371.7  428.11
#Mann=4,-1,0
  4601.0    0.16       0  4732.3    0.12       0  5000.3    0.07       0
  5006.3    0.12       0
Bank Sta=4842.8,5146.4
Exp/Cntr=0.3,0.1

Type RM Length L Ch R = 1,49,0,0,0
BEGIN DESCRIPTION:
UNT 101 1.0
END DESCRIPTION:
XS GIS Cut Line= 4
      2897434.40      7018649.69      2896952.91      7018556.13
      2896885.28      7018619.65      2896742.13      7019005.58
#Sta/Elev= 30
  4509.5  429.04  4519.1  428.36  4570.0  427.20  4615.7  424.02  4671.9  420.80
  4735.9  418.58  4753.4  417.89  4814.5  418.49  4877.8  417.93  4957.1  418.16
  4981.2  417.70  4987.7  416.49  4993.4  414.55  4993.9  413.75  4998.9  413.75
  4999.4  414.55  5000.0  414.55  5004.8  417.96  5011.7  418.46  5085.3  418.58
  5151.8  419.19  5282.8  418.91  5338.2  419.69  5363.3  421.10  5399.0  422.12
  5439.8  424.83  5454.4  425.01  5479.4  426.34  5484.8  426.11  5504.4  427.17
#Mann=4,-1,0
  4509.5    0.16       0  4615.7    0.12       0  4993.4    0.07       0
  4999.4    0.12       0
Bank Sta=4735.9,5085.3
Exp/Cntr=0.3,0.1

Chan Stop Cuts=-1