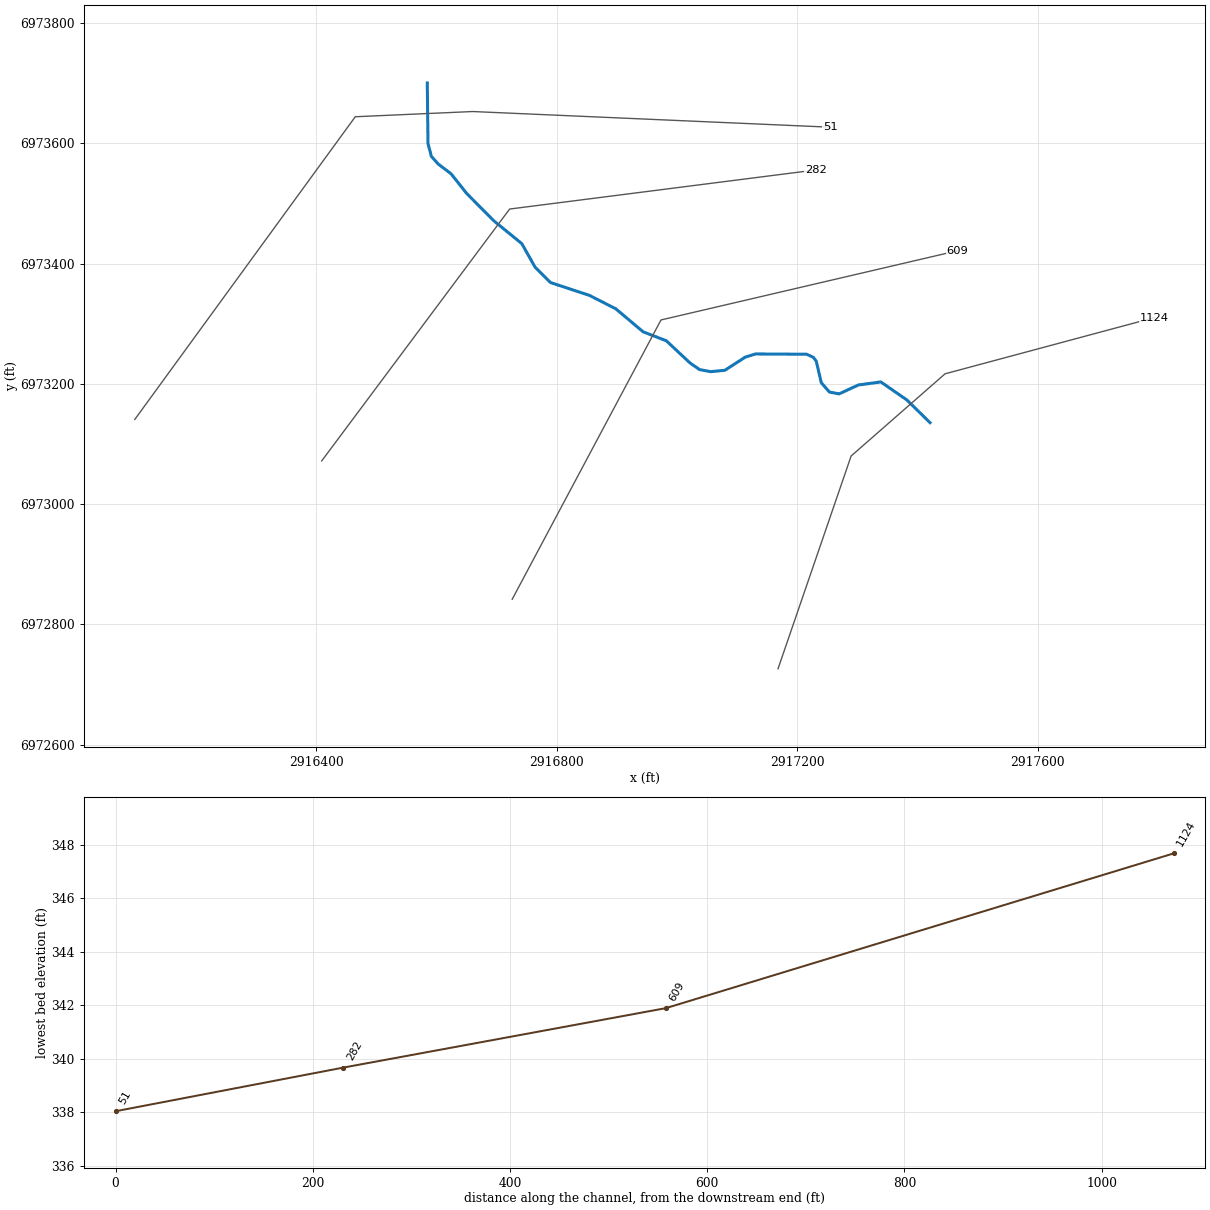
--- UNT 102 IN DRY CR WATERSHED.prj (project) ---

Proj Title=UNT 102 IN DRY CR WATERSHED Base Level Engineering
Current Plan=p01
Default Exp/Contr=0.3,0.1
English Units
Geom File=g01
Flow File=f01
Plan File=p01
BEGIN DESCRIPTION:
UNT 102 IN DRY CR WATERSHED
END DESCRIPTION:

--- UNT 102 IN DRY CR WATERSHED.p01 (plan) ---

Plan Title=Multiple Run
Short Identifier=Multiple
Geom File=g01
Flow File=f01
Subcritical Flow
K Sum by GR= 0
Std Step Tol= 0.01
Critical Tol= 0.01
Num of Std Step Trials= 20
Max Error Tol= 0.3
Flow Tol Ratio= 0.001
Split Flow NTrial= 30
Split Flow Tol= 0.02
Split Flow Ratio= 0.02
Log Output Level= 0
Friction Slope Method= 1
Unsteady Friction Slope Method= 2
Unsteady Bridges Friction Slope Method= 1
Parabolic Critical Depth
Global Vel Dist=  1 , 1 , 1
Global Log Level= 0
CheckData=True
Encroach Param= -1, 0, 0, 0
BEGIN DESCRIPTION:
Multiple Run
END DESCRIPTION:

--- UNT 102 IN DRY CR WATERSHED.f01 (steady flow) ---

Flow Title=Multiple
Number of Profiles=7
Profile Names=10-year,25-year,50-year,1pct_min,100-year,1pct_plu,500-year
River Rch & RM= UNT 102 IN DRY C,Reach-1,1124
     182     227     262     151     301     601     398
Boundary for River Rch & Prof#=UNT 102 IN DRY C,Reach-1,1
Up Type=0
Dn Type=3
Dn Slope=0.005
Boundary for River Rch & Prof#=UNT 102 IN DRY C,Reach-1,2
Up Type=0
Dn Type=3
Dn Slope=0.005
Boundary for River Rch & Prof#=UNT 102 IN DRY C,Reach-1,3
Up Type=0
Dn Type=3
Dn Slope=0.005
Boundary for River Rch & Prof#=UNT 102 IN DRY C,Reach-1,4
Up Type=0
Dn Type=3
Dn Slope=0.005
Boundary for River Rch & Prof#=UNT 102 IN DRY C,Reach-1,5
Up Type=0
Dn Type=3
Dn Slope=0.005
Boundary for River Rch & Prof#=UNT 102 IN DRY C,Reach-1,6
Up Type=0
Dn Type=3
Dn Slope=0.005
Boundary for River Rch & Prof#=UNT 102 IN DRY C,Reach-1,7
Up Type=0
Dn Type=3
Dn Slope=0.005

--- UNT 102 IN DRY CR WATERSHED.g01 (geometry) ---

Geom Title=Existing Conditions

River Reach=UNT 102 IN DRY C,Reach-1
Reach XY= 30
      2917420.59      6973135.71      2917382.13      6973173.37
      2917338.75      6973203.41      2917301.43      6973198.35
      2917269.52      6973183.61      2917253.29      6973186.53
      2917239.75      6973202.14      2917231.28      6973238.23
      2917226.39      6973244.37      2917215.44      6973249.48
      2917130.34      6973249.93      2917113.33      6973244.67
      2917079.36      6973222.77      2917055.68      6973220.51
      2917037.24      6973224.02      2917021.62      6973234.78
      2916981.94      6973271.90      2916943.40      6973286.80
      2916897.96      6973325.05      2916854.18      6973347.34
      2916789.33      6973368.73      2916763.71      6973394.42
      2916741.58      6973433.50      2916694.79      6973471.68
      2916649.85      6973516.99      2916624.13      6973549.49
      2916602.81      6973565.69      2916591.26      6973578.54
      2916585.65      6973599.92      2916584.45      6973700.60

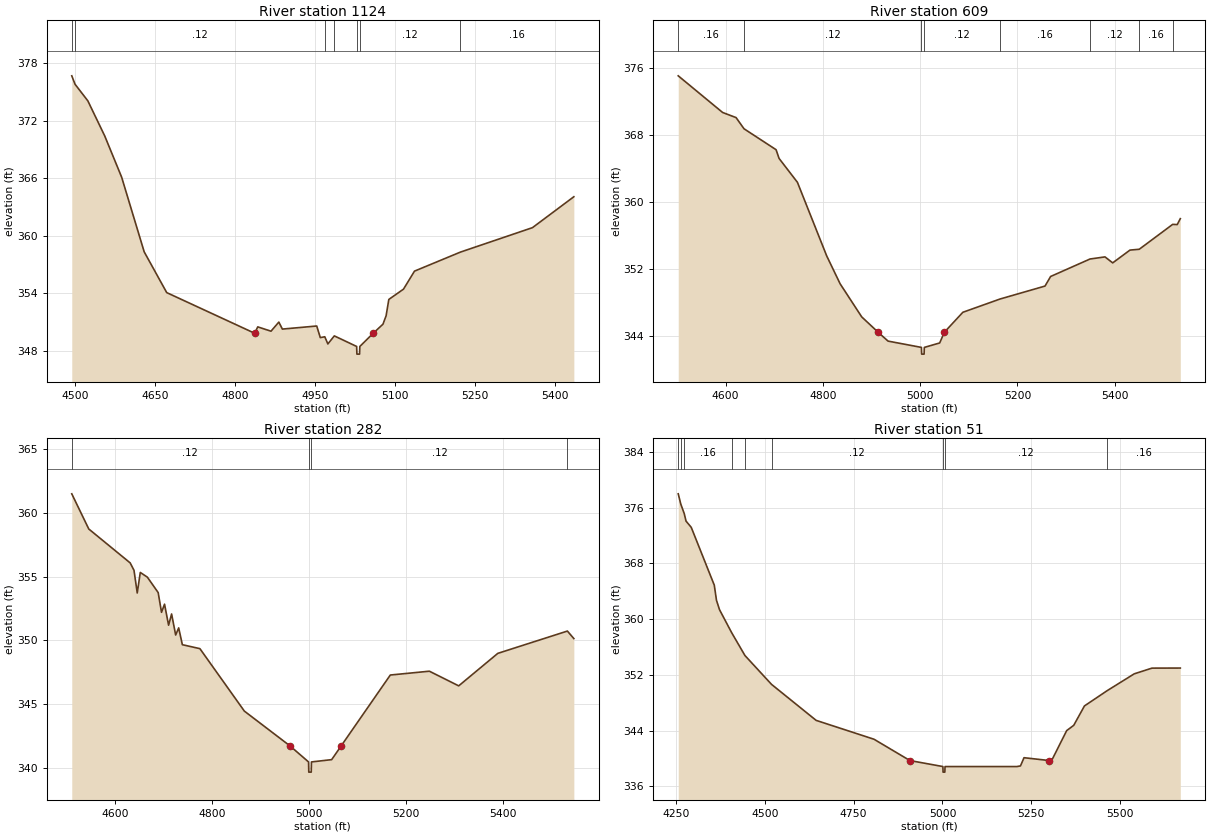
Type RM Length L Ch R = 1,1124,515,515,515
BEGIN DESCRIPTION:
UNT 102 2.0
END DESCRIPTION:
XS GIS Cut Line= 4
      2917167.82      6972726.45      2917289.36      6973080.21
      2917445.61      6973216.93      2917793.80      6973310.43
#Sta/Elev= 30
  4493.6  376.67  4499.8  375.79  4523.8  374.06  4555.5  370.40  4587.2  366.11
  4629.5  358.33  4671.8  354.08  4837.0  349.84  4842.6  350.51  4867.5  350.06
  4882.2  351.01  4888.8  350.28  4953.3  350.60  4960.0  349.39  4968.4  349.48
  4974.2  348.73  4986.3  349.57  5028.2  348.47  5028.7  347.67  5033.7  347.67
  5034.2  348.47  5059.2  349.84  5077.6  350.79  5083.5  351.67  5088.6  353.37
  5116.1  354.44  5136.8  356.32  5222.9  358.30  5358.2  360.85  5435.8  364.07
#Mann=7,-1,0
  4493.6    0.16       0  4499.8    0.12       0  4968.4    0.16       0
  4986.3    0.12       0  5028.2    0.07       0  5034.2    0.12       0
  5222.9    0.16       0
Bank Sta=4837,5059.2
Exp/Cntr=0.3,0.1

Type RM Length L Ch R = 1,609,327,327,327
BEGIN DESCRIPTION:
Mapping XS 3ebf321c
END DESCRIPTION:
XS GIS Cut Line= 3
      2916725.73      6972842.07      2916973.13      6973306.49
      2917465.78      6973421.51
#Sta/Elev= 30
  4502.7  375.01  4593.9  370.65  4621.6  370.04  4637.9  368.71  4703.8  366.22
  4710.0  365.18  4747.7  362.34  4807.9  353.58  4835.5  350.26  4879.9  346.32
  4913.7  344.49  4934.0  343.44  5002.6  342.69  5003.1  341.89  5008.1  341.89
  5008.6  342.69  5040.2  343.22  5049.7  344.49  5087.8  346.87  5164.3  348.45
  5256.7  349.99  5268.2  351.13  5349.2  353.21  5380.0  353.46  5395.8  352.75
  5431.3  354.27  5450.4  354.37  5519.1  357.33  5528.5  357.31  5534.8  358.01
#Mann=8,-1,0
  4502.7    0.16       0  4637.9    0.12       0  5002.6    0.07       0
  5008.6    0.12       0  5164.3    0.16       0  5349.2    0.12       0
  5450.4    0.16       0  5519.1    0.12       0
Bank Sta=4913.7,5049.7
Exp/Cntr=0.3,0.1

Type RM Length L Ch R = 1,282,231,231,231
BEGIN DESCRIPTION:
Mapping XS 1f368399
END DESCRIPTION:
XS GIS Cut Line= 3
      2916408.88      6973072.09      2916721.40      6973490.95
      2917230.66      6973555.96
#Sta/Elev= 30
  4509.8  361.51  4544.9  358.75  4630.3  356.09  4638.2  355.51  4644.9  353.73
  4651.2  355.34  4665.8  354.97  4688.1  353.76  4695.0  352.21  4701.2  352.85
  4709.6  351.20  4715.8  352.08  4724.2  350.43  4730.4  350.99  4738.0  349.67
  4774.2  349.36  4865.9  344.46  4959.7  341.74  4998.4  340.47  4998.9  339.67
  5003.9  339.67  5004.4  340.47  5046.1  340.65  5065.9  341.74  5167.1  347.29
  5247.7  347.59  5308.2  346.44  5388.9  348.99  5532.5  350.74  5545.8  350.15
#Mann=4,-1,0
  4509.8    0.12       0  4998.4    0.07       0  5004.4    0.12       0
  5532.5    0.16       0
Bank Sta=4959.7,5065.9
Exp/Cntr=0.3,0.1

Type RM Length L Ch R = 1,51,0,0,0
BEGIN DESCRIPTION:
UNT 102 1.0
END DESCRIPTION:
XS GIS Cut Line= 4
      2916097.98      6973141.01      2916464.70      6973644.45
      2916660.02      6973653.13      2917254.60      6973627.09
#Sta/Elev= 30
  4256.1  377.99  4263.2  376.53  4273.0  375.15  4278.1  374.07  4292.7  373.18
  4357.6  364.88  4363.8  362.70  4372.3  361.36  4406.5  358.06  4443.9  354.78
  4518.7  350.64  4644.3  345.47  4807.3  342.76  4908.4  339.70  5001.2  338.84
  5001.7  338.04  5006.7  338.04  5007.2  338.84  5209.6  338.84  5219.6  338.93
  5229.6  340.11  5301.0  339.70  5309.7  339.94  5349.7  344.00  5369.6  344.76
  5399.7  347.54  5463.9  349.74  5539.9  352.15  5589.9  352.97  5669.6  352.98
#Mann=9,-1,0
  4256.1    0.16       0  4263.2    0.12       0  4273.0    0.16       0
  4406.5    0.12       0  4443.9    0.16       0  4518.7    0.12       0
  5001.2    0.07       0  5007.2    0.12       0  5463.9    0.16       0
Bank Sta=4908.4,5301
Exp/Cntr=0.3,0.1

Chan Stop Cuts=-1