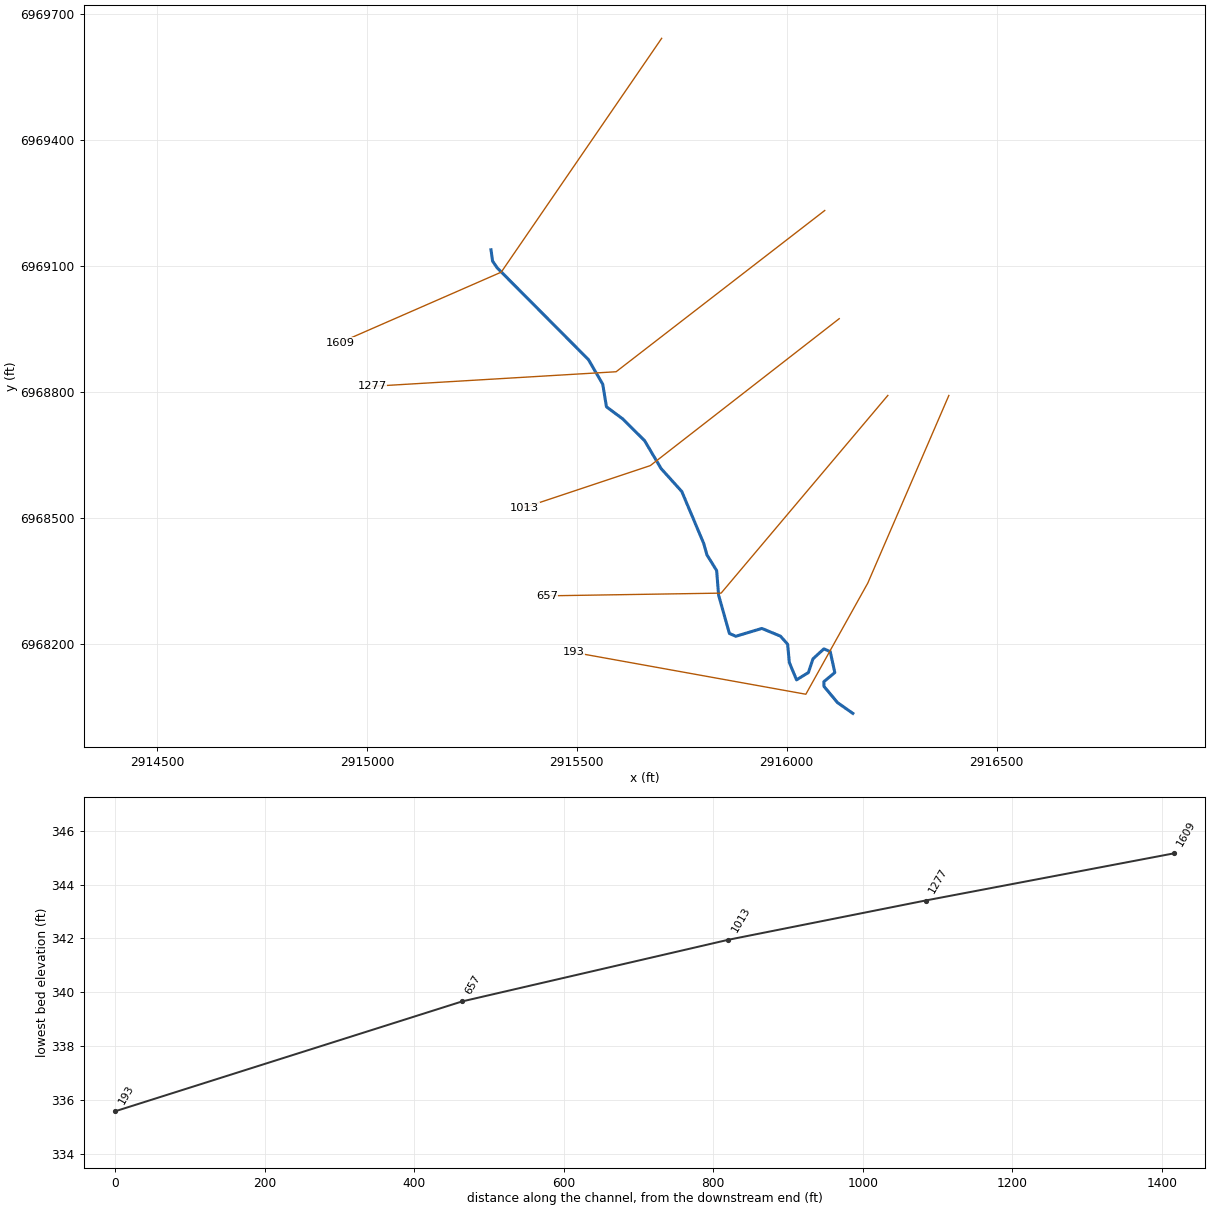
--- UNT 103 IN DRY CR WATERSHED.prj (project) ---

Proj Title=UNT 103 IN DRY CR WATERSHED Base Level Engineering
Current Plan=p01
Default Exp/Contr=0.3,0.1
English Units
Geom File=g01
Flow File=f01
Plan File=p01
BEGIN DESCRIPTION:
UNT 103 IN DRY CR WATERSHED
END DESCRIPTION:

--- UNT 103 IN DRY CR WATERSHED.p01 (plan) ---

Plan Title=Multiple Run
Short Identifier=Multiple
Geom File=g01
Flow File=f01
Subcritical Flow
K Sum by GR= 0
Std Step Tol= 0.01
Critical Tol= 0.01
Num of Std Step Trials= 20
Max Error Tol= 0.3
Flow Tol Ratio= 0.001
Split Flow NTrial= 30
Split Flow Tol= 0.02
Split Flow Ratio= 0.02
Log Output Level= 0
Friction Slope Method= 1
Unsteady Friction Slope Method= 2
Unsteady Bridges Friction Slope Method= 1
Parabolic Critical Depth
Global Vel Dist=  1 , 1 , 1
Global Log Level= 0
CheckData=True
Encroach Param= -1, 0, 0, 0
BEGIN DESCRIPTION:
Multiple Run
END DESCRIPTION:

--- UNT 103 IN DRY CR WATERSHED.f01 (steady flow) ---

Flow Title=Multiple
Number of Profiles=7
Profile Names=10-year,25-year,50-year,1pct_min,100-year,1pct_plu,500-year
River Rch & RM= UNT 103 IN DRY C,Reach-1,1609
     329     426     503     296     590    1178     812
Boundary for River Rch & Prof#=UNT 103 IN DRY C,Reach-1,1
Up Type=0
Dn Type=3
Dn Slope=0.005
Boundary for River Rch & Prof#=UNT 103 IN DRY C,Reach-1,2
Up Type=0
Dn Type=3
Dn Slope=0.005
Boundary for River Rch & Prof#=UNT 103 IN DRY C,Reach-1,3
Up Type=0
Dn Type=3
Dn Slope=0.005
Boundary for River Rch & Prof#=UNT 103 IN DRY C,Reach-1,4
Up Type=0
Dn Type=3
Dn Slope=0.005
Boundary for River Rch & Prof#=UNT 103 IN DRY C,Reach-1,5
Up Type=0
Dn Type=3
Dn Slope=0.005
Boundary for River Rch & Prof#=UNT 103 IN DRY C,Reach-1,6
Up Type=0
Dn Type=3
Dn Slope=0.005
Boundary for River Rch & Prof#=UNT 103 IN DRY C,Reach-1,7
Up Type=0
Dn Type=3
Dn Slope=0.005

--- UNT 103 IN DRY CR WATERSHED.g01 (geometry) ---

Geom Title=Existing Conditions

River Reach=UNT 103 IN DRY C,Reach-1
Reach XY= 30
      2915295.50      6969139.09      2915299.24      6969112.22
      2915309.72      6969096.59      2915527.65      6968877.39
      2915561.66      6968818.96      2915570.54      6968765.00
      2915609.06      6968736.35      2915661.28      6968684.50
      2915700.74      6968617.85      2915749.91      6968563.35
      2915802.27      6968439.34      2915809.81      6968412.46
      2915832.98      6968374.96      2915837.69      6968316.19
      2915863.43      6968225.09      2915878.62      6968218.40
      2915940.66      6968237.07      2915984.96      6968218.77
      2916002.10      6968199.50      2916006.12      6968156.05
      2916023.33      6968114.61      2916051.54      6968131.97
      2916062.39      6968164.52      2916088.43      6968188.39
      2916103.62      6968181.88      2916114.47      6968131.97
      2916088.43      6968110.27      2916088.43      6968099.42
      2916120.98      6968060.35      2916157.44      6968034.75

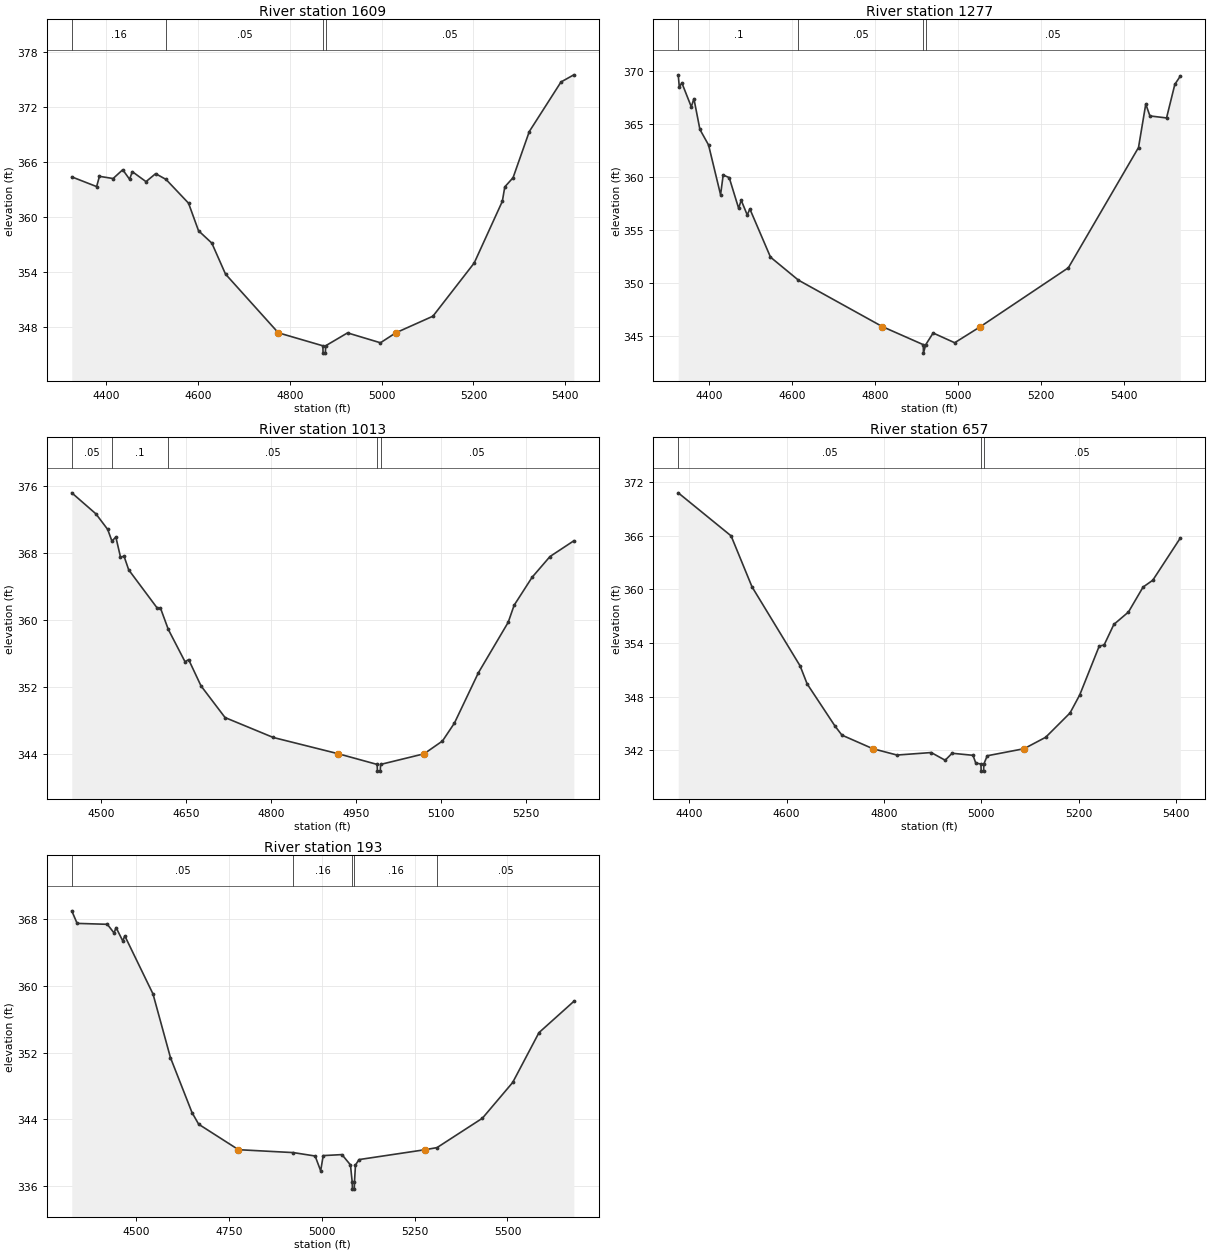
Type RM Length L Ch R = 1,1609,332,332,332
BEGIN DESCRIPTION:
UNT 103 IN DRY CR WATERSHED 3.0
END DESCRIPTION:
XS GIS Cut Line= 3
      2915702.00      6969642.81      2915319.83      6969085.81
      2914936.00      6968918.03
#Sta/Elev= 30
  4324.5  364.40  4378.7  363.34  4384.8  364.46  4414.6  364.22  4435.6  365.18
  4450.5  364.14  4456.5  364.97  4486.3  363.88  4507.3  364.75  4530.0  364.12
  4579.0  361.53  4600.8  358.52  4629.8  357.17  4659.6  353.79  4774.7  347.38
  4871.8  345.96  4872.3  345.16  4877.3  345.16  4877.8  345.96  4925.6  347.37
  4997.3  346.29  5030.9  347.38  5111.7  349.19  5201.7  355.00  5263.0  361.73
  5268.4  363.31  5286.4  364.31  5321.8  369.35  5390.9  374.76  5418.9  375.54
#Mann=4,-1,0
  4324.5    0.16       0  4530.0    0.05       0  4871.8    0.03       0
  4877.8    0.05       0
Bank Sta=4774.7,5030.9
Exp/Cntr=0.3,0.1

Type RM Length L Ch R = 1,1277,264,264,264
BEGIN DESCRIPTION:
Mapping XS a4591ae2
END DESCRIPTION:
XS GIS Cut Line= 3
      2916090.49      6969232.69      2915593.51      6968848.57
      2915011.87      6968813.84
#Sta/Elev= 30
  4324.8  369.68  4327.3  368.55  4333.6  368.91  4356.3  366.66  4362.6  367.43
  4377.1  364.52  4397.9  363.06  4426.9  358.36  4433.2  360.22  4447.7  359.98
  4470.4  357.09  4476.7  357.84  4491.2  356.45  4497.5  357.02  4547.3  352.47
  4614.6  350.30  4817.2  345.91  4915.7  344.21  4916.2  343.41  4921.7  344.21
  4939.5  345.31  4991.5  344.39  5053.5  345.91  5265.7  351.47  5434.8  362.82
  5452.3  366.92  5462.3  365.80  5502.4  365.61  5522.4  368.78  5535.6  369.56
#Mann=4,-1,0
  4324.8     0.1       0  4614.6    0.05       0  4915.7    0.03       0
  4921.7    0.05       0
Bank Sta=4817.2,5053.5
Exp/Cntr=0.3,0.1

Type RM Length L Ch R = 1,1013,356,356,356
BEGIN DESCRIPTION:
UNT 103 IN DRY CR WATERSHED 2.0
END DESCRIPTION:
XS GIS Cut Line= 3
      2916125.02      6968975.02      2915675.00      6968625.00
      2915375.04      6968525.01
#Sta/Elev= 30
  4447.8  375.20  4490.4  372.69  4511.2  370.83  4518.7  369.43  4525.6  369.92
  4533.8  367.53  4540.1  367.62  4548.3  366.00  4598.0  361.49  4604.4  361.43
  4618.2  358.88  4647.8  355.01  4654.1  355.28  4675.9  352.14  4718.4  348.35
  4803.5  345.97  4918.6  344.02  4986.9  342.75  4987.4  341.95  4992.4  341.95
  4992.9  342.75  5069.7  344.02  5102.2  345.55  5123.3  347.69  5165.5  353.69
  5218.2  359.73  5228.7  361.77  5260.4  365.11  5292.0  367.59  5334.1  369.47
#Mann=5,-1,0
  4447.8    0.05       0  4518.7     0.1       0  4618.2    0.05       0
  4986.9    0.03       0  4992.9    0.05       0
Bank Sta=4918.6,5069.7
Exp/Cntr=0.3,0.1

Type RM Length L Ch R = 1,657,464,464,464
BEGIN DESCRIPTION:
Mapping XS 8e6e9887
END DESCRIPTION:
XS GIS Cut Line= 3
      2916240.80      6968792.15      2915843.66      6968321.22
      2915428.54      6968314.74
#Sta/Elev= 30
  4377.3  370.81  4485.9  365.99  4528.8  360.29  4627.7  351.43  4642.0  349.43
  4699.2  344.71  4713.5  343.69  4777.0  342.17  4826.6  341.46  4896.9  341.74
  4925.5  340.88  4939.8  341.66  4982.7  341.43  4988.4  340.56  4999.0  340.46
  4999.5  339.66  5004.5  339.66  5005.0  340.46  5012.0  341.38  5087.6  342.17
  5132.0  343.45  5182.0  346.17  5202.0  348.20  5242.0  353.66  5252.0  353.78
  5272.0  356.08  5302.0  357.47  5332.0  360.26  5352.0  361.03  5408.5  365.75
#Mann=3,-1,0
  4377.3    0.05       0  4999.0    0.03       0  5005.0    0.05       0
Bank Sta=4777,5087.6
Exp/Cntr=0.3,0.1

Type RM Length L Ch R = 1,193,0,0,0
BEGIN DESCRIPTION:
UNT 103 IN DRY CR WATERSHED 1.0
END DESCRIPTION:
XS GIS Cut Line= 4
      2916386.18      6968792.12      2916193.05      6968345.10
      2916045.48      6968080.34      2915492.57      6968180.08
#Sta/Elev= 30
  4326.8  369.03  4341.2  367.52  4422.6  367.41  4440.6  366.37  4446.1  367.02
  4464.1  365.41  4469.6  366.02  4545.5  359.04  4592.5  351.39  4650.5  344.79
  4668.5  343.38  4775.7  340.32  4923.6  339.97  4982.1  339.56  4997.0  337.78
  5003.8  339.61  5054.3  339.73  5077.2  338.49  5082.0  336.38  5082.5  335.58
  5087.5  335.58  5088.0  336.38  5090.7  338.47  5100.1  339.13  5278.3  340.32
  5310.3  340.57  5432.4  344.10  5514.0  348.40  5584.8  354.39  5678.7  358.15
#Mann=5,-1,0
  4326.8    0.05       0  4923.6    0.16       0  5082.0    0.07       0
  5088.0    0.16       0  5310.3    0.05       0
Bank Sta=4775.7,5278.3
Exp/Cntr=0.3,0.1

Chan Stop Cuts=-1