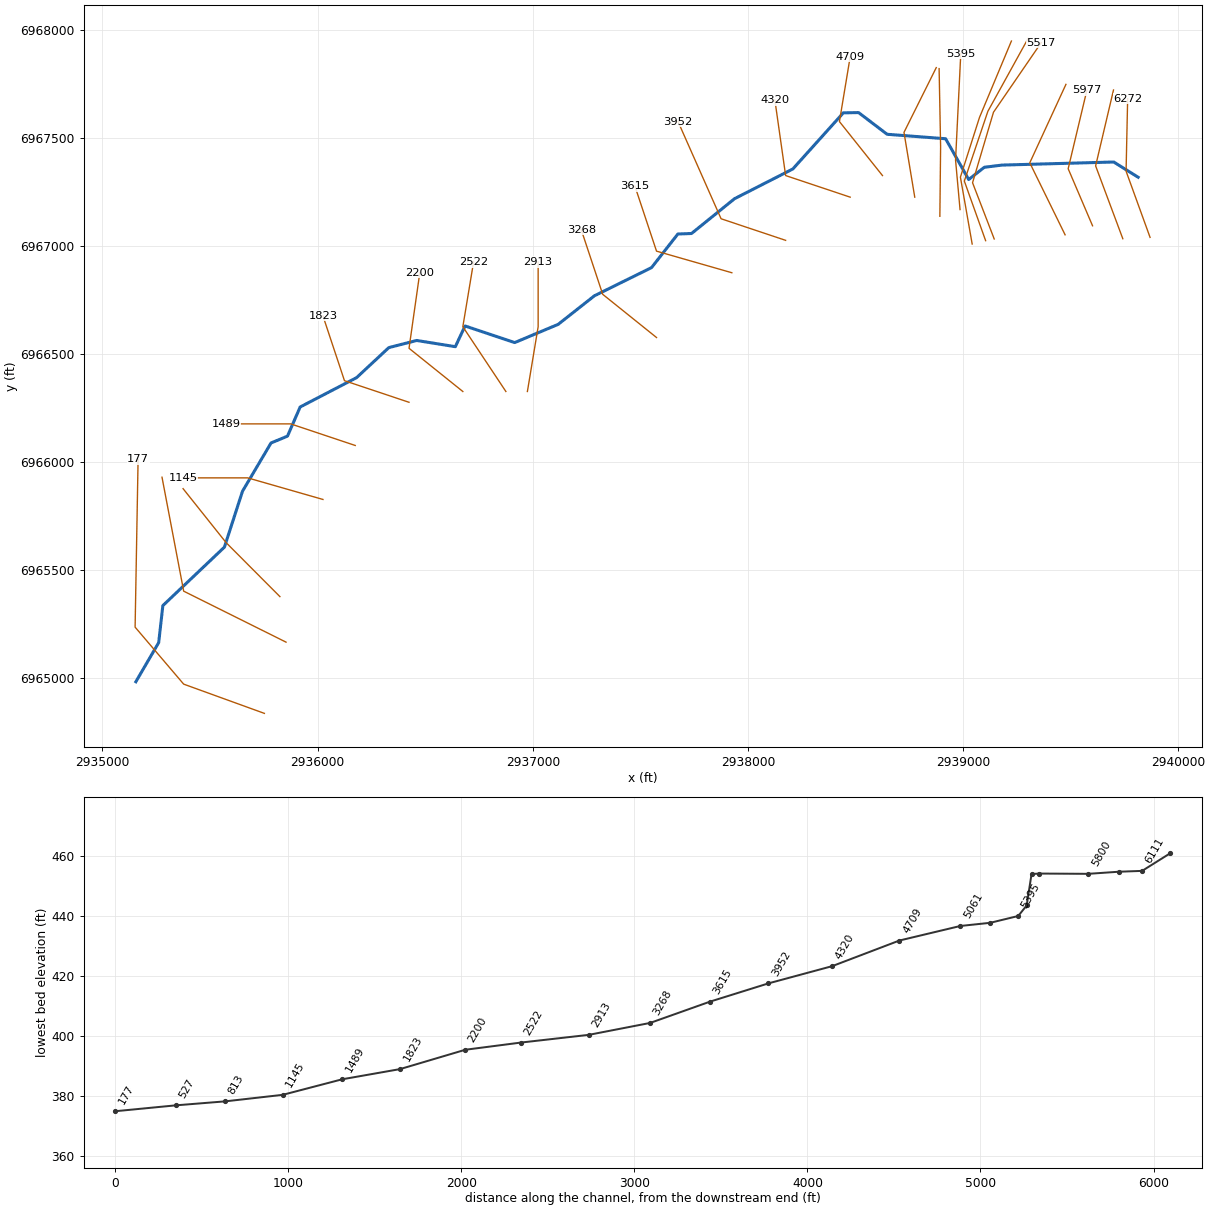
--- UNT 104 IN DRY CR WATERSHED.prj (project) ---

Proj Title=UNT 104 IN DRY CR WATERSHED Base Level Engineering
Current Plan=p01
Default Exp/Contr=0.3,0.1
English Units
Geom File=g01
Flow File=f01
Plan File=p01
BEGIN DESCRIPTION:
UNT 104 IN DRY CR WATERSHED
END DESCRIPTION:

--- UNT 104 IN DRY CR WATERSHED.p01 (plan) ---

Plan Title=Multiple Run
Short Identifier=Multiple
Geom File=g01
Flow File=f01
Subcritical Flow
K Sum by GR= 0
Std Step Tol= 0.01
Critical Tol= 0.01
Num of Std Step Trials= 20
Max Error Tol= 0.3
Flow Tol Ratio= 0.001
Split Flow NTrial= 30
Split Flow Tol= 0.02
Split Flow Ratio= 0.02
Log Output Level= 0
Friction Slope Method= 1
Unsteady Friction Slope Method= 2
Unsteady Bridges Friction Slope Method= 1
Parabolic Critical Depth
Global Vel Dist=  1 , 1 , 1
Global Log Level= 0
CheckData=True
Encroach Param= -1, 0, 0, 0
BEGIN DESCRIPTION:
Multiple Run
END DESCRIPTION:

--- UNT 104 IN DRY CR WATERSHED.f01 (steady flow) ---

Flow Title=Multiple
Number of Profiles=7
Profile Names=10-year,25-year,50-year,1pct_min,100-year,1pct_plu,500-year
River Rch & RM= UNT 104 IN DRY C,Reach-1,6272
     448     597     717     430     858    1713    1229
Boundary for River Rch & Prof#=UNT 104 IN DRY C,Reach-1,1
Up Type=0
Dn Type=3
Dn Slope=0.005
Boundary for River Rch & Prof#=UNT 104 IN DRY C,Reach-1,2
Up Type=0
Dn Type=3
Dn Slope=0.005
Boundary for River Rch & Prof#=UNT 104 IN DRY C,Reach-1,3
Up Type=0
Dn Type=3
Dn Slope=0.005
Boundary for River Rch & Prof#=UNT 104 IN DRY C,Reach-1,4
Up Type=0
Dn Type=3
Dn Slope=0.005
Boundary for River Rch & Prof#=UNT 104 IN DRY C,Reach-1,5
Up Type=0
Dn Type=3
Dn Slope=0.005
Boundary for River Rch & Prof#=UNT 104 IN DRY C,Reach-1,6
Up Type=0
Dn Type=3
Dn Slope=0.005
Boundary for River Rch & Prof#=UNT 104 IN DRY C,Reach-1,7
Up Type=0
Dn Type=3
Dn Slope=0.005

--- UNT 104 IN DRY CR WATERSHED.g01 (geometry) ---

Geom Title=Existing Conditions

River Reach=UNT 104 IN DRY C,Reach-1
Reach XY= 30
      2939813.21      6967317.17      2939699.73      6967387.77
      2939181.20      6967373.57      2939098.18      6967363.32
      2939025.67      6967306.75      2938918.45      6967495.47
      2938646.61      6967516.18      2938514.06      6967616.66
      2938443.13      6967615.50      2938208.45      6967355.54
      2937937.44      6967217.72      2937737.72      6967056.68
      2937674.22      6967054.30      2937551.83      6966898.65
      2937286.53      6966768.26      2937118.11      6966635.99
      2936915.96      6966551.49      2936685.38      6966628.51
      2936640.09      6966532.53      2936460.58      6966561.30
      2936331.20      6966528.25      2936181.23      6966389.07
      2935919.00      6966253.18      2935860.18      6966118.22
      2935783.71      6966086.48      2935651.16      6965863.12
      2935567.11      6965604.19      2935280.99      6965333.42
      2935261.75      6965162.30      2935155.59      6964980.71

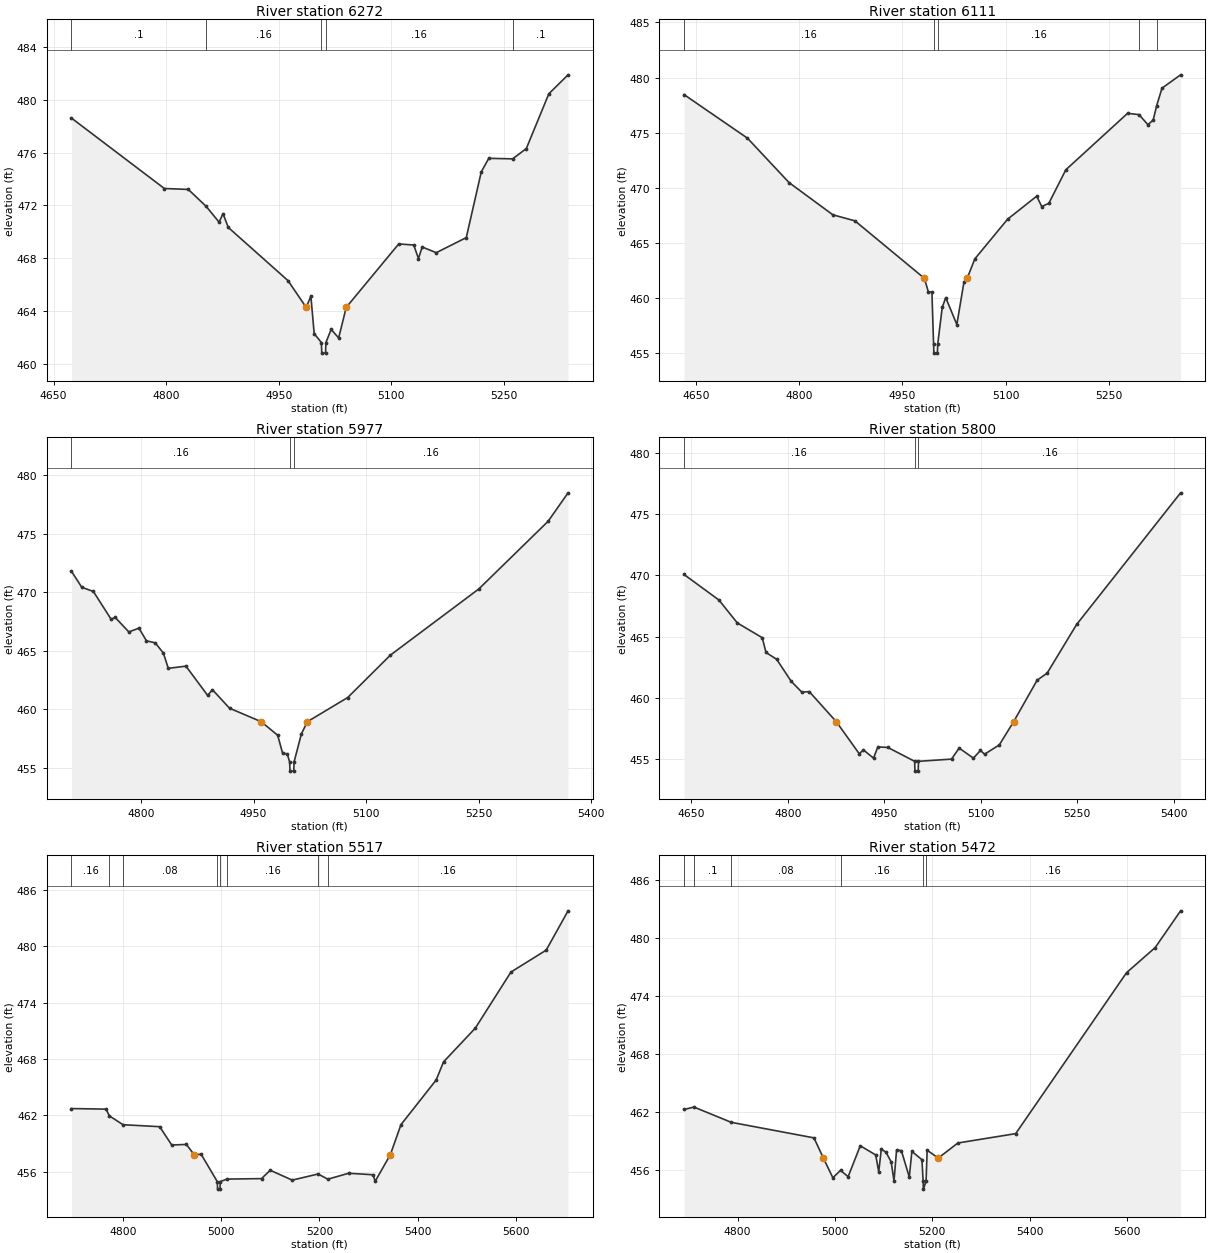
Type RM Length L Ch R = 1,6272,161,161,161
BEGIN DESCRIPTION:
UNT 104 IN DRY CR WATERSHED 16.0
END DESCRIPTION:
XS GIS Cut Line= 3
      2939868.47      6967038.78      2939757.02      6967345.24
      2939764.30      6967680.56
#Sta/Elev= 30
  4673.9  478.60  4797.6  473.28  4829.5  473.21  4853.1  471.94  4870.5  470.74
  4875.8  471.38  4882.7  470.34  4962.3  466.32  4986.5  464.30  4992.8  465.14
  4997.2  462.31  5006.8  461.64  5007.3  460.84  5012.3  460.84  5012.8  461.64
  5019.8  462.63  5029.8  461.99  5039.9  464.30  5109.8  469.09  5129.8  469.01
  5136.1  467.99  5141.1  468.86  5159.8  468.43  5199.8  469.57  5219.8  474.54
  5229.8  475.56  5261.6  475.52  5279.8  476.30  5309.8  480.44  5335.4  481.87
#Mann=5,-1,0
  4673.9     0.1       0  4853.1    0.16       0  5006.8    0.07       0
  5012.8    0.16       0  5261.6     0.1       0
Bank Sta=4986.5,5039.9
Exp/Cntr=0.3,0.1

Type RM Length L Ch R = 1,6111,134,134,134
BEGIN DESCRIPTION:
Mapping XS 366fab28
END DESCRIPTION:
XS GIS Cut Line= 3
      2939741.83      6967032.50      2939615.53      6967369.72
      2939698.55      6967721.25
#Sta/Elev= 30
  4632.7  478.46  4724.8  474.51  4785.3  470.48  4848.9  467.56  4881.0  467.01
  4981.9  461.80  4987.6  460.57  4992.8  460.57  4995.2  455.82  4995.7  455.02
  5000.7  455.02  5001.2  455.82  5007.8  459.17  5012.9  460.05  5029.0  457.61
  5039.3  461.45  5044.0  461.80  5055.2  463.57  5102.7  467.16  5145.0  469.25
  5152.3  468.31  5162.6  468.60  5187.3  471.64  5277.0  476.76  5293.7  476.64
  5306.5  475.73  5314.2  476.15  5319.3  477.46  5327.0  479.04  5354.0  480.25
#Mann=5,-1,0
  4632.7    0.16       0  4995.2    0.07       0  5001.2    0.16       0
  5293.7     0.1       0  5319.3    0.16       0
Bank Sta=4981.9,5044
Exp/Cntr=0.3,0.1

Type RM Length L Ch R = 1,5977,177,177,177
BEGIN DESCRIPTION:
Mapping XS 16bbfdeb
END DESCRIPTION:
XS GIS Cut Line= 3
      2939601.20      6967092.41      2939487.93      6967356.70
      2939575.02      6967720.68
#Sta/Elev= 30
  4707.3  471.79  4721.0  470.43  4736.5  470.07  4760.1  467.70  4765.5  467.86
  4783.7  466.62  4797.2  466.94  4807.2  465.86  4818.9  465.69  4829.8  464.81
  4836.3  463.51  4859.8  463.70  4888.8  461.20  4895.1  461.69  4917.9  460.11
  4960.1  458.96  4982.1  457.80  4988.6  456.28  4994.8  456.21  4998.0  455.54
  4998.5  454.74  5003.5  454.74  5004.0  455.54  5013.7  457.92  5021.7  458.96
  5075.4  461.02  5132.3  464.64  5250.2  470.29  5342.5  476.06  5369.1  478.49
#Mann=3,-1,0
  4707.3    0.16       0  4998.0    0.07       0  5004.0    0.16       0
Bank Sta=4960.1,5021.7
Exp/Cntr=0.3,0.1

Type RM Length L Ch R = 1,5800,283,283,283
BEGIN DESCRIPTION:
Mapping XS 1045bc8b
END DESCRIPTION:
XS GIS Cut Line= 3
      2939473.60      6967050.73      2939309.54      6967384.04
      2939477.50      6967747.29
#Sta/Elev= 30
  4638.7  470.08  4692.9  468.00  4721.5  466.13  4760.3  464.92  4766.1  463.72
  4782.7  463.16  4805.2  461.37  4821.8  460.48  4833.3  460.53  4875.4  458.07
  4911.0  455.46  4917.6  455.77  4933.2  455.10  4940.0  456.02  4955.5  455.97
  4997.1  454.84  4997.6  454.04  5002.6  454.04  5003.1  454.84  5054.4  455.02
  5066.3  455.92  5088.4  455.10  5099.4  455.73  5105.8  455.42  5128.7  456.18
  5150.9  458.07  5187.5  461.46  5203.0  462.03  5248.8  466.00  5410.4  476.74
#Mann=3,-1,0
  4638.7    0.16       0  4997.1    0.07       0  5003.1    0.16       0
Bank Sta=4875.4,5150.9
Exp/Cntr=0.3,0.1

Type RM Length L Ch R = 1,5517,45,45,45
BEGIN DESCRIPTION:
Mapping XS 5ff545d4
END DESCRIPTION:
XS GIS Cut Line= 4
      2939144.27      6967031.38      2939043.59      6967291.76
      2939140.81      6967618.15      2939362.67      6967940.55
#Sta/Elev= 30
  4695.1  462.71  4765.5  462.65  4772.2  461.93  4800.1  460.99  4874.6  460.78
  4899.2  458.83  4929.1  458.89  4944.6  457.81  4959.1  457.84  4992.0  454.93
  4992.5  454.13  4997.5  454.13  4998.0  454.93  5011.6  455.20  5082.0  455.25
  5099.7  456.14  5144.6  455.09  5197.1  455.74  5217.2  455.19  5259.4  455.82
  5309.2  455.66  5313.4  454.96  5344.4  457.81  5366.0  461.00  5437.7  465.76
  5452.6  467.68  5517.4  471.28  5589.9  477.25  5661.6  479.58  5706.2  483.77
#Mann=8,-1,0
  4695.1    0.16       0  4772.2     0.1       0  4800.1    0.08       0
  4992.0    0.07       0  4998.0    0.08       0  5011.6    0.16       0
  5197.1    0.05       0  5217.2    0.16       0
Bank Sta=4944.6,5344.4
Exp/Cntr=0.3,0.1

Type RM Length L Ch R = 1,5472,28,28,28
BEGIN DESCRIPTION:
Mapping XS f0c53e1f
END DESCRIPTION:
XS GIS Cut Line= 4
      2939104.35      6967023.54      2939005.39      6967299.58
      2939114.77      6967622.49      2939301.99      6967960.53
#Sta/Elev= 30
  4689.9  462.22  4710.4  462.47  4787.0  460.89  4957.0  459.28  4976.3  457.19
  4995.8  455.15  5011.6  455.91  5027.2  455.26  5052.2  458.46  5083.9  457.51
  5090.1  455.76  5095.4  458.12  5105.0  457.79  5115.6  456.80  5121.5  454.83
  5126.8  458.04  5136.7  457.95  5152.9  455.22  5158.2  457.88  5178.9  457.02
  5181.4  454.77  5181.9  453.97  5187.4  454.77  5189.6  458.00  5212.5  457.19
  5252.8  458.75  5371.6  459.72  5599.4  476.39  5658.4  479.00  5710.5  482.80
#Mann=6,-1,0
  4689.9    0.08       0  4710.4     0.1       0  4787.0    0.08       0
  5011.6    0.16       0  5181.4    0.07       0  5187.4    0.16       0
Bank Sta=4976.3,5212.5
Exp/Cntr=0.3,0.1

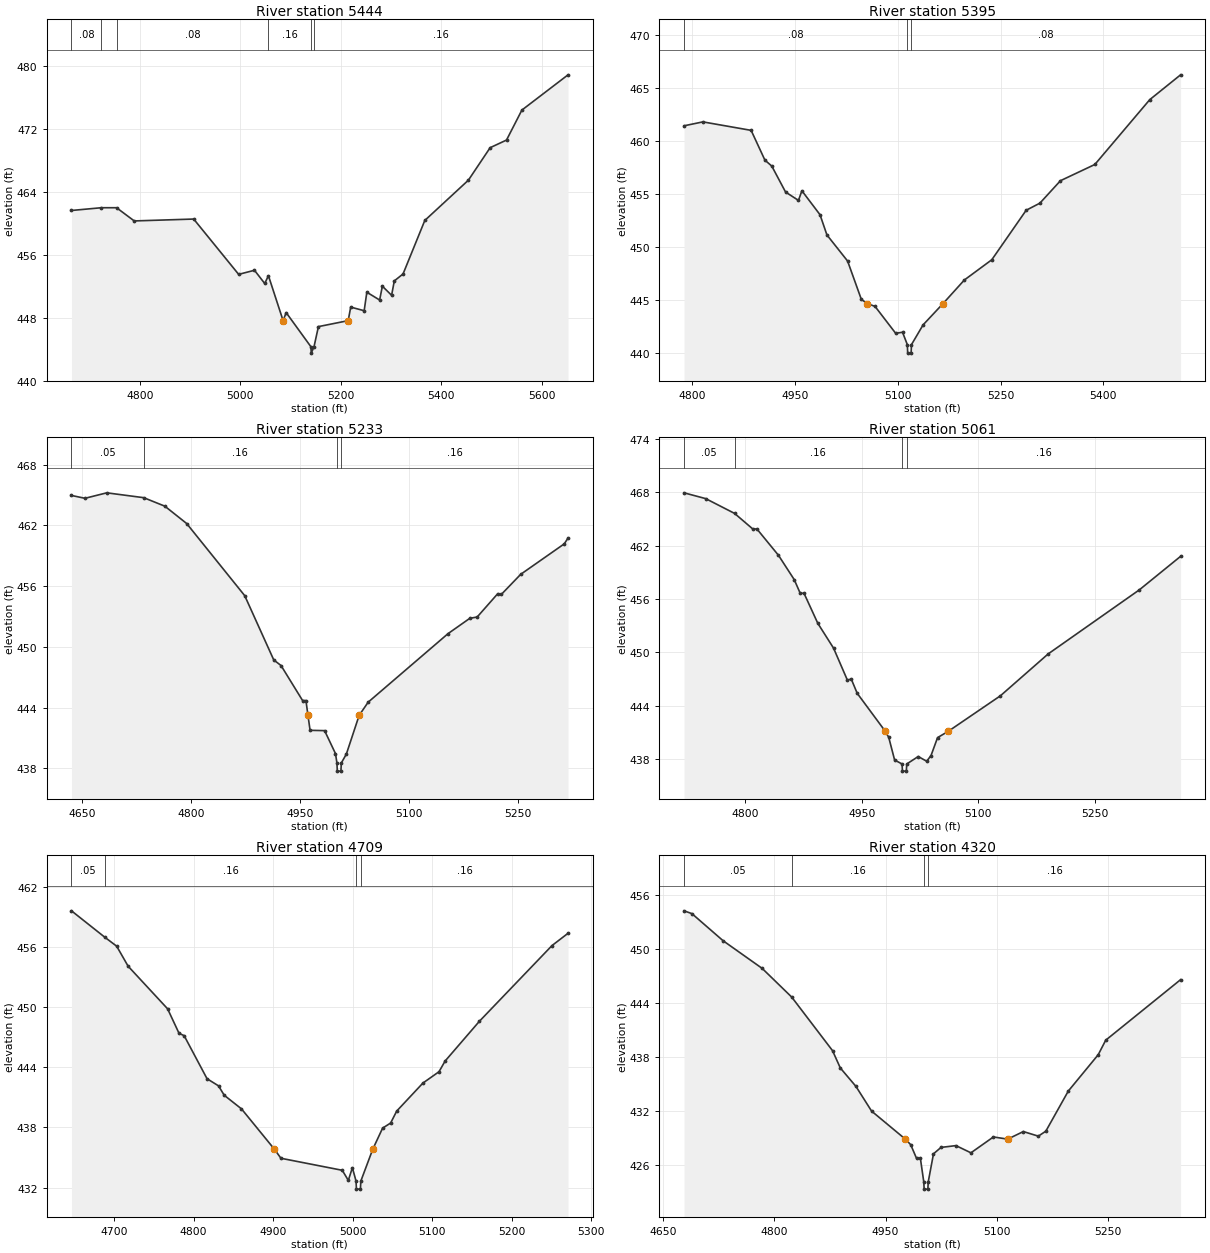
Type RM Length L Ch R = 1,5444,49,49,49
BEGIN DESCRIPTION:
Mapping XS 25102b5e
END DESCRIPTION:
XS GIS Cut Line= 4
      2939041.85      6967007.90      2938987.16      6967317.80
      2939075.70      6967593.85      2939224.14      6967948.01
#Sta/Elev= 30
  4664.2  461.65  4723.7  462.00  4753.9  462.00  4789.1  460.32  4907.5  460.56
  4997.0  453.53  5028.5  454.05  5048.9  452.37  5056.3  453.36  5085.5  447.65
  5091.6  448.67  5141.0  444.32  5141.5  443.52  5147.0  444.32  5155.8  446.89
  5215.1  447.65  5220.1  449.37  5246.9  448.91  5252.2  451.26  5277.7  450.27
  5283.1  452.03  5301.5  450.87  5306.9  452.70  5324.3  453.58  5367.6  460.38
  5454.4  465.50  5497.7  469.63  5530.3  470.60  5560.9  474.41  5652.8  478.89
#Mann=6,-1,0
  4664.2    0.08       0  4723.7     0.1       0  4753.9    0.08       0
  5056.3    0.16       0  5141.0    0.07       0  5147.0    0.16       0
Bank Sta=5085.5,5215.1
Exp/Cntr=0.3,0.1

Type RM Length L Ch R = 1,5395,162,162,162
BEGIN DESCRIPTION:
Mapping XS 613e88e0
END DESCRIPTION:
XS GIS Cut Line= 3
      2938985.43      6967167.58      2938964.59      6967396.80
      2938988.90      6967889.84
#Sta/Elev= 30
  4788.7  461.45  4816.2  461.82  4886.5  461.02  4906.6  458.21  4916.6  457.65
  4936.7  455.20  4955.5  454.41  4960.5  455.32  4986.9  453.06  4997.0  451.15
  5027.1  448.69  5047.1  445.08  5055.6  444.68  5067.1  444.41  5097.2  441.87
  5107.2  441.97  5114.2  440.80  5114.7  440.00  5119.7  440.00  5120.2  440.80
  5137.2  442.67  5166.3  444.68  5197.3  446.90  5237.3  448.81  5287.4  453.48
  5307.4  454.15  5337.4  456.27  5387.5  457.80  5467.6  463.92  5512.5  466.26
#Mann=3,-1,0
  4788.7    0.08       0  5114.2    0.07       0  5120.2    0.08       0
Bank Sta=5055.6,5166.3
Exp/Cntr=0.3,0.1

Type RM Length L Ch R = 1,5233,172,172,172
BEGIN DESCRIPTION:
Mapping XS 6d005f51
END DESCRIPTION:
XS GIS Cut Line= 3
      2938891.68      6967136.41      2938895.15      6967459.30
      2938888.21      6967820.22
#Sta/Elev= 30
  4635.3  464.96  4653.9  464.68  4683.9  465.22  4734.8  464.74  4763.9  463.90
  4793.9  462.19  4873.9  455.06  4913.9  448.71  4923.9  448.16  4953.6  444.70
  4958.2  444.70  4961.0  443.24  4963.9  441.76  4983.9  441.73  4998.9  439.46
  5000.9  438.53  5001.4  437.73  5006.4  437.73  5006.9  438.53  5013.9  439.42
  5031.5  443.24  5043.9  444.54  5153.9  451.31  5184.0  452.83  5194.0  452.95
  5222.4  455.26  5227.4  455.19  5254.0  457.17  5314.0  460.18  5319.2  460.76
#Mann=4,-1,0
  4635.3    0.05       0  4734.8    0.16       0  5000.9    0.07       0
  5006.9    0.16       0
Bank Sta=4961,5031.5
Exp/Cntr=0.3,0.1

Type RM Length L Ch R = 1,5061,352,352,352
BEGIN DESCRIPTION:
UNT 104 IN DRY CR WATERSHED 14.0
END DESCRIPTION:
XS GIS Cut Line= 3
      2938775.00      6967225.02      2938725.00      6967525.00
      2938874.99      6967824.98
#Sta/Elev= 30
  4721.1  467.92  4749.0  467.27  4786.2  465.61  4809.8  463.85  4814.9  463.87
  4842.7  460.91  4863.0  458.18  4870.6  456.67  4875.7  456.63  4893.4  453.27
  4913.7  450.48  4931.4  446.91  4936.5  447.01  4944.1  445.42  4980.3  441.15
  4984.7  440.48  4992.3  437.93  5001.9  437.48  5002.4  436.68  5007.4  436.68
  5007.9  437.48  5022.7  438.32  5033.6  437.79  5039.2  438.43  5047.6  440.44
  5061.4  441.15  5128.6  445.14  5190.1  449.84  5307.5  457.03  5360.6  460.79
#Mann=4,-1,0
  4721.1    0.05       0  4786.2    0.16       0  5001.9    0.07       0
  5007.9    0.16       0
Bank Sta=4980.3,5061.4
Exp/Cntr=0.3,0.1

Type RM Length L Ch R = 1,4709,389,389,389
BEGIN DESCRIPTION:
UNT 104 IN DRY CR WATERSHED 13.0
END DESCRIPTION:
XS GIS Cut Line= 3
      2938624.97      6967325.04      2938425.00      6967575.00
      2938474.99      6967874.96
#Sta/Elev= 30
  4646.6  459.62  4688.7  456.97  4703.4  456.09  4717.8  454.09  4767.4  449.84
  4781.8  447.39  4788.2  447.16  4817.0  442.86  4831.4  442.15  4838.6  441.21
  4860.3  439.85  4901.7  435.82  4909.9  434.92  4987.0  433.72  4994.6  432.71
  4999.7  433.98  5004.3  432.64  5004.8  431.84  5009.8  431.84  5010.3  432.64
  5025.3  435.82  5037.7  437.93  5047.8  438.44  5055.4  439.63  5088.4  442.43
  5108.6  443.56  5116.2  444.62  5159.3  448.59  5250.6  456.15  5270.8  457.38
#Mann=4,-1,0
  4646.6    0.05       0  4688.7    0.16       0  5004.3    0.07       0
  5010.3    0.16       0
Bank Sta=4901.7,5025.3
Exp/Cntr=0.3,0.1

Type RM Length L Ch R = 1,4320,368,368,368
BEGIN DESCRIPTION:
UNT 104 IN DRY CR WATERSHED 12.0
END DESCRIPTION:
XS GIS Cut Line= 3
      2938475.03      6967224.99      2938175.00      6967325.00
      2938125.00      6967674.99
#Sta/Elev= 30
  4678.2  454.19  4688.8  453.88  4730.9  450.87  4783.6  447.80  4823.4  444.62
  4878.5  438.67  4889.0  436.75  4910.1  434.70  4931.2  431.96  4976.7  428.85
  4983.9  428.24  4991.8  426.72  4997.0  426.72  5001.6  424.10  5002.1  423.30
  5007.1  423.30  5007.6  424.10  5014.7  427.22  5024.8  427.93  5045.0  428.13
  5065.2  427.33  5095.5  429.09  5114.8  428.85  5135.9  429.69  5156.1  429.18
  5166.2  429.73  5196.5  434.18  5236.9  438.22  5247.0  439.83  5348.0  446.55
#Mann=4,-1,0
  4678.2    0.05       0  4823.4    0.16       0  5001.6    0.07       0
  5007.6    0.16       0
Bank Sta=4976.7,5114.8
Exp/Cntr=0.3,0.1

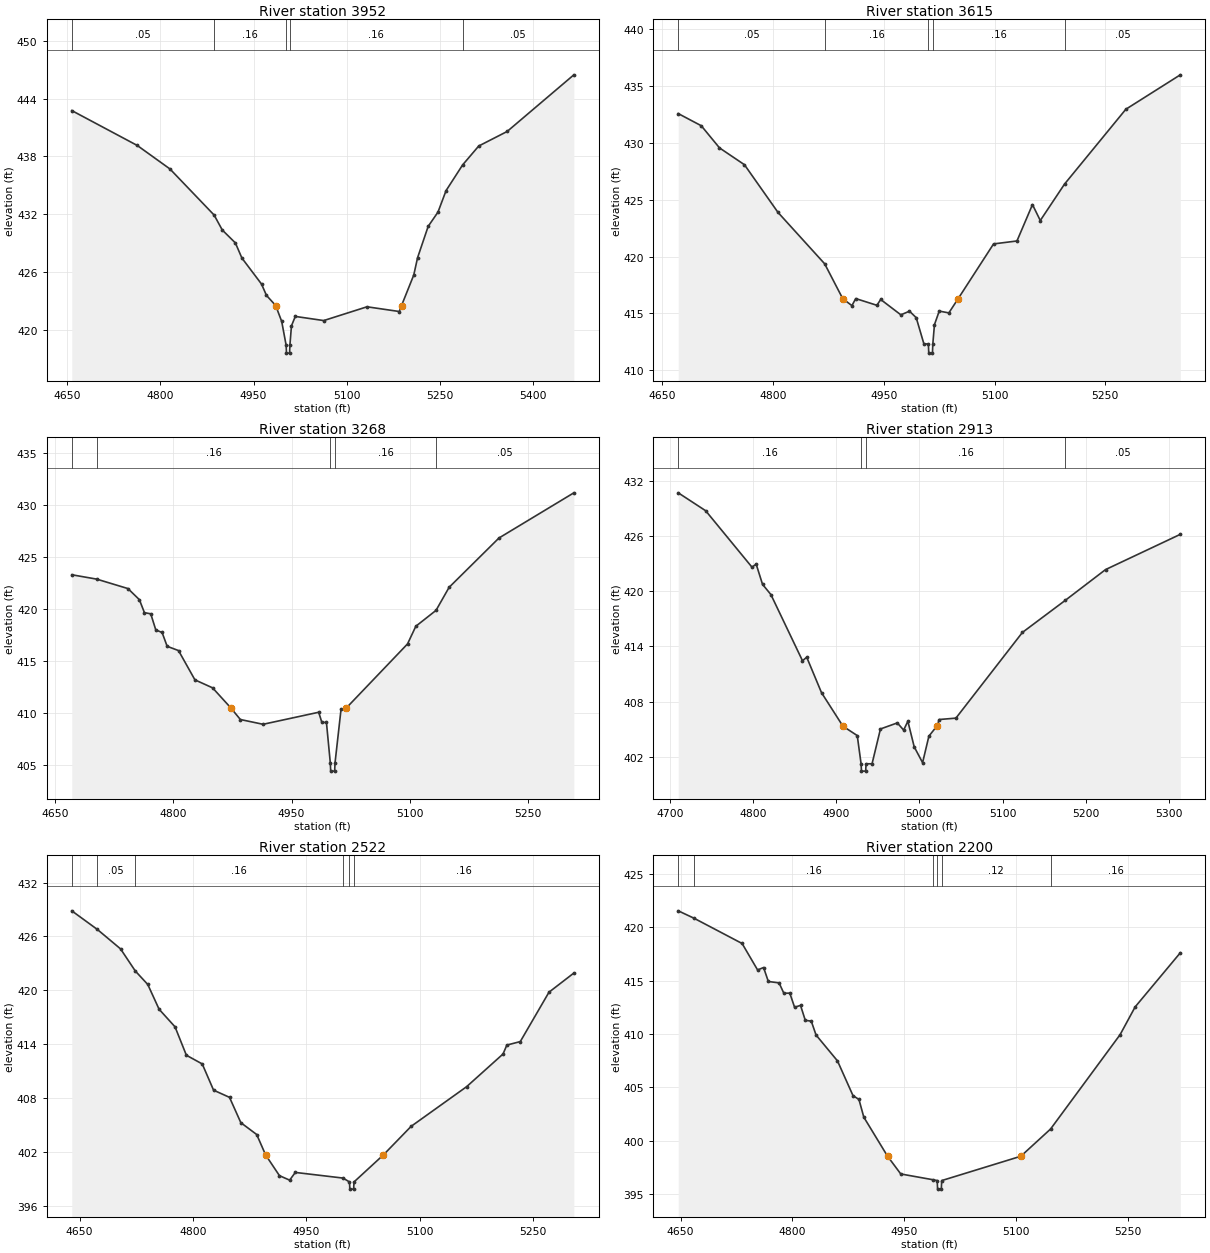
Type RM Length L Ch R = 1,3952,337,337,337
BEGIN DESCRIPTION:
UNT 104 IN DRY CR WATERSHED 11.0
END DESCRIPTION:
XS GIS Cut Line= 3
      2938174.96      6967025.01      2937875.00      6967125.00
      2937675.01      6967574.98
#Sta/Elev= 30
  4657.3  442.75  4762.7  439.13  4815.4  436.69  4886.6  431.90  4899.7  430.35
  4920.8  429.01  4931.3  427.44  4962.9  424.74  4970.8  423.57  4985.7  422.51
  4995.4  420.86  5002.6  418.37  5003.1  417.57  5008.1  417.57  5008.6  418.37
  5011.1  420.40  5017.3  421.38  5063.1  420.95  5132.8  422.38  5184.8  421.89
  5188.4  422.51  5208.1  425.68  5214.2  427.47  5231.3  430.73  5247.1  432.21
  5260.1  434.44  5286.8  437.11  5312.7  439.07  5358.5  440.58  5465.9  446.46
#Mann=5,-1,0
  4657.3    0.05       0  4886.6    0.16       0  5002.6    0.07       0
  5008.6    0.16       0  5286.8    0.05       0
Bank Sta=4985.7,5188.4
Exp/Cntr=0.3,0.1

Type RM Length L Ch R = 1,3615,347,347,347
BEGIN DESCRIPTION:
UNT 104 IN DRY CR WATERSHED 10.0
END DESCRIPTION:
XS GIS Cut Line= 3
      2937924.98      6966875.01      2937575.00      6966975.00
      2937475.00      6967274.99
#Sta/Elev= 30
  4671.5  432.58  4702.7  431.51  4727.4  429.56  4761.2  428.08  4806.7  423.88
  4869.9  419.36  4894.4  416.29  4906.8  415.68  4912.0  416.30  4940.6  415.71
  4945.8  416.22  4973.1  414.87  4984.8  415.19  4993.9  414.62  5004.3  412.32
  5010.4  412.30  5010.9  411.50  5015.9  411.50  5016.4  412.30  5018.6  414.00
  5025.1  415.20  5038.1  415.04  5050.7  416.29  5098.7  421.11  5130.4  421.37
  5151.4  424.57  5162.0  423.17  5194.9  426.38  5277.9  432.96  5351.7  435.99
#Mann=5,-1,0
  4671.5    0.05       0  4869.9    0.16       0  5010.4    0.07       0
  5016.4    0.16       0  5194.9    0.05       0
Bank Sta=4894.4,5050.7
Exp/Cntr=0.3,0.1

Type RM Length L Ch R = 1,3268,355,355,355
BEGIN DESCRIPTION:
UNT 104 IN DRY CR WATERSHED 9.0
END DESCRIPTION:
XS GIS Cut Line= 3
      2937575.01      6966574.99      2937325.00      6966775.00
      2937225.00      6967075.00
#Sta/Elev= 30
  4671.4  423.30  4703.0  422.88  4742.6  421.97  4757.1  420.90  4763.5  419.65
  4771.5  419.54  4777.9  417.99  4785.9  417.74  4792.3  416.41  4806.7  416.00
  4827.5  413.18  4849.9  412.41  4873.0  410.48  4885.1  409.36  4913.9  408.90
  4984.4  410.06  4988.4  409.08  4994.2  409.08  4999.1  405.19  4999.6  404.39
  5004.6  404.39  5005.1  405.19  5012.7  410.34  5019.5  410.48  5097.0  416.64
  5107.5  418.34  5133.1  419.87  5149.7  422.09  5212.9  426.84  5307.8  431.19
#Mann=5,-1,0
  4671.4    0.05       0  4703.0    0.16       0  4999.1    0.07       0
  5005.1    0.16       0  5133.1    0.05       0
Bank Sta=4873,5019.5
Exp/Cntr=0.3,0.1

Type RM Length L Ch R = 1,2913,391,391,391
BEGIN DESCRIPTION:
UNT 104 IN DRY CR WATERSHED 8.0
END DESCRIPTION:
XS GIS Cut Line= 3
      2936975.00      6966324.99      2937025.00      6966625.00
      2937025.00      6966924.95
#Sta/Elev= 30
  4709.8  430.72  4742.8  428.77  4798.5  422.63  4803.6  422.95  4811.2  420.76
  4821.3  419.64  4859.3  412.44  4864.4  412.82  4882.2  408.96  4908.0  405.31
  4925.2  404.29  4929.8  401.22  4930.3  400.42  4935.3  400.42  4935.8  401.22
  4943.0  401.22  4953.1  405.01  4973.4  405.67  4981.0  404.89  4986.1  405.85
  4993.7  403.07  5003.8  401.34  5011.4  404.23  5020.9  405.31  5023.9  406.04
  5043.9  406.19  5123.9  415.52  5175.3  419.00  5223.9  422.36  5313.9  426.20
#Mann=4,-1,0
  4709.8    0.16       0  4929.8    0.07       0  4935.8    0.16       0
  5175.3    0.05       0
Bank Sta=4908,5020.9
Exp/Cntr=0.3,0.1

Type RM Length L Ch R = 1,2522,322,322,322
BEGIN DESCRIPTION:
UNT 104 IN DRY CR WATERSHED 7.0
END DESCRIPTION:
XS GIS Cut Line= 3
      2936874.98      6966325.04      2936675.00      6966625.00
      2936724.99      6966924.95
#Sta/Elev= 30
  4639.6  428.85  4673.4  426.78  4704.2  424.61  4723.7  422.15  4740.2  420.65
  4755.2  417.89  4776.3  415.93  4791.3  412.77  4812.3  411.80  4827.3  408.88
  4848.4  408.08  4863.4  405.26  4884.4  403.94  4896.2  401.67  4914.5  399.36
  4928.0  398.86  4935.5  399.72  4998.7  399.09  5007.2  398.66  5007.7  397.86
  5012.7  397.86  5013.2  398.66  5052.1  401.67  5088.8  404.85  5162.3  409.27
  5210.5  412.91  5215.5  413.90  5233.3  414.29  5271.3  419.79  5304.2  421.92
#Mann=6,-1,0
  4639.6    0.16       0  4673.4    0.05       0  4723.7    0.16       0
  4998.7    0.12       0  5007.2    0.07       0  5013.2    0.16       0
Bank Sta=4896.2,5052.1
Exp/Cntr=0.3,0.1

Type RM Length L Ch R = 1,2200,377,377,377
BEGIN DESCRIPTION:
UNT 104 IN DRY CR WATERSHED 6.0
END DESCRIPTION:
XS GIS Cut Line= 3
      2936675.02      6966324.98      2936425.00      6966525.00
      2936474.99      6966874.96
#Sta/Elev= 30
  4646.8  421.53  4667.9  420.84  4732.5  418.47  4753.3  415.99  4761.3  416.22
  4767.7  414.91  4782.1  414.78  4788.5  413.81  4796.5  413.82  4802.9  412.50
  4810.9  412.67  4817.3  411.27  4825.3  411.20  4831.7  409.90  4860.5  407.47
  4881.3  404.22  4889.3  403.86  4895.8  402.20  4927.7  398.54  4945.4  396.88
  4988.6  396.34  4994.3  396.26  4994.8  395.46  4999.8  395.46  5000.3  396.26
  5106.5  398.54  5146.4  401.09  5239.7  409.93  5259.9  412.53  5320.5  417.60
#Mann=6,-1,0
  4646.8    0.05       0  4667.9    0.16       0  4988.6    0.12       0
  4994.3    0.07       0  5000.3    0.12       0  5146.4    0.16       0
Bank Sta=4927.7,5106.5
Exp/Cntr=0.3,0.1

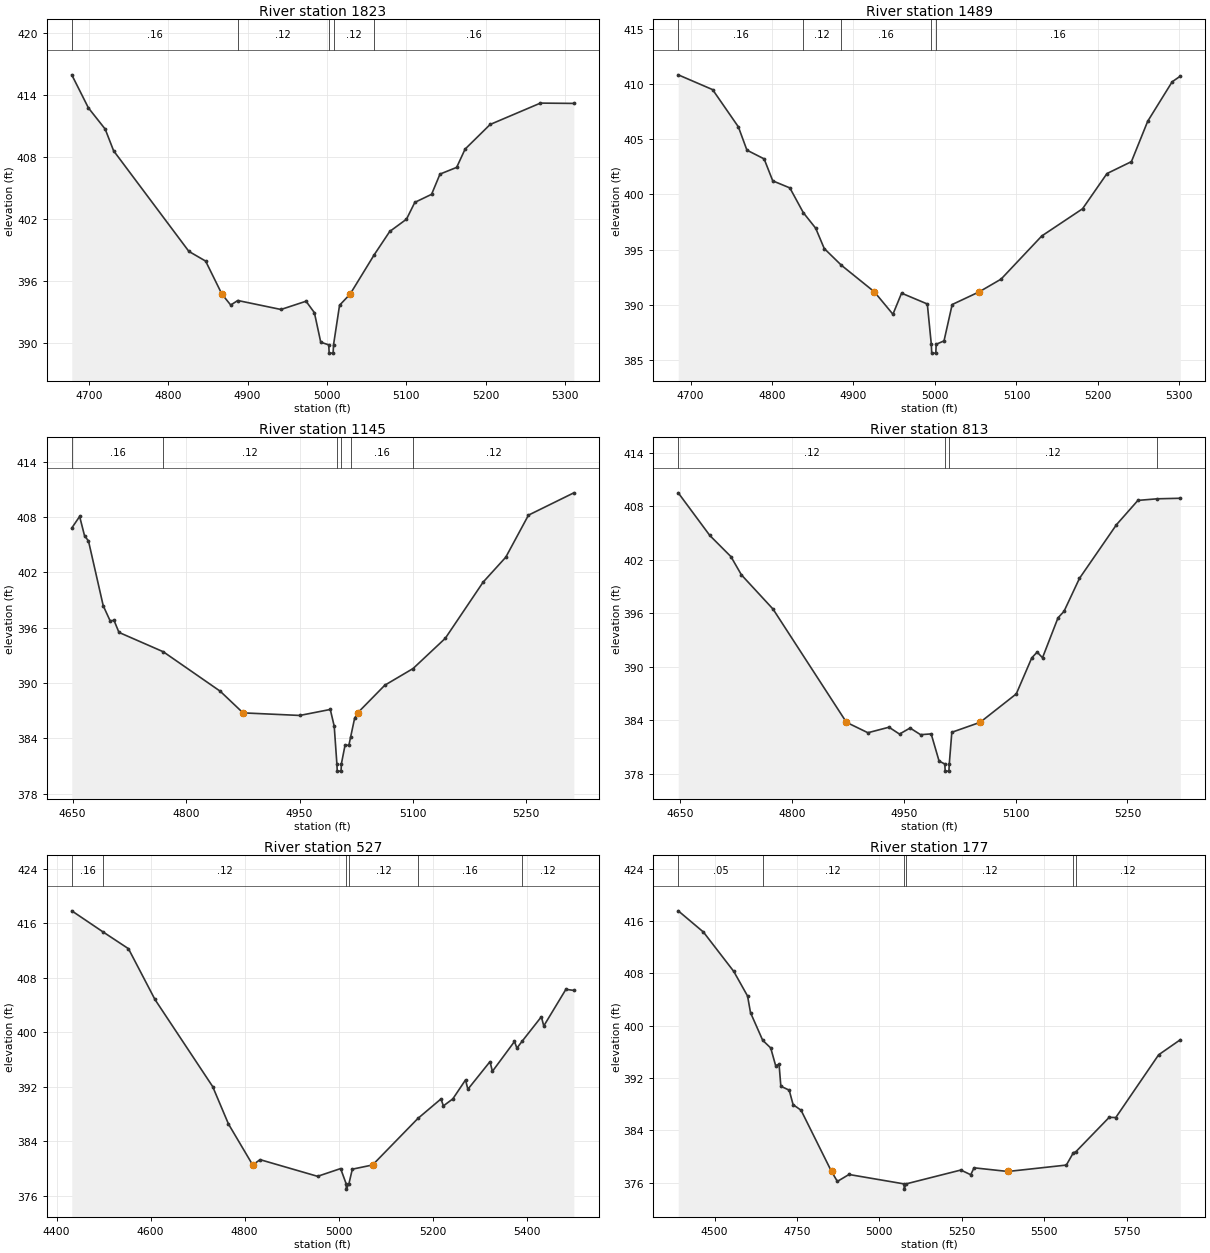
Type RM Length L Ch R = 1,1823,334,334,334
BEGIN DESCRIPTION:
UNT 104 IN DRY CR WATERSHED 5.0
END DESCRIPTION:
XS GIS Cut Line= 3
      2936424.96      6966275.01      2936125.00      6966375.00
      2936025.01      6966674.98
#Sta/Elev= 30
  4678.6  415.99  4699.6  412.78  4720.7  410.73  4731.3  408.63  4826.1  398.88
  4847.2  397.94  4867.7  394.74  4878.8  393.68  4887.7  394.12  4942.1  393.25
  4973.7  394.05  4984.2  392.94  4992.2  390.08  5002.3  389.82  5002.8  389.02
  5007.8  389.02  5008.3  389.82  5015.9  393.66  5029.2  394.74  5059.7  398.57
  5079.1  400.81  5100.2  402.00  5110.7  403.63  5131.8  404.41  5142.4  406.37
  5163.4  407.02  5174.0  408.79  5205.6  411.18  5268.9  413.25  5311.0  413.22
#Mann=5,-1,0
  4678.6    0.16       0  4887.7    0.12       0  5002.3    0.07       0
  5008.3    0.12       0  5059.7    0.16       0
Bank Sta=4867.7,5029.2
Exp/Cntr=0.3,0.1

Type RM Length L Ch R = 1,1489,344,344,344
BEGIN DESCRIPTION:
UNT 104 IN DRY CR WATERSHED 4.0
END DESCRIPTION:
XS GIS Cut Line= 3
      2936175.01      6966075.00      2935875.00      6966175.00
      2935575.04      6966175.00
#Sta/Elev= 30
  4684.9  410.83  4727.1  409.49  4758.7  406.12  4769.2  404.01  4790.3  403.22
  4800.9  401.23  4821.9  400.59  4838.4  398.35  4853.6  396.94  4864.1  395.10
  4885.1  393.59  4925.6  391.18  4948.4  389.15  4959.0  391.06  4990.6  390.08
  4995.5  386.43  4996.0  385.63  5001.0  385.63  5001.5  386.43  5011.1  386.74
  5021.1  390.03  5054.3  391.18  5081.1  392.33  5131.1  396.24  5181.1  398.70
  5211.1  401.89  5241.1  402.97  5261.1  406.63  5291.1  410.20  5301.1  410.71
#Mann=5,-1,0
  4684.9    0.16       0  4838.4    0.12       0  4885.1    0.16       0
  4995.5    0.07       0  5001.5    0.16       0
Bank Sta=4925.6,5054.3
Exp/Cntr=0.3,0.1

Type RM Length L Ch R = 1,1145,332,332,332
BEGIN DESCRIPTION:
UNT 104 IN DRY CR WATERSHED 3.0
END DESCRIPTION:
XS GIS Cut Line= 3
      2936025.04      6965824.99      2935675.00      6965925.00
      2935375.04      6965925.00
#Sta/Elev= 30
  4648.8  406.82  4659.2  408.08  4665.7  405.98  4670.9  405.42  4690.4  398.39
  4699.5  396.76  4704.7  396.80  4711.2  395.50  4769.8  393.40  4845.1  389.12
  4875.3  386.77  4950.4  386.49  4990.7  387.14  4995.9  385.32  4999.4  381.25
  4999.9  380.45  5004.9  380.45  5005.4  381.25  5010.2  383.26  5015.3  383.26
  5017.5  384.11  5022.8  386.16  5026.9  386.77  5062.8  389.77  5100.2  391.58
  5142.8  394.86  5192.8  400.95  5222.8  403.66  5252.8  408.22  5312.8  410.64
#Mann=6,-1,0
  4648.8    0.16       0  4769.8    0.12       0  4999.4    0.07       0
  5005.4    0.12       0  5017.5    0.16       0  5100.2    0.12       0
Bank Sta=4875.3,5026.9
Exp/Cntr=0.3,0.1

Type RM Length L Ch R = 1,813,286,286,286
BEGIN DESCRIPTION:
UNT 104 IN DRY CR WATERSHED 2.0
END DESCRIPTION:
XS GIS Cut Line= 3
      2935824.97      6965375.03      2935575.00      6965625.00
      2935374.98      6965875.03
#Sta/Elev= 30
  4647.3  409.52  4689.7  404.73  4718.0  402.36  4732.1  400.31  4774.5  396.47
  4873.0  383.76  4901.8  382.59  4930.1  383.21  4944.2  382.44  4958.4  383.12
  4972.5  382.37  4986.7  382.46  4997.3  379.41  5005.0  379.08  5005.5  378.28
  5010.5  378.28  5011.0  379.08  5014.4  382.64  5052.4  383.76  5100.9  386.95
  5121.7  391.00  5128.9  391.64  5136.1  391.01  5156.9  395.49  5164.9  396.21
  5185.7  399.92  5235.3  405.94  5264.1  408.67  5290.2  408.85  5321.0  408.91
#Mann=4,-1,0
  4647.3    0.12       0  5005.0    0.07       0  5011.0    0.12       0
  5290.2    0.16       0
Bank Sta=4873,5052.4
Exp/Cntr=0.3,0.1

Type RM Length L Ch R = 1,527,350,350,350
BEGIN DESCRIPTION:
Mapping XS ef55c32c
END DESCRIPTION:
XS GIS Cut Line= 3
      2935853.52      6965164.14      2935377.79      6965400.27
      2935277.09      6965928.03
#Sta/Elev= 30
  4432.2  417.83  4499.0  414.72  4552.8  412.27  4609.2  404.81  4732.0  392.02
  4765.7  386.51  4817.2  380.50  4832.9  381.28  4955.3  378.83  5004.3  379.97
  5016.0  377.75  5016.5  376.95  5022.0  377.75  5029.2  379.88  5072.3  380.50
  5168.7  387.33  5217.9  390.20  5223.0  389.18  5243.0  390.20  5270.1  392.99
  5275.1  391.62  5322.2  395.68  5327.3  394.25  5374.3  398.64  5379.4  397.66
  5390.6  398.68  5431.5  402.27  5436.6  400.92  5483.7  406.30  5500.6  406.14
#Mann=6,-1,0
  4432.2    0.16       0  4499.0    0.12       0  5016.0    0.07       0
  5022.0    0.12       0  5168.7    0.16       0  5390.6    0.12       0
Bank Sta=4817.2,5072.3
Exp/Cntr=0.3,0.1

Type RM Length L Ch R = 1,177,0,0,0
BEGIN DESCRIPTION:
UNT 104 IN DRY CR WATERSHED 1.0
END DESCRIPTION:
XS GIS Cut Line= 4
      2935752.79      6964834.29      2935377.79      6964969.71
      2935152.09      6965233.60      2935165.97      6966010.73
#Sta/Elev= 30
  4389.6  417.56  4466.1  414.31  4558.1  408.29  4599.9  404.53  4608.9  401.98
  4645.8  397.76  4670.2  396.58  4685.0  393.90  4695.5  394.08  4700.9  390.73
  4726.2  390.13  4738.1  387.91  4762.2  387.06  4854.6  377.69  4872.4  376.17
  4907.6  377.23  5074.7  375.79  5075.2  374.99  5080.7  375.79  5247.0  377.91
  5277.0  377.19  5287.0  378.25  5389.8  377.69  5567.0  378.67  5588.5  380.57
  5595.9  380.71  5697.0  385.97  5717.0  385.94  5847.1  395.54  5912.8  397.84
#Mann=6,-1,0
  4389.6    0.05       0  4645.8    0.12       0  5074.7    0.07       0
  5080.7    0.12       0  5588.5    0.16       0  5595.9    0.12       0
Bank Sta=4854.6,5389.8
Exp/Cntr=0.3,0.1

Chan Stop Cuts=-1