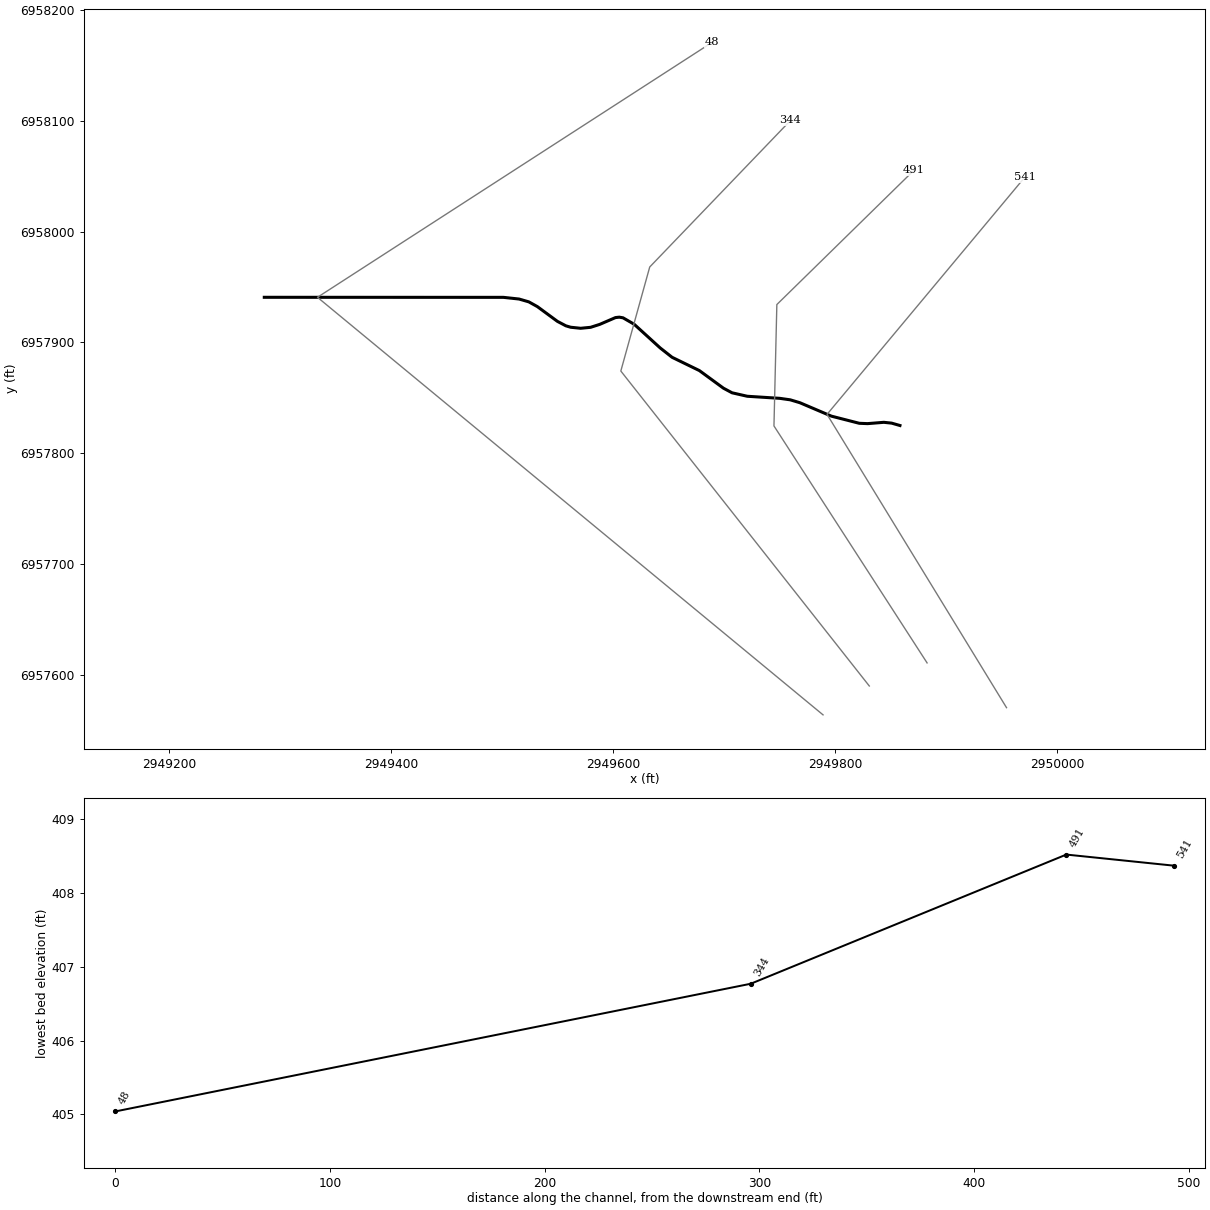
--- UNT 105 IN DRY CR WATERSHED.prj (project) ---

Proj Title=UNT 105 IN DRY CR WATERSHED Base Level Engineering
Current Plan=p01
Default Exp/Contr=0.3,0.1
English Units
Geom File=g01
Flow File=f01
Plan File=p01
BEGIN DESCRIPTION:
UNT 105 IN DRY CR WATERSHED
END DESCRIPTION:

--- UNT 105 IN DRY CR WATERSHED.p01 (plan) ---

Plan Title=Multiple Run
Short Identifier=Multiple
Geom File=g01
Flow File=f01
Subcritical Flow
K Sum by GR= 0
Std Step Tol= 0.01
Critical Tol= 0.01
Num of Std Step Trials= 20
Max Error Tol= 0.3
Flow Tol Ratio= 0.001
Split Flow NTrial= 30
Split Flow Tol= 0.02
Split Flow Ratio= 0.02
Log Output Level= 0
Friction Slope Method= 1
Unsteady Friction Slope Method= 2
Unsteady Bridges Friction Slope Method= 1
Parabolic Critical Depth
Global Vel Dist=  1 , 1 , 1
Global Log Level= 0
CheckData=True
Encroach Param= -1, 0, 0, 0
BEGIN DESCRIPTION:
Multiple Run
END DESCRIPTION:

--- UNT 105 IN DRY CR WATERSHED.f01 (steady flow) ---

Flow Title=Multiple
Number of Profiles=7
Profile Names=10-year,25-year,50-year,1pct_min,100-year,1pct_plu,500-year
River Rch & RM= UNT 105 IN DRY C,Reach-1,541
     504     680     826     500     998    1991    1457
Boundary for River Rch & Prof#=UNT 105 IN DRY C,Reach-1,1
Up Type=0
Dn Type=3
Dn Slope=0.005
Boundary for River Rch & Prof#=UNT 105 IN DRY C,Reach-1,2
Up Type=0
Dn Type=3
Dn Slope=0.005
Boundary for River Rch & Prof#=UNT 105 IN DRY C,Reach-1,3
Up Type=0
Dn Type=3
Dn Slope=0.005
Boundary for River Rch & Prof#=UNT 105 IN DRY C,Reach-1,4
Up Type=0
Dn Type=3
Dn Slope=0.005
Boundary for River Rch & Prof#=UNT 105 IN DRY C,Reach-1,5
Up Type=0
Dn Type=3
Dn Slope=0.005
Boundary for River Rch & Prof#=UNT 105 IN DRY C,Reach-1,6
Up Type=0
Dn Type=3
Dn Slope=0.005
Boundary for River Rch & Prof#=UNT 105 IN DRY C,Reach-1,7
Up Type=0
Dn Type=3
Dn Slope=0.005

--- UNT 105 IN DRY CR WATERSHED.g01 (geometry) ---

Geom Title=Existing Conditions

River Reach=UNT 105 IN DRY C,Reach-1
Reach XY= 30
      2949858.56      6957825.17      2949851.06      6957827.31
      2949844.01      6957828.05      2949829.39      6957826.87
      2949821.90      6957827.17      2949796.83      6957833.59
      2949768.33      6957845.72      2949759.67      6957848.32
      2949750.20      6957849.66      2949720.94      6957851.53
      2949707.22      6957854.65      2949699.49      6957858.78
      2949677.75      6957874.68      2949653.18      6957886.64
      2949642.47      6957895.05      2949618.95      6957916.45
      2949608.94      6957922.23      2949605.57      6957922.81
      2949602.17      6957922.44      2949587.89      6957916.29
      2949579.71      6957913.66      2949570.73      6957912.79
      2949561.75      6957913.73      2949557.43      6957915.01
      2949549.80      6957919.03      2949531.71      6957932.33
      2949524.02      6957936.60      2949515.24      6957939.15
      2949501.14      6957940.67      2949285.59      6957940.71

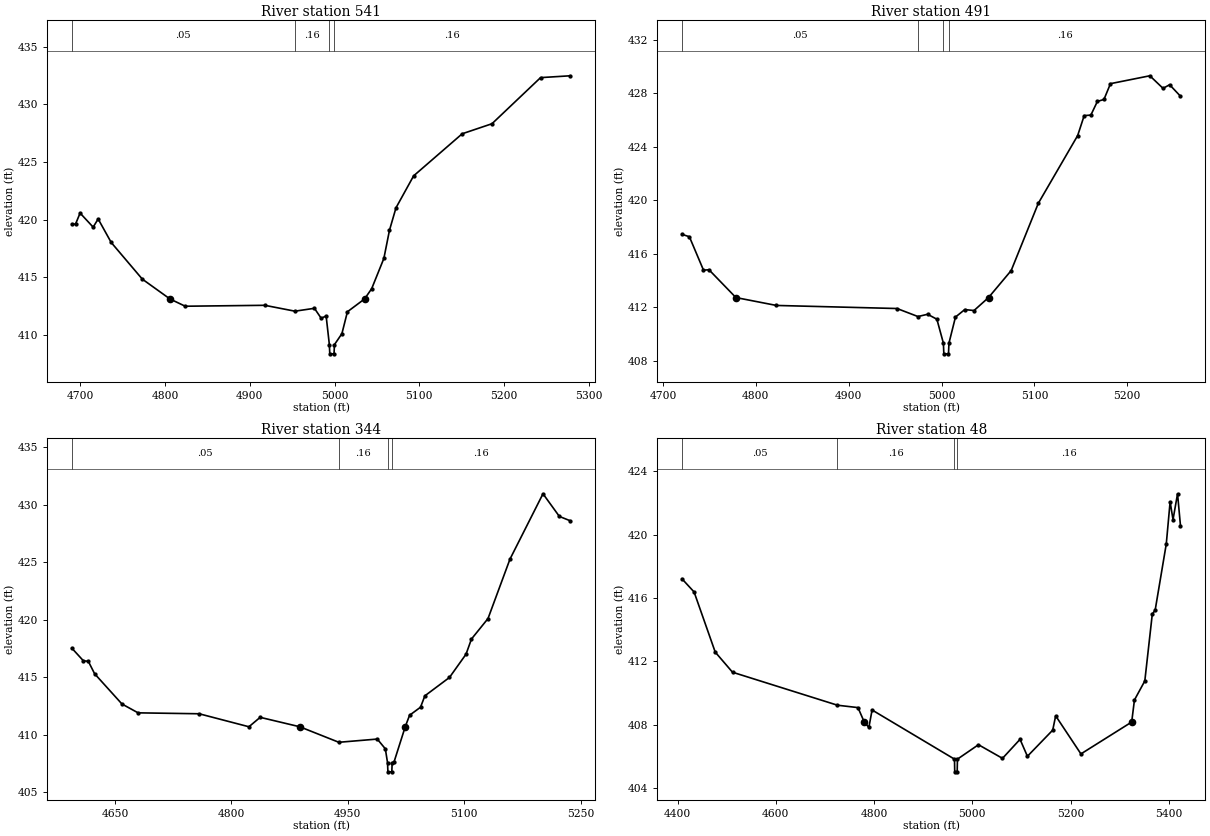
Type RM Length L Ch R = 1,541,50,50,50
BEGIN DESCRIPTION:
UNT 105 IN DRY CR WATERSHED 1.0
END DESCRIPTION:
XS GIS Cut Line= 3
      2949954.61      6957570.90      2949792.83      6957835.22
      2949970.97      6958048.78
#Sta/Elev= 30
  4690.1  419.62  4694.5  419.62  4699.9  420.58  4715.3  419.36  4721.2  420.07
  4736.6  418.03  4773.3  414.85  4805.9  413.13  4823.9  412.50  4917.7  412.58
  4953.3  412.07  4976.3  412.32  4984.2  411.46  4990.1  411.65  4993.9  409.17
  4994.4  408.37  4999.4  408.37  4999.9  409.17  5008.7  410.12  5015.2  412.02
  5035.4  413.13  5043.8  414.02  5058.2  416.65  5064.8  419.09  5072.5  421.04
  5093.3  423.81  5150.6  427.46  5185.7  428.33  5243.0  432.33  5278.1  432.49
#Mann=4,-1,0
  4690.1    0.05       0  4953.3    0.16       0  4993.9    0.07       0
  4999.9    0.16       0
Bank Sta=4805.9,5035.4
Exp/Cntr=0.3,0.1

Type RM Length L Ch R = 1,491,147,147,147
BEGIN DESCRIPTION:
Mapping XS 8e40091a
END DESCRIPTION:
XS GIS Cut Line= 4
      2949883.01      6957611.24      2949744.99      6957824.79
      2949747.59      6957934.17      2949871.28      6958055.29
#Sta/Elev= 30
  4720.5  417.46  4728.5  417.28  4743.7  414.78  4749.6  414.81  4778.6  412.73
  4822.2  412.14  4952.1  411.91  4974.6  411.31  4985.0  411.48  4995.0  411.11
  5002.0  409.32  5002.5  408.52  5007.5  408.52  5008.0  409.32  5015.0  411.27
  5025.0  411.83  5035.0  411.76  5050.6  412.73  5075.0  414.75  5104.2  419.78
  5146.6  424.85  5153.6  426.34  5160.8  426.38  5167.8  427.40  5174.9  427.55
  5181.9  428.73  5224.3  429.32  5238.5  428.38  5245.6  428.65  5257.3  427.79
#Mann=4,-1,0
  4720.5    0.05       0  4974.6    0.16       0  5002.0    0.07       0
  5008.0    0.16       0
Bank Sta=4778.6,5050.6
Exp/Cntr=0.3,0.1

Type RM Length L Ch R = 1,344,296,296,296
BEGIN DESCRIPTION:
Mapping XS ca9cfbd0
END DESCRIPTION:
XS GIS Cut Line= 4
      2949830.92      6957590.43      2949606.96      6957874.27
      2949633.01      6957968.02      2949759.89      6958100.09
#Sta/Elev= 30
  4594.5  417.53  4609.4  416.43  4615.8  416.38  4623.9  415.30  4659.1  412.67
  4679.9  411.90  4758.5  411.82  4822.6  410.69  4837.1  411.51  4888.1  410.69
  4938.4  409.34  4987.9  409.62  4998.3  408.77  5001.1  407.57  5001.6  406.77
  5006.6  406.77  5007.1  407.57  5009.3  407.59  5023.9  410.69  5029.5  411.69
  5043.6  412.39  5049.2  413.38  5080.9  414.98  5102.2  417.00  5109.2  418.32
  5130.5  420.10  5158.8  425.27  5201.3  430.95  5222.4  428.98  5236.5  428.60
#Mann=4,-1,0
  4594.5    0.05       0  4938.4    0.16       0  5001.1    0.07       0
  5007.1    0.16       0
Bank Sta=4888.1,5023.9
Exp/Cntr=0.3,0.1

Type RM Length L Ch R = 1,48,0,0,0
BEGIN DESCRIPTION:
UNT 105 IN DRY CR WATERSHED 2.0
END DESCRIPTION:
XS GIS Cut Line= 3
      2949789.23      6957564.40      2949333.53      6957940.72
      2949689.28      6958170.49
#Sta/Elev= 30
  4409.0  417.21  4433.7  416.38  4476.7  412.59  4511.9  411.32  4725.5  409.24
  4767.2  409.09  4780.0  408.18  4789.4  407.84  4795.9  408.94  4963.6  405.84
  4964.1  405.04  4969.1  405.04  4969.6  405.84  5012.4  406.75  5061.3  405.89
  5097.0  407.09  5112.0  406.02  5163.5  407.67  5169.5  408.57  5220.9  406.17
  5324.2  408.18  5329.8  409.57  5350.9  410.77  5366.1  414.98  5372.0  415.24
  5394.6  419.41  5402.4  422.07  5408.3  420.94  5417.5  422.57  5423.5  420.55
#Mann=4,-1,0
  4409.0    0.05       0  4725.5    0.16       0  4963.6    0.07       0
  4969.6    0.16       0
Bank Sta=4780,5324.2
Exp/Cntr=0.3,0.1

Chan Stop Cuts=-1