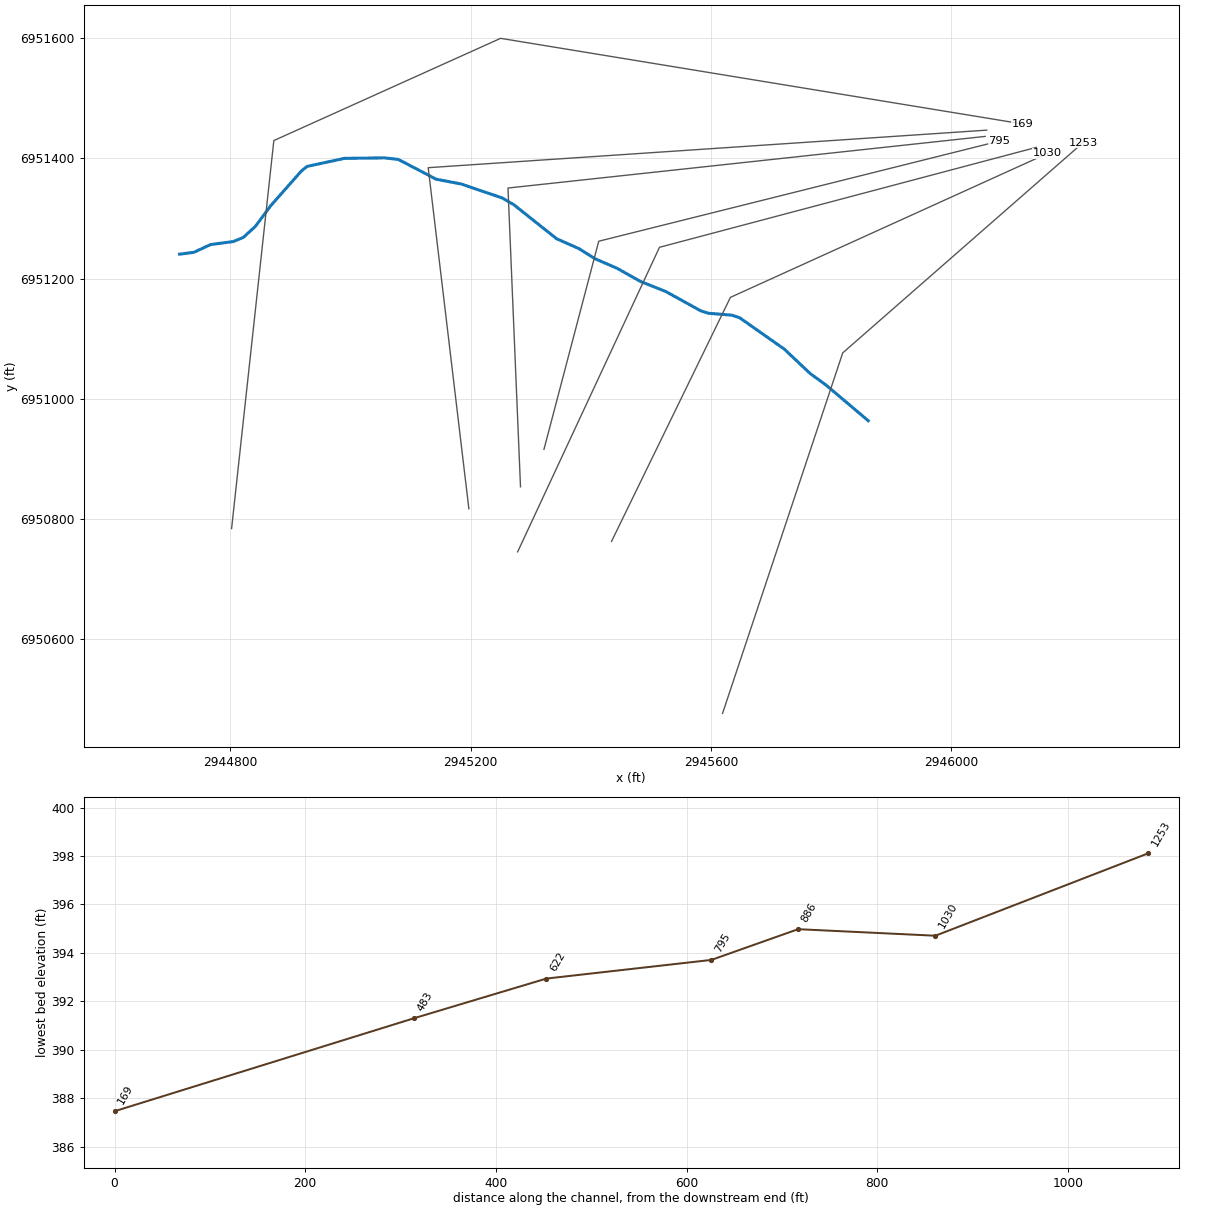
--- UNT 107 IN DRY CR WATERSHED.prj (project) ---

Proj Title=UNT 107 IN DRY CR WATERSHED Base Level Engineering
Current Plan=p01
Default Exp/Contr=0.3,0.1
English Units
Geom File=g01
Flow File=f01
Plan File=p01
BEGIN DESCRIPTION:
UNT 107 IN DRY CR WATERSHED
END DESCRIPTION:

--- UNT 107 IN DRY CR WATERSHED.p01 (plan) ---

Plan Title=Multiple Run
Short Identifier=Multiple
Geom File=g01
Flow File=f01
Subcritical Flow
K Sum by GR= 0
Std Step Tol= 0.01
Critical Tol= 0.01
Num of Std Step Trials= 20
Max Error Tol= 0.3
Flow Tol Ratio= 0.001
Split Flow NTrial= 30
Split Flow Tol= 0.02
Split Flow Ratio= 0.02
Log Output Level= 0
Friction Slope Method= 1
Unsteady Friction Slope Method= 2
Unsteady Bridges Friction Slope Method= 1
Parabolic Critical Depth
Global Vel Dist=  1 , 1 , 1
Global Log Level= 0
CheckData=True
Encroach Param= -1, 0, 0, 0
BEGIN DESCRIPTION:
Multiple Run
END DESCRIPTION:

--- UNT 107 IN DRY CR WATERSHED.f01 (steady flow) ---

Flow Title=Multiple
Program Version=5.07
Number of Profiles= 7
Profile Names=10-year,25-year,50-year,1pct_min,100-year,1pct_plu,500-year
River Rch & RM=UNT 107 IN DRY C,Reach-1         ,1253
     666     911    1116     681    1358    2710    2014
Boundary for River Rch & Prof#=UNT 107 IN DRY C,Reach-1         , 1
Up Type= 0
Dn Type= 3
Dn Slope=0.01204
Boundary for River Rch & Prof#=UNT 107 IN DRY C,Reach-1         , 2
Up Type= 0
Dn Type= 3
Dn Slope=0.01204
Boundary for River Rch & Prof#=UNT 107 IN DRY C,Reach-1         , 3
Up Type= 0
Dn Type= 3
Dn Slope=0.01204
Boundary for River Rch & Prof#=UNT 107 IN DRY C,Reach-1         , 4
Up Type= 0
Dn Type= 3
Dn Slope=0.01204
Boundary for River Rch & Prof#=UNT 107 IN DRY C,Reach-1         , 5
Up Type= 0
Dn Type= 3
Dn Slope=0.01204
Boundary for River Rch & Prof#=UNT 107 IN DRY C,Reach-1         , 6
Up Type= 0
Dn Type= 3
Dn Slope=0.01204
Boundary for River Rch & Prof#=UNT 107 IN DRY C,Reach-1         , 7
Up Type= 0
Dn Type= 3
Dn Slope=0.01204
DSS Import GetInterval= 0
DSS Import GetPeak= 0
DSS Import FillOption= 0

--- UNT 107 IN DRY CR WATERSHED.g01 (geometry) ---

Geom Title=Existing Conditions

River Reach=UNT 107 IN DRY C,Reach-1
Reach XY= 30
      2945862.04      6950963.45      2945791.75      6951022.82
      2945765.31      6951042.04      2945722.24      6951082.66
      2945647.90      6951134.90      2945634.96      6951139.18
      2945596.28      6951142.37      2945583.24      6951146.43
      2945524.74      6951178.66      2945482.80      6951195.36
      2945444.10      6951217.10      2945406.69      6951233.37
      2945380.31      6951250.03      2945343.24      6951266.43
      2945271.88      6951323.13      2945252.41      6951334.42
      2945184.29      6951357.58      2945142.85      6951365.49
      2945079.82      6951398.40      2945056.94      6951401.00
      2944990.16      6951400.22      2944927.81      6951386.78
      2944918.30      6951379.08      2944866.95      6951320.93
      2944841.99      6951287.16      2944821.83      6951268.62
      2944805.23      6951261.79      2944767.27      6951256.70
      2944739.49      6951243.86      2944715.59      6951240.71

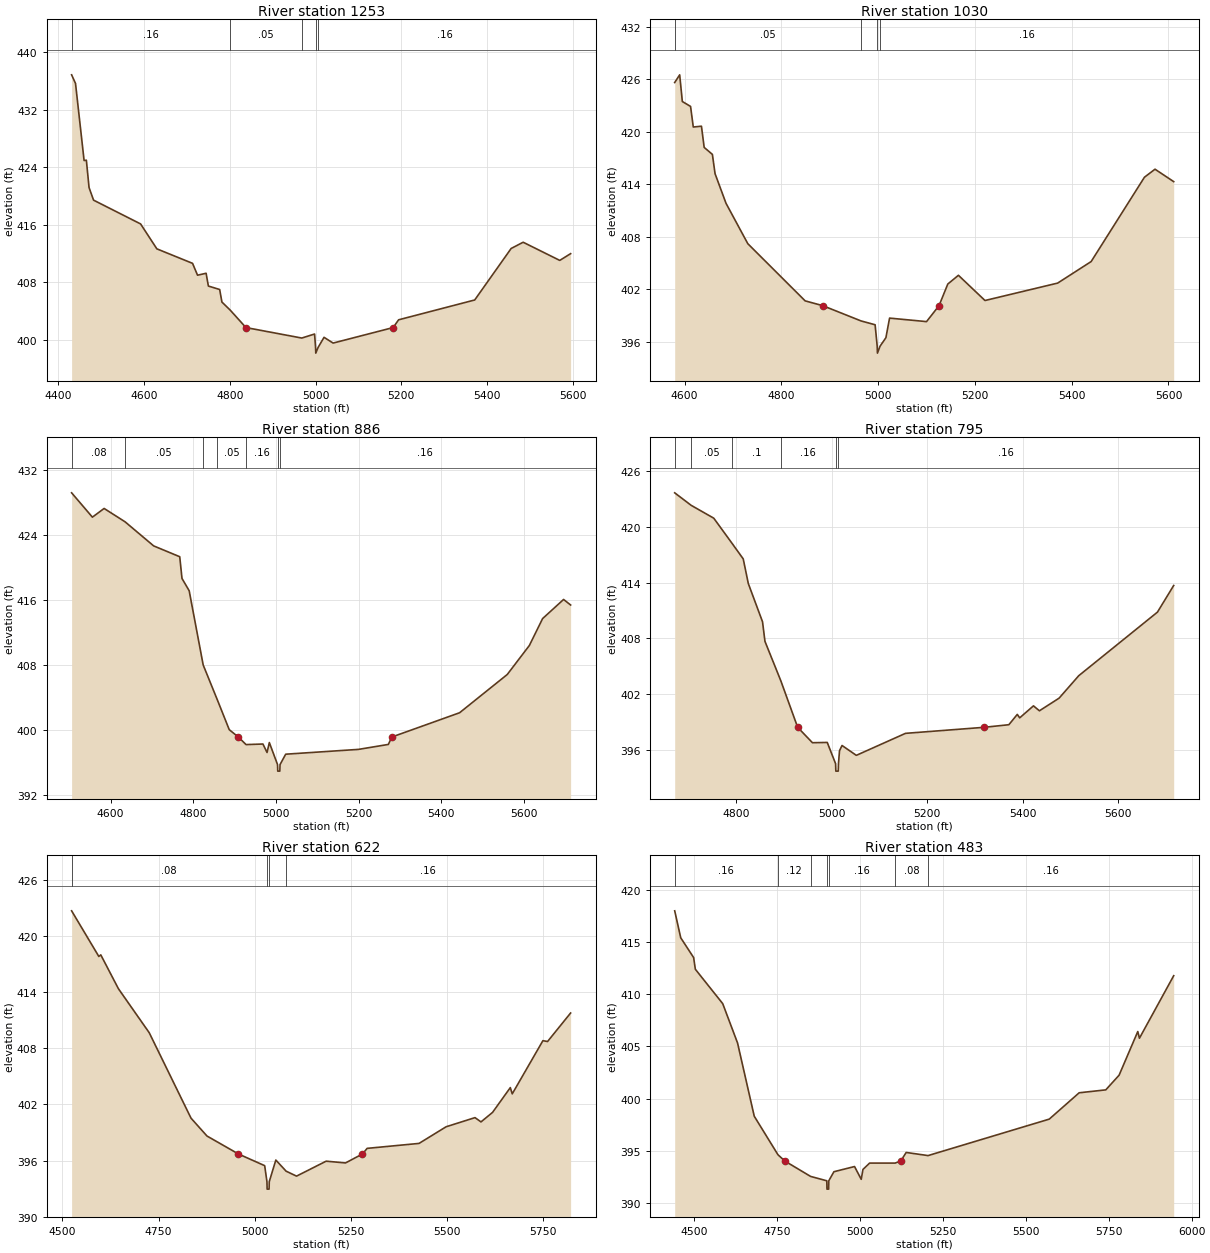
Type RM Length L Ch R = 1,1253,223,223,223
BEGIN DESCRIPTION:
UNT 107 IN DRY CR WATERSHED 2.0
END DESCRIPTION:
XS GIS Cut Line= 3
      2945619.45      6950476.40      2945819.44      6951076.39
      2946219.41      6951426.36
#Sta/Elev= 30
  4431.0  436.86  4440.1  435.66  4460.1  424.93  4465.4  424.97  4471.7  421.16
  4482.2  419.41  4591.9  416.10  4629.8  412.63  4713.1  410.61  4724.7  408.96
  4744.7  409.23  4750.0  407.45  4776.3  406.97  4781.6  405.22  4800.9  404.10
  4837.6  401.67  4967.9  400.21  4997.7  400.77  5000.0  398.91  5000.5  398.11
  5006.0  398.91  5019.8  400.31  5040.9  399.51  5181.0  401.67  5193.7  402.75
  5371.2  405.51  5456.2  412.68  5484.2  413.55  5569.6  411.02  5594.9  411.96
#Mann=5,-1,0
  4431.0    0.16       0  4800.9    0.05       0  4967.9    0.16       0
  5000.0    0.07       0  5006.0    0.16       0
Bank Sta=4837.6,5181
Exp/Cntr=0.3,0.1

Type RM Length L Ch R = 1,1030,144,144,144
BEGIN DESCRIPTION:
Mapping XS a7506c3e
END DESCRIPTION:
XS GIS Cut Line= 3
      2945434.62      6950762.60      2945632.54      6951168.85
      2946160.12      6951408.35
#Sta/Elev= 30
  4579.5  425.62  4589.8  426.50  4595.3  423.45  4612.3  422.89  4617.9  420.54
  4634.8  420.63  4640.4  418.21  4657.4  417.41  4662.9  415.21  4685.5  411.83
  4730.6  407.21  4849.1  400.68  4885.6  400.13  4964.5  398.39  4993.7  397.95
  4998.0  395.51  4998.5  394.71  5004.0  395.51  5016.0  396.47  5023.6  398.71
  5100.0  398.31  5125.8  400.13  5143.9  402.60  5165.9  403.60  5220.8  400.72
  5371.0  402.71  5440.2  405.17  5550.3  414.80  5572.2  415.72  5610.8  414.30
#Mann=4,-1,0
  4579.5    0.05       0  4964.5    0.16       0  4998.0    0.07       0
  5004.0    0.16       0
Bank Sta=4885.6,5125.8
Exp/Cntr=0.3,0.1

Type RM Length L Ch R = 1,886,91,91,91
BEGIN DESCRIPTION:
Mapping XS eaa09043
END DESCRIPTION:
XS GIS Cut Line= 3
      2945278.36      6950745.23      2945514.48      6951252.19
      2946141.46      6951418.46
#Sta/Elev= 30
  4505.5  429.17  4555.8  426.18  4584.2  427.25  4634.9  425.61  4704.1  422.65
  4767.2  421.32  4772.7  418.65  4790.1  417.14  4824.0  408.02  4858.4  403.72
  4887.1  400.07  4909.0  399.17  4927.8  398.24  4968.6  398.31  4978.6  397.27
  4984.1  398.49  5004.0  395.78  5004.5  394.98  5009.5  394.98  5010.0  395.78
  5023.7  397.06  5199.8  397.65  5272.2  398.26  5280.6  399.17  5444.6  402.15
  5560.0  406.85  5613.6  410.42  5645.6  413.72  5696.4  416.07  5713.4  415.39
#Mann=7,-1,0
  4505.5    0.08       0  4634.9    0.05       0  4824.0     0.1       0
  4858.4    0.05       0  4927.8    0.16       0  5004.0    0.07       0
  5010.0    0.16       0
Bank Sta=4909,5280.6
Exp/Cntr=0.3,0.1

Type RM Length L Ch R = 1,795,173,173,173
BEGIN DESCRIPTION:
Mapping XS 77a60a24
END DESCRIPTION:
XS GIS Cut Line= 3
      2945322.19      6950915.90      2945413.34      6951262.29
      2946080.04      6951428.96
#Sta/Elev= 30
  4671.2  423.69  4705.8  422.34  4753.0  420.96  4791.9  418.21  4814.8  416.57
  4825.4  413.92  4855.2  409.80  4860.3  407.69  4893.7  403.42  4928.8  398.43
  4959.8  396.77  4990.8  396.80  5008.3  394.51  5008.8  393.71  5013.8  393.71
  5014.3  394.51  5016.5  395.91  5021.8  396.47  5051.7  395.41  5154.8  397.78
  5319.5  398.43  5371.3  398.71  5388.9  399.82  5394.0  399.45  5422.8  400.74
  5435.3  400.21  5476.5  401.57  5517.7  403.99  5682.6  410.84  5716.6  413.71
#Mann=6,-1,0
  4671.2    0.08       0  4705.8    0.05       0  4791.9     0.1       0
  4893.7    0.16       0  5008.3    0.07       0  5014.3    0.16       0
Bank Sta=4928.8,5319.5
Exp/Cntr=0.3,0.1

Type RM Length L Ch R = 1,622,139,139,139
BEGIN DESCRIPTION:
Mapping XS c0306c7b
END DESCRIPTION:
XS GIS Cut Line= 3
      2945283.13      6950853.48      2945262.30      6951350.83
      2946056.58      6951436.77
#Sta/Elev= 30
  4524.2  422.71  4594.9  417.83  4600.0  418.00  4645.8  414.38  4725.9  409.67
  4834.5  400.53  4876.0  398.62  4957.7  396.70  5025.9  395.45  5031.8  393.74
  5032.3  392.94  5037.3  392.94  5037.8  393.74  5054.9  396.05  5081.6  394.86
  5108.7  394.33  5185.6  395.93  5235.9  395.74  5280.0  396.70  5292.2  397.30
  5427.0  397.83  5497.4  399.61  5572.5  400.59  5588.0  400.13  5618.1  401.15
  5664.2  403.80  5669.2  403.13  5748.9  408.82  5761.0  408.73  5820.9  411.78
#Mann=4,-1,0
  4524.2    0.08       0  5031.8    0.07       0  5037.8    0.08       0
  5081.6    0.16       0
Bank Sta=4957.7,5280
Exp/Cntr=0.3,0.1

Type RM Length L Ch R = 1,483,314,314,314
BEGIN DESCRIPTION:
Mapping XS 5f041813
END DESCRIPTION:
XS GIS Cut Line= 3
      2945197.20      6950816.95      2945129.49      6951384.69
      2946059.14      6951447.18
#Sta/Elev= 30
  4442.4  418.02  4460.6  415.43  4499.5  413.53  4504.6  412.41  4587.1  409.11
  4631.8  405.33  4682.1  398.30  4753.6  394.60  4774.1  394.00  4851.9  392.52
  4900.7  392.10  4901.2  391.30  4906.2  391.30  4906.7  392.10  4922.1  392.97
  4984.3  393.47  5004.4  392.24  5009.6  393.19  5029.7  393.80  5106.7  393.80
  5123.5  394.00  5139.9  394.82  5205.8  394.52  5570.9  398.02  5661.1  400.55
  5741.3  400.83  5781.4  402.24  5837.7  406.43  5842.7  405.79  5945.9  411.79
#Mann=7,-1,0
  4442.4    0.16       0  4753.6    0.12       0  4851.9    0.16       0
  4900.7    0.07       0  4906.7    0.16       0  5106.7    0.08       0
  5205.8    0.16       0
Bank Sta=4774.1,5123.5
Exp/Cntr=0.3,0.1

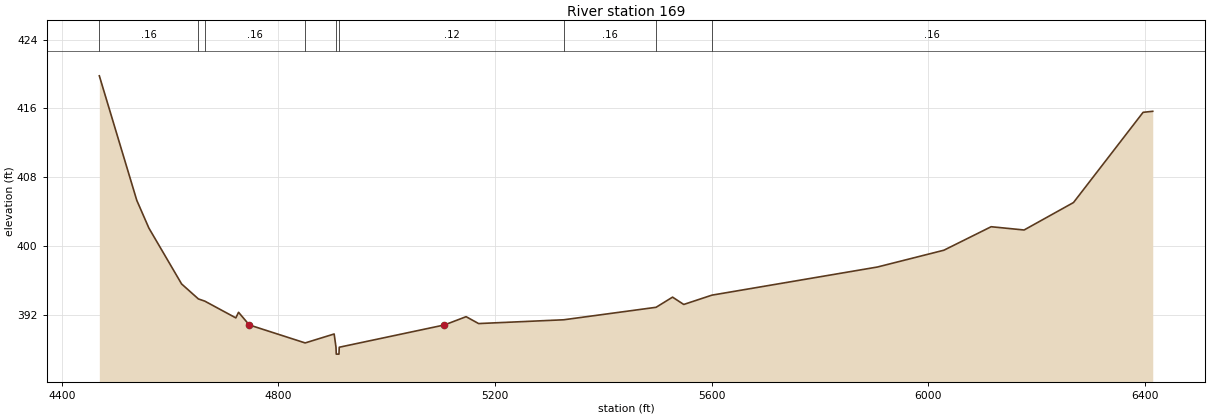
Type RM Length L Ch R = 1,169,0,0,0
BEGIN DESCRIPTION:
Mapping XS 4150919c
END DESCRIPTION:
XS GIS Cut Line= 4
      2944802.24      6950784.01      2944872.55      6951429.83
      2945250.00      6951600.00      2946119.41      6951457.41
#Sta/Elev= 30
  4469.3  419.79  4538.4  405.33  4560.8  402.10  4621.2  395.61  4652.2  393.87
  4663.9  393.62  4721.3  391.67  4726.3  392.32  4746.1  390.85  4849.3  388.76
  4902.8  389.80  4906.2  388.26  4906.7  387.46  4911.7  387.46  4912.2  388.26
  5106.4  390.85  5146.4  391.81  5169.5  391.01  5326.6  391.45  5497.1  392.90
  5527.5  394.08  5548.2  393.23  5600.1  394.31  5905.8  397.58  6028.4  399.53
  6115.7  402.26  6176.5  401.88  6267.7  405.07  6396.2  415.55  6414.0  415.67
#Mann=9,-1,0
  4469.3    0.16       0  4652.2    0.12       0  4663.9    0.16       0
  4849.3    0.12       0  4906.2    0.07       0  4912.2    0.12       0
  5326.6    0.16       0  5497.1    0.05       0  5600.1    0.16       0
Bank Sta=4746.1,5106.4
Exp/Cntr=0.3,0.1

Chan Stop Cuts=-1