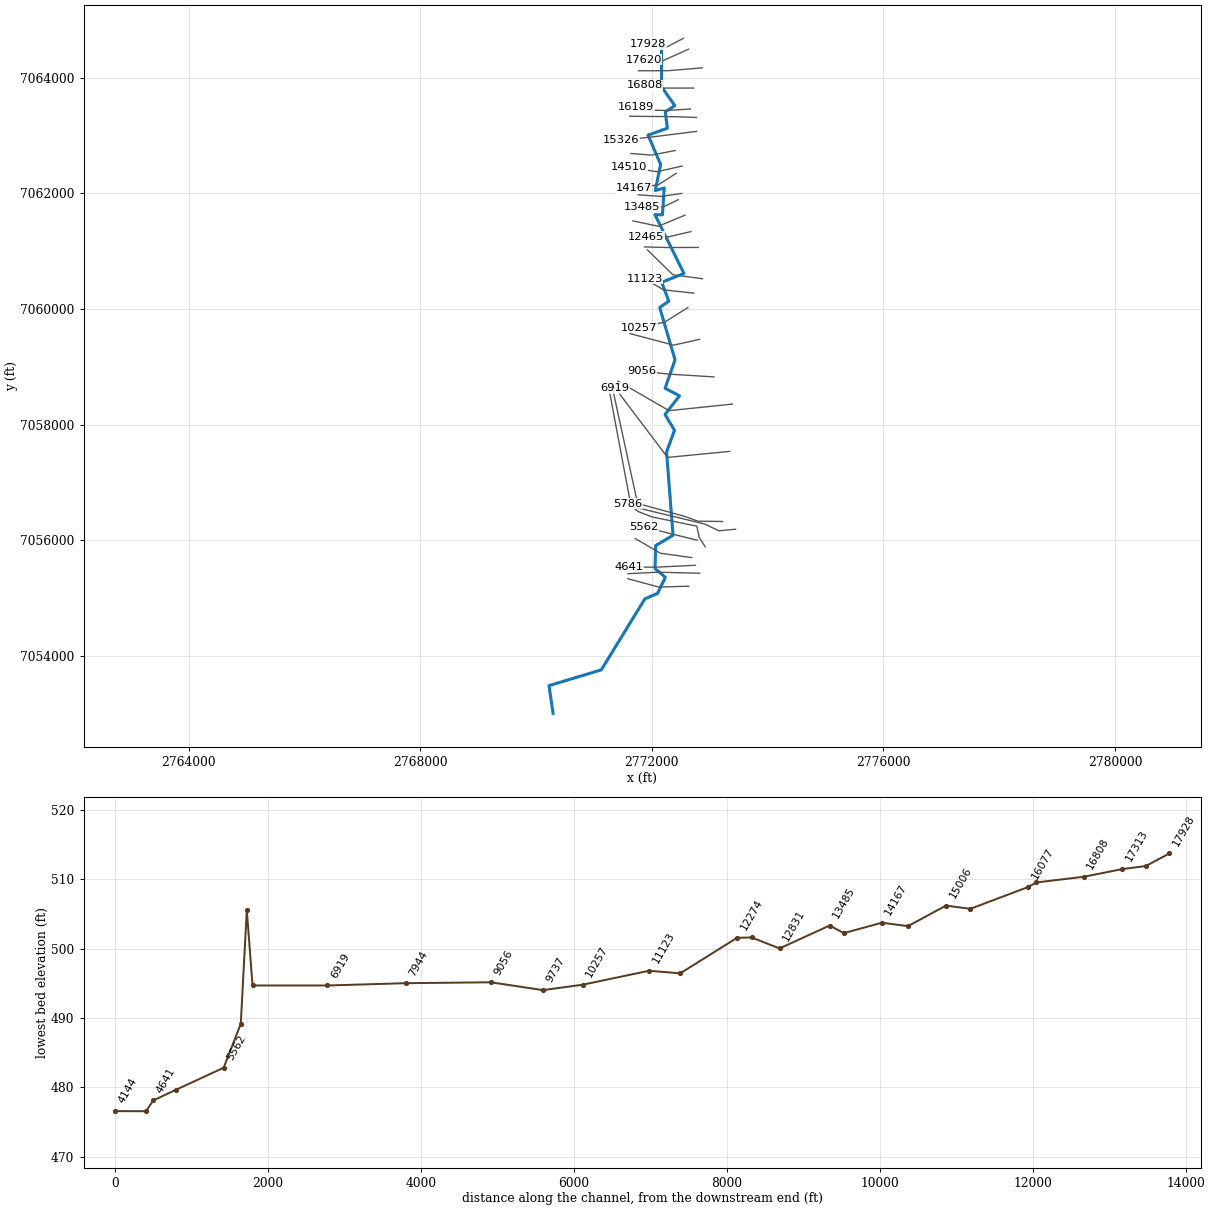
--- ARR BRANCH.prj (project) ---

Proj Title=ARR BRANCH Base Level Engineering
Current Plan=p01
Default Exp/Contr=0.3,0.1
English Units
Geom File=g01
Flow File=f01
Plan File=p01
BEGIN DESCRIPTION:
ARR BRANCH
END DESCRIPTION:

--- ARR BRANCH.p01 (plan) ---

Plan Title=Multiple Run
Short Identifier=Multiple
Geom File=g01
Flow File=f01
Subcritical Flow
K Sum by GR= 0
Std Step Tol= 0.01
Critical Tol= 0.01
Num of Std Step Trials= 20
Max Error Tol= 0.3
Flow Tol Ratio= 0.001
Split Flow NTrial= 30
Split Flow Tol= 0.02
Split Flow Ratio= 0.02
Log Output Level= 0
Friction Slope Method= 1
Unsteady Friction Slope Method= 2
Unsteady Bridges Friction Slope Method= 1
Parabolic Critical Depth
Global Vel Dist=  1 , 1 , 1
Global Log Level= 0
CheckData=True
Encroach Param= -1, 0, 0, 0
BEGIN DESCRIPTION:
Multiple Run
END DESCRIPTION:

--- ARR BRANCH.f01 (steady flow) ---

Flow Title=Multiple
Number of Profiles=7
Profile Names=10-year,25-year,50-year,1pct_min,100-year,1pct_plu,500-year
River Rch & RM= ARR BRANCH,Reach-1,17928
     633     838    1001     593    1184    2362    1651
River Rch & RM= ARR BRANCH,Reach-1,17620
    1063    1448    1764    1062    2120    4230    3060
River Rch & RM= ARR BRANCH,Reach-1,5562
    1397    1934    2382    1450    2894    5774    4271
Boundary for River Rch & Prof#=ARR BRANCH,Reach-1,1
Up Type=0
Dn Type=3
Dn Slope=0.005
Boundary for River Rch & Prof#=ARR BRANCH,Reach-1,2
Up Type=0
Dn Type=3
Dn Slope=0.005
Boundary for River Rch & Prof#=ARR BRANCH,Reach-1,3
Up Type=0
Dn Type=3
Dn Slope=0.005
Boundary for River Rch & Prof#=ARR BRANCH,Reach-1,4
Up Type=0
Dn Type=3
Dn Slope=0.005
Boundary for River Rch & Prof#=ARR BRANCH,Reach-1,5
Up Type=0
Dn Type=3
Dn Slope=0.005
Boundary for River Rch & Prof#=ARR BRANCH,Reach-1,6
Up Type=0
Dn Type=3
Dn Slope=0.005
Boundary for River Rch & Prof#=ARR BRANCH,Reach-1,7
Up Type=0
Dn Type=3
Dn Slope=0.005

--- ARR BRANCH.g01 (geometry) ---

Geom Title=Existing Conditions

River Reach=ARR BRANCH,Reach-1
Reach XY= 30
      2772167.88      7064616.55      2772170.99      7063844.89
      2772398.41      7063521.57      2772234.27      7063412.80
      2772269.73      7063129.63      2771936.35      7063010.72
      2772153.32      7062505.06      2772060.63      7062050.95
      2772215.37      7062096.39      2772185.09      7061630.84
      2772055.31      7061633.02      2772556.61      7060616.56
      2772171.98      7060462.31      2772294.59      7060136.02
      2772137.38      7060027.26      2772402.37      7059121.54
      2772230.32      7058628.15      2772479.49      7058498.62
      2772229.33      7058173.31      2772393.47      7057901.40
      2772256.03      7057526.66      2772368.24      7056084.26
      2772067.34      7055904.65      2772058.05      7055506.72
      2772234.83      7055356.22      2772100.98      7055077.57
      2771881.20      7054983.00      2771128.85      7053753.45
      2770226.10      7053481.34      2770295.59      7053000.71

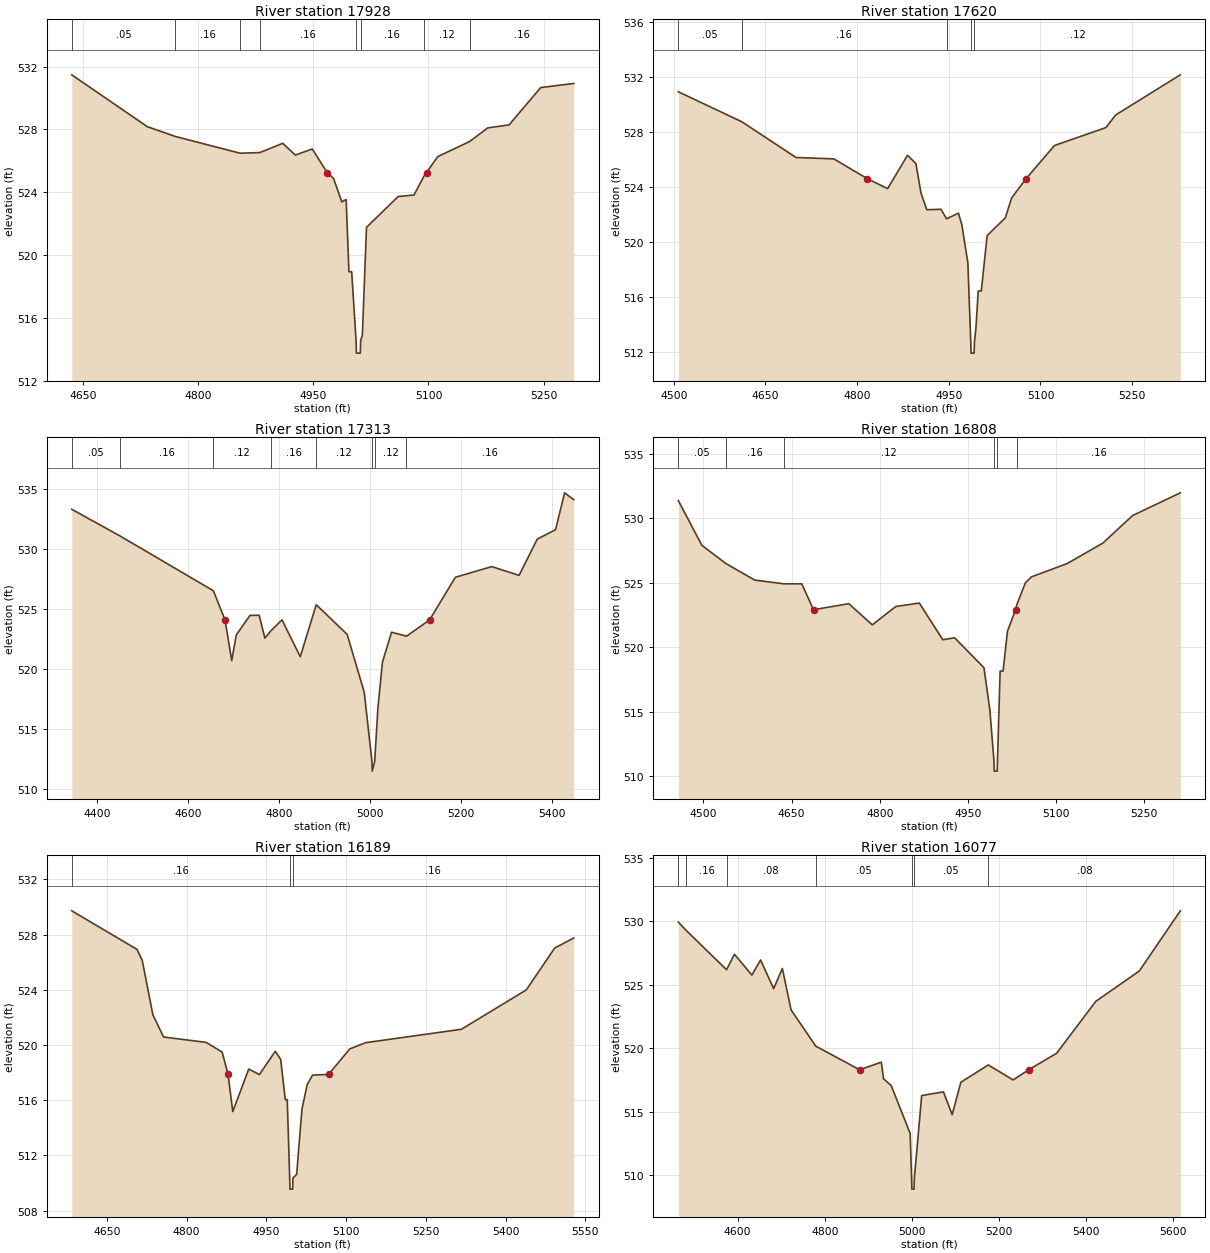
Type RM Length L Ch R = 1,17928,308,308,308
BEGIN DESCRIPTION:
ARR BRANCH 28.0
END DESCRIPTION:
XS GIS Cut Line= 3
      2772546.73      7064685.85      2772223.66      7064516.62
      2771943.35      7064588.19
#Sta/Elev= 30
  4635.3  531.47  4733.7  528.17  4769.9  527.55  4854.5  526.48  4880.3  526.52
  4910.2  527.11  4926.6  526.36  4948.7  526.75  4968.0  525.25  4976.4  524.87
  4987.1  523.38  4992.8  523.53  4996.4  518.93  5000.0  518.93  5005.7  514.55
  5006.2  513.75  5011.2  513.75  5011.7  514.55  5013.9  514.90  5019.3  521.76
  5060.5  523.72  5081.2  523.82  5094.3  525.03  5097.6  525.25  5112.1  526.26
  5153.9  527.23  5177.3  528.09  5205.0  528.28  5246.3  530.66  5289.3  530.92
#Mann=8,-1,0
  4635.3    0.05       0  4769.9    0.16       0  4854.5    0.12       0
  4880.3    0.16       0  5005.7    0.07       0  5011.7    0.16       0
  5094.3    0.12       0  5153.9    0.16       0
Bank Sta=4968,5097.6
Exp/Cntr=0.3,0.1

Type RM Length L Ch R = 1,17620,307,307,307
BEGIN DESCRIPTION:
Mapping XS 88bc12dd
END DESCRIPTION:
XS GIS Cut Line= 3
      2772636.96      7064498.33      2772189.06      7064296.94
      2771859.60      7064317.75
#Sta/Elev= 30
  4507.6  530.90  4611.6  528.72  4700.1  526.13  4761.9  526.03  4816.5  524.60
  4850.0  523.87  4882.5  526.29  4896.3  525.69  4904.5  523.56  4914.0  522.34
  4937.2  522.37  4946.5  521.68  4965.8  522.09  4971.3  521.27  4981.2  518.50
  4986.0  512.73  4986.5  511.93  4991.5  511.93  4992.0  512.73  4994.4  513.72
  4998.2  516.44  5003.2  516.44  5012.8  520.46  5042.5  521.75  5052.9  523.20
  5076.6  524.60  5123.0  527.00  5207.0  528.30  5223.2  529.22  5328.8  532.13
#Mann=5,-1,0
  4507.6    0.05       0  4611.6    0.16       0  4946.5    0.12       0
  4986.0    0.07       0  4992.0    0.12       0
Bank Sta=4816.5,5076.6
Exp/Cntr=0.3,0.1

Type RM Length L Ch R = 1,17313,505,505,505
BEGIN DESCRIPTION:
ARR BRANCH 27.0
END DESCRIPTION:
XS GIS Cut Line= 3
      2772874.99      7064175.00      2772275.00      7064125.00
      2771774.97      7064125.00
#Sta/Elev= 30
  4344.7  533.28  4451.1  531.05  4655.6  526.50  4681.2  524.07  4695.9  520.68
  4705.9  522.82  4736.0  524.45  4756.1  524.46  4768.7  522.56  4782.2  523.18
  4806.3  524.08  4846.4  521.01  4881.4  525.34  4949.3  522.87  4986.8  518.06
  5003.8  512.29  5004.3  511.49  5009.8  512.29  5016.8  516.72  5026.8  520.56
  5046.8  523.05  5079.6  522.72  5130.3  524.07  5186.8  527.62  5266.8  528.51
  5326.8  527.78  5366.8  530.80  5406.8  531.58  5426.8  534.65  5446.8  534.08
#Mann=8,-1,0
  4344.7    0.05       0  4451.1    0.16       0  4655.6    0.12       0
  4782.2    0.16       0  4881.4    0.12       0  5003.8    0.07       0
  5009.8    0.12       0  5079.6    0.16       0
Bank Sta=4681.2,5130.3
Exp/Cntr=0.3,0.1

Type RM Length L Ch R = 1,16808,619,619,619
BEGIN DESCRIPTION:
ARR BRANCH 26.0
END DESCRIPTION:
XS GIS Cut Line= 3
      2772724.96      7063825.00      2772175.00      7063825.00
      2771875.00      7063875.00
#Sta/Elev= 30
  4457.4  531.37  4497.4  527.90  4537.8  526.50  4587.4  525.20  4636.9  524.91
  4667.4  524.91  4687.4  522.90  4747.4  523.37  4787.4  521.73  4827.4  523.15
  4867.4  523.42  4907.4  520.57  4927.4  520.73  4977.4  518.40  4987.4  515.15
  4994.4  511.18  4994.9  510.38  4999.9  510.38  5000.4  511.18  5004.9  518.14
  5009.9  518.14  5017.5  521.25  5031.3  522.90  5033.6  523.32  5047.9  524.99
  5058.1  525.45  5118.9  526.48  5179.7  528.07  5230.4  530.21  5311.5  531.97
#Mann=6,-1,0
  4457.4    0.05       0  4537.8    0.16       0  4636.9    0.12       0
  4994.4    0.07       0  5000.4    0.12       0  5033.6    0.16       0
Bank Sta=4687.4,5031.3
Exp/Cntr=0.3,0.1

Type RM Length L Ch R = 1,16189,112,112,112
BEGIN DESCRIPTION:
Mapping XS 6403831f
END DESCRIPTION:
XS GIS Cut Line= 4
      2772667.36      7063461.78      2772262.70      7063437.44
      2771852.01      7063443.53      2771733.33      7063492.21
#Sta/Elev= 30
  4583.9  529.72  4706.5  526.93  4716.5  526.13  4736.5  522.19  4756.6  520.58
  4836.7  520.19  4866.8  519.49  4878.0  517.87  4886.8  515.18  4916.9  518.26
  4936.9  517.86  4966.9  519.55  4977.0  518.95  4985.6  516.04  4989.3  516.04
  4993.9  510.36  4994.4  509.56  4999.5  509.56  5000.0  510.36  5007.0  510.63
  5017.0  515.37  5027.0  517.15  5037.0  517.82  5067.1  517.87  5107.0  519.72
  5137.0  520.17  5317.0  521.14  5439.0  523.99  5492.4  527.02  5528.3  527.75
#Mann=3,-1,0
  4583.9    0.16       0  4993.9    0.07       0  5000.0    0.16       0
Bank Sta=4878,5067.1
Exp/Cntr=0.3,0.1

Type RM Length L Ch R = 1,16077,751,751,751
BEGIN DESCRIPTION:
Mapping XS daf1e894
END DESCRIPTION:
XS GIS Cut Line= 4
      2772773.80      7063315.76      2772442.19      7063327.92
      2772241.40      7063330.97      2771620.78      7063337.05
#Sta/Elev= 30
  4463.7  529.92  4481.9  529.26  4574.5  526.17  4592.6  527.39  4632.6  525.75
  4652.6  526.94  4682.6  524.68  4702.7  526.27  4722.7  523.01  4779.5  520.15
  4880.3  518.29  4930.1  518.89  4935.1  517.58  4952.7  517.05  4996.3  513.28
  4999.7  509.69  5000.2  508.89  5005.3  508.89  5005.8  509.69  5022.8  516.26
  5072.8  516.55  5092.8  514.75  5112.8  517.31  5175.9  518.67  5232.8  517.49
  5268.6  518.29  5332.8  519.59  5422.8  523.68  5522.8  526.07  5617.0  530.81
#Mann=7,-1,0
  4463.7    0.05       0  4481.9    0.16       0  4574.5    0.08       0
  4779.5    0.05       0  4999.7    0.04       0  5005.8    0.05       0
  5175.9    0.08       0
Bank Sta=4880.3,5268.6
Exp/Cntr=0.3,0.1

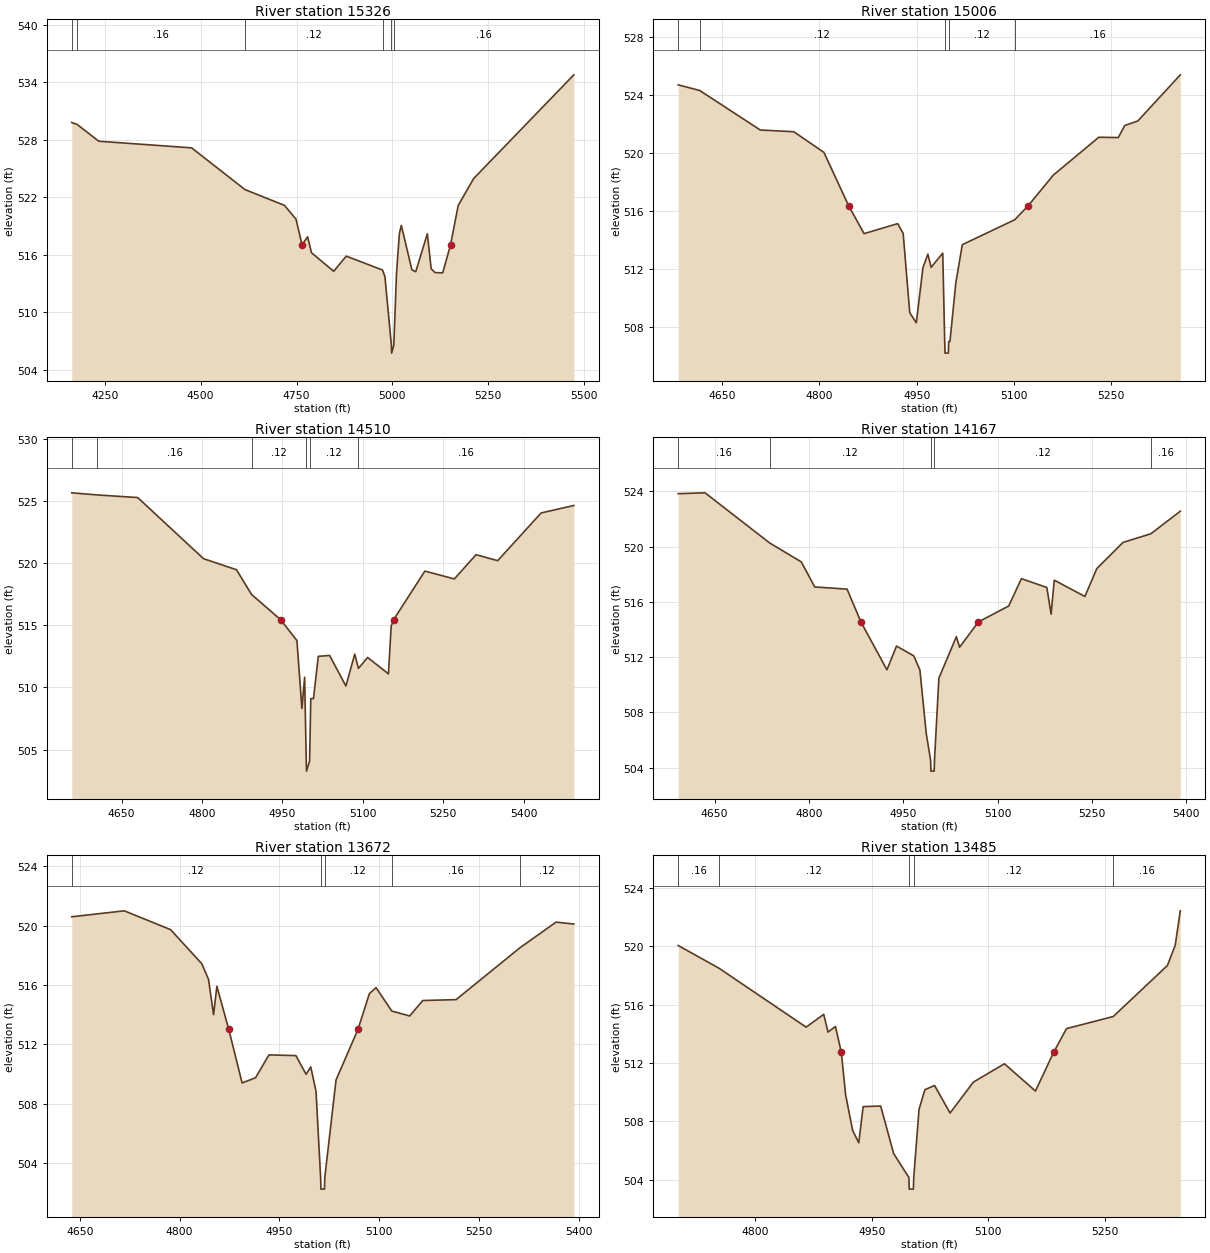
Type RM Length L Ch R = 1,15326,320,320,320
BEGIN DESCRIPTION:
ARR BRANCH 24.0
END DESCRIPTION:
XS GIS Cut Line= 3
      2772774.97      7063075.00      2771975.00      7062975.00
      2771474.99      7062925.00
#Sta/Elev= 30
  4164.2  529.82  4177.9  529.63  4234.7  527.87  4476.6  527.18  4615.9  522.82
  4718.5  521.18  4748.7  519.74  4764.4  517.07  4778.9  517.90  4789.0  516.24
  4846.9  514.30  4879.7  515.88  4974.2  514.43  4980.4  513.76  4997.4  506.56
  4997.9  505.76  5003.6  506.56  5010.6  514.03  5018.1  518.22  5023.2  519.09
  5050.8  514.45  5060.8  514.25  5091.0  518.21  5101.0  514.56  5111.1  514.16
  5131.2  514.14  5151.6  517.07  5171.4  521.16  5211.6  523.97  5472.9  534.80
#Mann=6,-1,0
  4164.2    0.05       0  4177.9    0.16       0  4615.9    0.12       0
  4974.2    0.16       0  4997.4    0.07       0  5003.6    0.16       0
Bank Sta=4764.4,5151.6
Exp/Cntr=0.3,0.1

Type RM Length L Ch R = 1,15006,496,496,496
BEGIN DESCRIPTION:
Mapping XS af652a03
END DESCRIPTION:
XS GIS Cut Line= 3
      2772405.72      7062743.83      2771998.03      7062664.73
      2771639.56      7062692.07
#Sta/Elev= 30
  4582.1  524.70  4615.3  524.31  4708.7  521.59  4760.4  521.47  4806.9  520.05
  4845.2  516.36  4868.9  514.45  4920.7  515.14  4929.2  514.47  4939.4  509.00
  4949.5  508.31  4959.7  512.09  4967.3  513.04  4972.4  512.13  4990.3  513.11
  4993.3  507.02  4993.8  506.22  4999.0  506.22  4999.5  507.02  5001.4  507.02
  5010.5  511.07  5020.5  513.69  5101.5  515.41  5121.9  516.36  5160.9  518.48
  5231.1  521.09  5261.2  521.07  5271.2  521.90  5291.3  522.21  5356.9  525.39
#Mann=5,-1,0
  4582.1    0.05       0  4615.3    0.12       0  4993.3    0.07       0
  4999.5    0.12       0  5101.5    0.16       0
Bank Sta=4845.2,5121.9
Exp/Cntr=0.3,0.1

Type RM Length L Ch R = 1,14510,343,343,343
BEGIN DESCRIPTION:
ARR BRANCH 23.0
END DESCRIPTION:
XS GIS Cut Line= 3
      2772524.97      7062474.99      2772089.46      7062377.24
      2771604.62      7062452.60
#Sta/Elev= 30
  4556.9  525.66  4604.4  525.49  4679.9  525.28  4802.8  520.36  4864.3  519.47
  4892.4  517.48  4946.6  515.45  4977.1  513.77  4986.4  508.30  4991.5  510.82
  4994.5  504.06  4995.0  503.26  5000.7  504.06  5003.0  509.10  5008.0  509.10
  5017.0  512.50  5038.1  512.57  5068.5  510.11  5085.0  512.68  5091.9  511.53
  5109.0  512.41  5147.9  511.09  5153.0  514.92  5157.6  515.45  5215.9  519.36
  5270.9  518.73  5311.4  520.68  5351.8  520.20  5432.8  524.04  5493.9  524.64
#Mann=6,-1,0
  4556.9    0.05       0  4604.4    0.16       0  4892.4    0.12       0
  4994.5    0.07       0  5000.7    0.12       0  5091.9    0.16       0
Bank Sta=4946.6,5157.6
Exp/Cntr=0.3,0.1

Type RM Length L Ch R = 1,14167,495,495,495
BEGIN DESCRIPTION:
Mapping XS 8309e351
END DESCRIPTION:
XS GIS Cut Line= 3
      2772420.87      7062348.33      2772113.63      7062150.60
      2771684.68      7062092.80
#Sta/Elev= 30
  4592.1  523.83  4634.8  523.89  4737.2  520.27  4787.8  518.89  4809.0  517.08
  4860.5  516.92  4882.5  514.55  4923.9  511.08  4939.1  512.80  4966.6  512.09
  4976.3  511.07  4986.4  506.47  4993.3  504.55  4993.8  503.75  4999.0  503.75
  4999.5  504.55  5006.5  510.48  5034.3  513.48  5039.4  512.72  5069.4  514.55
  5117.5  515.70  5137.7  517.68  5178.1  517.04  5184.9  515.11  5189.9  517.57
  5238.6  516.39  5257.6  518.41  5299.2  520.30  5343.6  520.93  5390.3  522.56
#Mann=5,-1,0
  4592.1    0.16       0  4737.2    0.12       0  4993.3    0.07       0
  4999.5    0.12       0  5343.6    0.16       0
Bank Sta=4882.5,5069.4
Exp/Cntr=0.3,0.1

Type RM Length L Ch R = 1,13672,187,187,187
BEGIN DESCRIPTION:
Mapping XS 005d209e
END DESCRIPTION:
XS GIS Cut Line= 3
      2772518.25      7062001.54      2772168.39      7061949.82
      2771768.38      7061977.09
#Sta/Elev= 30
  4637.9  520.59  4716.9  520.99  4786.5  519.72  4833.3  517.43  4843.4  516.38
  4851.0  514.00  4856.0  515.91  4873.9  513.00  4893.9  509.40  4914.1  509.75
  4934.3  511.29  4974.8  511.24  4990.1  509.98  4997.1  510.48  5005.0  508.83
  5011.9  503.05  5012.4  502.25  5017.7  502.25  5018.2  503.05  5035.1  509.60
  5068.0  513.00  5085.2  515.41  5095.2  515.82  5118.9  514.24  5145.8  513.91
  5165.4  514.95  5215.5  515.01  5311.7  518.51  5365.8  520.23  5392.5  520.10
#Mann=5,-1,0
  4637.9    0.12       0  5011.9    0.07       0  5018.2    0.12       0
  5118.9    0.16       0  5311.7    0.12       0
Bank Sta=4873.9,5068
Exp/Cntr=0.3,0.1

Type RM Length L Ch R = 1,13485,654,654,654
BEGIN DESCRIPTION:
Mapping XS 145557e1
END DESCRIPTION:
XS GIS Cut Line= 3
      2772457.43      7061892.03      2772204.90      7061770.33
      2771838.44      7061767.30
#Sta/Elev= 30
  4700.6  520.06  4752.9  518.51  4865.4  514.46  4888.0  515.34  4893.6  514.12
  4903.1  514.51  4910.7  512.74  4916.2  509.83  4925.3  507.37  4933.2  506.53
  4938.8  509.01  4961.4  509.05  4978.1  505.79  4997.7  504.15  4998.2  503.35
  5003.5  503.35  5004.0  504.15  5010.8  508.82  5018.4  510.17  5030.8  510.46
  5050.8  508.57  5080.8  510.69  5120.8  511.95  5160.8  510.08  5184.3  512.74
  5200.8  514.36  5261.0  515.19  5330.8  518.69  5340.8  520.07  5347.4  522.44
#Mann=5,-1,0
  4700.6    0.16       0  4752.9    0.12       0  4997.7    0.07       0
  5004.0    0.12       0  5261.0    0.16       0
Bank Sta=4910.7,5184.3
Exp/Cntr=0.3,0.1

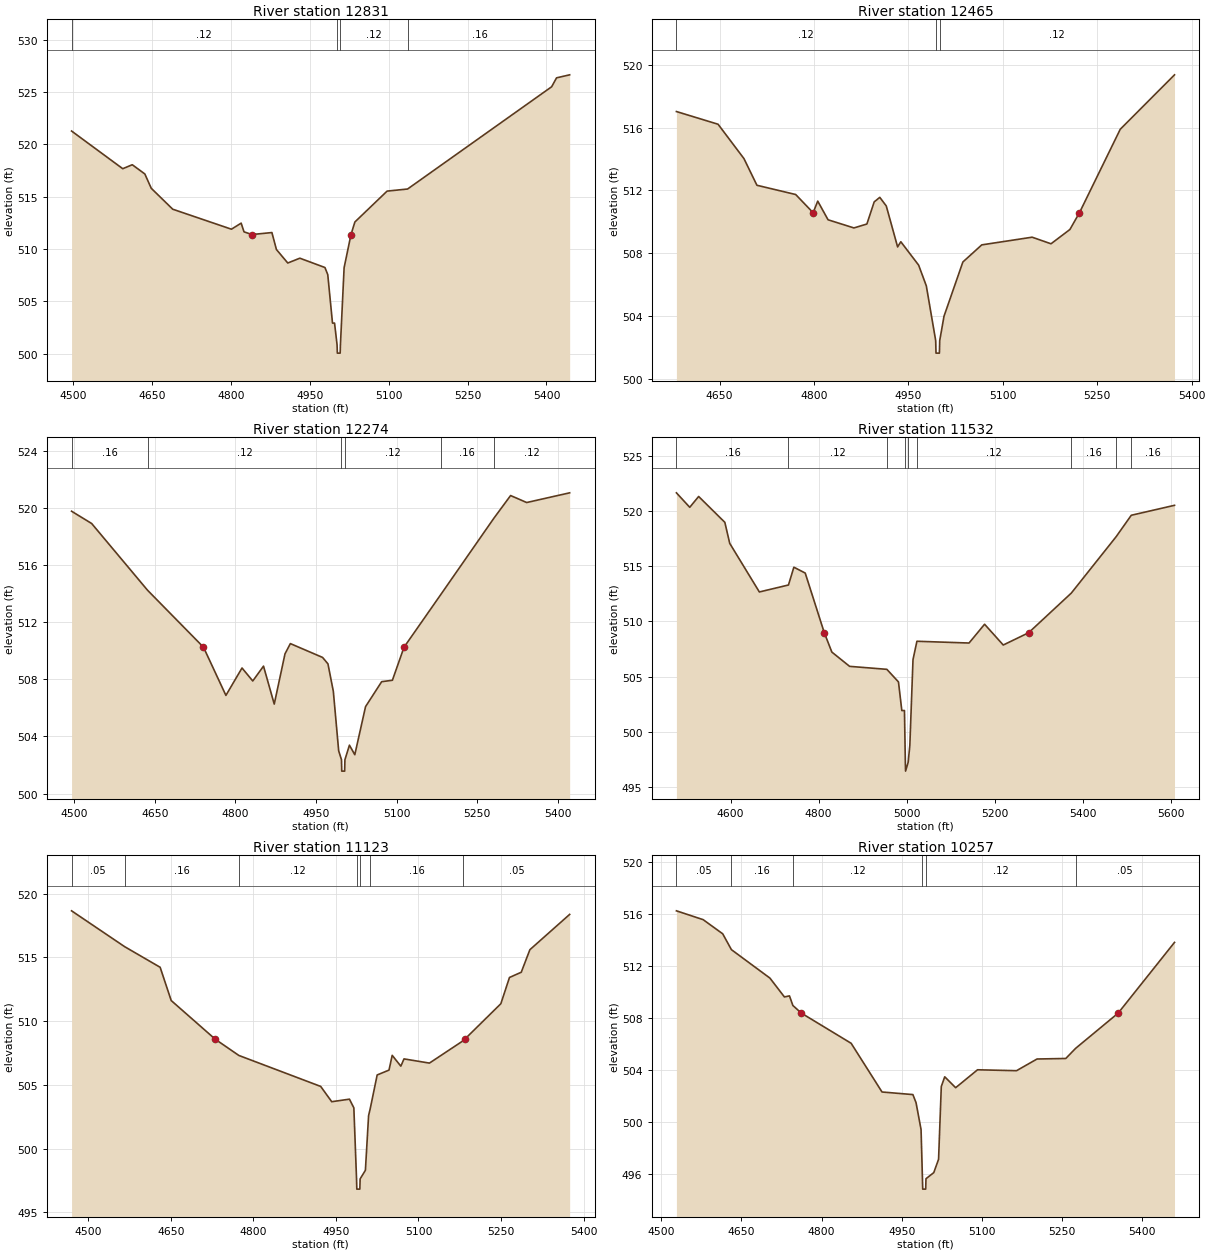
Type RM Length L Ch R = 1,12831,366,366,366
BEGIN DESCRIPTION:
ARR BRANCH 21.0
END DESCRIPTION:
XS GIS Cut Line= 3
      2772574.97      7061624.99      2772112.78      7061433.08
      2771674.97      7061525.01
#Sta/Elev= 30
  4496.4  521.26  4593.8  517.66  4611.9  518.04  4635.8  517.16  4648.0  515.79
  4688.9  513.79  4800.6  511.88  4819.1  512.46  4824.5  511.63  4839.5  511.37
  4877.6  511.56  4886.2  509.94  4907.8  508.65  4930.8  509.11  4978.5  508.22
  4983.9  507.54  4992.9  502.91  4996.8  502.91  5001.6  500.84  5002.1  500.04
  5007.5  500.04  5008.0  500.84  5015.0  508.20  5028.1  511.37  5035.5  512.57
  5096.8  515.52  5135.8  515.72  5409.9  525.49  5419.2  526.34  5444.2  526.63
#Mann=5,-1,0
  4496.4    0.12       0  5001.6    0.07       0  5008.0    0.12       0
  5135.8    0.16       0  5409.9     0.1       0
Bank Sta=4839.5,5028.1
Exp/Cntr=0.3,0.1

Type RM Length L Ch R = 1,12465,191,191,191
BEGIN DESCRIPTION:
Mapping XS 051947e2
END DESCRIPTION:
XS GIS Cut Line= 3
      2772679.45      7061341.38      2772293.12      7061250.12
      2771898.79      7061250.12
#Sta/Elev= 30
  4581.5  517.03  4647.7  516.22  4688.8  514.03  4709.4  512.33  4771.0  511.74
  4798.7  510.58  4806.0  511.32  4822.4  510.13  4863.5  509.61  4884.1  509.86
  4895.7  511.27  4904.6  511.56  4914.9  511.01  4932.9  508.40  4938.0  508.73
  4966.3  507.24  4978.5  505.92  4993.4  502.43  4993.9  501.63  4999.3  501.63
  4999.8  502.43  5006.6  503.98  5036.6  507.44  5066.6  508.53  5146.6  509.02
  5176.6  508.60  5206.6  509.51  5221.8  510.58  5286.6  515.90  5372.8  519.37
#Mann=3,-1,0
  4581.5    0.12       0  4993.4    0.07       0  4999.8    0.12       0
Bank Sta=4798.7,5221.8
Exp/Cntr=0.3,0.1

Type RM Length L Ch R = 1,12274,742,742,742
BEGIN DESCRIPTION:
ARR BRANCH 20.0
END DESCRIPTION:
XS GIS Cut Line= 3
      2772802.36      7061066.66      2772293.12      7061064.55
      2771874.99      7061075.00
#Sta/Elev= 30
  4494.9  519.79  4532.3  518.93  4636.4  514.25  4740.5  510.26  4782.3  506.88
  4812.3  508.80  4832.3  507.89  4852.3  508.93  4872.3  506.27  4892.3  509.79
  4902.3  510.51  4962.3  509.54  4972.3  509.09  4982.3  507.17  4992.3  502.99
  4997.5  502.37  4998.0  501.57  5003.4  501.57  5003.9  502.37  5012.3  503.39
  5022.3  502.72  5042.3  506.09  5072.3  507.84  5092.3  507.94  5114.0  510.26
  5181.9  513.92  5281.1  519.29  5312.4  520.89  5342.4  520.40  5422.4  521.08
#Mann=6,-1,0
  4494.9    0.16       0  4636.4    0.12       0  4997.5    0.07       0
  5003.9    0.12       0  5181.9    0.16       0  5281.1    0.12       0
Bank Sta=4740.5,5114
Exp/Cntr=0.3,0.1

Type RM Length L Ch R = 1,11532,409,409,409
BEGIN DESCRIPTION:
ARR BRANCH 19.0
END DESCRIPTION:
XS GIS Cut Line= 3
      2772875.02      7060525.00      2772365.00      7060592.65
      2771924.97      7061025.03
#Sta/Elev= 30
  4477.1  521.63  4507.4  520.32  4527.6  521.30  4587.1  518.96  4598.2  517.06
  4665.5  512.66  4731.6  513.29  4743.9  514.90  4769.7  514.37  4813.0  508.97
  4830.2  507.22  4870.5  505.93  4955.1  505.66  4981.5  504.52  4989.1  501.93
  4995.1  501.93  4997.1  497.25  4997.6  496.45  5003.5  497.25  5007.3  498.77
  5014.5  506.54  5023.4  508.20  5141.8  508.04  5177.1  509.74  5219.5  507.86
  5277.1  508.97  5374.1  512.56  5475.9  517.66  5510.3  519.60  5608.5  520.50
#Mann=9,-1,0
  4477.1    0.16       0  4731.6    0.12       0  4955.1    0.16       0
  4997.1    0.07       0  5003.5    0.16       0  5023.4    0.12       0
  5374.1    0.16       0  5475.9    0.12       0  5510.3    0.16       0
Bank Sta=4813,5277.1
Exp/Cntr=0.3,0.1

Type RM Length L Ch R = 1,11123,866,866,866
BEGIN DESCRIPTION:
ARR BRANCH 18.0
END DESCRIPTION:
XS GIS Cut Line= 3
      2772725.04      7060275.00      2772203.86      7060332.43
      2771875.02      7060524.99
#Sta/Elev= 30
  4469.4  518.66  4565.8  515.85  4630.4  514.23  4650.5  511.62  4730.7  508.58
  4773.5  507.31  4922.2  504.88  4942.3  503.68  4974.5  503.88  4982.5  503.20
  4987.4  497.62  4987.9  496.82  4993.4  496.82  4993.9  497.62  5003.5  498.30
  5009.3  502.59  5012.3  503.14  5024.9  505.78  5046.4  506.16  5052.2  507.32
  5067.9  506.47  5073.7  507.04  5119.9  506.71  5181.7  508.48  5184.0  508.58
  5249.7  511.37  5265.4  513.43  5286.8  513.84  5302.5  515.61  5374.8  518.38
#Mann=7,-1,0
  4469.4    0.05       0  4565.8    0.16       0  4773.5    0.12       0
  4987.4    0.07       0  4993.9    0.12       0  5012.3    0.16       0
  5181.7    0.05       0
Bank Sta=4730.7,5184
Exp/Cntr=0.3,0.1

Type RM Length L Ch R = 1,10257,520,520,520
BEGIN DESCRIPTION:
ARR BRANCH 17.0
END DESCRIPTION:
XS GIS Cut Line= 3
      2772624.98      7060024.99      2772225.00      7059775.00
      2771774.95      7059674.99
#Sta/Elev= 30
  4528.2  516.24  4578.3  515.56  4614.9  514.47  4631.2  513.25  4703.3  511.06
  4730.4  509.61  4739.9  509.69  4746.3  508.95  4762.3  508.36  4855.4  506.04
  4913.2  502.29  4971.0  502.09  4976.9  501.47  4986.3  499.40  4988.9  495.61
  4989.4  494.81  4995.0  494.81  4995.5  495.61  5010.1  496.08  5019.1  497.11
  5024.2  502.71  5030.6  503.46  5051.1  502.62  5092.1  504.00  5165.1  503.93
  5203.5  504.83  5257.3  504.87  5275.7  505.65  5355.3  508.36  5460.9  513.81
#Mann=6,-1,0
  4528.2    0.05       0  4631.2    0.16       0  4746.3    0.12       0
  4988.9    0.07       0  4995.5    0.12       0  5275.7    0.05       0
Bank Sta=4762.3,5355.3
Exp/Cntr=0.3,0.1

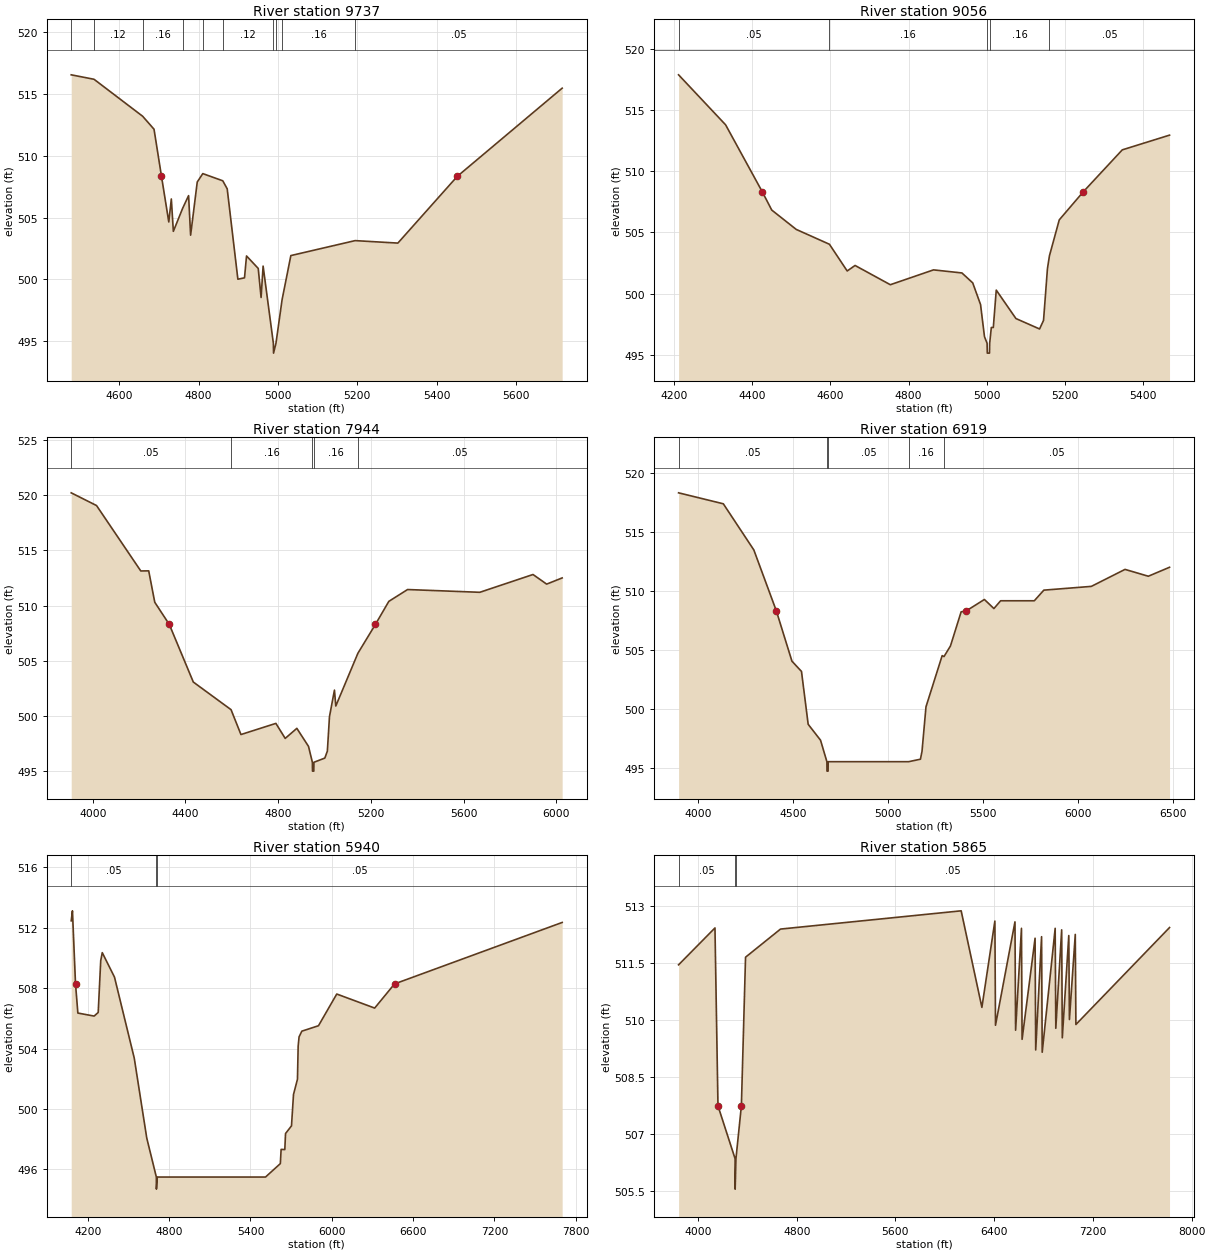
Type RM Length L Ch R = 1,9737,681,681,681
BEGIN DESCRIPTION:
ARR BRANCH 16.0
END DESCRIPTION:
XS GIS Cut Line= 3
      2772825.02      7059475.00      2772375.00      7059375.00
      2771625.01      7059575.00
#Sta/Elev= 30
  4479.2  516.54  4536.7  516.18  4659.2  513.19  4687.9  512.14  4706.7  508.33
  4725.1  504.64  4731.5  506.50  4736.6  503.88  4760.1  505.75  4775.0  506.77
  4780.1  503.57  4796.8  507.87  4810.8  508.55  4861.1  507.97  4872.3  507.32
  4899.2  500.01  4915.9  500.12  4921.0  501.89  4950.5  500.88  4957.7  498.53
  4962.8  501.07  4988.6  494.83  4989.1  494.03  4995.2  494.83  5010.6  498.35
  5032.7  501.92  5194.7  503.13  5302.4  502.93  5452.2  508.33  5716.4  515.46
#Mann=10,-1,0
  4479.2    0.05       0  4536.7    0.12       0  4659.2    0.16       0
  4760.1    0.12       0  4810.8    0.16       0  4861.1    0.12       0
  4988.6    0.07       0  4995.2    0.12       0  5010.6    0.16       0
  5194.7    0.05       0
Bank Sta=4706.7,5452.2
Exp/Cntr=0.3,0.1

Type RM Length L Ch R = 1,9056,1112,1112,1112
BEGIN DESCRIPTION:
ARR BRANCH 15.0
END DESCRIPTION:
XS GIS Cut Line= 3
      2773074.99      7058825.00      2772275.00      7058875.00
      2771825.02      7058925.00
#Sta/Elev= 30
  4212.5  517.86  4332.7  513.78  4426.5  508.31  4450.5  506.83  4513.1  505.25
  4597.9  504.04  4643.3  501.86  4663.4  502.31  4753.5  500.74  4863.8  501.95
  4936.4  501.70  4964.0  500.89  4984.0  499.12  4994.0  496.51  5000.7  495.96
  5001.2  495.16  5006.8  495.16  5007.3  495.96  5011.5  497.25  5016.6  497.25
  5024.1  500.30  5074.4  497.98  5134.8  497.13  5144.9  497.83  5154.9  502.05
  5160.0  503.10  5185.1  506.03  5246.2  508.31  5346.1  511.74  5466.8  512.94
#Mann=5,-1,0
  4212.5    0.05       0  4597.9    0.16       0  5000.7    0.07       0
  5007.3    0.16       0  5160.0    0.05       0
Bank Sta=4426.5,5246.2
Exp/Cntr=0.3,0.1

Type RM Length L Ch R = 1,7944,1025,1025,1025
BEGIN DESCRIPTION:
Mapping XS 5fd8ba6d
END DESCRIPTION:
XS GIS Cut Line= 3
      2773393.72      7058354.40      2772299.45      7058240.92
      2771417.33      7058750.77
#Sta/Elev= 30
  3906.8  520.21  4016.1  519.06  4207.1  513.14  4241.3  513.15  4267.4  510.31
  4330.2  508.30  4433.8  503.09  4596.7  500.59  4639.4  498.34  4790.2  499.35
  4830.4  497.99  4880.7  498.90  4931.0  497.27  4947.7  495.83  4948.2  495.03
  4953.9  495.03  4954.4  495.83  5001.4  496.21  5012.4  496.84  5021.5  499.96
  5043.0  502.36  5048.8  500.92  5144.1  505.69  5219.7  508.30  5277.7  510.39
  5358.6  511.46  5670.4  511.21  5900.0  512.82  5958.9  511.95  6025.8  512.51
#Mann=5,-1,0
  3906.8    0.05       0  4596.7    0.16       0  4947.7    0.07       0
  4954.4    0.16       0  5144.1    0.05       0
Bank Sta=4330.2,5219.7
Exp/Cntr=0.3,0.1

Type RM Length L Ch R = 1,6919,979,979,979
BEGIN DESCRIPTION:
Mapping XS 8c237ee9
END DESCRIPTION:
XS GIS Cut Line= 3
      2773349.75      7057535.79      2772273.34      7057431.62
      2771366.24      7058633.86
#Sta/Elev= 30
  3895.9  518.29  4131.7  517.36  4292.5  513.45  4411.0  508.29  4493.4  504.02
  4543.7  503.15  4578.9  498.67  4644.1  497.32  4677.6  495.50  4678.1  494.70
  4683.9  494.70  4684.4  495.50  5108.2  495.50  5170.6  495.71  5178.9  496.38
  5199.8  500.15  5285.1  504.49  5294.8  504.41  5328.8  505.31  5385.0  508.20
  5412.8  508.29  5507.7  509.25  5557.8  508.48  5593.2  509.14  5770.8  509.14
  5820.9  510.04  6071.4  510.36  6248.9  511.80  6371.7  511.22  6483.4  511.98
#Mann=5,-1,0
  3895.9    0.05       0  4677.6   0.033       0  4684.4    0.05       0
  5108.2    0.16       0  5294.8    0.05       0
Bank Sta=4411,5412.8
Exp/Cntr=0.3,0.1

Type RM Length L Ch R = 1,5940,75,75,75
BEGIN DESCRIPTION:
Mapping XS 59f75b31
END DESCRIPTION:
XS GIS Cut Line= 6
      2773224.14      7056322.32      2772797.08      7056327.53
      2772578.33      7056408.26      2771773.64      7056629.62
      2771745.00      7056681.70      2771306.81      7058701.51
#Sta/Elev= 30
  4077.9  512.47  4087.0  513.13  4109.6  508.29  4127.0  506.36  4247.0  506.16
  4277.0  506.40  4295.6  509.83  4307.0  510.36  4397.1  508.74  4542.8  503.38
  4635.2  498.08  4705.9  495.50  4706.4  494.70  4712.8  495.50  5511.1  495.50
  5620.5  496.39  5626.2  497.33  5653.5  497.32  5658.7  498.38  5702.7  498.89
  5717.6  500.97  5746.8  501.98  5751.9  504.17  5758.6  504.78  5779.0  505.16
  5901.8  505.52  6036.6  507.62  6316.3  506.69  6462.8  508.29  7699.2  512.36
#Mann=3,-1,0
  4077.9    0.05       0  4705.9    0.03       0  4712.8    0.05       0
Bank Sta=4109.6,6462.8
Exp/Cntr=0.3,0.1

Type RM Length L Ch R = 1,5865,79,79,79
BEGIN DESCRIPTION:
Mapping XS 76b7f32a
END DESCRIPTION:
XS GIS Cut Line= 6
      2773447.96      7056188.27      2773160.15      7056160.92
      2772916.87      7056278.05      2771718.95      7056567.12
      2771617.39      7056720.76      2771249.76      7058682.72
#Sta/Elev= 30
  3843.1  511.45  4137.9  512.42  4162.3  507.74  4301.0  506.35  4301.5  505.55
  4307.9  506.35  4351.9  507.74  4385.6  511.65  4668.9  512.39  6132.6  512.87
  6300.5  510.33  6405.7  512.60  6410.8  509.86  6568.5  512.58  6573.6  509.73
  6621.1  512.41  6626.2  509.49  6731.4  512.15  6736.5  509.21  6784.0  512.19
  6789.1  509.15  6894.2  512.41  6899.3  509.78  6946.8  512.37  6951.9  509.53
  7004.5  512.22  7009.6  510.01  7057.1  512.25  7062.1  509.88  7820.7  512.43
#Mann=3,-1,0
  3843.1    0.05       0  4301.0    0.03       0  4307.9    0.05       0
Bank Sta=4162.3,4351.9
Exp/Cntr=0.3,0.1

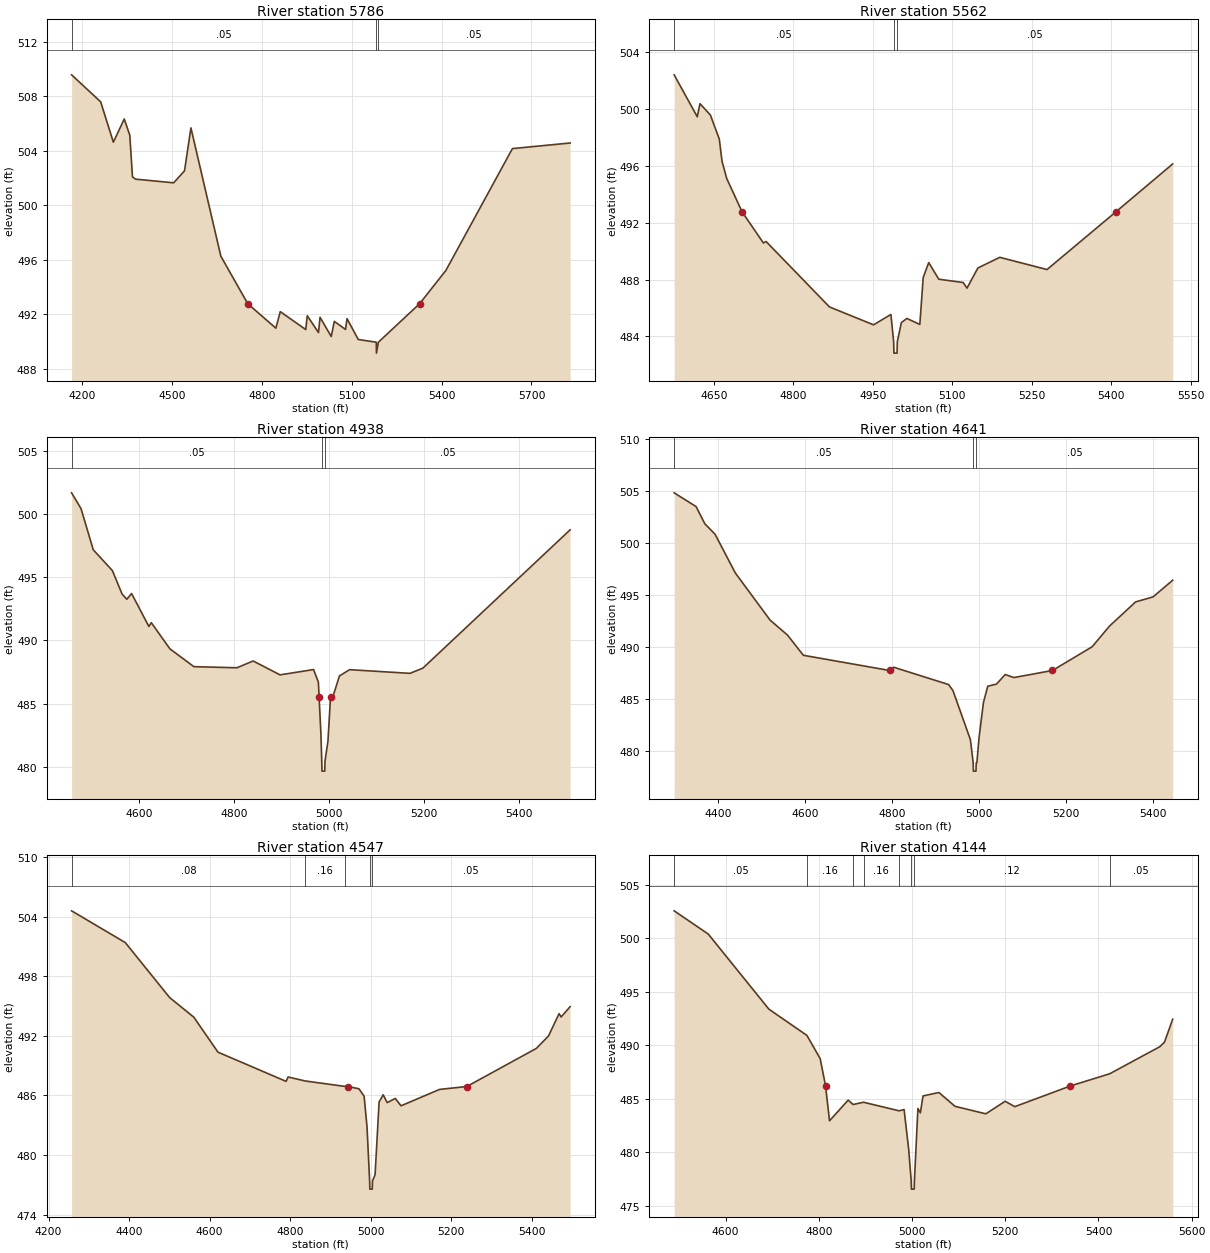
Type RM Length L Ch R = 1,5786,224,224,224
BEGIN DESCRIPTION:
Mapping XS 9adcfcde
END DESCRIPTION:
XS GIS Cut Line= 6
      2772924.71      7055882.18      2772820.52      7056046.28
      2772778.85      7056241.60      2772008.02      7056400.45
      2771765.83      7056494.20      2771592.41      7056631.08
#Sta/Elev= 30
  4164.3  509.57  4261.4  507.59  4303.8  504.63  4340.2  506.33  4358.7  505.14
  4367.6  502.09  4377.8  501.92  4505.3  501.65  4541.4  502.53  4562.8  505.68
  4662.7  496.27  4752.8  492.78  4846.5  490.99  4861.2  492.20  4946.3  490.89
  4951.4  491.90  4988.9  490.67  4994.0  491.79  5031.4  490.38  5041.7  491.49
  5079.1  490.90  5084.2  491.69  5121.6  490.16  5181.9  489.96  5182.4  489.16
  5188.8  489.96  5326.4  492.78  5414.2  495.22  5636.5  504.16  5829.2  504.57
#Mann=3,-1,0
  4164.3    0.05       0  5181.9    0.03       0  5188.8    0.05       0
Bank Sta=4752.8,5326.4
Exp/Cntr=0.3,0.1

Type RM Length L Ch R = 1,5562,624,624,624
BEGIN DESCRIPTION:
Mapping XS 9859598c
END DESCRIPTION:
XS GIS Cut Line= 3
      2772781.48      7055999.40      2772388.22      7056095.76
      2771868.74      7056228.23
#Sta/Elev= 30
  4574.8  502.41  4618.4  499.46  4623.6  500.38  4643.2  499.58  4660.0  497.89
  4665.2  496.32  4674.1  495.11  4702.9  492.78  4743.2  490.58  4748.4  490.68
  4868.0  486.08  4951.2  484.82  4983.9  485.55  4989.1  483.63  4989.6  482.83
  4995.5  482.83  4996.0  483.63  5003.7  484.98  5014.0  485.27  5038.5  484.85
  5044.9  488.15  5055.3  489.20  5074.3  488.03  5120.3  487.80  5127.5  487.40
  5148.1  488.82  5189.4  489.57  5278.6  488.71  5408.9  492.78  5515.8  496.14
#Mann=3,-1,0
  4574.8    0.05       0  4989.1    0.03       0  4996.0    0.05       0
Bank Sta=4702.9,5408.9
Exp/Cntr=0.3,0.1

Type RM Length L Ch R = 1,4938,297,297,297
BEGIN DESCRIPTION:
Mapping XS 58ac1f05
END DESCRIPTION:
XS GIS Cut Line= 3
      2772690.28      7055697.33      2772148.64      7055772.85
      2771713.77      7056028.04
#Sta/Elev= 30
  4457.1  501.68  4477.0  500.43  4502.8  497.17  4543.2  495.52  4563.4  493.68
  4573.5  493.25  4583.6  493.71  4620.1  491.10  4625.2  491.40  4664.4  489.33
  4714.9  487.92  4805.7  487.83  4839.8  488.37  4896.6  487.27  4967.3  487.69
  4977.4  486.70  4978.9  485.55  4982.9  482.50  4984.5  480.45  4985.0  479.65
  4990.9  479.65  4991.4  480.45  4997.6  482.02  5003.1  485.55  5009.0  485.66
  5021.9  487.19  5043.3  487.68  5170.5  487.39  5197.7  487.80  5508.2  498.75
#Mann=3,-1,0
  4457.1    0.05       0  4984.5    0.03       0  4991.4    0.05       0
Bank Sta=4978.9,5003.1
Exp/Cntr=0.3,0.1

Type RM Length L Ch R = 1,4641,94,94,94
BEGIN DESCRIPTION:
Mapping XS 119fa1d4
END DESCRIPTION:
XS GIS Cut Line= 3
      2772755.38      7055564.51      2772060.10      7055530.66
      2771609.84      7055535.86
#Sta/Elev= 30
  4299.4  504.85  4349.8  503.53  4369.9  501.88  4393.5  500.87  4439.9  497.16
  4520.0  492.62  4560.1  491.18  4596.5  489.24  4794.8  487.78  4804.4  488.09
  4930.5  486.43  4940.5  485.85  4980.6  481.14  4987.0  478.91  4987.5  478.11
  4993.5  478.11  4994.0  478.91  4995.5  478.91  5000.6  481.36  5010.6  484.70
  5020.6  486.27  5040.6  486.47  5060.6  487.39  5080.6  487.10  5169.4  487.78
  5260.6  490.06  5300.6  492.05  5360.6  494.37  5400.6  494.85  5445.8  496.45
#Mann=3,-1,0
  4299.4    0.05       0  4987.0    0.04       0  4994.0    0.05       0
Bank Sta=4794.8,5169.4
Exp/Cntr=0.3,0.1

Type RM Length L Ch R = 1,4547,403,403,403
BEGIN DESCRIPTION:
Mapping XS a32adb57
END DESCRIPTION:
XS GIS Cut Line= 3
      2772828.36      7055426.49      2772104.37      7055444.72
      2771591.35      7055418.68
#Sta/Elev= 30
  4257.2  504.58  4390.6  501.38  4500.6  495.85  4560.7  493.87  4620.7  490.35
  4789.8  487.41  4794.8  487.85  4837.2  487.45  4936.3  486.90  4943.5  486.89
  4970.8  486.66  4983.6  485.91  4990.8  482.82  4997.3  477.36  4997.8  476.56
  5003.8  476.56  5004.3  477.36  5010.8  478.02  5020.8  485.34  5030.9  486.06
  5040.9  485.27  5060.9  485.69  5075.2  484.95  5171.0  486.60  5238.5  486.89
  5411.3  490.73  5441.4  491.98  5467.7  494.23  5472.7  493.89  5495.1  494.93
#Mann=5,-1,0
  4257.2    0.08       0  4837.2    0.16       0  4936.3    0.05       0
  4997.3    0.03       0  5004.3    0.05       0
Bank Sta=4943.5,5238.5
Exp/Cntr=0.3,0.1

Type RM Length L Ch R = 1,4144,521,521,521
BEGIN DESCRIPTION:
Mapping XS 1e2de094
END DESCRIPTION:
XS GIS Cut Line= 3
      2772638.21      7055202.53      2772122.60      7055186.91
      2771588.05      7055332.22
#Sta/Elev= 30
  4489.5  502.56  4562.7  500.39  4692.8  493.38  4774.4  490.93  4802.9  488.76
  4814.4  486.21  4822.9  482.96  4862.9  484.89  4873.4  484.48  4895.9  484.69
  4972.4  483.89  4982.9  484.01  4992.9  480.25  4998.1  477.38  4998.6  476.58
  5004.6  476.58  5005.1  477.38  5012.6  484.11  5017.8  483.70  5023.6  485.28
  5057.6  485.60  5092.2  484.31  5158.3  483.61  5199.8  484.78  5220.5  484.28
  5339.7  486.21  5424.2  487.35  5531.4  489.87  5541.7  490.30  5559.3  492.44
#Mann=8,-1,0
  4489.5    0.05       0  4774.4    0.16       0  4873.4    0.12       0
  4895.9    0.16       0  4972.4    0.12       0  4998.1    0.07       0
  5005.1    0.12       0  5424.2    0.05       0
Bank Sta=4814.4,5339.7
Exp/Cntr=0.3,0.1