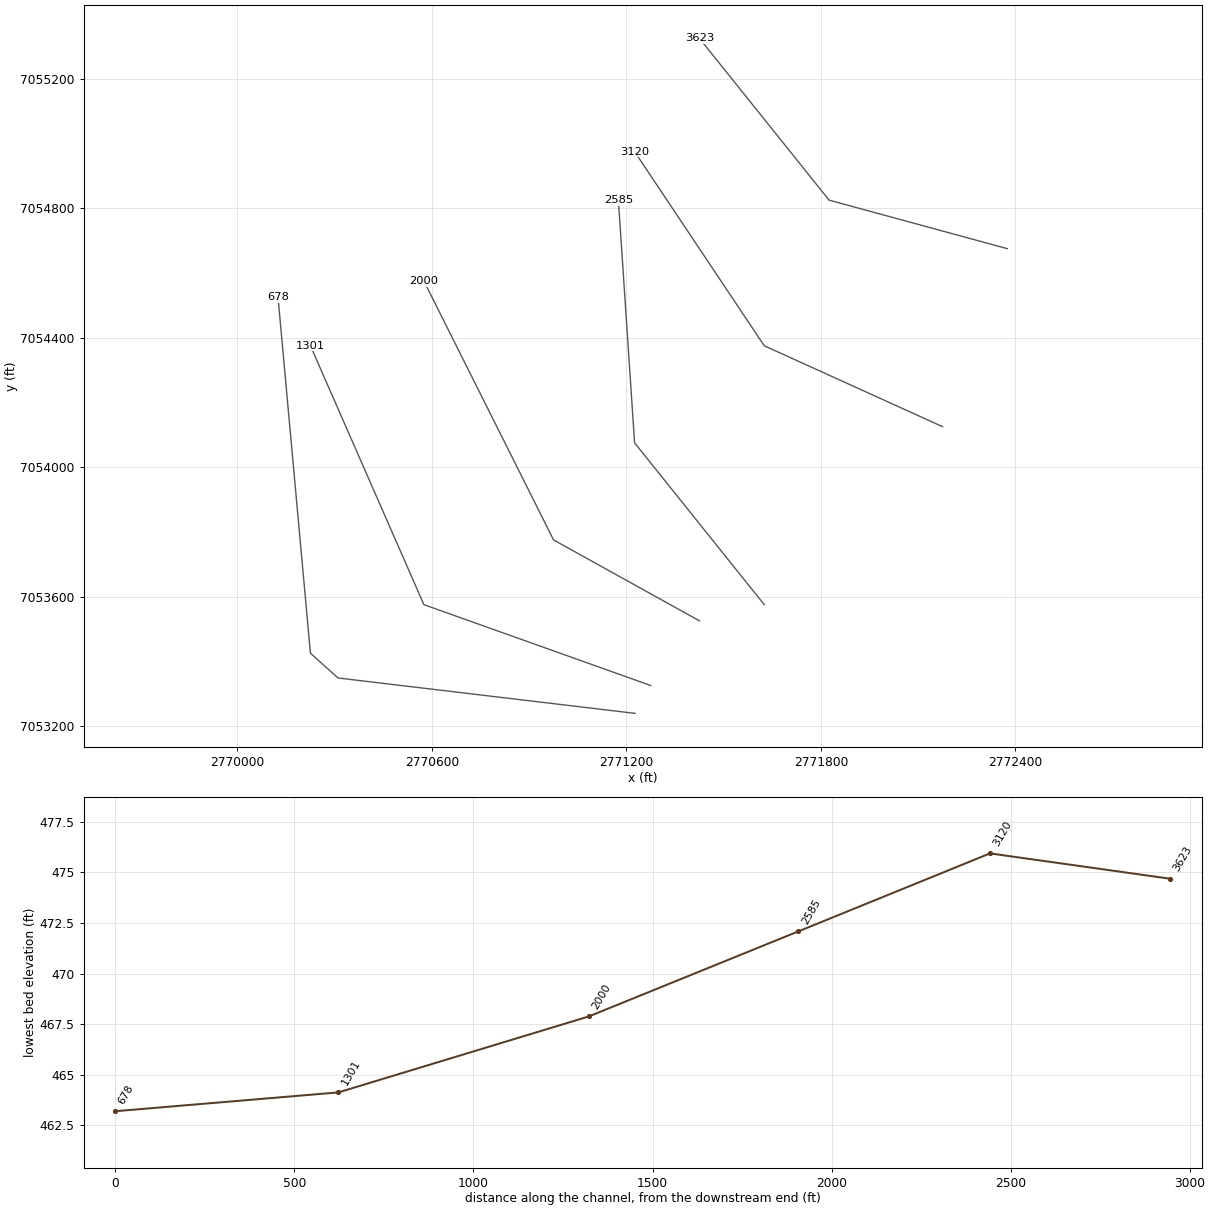
HEC-RAS study ARR BRANCH.prj: ARR BRANCH Base Level Engineering

--- ARR BRANCH.g01 (geometry) --- (continued)

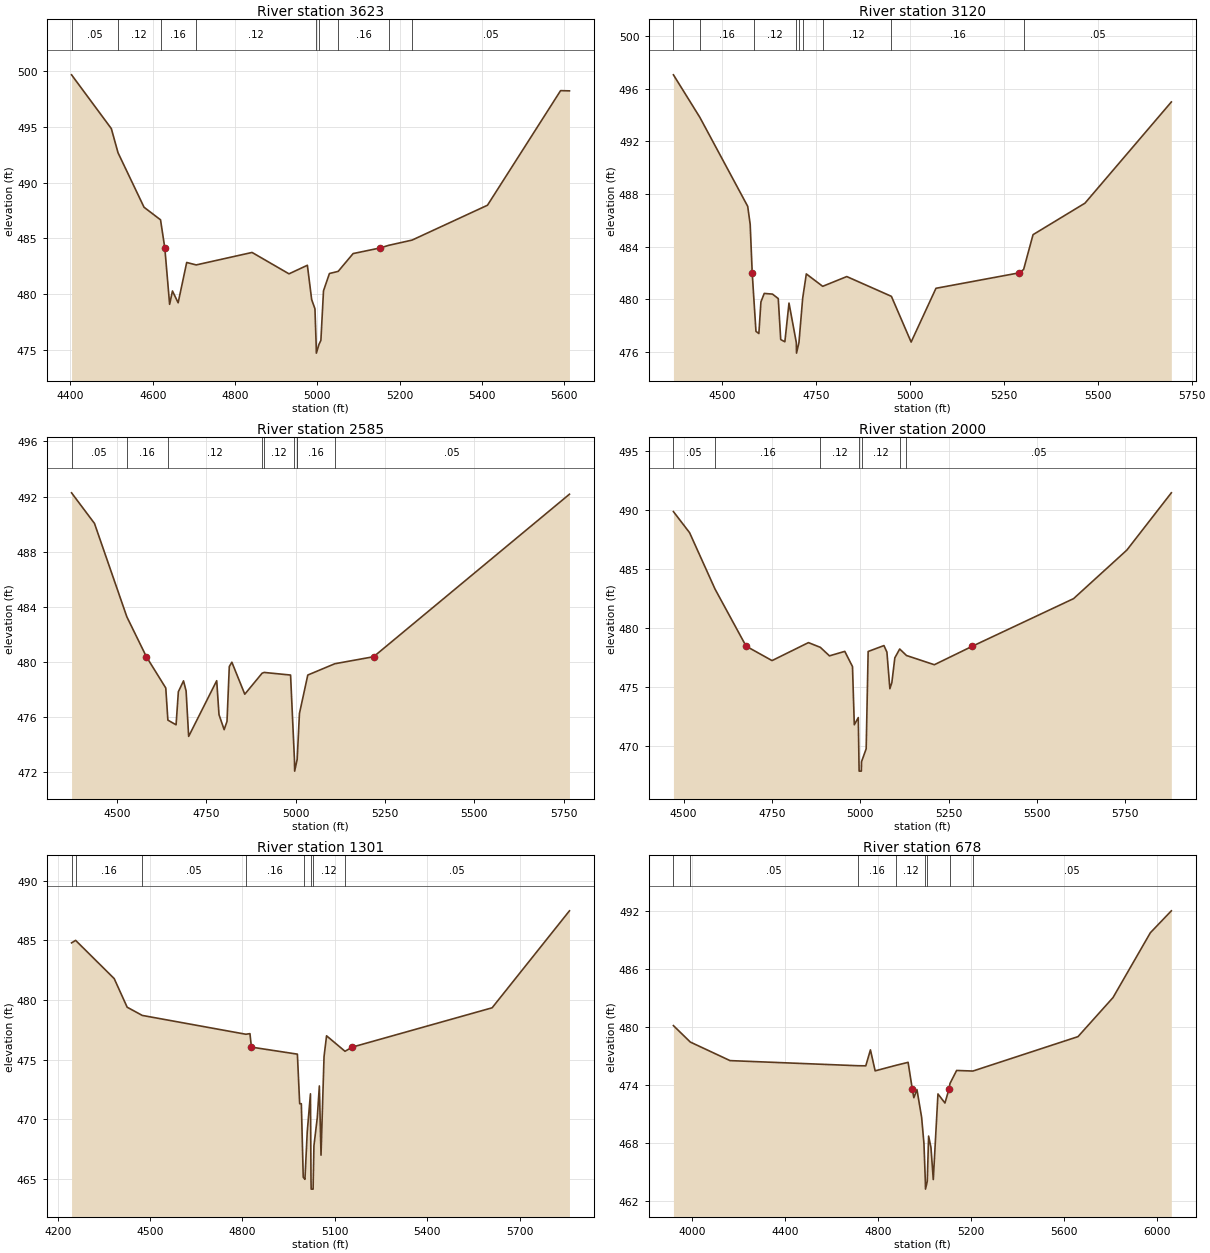
Type RM Length L Ch R = 1,3623,503,503,503
BEGIN DESCRIPTION:
ARR BRANCH 6.0
END DESCRIPTION:
XS GIS Cut Line= 3
      2772375.00      7054675.00      2771825.00      7054825.00
      2771425.00      7055325.00
#Sta/Elev= 30
  4402.7  499.67  4499.4  494.84  4515.7  492.67  4578.9  487.78  4619.0  486.65
  4629.4  484.12  4641.1  479.06  4648.0  480.26  4661.8  479.20  4682.6  482.82
  4705.7  482.60  4841.5  483.72  4931.3  481.80  4976.0  482.57  4986.4  479.49
  4994.4  478.66  4997.3  475.48  4997.8  474.68  5004.3  475.48  5008.8  475.82
  5015.2  480.28  5029.6  481.83  5050.8  482.02  5087.2  483.62  5152.3  484.12
  5173.8  484.36  5230.5  484.83  5413.8  487.96  5591.5  498.25  5613.1  498.23
#Mann=9,-1,0
  4402.7    0.05       0  4515.7    0.12       0  4619.0    0.16       0
  4705.7    0.12       0  4997.3    0.07       0  5004.3    0.12       0
  5050.8    0.16       0  5173.8    0.12       0  5230.5    0.05       0
Bank Sta=4629.4,5152.3
Exp/Cntr=0.3,0.1

Type RM Length L Ch R = 1,3120,535,535,535
BEGIN DESCRIPTION:
ARR BRANCH 5.0
END DESCRIPTION:
XS GIS Cut Line= 3
      2772175.01      7054125.00      2771625.00      7054375.00
      2771224.98      7054975.03
#Sta/Elev= 30
  4370.6  497.05  4441.0  493.82  4568.3  487.07  4574.9  485.70  4580.3  482.02
  4584.3  480.22  4590.3  477.58  4598.0  477.42  4603.5  479.82  4612.3  480.46
  4634.2  480.41  4649.6  480.07  4656.2  476.96  4667.2  476.79  4678.2  479.73
  4697.7  476.73  4698.2  475.93  4704.7  476.73  4714.6  480.09  4724.3  481.94
  4767.9  481.00  4832.0  481.74  4950.8  480.24  5003.3  476.77  5069.4  480.85
  5290.4  482.02  5302.7  482.28  5327.8  484.92  5466.0  487.31  5695.9  494.99
#Mann=9,-1,0
  4370.6    0.05       0  4441.0    0.16       0  4584.3    0.12       0
  4697.7    0.07       0  4704.7    0.12       0  4714.6    0.16       0
  4767.9    0.12       0  4950.8    0.16       0  5302.7    0.05       0
Bank Sta=4580.3,5290.4
Exp/Cntr=0.3,0.1

Type RM Length L Ch R = 1,2585,585,585,585
BEGIN DESCRIPTION:
ARR BRANCH 4.0
END DESCRIPTION:
XS GIS Cut Line= 3
      2771625.02      7053574.98      2771225.00      7054075.00
      2771175.00      7054825.00
#Sta/Elev= 30
  4373.8  492.27  4437.9  490.05  4528.3  483.28  4583.0  480.38  4637.2  478.11
  4643.1  475.78  4666.0  475.44  4672.4  477.84  4686.8  478.63  4694.0  477.90
  4701.2  474.60  4779.6  478.64  4786.0  476.18  4800.4  475.09  4808.4  475.69
  4814.8  479.67  4822.0  479.98  4858.1  477.66  4906.4  479.18  4912.1  479.24
  4986.1  479.05  4997.0  472.88  4997.5  472.08  5004.1  472.88  5004.5  472.90
  5010.9  476.26  5034.2  479.05  5109.7  479.87  5218.3  480.38  5765.8  492.17
#Mann=9,-1,0
  4373.8    0.05       0  4528.3    0.16       0  4643.1    0.12       0
  4906.4    0.16       0  4912.1    0.12       0  4997.0    0.07       0
  5004.1    0.12       0  5004.5    0.16       0  5109.7    0.05       0
Bank Sta=4583,5218.3
Exp/Cntr=0.3,0.1

Type RM Length L Ch R = 1,2000,699,699,699
BEGIN DESCRIPTION:
ARR BRANCH 3.0
END DESCRIPTION:
XS GIS Cut Line= 3
      2771424.99      7053525.01      2770975.00      7053775.00
      2770575.00      7054575.00
#Sta/Elev= 30
  4471.1  489.83  4516.8  488.05  4589.0  483.27  4676.8  478.45  4750.2  477.23
  4853.2  478.75  4886.9  478.35  4912.7  477.63  4956.1  478.01  4977.9  476.72
  4983.0  471.80  4994.3  472.41  4996.2  468.68  4996.7  467.88  5002.9  467.88
  5003.5  468.68  5016.6  469.77  5022.2  478.00  5066.9  478.50  5075.3  477.95
  5083.7  474.85  5089.3  475.37  5097.7  477.46  5111.5  478.21  5130.7  477.66
  5209.5  476.88  5317.5  478.45  5603.6  482.47  5754.5  486.58  5880.3  491.42
#Mann=7,-1,0
  4471.1    0.05       0  4589.0    0.16       0  4886.9    0.12       0
  4996.2    0.07       0  5003.5    0.12       0  5111.5    0.16       0
  5130.7    0.05       0
Bank Sta=4676.8,5317.5
Exp/Cntr=0.3,0.1

Type RM Length L Ch R = 1,1301,623,623,623
BEGIN DESCRIPTION:
ARR BRANCH 2.0
END DESCRIPTION:
XS GIS Cut Line= 3
      2771274.96      7053325.01      2770575.00      7053575.00
      2770224.99      7054375.02
#Sta/Elev= 30
  4245.1  484.80  4258.3  485.01  4383.6  481.80  4425.6  479.40  4474.7  478.71
  4811.0  477.13  4824.3  477.18  4829.0  476.05  4978.3  475.46  4985.7  471.30
  4991.1  471.30  4997.3  465.13  5000.0  465.04  5002.8  464.95  5010.2  468.91
  5020.7  472.13  5022.5  464.93  5023.1  464.13  5029.3  464.13  5029.8  464.93
  5032.0  467.77  5042.9  470.14  5049.6  472.79  5055.0  466.98  5064.8  475.25
  5073.0  477.00  5132.9  475.70  5156.4  476.05  5610.5  479.35  5861.6  487.49
#Mann=8,-1,0
  4245.1    0.05       0  4258.3    0.16       0  4474.7    0.05       0
  4811.0    0.16       0  5000.0    0.12       0  5022.5    0.07       0
  5029.8    0.12       0  5132.9    0.05       0
Bank Sta=4829,5156.4
Exp/Cntr=0.3,0.1

Type RM Length L Ch R = 1,678,0,0,0
BEGIN DESCRIPTION:
ARR BRANCH 1.0
END DESCRIPTION:
XS GIS Cut Line= 4
      2771226.78      7053238.99      2770310.10      7053348.37
      2770225.00      7053425.00      2770125.00      7054524.96
#Sta/Elev= 30
  3920.3  480.12  3992.9  478.42  4163.8  476.50  4713.8  475.97  4747.9  475.96
  4767.9  477.61  4788.2  475.44  4877.4  476.01  4930.0  476.32  4947.9  473.57
  4954.6  472.66  4968.0  473.50  4988.1  470.64  4998.2  467.90  5004.1  464.00
  5004.8  463.20  5012.4  464.00  5018.2  468.69  5028.3  467.51  5038.3  464.19
  5058.4  473.05  5088.5  472.11  5106.0  473.57  5110.3  474.14  5138.7  475.48
  5208.8  475.42  5660.9  478.98  5811.5  483.02  5972.2  489.73  6062.5  492.00
#Mann=8,-1,0
  3920.3    0.16       0  3992.9    0.05       0  4713.8    0.16       0
  4877.4    0.12       0  5004.1    0.07       0  5012.4    0.12       0
  5110.3    0.16       0  5208.8    0.05       0
Bank Sta=4947.9,5106
Exp/Cntr=0.3,0.1

Chan Stop Cuts=-1