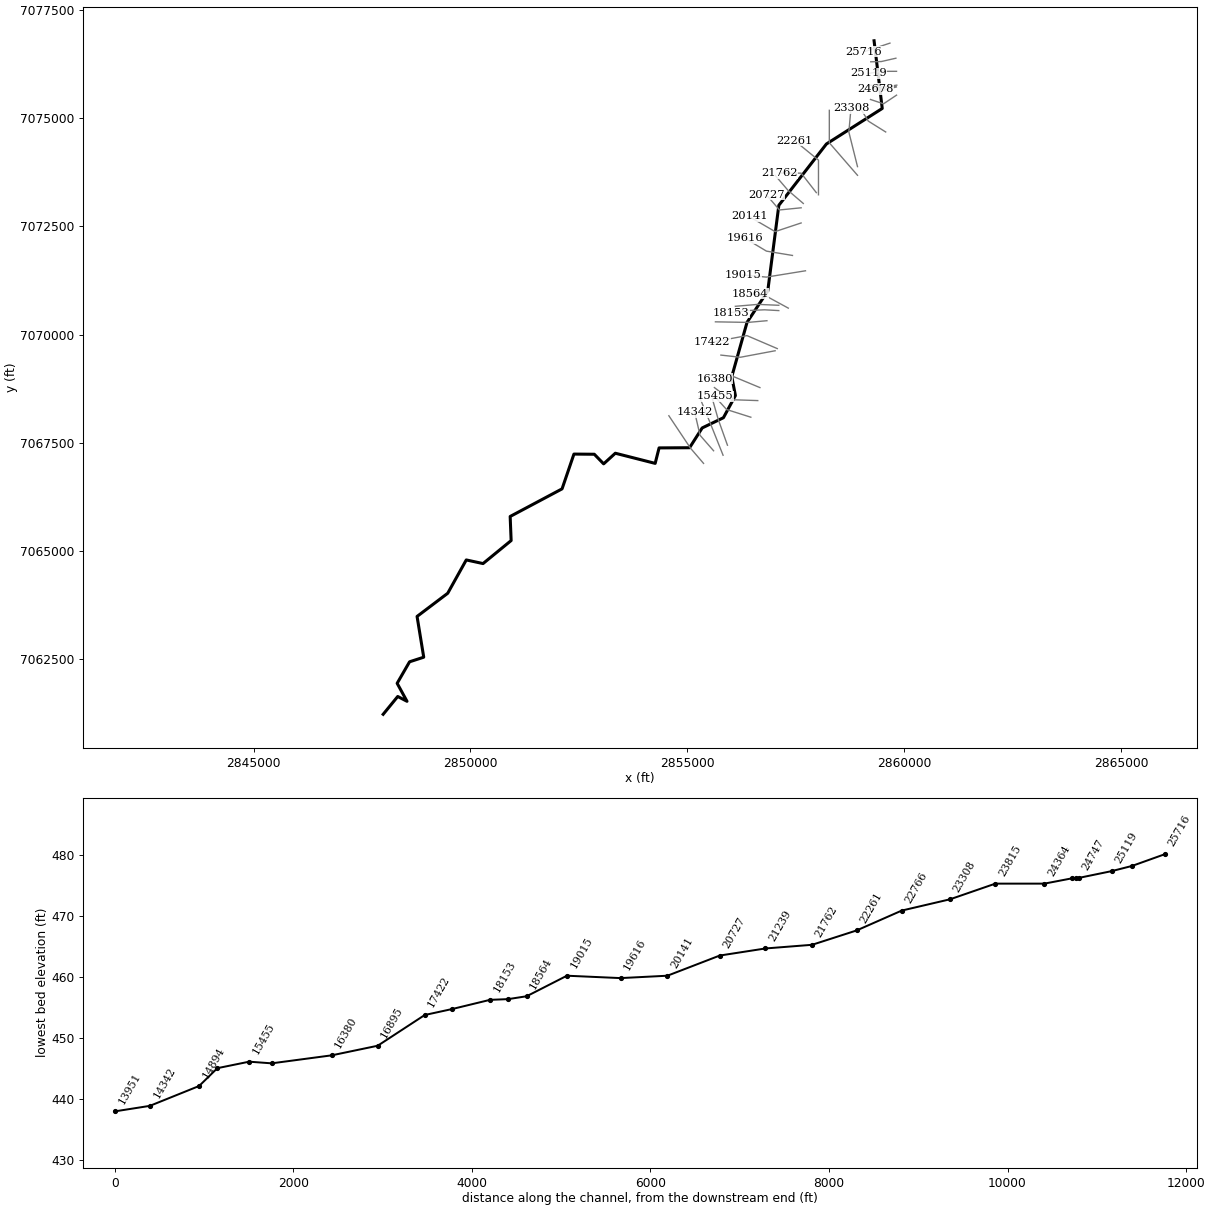
--- BASSET BRANCH.prj (project) ---

Proj Title=BASSET BRANCH Base Level Engineering
Current Plan=p01
Default Exp/Contr=0.3,0.1
English Units
Geom File=g01
Flow File=f01
Plan File=p01
BEGIN DESCRIPTION:
BASSET BRANCH
END DESCRIPTION:

--- BASSET BRANCH.p01 (plan) ---

Plan Title=Multiple Run
Short Identifier=Multiple
Geom File=g01
Flow File=f01
Subcritical Flow
K Sum by GR= 0
Std Step Tol= 0.01
Critical Tol= 0.01
Num of Std Step Trials= 20
Max Error Tol= 0.3
Flow Tol Ratio= 0.001
Split Flow NTrial= 30
Split Flow Tol= 0.02
Split Flow Ratio= 0.02
Log Output Level= 0
Friction Slope Method= 1
Unsteady Friction Slope Method= 2
Unsteady Bridges Friction Slope Method= 1
Parabolic Critical Depth
Global Vel Dist=  1 , 1 , 1
Global Log Level= 0
CheckData=True
Encroach Param= -1, 0, 0, 0
BEGIN DESCRIPTION:
Multiple Run
END DESCRIPTION:

--- BASSET BRANCH.f01 (steady flow) ---

Flow Title=Multiple
Number of Profiles=7
Profile Names=10-year,25-year,50-year,1pct_min,100-year,1pct_plu,500-year
River Rch & RM= BASSET BRANCH,Reach-1,25716
     464     606     720     425     847    1691    1170
River Rch & RM= BASSET BRANCH,Reach-1,23815
    1403    1964    2439    1499    2992    5969    4494
River Rch & RM= BASSET BRANCH,Reach-1,22261
    1780    2510    3131    1931    3854    7689    5830
River Rch & RM= BASSET BRANCH,Reach-1,16380
    1899    2682    3347    2065    4120    8221    6238
River Rch & RM= BASSET BRANCH,Reach-1,12261
    2491    3547    4451    2758    5502   10978    8401
Boundary for River Rch & Prof#=BASSET BRANCH,Reach-1,1
Up Type=0
Dn Type=3
Dn Slope=0.005
Boundary for River Rch & Prof#=BASSET BRANCH,Reach-1,2
Up Type=0
Dn Type=3
Dn Slope=0.005
Boundary for River Rch & Prof#=BASSET BRANCH,Reach-1,3
Up Type=0
Dn Type=3
Dn Slope=0.005
Boundary for River Rch & Prof#=BASSET BRANCH,Reach-1,4
Up Type=0
Dn Type=3
Dn Slope=0.005
Boundary for River Rch & Prof#=BASSET BRANCH,Reach-1,5
Up Type=0
Dn Type=3
Dn Slope=0.005
Boundary for River Rch & Prof#=BASSET BRANCH,Reach-1,6
Up Type=0
Dn Type=3
Dn Slope=0.005
Boundary for River Rch & Prof#=BASSET BRANCH,Reach-1,7
Up Type=0
Dn Type=3
Dn Slope=0.005

--- BASSET BRANCH.g01 (geometry) ---

Geom Title=Existing Conditions

River Reach=BASSET BRANCH,Reach-1
Reach XY= 30
      2859306.93      7076780.07      2859495.28      7075217.95
      2858207.68      7074397.45      2857111.13      7072983.33
      2856855.18      7071003.63      2856377.43      7070280.69
      2856025.69      7069028.43      2856109.33      7068590.77
      2855833.21      7068079.79      2855343.91      7067844.02
      2855052.53      7067386.83      2854349.31      7067382.96
      2854259.04      7067025.79      2853340.16      7067259.92
      2853070.88      7067014.72      2852855.82      7067236.34
      2852385.86      7067240.14      2852112.17      7066437.54
      2850915.40      7065800.31      2850937.70      7065244.23
      2850290.09      7064713.15      2849903.12      7064796.99
      2849475.41      7064027.86      2848768.56      7063492.85
      2848922.16      7062551.84      2848595.49      7062445.93
      2848309.18      7061949.25      2848536.54      7061533.77
      2848322.74      7061645.37      2847986.76      7061234.18

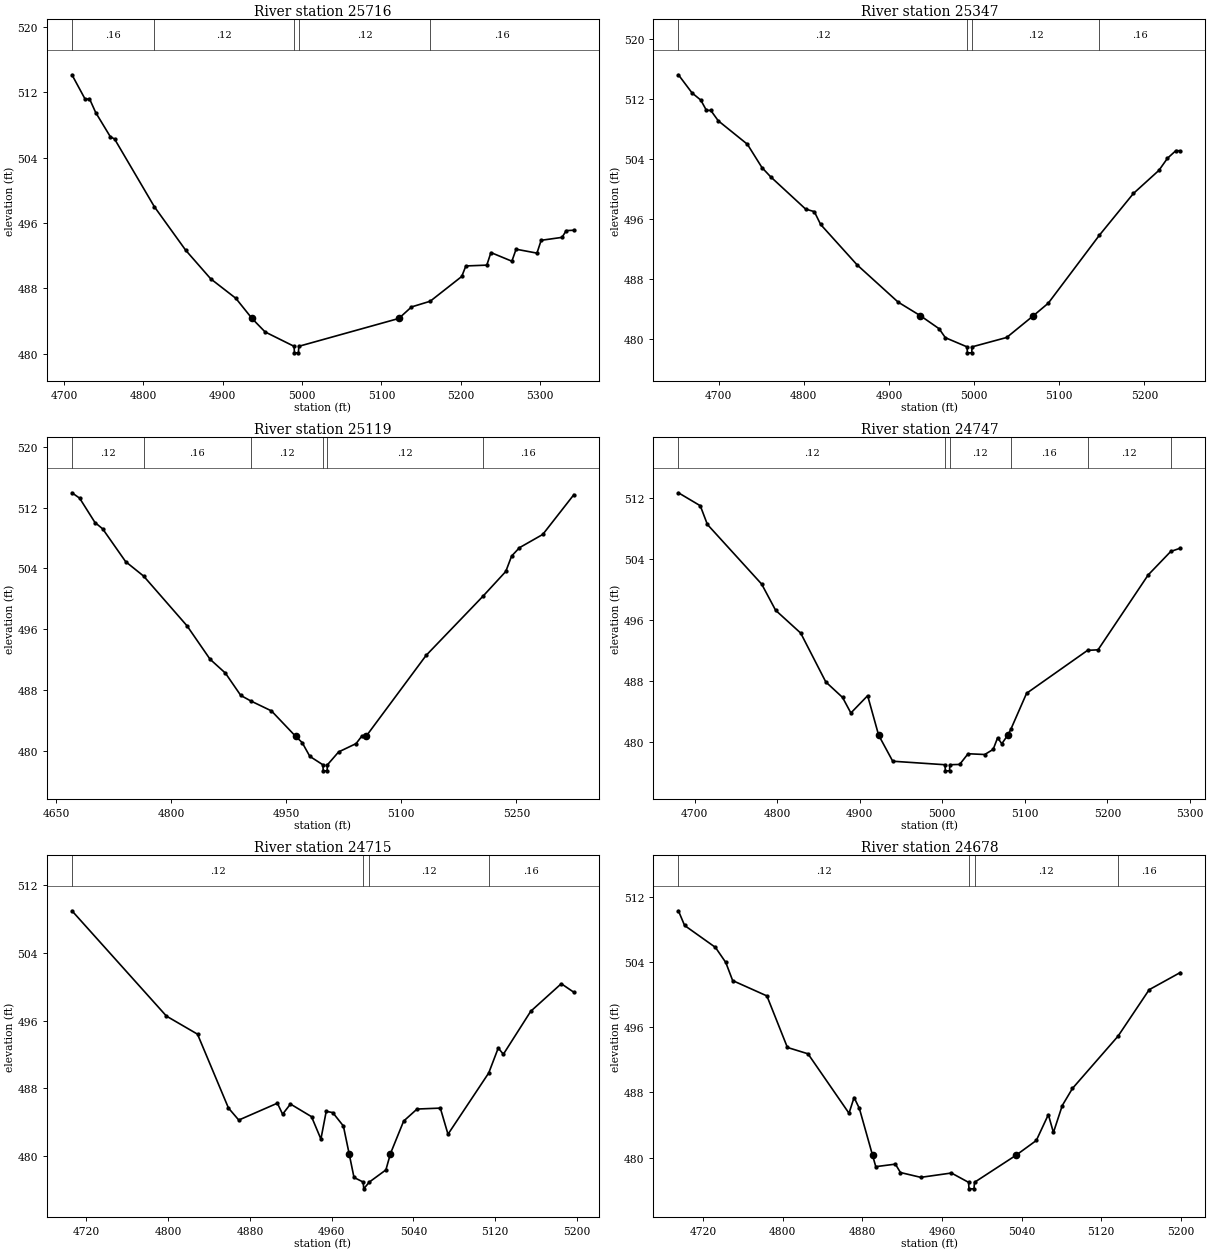
Type RM Length L Ch R = 1,25716,369,369,369
BEGIN DESCRIPTION:
BASSET BRANCH 36.0
END DESCRIPTION:
XS GIS Cut Line= 3
      2859673.41      7076726.16      2859373.39      7076626.16
      2859073.37      7076526.15
#Sta/Elev= 30
  4710.0  514.16  4726.8  511.14  4732.1  511.23  4739.9  509.54  4758.4  506.57
  4763.7  506.30  4813.8  498.01  4853.3  492.68  4884.9  489.17  4916.5  486.79
  4936.9  484.32  4953.4  482.67  4989.9  480.91  4990.4  480.11  4995.4  480.11
  4995.9  480.91  5121.9  484.32  5137.9  485.73  5161.5  486.43  5201.2  489.46
  5206.4  490.75  5232.8  490.85  5238.0  492.39  5264.4  491.33  5269.7  492.80
  5296.0  492.32  5301.3  493.89  5327.6  494.25  5332.9  495.08  5342.5  495.12
#Mann=5,-1,0
  4710.0    0.16       0  4813.8    0.12       0  4989.9    0.07       0
  4995.9    0.12       0  5161.5    0.16       0
Bank Sta=4936.9,5121.9
Exp/Cntr=0.3,0.1

Type RM Length L Ch R = 1,25347,228,228,228
BEGIN DESCRIPTION:
Mapping XS 87ea0c93
END DESCRIPTION:
XS GIS Cut Line= 3
      2859810.62      7076377.67      2859474.69      7076300.94
      2859229.95      7076294.72
#Sta/Elev= 30
  4652.8  515.28  4668.8  512.86  4679.1  511.90  4685.7  510.53  4690.8  510.53
  4699.6  509.14  4733.8  506.01  4750.9  502.90  4761.1  501.67  4802.2  497.36
  4812.4  497.02  4819.8  495.31  4862.7  489.91  4910.8  484.95  4937.0  483.13
  4958.9  481.40  4966.3  480.20  4991.7  478.98  4992.2  478.18  4997.2  478.18
  4997.7  478.98  5038.3  480.23  5069.6  483.13  5087.1  484.80  5147.2  493.88
  5187.1  499.44  5217.1  502.53  5227.1  504.14  5237.1  505.17  5242.2  505.13
#Mann=4,-1,0
  4652.8    0.12       0  4991.7    0.07       0  4997.7    0.12       0
  5147.2    0.16       0
Bank Sta=4937,5069.6
Exp/Cntr=0.3,0.1

Type RM Length L Ch R = 1,25119,372,372,372
BEGIN DESCRIPTION:
BASSET BRANCH 35.0
END DESCRIPTION:
XS GIS Cut Line= 3
      2859824.99      7076075.00      2859475.00      7076075.00
      2859175.03      7076025.01
#Sta/Elev= 30
  4670.7  513.98  4680.7  513.27  4700.7  510.06  4710.7  509.23  4740.7  504.90
  4764.1  503.00  4820.7  496.44  4850.7  492.04  4870.7  490.21  4890.7  487.27
  4903.8  486.54  4930.7  485.23  4962.1  481.89  4970.7  481.06  4980.7  479.24
  4997.7  478.13  4998.2  477.33  5003.2  477.33  5003.7  478.13  5018.2  479.82
  5041.0  480.92  5048.6  481.93  5054.1  481.89  5132.2  492.54  5206.4  500.35
  5236.1  503.61  5243.7  505.64  5253.9  506.74  5284.3  508.49  5324.8  513.73
#Mann=6,-1,0
  4670.7    0.12       0  4764.1    0.16       0  4903.8    0.12       0
  4997.7    0.07       0  5003.7    0.12       0  5206.4    0.16       0
Bank Sta=4962.1,5054.1
Exp/Cntr=0.3,0.1

Type RM Length L Ch R = 1,24747,32,32,32
BEGIN DESCRIPTION:
BASSET BRANCH 34.0
END DESCRIPTION:
XS GIS Cut Line= 3
      2859831.18      7075756.33      2859531.22      7075706.34
      2859231.25      7075756.33
#Sta/Elev= 30
  4680.2  512.65  4706.7  510.95  4715.3  508.50  4781.1  500.68  4798.0  497.25
  4828.4  494.26  4858.8  487.86  4879.1  485.83  4889.2  483.79  4909.5  486.06
  4922.8  480.89  4939.9  477.47  5003.2  477.01  5003.7  476.21  5008.7  476.21
  5009.2  477.01  5021.0  477.05  5031.2  478.45  5051.4  478.35  5061.6  479.02
  5067.0  480.54  5072.1  479.76  5079.3  480.89  5083.0  481.65  5102.1  486.37
  5176.0  492.00  5188.7  492.07  5249.5  501.89  5276.8  504.96  5288.4  505.39
#Mann=6,-1,0
  4680.2    0.12       0  5003.2    0.07       0  5009.2    0.12       0
  5083.0    0.16       0  5176.0    0.12       0  5276.8    0.16       0
Bank Sta=4922.8,5079.3
Exp/Cntr=0.3,0.1

Type RM Length L Ch R = 1,24715,37,37,37
BEGIN DESCRIPTION:
Mapping XS a00ea07e
END DESCRIPTION:
XS GIS Cut Line= 5
      2859806.48      7075730.65      2859588.75      7075697.48
      2859493.35      7075670.52      2859464.32      7075668.44
      2859323.34      7075691.25
#Sta/Elev= 30
  4705.8  508.94  4798.3  496.52  4828.7  494.39  4859.0  485.68  4869.1  484.26
  4906.9  486.25  4912.0  484.95  4919.7  486.15  4940.3  484.66  4949.5  482.02
  4954.7  485.29  4961.1  485.14  4971.5  483.56  4977.1  480.31  4981.9  477.49
  4990.9  476.95  4991.4  476.15  4996.9  476.95  5013.1  478.38  5017.6  480.31
  5030.5  484.14  5043.6  485.56  5066.4  485.67  5073.9  482.59  5113.8  489.82
  5123.1  492.76  5128.1  492.02  5154.9  497.09  5184.8  500.34  5197.1  499.33
#Mann=4,-1,0
  4705.8    0.12       0  4990.9    0.07       0  4996.9    0.12       0
  5113.8    0.16       0
Bank Sta=4977.1,5017.6
Exp/Cntr=0.3,0.1

Type RM Length L Ch R = 1,24678,314,314,314
BEGIN DESCRIPTION:
Mapping XS d3989ca3
END DESCRIPTION:
XS GIS Cut Line= 5
      2859821.05      7075714.07      2859628.15      7075664.29
      2859530.68      7075641.48      2859470.54      7075637.34
      2859328.73      7075666.11
#Sta/Elev= 30
  4695.1  510.26  4701.3  508.46  4732.3  505.77  4742.7  503.92  4749.6  501.70
  4784.0  499.82  4804.6  493.50  4825.3  492.72  4866.5  485.43  4871.6  487.36
  4876.9  486.03  4890.2  480.26  4893.4  478.88  4913.1  479.19  4918.2  478.16
  4938.6  477.57  4969.4  478.10  4986.6  476.96  4987.1  476.16  4992.1  476.16
  4992.6  476.96  5034.1  480.26  5054.7  482.09  5066.8  485.26  5071.9  483.07
  5080.8  486.38  5091.0  488.47  5136.8  494.88  5168.1  500.58  5199.4  502.69
#Mann=4,-1,0
  4695.1    0.12       0  4986.6    0.07       0  4992.6    0.12       0
  5136.8    0.16       0
Bank Sta=4890.2,5034.1
Exp/Cntr=0.3,0.1

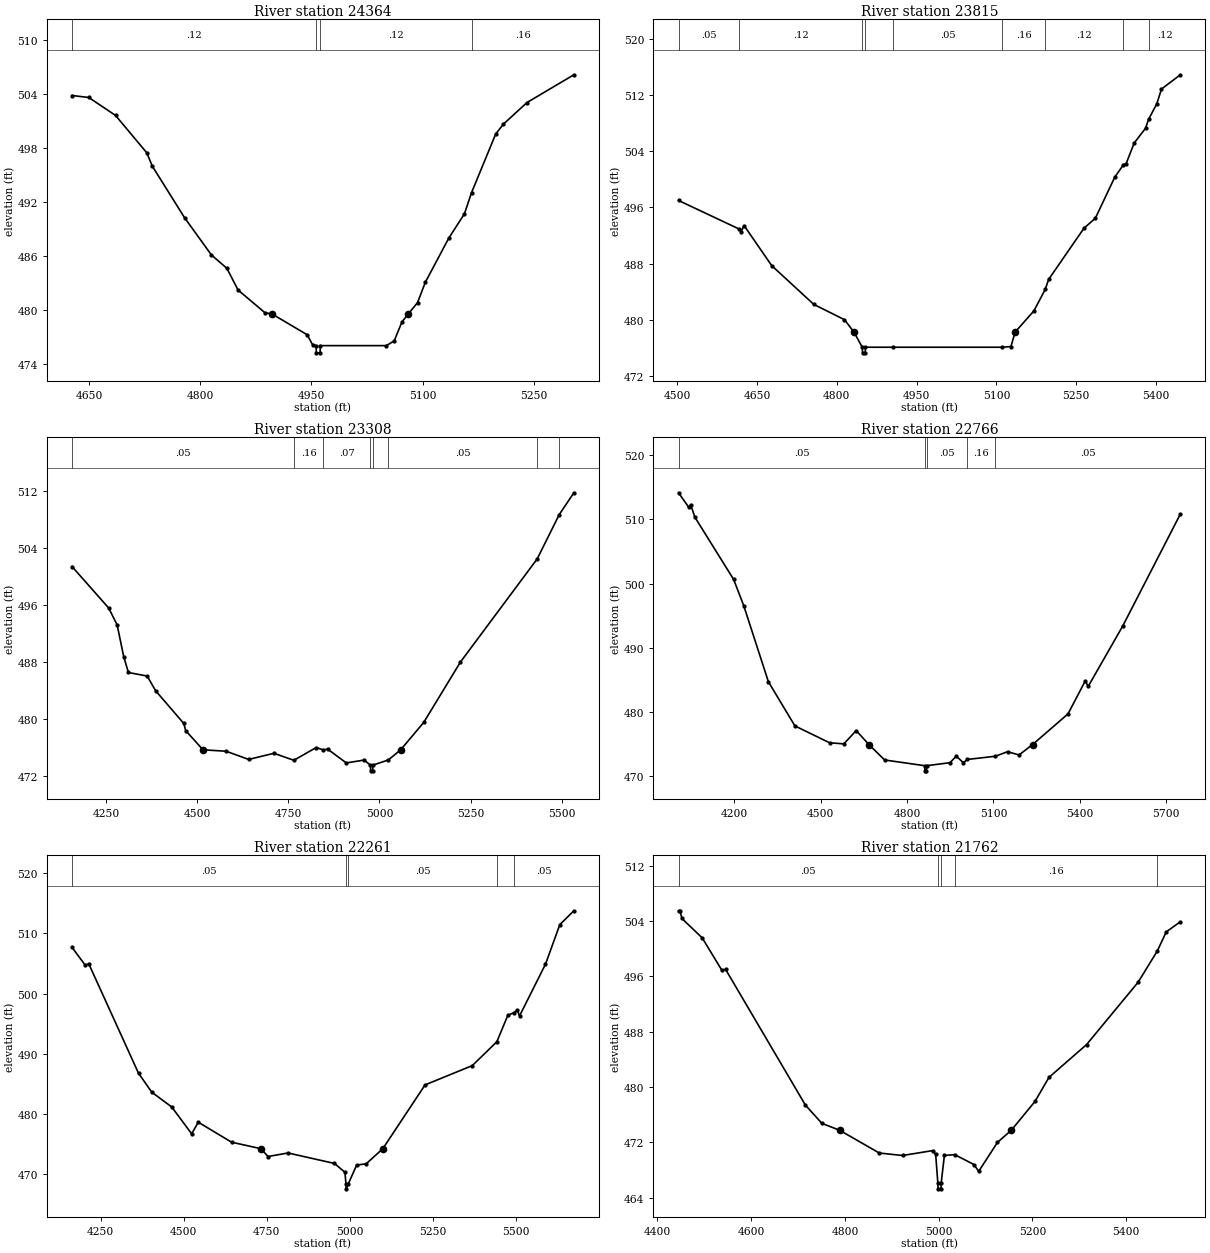
Type RM Length L Ch R = 1,24364,549,549,549
BEGIN DESCRIPTION:
BASSET BRANCH 33.0
END DESCRIPTION:
XS GIS Cut Line= 3
      2859825.01      7075525.01      2859525.00      7075325.00
      2859225.00      7075425.00
#Sta/Elev= 30
  4627.3  503.84  4649.8  503.62  4685.9  501.63  4728.0  497.49  4735.5  496.00
  4779.0  490.28  4815.1  486.16  4836.1  484.66  4851.2  482.25  4887.2  479.75
  4897.5  479.57  4944.3  477.29  4951.8  476.17  4956.3  476.08  4956.8  475.28
  4961.8  475.28  4962.3  476.08  5051.1  476.08  5061.7  476.60  5072.2  478.70
  5080.5  479.57  5093.3  480.86  5103.8  483.12  5135.4  488.01  5156.5  490.71
  5166.1  493.06  5198.7  499.57  5209.2  500.67  5240.9  503.06  5304.1  506.14
#Mann=4,-1,0
  4627.3    0.12       0  4956.3    0.07       0  4962.3    0.12       0
  5166.1    0.16       0
Bank Sta=4897.5,5080.5
Exp/Cntr=0.3,0.1

Type RM Length L Ch R = 1,23815,507,507,507
BEGIN DESCRIPTION:
BASSET BRANCH 32.0
END DESCRIPTION:
XS GIS Cut Line= 3
      2859575.02      7074674.99      2859175.00      7074925.00
      2858925.01      7075324.98
#Sta/Elev= 30
  4502.4  497.00  4615.8  492.95  4619.8  492.54  4625.7  493.42  4677.5  487.72
  4756.6  482.19  4814.3  480.01  4832.3  478.23  4847.8  476.08  4848.3  475.28
  4853.4  475.28  4853.9  476.08  4905.3  476.08  5111.4  476.08  5127.4  476.18
  5135.1  478.23  5170.5  481.26  5191.9  484.34  5198.2  485.75  5264.8  493.06
  5286.0  494.46  5322.6  500.33  5338.8  502.09  5343.8  502.23  5359.1  505.20
  5380.4  507.29  5386.1  508.57  5401.6  510.79  5410.4  512.89  5445.8  514.92
#Mann=9,-1,0
  4502.4    0.05       0  4615.8    0.12       0  4847.8   0.033       0
  4853.9    0.12       0  4905.3    0.05       0  5111.4    0.16       0
  5191.9    0.12       0  5338.8    0.16       0  5386.1    0.12       0
Bank Sta=4832.3,5135.1
Exp/Cntr=0.3,0.1

Type RM Length L Ch R = 1,23308,542,542,542
BEGIN DESCRIPTION:
BASSET BRANCH 31.0
END DESCRIPTION:
XS GIS Cut Line= 3
      2858925.00      7073875.01      2858725.00      7074675.00
      2858775.00      7075225.02
#Sta/Elev= 30
  4156.5  501.36  4257.0  495.55  4280.2  493.18  4298.2  488.73  4311.1  486.51
  4362.6  486.01  4385.8  483.95  4463.1  479.36  4468.3  478.36  4515.8  475.67
  4579.1  475.47  4641.0  474.32  4710.5  475.18  4765.0  474.20  4826.5  475.99
  4846.4  475.64  4857.4  475.78  4909.0  473.83  4957.9  474.23  4975.2  473.52
  4975.7  472.72  4981.3  472.72  4981.8  473.52  5024.2  474.24  5058.2  475.67
  5121.7  479.53  5222.1  487.97  5432.8  502.44  5493.4  508.66  5533.4  511.71
#Mann=8,-1,0
  4156.5    0.05       0  4765.0    0.16       0  4846.4    0.07       0
  4975.2    0.07       0  4981.8    0.07       0  5024.2    0.05       0
  5432.8    0.16       0  5493.4    0.05       0
Bank Sta=4515.8,5058.2
Exp/Cntr=0.3,0.1

Type RM Length L Ch R = 1,22766,505,505,505
BEGIN DESCRIPTION:
BASSET BRANCH 30.0
END DESCRIPTION:
XS GIS Cut Line= 3
      2858924.98      7073675.02      2858275.00      7074425.00
      2858275.00      7075174.96
#Sta/Elev= 30
  4006.5  514.13  4042.1  511.87  4048.7  512.28  4063.0  510.35  4197.8  500.65
  4233.0  496.56  4318.5  484.73  4410.6  477.86  4531.2  475.23  4580.6  475.07
  4623.3  477.13  4667.7  474.96  4722.1  472.56  4861.3  471.67  4861.8  470.87
  4867.4  470.87  4867.9  471.67  4949.1  472.14  4970.9  473.15  4995.6  472.13
  5009.1  472.64  5106.9  473.14  5148.9  473.85  5188.9  473.34  5235.9  474.96
  5358.9  479.73  5418.9  484.86  5428.9  484.00  5548.9  493.40  5748.9  510.81
#Mann=5,-1,0
  4006.5    0.05       0  4861.3    0.03       0  4867.9    0.05       0
  5009.1    0.16       0  5106.9    0.05       0
Bank Sta=4667.7,5235.9
Exp/Cntr=0.3,0.1

Type RM Length L Ch R = 1,22261,499,499,499
BEGIN DESCRIPTION:
BASSET BRANCH 29.0
END DESCRIPTION:
XS GIS Cut Line= 3
      2858025.00      7073225.02      2858025.00      7074025.00
      2857475.01      7074474.99
#Sta/Elev= 30
  4163.6  507.66  4203.6  504.69  4213.6  504.98  4363.6  486.80  4403.6  483.65
  4463.6  481.20  4523.6  476.75  4543.6  478.67  4643.6  475.36  4731.9  474.28
  4753.6  472.98  4813.6  473.57  4953.6  471.83  4985.1  470.36  4988.1  468.42
  4988.6  467.62  4995.0  468.42  5020.3  471.56  5049.0  471.77  5099.1  474.28
  5226.3  484.86  5368.4  488.06  5442.4  492.02  5475.4  496.40  5494.3  496.86
  5504.1  497.27  5510.6  496.29  5588.8  504.88  5631.9  511.44  5674.2  513.74
#Mann=5,-1,0
  4163.6    0.05       0  4988.1    0.03       0  4995.0    0.05       0
  5442.4    0.08       0  5494.3    0.05       0
Bank Sta=4731.9,5099.1
Exp/Cntr=0.3,0.1

Type RM Length L Ch R = 1,21762,523,523,523
BEGIN DESCRIPTION:
BASSET BRANCH 28.0
END DESCRIPTION:
XS GIS Cut Line= 3
      2857974.98      7073275.03      2857625.00      7073725.00
      2857125.05      7073725.00
#Sta/Elev= 30
  4445.3  505.47  4448.4  505.47  4452.5  504.36  4495.9  501.54  4537.6  496.88
  4545.7  496.99  4715.8  477.38  4751.1  474.73  4788.8  473.74  4873.3  470.45
  4923.0  470.09  4987.3  470.80  4993.6  470.25  4998.3  466.07  4998.8  465.27
  5004.8  465.27  5005.3  466.07  5012.2  470.10  5034.4  470.21  5075.3  468.78
  5085.3  467.79  5125.3  471.98  5154.9  473.74  5205.3  477.90  5235.3  481.39
  5315.3  486.12  5425.3  495.14  5466.4  499.68  5485.3  502.42  5515.3  503.88
#Mann=5,-1,0
  4445.3    0.05       0  4998.3    0.03       0  5005.3    0.05       0
  5034.4    0.16       0  5466.4    0.05       0
Bank Sta=4788.8,5154.9
Exp/Cntr=0.3,0.1

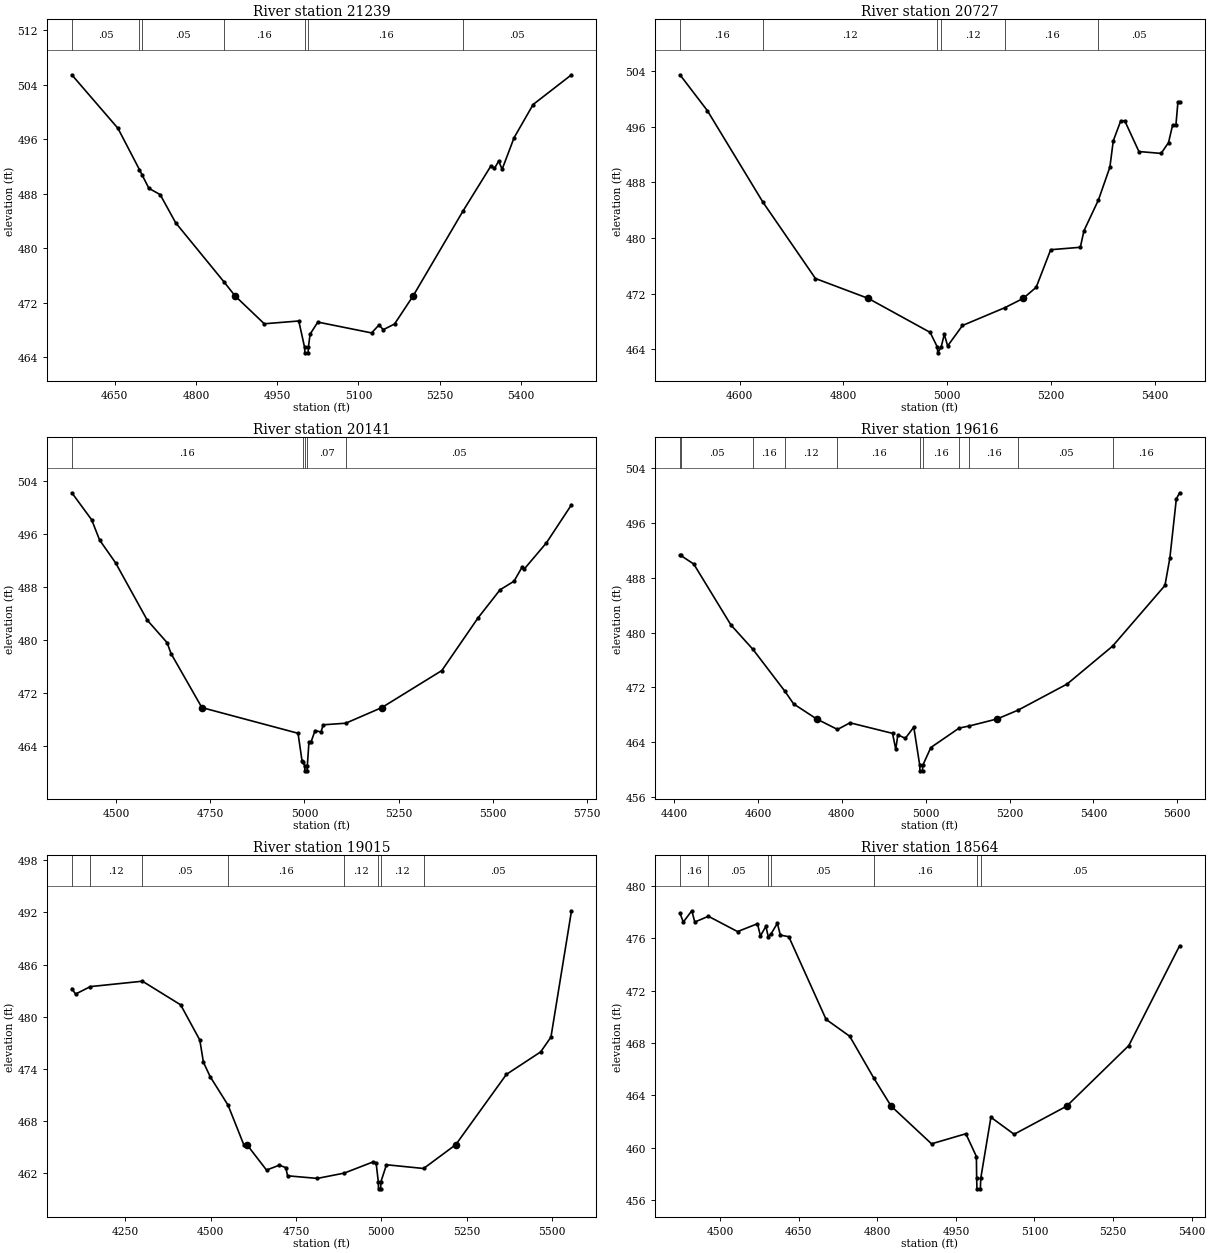
Type RM Length L Ch R = 1,21239,512,512,512
BEGIN DESCRIPTION:
BASSET BRANCH 27.0
END DESCRIPTION:
XS GIS Cut Line= 3
      2857675.03      7073024.98      2857325.00      7073325.00
      2857024.99      7073675.01
#Sta/Elev= 30
  4571.1  505.43  4656.2  497.59  4695.8  491.54  4700.8  490.75  4713.3  488.79
  4734.1  487.87  4762.7  483.74  4851.6  475.10  4872.3  473.02  4926.2  468.93
  4989.9  469.34  5000.6  465.47  5001.1  464.67  5007.1  464.67  5007.6  465.47
  5010.7  467.40  5025.0  469.18  5124.3  467.59  5138.0  468.77  5145.7  468.06
  5166.6  468.90  5200.9  473.02  5293.1  485.49  5344.4  492.07  5351.0  491.70
  5358.6  492.78  5365.2  491.60  5387.2  496.22  5422.3  501.08  5493.1  505.44
#Mann=7,-1,0
  4571.1    0.05       0  4695.8    0.16       0  4700.8    0.05       0
  4851.6    0.16       0  5000.6    0.07       0  5007.6    0.16       0
  5293.1    0.05       0
Bank Sta=4872.3,5200.9
Exp/Cntr=0.3,0.1

Type RM Length L Ch R = 1,20727,586,586,586
BEGIN DESCRIPTION:
BASSET BRANCH 26.0
END DESCRIPTION:
XS GIS Cut Line= 3
      2857625.02      7072925.00      2857125.00      7072875.00
      2856825.00      7073225.00
#Sta/Elev= 30
  4484.7  503.47  4537.5  498.32  4644.7  485.16  4746.0  474.19  4847.9  471.33
  4967.1  466.45  4981.2  464.31  4981.7  463.51  4988.3  464.31  4994.4  466.18
  5000.9  464.50  5029.5  467.44  5110.9  469.99  5146.5  471.33  5171.6  472.93
  5199.6  478.33  5256.7  478.68  5263.8  481.07  5291.6  485.47  5313.7  490.19
  5320.3  493.99  5334.6  496.83  5342.3  496.87  5369.7  492.44  5412.5  492.17
  5426.8  493.72  5434.5  496.19  5441.1  496.28  5444.9  499.52  5448.2  499.52
#Mann=6,-1,0
  4484.7    0.16       0  4644.7    0.12       0  4981.2    0.07       0
  4988.3    0.12       0  5110.9    0.16       0  5291.6    0.05       0
Bank Sta=4847.9,5146.5
Exp/Cntr=0.3,0.1

Type RM Length L Ch R = 1,20141,525,525,525
BEGIN DESCRIPTION:
BASSET BRANCH 25.0
END DESCRIPTION:
XS GIS Cut Line= 3
      2857625.01      7072575.00      2857025.00      7072375.00
      2856424.99      7072725.01
#Sta/Elev= 30
  4382.2  502.19  4434.9  498.11  4456.0  495.05  4498.2  491.63  4582.5  482.96
  4635.2  479.56  4645.7  477.91  4727.6  469.76  4983.0  465.88  4993.6  461.71
  4995.8  461.49  5000.5  461.01  5001.1  460.21  5007.2  460.21  5007.7  461.01
  5012.0  464.58  5017.6  464.58  5028.3  466.30  5044.0  466.07  5049.8  467.16
  5109.7  467.40  5205.5  469.76  5364.9  475.35  5460.8  483.28  5519.5  487.54
  5556.7  488.84  5578.2  490.98  5584.0  490.69  5642.7  494.63  5709.3  500.38
#Mann=5,-1,0
  4382.2    0.16       0  4995.8    0.07       0  5000.5    0.07       0
  5007.7    0.07       0  5109.7    0.05       0
Bank Sta=4727.6,5205.5
Exp/Cntr=0.3,0.1

Type RM Length L Ch R = 1,19616,601,601,601
BEGIN DESCRIPTION:
BASSET BRANCH 24.0
END DESCRIPTION:
XS GIS Cut Line= 3
      2857424.95      7071825.01      2856825.00      7071925.00
      2856325.02      7072224.99
#Sta/Elev= 30
  4414.2  491.27  4415.7  491.27  4447.1  490.00  4535.8  481.10  4588.2  477.55
  4664.2  471.45  4685.3  469.58  4739.9  467.40  4789.8  465.86  4819.7  466.83
  4921.0  465.29  4928.7  462.97  4933.7  465.08  4951.5  464.56  4971.7  466.20
  4985.9  460.62  4986.4  459.82  4992.5  459.82  4993.1  460.62  5012.3  463.22
  5079.8  466.06  5103.6  466.36  5170.7  467.40  5220.8  468.69  5337.3  472.49
  5445.7  478.02  5570.5  486.87  5582.2  490.87  5597.7  499.51  5605.5  500.40
#Mann=11,-1,0
  4414.2    0.12       0  4415.7    0.05       0  4588.2    0.16       0
  4664.2    0.12       0  4789.8    0.16       0  4985.9    0.07       0
  4993.1    0.16       0  5079.8    0.12       0  5103.6    0.16       0
  5220.8    0.05       0  5445.7    0.16       0
Bank Sta=4739.9,5170.7
Exp/Cntr=0.3,0.1

Type RM Length L Ch R = 1,19015,451,451,451
BEGIN DESCRIPTION:
BASSET BRANCH 23.0
END DESCRIPTION:
XS GIS Cut Line= 3
      2857725.20      7071471.00      2856825.00      7071325.00
      2856275.03      7071375.00
#Sta/Elev= 30
  4093.2  483.25  4104.0  482.61  4147.6  483.47  4300.1  484.09  4412.1  481.37
  4468.2  477.32  4478.8  474.77  4498.6  473.11  4551.0  469.83  4597.0  465.29
  4606.3  465.29  4663.7  462.37  4701.2  462.93  4720.3  462.65  4725.3  461.71
  4812.7  461.41  4891.4  462.02  4976.9  463.32  4984.9  463.18  4991.3  461.01
  4991.9  460.21  4998.2  460.21  4998.8  461.01  5015.2  462.98  5124.1  462.55
  5218.3  465.29  5366.6  473.37  5467.1  475.96  5497.2  477.66  5557.4  492.19
#Mann=8,-1,0
  4093.2    0.16       0  4147.6    0.12       0  4300.1    0.05       0
  4551.0    0.16       0  4891.4    0.12       0  4991.3    0.07       0
  4998.8    0.12       0  5124.1    0.05       0
Bank Sta=4606.3,5218.3
Exp/Cntr=0.3,0.1

Type RM Length L Ch R = 1,18564,207,207,207
BEGIN DESCRIPTION:
Mapping XS 490eedad
END DESCRIPTION:
XS GIS Cut Line= 3
      2857329.46      7070609.01      2856834.75      7070878.65
      2856449.21      7070939.30
#Sta/Elev= 30
  4423.3  477.91  4429.7  477.24  4445.9  478.10  4451.6  477.24  4477.6  477.68
  4533.2  476.51  4571.2  477.11  4576.9  476.18  4587.3  476.91  4591.8  476.12
  4597.2  476.34  4609.2  477.14  4614.9  476.24  4631.0  476.12  4702.2  469.80
  4747.3  468.51  4793.2  465.32  4826.4  463.17  4903.5  460.29  4969.0  461.06
  4989.1  459.32  4989.6  457.65  4990.2  456.85  4996.7  456.85  4997.4  457.65
  5016.8  462.32  5061.1  461.02  5161.4  463.17  5280.0  467.80  5377.0  475.43
#Mann=7,-1,0
  4423.3    0.16       0  4477.6    0.05       0  4591.8    0.08       0
  4597.2    0.05       0  4793.2    0.16       0  4989.6    0.03       0
  4997.4    0.05       0
Bank Sta=4826.4,5161.4
Exp/Cntr=0.3,0.1

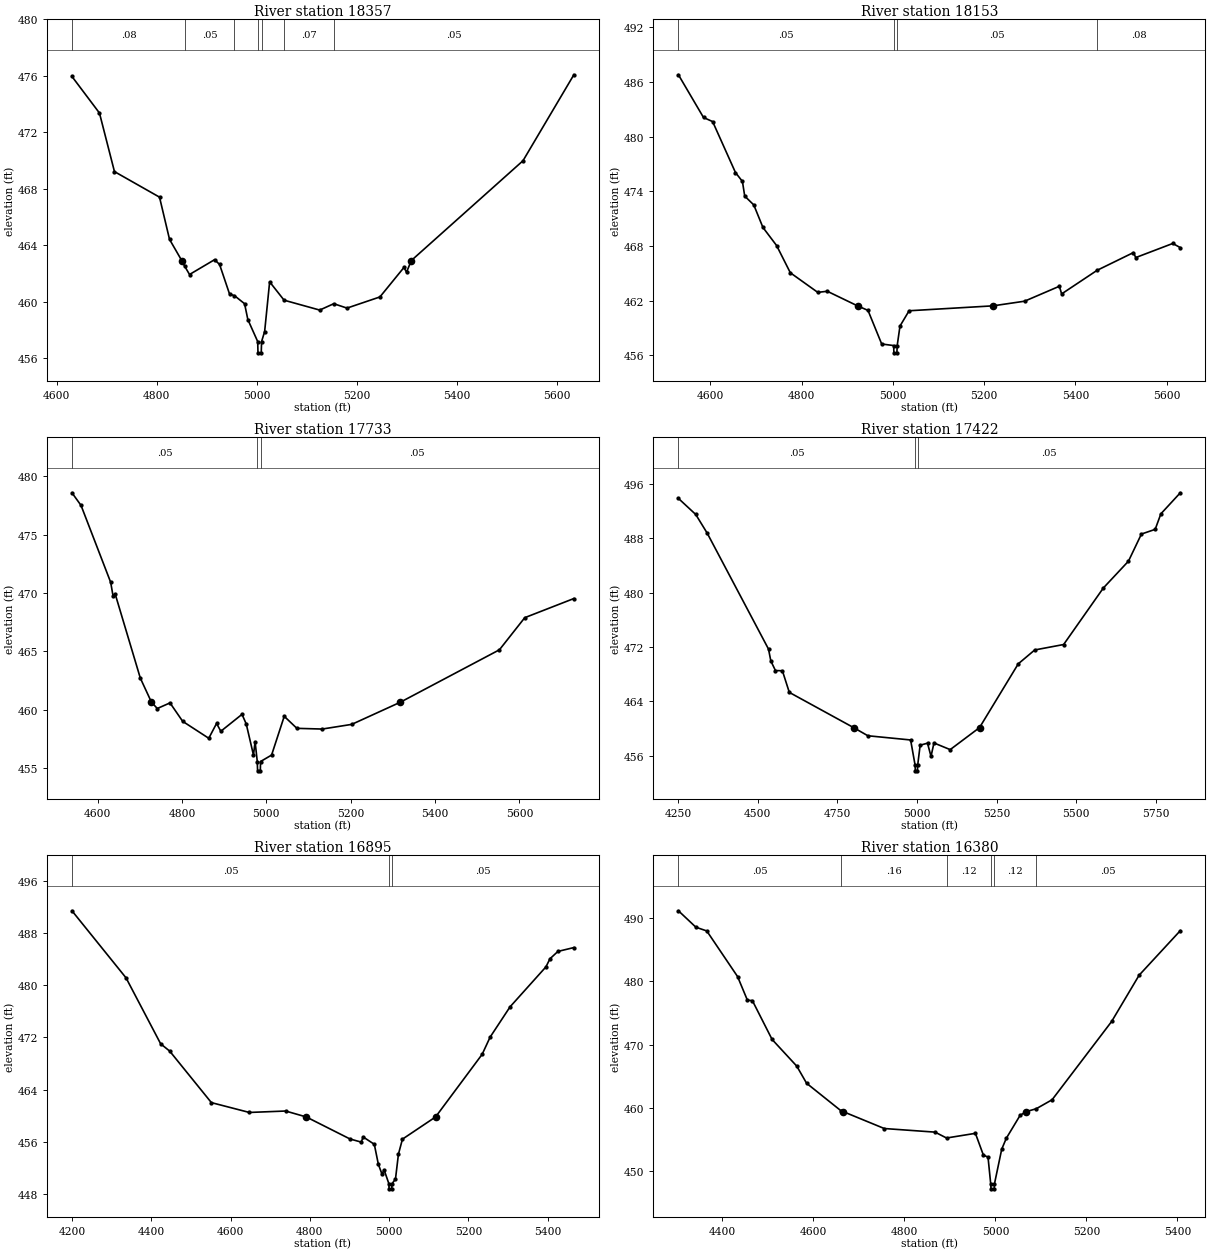
Type RM Length L Ch R = 1,18357,204,204,204
BEGIN DESCRIPTION:
Mapping XS 89e1958c
END DESCRIPTION:
XS GIS Cut Line= 4
      2857109.92      7070674.66      2856750.55      7070690.29
      2856625.55      7070695.49      2856108.65      7070651.34
#Sta/Elev= 30
  4630.7  475.96  4685.7  473.37  4715.7  469.22  4805.8  467.41  4825.8  464.42
  4850.2  462.92  4856.4  462.50  4865.8  461.93  4915.9  462.98  4925.9  462.64
  4945.9  460.54  4955.7  460.43  4975.9  459.86  4982.4  458.74  5002.1  457.18
  5002.7  456.38  5009.2  456.38  5009.9  457.18  5016.0  457.89  5026.0  461.41
  5054.9  460.11  5126.1  459.41  5154.2  459.86  5180.7  459.55  5246.5  460.34
  5294.6  462.43  5299.7  462.09  5309.3  462.92  5532.6  469.99  5634.3  476.08
#Mann=7,-1,0
  4630.7    0.08       0  4856.4    0.05       0  4955.7    0.12       0
  5002.1    0.07       0  5009.9    0.12       0  5054.9    0.07       0
  5154.2    0.05       0
Bank Sta=4850.2,5309.3
Exp/Cntr=0.3,0.1

Type RM Length L Ch R = 1,18153,420,420,420
BEGIN DESCRIPTION:
Mapping XS 9105536e
END DESCRIPTION:
XS GIS Cut Line= 4
      2857109.91      7070552.27      2856779.19      7070570.49
      2856372.94      7070552.27      2856013.53      7070507.99
#Sta/Elev= 30
  4529.8  486.79  4584.8  482.10  4604.8  481.65  4654.9  476.05  4670.1  475.08
  4675.1  473.47  4695.0  472.50  4715.0  470.03  4745.0  468.04  4775.1  465.05
  4835.2  462.90  4856.1  463.02  4922.3  461.42  4945.3  460.92  4975.3  457.23
  5001.5  457.06  5002.1  456.26  5008.6  456.26  5009.3  457.06  5015.4  459.20
  5035.4  460.88  5219.3  461.42  5288.5  461.93  5364.7  463.57  5369.7  462.73
  5447.4  465.32  5527.1  467.27  5532.1  466.72  5613.3  468.27  5629.8  467.81
#Mann=4,-1,0
  4529.8    0.05       0  5001.5    0.03       0  5009.3    0.05       0
  5447.4    0.08       0
Bank Sta=4922.3,5219.3
Exp/Cntr=0.3,0.1

Type RM Length L Ch R = 1,17733,311,311,311
BEGIN DESCRIPTION:
Mapping XS 8ee95f0b
END DESCRIPTION:
XS GIS Cut Line= 3
      2856836.46      7070318.76      2856402.46      7070279.70
      2855648.62      7070292.69
#Sta/Elev= 30
  4539.2  478.59  4560.7  477.51  4631.0  470.92  4636.5  469.78  4641.5  469.94
  4701.3  462.71  4727.7  460.65  4741.5  460.11  4771.6  460.59  4801.7  459.01
  4863.5  457.56  4882.0  458.83  4892.1  458.16  4942.3  459.61  4952.3  458.79
  4969.5  456.12  4973.3  457.27  4978.5  455.57  4979.2  454.77  4985.7  454.77
  4986.3  455.57  5012.4  456.12  5042.4  459.44  5072.4  458.41  5132.4  458.35
  5202.4  458.75  5317.7  460.65  5552.5  465.14  5612.5  467.89  5728.9  469.53
#Mann=3,-1,0
  4539.2    0.05       0  4978.5    0.03       0  4986.3    0.05       0
Bank Sta=4727.7,5317.7
Exp/Cntr=0.3,0.1

Type RM Length L Ch R = 1,17422,527,527,527
BEGIN DESCRIPTION:
BASSET BRANCH 20.0
END DESCRIPTION:
XS GIS Cut Line= 3
      2857074.97      7069675.01      2856375.00      7069975.00
      2855574.99      7069825.00
#Sta/Elev= 30
  4251.5  493.85  4305.9  491.49  4342.1  488.72  4534.3  471.69  4541.6  469.94
  4556.1  468.53  4577.9  468.50  4599.6  465.32  4801.4  460.14  4846.2  458.94
  4980.4  458.32  4994.6  454.58  4995.2  453.78  5001.8  453.78  5002.5  454.58
  5010.3  457.55  5033.4  457.85  5044.4  455.91  5053.7  457.88  5104.6  456.90
  5196.7  460.14  5318.3  469.52  5370.0  471.56  5460.7  472.36  5585.3  480.67
  5664.2  484.62  5704.9  488.61  5748.1  489.30  5765.9  491.58  5827.0  494.68
#Mann=3,-1,0
  4251.5    0.05       0  4994.6    0.03       0  5002.5    0.05       0
Bank Sta=4801.4,5196.7
Exp/Cntr=0.3,0.1

Type RM Length L Ch R = 1,16895,515,515,515
BEGIN DESCRIPTION:
BASSET BRANCH 19.0
END DESCRIPTION:
XS GIS Cut Line= 3
      2857025.02      7069625.00      2856225.00      7069475.00
      2855775.03      7069525.00
#Sta/Elev= 30
  4199.6  491.45  4336.1  481.15  4423.5  471.02  4446.3  469.90  4551.5  461.99
  4647.3  460.48  4738.9  460.70  4791.0  459.79  4901.6  456.40  4929.6  455.93
  4934.7  456.71  4962.7  455.59  4972.9  452.52  4982.2  450.99  4987.3  451.68
  4999.4  449.55  5000.0  448.75  5006.7  448.75  5007.4  449.55  5016.1  450.24
  5023.6  454.08  5033.7  456.38  5117.3  459.79  5234.9  469.41  5255.0  472.05
  5305.3  476.70  5395.9  482.84  5406.0  484.08  5426.1  485.21  5466.3  485.80
#Mann=3,-1,0
  4199.6    0.05       0  4999.4    0.03       0  5007.4    0.05       0
Bank Sta=4791,5117.3
Exp/Cntr=0.3,0.1

Type RM Length L Ch R = 1,16380,673,673,673
BEGIN DESCRIPTION:
BASSET BRANCH 18.0
END DESCRIPTION:
XS GIS Cut Line= 3
      2856674.97      7068775.01      2856075.00      7069025.00
      2855625.04      7068975.00
#Sta/Elev= 30
  4303.5  491.16  4341.9  488.56  4365.8  487.97  4433.5  480.75  4455.1  477.01
  4466.0  476.95  4509.3  470.81  4563.5  466.59  4585.1  463.88  4660.1  459.56
  4665.9  459.38  4755.8  456.72  4867.3  456.15  4892.6  455.22  4956.0  455.96
  4973.6  452.50  4983.7  452.21  4989.6  447.98  4990.3  447.18  4997.2  447.18
  4997.9  447.98  5013.8  453.45  5023.9  455.18  5054.1  458.79  5067.0  459.38
  5089.7  459.85  5124.5  461.27  5255.3  473.65  5315.7  480.97  5406.2  488.02
#Mann=6,-1,0
  4303.5    0.05       0  4660.1    0.16       0  4892.6    0.12       0
  4989.6    0.07       0  4997.9    0.12       0  5089.7    0.05       0
Bank Sta=4665.9,5067
Exp/Cntr=0.3,0.1

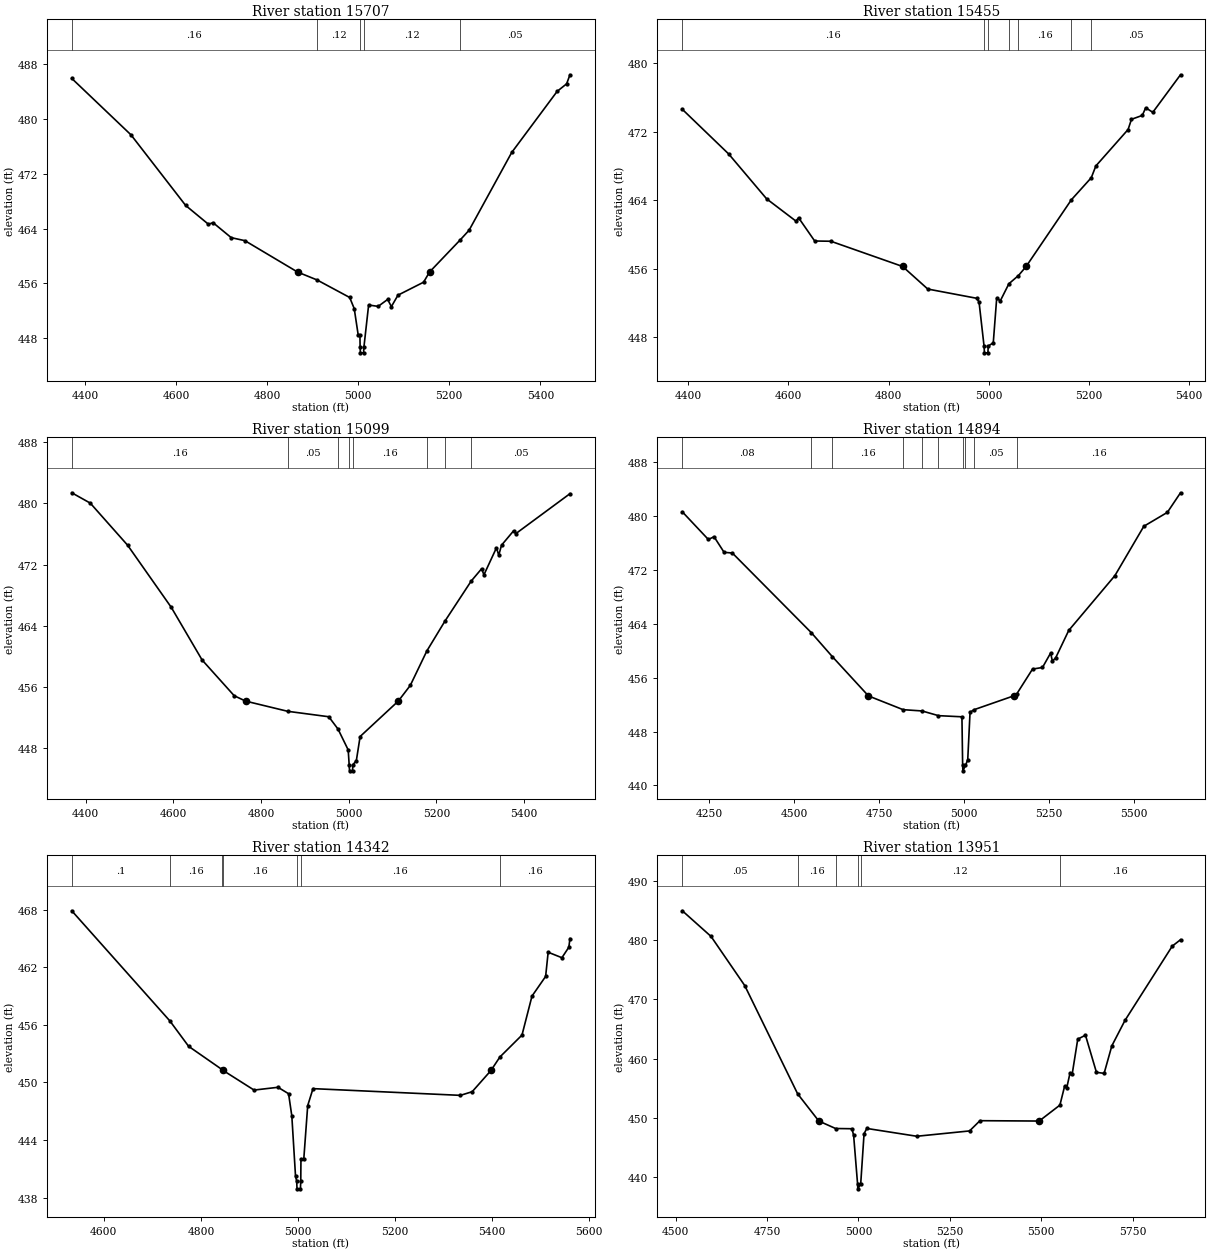
Type RM Length L Ch R = 1,15707,252,252,252
BEGIN DESCRIPTION:
BASSET BRANCH 17.0
END DESCRIPTION:
XS GIS Cut Line= 3
      2856624.98      7068475.00      2855992.51      7068496.39
      2855625.01      7068774.99
#Sta/Elev= 30
  4371.0  485.92  4501.1  477.68  4621.1  467.38  4671.2  464.63  4681.2  464.87
  4721.2  462.68  4751.2  462.24  4866.9  457.66  4909.6  456.51  4981.3  453.95
  4991.3  452.32  5000.1  448.43  5003.8  448.43  5004.2  446.67  5004.9  445.87
  5011.8  445.87  5012.5  446.67  5022.9  452.85  5043.8  452.65  5064.6  453.66
  5072.9  452.62  5087.4  454.29  5143.6  456.18  5156.6  457.66  5224.0  462.35
  5243.5  463.76  5337.1  475.11  5436.9  484.03  5457.7  485.13  5465.0  486.45
#Mann=5,-1,0
  4371.0    0.16       0  4909.6    0.12       0  5004.2    0.07       0
  5012.5    0.12       0  5224.0    0.05       0
Bank Sta=4866.9,5156.6
Exp/Cntr=0.3,0.1

Type RM Length L Ch R = 1,15455,356,356,356
BEGIN DESCRIPTION:
Mapping XS c932f08d
END DESCRIPTION:
XS GIS Cut Line= 3
      2856465.38      7068091.11      2855905.50      7068269.06
      2855633.35      7068571.44
#Sta/Elev= 30
  4388.3  474.62  4480.8  469.40  4556.6  464.15  4615.0  461.55  4620.3  461.94
  4652.5  459.22  4684.8  459.19  4828.0  456.24  4878.2  453.60  4975.8  452.52
  4980.5  452.09  4990.5  446.94  4991.3  446.14  4998.2  446.14  4998.9  446.94
  5008.9  447.31  5015.7  452.50  5023.1  452.24  5040.1  454.22  5059.2  455.18
  5074.5  456.24  5164.8  464.04  5204.5  466.62  5213.7  468.00  5278.0  472.26
  5284.7  473.45  5306.4  473.91  5313.1  474.80  5327.3  474.27  5382.6  478.66
#Mann=7,-1,0
  4388.3    0.16       0  4990.5    0.07       0  4998.9    0.16       0
  5040.1    0.12       0  5059.2    0.16       0  5164.8    0.12       0
  5204.5    0.05       0
Bank Sta=4828,5074.5
Exp/Cntr=0.3,0.1

Type RM Length L Ch R = 1,15099,205,205,205
BEGIN DESCRIPTION:
BASSET BRANCH 16.0
END DESCRIPTION:
XS GIS Cut Line= 3
      2855925.90      7067445.07      2855714.10      7068038.78
      2855575.00      7068525.01
#Sta/Elev= 30
  4368.6  481.37  4410.8  480.02  4495.9  474.53  4595.6  466.41  4665.8  459.55
  4739.1  454.88  4765.1  454.18  4861.0  452.85  4954.7  452.14  4975.8  450.53
  4999.0  447.81  5001.2  445.88  5002.0  445.08  5008.9  445.08  5009.6  445.88
  5017.5  446.39  5026.2  449.56  5113.2  454.18  5140.6  456.23  5178.4  460.73
  5219.6  464.62  5279.4  469.84  5303.3  471.46  5308.5  470.66  5337.1  474.19
  5342.3  473.23  5348.7  474.53  5376.1  476.40  5381.3  476.04  5504.7  481.25
#Mann=8,-1,0
  4368.6    0.16       0  4861.0    0.05       0  4975.8    0.16       0
  5001.2    0.07       0  5009.6    0.16       0  5178.4    0.05       0
  5219.6    0.08       0  5279.4    0.05       0
Bank Sta=4765.1,5113.2
Exp/Cntr=0.3,0.1

Type RM Length L Ch R = 1,14894,552,552,552
BEGIN DESCRIPTION:
BASSET BRANCH 15.0
END DESCRIPTION:
XS GIS Cut Line= 3
      2855824.85      7067213.77      2855521.27      7067975.16
      2855275.00      7068575.00
#Sta/Elev= 30
  4170.2  480.65  4246.9  476.54  4263.7  476.95  4293.3  474.63  4317.6  474.53
  4550.4  462.69  4612.1  459.14  4718.8  453.29  4820.8  451.25  4876.5  451.06
  4925.1  450.36  4994.2  450.19  4996.3  442.96  4997.0  442.16  5004.7  442.96
  5011.3  443.81  5018.1  450.86  5029.6  451.24  5146.2  453.29  5156.1  453.62
  5202.2  457.28  5231.6  457.52  5255.5  459.66  5260.9  458.45  5270.8  458.99
  5308.9  463.02  5445.0  471.17  5530.2  478.50  5599.6  480.57  5638.3  483.48
#Mann=10,-1,0
  4170.2    0.08       0  4550.4     0.1       0  4612.1    0.16       0
  4820.8    0.05       0  4876.5    0.12       0  4925.1    0.16       0
  4996.3    0.07       0  5004.7    0.16       0  5029.6    0.05       0
  5156.1    0.16       0
Bank Sta=4718.8,5146.2
Exp/Cntr=0.3,0.1

Type RM Length L Ch R = 1,14342,391,391,391
BEGIN DESCRIPTION:
Mapping XS bd23b1b2
END DESCRIPTION:
XS GIS Cut Line= 3
      2855606.44      7067316.59      2855293.97      7067674.20
      2855169.24      7068211.21
#Sta/Elev= 30
  4534.0  467.88  4736.0  456.41  4774.7  453.76  4843.2  451.35  4845.1  451.27
  4845.9  451.24  4909.5  449.20  4958.8  449.49  4980.6  448.82  4987.3  446.50
  4994.9  440.24  4997.3  439.71  4998.0  438.91  5005.0  438.91  5005.7  439.71
  5006.1  441.99  5011.9  441.99  5020.0  447.58  5030.9  449.35  5334.5  448.65
  5358.8  449.03  5397.5  451.24  5415.8  452.64  5461.4  454.93  5482.0  458.99
  5510.1  461.04  5515.3  463.56  5543.6  462.99  5557.9  464.08  5560.2  464.98
#Mann=7,-1,0
  4534.0     0.1       0  4736.0    0.16       0  4843.2    0.12       0
  4845.1    0.16       0  4997.3    0.07       0  5005.7    0.16       0
  5415.8    0.16       0
Bank Sta=4845.9,5397.5
Exp/Cntr=0.3,0.1

Type RM Length L Ch R = 1,13951,454,454,454
BEGIN DESCRIPTION:
BASSET BRANCH 14.0
END DESCRIPTION:
XS GIS Cut Line= 3
      2855375.00      7067025.00      2855075.00      7067375.00
      2854574.98      7068125.03
#Sta/Elev= 30
  4518.3  484.97  4596.8  480.64  4689.0  472.34  4833.7  454.05  4891.6  449.46
  4937.4  448.20  4982.3  448.16  4986.8  447.03  4997.6  438.81  4998.3  438.01
  5006.1  438.81  5015.3  447.32  5022.8  448.21  5159.5  446.89  5303.8  447.79
  5332.3  449.52  5494.2  449.46  5550.9  452.15  5563.7  455.33  5569.7  455.09
  5578.7  457.61  5584.7  457.47  5599.7  463.29  5620.8  463.96  5650.8  457.69
  5671.8  457.51  5692.9  462.16  5728.9  466.46  5858.1  479.00  5880.7  480.08
#Mann=6,-1,0
  4518.3    0.05       0  4833.7    0.16       0  4937.4    0.12       0
  4997.6    0.07       0  5006.1    0.12       0  5550.9    0.16       0
Bank Sta=4891.6,5494.2
Exp/Cntr=0.3,0.1