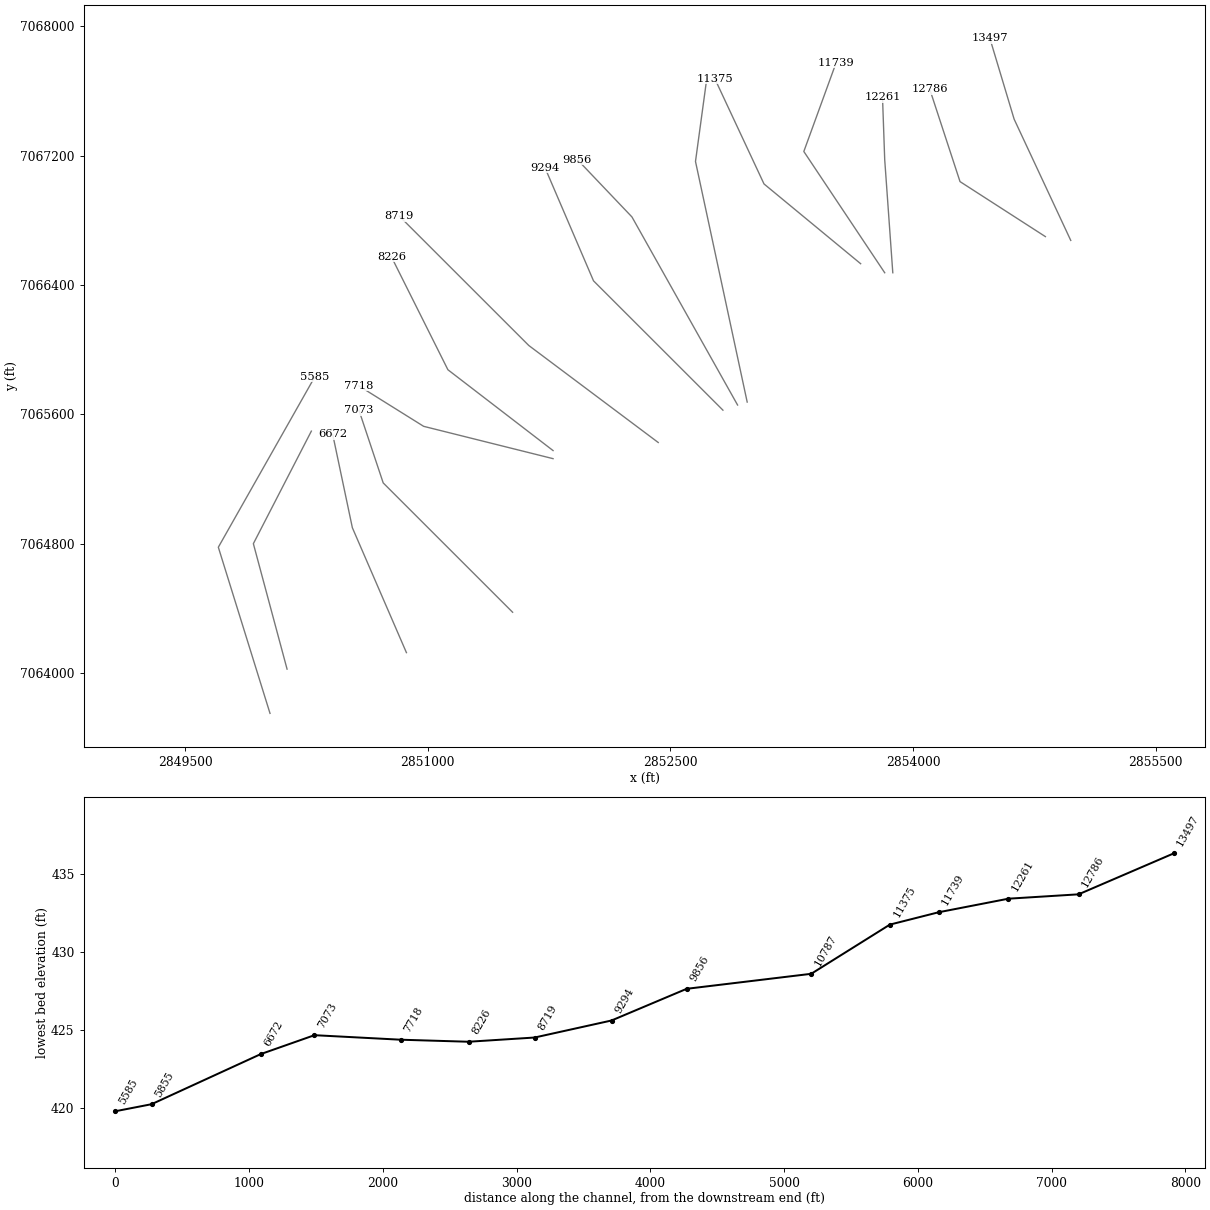
HEC-RAS study BASSET BRANCH.prj: BASSET BRANCH Base Level Engineering

--- BASSET BRANCH.g01 (geometry) --- (continued)

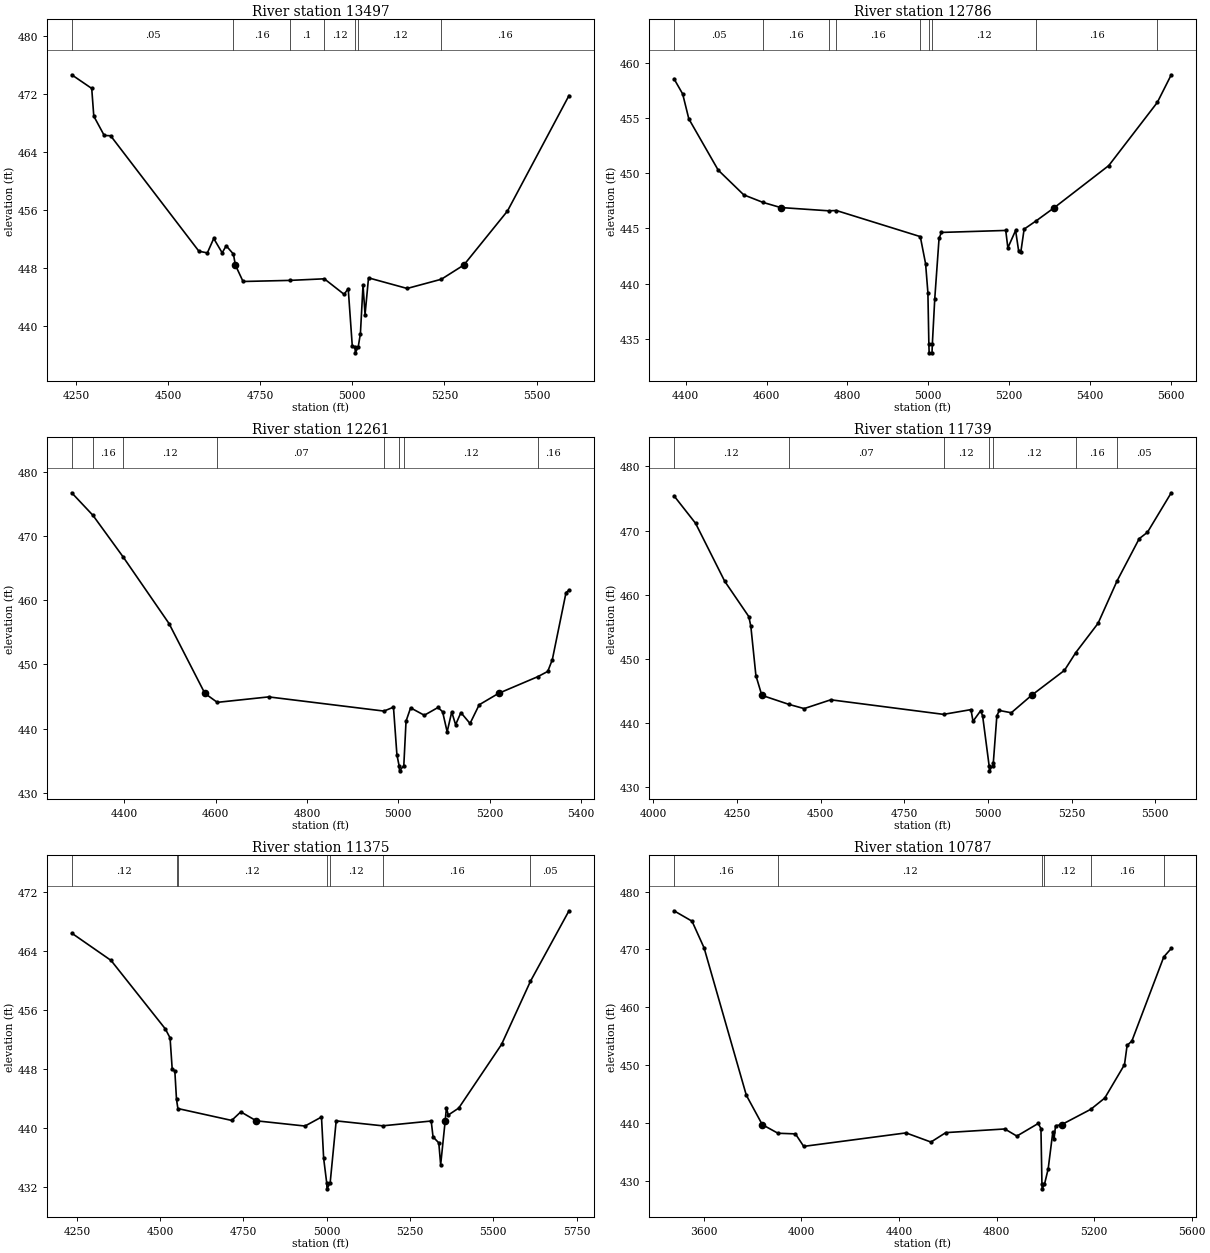
Type RM Length L Ch R = 1,13497,711,711,711
BEGIN DESCRIPTION:
BASSET BRANCH 13.0
END DESCRIPTION:
XS GIS Cut Line= 3
      2854974.98      7066675.04      2854625.00      7067425.00
      2854475.01      7067924.98
#Sta/Elev= 30
  4238.4  474.64  4292.7  472.76  4298.3  468.94  4326.6  466.28  4344.0  466.24
  4583.6  450.33  4606.5  450.10  4623.8  452.09  4646.7  450.11  4657.7  451.08
  4677.3  449.93  4682.5  448.43  4703.4  446.16  4829.9  446.31  4923.9  446.53
  4977.7  444.39  4988.8  445.18  4999.8  437.30  5007.3  437.13  5008.1  436.33
  5015.9  437.13  5021.9  438.98  5029.0  445.66  5034.5  441.60  5043.9  446.66
  5148.7  445.20  5241.6  446.47  5302.6  448.43  5421.0  455.87  5588.0  471.78
#Mann=7,-1,0
  4238.4    0.05       0  4677.3    0.16       0  4829.9     0.1       0
  4923.9    0.12       0  5007.3    0.07       0  5015.9    0.12       0
  5241.6    0.16       0
Bank Sta=4682.5,5302.6
Exp/Cntr=0.3,0.1

Type RM Length L Ch R = 1,12786,525,525,525
BEGIN DESCRIPTION:
Mapping XS bc1252e9
END DESCRIPTION:
XS GIS Cut Line= 3
      2854818.27      7066698.50      2854290.49      7067038.78
      2854103.27      7067610.86
#Sta/Elev= 30
  4370.9  458.59  4392.4  457.21  4407.6  454.95  4480.2  450.30  4543.5  448.05
  4590.7  447.37  4634.6  446.90  4754.3  446.60  4772.4  446.63  4980.1  444.26
  4993.2  441.80  4998.9  439.18  5001.3  434.51  5002.0  433.71  5009.1  433.71
  5009.9  434.51  5015.9  438.63  5026.5  444.09  5032.2  444.64  5191.4  444.82
  5196.7  443.24  5215.8  444.82  5223.3  442.97  5228.6  442.82  5236.9  444.94
  5267.0  445.70  5311.9  446.90  5446.3  450.71  5566.3  456.44  5600.8  458.95
#Mann=9,-1,0
  4370.9    0.05       0  4590.7    0.16       0  4754.3    0.12       0
  4772.4    0.16       0  4980.1    0.12       0  5001.3    0.07       0
  5009.9    0.12       0  5267.0    0.16       0  5566.3    0.05       0
Bank Sta=4634.6,5311.9
Exp/Cntr=0.3,0.1

Type RM Length L Ch R = 1,12261,522,522,522
BEGIN DESCRIPTION:
BASSET BRANCH 11.0
END DESCRIPTION:
XS GIS Cut Line= 3
      2853875.00      7066475.02      2853825.00      7067175.00
      2853811.38      7067561.50
#Sta/Elev= 30
  4285.2  476.75  4331.6  473.24  4398.1  466.72  4498.2  456.38  4576.6  445.50
  4603.8  444.10  4716.3  444.95  4968.7  442.74  4989.5  443.35  4997.0  435.95
  5001.8  434.23  5002.8  433.43  5012.1  434.23  5017.0  441.17  5027.0  443.24
  5057.0  442.09  5087.0  443.30  5097.0  442.64  5107.0  439.51  5117.0  442.60
  5125.5  440.62  5137.1  442.50  5157.1  440.81  5177.1  443.72  5219.5  445.50
  5305.4  448.10  5327.2  448.92  5337.2  450.75  5367.2  461.20  5373.7  461.57
#Mann=8,-1,0
  4285.2    0.12       0  4331.6    0.16       0  4398.1    0.12       0
  4603.8    0.07       0  4968.7    0.12       0  5001.8    0.07       0
  5012.1    0.12       0  5305.4    0.16       0
Bank Sta=4576.6,5219.5
Exp/Cntr=0.3,0.1

Type RM Length L Ch R = 1,11739,364,364,364
BEGIN DESCRIPTION:
BASSET BRANCH 10.0
END DESCRIPTION:
XS GIS Cut Line= 3
      2853824.99      7066475.01      2853325.00      7067225.00
      2853525.00      7067774.99
#Sta/Elev= 30
  4061.6  475.42  4126.2  471.13  4213.3  462.10  4285.4  456.59  4291.4  455.07
  4306.5  447.41  4324.2  444.33  4405.0  442.92  4450.7  442.26  4530.3  443.63
  4867.4  441.36  4949.5  442.10  4955.5  440.28  4978.3  441.92  4984.3  441.13
  5003.7  433.36  5004.7  432.56  5014.0  433.36  5016.2  433.78  5026.8  441.12
  5034.1  441.97  5070.0  441.61  5130.7  444.33  5229.0  448.22  5262.8  450.99
  5329.4  455.55  5386.4  462.18  5452.4  468.74  5477.0  469.73  5548.2  475.89
#Mann=7,-1,0
  4061.6    0.12       0  4405.0    0.07       0  4867.4    0.12       0
  5003.7    0.07       0  5014.0    0.12       0  5262.8    0.16       0
  5386.4    0.05       0
Bank Sta=4324.2,5130.7
Exp/Cntr=0.3,0.1

Type RM Length L Ch R = 1,11375,588,588,588
BEGIN DESCRIPTION:
BASSET BRANCH 9.0
END DESCRIPTION:
XS GIS Cut Line= 3
      2853676.30      7066530.85      2853078.90      7067024.35
      2852775.00      7067675.00
#Sta/Elev= 30
  4234.3  466.42  4352.4  462.72  4515.2  453.45  4529.6  452.22  4536.0  447.98
  4543.9  447.74  4548.9  443.88  4553.1  442.65  4714.6  441.04  4741.9  442.20
  4788.3  440.99  4934.7  440.28  4984.2  441.50  4990.7  435.90  4999.9  432.57
  5000.8  431.77  5010.2  432.57  5028.3  440.98  5167.9  440.31  5313.6  440.96
  5319.1  438.81  5336.4  438.00  5342.0  435.03  5355.6  440.99  5359.3  442.79
  5364.8  441.77  5396.2  442.71  5524.8  451.34  5611.7  459.91  5727.3  469.45
#Mann=7,-1,0
  4234.3    0.12       0  4548.9    0.07       0  4553.1    0.12       0
  4999.9    0.07       0  5010.2    0.12       0  5167.9    0.16       0
  5611.7    0.05       0
Bank Sta=4788.3,5355.6
Exp/Cntr=0.3,0.1

Type RM Length L Ch R = 1,10787,931,931,931
BEGIN DESCRIPTION:
BASSET BRANCH 8.0
END DESCRIPTION:
XS GIS Cut Line= 3
      2852974.99      7065675.05      2852655.37      7067163.31
      2852725.00      7067675.00
#Sta/Elev= 30
  3477.8  476.69  3551.8  474.89  3601.2  470.28  3774.4  444.80  3839.8  439.72
  3904.1  438.23  3975.8  438.12  4009.6  435.96  4429.0  438.29  4531.2  436.71
  4592.2  438.34  4834.0  438.97  4883.4  437.74  4971.0  439.92  4982.2  439.04
  4986.3  429.42  4987.2  428.62  4996.7  429.42  5011.8  432.06  5030.6  438.36
  5035.7  437.19  5042.1  439.53  5067.0  439.72  5186.9  442.38  5243.9  444.32
  5324.7  450.09  5335.4  453.42  5354.9  454.17  5485.8  468.72  5516.4  470.18
#Mann=6,-1,0
  3477.8    0.16       0  3904.1    0.12       0  4986.3    0.07       0
  4996.7    0.12       0  5186.9    0.16       0  5485.8    0.05       0
Bank Sta=3839.8,5067
Exp/Cntr=0.3,0.1

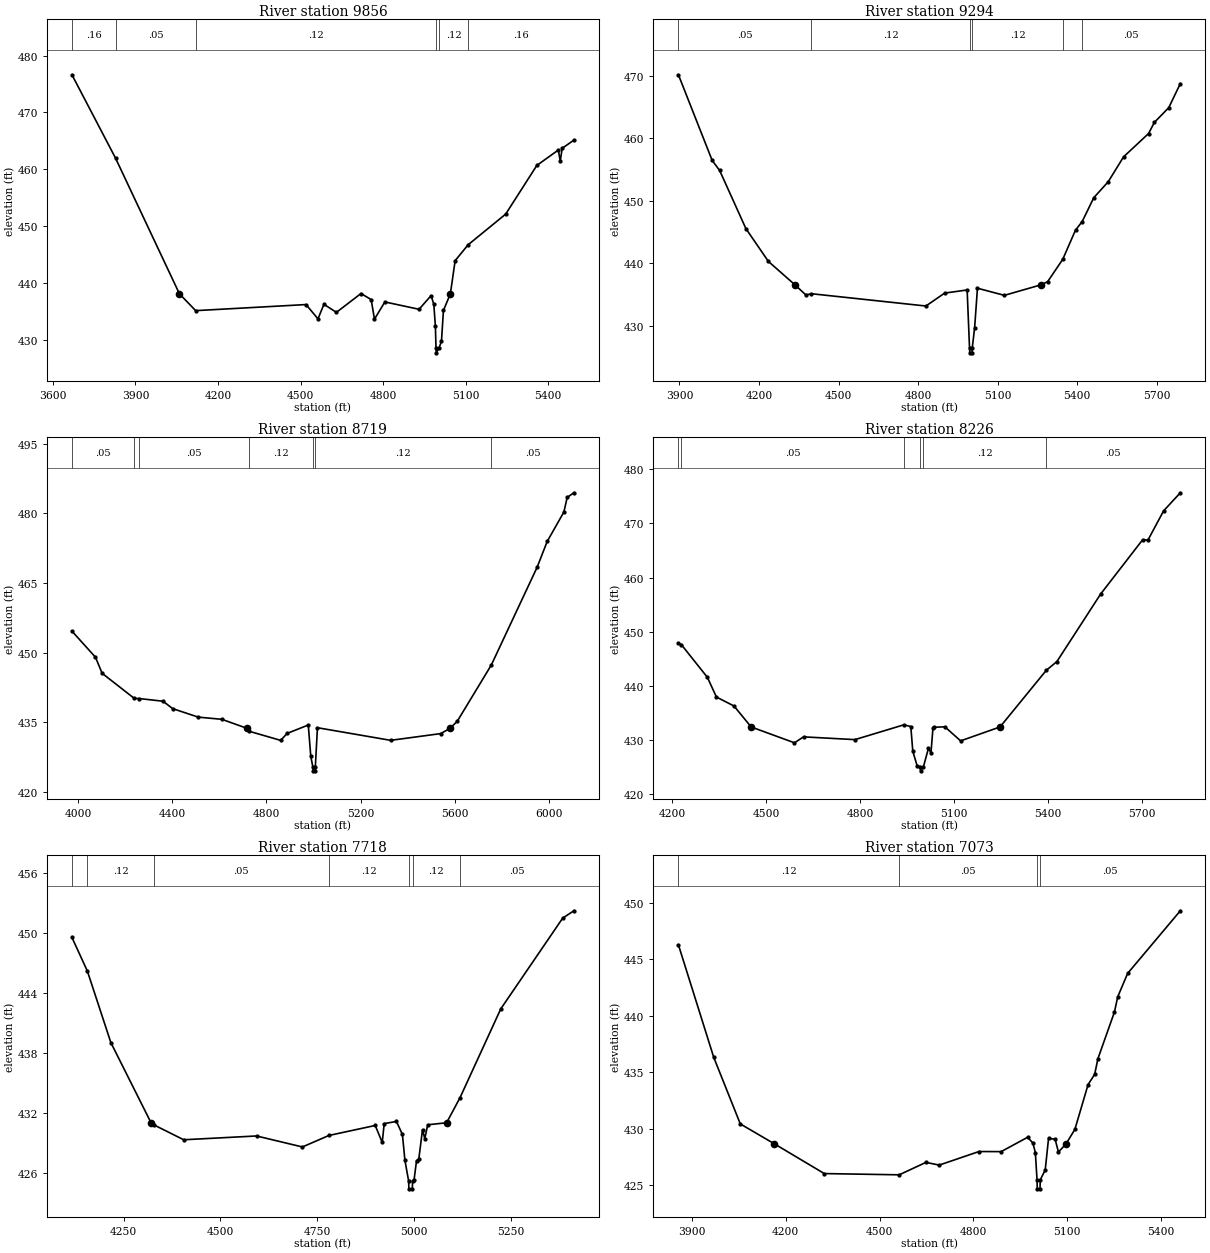
Type RM Length L Ch R = 1,9856,562,562,562
BEGIN DESCRIPTION:
BASSET BRANCH 7.0
END DESCRIPTION:
XS GIS Cut Line= 3
      2852915.49      7065656.84      2852262.72      7066820.03
      2851925.00      7067175.00
#Sta/Elev= 30
  3669.4  476.62  3827.7  461.95  4059.9  438.06  4118.9  435.09  4520.0  436.16
  4563.4  433.64  4585.0  436.20  4630.5  434.79  4719.6  438.10  4756.7  437.04
  4768.7  433.59  4806.4  436.62  4930.7  435.33  4974.5  437.74  4984.3  436.21
  4990.1  432.32  4992.3  428.46  4993.2  427.66  5002.7  428.46  5012.1  429.66
  5019.3  435.12  5044.5  438.06  5061.8  443.89  5109.1  446.69  5245.5  452.09
  5358.7  460.66  5436.8  463.37  5443.7  461.43  5450.9  463.68  5493.2  465.11
#Mann=6,-1,0
  3669.4    0.16       0  3827.7    0.05       0  4118.9    0.12       0
  4992.3    0.07       0  5002.7    0.12       0  5109.1    0.16       0
Bank Sta=4059.9,5044.5
Exp/Cntr=0.3,0.1

Type RM Length L Ch R = 1,9294,575,575,575
BEGIN DESCRIPTION:
BASSET BRANCH 6.0
END DESCRIPTION:
XS GIS Cut Line= 3
      2852824.98      7065625.02      2852025.00      7066425.00
      2851725.01      7067124.98
#Sta/Elev= 30
  3896.1  470.17  4023.4  456.45  4051.6  454.84  4150.6  445.53  4235.5  440.27
  4335.7  436.52  4376.9  434.90  4397.6  435.10  4829.5  433.13  4900.2  435.20
  4985.0  435.70  4994.0  426.43  4994.9  425.63  5003.5  425.63  5004.4  426.43
  5013.3  429.67  5023.9  435.98  5125.4  434.84  5264.1  436.53  5288.6  437.03
  5345.6  440.61  5393.7  445.29  5418.8  446.65  5462.6  450.48  5517.0  453.03
  5575.1  457.03  5669.3  460.76  5691.1  462.54  5745.5  464.91  5789.0  468.76
#Mann=6,-1,0
  3896.1    0.05       0  4397.6    0.12       0  4994.0    0.07       0
  5004.4    0.12       0  5345.6    0.16       0  5418.8    0.05       0
Bank Sta=4335.7,5264.1
Exp/Cntr=0.3,0.1

Type RM Length L Ch R = 1,8719,493,493,493
BEGIN DESCRIPTION:
BASSET BRANCH 5.0
END DESCRIPTION:
XS GIS Cut Line= 3
      2852425.02      7065424.98      2851625.00      7066025.00
      2850825.00      7066825.00
#Sta/Elev= 30
  3974.3  454.63  4074.3  449.01  4102.5  445.55  4239.4  440.13  4258.6  440.12
  4360.8  439.54  4402.5  437.93  4510.8  436.11  4610.8  435.64  4718.1  433.69
  4728.0  433.05  4860.8  431.10  4887.9  432.60  4977.9  434.41  4988.5  427.69
  4997.4  425.34  4998.3  424.54  5006.9  424.54  5007.8  425.34  5016.8  433.83
  5327.9  431.11  5540.0  432.56  5579.7  433.69  5610.7  435.23  5754.9  447.31
  5950.1  468.44  5992.6  473.97  6063.3  480.29  6077.4  483.44  6105.7  484.44
#Mann=7,-1,0
  3974.3    0.05       0  4239.4    0.16       0  4258.6    0.05       0
  4728.0    0.12       0  4997.4    0.07       0  5007.8    0.12       0
  5754.9    0.05       0
Bank Sta=4718.1,5579.7
Exp/Cntr=0.3,0.1

Type RM Length L Ch R = 1,8226,508,508,508
BEGIN DESCRIPTION:
BASSET BRANCH 4.0
END DESCRIPTION:
XS GIS Cut Line= 3
      2851774.97      7065375.02      2851125.00      7065875.00
      2850774.98      7066575.04
#Sta/Elev= 30
  4219.9  447.83  4229.4  447.59  4312.3  441.56  4341.3  437.91  4397.4  436.25
  4452.2  432.38  4590.5  429.45  4619.5  430.55  4783.5  430.04  4939.5  432.77
  4962.0  432.46  4968.3  427.90  4982.8  425.08  4992.1  425.07  4993.0  424.27
  5002.5  425.07  5018.2  428.41  5026.4  427.62  5032.7  432.16  5036.8  432.32
  5070.7  432.41  5121.0  429.81  5246.9  432.38  5394.6  442.85  5428.4  444.46
  5568.2  456.95  5702.4  466.99  5719.1  466.91  5769.4  472.33  5822.6  475.66
#Mann=6,-1,0
  4219.9    0.07       0  4229.4    0.05       0  4939.5    0.12       0
  4992.1    0.07       0  5002.5    0.12       0  5394.6    0.05       0
Bank Sta=4452.2,5246.9
Exp/Cntr=0.3,0.1

Type RM Length L Ch R = 1,7718,645,645,645
BEGIN DESCRIPTION:
BASSET BRANCH 3.0
END DESCRIPTION:
XS GIS Cut Line= 3
      2851774.96      7065325.01      2850975.00      7065525.00
      2850574.98      7065775.01
#Sta/Elev= 30
  4116.6  449.55  4156.5  446.18  4217.1  439.03  4320.9  431.01  4327.7  430.81
  4405.2  429.31  4593.3  429.69  4711.8  428.59  4780.3  429.74  4899.9  430.74
  4918.0  429.04  4923.1  430.93  4954.7  431.14  4970.1  429.84  4976.6  427.25
  4986.1  425.20  4986.9  424.40  4995.6  424.40  4996.5  425.20  5000.1  425.27
  5006.6  427.22  5012.5  427.40  5022.0  430.32  5027.9  429.42  5035.5  430.81
  5084.2  431.01  5118.9  433.52  5224.2  442.41  5384.0  451.48  5412.9  452.22
#Mann=7,-1,0
  4116.6    0.07       0  4156.5    0.12       0  4327.7    0.05       0
  4780.3    0.12       0  4986.1    0.07       0  4996.5    0.12       0
  5118.9    0.05       0
Bank Sta=4320.9,5084.2
Exp/Cntr=0.3,0.1

Type RM Length L Ch R = 1,7073,401,401,401
BEGIN DESCRIPTION:
BASSET BRANCH 2.0
END DESCRIPTION:
XS GIS Cut Line= 3
      2851525.00      7064375.00      2850725.00      7065175.00
      2850575.00      7065624.99
#Sta/Elev= 30
  3856.5  446.27  3969.6  436.31  4054.5  430.43  4163.5  428.67  4323.2  426.04
  4562.8  425.93  4648.5  427.03  4690.9  426.79  4818.2  427.99  4888.9  427.98
  4973.7  429.25  4990.5  428.74  4998.4  427.90  5003.8  425.49  5004.6  424.69
  5013.3  424.69  5014.2  425.49  5030.0  426.36  5040.6  429.15  5061.7  429.08
  5072.2  427.94  5096.7  428.67  5124.9  429.95  5167.1  433.91  5188.1  434.81
  5198.7  436.21  5251.4  440.32  5261.9  441.67  5293.6  443.74  5462.2  449.28
#Mann=4,-1,0
  3856.5    0.12       0  4562.8    0.05       0  5003.8    0.03       0
  5014.2    0.05       0
Bank Sta=4163.5,5096.7
Exp/Cntr=0.3,0.1

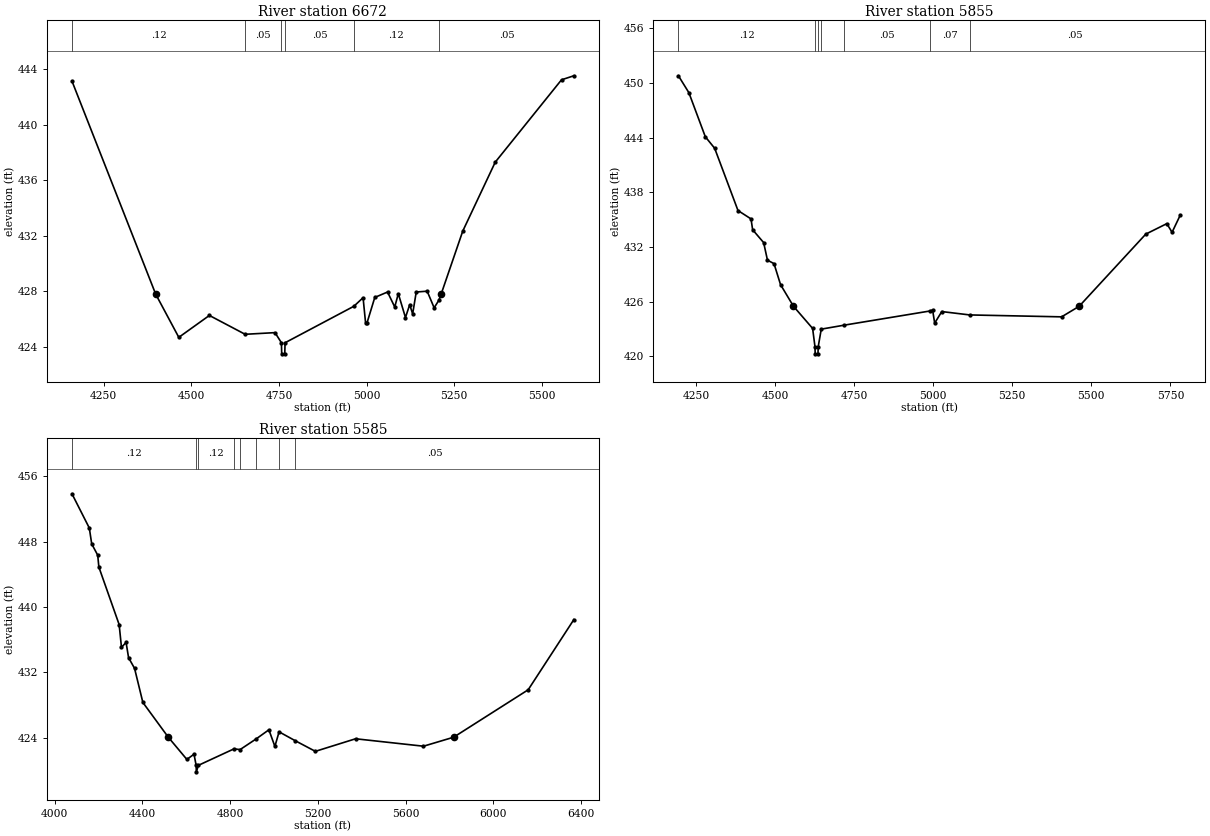
Type RM Length L Ch R = 1,6672,817,817,817
BEGIN DESCRIPTION:
Mapping XS b6c9056a
END DESCRIPTION:
XS GIS Cut Line= 3
      2850868.59      7064125.22      2850534.40      7064897.75
      2850412.88      7065474.98
#Sta/Elev= 30
  4159.7  443.16  4398.5  427.79  4464.5  424.67  4551.7  426.25  4653.7  424.89
  4738.9  425.01  4757.2  424.28  4758.0  423.48  4766.7  423.48  4767.6  424.28
  4963.7  426.91  4990.1  427.53  4997.2  425.72  5001.4  425.72  5023.5  427.55
  5059.9  427.94  5080.4  426.86  5090.6  427.82  5111.0  426.10  5123.1  427.03
  5131.5  426.36  5141.7  427.94  5172.9  428.00  5192.8  426.80  5206.6  427.36
  5212.8  427.79  5274.5  432.34  5367.1  437.31  5556.1  443.25  5591.3  443.54
#Mann=6,-1,0
  4159.7    0.12       0  4653.7    0.05       0  4757.2    0.07       0
  4767.6    0.05       0  4963.7    0.12       0  5206.6    0.05       0
Bank Sta=4398.5,5212.8
Exp/Cntr=0.3,0.1

Type RM Length L Ch R = 1,5855,270,270,270
BEGIN DESCRIPTION:
BASSET BRANCH 1.0
END DESCRIPTION:
XS GIS Cut Line= 3
      2850130.77      7064023.16      2849922.44      7064799.20
      2850280.89      7065495.32
#Sta/Elev= 30
  4194.9  450.79  4227.9  448.94  4279.9  444.10  4309.5  442.83  4383.2  436.00
  4424.4  435.08  4429.5  433.89  4464.3  432.48  4476.4  430.55  4497.1  430.17
  4517.8  427.86  4558.6  425.49  4619.1  423.06  4626.5  421.07  4627.3  420.27
  4636.0  420.27  4636.9  421.07  4646.4  422.98  4719.3  423.42  4991.3  424.98
  4998.4  425.08  5004.9  423.64  5027.4  424.91  5115.7  424.54  5406.2  424.33
  5461.7  425.49  5672.2  433.41  5738.7  434.56  5755.3  433.61  5781.4  435.51
#Mann=7,-1,0
  4194.9    0.12       0  4626.5    0.07       0  4636.9    0.12       0
  4646.4    0.07       0  4719.3    0.05       0  4991.3    0.07       0
  5115.7    0.05       0
Bank Sta=4558.6,5461.7
Exp/Cntr=0.3,0.1

Type RM Length L Ch R = 1,5585,0,0,0
BEGIN DESCRIPTION:
Mapping XS 1d260400
END DESCRIPTION:
XS GIS Cut Line= 3
      2850025.34      7063749.45      2849705.91      7064777.19
      2850302.38      7065831.41
#Sta/Elev= 30
  4079.1  453.88  4158.2  449.69  4169.2  447.74  4196.5  446.36  4201.8  444.90
  4294.2  437.86  4304.8  435.07  4325.8  435.67  4337.2  433.80  4364.5  432.49
  4402.3  428.32  4518.2  424.06  4602.9  421.34  4635.4  421.98  4645.1  420.62
  4646.0  419.82  4655.6  420.62  4817.3  422.63  4845.7  422.55  4919.0  423.86
  4976.7  424.97  5004.0  422.93  5023.1  424.72  5095.5  423.65  5188.5  422.33
  5371.8  423.87  5681.3  422.96  5818.6  424.06  6158.4  429.87  6366.6  438.47
#Mann=8,-1,0
  4079.1    0.12       0  4645.1    0.03       0  4655.6    0.12       0
  4817.3    0.05       0  4845.7    0.07       0  4919.0    0.05       0
  5023.1    0.07       0  5095.5    0.05       0
Bank Sta=4518.2,5818.6
Exp/Cntr=0.3,0.1

Chan Stop Cuts=-1