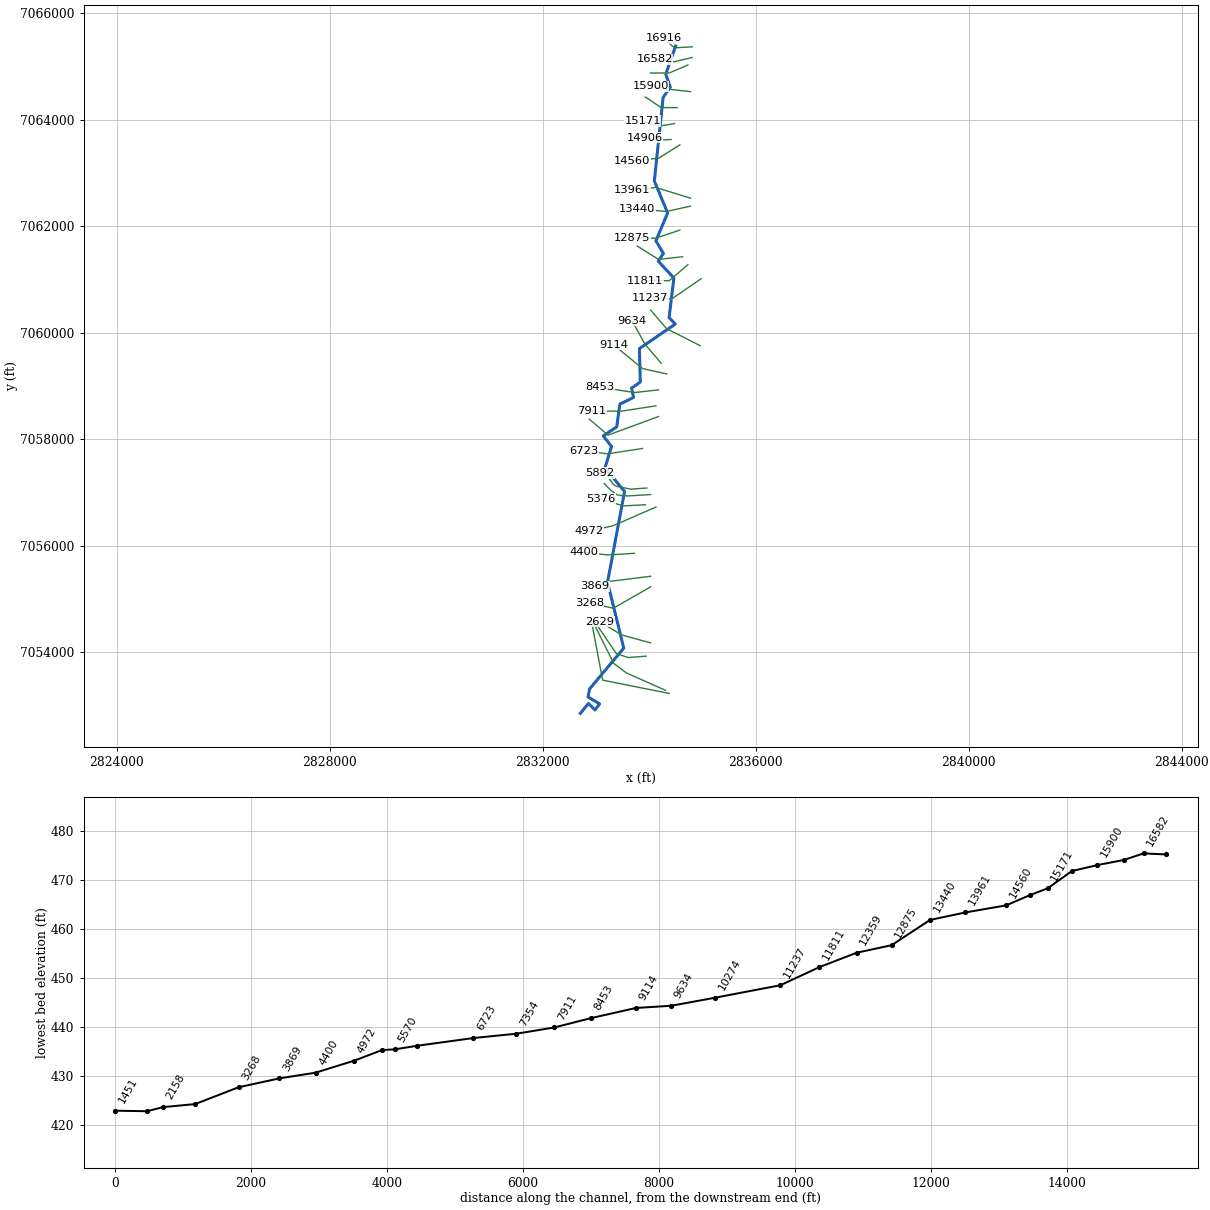
--- BERNARD BRANCH.prj (project) ---

Proj Title=BERNARD BRANCH Base Level Engineering
Current Plan=p01
Default Exp/Contr=0.3,0.1
English Units
Geom File=g01
Flow File=f01
Plan File=p01
BEGIN DESCRIPTION:
BERNARD BRANCH
END DESCRIPTION:

--- BERNARD BRANCH.p01 (plan) ---

Plan Title=Multiple Run
Short Identifier=Multiple
Geom File=g01
Flow File=f01
Subcritical Flow
K Sum by GR= 0
Std Step Tol= 0.01
Critical Tol= 0.01
Num of Std Step Trials= 20
Max Error Tol= 0.3
Flow Tol Ratio= 0.001
Split Flow NTrial= 30
Split Flow Tol= 0.02
Split Flow Ratio= 0.02
Log Output Level= 0
Friction Slope Method= 1
Unsteady Friction Slope Method= 2
Unsteady Bridges Friction Slope Method= 1
Parabolic Critical Depth
Global Vel Dist=  1 , 1 , 1
Global Log Level= 0
CheckData=True
Encroach Param= -1, 0, 0, 0
BEGIN DESCRIPTION:
Multiple Run
END DESCRIPTION:

--- BERNARD BRANCH.f01 (steady flow) ---

Flow Title=Multiple
Number of Profiles=7
Profile Names=10-year,25-year,50-year,1pct_min,100-year,1pct_plu,500-year
River Rch & RM= BERNARD BRANCH,Reach-1,16916
     750    1006    1214     727    1450    2893    2062
River Rch & RM= BERNARD BRANCH,Reach-1,16582
     914    1238    1502     903    1802    3595    2587
River Rch & RM= BERNARD BRANCH,Reach-1,10274
    1551    2160    2670    1633    3257    6499    4844
River Rch & RM= BERNARD BRANCH,Reach-1,3869
    1600    2232    2762    1690    3372    6729    5026
River Rch & RM= BERNARD BRANCH,Reach-1,1920
    1771    2480    3079    1889    3770    7522    5655
Boundary for River Rch & Prof#=BERNARD BRANCH,Reach-1,1
Up Type=0
Dn Type=3
Dn Slope=0.005
Boundary for River Rch & Prof#=BERNARD BRANCH,Reach-1,2
Up Type=0
Dn Type=3
Dn Slope=0.005
Boundary for River Rch & Prof#=BERNARD BRANCH,Reach-1,3
Up Type=0
Dn Type=3
Dn Slope=0.005
Boundary for River Rch & Prof#=BERNARD BRANCH,Reach-1,4
Up Type=0
Dn Type=3
Dn Slope=0.005
Boundary for River Rch & Prof#=BERNARD BRANCH,Reach-1,5
Up Type=0
Dn Type=3
Dn Slope=0.005
Boundary for River Rch & Prof#=BERNARD BRANCH,Reach-1,6
Up Type=0
Dn Type=3
Dn Slope=0.005
Boundary for River Rch & Prof#=BERNARD BRANCH,Reach-1,7
Up Type=0
Dn Type=3
Dn Slope=0.005

--- BERNARD BRANCH.g01 (geometry) ---

Geom Title=Existing Conditions

River Reach=BERNARD BRANCH,Reach-1
Reach XY= 30
      2834495.59      7065380.71      2834310.01      7064850.57
      2834395.47      7064609.50      2834260.54      7064416.74
      2834095.86      7062848.56      2834345.10      7062246.72
      2834124.96      7061724.19      2834265.74      7061485.81
      2834169.42      7061342.66      2834462.92      7061024.09
      2834372.31      7060281.25      2834489.47      7060160.97
      2833815.59      7059700.71      2833832.11      7059072.14
      2833669.14      7058959.33      2833703.91      7058781.24
      2833448.91      7058657.43      2833388.97      7058229.85
      2833136.73      7058060.87      2833291.42      7057862.71
      2833168.70      7057461.73      2833536.45      7057016.07
      2833216.68      7055313.54      2833521.59      7054076.15
      2832879.45      7053309.32      2832851.14      7053159.04
      2833068.74      7053029.20      2832981.35      7052914.94
      2832857.92      7053036.86      2832705.59      7052850.71

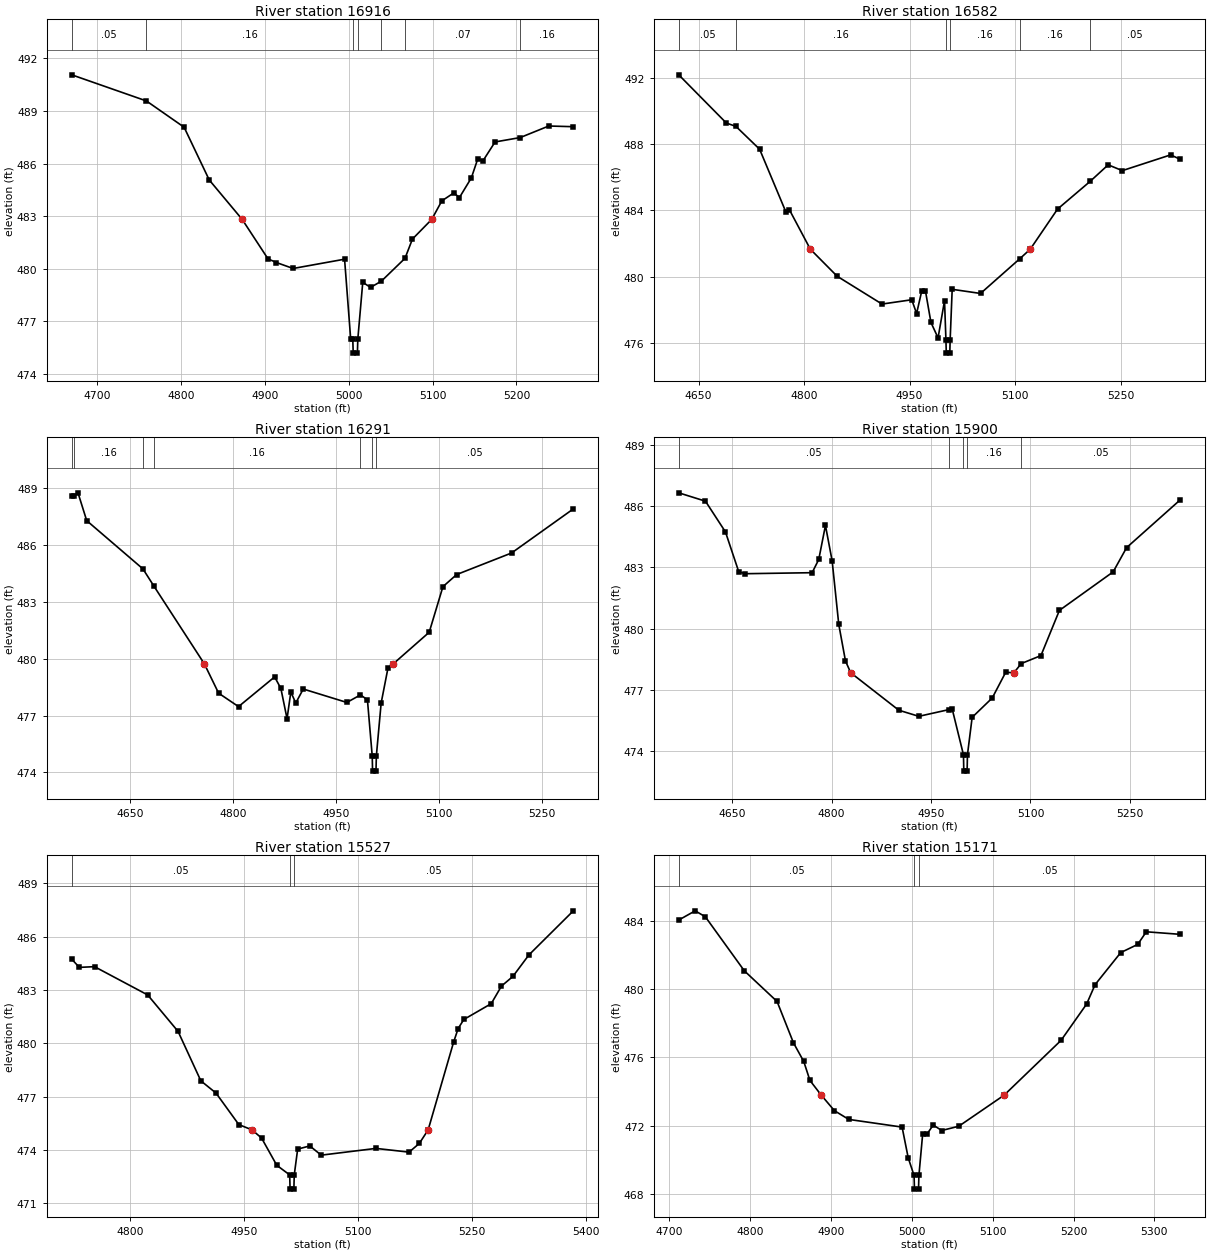
Type RM Length L Ch R = 1,16916,334,334,334
BEGIN DESCRIPTION:
BERNARD BRANCH 28.0
END DESCRIPTION:
XS GIS Cut Line= 4
      2834808.88      7065366.12      2834500.00      7065350.00
      2834435.67      7065377.41      2834274.15      7065525.85
#Sta/Elev= 30
  4669.3  491.06  4758.4  489.57  4803.4  488.07  4833.4  485.06  4872.7  482.81
  4903.5  480.56  4913.5  480.35  4933.5  480.01  4994.9  480.54  5002.2  475.98
  5004.7  475.98  5005.2  475.18  5010.2  475.18  5010.7  475.98  5016.6  479.22
  5025.9  478.93  5038.9  479.29  5067.0  480.59  5075.9  481.69  5098.9  482.81
  5111.0  483.87  5125.2  484.32  5132.0  484.06  5146.2  485.18  5153.6  486.23
  5160.3  486.17  5174.5  487.23  5204.5  487.48  5238.6  488.14  5267.9  488.10
#Mann=7,-1,0
  4669.3    0.05       0  4758.4    0.16       0  5004.7    0.07       0
  5010.7    0.16       0  5038.9    0.12       0  5067.0    0.07       0
  5204.5    0.16       0
Bank Sta=4872.7,5098.9
Exp/Cntr=0.3,0.1

Type RM Length L Ch R = 1,16582,291,291,291
BEGIN DESCRIPTION:
Mapping XS 4aa08fb2
END DESCRIPTION:
XS GIS Cut Line= 3
      2834804.11      7065166.03      2834465.62      7065085.74
      2834103.16      7065131.32
#Sta/Elev= 30
  4621.8  492.18  4689.5  489.27  4703.1  489.07  4736.8  487.69  4773.9  483.93
  4779.0  484.05  4808.9  481.66  4847.0  480.03  4910.8  478.35  4953.1  478.61
  4960.0  477.78  4967.4  479.16  4972.5  479.16  4980.4  477.24  4990.5  476.31
  4999.7  478.55  5001.7  476.19  5002.2  475.39  5007.2  475.39  5007.7  476.19
  5010.6  479.24  5050.9  478.99  5106.6  481.08  5121.6  481.66  5160.4  484.08
  5206.7  485.75  5232.4  486.75  5252.5  486.40  5321.2  487.35  5335.0  487.08
#Mann=6,-1,0
  4621.8    0.05       0  4703.1    0.16       0  5001.7    0.07       0
  5007.7    0.16       0  5106.6    0.16       0  5206.7    0.05       0
Bank Sta=4808.9,5121.6
Exp/Cntr=0.3,0.1

Type RM Length L Ch R = 1,16291,391,391,391
BEGIN DESCRIPTION:
BERNARD BRANCH 27.0
END DESCRIPTION:
XS GIS Cut Line= 3
      2834725.03      7065025.01      2834375.00      7064875.00
      2834025.02      7064875.00
#Sta/Elev= 30
  4565.1  488.59  4568.9  488.62  4574.2  488.77  4586.9  487.30  4668.8  484.75
  4684.8  483.84  4758.3  479.73  4779.1  478.18  4808.1  477.47  4860.7  479.04
  4869.8  478.43  4878.8  476.83  4884.3  478.24  4891.5  477.66  4902.4  478.40
  4965.9  477.69  4985.8  478.09  4995.9  477.83  5002.9  474.86  5003.4  474.06
  5008.4  474.06  5008.9  474.86  5015.9  477.66  5025.9  479.52  5033.5  479.73
  5085.9  481.40  5105.9  483.81  5125.9  484.45  5205.9  485.59  5295.9  487.92
#Mann=7,-1,0
  4565.1    0.05       0  4568.9    0.16       0  4668.8    0.12       0
  4684.8    0.16       0  4985.8    0.05       0  5002.9    0.03       0
  5008.9    0.05       0
Bank Sta=4758.3,5033.5
Exp/Cntr=0.3,0.1

Type RM Length L Ch R = 1,15900,373,373,373
BEGIN DESCRIPTION:
BERNARD BRANCH 26.0
END DESCRIPTION:
XS GIS Cut Line= 3
      2834775.05      7064524.99      2834325.00      7064575.00
      2834024.95      7064625.01
#Sta/Elev= 30
  4569.2  486.66  4609.5  486.25  4639.7  484.74  4659.8  482.78  4669.9  482.69
  4770.5  482.74  4780.5  483.39  4790.6  485.06  4800.7  483.32  4810.7  480.20
  4820.8  478.41  4828.7  477.83  4901.3  475.99  4931.5  475.69  4977.0  476.02
  4981.8  476.06  4998.9  473.80  4999.4  473.00  5004.4  473.00  5004.9  473.80
  5012.0  475.64  5042.3  476.59  5062.6  477.85  5075.1  477.83  5086.1  478.28
  5115.8  478.67  5143.7  480.89  5224.8  482.78  5245.1  483.97  5326.2  486.32
#Mann=5,-1,0
  4569.2    0.05       0  4977.0    0.16       0  4998.9    0.07       0
  5004.9    0.16       0  5086.1    0.05       0
Bank Sta=4828.7,5075.1
Exp/Cntr=0.3,0.1

Type RM Length L Ch R = 1,15527,356,356,356
BEGIN DESCRIPTION:
BERNARD BRANCH 25.0
END DESCRIPTION:
XS GIS Cut Line= 3
      2834524.99      7064225.00      2834225.00      7064225.00
      2833925.04      7064424.97
#Sta/Elev= 30
  4723.2  484.73  4733.2  484.27  4753.2  484.31  4823.2  482.72  4863.2  480.67
  4893.2  477.89  4913.2  477.20  4943.2  475.43  4960.7  475.13  4973.2  474.67
  4993.2  473.14  5010.2  472.60  5010.7  471.80  5015.7  471.80  5016.2  472.60
  5020.7  474.05  5036.7  474.23  5051.7  473.71  5123.8  474.09  5167.4  473.88
  5180.9  474.37  5192.5  475.13  5226.0  480.06  5232.0  480.83  5239.5  481.34
  5275.6  482.23  5289.1  483.22  5304.1  483.76  5325.2  484.97  5383.7  487.45
#Mann=3,-1,0
  4723.2    0.05       0  5010.2    0.03       0  5016.2    0.05       0
Bank Sta=4960.7,5192.5
Exp/Cntr=0.3,0.1

Type RM Length L Ch R = 1,15171,265,265,265
BEGIN DESCRIPTION:
BERNARD BRANCH 24.0
END DESCRIPTION:
XS GIS Cut Line= 3
      2834474.98      7063925.00      2834175.00      7063875.00
      2833875.04      7063974.99
#Sta/Elev= 30
  4711.8  484.06  4732.1  484.60  4744.7  484.25  4792.9  481.08  4833.4  479.28
  4853.7  476.85  4866.4  475.76  4874.0  474.65  4888.1  473.78  4904.4  472.87
  4922.1  472.36  4988.0  471.91  4995.6  470.10  5002.8  469.07  5003.3  468.27
  5008.3  468.27  5008.8  469.07  5013.4  471.48  5018.5  471.48  5026.5  472.03
  5037.0  471.71  5058.1  471.96  5114.1  473.78  5184.6  477.00  5216.2  479.13
  5226.7  480.27  5258.4  482.15  5279.4  482.63  5290.0  483.37  5332.1  483.22
#Mann=3,-1,0
  4711.8    0.05       0  5002.8    0.03       0  5008.8    0.05       0
Bank Sta=4888.1,5114.1
Exp/Cntr=0.3,0.1

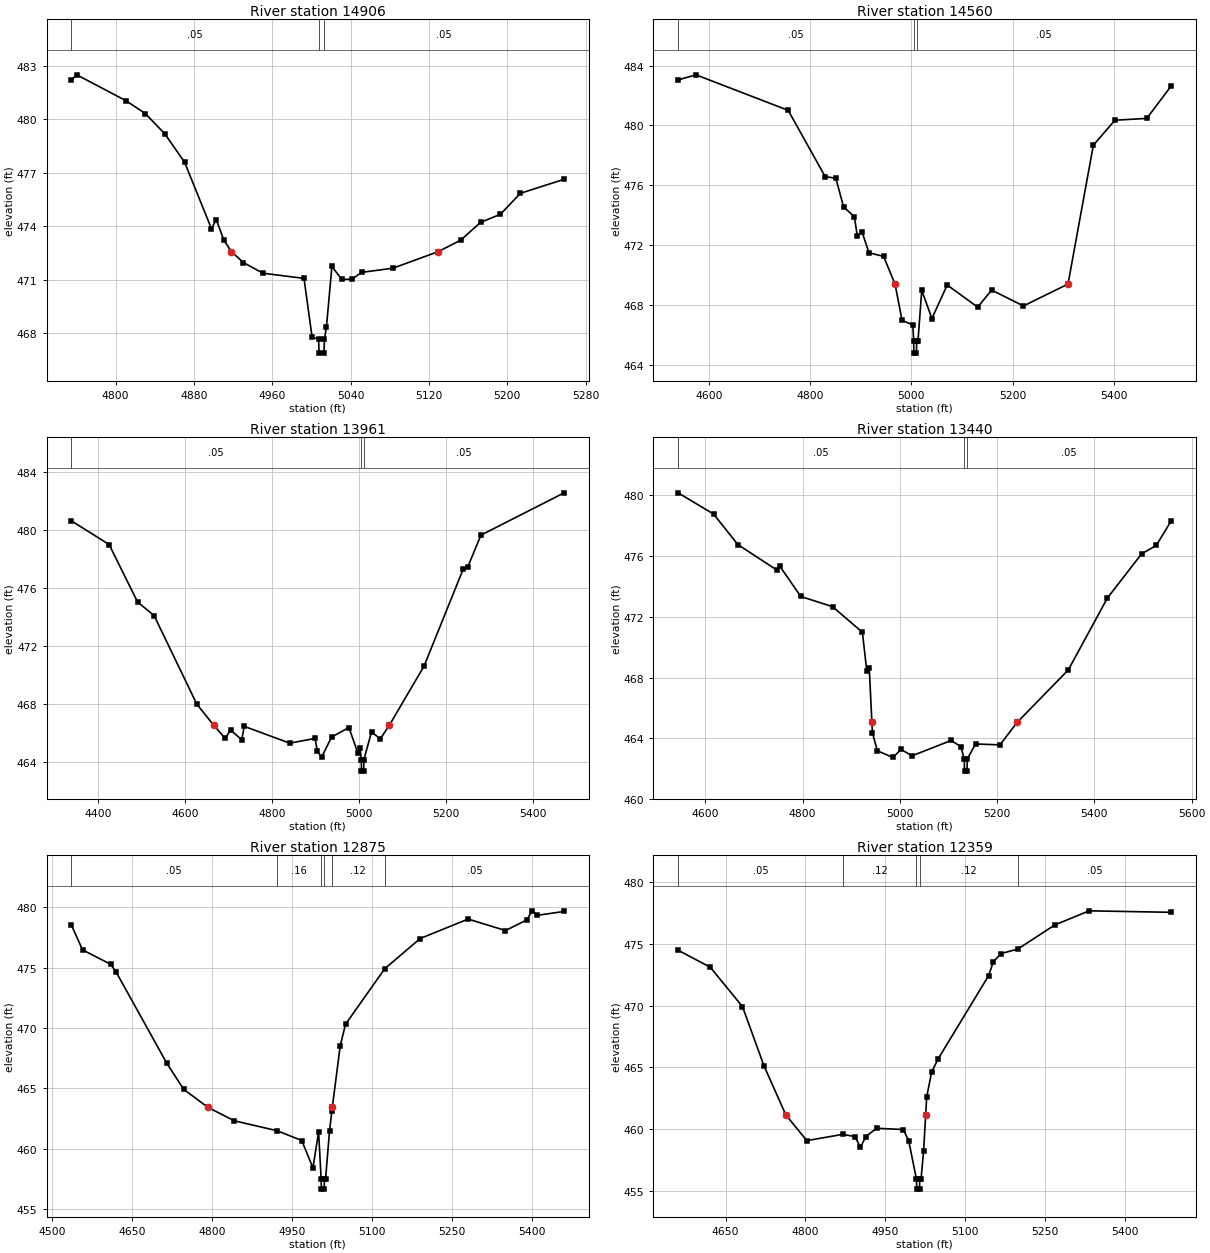
Type RM Length L Ch R = 1,14906,346,346,346
BEGIN DESCRIPTION:
Mapping XS 697a7ae0
END DESCRIPTION:
XS GIS Cut Line= 3
      2834410.61      7063626.46      2834176.27      7063616.04
      2833910.69      7063657.70
#Sta/Elev= 30
  4754.7  482.23  4760.3  482.51  4810.4  481.06  4830.4  480.33  4850.4  479.18
  4870.4  477.60  4897.8  473.87  4902.8  474.37  4910.5  473.23  4918.3  472.57
  4930.5  471.96  4950.5  471.36  4992.4  471.07  5000.7  467.75  5007.3  467.67
  5007.8  466.87  5012.8  466.87  5013.3  467.67  5015.3  468.33  5020.9  471.74
  5031.0  471.01  5041.2  471.02  5051.3  471.41  5083.0  471.64  5129.4  472.57
  5152.5  473.22  5172.8  474.22  5193.0  474.67  5213.4  475.85  5258.1  476.64
#Mann=3,-1,0
  4754.7    0.05       0  5007.3    0.03       0  5013.3    0.05       0
Bank Sta=4918.3,5129.4
Exp/Cntr=0.3,0.1

Type RM Length L Ch R = 1,14560,599,599,599
BEGIN DESCRIPTION:
BERNARD BRANCH 23.0
END DESCRIPTION:
XS GIS Cut Line= 3
      2834574.99      7063525.00      2834175.00      7063275.00
      2833674.99      7063225.00
#Sta/Elev= 30
  4538.8  483.04  4574.2  483.38  4756.4  481.01  4829.5  476.59  4850.7  476.47
  4866.0  474.56  4887.3  473.91  4893.2  472.60  4902.6  472.88  4916.2  471.50
  4945.0  471.26  4967.7  469.41  4981.6  466.98  5002.8  466.69  5004.5  465.60
  5005.0  464.80  5010.0  464.80  5010.5  465.60  5013.0  465.60  5020.5  468.99
  5040.6  467.11  5070.8  469.35  5131.1  467.87  5158.7  469.01  5221.5  467.95
  5309.6  469.41  5359.7  478.68  5402.4  480.35  5465.3  480.47  5513.0  482.61
#Mann=3,-1,0
  4538.8    0.05       0  5004.5    0.03       0  5010.5    0.05       0
Bank Sta=4967.7,5309.6
Exp/Cntr=0.3,0.1

Type RM Length L Ch R = 1,13961,521,521,521
BEGIN DESCRIPTION:
BERNARD BRANCH 22.0
END DESCRIPTION:
XS GIS Cut Line= 3
      2834775.01      7062525.00      2834125.00      7062725.00
      2833674.95      7062674.99
#Sta/Elev= 30
  4339.0  480.64  4426.0  479.00  4491.4  475.03  4529.3  474.10  4627.4  467.99
  4666.3  466.53  4692.8  465.62  4705.2  466.20  4730.7  465.52  4736.6  466.45
  4841.2  465.29  4899.4  465.62  4904.6  464.74  4914.5  464.33  4937.3  465.71
  4977.2  466.37  4997.5  464.63  5002.7  464.99  5005.6  464.16  5006.1  463.36
  5011.1  463.36  5011.6  464.16  5029.1  466.06  5049.3  465.59  5070.2  466.53
  5149.9  470.61  5240.4  477.34  5250.5  477.46  5280.7  479.65  5471.9  482.57
#Mann=3,-1,0
  4339.0    0.05       0  5005.6    0.03       0  5011.6    0.05       0
Bank Sta=4666.3,5070.2
Exp/Cntr=0.3,0.1

Type RM Length L Ch R = 1,13440,565,565,565
BEGIN DESCRIPTION:
BERNARD BRANCH 21.0
END DESCRIPTION:
XS GIS Cut Line= 3
      2834774.97      7062374.99      2834325.00      7062275.00
      2833775.01      7062325.00
#Sta/Elev= 30
  4544.1  480.17  4617.1  478.77  4667.0  476.76  4747.7  475.07  4752.8  475.36
  4796.3  473.34  4861.6  472.67  4923.1  470.98  4932.1  468.41  4937.2  468.60
  4942.6  465.04  4943.6  464.37  4953.8  463.17  4985.8  462.73  5002.5  463.26
  5025.1  462.84  5105.5  463.85  5125.5  463.44  5132.5  462.63  5133.0  461.83
  5138.2  461.83  5138.7  462.63  5155.7  463.62  5205.9  463.56  5241.1  465.04
  5346.4  468.50  5426.8  473.24  5497.1  476.15  5527.2  476.70  5557.3  478.29
#Mann=3,-1,0
  4544.1    0.05       0  5132.5    0.03       0  5138.7    0.05       0
Bank Sta=4942.6,5241.1
Exp/Cntr=0.3,0.1

Type RM Length L Ch R = 1,12875,516,516,516
BEGIN DESCRIPTION:
BERNARD BRANCH 20.0
END DESCRIPTION:
XS GIS Cut Line= 3
      2834574.99      7061925.00      2834125.00      7061775.00
      2833675.03      7061775.00
#Sta/Elev= 30
  4536.0  478.53  4557.1  476.46  4609.8  475.27  4620.3  474.61  4715.2  467.08
  4746.8  464.93  4792.6  463.43  4841.7  462.33  4921.8  461.51  4968.2  460.70
  4989.2  458.44  4999.8  461.43  5004.6  457.48  5005.1  456.68  5010.3  456.68
  5010.8  457.48  5012.8  457.48  5020.3  461.49  5024.8  463.17  5025.5  463.43
  5040.3  468.52  5050.3  470.31  5123.8  474.90  5190.3  477.40  5280.3  479.01
  5350.3  478.06  5390.3  478.94  5400.3  479.69  5410.3  479.32  5460.3  479.64
#Mann=6,-1,0
  4536.0    0.05       0  4921.8    0.16       0  5004.6    0.07       0
  5010.8    0.16       0  5024.8    0.12       0  5123.8    0.05       0
Bank Sta=4792.6,5025.5
Exp/Cntr=0.3,0.1

Type RM Length L Ch R = 1,12359,548,548,548
BEGIN DESCRIPTION:
BERNARD BRANCH 19.0
END DESCRIPTION:
XS GIS Cut Line= 3
      2834625.04      7061425.00      2834175.00      7061375.00
      2833775.01      7061625.00
#Sta/Elev= 30
  4561.0  474.50  4621.4  473.12  4681.8  469.93  4722.0  465.15  4763.2  461.15
  4802.5  459.07  4870.2  459.58  4893.1  459.39  4903.1  458.52  4913.2  459.40
  4933.3  460.07  4983.6  459.97  4993.7  459.05  5008.2  455.94  5008.7  455.14
  5013.9  455.14  5014.4  455.94  5016.8  455.94  5021.5  458.20  5025.5  461.15
  5027.4  462.61  5036.8  464.65  5049.2  465.72  5143.5  472.43  5152.4  473.57
  5167.1  474.23  5198.3  474.59  5267.9  476.55  5332.2  477.69  5485.5  477.57
#Mann=5,-1,0
  4561.0    0.05       0  4870.2    0.12       0  5008.2    0.07       0
  5014.4    0.12       0  5198.3    0.05       0
Bank Sta=4763.2,5025.5
Exp/Cntr=0.3,0.1

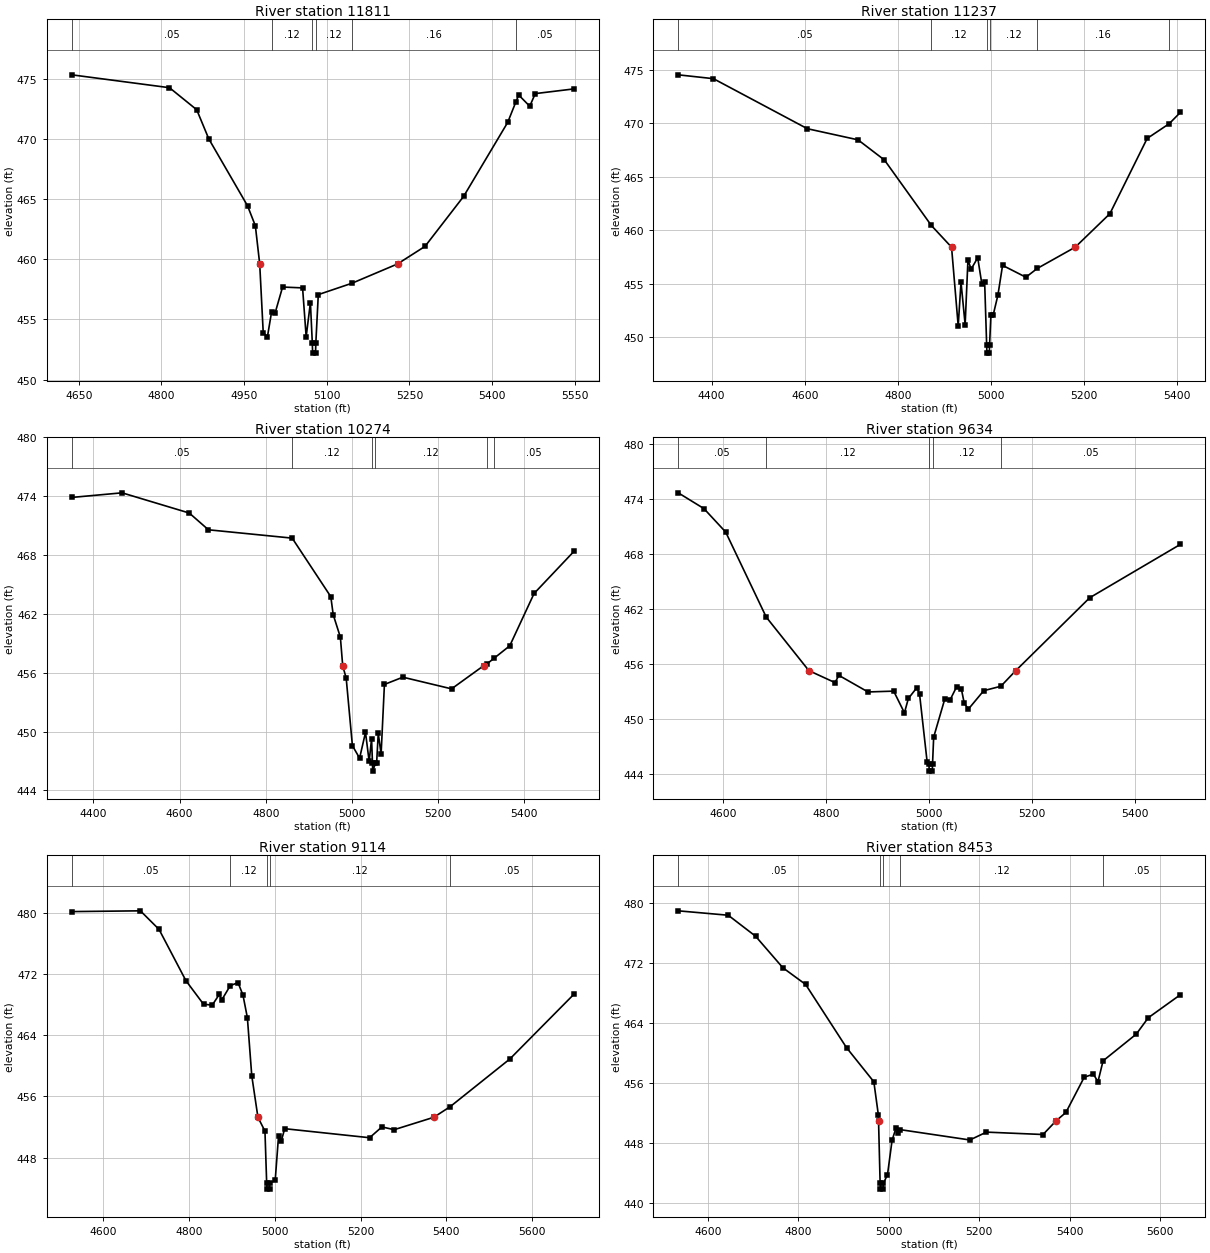
Type RM Length L Ch R = 1,11811,574,574,574
BEGIN DESCRIPTION:
BERNARD BRANCH 18.0
END DESCRIPTION:
XS GIS Cut Line= 3
      2834725.03      7061275.02      2834375.00      7060975.00
      2833925.01      7060975.00
#Sta/Elev= 30
  4637.4  475.32  4814.7  474.25  4864.1  472.42  4886.0  470.00  4956.3  464.44
  4970.5  462.78  4978.4  459.61  4984.8  453.89  4992.5  453.58  4999.9  455.61
  5006.2  455.51  5019.9  457.69  5056.2  457.62  5062.7  453.56  5070.4  456.40
  5073.9  453.00  5074.4  452.20  5079.7  452.20  5080.2  453.00  5084.7  457.06
  5146.0  458.01  5228.5  459.61  5278.4  461.07  5348.4  465.22  5428.4  471.37
  5443.2  473.07  5448.4  473.64  5468.4  472.71  5478.4  473.76  5548.4  474.15
#Mann=6,-1,0
  4637.4    0.05       0  4999.9    0.12       0  5073.9    0.07       0
  5080.2    0.12       0  5146.0    0.16       0  5443.2    0.05       0
Bank Sta=4978.4,5228.5
Exp/Cntr=0.3,0.1

Type RM Length L Ch R = 1,11237,963,963,963
BEGIN DESCRIPTION:
BERNARD BRANCH 17.0
END DESCRIPTION:
XS GIS Cut Line= 3
      2834973.72      7061011.80      2834419.89      7060631.54
      2834013.99      7060656.90
#Sta/Elev= 30
  4328.2  474.55  4403.8  474.19  4605.6  469.51  4714.4  468.47  4771.2  466.58
  4871.9  460.46  4915.3  458.43  4929.6  451.06  4935.6  455.16  4944.5  451.18
  4950.5  457.22  4957.4  456.38  4971.5  457.44  4980.3  455.01  4986.4  455.18
  4990.7  449.32  4991.2  448.52  4996.5  448.52  4997.0  449.32  4999.9  452.13
  5005.0  452.13  5014.9  453.95  5024.9  456.73  5075.0  455.62  5099.4  456.44
  5181.0  458.43  5255.4  461.56  5335.5  468.60  5382.9  469.98  5406.7  471.03
#Mann=6,-1,0
  4328.2    0.05       0  4871.9    0.12       0  4990.7    0.07       0
  4997.0    0.12       0  5099.4    0.16       0  5382.9    0.05       0
Bank Sta=4915.3,5181
Exp/Cntr=0.3,0.1

Type RM Length L Ch R = 1,10274,640,640,640
BEGIN DESCRIPTION:
BERNARD BRANCH 16.0
END DESCRIPTION:
XS GIS Cut Line= 3
      2834952.83      7059756.59      2834325.00      7060075.00
      2834025.02      7060424.97
#Sta/Elev= 30
  4349.8  473.88  4466.5  474.35  4622.4  472.29  4666.9  470.58  4861.2  469.73
  4950.8  463.76  4956.4  461.92  4973.0  459.63  4978.4  456.72  4986.5  455.45
  5000.9  448.57  5017.6  447.29  5031.3  449.92  5039.8  446.96  5045.4  449.28
  5047.5  446.77  5048.0  445.97  5054.4  446.77  5057.1  446.77  5060.9  449.83
  5067.5  447.70  5075.2  454.81  5118.0  455.55  5231.0  454.36  5305.4  456.72
  5312.7  456.89  5329.6  457.48  5366.0  458.75  5422.5  464.09  5514.7  468.37
#Mann=6,-1,0
  4349.8    0.05       0  4861.2    0.12       0  5047.5    0.07       0
  5054.4    0.12       0  5312.7    0.16       0  5329.6    0.05       0
Bank Sta=4978.4,5305.4
Exp/Cntr=0.3,0.1

Type RM Length L Ch R = 1,9634,520,520,520
BEGIN DESCRIPTION:
BERNARD BRANCH 15.0
END DESCRIPTION:
XS GIS Cut Line= 3
      2834224.99      7059425.01      2833925.00      7059775.00
      2833675.02      7060224.96
#Sta/Elev= 30
  4512.3  474.71  4562.2  472.99  4604.5  470.43  4683.3  461.15  4766.1  455.31
  4816.9  454.00  4824.5  454.79  4881.1  452.98  4931.0  453.07  4951.9  450.70
  4959.5  452.27  4976.1  453.45  4981.3  452.73  4996.1  445.29  4999.5  445.14
  5000.0  444.34  5006.0  444.34  5006.5  445.14  5008.7  448.05  5030.5  452.25
  5040.8  452.14  5053.3  453.54  5062.5  453.30  5068.2  451.73  5076.2  451.11
  5106.0  453.12  5139.2  453.60  5168.3  455.31  5311.9  463.26  5488.0  469.08
#Mann=5,-1,0
  4512.3    0.05       0  4683.3    0.12       0  4999.5    0.07       0
  5006.5    0.12       0  5139.2    0.05       0
Bank Sta=4766.1,5168.3
Exp/Cntr=0.3,0.1

Type RM Length L Ch R = 1,9114,661,661,661
BEGIN DESCRIPTION:
BERNARD BRANCH 14.0
END DESCRIPTION:
XS GIS Cut Line= 3
      2834325.03      7059224.99      2833875.00      7059325.00
      2833325.04      7059774.97
#Sta/Elev= 30
  4526.0  480.12  4686.1  480.22  4729.6  477.80  4792.4  471.10  4833.4  468.03
  4853.8  467.91  4870.5  469.33  4875.6  468.55  4895.9  470.46  4914.0  470.84
  4925.5  469.22  4935.8  466.26  4946.0  458.70  4960.4  453.27  4976.8  451.46
  4980.8  444.69  4981.3  443.89  4987.6  443.89  4988.2  444.69  5000.7  445.02
  5008.5  450.83  5015.0  450.20  5022.9  451.78  5221.0  450.60  5249.7  452.01
  5278.4  451.65  5370.9  453.27  5408.9  454.65  5548.3  460.88  5697.6  469.32
#Mann=5,-1,0
  4526.0    0.05       0  4895.9    0.12       0  4980.8    0.07       0
  4988.2    0.12       0  5408.9    0.05       0
Bank Sta=4960.4,5370.9
Exp/Cntr=0.3,0.1

Type RM Length L Ch R = 1,8453,542,542,542
BEGIN DESCRIPTION:
BERNARD BRANCH 13.0
END DESCRIPTION:
XS GIS Cut Line= 3
      2834174.96      7058925.00      2833725.00      7058875.00
      2833074.98      7058975.00
#Sta/Elev= 30
  4534.5  479.02  4645.1  478.43  4705.5  475.63  4765.9  471.41  4816.2  469.18
  4906.7  460.73  4967.1  456.17  4977.2  451.70  4977.5  450.94  4981.0  442.62
  4981.6  441.82  4987.9  441.82  4988.4  442.62  4997.3  443.75  5007.5  448.37
  5016.3  450.01  5021.4  449.38  5025.6  449.77  5179.5  448.39  5216.1  449.44
  5341.3  449.12  5370.0  450.94  5391.9  452.07  5432.4  456.78  5452.6  457.19
  5462.8  456.18  5474.1  458.97  5547.5  462.54  5574.1  464.73  5644.9  467.80
#Mann=5,-1,0
  4534.5    0.05       0  4981.0    0.03       0  4988.4    0.05       0
  5025.6    0.12       0  5474.1    0.05       0
Bank Sta=4977.5,5370
Exp/Cntr=0.3,0.1

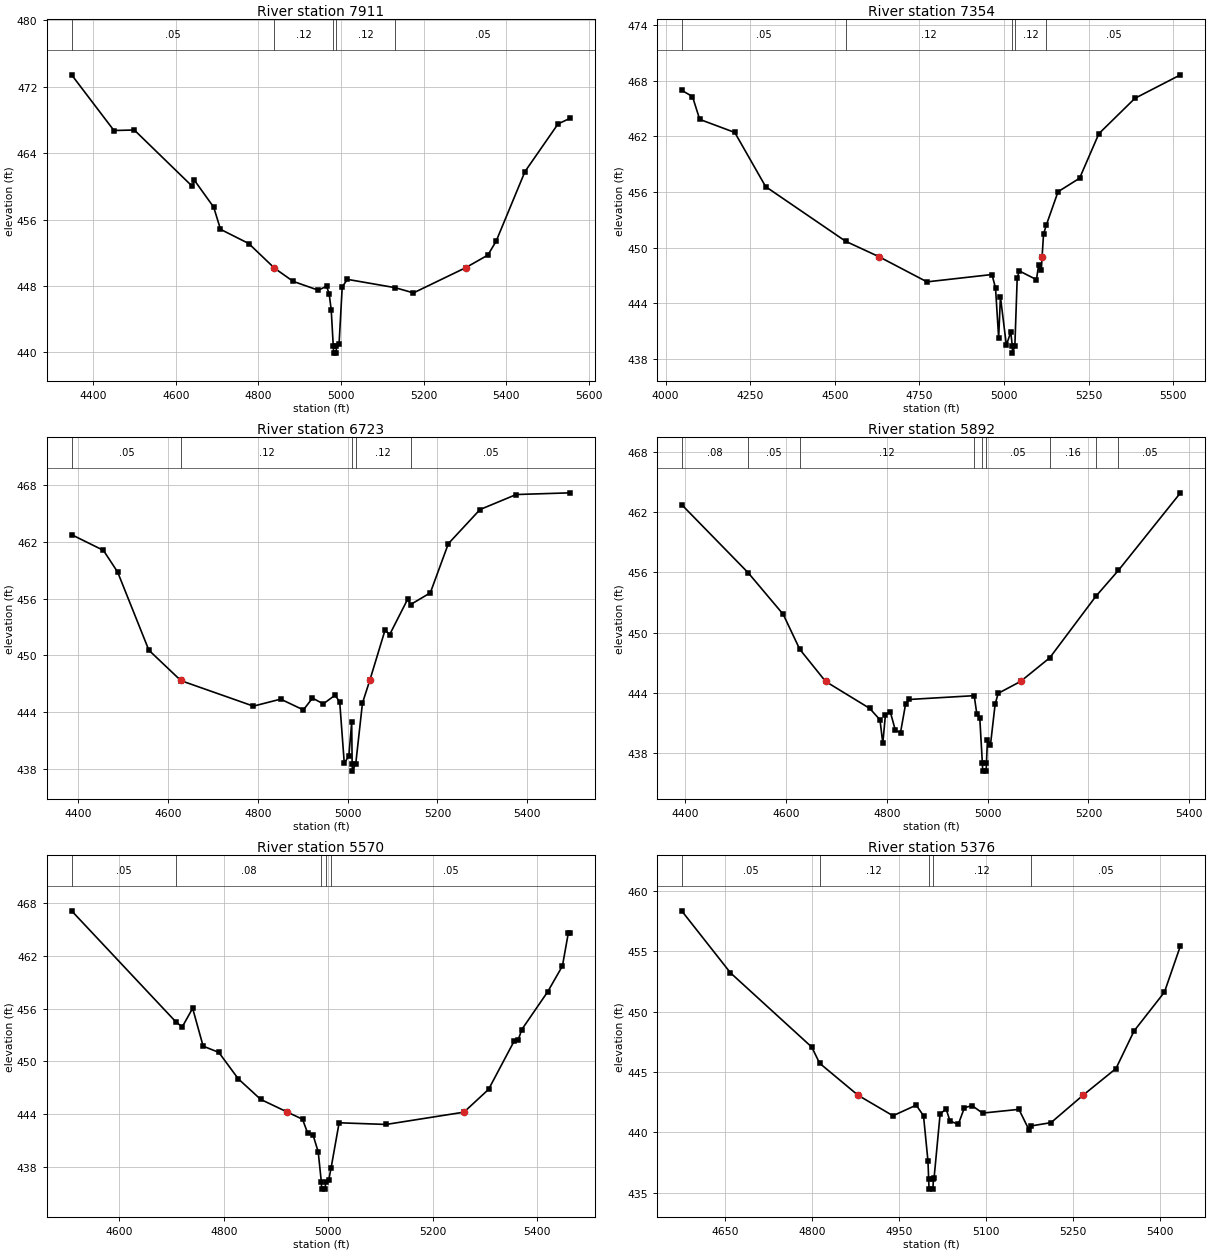
Type RM Length L Ch R = 1,7911,557,557,557
BEGIN DESCRIPTION:
BERNARD BRANCH 12.0
END DESCRIPTION:
XS GIS Cut Line= 3
      2834125.03      7058625.01      2833475.00      7058525.00
      2832924.98      7058525.00
#Sta/Elev= 30
  4347.8  473.45  4450.3  466.74  4499.6  466.80  4640.0  460.01  4645.0  460.75
  4691.8  457.50  4708.3  454.83  4776.6  453.12  4838.0  450.20  4838.2  450.18
  4884.1  448.56  4944.8  447.50  4965.0  447.96  4971.3  447.09  4976.4  445.11
  4981.4  440.71  4982.0  439.91  4988.4  439.91  4989.0  440.71  4995.4  441.03
  5003.0  447.89  5015.5  448.80  5131.0  447.80  5175.5  447.17  5301.7  450.20
  5355.5  451.72  5375.5  453.38  5445.5  461.79  5525.5  467.53  5555.5  468.23
#Mann=5,-1,0
  4347.8    0.05       0  4838.2    0.12       0  4981.4    0.07       0
  4989.0    0.12       0  5131.0    0.05       0
Bank Sta=4838,5301.7
Exp/Cntr=0.3,0.1

Type RM Length L Ch R = 1,7354,631,631,631
BEGIN DESCRIPTION:
BERNARD BRANCH 11.0
END DESCRIPTION:
XS GIS Cut Line= 3
      2834174.96      7058424.98      2833225.00      7058075.00
      2832874.96      7058375.03
#Sta/Elev= 30
  4047.6  466.96  4079.5  466.29  4100.8  463.83  4204.4  462.42  4295.7  456.58
  4532.1  450.69  4629.9  449.04  4772.2  446.32  4964.1  447.11  4974.7  445.66
  4983.9  440.28  4989.2  444.70  5006.7  439.50  5019.6  440.90  5024.2  439.44
  5024.8  438.64  5031.8  439.44  5038.7  446.72  5044.8  447.50  5095.6  446.56
  5102.2  448.19  5109.9  447.64  5112.3  449.04  5116.5  451.46  5124.7  452.44
  5159.3  456.03  5223.0  457.49  5280.0  462.29  5386.5  466.10  5521.0  468.63
#Mann=5,-1,0
  4047.6    0.05       0  4532.1    0.12       0  5024.2    0.07       0
  5031.8    0.12       0  5124.7    0.05       0
Bank Sta=4629.9,5112.3
Exp/Cntr=0.3,0.1

Type RM Length L Ch R = 1,6723,831,831,831
BEGIN DESCRIPTION:
BERNARD BRANCH 10.0
END DESCRIPTION:
XS GIS Cut Line= 3
      2833874.99      7057825.00      2833225.00      7057725.00
      2832775.00      7057775.00
#Sta/Elev= 30
  4385.5  462.79  4456.3  461.13  4487.9  458.84  4557.5  450.56  4628.2  447.37
  4630.0  447.32  4790.2  444.64  4850.9  445.38  4901.5  444.24  4921.7  445.49
  4945.8  444.88  4972.3  445.81  4982.4  445.04  4992.5  438.59  5002.7  439.37
  5009.0  442.92  5010.0  438.56  5010.7  437.76  5018.1  438.56  5033.0  444.97
  5049.3  447.37  5083.4  452.71  5093.4  452.20  5133.7  455.97  5140.0  455.39
  5184.0  456.63  5224.2  461.84  5294.7  465.45  5375.2  467.04  5495.9  467.22
#Mann=5,-1,0
  4385.5    0.05       0  4630.0    0.12       0  5010.0    0.07       0
  5018.1    0.12       0  5140.0    0.05       0
Bank Sta=4628.2,5049.3
Exp/Cntr=0.3,0.1

Type RM Length L Ch R = 1,5892,322,322,322
BEGIN DESCRIPTION:
Mapping XS d4fb3e9b
END DESCRIPTION:
XS GIS Cut Line= 6
      2833956.01      7057082.19      2833656.48      7057061.35
      2833385.65      7057113.44      2833320.55      7057155.10
      2833221.59      7057298.33      2833073.16      7057363.43
#Sta/Elev= 30
  4393.1  462.77  4524.9  455.98  4594.6  451.82  4627.3  448.34  4678.6  445.13
  4766.1  442.44  4786.5  441.30  4792.1  438.94  4797.2  441.76  4806.8  442.12
  4817.0  440.25  4827.2  440.02  4837.4  442.90  4844.2  443.33  4973.4  443.71
  4978.6  441.89  4984.5  441.45  4989.6  436.98  4990.3  436.18  4997.1  436.18
  4997.7  436.98  4999.7  439.33  5005.7  438.81  5014.9  442.85  5020.9  443.94
  5065.4  445.13  5123.3  447.49  5214.5  453.61  5259.6  456.22  5382.6  463.95
#Mann=9,-1,0
  4393.1    0.08       0  4524.9    0.05       0  4627.3    0.12       0
  4973.4    0.05       0  4989.6    0.04       0  4997.7    0.05       0
  5123.3    0.16       0  5214.5    0.08       0  5259.6    0.05       0
Bank Sta=4678.6,5065.4
Exp/Cntr=0.3,0.1

Type RM Length L Ch R = 1,5570,194,194,194
BEGIN DESCRIPTION:
Mapping XS 7567c488
END DESCRIPTION:
XS GIS Cut Line= 6
      2834026.29      7056959.79      2833604.40      7056933.75
      2833500.23      7056936.35      2833396.07      7056954.58
      2833289.30      7057030.10      2833153.90      7057165.50
#Sta/Elev= 30
  4508.5  467.13  4707.7  454.52  4720.2  453.91  4740.2  456.04  4760.3  451.73
  4790.3  451.02  4827.6  448.01  4870.5  445.67  4921.8  444.22  4950.6  443.41
  4960.6  441.80  4970.6  441.64  4980.6  439.70  4986.6  436.26  4987.2  435.46
  4994.0  435.46  4994.7  436.26  5000.6  436.46  5005.1  437.82  5020.6  443.01
  5110.6  442.82  5259.6  444.22  5306.7  446.81  5356.2  452.36  5363.3  452.41
  5370.3  453.62  5419.8  457.91  5448.1  460.85  5459.5  464.64  5463.4  464.64
#Mann=5,-1,0
  4508.5    0.05       0  4707.7    0.08       0  4986.6    0.07       0
  4994.7    0.08       0  5005.1    0.05       0
Bank Sta=4921.8,5259.6
Exp/Cntr=0.3,0.1

Type RM Length L Ch R = 1,5376,404,404,404
BEGIN DESCRIPTION:
Mapping XS 8493dff0
END DESCRIPTION:
XS GIS Cut Line= 3
      2833929.05      7056767.95      2833512.39      7056746.25
      2833088.53      7056876.00
#Sta/Elev= 30
  4574.6  458.36  4658.8  453.22  4799.0  447.07  4812.6  445.73  4878.8  443.08
  4939.1  441.38  4979.2  442.26  4991.8  441.38  4999.5  437.62  5000.7  436.10
  5001.3  435.30  5008.1  435.30  5008.8  436.10  5010.0  436.21  5020.5  441.55
  5030.9  441.93  5037.5  440.94  5051.8  440.67  5062.3  442.04  5075.5  442.22
  5093.7  441.60  5156.4  441.91  5173.8  440.21  5176.7  440.53  5211.8  440.81
  5267.0  443.08  5323.8  445.29  5355.1  448.41  5407.4  451.62  5435.1  455.47
#Mann=5,-1,0
  4574.6    0.05       0  4812.6    0.12       0  5000.7    0.07       0
  5008.8    0.12       0  5176.7    0.05       0
Bank Sta=4878.8,5267
Exp/Cntr=0.3,0.1

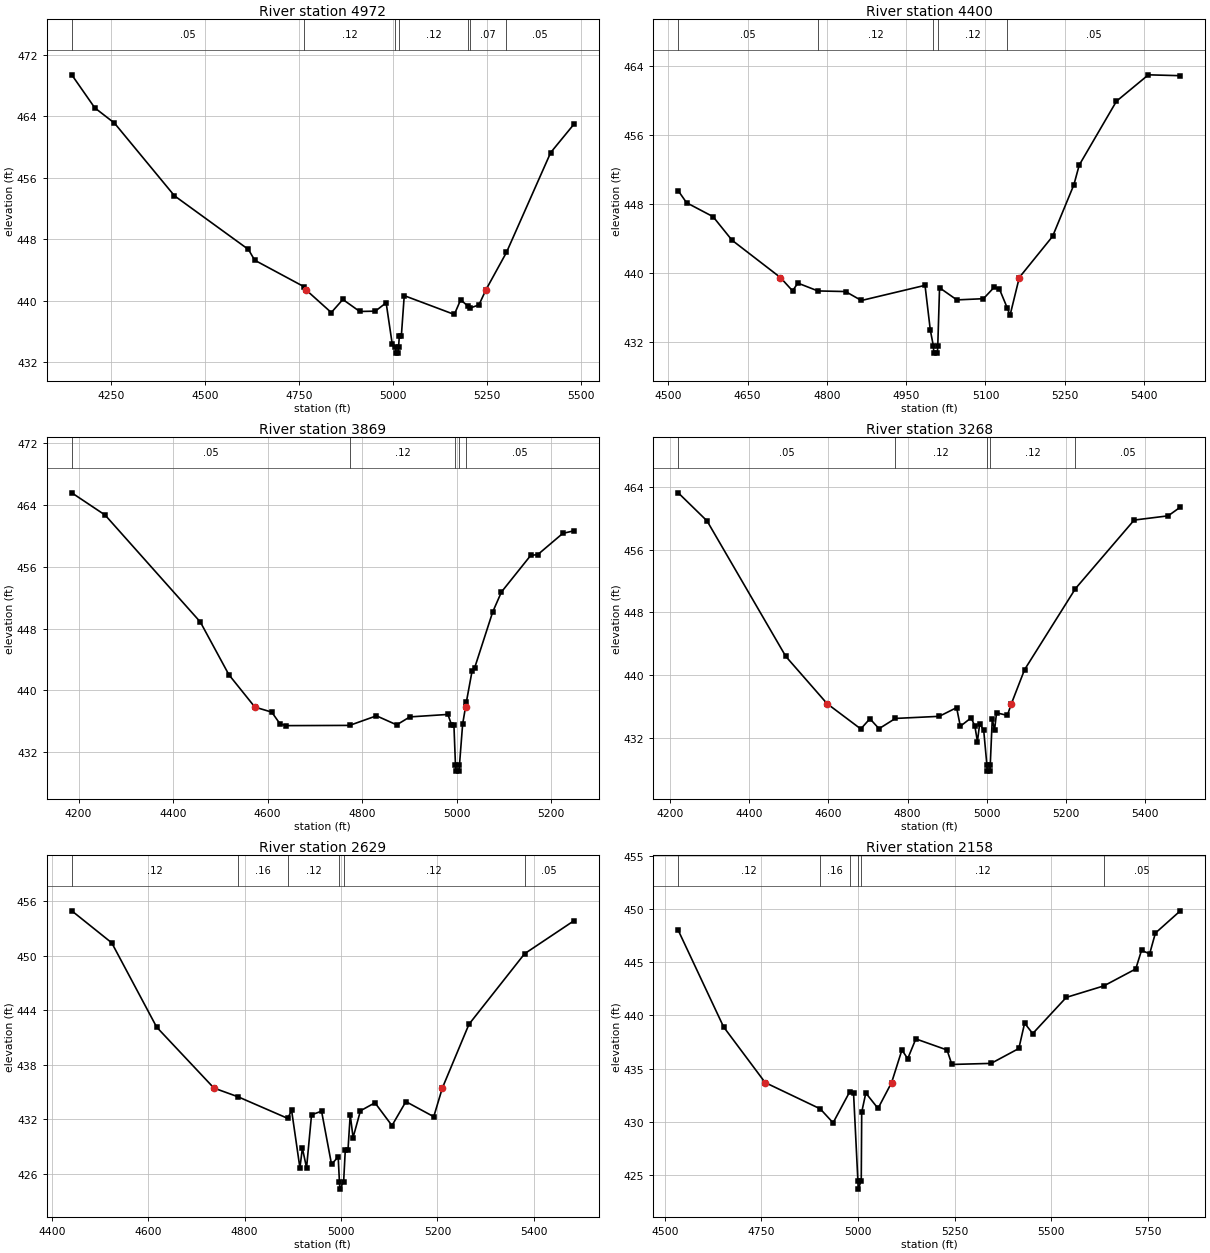
Type RM Length L Ch R = 1,4972,572,572,572
BEGIN DESCRIPTION:
BERNARD BRANCH 7.0
END DESCRIPTION:
XS GIS Cut Line= 3
      2834125.00      7056725.00      2833325.00      7056375.00
      2832874.99      7056275.00
#Sta/Elev= 30
  4146.3  469.37  4207.5  465.07  4259.7  463.09  4419.2  453.63  4615.7  446.65
  4632.4  445.25  4763.9  441.79  4767.9  441.43  4835.9  438.44  4866.7  440.14
  4911.5  438.58  4952.9  438.62  4981.7  439.71  4997.7  434.40  5006.5  433.96
  5007.2  433.16  5014.0  433.16  5014.7  433.96  5016.8  435.39  5022.1  435.39
  5029.8  440.64  5162.9  438.19  5179.6  440.09  5200.4  439.23  5204.8  439.03
  5228.2  439.43  5247.2  441.43  5301.4  446.26  5419.0  459.26  5480.5  462.93
#Mann=7,-1,0
  4146.3    0.05       0  4763.9    0.12       0  5006.5    0.07       0
  5014.7    0.12       0  5200.4    0.05       0  5204.8    0.07       0
  5301.4    0.05       0
Bank Sta=4767.9,5247.2
Exp/Cntr=0.3,0.1

Type RM Length L Ch R = 1,4400,531,531,531
BEGIN DESCRIPTION:
BERNARD BRANCH 6.0
END DESCRIPTION:
XS GIS Cut Line= 3
      2833720.74      7055856.49      2833225.00      7055825.00
      2832775.00      7055875.00
#Sta/Elev= 30
  4519.0  449.55  4534.8  448.16  4584.9  446.54  4620.7  443.81  4712.2  439.48
  4735.2  437.93  4745.2  438.83  4783.1  437.92  4835.4  437.85  4865.4  436.81
  4985.7  438.57  4995.7  433.38  5001.6  431.50  5002.3  430.70  5009.1  430.70
  5009.8  431.50  5013.2  438.29  5045.9  436.88  5096.2  437.02  5116.4  438.34
  5126.4  438.14  5141.0  435.98  5146.5  435.09  5164.0  439.48  5227.0  444.26
  5267.3  450.26  5277.3  452.53  5347.8  459.95  5408.1  463.01  5468.5  462.91
#Mann=5,-1,0
  4519.0    0.05       0  4783.1    0.12       0  5001.6    0.07       0
  5009.8    0.12       0  5141.0    0.05       0
Bank Sta=4712.2,5164
Exp/Cntr=0.3,0.1

Type RM Length L Ch R = 1,3869,601,601,601
BEGIN DESCRIPTION:
BERNARD BRANCH 5.0
END DESCRIPTION:
XS GIS Cut Line= 3
      2834025.03      7055425.00      2833225.00      7055325.00
      2832982.89      7055240.18
#Sta/Elev= 30
  4185.5  465.57  4256.1  462.69  4457.6  448.85  4518.1  442.02  4573.1  437.83
  4608.8  437.18  4626.4  435.65  4639.0  435.43  4773.6  435.46  4830.5  436.70
  4873.3  435.53  4901.1  436.56  4981.7  436.88  4989.2  435.57  4994.4  435.57
  4997.7  430.34  4998.5  429.54  5005.5  429.54  5006.2  430.34  5012.9  435.63
  5019.0  437.83  5020.8  438.49  5033.0  442.54  5038.3  442.91  5076.5  450.14
  5095.0  452.73  5157.0  457.47  5171.9  457.57  5224.9  460.32  5248.3  460.65
#Mann=5,-1,0
  4185.5    0.05       0  4773.6    0.12       0  4997.7    0.07       0
  5006.2    0.12       0  5020.8    0.05       0
Bank Sta=4573.1,5019
Exp/Cntr=0.3,0.1

Type RM Length L Ch R = 1,3268,639,639,639
BEGIN DESCRIPTION:
BERNARD BRANCH 4.0
END DESCRIPTION:
XS GIS Cut Line= 3
      2834025.03      7055225.02      2833325.00      7054825.00
      2832875.03      7054924.99
#Sta/Elev= 30
  4221.1  463.28  4293.8  459.69  4492.5  442.39  4596.8  436.35  4681.8  433.12
  4704.9  434.42  4727.9  433.15  4769.1  434.46  4879.8  434.73  4923.7  435.84
  4933.1  433.46  4960.4  434.54  4969.8  433.47  4976.2  431.51  4982.0  433.81
  4992.1  432.94  5000.1  428.53  5000.8  427.73  5007.8  427.73  5008.6  428.53
  5013.7  434.41  5019.4  432.96  5024.5  435.18  5051.7  434.85  5062.0  436.35
  5095.2  440.69  5223.7  451.05  5371.8  459.80  5457.6  460.34  5488.3  461.45
#Mann=5,-1,0
  4221.1    0.05       0  4769.1    0.12       0  5000.1    0.07       0
  5008.6    0.12       0  5223.7    0.05       0
Bank Sta=4596.8,5062
Exp/Cntr=0.3,0.1

Type RM Length L Ch R = 1,2629,471,471,471
BEGIN DESCRIPTION:
BERNARD BRANCH 3.0
END DESCRIPTION:
XS GIS Cut Line= 3
      2834025.02      7054175.00      2833475.00      7054325.00
      2833075.00      7054575.00
#Sta/Elev= 30
  4441.3  454.92  4524.2  451.40  4617.5  442.12  4736.3  435.42  4786.3  434.46
  4889.6  432.08  4897.4  432.99  4914.7  426.63  4919.8  428.81  4928.5  426.65
  4938.8  432.47  4959.6  432.88  4980.3  427.03  4994.1  427.85  4996.7  425.10
  4997.5  424.30  5005.4  425.10  5008.8  428.57  5014.4  428.57  5019.1  432.49
  5025.0  429.97  5040.3  432.92  5070.4  433.80  5105.7  431.29  5134.6  433.93
  5192.4  432.27  5210.2  435.42  5265.5  442.44  5380.9  450.20  5483.1  453.82
#Mann=6,-1,0
  4441.3    0.12       0  4786.3    0.16       0  4889.6    0.12       0
  4996.7    0.07       0  5005.4    0.12       0  5380.9    0.05       0
Bank Sta=4736.3,5210.2
Exp/Cntr=0.3,0.1

Type RM Length L Ch R = 1,2158,238,238,238
BEGIN DESCRIPTION:
BERNARD BRANCH 2.0
END DESCRIPTION:
XS GIS Cut Line= 4
      2833942.06      7053925.07      2833603.53      7053899.03
      2833382.18      7053972.81      2832974.99      7054575.01
#Sta/Elev= 30
  4534.7  447.99  4652.1  438.92  4759.7  433.69  4902.3  431.22  4935.6  429.91
  4978.9  432.84  4988.6  432.67  4999.8  424.48  5000.6  423.68  5008.5  424.48
  5009.7  430.91  5020.3  432.71  5051.9  431.26  5087.1  433.69  5113.8  436.75
  5128.8  435.93  5149.8  437.79  5230.6  436.75  5243.0  435.39  5344.6  435.49
  5416.5  436.89  5431.4  439.27  5452.4  438.29  5539.3  441.69  5636.6  442.77
  5719.1  444.36  5734.1  446.11  5755.1  445.78  5770.0  447.73  5834.5  449.82
#Mann=6,-1,0
  4534.7    0.12       0  4902.3    0.16       0  4978.9    0.12       0
  4999.8    0.07       0  5008.5    0.12       0  5636.6    0.05       0
Bank Sta=4759.7,5087.1
Exp/Cntr=0.3,0.1

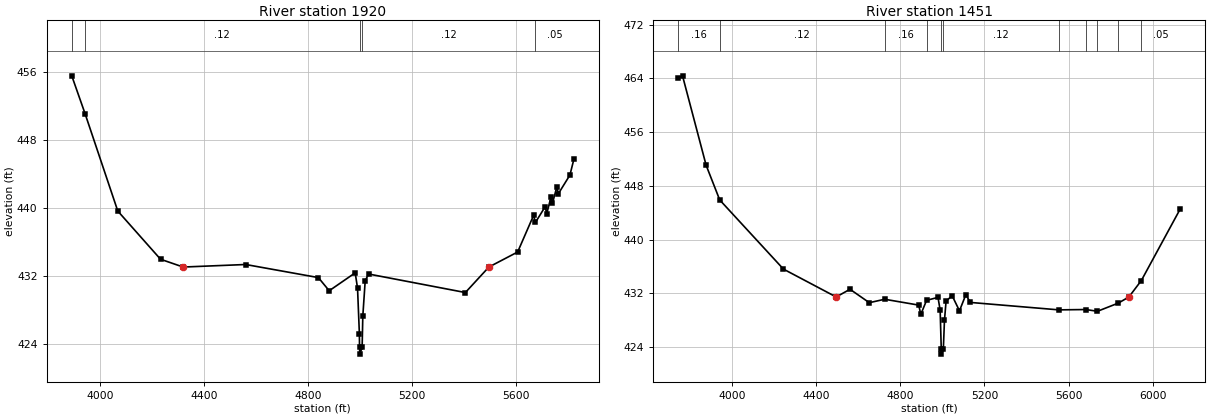
Type RM Length L Ch R = 1,1920,469,469,469
BEGIN DESCRIPTION:
Mapping XS aa3338ad
END DESCRIPTION:
XS GIS Cut Line= 4
      2834306.99      7053283.44      2833573.47      7053608.96
      2833334.76      7053786.91      2832962.34      7054531.75
#Sta/Elev= 30
  3890.8  455.60  3942.5  451.10  4068.0  439.68  4232.5  434.01  4319.8  433.09
  4560.3  433.39  4840.2  431.85  4881.9  430.30  4982.0  432.41  4991.0  430.61
  4998.1  425.24  4998.7  423.64  4999.7  422.84  5008.7  423.64  5011.3  427.31
  5020.5  431.47  5033.6  432.27  5406.2  430.09  5496.6  433.09  5607.4  434.86
  5668.9  439.18  5675.8  438.34  5713.6  440.20  5719.2  439.34  5736.0  441.35
  5741.6  440.61  5758.4  442.53  5763.9  441.71  5808.7  443.92  5823.8  445.77
#Mann=5,-1,0
  3890.8    0.16       0  3942.5    0.12       0  4998.7    0.07       0
  5008.7    0.12       0  5675.8    0.05       0
Bank Sta=4319.8,5496.6
Exp/Cntr=0.3,0.1

Type RM Length L Ch R = 1,1451,0,0,0
BEGIN DESCRIPTION:
BERNARD BRANCH 1.0
END DESCRIPTION:
XS GIS Cut Line= 3
      2834374.96      7053225.01      2833125.00      7053475.00
      2832918.63      7054565.74
#Sta/Elev= 30
  3745.7  464.08  3766.1  464.39  3878.2  451.07  3942.7  445.91  4245.4  435.61
  4496.0  431.46  4561.5  432.61  4653.3  430.61  4726.4  431.12  4887.8  430.25
  4898.0  428.88  4925.3  430.96  4979.6  431.40  4989.8  429.48  4995.0  423.75
  4996.0  422.95  5005.0  423.75  5010.2  427.96  5017.9  430.83  5046.6  431.66
  5081.5  429.40  5112.0  431.82  5132.4  430.65  5553.7  429.54  5681.5  429.59
  5737.0  429.33  5836.1  430.55  5886.3  431.46  5945.4  433.91  6130.5  444.59
#Mann=11,-1,0
  3745.7    0.16       0  3942.7    0.12       0  4726.4    0.16       0
  4925.3    0.12       0  4995.0    0.07       0  5005.0    0.12       0
  5553.7    0.16       0  5681.5    0.05       0  5737.0    0.16       0
  5836.1    0.12       0  5945.4    0.05       0
Bank Sta=4496,5886.3
Exp/Cntr=0.3,0.1

Chan Stop Cuts=-1