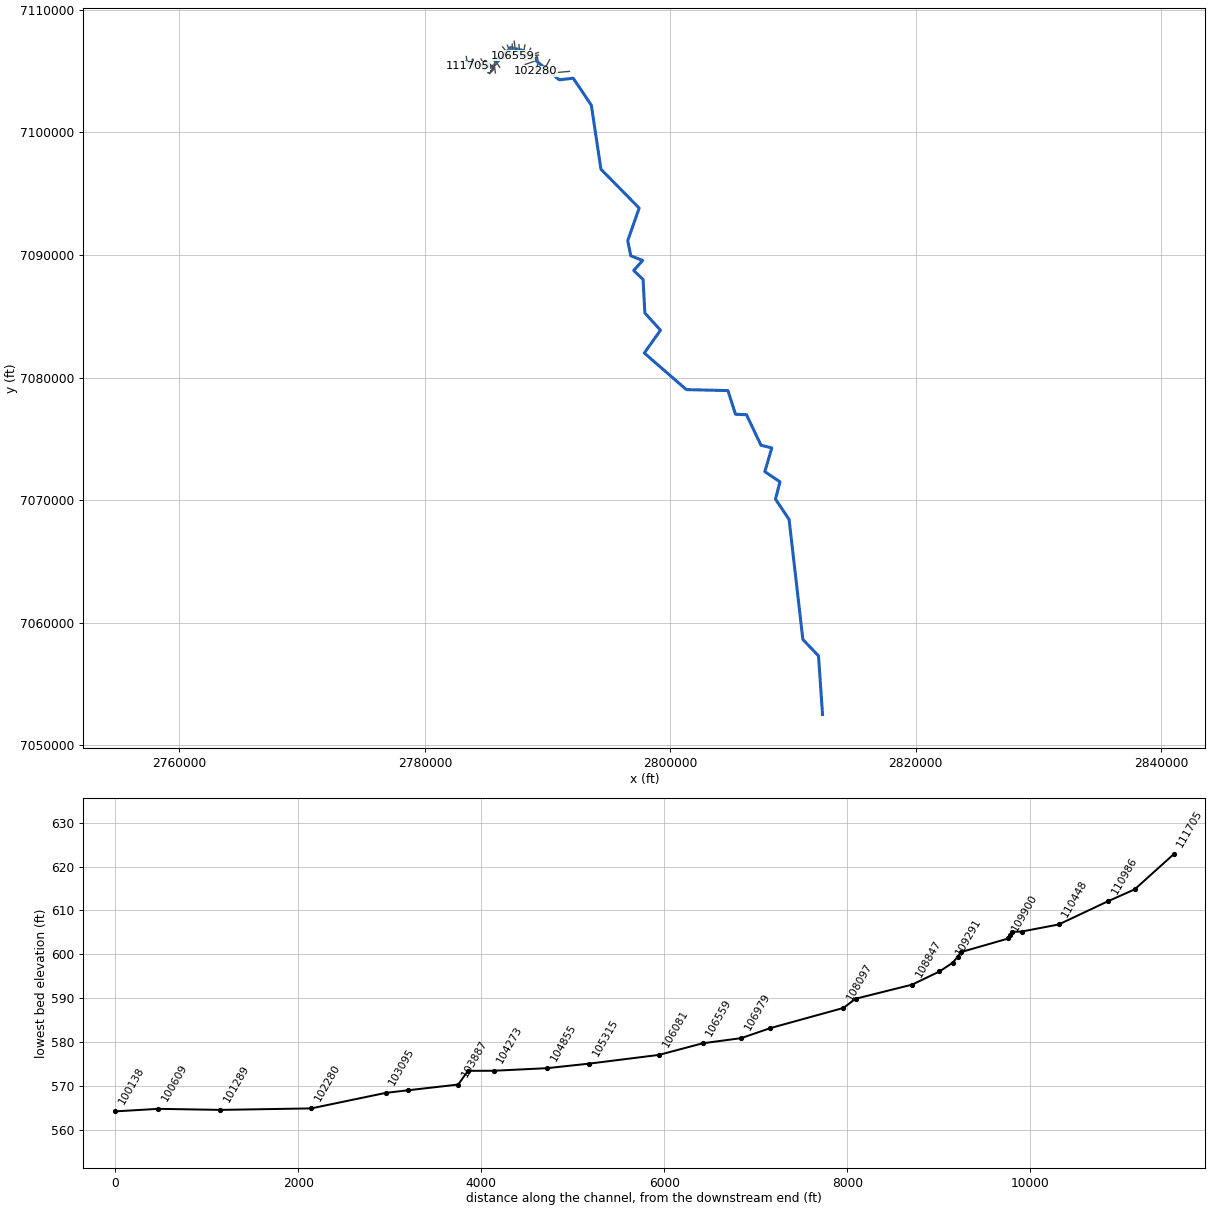
--- BIG CREEK.prj (project) ---

Proj Title=BIG CREEK Base Level Engineering
Current Plan=p01
Default Exp/Contr=0.3,0.1
English Units
Geom File=g01
Flow File=f01
Plan File=p01
BEGIN DESCRIPTION:
BIG CREEK
END DESCRIPTION:

--- BIG CREEK.p01 (plan) ---

Plan Title=Multiple Run
Short Identifier=Multiple
Geom File=g01
Flow File=f01
Subcritical Flow
K Sum by GR= 0
Std Step Tol= 0.01
Critical Tol= 0.01
Num of Std Step Trials= 20
Max Error Tol= 0.3
Flow Tol Ratio= 0.001
Split Flow NTrial= 30
Split Flow Tol= 0.02
Split Flow Ratio= 0.02
Log Output Level= 0
Friction Slope Method= 1
Unsteady Friction Slope Method= 2
Unsteady Bridges Friction Slope Method= 1
Parabolic Critical Depth
Global Vel Dist=  1 , 1 , 1
Global Log Level= 0
CheckData=True
Encroach Param= -1, 0, 0, 0
BEGIN DESCRIPTION:
Multiple Run
END DESCRIPTION:

--- BIG CREEK.f01 (steady flow) ---

Flow Title=Multiple
Program Version=5.07
Number of Profiles= 7
Profile Names=10-year,25-year,50-year,1pct_min,100-year,1pct_plu,500-year
River Rch & RM=BIG CREEK,Reach-1         ,111705
     367     473     556     325     649    1295     880
River Rch & RM=BIG CREEK,Reach-1         ,107298
     816    1105    1341     807    1610    3213    2316
River Rch & RM=BIG CREEK,Reach-1         ,103993
    1158    1592    1951    1184    2362    4712    3455
River Rch & RM=BIG CREEK,Reach-1         ,99263
    1409    1956    2413    1472    2938    5862    4349
River Rch & RM=BIG CREEK,Reach-1         ,95269
    1542    2148    2655    1623    3238    6460    4810
River Rch & RM=BIG CREEK,Reach-1         ,94225
    1713    2388    2953    1804    3600    7183    5345
River Rch & RM=BIG CREEK,Reach-1         ,83267
    1835    2557    3163    1932    3855    7691    5719
River Rch & RM=BIG CREEK,Reach-1         ,79352
    2026    2839    3523    2158    4306    8592    6429
River Rch & RM=BIG CREEK,Reach-1         ,74926
    2300    3239    4034    2478    4945    9867    7427
River Rch & RM=BIG CREEK,Reach-1         ,72994
    2480    3503    4371    2691    5369   10713    8095
River Rch & RM=BIG CREEK,Reach-1         ,69890
    2662    3761    4694    2889    5764   11501    8685
River Rch & RM=BIG CREEK,Reach-1         ,60366
    2646    3729    4646    2854    5694   11361    8548
River Rch & RM=BIG CREEK,Reach-1         ,58558
    2866    4051    5058    3113    6210   12391    9357
River Rch & RM=BIG CREEK,Reach-1         ,48515
    2971    4206    5255    3236    6457   12884    9743
River Rch & RM=BIG CREEK,Reach-1         ,46148
    3865    5511    6918    4278    8535   17030   12980
River Rch & RM=BIG CREEK,Reach-1         ,29685
    4055    5784    7262    4490    8959   17876   13624
River Rch & RM=BIG CREEK,Reach-1         ,21191
    7755   11272   14341    8973   17903   35721   27860
Boundary for River Rch & Prof#=BIG CREEK,Reach-1         , 1
Up Type= 0
Dn Type= 3
Dn Slope=0.00055
Boundary for River Rch & Prof#=BIG CREEK,Reach-1         , 2
Up Type= 0
Dn Type= 3
Dn Slope=0.00055
Boundary for River Rch & Prof#=BIG CREEK,Reach-1         , 3
Up Type= 0
Dn Type= 3
Dn Slope=0.00055
Boundary for River Rch & Prof#=BIG CREEK,Reach-1         , 4
Up Type= 0
Dn Type= 3
Dn Slope=0.00055
Boundary for River Rch & Prof#=BIG CREEK,Reach-1         , 5
Up Type= 0
Dn Type= 3
Dn Slope=0.00055
Boundary for River Rch & Prof#=BIG CREEK,Reach-1         , 6
Up Type= 0
Dn Type= 3
Dn Slope=0.00055
Boundary for River Rch & Prof#=BIG CREEK,Reach-1         , 7
Up Type= 0
Dn Type= 3
Dn Slope=0.00055
DSS Import GetInterval= 0
DSS Import GetPeak= 0
DSS Import FillOption= 0

--- BIG CREEK.g01 (geometry) ---

Geom Title=Existing Conditions

River Reach=BIG CREEK,Reach-1
Reach XY= 30
      2783403.29      7105734.46      2785474.11      7105283.25
      2786992.82      7106905.24      2788053.99      7106655.08
      2790957.20      7104274.55      2792086.80      7104403.98
      2793566.17      7102205.70      2794346.47      7096991.70
      2797463.93      7093814.50      2796529.79      7091149.07
      2796781.39      7089920.04      2797754.45      7089545.07
      2797016.10      7088725.84      2797783.18      7087999.53
      2797928.36      7085261.66      2799204.89      7083857.79
      2797881.15      7081997.61      2801307.04      7079014.17
      2804701.06      7078933.32      2805313.27      7077004.79
      2806213.17      7076963.59      2807391.02      7074479.14
      2808272.93      7074259.91      2807707.15      7072326.41
      2808940.34      7071493.31      2808577.33      7070076.43
      2809683.07      7068419.64      2810806.51      7058641.14
      2812081.26      7057299.96      2812409.79      7052527.69

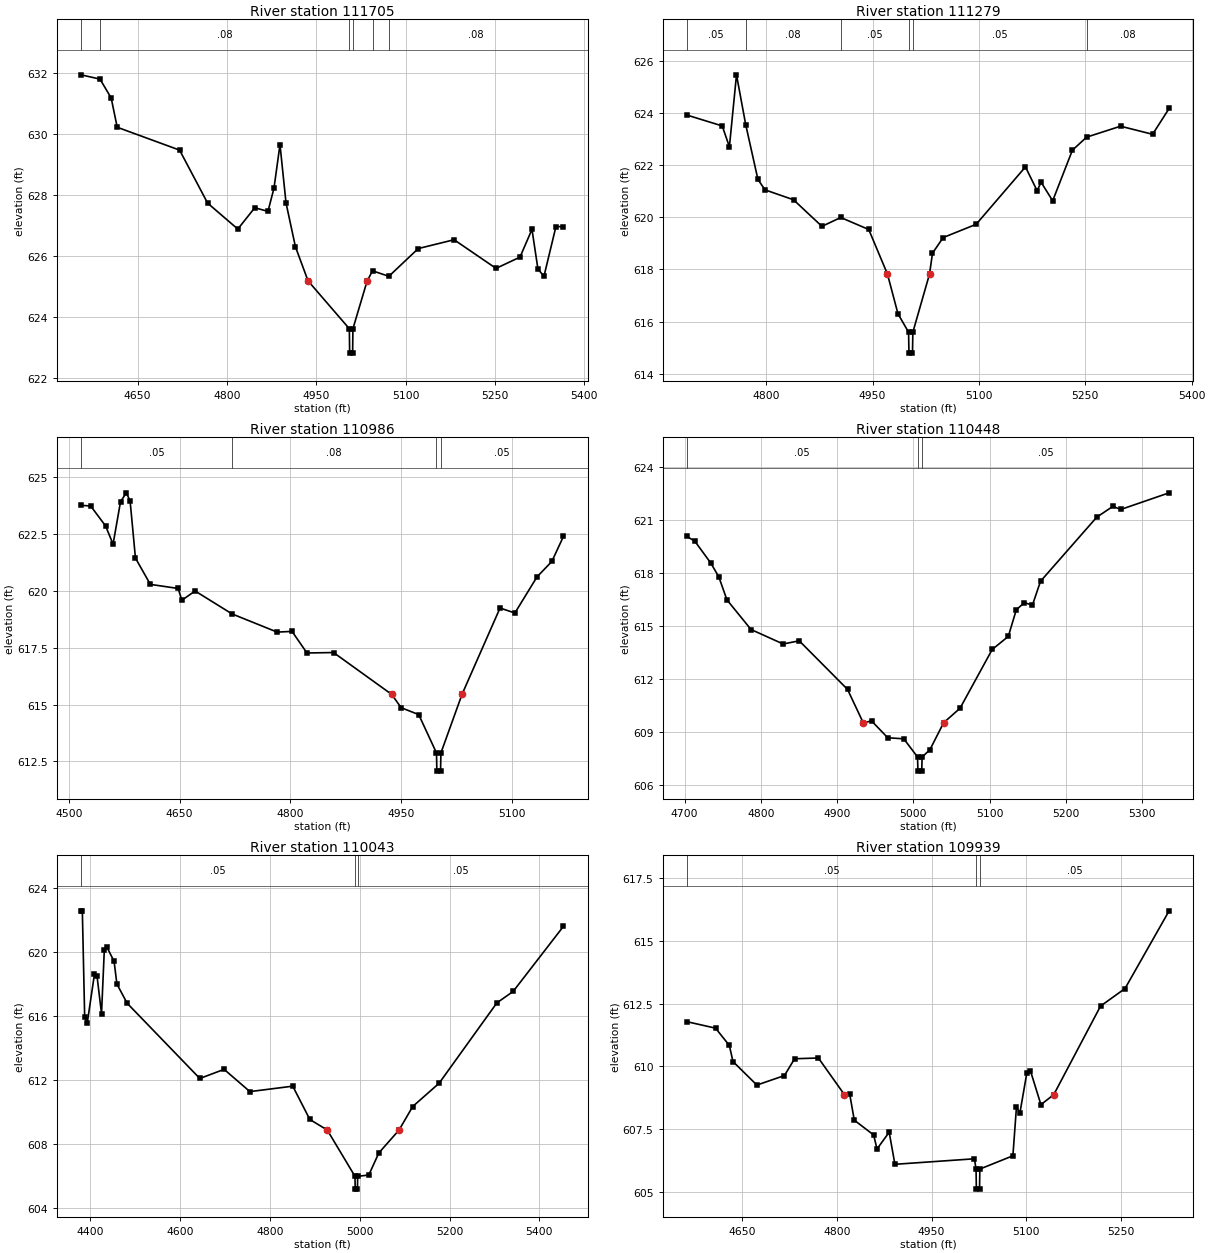
Type RM Length L Ch R = 1,111705,426,426,426
BEGIN DESCRIPTION:
BIG CREEK 108.0
END DESCRIPTION:
XS GIS Cut Line= 3
      2783375.00      7106174.98      2783444.66      7105723.95
      2783479.38      7105372.43
#Sta/Elev= 30
  4555.2  631.93  4587.0  631.79  4605.8  631.17  4615.9  630.21  4720.6  629.46
  4767.7  627.72  4818.3  626.87  4846.8  627.57  4868.9  627.45  4879.0  628.21
  4889.1  629.64  4899.2  627.73  4915.0  626.29  4936.2  625.17  5005.5  623.60
  5006.0  622.80  5011.0  622.80  5011.5  623.60  5035.4  625.17  5044.5  625.50
  5071.8  625.32  5121.1  626.23  5181.3  626.52  5251.7  625.58  5291.9  625.95
  5312.0  626.86  5322.0  625.56  5332.1  625.32  5352.2  626.95  5364.8  626.95
#Mann=6,-1,0
  4555.2     0.1       0  4587.0    0.08       0  5005.5    0.07       0
  5011.5    0.08       0  5044.5    0.05       0  5071.8    0.08       0
Bank Sta=4936.2,5035.4
Exp/Cntr=0.3,0.1

Type RM Length L Ch R = 1,111279,293,293,293
BEGIN DESCRIPTION:
Mapping XS b73b5110
END DESCRIPTION:
XS GIS Cut Line= 5
      2783861.32      7105954.90      2783885.63      7105701.39
      2783750.22      7105652.77      2783680.77      7105628.47
      2783583.53      7105444.41
#Sta/Elev= 30
  4687.9  623.92  4738.0  623.50  4748.1  622.70  4758.1  625.46  4771.1  623.55
  4788.3  621.45  4798.3  621.05  4838.5  620.67  4878.6  619.65  4905.1  619.99
  4944.6  619.53  4971.0  617.82  4985.8  616.30  5000.8  615.59  5001.3  614.79
  5006.3  614.79  5006.8  615.59  5030.3  617.82  5034.5  618.62  5049.5  619.22
  5096.1  619.73  5165.6  621.93  5182.0  621.02  5187.7  621.34  5204.0  620.63
  5231.8  622.57  5251.8  623.07  5299.7  623.49  5344.9  623.18  5368.2  624.17
#Mann=6,-1,0
  4687.9    0.05       0  4771.1    0.08       0  4905.1    0.05       0
  5000.8    0.03       0  5006.8    0.05       0  5251.8    0.08       0
Bank Sta=4971,5030.3
Exp/Cntr=0.3,0.1

Type RM Length L Ch R = 1,110986,538,538,538
BEGIN DESCRIPTION:
Mapping XS 4f8635d8
END DESCRIPTION:
XS GIS Cut Line= 3
      2783930.77      7105947.94      2783993.27      7105517.36
      2783979.43      7105299.29
#Sta/Elev= 30
  4516.5  623.77  4529.6  623.74  4549.8  622.86  4559.9  622.06  4570.0  623.93
  4577.9  624.32  4583.0  623.96  4590.2  621.45  4610.4  620.29  4648.1  620.11
  4653.1  619.59  4671.0  620.00  4721.1  618.99  4782.2  618.19  4802.4  618.22
  4822.6  617.27  4858.6  617.29  4937.3  615.45  4950.3  614.86  4974.0  614.56
  4998.1  612.87  4998.6  612.07  5003.6  612.07  5004.1  612.87  5032.7  615.45
  5084.2  619.25  5104.3  619.03  5134.3  620.62  5154.4  621.30  5170.1  622.40
#Mann=4,-1,0
  4516.5    0.05       0  4721.1    0.08       0  4998.1    0.03       0
  5004.1    0.05       0
Bank Sta=4937.3,5032.7
Exp/Cntr=0.3,0.1

Type RM Length L Ch R = 1,110448,405,405,405
BEGIN DESCRIPTION:
BIG CREEK 105.0
END DESCRIPTION:
XS GIS Cut Line= 3
      2784375.02      7105724.95      2784475.00      7105425.00
      2784375.00      7105125.01
#Sta/Elev= 30
  4702.8  620.07  4713.3  619.81  4734.4  618.56  4744.9  617.78  4755.5  616.48
  4787.1  614.80  4829.2  613.98  4850.3  614.16  4913.6  611.41  4934.2  609.52
  4945.2  609.62  4966.3  608.67  4987.4  608.61  5005.4  607.58  5005.9  606.78
  5010.9  606.78  5011.4  607.58  5021.6  607.99  5039.6  609.52  5061.1  610.34
  5103.3  613.67  5124.4  614.41  5134.9  615.92  5145.5  616.32  5156.0  616.18
  5166.6  617.53  5240.3  621.16  5261.4  621.77  5272.0  621.60  5335.2  622.54
#Mann=3,-1,0
  4702.8    0.05       0  5005.4    0.03       0  5011.4    0.05       0
Bank Sta=4934.2,5039.6
Exp/Cntr=0.3,0.1

Type RM Length L Ch R = 1,110043,104,104,104
BEGIN DESCRIPTION:
BIG CREEK 104.0
END DESCRIPTION:
XS GIS Cut Line= 3
      2784574.98      7105975.04      2784875.00      7105425.00
      2784674.98      7105024.96
#Sta/Elev= 30
  4379.7  622.55  4382.6  622.55  4387.8  615.91  4393.5  615.54  4409.6  618.60
  4415.3  618.47  4425.3  616.13  4431.5  620.10  4437.2  620.29  4453.3  619.39
  4459.5  617.98  4482.3  616.78  4644.1  612.08  4698.2  612.65  4755.6  611.26
  4851.0  611.60  4889.0  609.52  4927.8  608.86  4989.5  605.97  4990.0  605.17
  4995.0  605.17  4995.5  605.97  5020.2  606.05  5042.6  607.43  5087.6  608.86
  5118.0  610.33  5176.7  611.78  5305.3  616.80  5341.7  617.52  5453.5  621.58
#Mann=3,-1,0
  4379.7    0.05       0  4989.5    0.03       0  4995.5    0.05       0
Bank Sta=4927.8,5087.6
Exp/Cntr=0.3,0.1

Type RM Length L Ch R = 1,109939,21,21,21
BEGIN DESCRIPTION:
Mapping XS 58886106
END DESCRIPTION:
XS GIS Cut Line= 6
      2784837.03      7105788.18      2784982.85      7105520.83
      2784996.74      7105465.27      2784989.80      7105434.02
      2784975.91      7105409.72      2784819.84      7105104.51
#Sta/Elev= 30
  4562.0  611.78  4607.7  611.52  4629.6  610.83  4635.3  610.19  4673.2  609.25
  4716.9  609.63  4733.0  610.30  4770.7  610.33  4811.9  608.87  4820.4  608.88
  4827.6  607.85  4858.3  607.26  4863.6  606.70  4882.9  607.37  4892.0  606.09
  5018.0  606.31  5020.6  605.90  5021.1  605.10  5026.1  605.10  5026.6  605.90
  5079.0  606.43  5084.6  608.36  5090.2  608.15  5101.2  609.75  5106.8  609.82
  5123.4  608.47  5143.8  608.87  5217.9  612.40  5256.7  613.10  5326.6  616.20
#Mann=3,-1,0
  4562.0    0.05       0  5020.6    0.03       0  5026.6    0.05       0
Bank Sta=4811.9,5143.8
Exp/Cntr=0.3,0.1

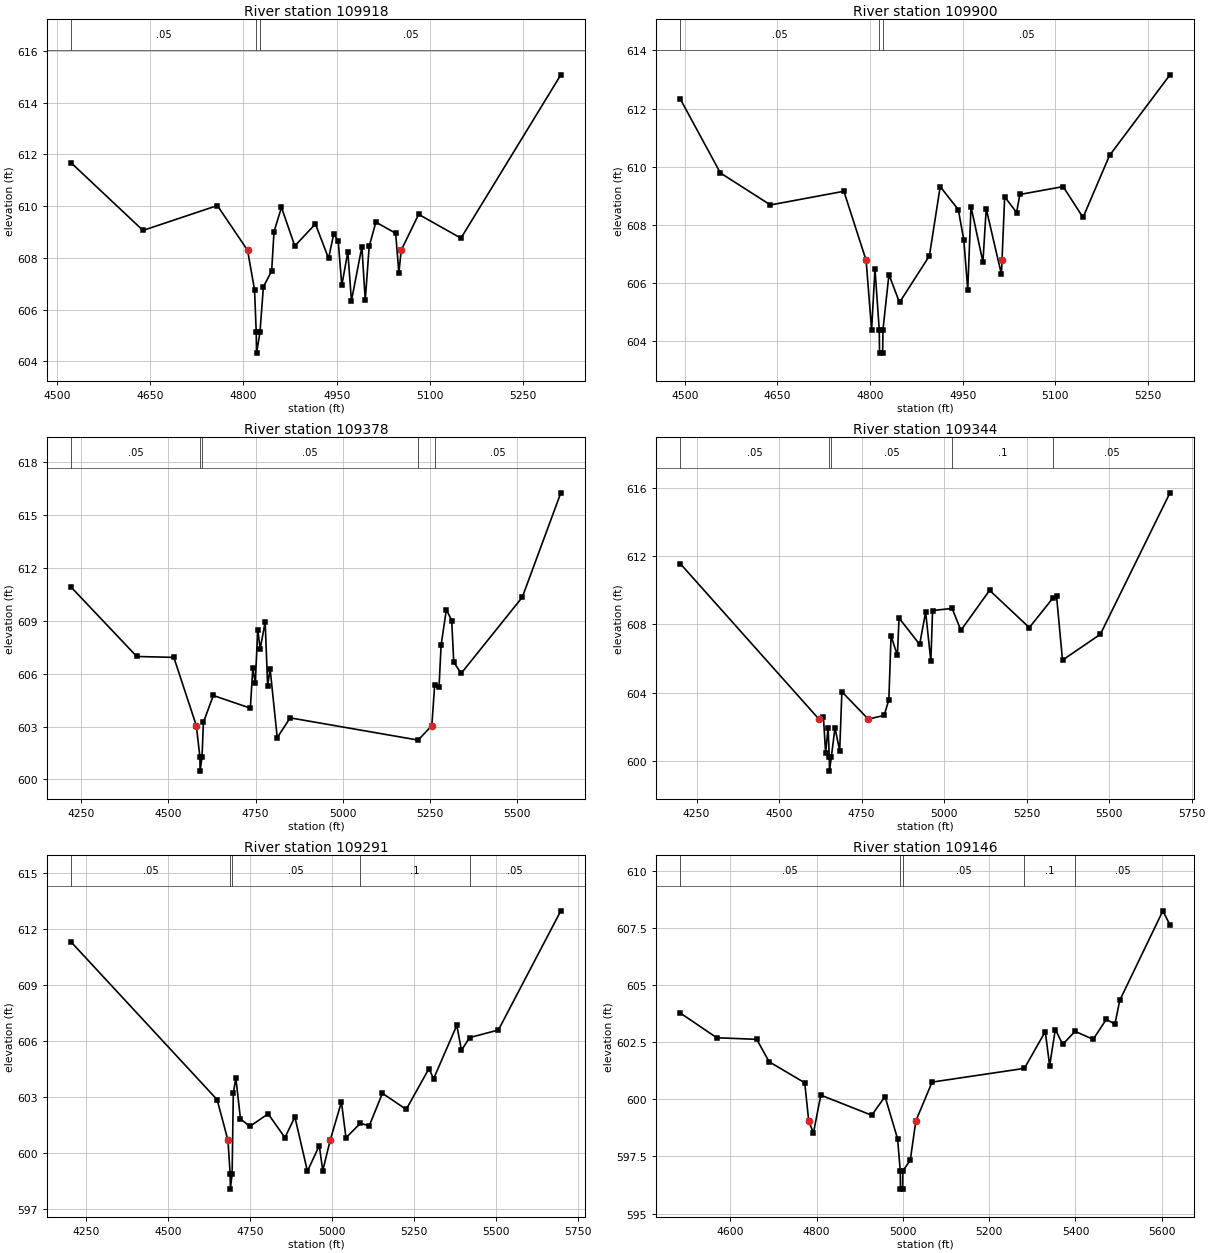
Type RM Length L Ch R = 1,109918,18,18,18
BEGIN DESCRIPTION:
Mapping XS 8ac21d55
END DESCRIPTION:
XS GIS Cut Line= 6
      2784847.45      7105806.39      2785027.13      7105480.90
      2785029.73      7105460.07      2784993.27      7105400.17
      2784956.81      7105301.21      2784857.85      7105105.89
#Sta/Elev= 30
  4523.1  611.67  4638.6  609.06  4758.2  610.02  4806.8  608.29  4818.0  606.76
  4820.7  605.12  4821.2  604.32  4826.7  605.12  4832.2  606.88  4845.5  607.49
  4849.3  609.01  4861.3  609.95  4882.7  608.46  4915.9  609.31  4937.0  607.98
  4945.3  608.92  4952.5  608.65  4958.3  606.94  4968.0  608.23  4973.8  606.34
  4990.6  608.43  4996.0  606.36  5002.3  608.44  5013.1  609.38  5044.9  608.95
  5050.1  607.40  5053.7  608.29  5081.9  609.68  5149.9  608.76  5310.5  615.07
#Mann=3,-1,0
  4523.1    0.05       0  4820.7    0.03       0  4826.7    0.05       0
Bank Sta=4806.8,5053.7
Exp/Cntr=0.3,0.1

Type RM Length L Ch R = 1,109900,522,522,522
BEGIN DESCRIPTION:
Mapping XS 8a10847a
END DESCRIPTION:
XS GIS Cut Line= 6
      2784889.12      7105835.04      2785019.31      7105579.86
      2785058.38      7105499.13      2785050.56      7105473.09
      2785027.13      7105436.63      2784902.11      7105113.67
#Sta/Elev= 30
  4492.7  612.33  4557.6  609.79  4638.7  608.69  4757.6  609.16  4793.6  606.79
  4802.5  604.40  4808.0  606.49  4814.9  604.40  4815.4  603.60  4820.4  603.60
  4820.9  604.40  4830.6  606.30  4847.7  605.34  4896.1  606.94  4913.6  609.32
  4942.9  608.53  4951.9  607.48  4958.2  605.78  4963.5  608.63  4982.8  606.73
  4988.1  608.56  5012.7  606.31  5013.7  606.79  5018.0  608.97  5037.3  608.43
  5042.6  609.05  5112.7  609.32  5144.9  608.26  5187.8  610.39  5285.7  613.16
#Mann=3,-1,0
  4492.7    0.05       0  4814.9    0.03       0  4820.9    0.05       0
Bank Sta=4793.6,5013.7
Exp/Cntr=0.3,0.1

Type RM Length L Ch R = 1,109378,34,34,34
BEGIN DESCRIPTION:
Mapping XS ba80f969
END DESCRIPTION:
XS GIS Cut Line= 6
      2784942.31      7105798.17      2785358.96      7105378.91
      2785486.56      7105350.27      2785523.02      7105134.12
      2785473.54      7105084.64      2785145.44      7104871.11
#Sta/Elev= 30
  4221.8  610.90  4409.8  606.97  4515.9  606.92  4580.3  603.05  4590.6  601.27
  4591.1  600.47  4596.6  601.27  4600.7  603.24  4629.0  604.76  4735.0  604.04
  4742.1  606.29  4749.2  605.47  4756.3  608.50  4763.3  607.40  4777.5  608.93
  4784.6  605.30  4791.6  606.28  4812.1  602.37  4849.1  603.49  5215.7  602.23
  5254.9  603.05  5263.1  605.38  5275.5  605.23  5281.5  607.63  5296.6  609.63
  5311.8  609.01  5317.7  606.65  5338.8  606.01  5514.0  610.33  5624.4  616.25
#Mann=5,-1,0
  4221.8    0.05       0  4590.6   0.035       0  4596.6    0.05       0
  5215.7     0.1       0  5263.1    0.05       0
Bank Sta=4580.3,5254.9
Exp/Cntr=0.3,0.1

Type RM Length L Ch R = 1,109344,53,53,53
BEGIN DESCRIPTION:
Mapping XS c146fff9
END DESCRIPTION:
XS GIS Cut Line= 6
      2784947.53      7105818.99      2785434.48      7105391.94
      2785512.61      7105381.52      2785541.25      7105256.52
      2785562.08      7105121.10      2785169.41      7104835.05
#Sta/Elev= 30
  4200.6  611.55  4620.7  602.46  4634.2  602.61  4640.9  600.49  4648.4  601.97
  4652.1  600.22  4652.6  599.42  4658.1  600.22  4669.3  601.95  4683.6  600.61
  4690.2  604.06  4770.2  602.46  4818.3  602.68  4832.5  603.59  4839.2  607.33
  4858.4  606.18  4863.4  608.37  4925.8  606.83  4944.0  608.72  4959.8  605.84
  4965.0  608.81  5024.3  608.93  5050.8  607.65  5137.8  609.99  5258.1  607.81
  5329.3  609.53  5340.7  609.63  5358.7  605.91  5473.4  607.42  5684.3  615.69
#Mann=5,-1,0
  4200.6    0.05       0  4652.1   0.035       0  4658.1    0.05       0
  5024.3     0.1       0  5329.3    0.05       0
Bank Sta=4620.7,4770.2
Exp/Cntr=0.3,0.1

Type RM Length L Ch R = 1,109291,145,145,145
BEGIN DESCRIPTION:
Mapping XS b2f97154
END DESCRIPTION:
XS GIS Cut Line= 6
      2784976.13      7105834.66      2785012.61      7105790.37
      2785434.48      7105431.00      2785555.77      7105407.98
      2785601.69      7105115.57      2785286.08      7104774.78
#Sta/Elev= 30
  4203.3  611.30  4649.1  602.86  4682.2  600.68  4688.9  598.87  4689.4  598.07
  4694.9  598.87  4698.5  603.19  4706.2  604.03  4720.4  601.83  4749.0  601.43
  4805.0  602.10  4856.1  600.83  4886.6  601.93  4924.9  599.03  4961.1  600.40
  4971.7  599.06  4994.3  600.68  5028.7  602.74  5042.6  600.82  5086.9  601.60
  5113.4  601.45  5153.9  603.20  5226.6  602.34  5296.0  604.52  5310.2  603.98
  5381.1  606.84  5395.3  605.50  5419.9  606.18  5508.1  606.59  5698.8  612.97
#Mann=5,-1,0
  4203.3    0.05       0  4688.9    0.03       0  4694.9    0.05       0
  5086.9     0.1       0  5419.9    0.05       0
Bank Sta=4682.2,4994.3
Exp/Cntr=0.3,0.1

Type RM Length L Ch R = 1,109146,299,299,299
BEGIN DESCRIPTION:
Mapping XS 9bb01357
END DESCRIPTION:
XS GIS Cut Line= 5
      2785560.18      7105900.09      2785708.02      7105720.11
      2785718.73      7105625.83      2785656.60      7105492.99
      2785746.40      7104838.68
#Sta/Elev= 30
  4484.2  603.77  4568.8  602.69  4661.4  602.62  4690.1  601.64  4772.6  600.72
  4781.9  599.05  4792.7  598.52  4809.9  600.18  4927.9  599.30  4958.7  600.12
  4987.8  598.27  4994.0  596.87  4994.5  596.07  4999.5  596.07  5000.0  596.87
  5017.2  597.33  5030.1  599.05  5067.7  600.75  5281.7  601.35  5330.1  602.96
  5340.2  601.47  5353.4  603.05  5370.5  602.40  5399.1  602.97  5441.1  602.62
  5471.4  603.49  5491.6  603.29  5502.6  604.32  5602.6  608.24  5619.1  607.62
#Mann=5,-1,0
  4484.2    0.05       0  4994.0    0.03       0  5000.0    0.05       0
  5281.7     0.1       0  5399.1    0.05       0
Bank Sta=4781.9,5030.1
Exp/Cntr=0.3,0.1

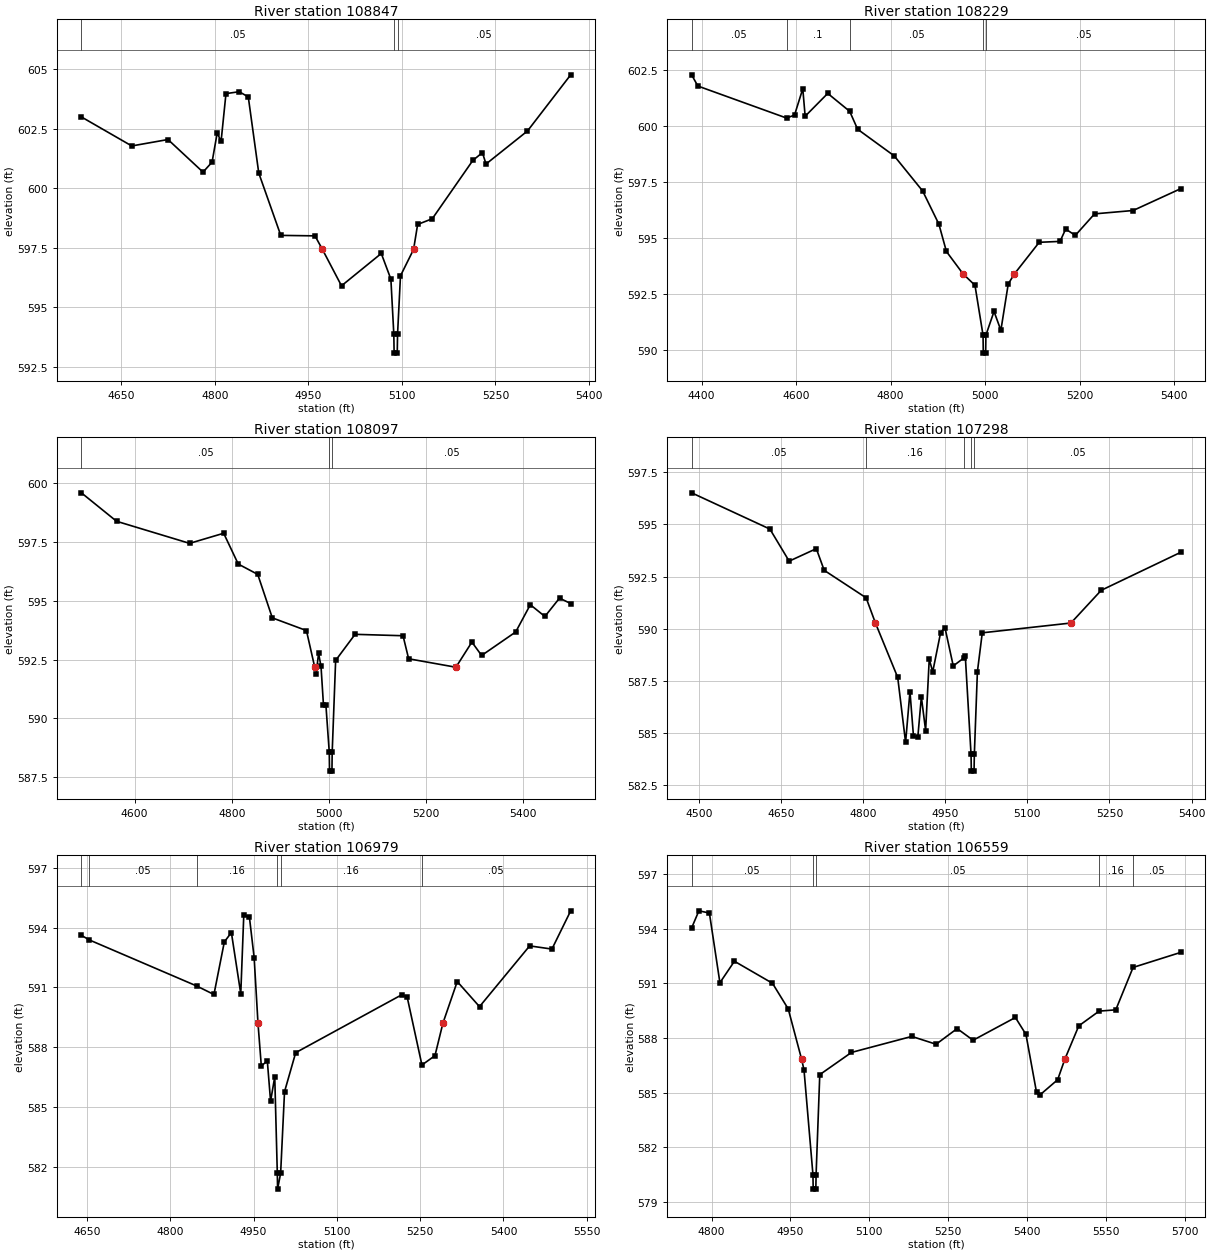
Type RM Length L Ch R = 1,108847,618,618,618
BEGIN DESCRIPTION:
Mapping XS ed9b3ee9
END DESCRIPTION:
XS GIS Cut Line= 4
      2785620.89      7105905.37      2785831.81      7105743.92
      2785857.85      7105676.21      2786092.22      7105296.01
#Sta/Elev= 30
  4585.9  603.00  4666.7  601.78  4724.8  602.05  4781.0  600.68  4795.5  601.10
  4803.7  602.32  4810.0  601.98  4817.8  603.98  4839.1  604.06  4853.6  603.84
  4870.4  600.64  4905.7  598.02  4960.6  598.00  4972.5  597.43  5003.1  595.90
  5066.9  597.26  5082.3  596.18  5087.0  593.87  5087.5  593.07  5092.5  593.07
  5093.0  593.87  5097.7  596.32  5118.7  597.43  5125.2  598.48  5148.7  598.72
  5213.7  601.17  5229.1  601.50  5234.9  601.02  5301.4  602.41  5370.7  604.77
#Mann=3,-1,0
  4585.9    0.05       0  5087.0    0.03       0  5093.0    0.05       0
Bank Sta=4972.5,5118.7
Exp/Cntr=0.3,0.1

Type RM Length L Ch R = 1,108229,132,132,132
BEGIN DESCRIPTION:
Mapping XS d9d917d0
END DESCRIPTION:
XS GIS Cut Line= 4
      2785618.26      7105988.71      2786139.10      7106035.59
      2786350.04      7106059.02      2786644.33      7106001.73
#Sta/Elev= 30
  4379.1  602.28  4392.2  601.78  4579.8  600.35  4596.7  600.48  4614.2  601.66
  4619.2  600.43  4667.0  601.45  4713.4  600.65  4730.2  599.85  4807.6  598.66
  4867.8  597.09  4902.1  595.61  4918.0  594.39  4953.2  593.39  4978.4  592.88
  4995.5  590.65  4996.0  589.85  5001.0  589.85  5001.5  590.65  5018.7  591.71
  5033.2  590.87  5048.8  592.94  5061.9  593.39  5114.3  594.80  5158.3  594.84
  5170.3  595.39  5190.7  595.11  5231.4  596.07  5312.9  596.22  5414.1  597.20
#Mann=5,-1,0
  4379.1    0.05       0  4579.8     0.1       0  4713.4    0.05       0
  4995.5    0.03       0  5001.5    0.05       0
Bank Sta=4953.2,5061.9
Exp/Cntr=0.3,0.1

Type RM Length L Ch R = 1,108097,799,799,799
BEGIN DESCRIPTION:
Mapping XS d9cd9b8b
END DESCRIPTION:
XS GIS Cut Line= 3
      2785792.70      7106131.94      2786290.15      7106160.59
      2786797.97      7106189.23
#Sta/Elev= 30
  4490.6  599.60  4563.0  598.39  4713.3  597.45  4783.4  597.88  4813.4  596.57
  4853.5  596.13  4883.5  594.28  4953.7  593.74  4970.8  592.18  4973.7  591.90
  4978.7  592.77  4983.7  592.22  4988.8  590.56  4993.8  590.56  5000.7  588.56
  5001.2  587.76  5006.2  587.76  5006.7  588.56  5013.8  592.47  5053.8  593.58
  5152.5  593.52  5164.0  592.54  5261.3  592.18  5294.2  593.25  5314.2  592.68
  5384.3  593.68  5414.4  594.84  5444.4  594.34  5474.5  595.12  5497.5  594.89
#Mann=3,-1,0
  4490.6    0.05       0  5000.7    0.03       0  5006.7    0.05       0
Bank Sta=4970.8,5261.3
Exp/Cntr=0.3,0.1

Type RM Length L Ch R = 1,107298,319,319,319
BEGIN DESCRIPTION:
Mapping XS c58e35da
END DESCRIPTION:
XS GIS Cut Line= 3
      2786337.03      7106957.45      2786633.90      7106590.27
      2786811.00      7106207.42
#Sta/Elev= 30
  4486.6  596.52  4629.6  594.78  4664.8  593.24  4714.4  593.84  4728.8  592.80
  4805.4  591.48  4822.4  590.27  4863.1  587.66  4877.5  584.54  4885.5  586.98
  4891.9  584.84  4899.8  584.78  4906.3  586.72  4914.1  585.11  4920.7  588.53
  4927.1  587.93  4941.5  589.81  4949.4  590.05  4964.6  588.21  4984.3  588.60
  4986.6  588.68  4997.1  583.96  4997.6  583.16  5002.6  583.16  5003.1  583.96
  5008.7  587.93  5017.6  589.80  5179.6  590.27  5234.9  591.84  5380.6  593.67
#Mann=5,-1,0
  4486.6    0.05       0  4805.4    0.16       0  4984.3    0.05       0
  4997.1    0.03       0  5003.1    0.05       0
Bank Sta=4822.4,5179.6
Exp/Cntr=0.3,0.1

Type RM Length L Ch R = 1,106979,420,420,420
BEGIN DESCRIPTION:
Mapping XS ef5fd751
END DESCRIPTION:
XS GIS Cut Line= 3
      2786722.43      7107095.51      2786852.65      7106772.57
      2786894.31      7106241.30
#Sta/Elev= 30
  4639.9  593.61  4654.1  593.38  4847.3  591.07  4878.6  590.64  4897.3  593.28
  4910.0  593.75  4926.9  590.68  4932.3  594.61  4942.4  594.54  4951.0  592.49
  4957.9  589.20  4963.9  587.05  4974.7  587.31  4980.6  585.28  4988.1  586.51
  4992.7  581.67  4993.2  580.87  4998.7  581.67  5005.7  585.76  5025.8  587.72
  5216.4  590.62  5226.4  590.53  5253.1  587.10  5276.6  587.57  5290.9  589.20
  5316.7  591.29  5356.8  590.03  5447.1  593.08  5487.2  592.92  5521.0  594.84
#Mann=6,-1,0
  4639.9    0.08       0  4654.1    0.05       0  4847.3    0.16       0
  4992.7    0.07       0  4998.7    0.16       0  5253.1    0.05       0
Bank Sta=4957.9,5290.9
Exp/Cntr=0.3,0.1

Type RM Length L Ch R = 1,106559,478,478,478
BEGIN DESCRIPTION:
Mapping XS efb6c95a
END DESCRIPTION:
XS GIS Cut Line= 4
      2787120.88      7107178.80      2787118.27      7106928.82
      2787081.81      7106595.48      2787118.27      7106251.73
#Sta/Elev= 30
  4762.1  594.05  4775.9  594.99  4795.9  594.87  4815.9  591.04  4843.5  592.22
  4915.9  591.01  4945.9  589.60  4971.3  586.84  4975.9  586.25  4992.9  580.50
  4993.4  579.70  4998.4  579.70  4998.9  580.50  5005.9  585.99  5066.2  587.21
  5181.0  588.09  5227.2  587.66  5267.3  588.52  5297.6  587.88  5378.1  589.13
  5398.2  588.20  5418.3  585.02  5424.2  584.86  5458.5  585.71  5472.2  586.84
  5498.7  588.67  5537.4  589.48  5569.1  589.55  5602.0  591.88  5693.1  592.71
#Mann=5,-1,0
  4762.1    0.05       0  4992.9    0.03       0  4998.9    0.05       0
  5537.4    0.16       0  5602.0    0.05       0
Bank Sta=4971.3,5472.2
Exp/Cntr=0.3,0.1

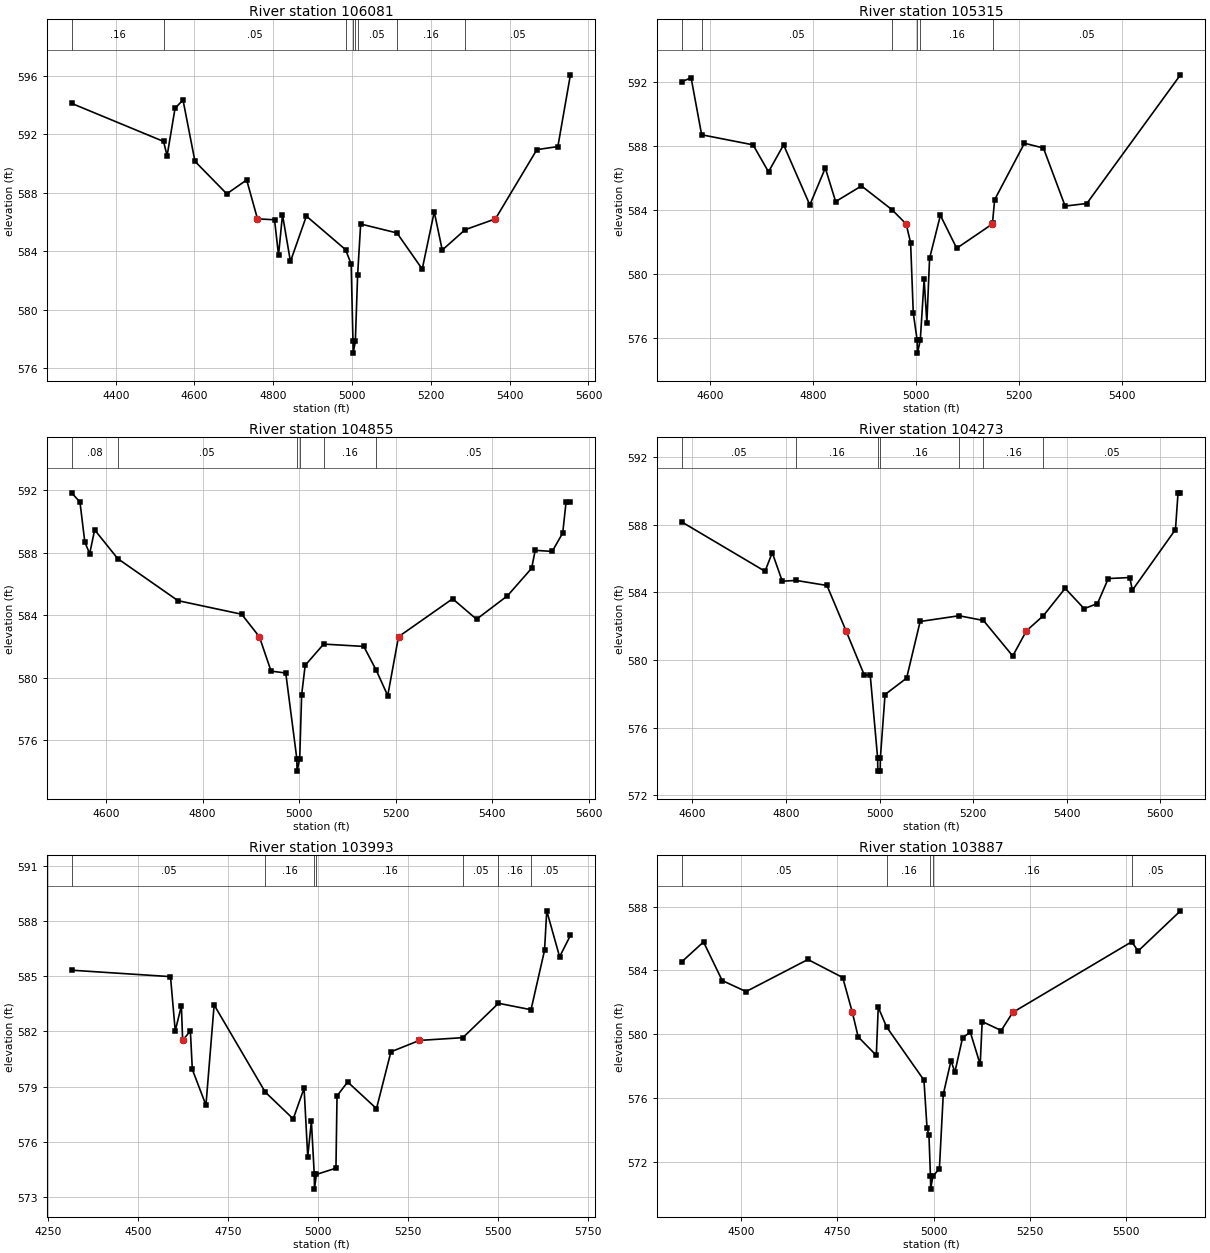
Type RM Length L Ch R = 1,106081,766,766,766
BEGIN DESCRIPTION:
BIG CREEK 94.0
END DESCRIPTION:
XS GIS Cut Line= 3
      2787275.01      7107424.96      2787375.00      7106725.00
      2787275.00      7106174.98
#Sta/Elev= 30
  4288.1  594.11  4521.5  591.51  4530.5  590.53  4550.7  593.78  4570.9  594.34
  4601.2  590.15  4682.0  587.93  4732.5  588.88  4759.9  586.22  4803.2  586.16
  4813.3  583.75  4823.4  586.50  4843.6  583.31  4884.0  586.41  4983.4  584.12
  4997.7  583.14  5002.3  577.85  5002.8  577.05  5008.3  577.85  5014.1  582.39
  5021.8  585.87  5113.9  585.26  5178.1  582.79  5208.6  586.70  5228.9  584.09
  5286.9  585.48  5363.9  586.22  5469.1  590.95  5522.4  591.16  5554.2  596.06
#Mann=8,-1,0
  4288.1    0.16       0  4521.5    0.05       0  4983.4    0.16       0
  5002.3    0.07       0  5008.3    0.16       0  5014.1    0.05       0
  5113.9    0.16       0  5286.9    0.05       0
Bank Sta=4759.9,5363.9
Exp/Cntr=0.3,0.1

Type RM Length L Ch R = 1,105315,460,460,460
BEGIN DESCRIPTION:
Mapping XS 3b56d096
END DESCRIPTION:
XS GIS Cut Line= 3
      2787662.54      7107143.20      2787700.74      7106702.25
      2787534.09      7106202.30
#Sta/Elev= 30
  4544.5  592.02  4562.8  592.28  4583.3  588.71  4683.2  588.08  4713.3  586.39
  4742.6  588.08  4793.6  584.32  4823.7  586.63  4843.8  584.53  4894.0  585.51
  4953.4  584.02  4980.8  583.13  4989.5  581.96  4994.7  577.55  5002.3  575.85
  5002.8  575.05  5008.3  575.85  5015.8  579.67  5021.1  576.94  5026.4  580.98
  5047.4  583.67  5079.1  581.61  5148.5  583.13  5148.7  583.20  5152.9  584.65
  5210.8  588.18  5247.7  587.88  5289.9  584.25  5332.0  584.41  5514.1  592.46
#Mann=6,-1,0
  4544.5    0.08       0  4583.3    0.05       0  4953.4    0.16       0
  5002.3    0.07       0  5008.3    0.16       0  5148.7    0.05       0
Bank Sta=4980.8,5148.5
Exp/Cntr=0.3,0.1

Type RM Length L Ch R = 1,104855,582,582,582
BEGIN DESCRIPTION:
Mapping XS 3392cff9
END DESCRIPTION:
XS GIS Cut Line= 3
      2788152.12      7107111.96      2788072.26      7106653.64
      2787714.62      7106212.66
#Sta/Elev= 30
  4528.9  591.83  4546.2  591.24  4556.3  588.67  4566.4  587.94  4576.6  589.46
  4624.4  587.62  4749.1  584.93  4881.1  584.06  4917.7  582.62  4942.0  580.42
  4972.4  580.30  4995.3  574.82  4995.8  574.02  5001.3  574.82  5005.3  578.90
  5012.6  580.79  5050.9  582.15  5134.0  582.00  5159.9  580.47  5183.6  578.85
  5205.9  582.62  5318.0  585.05  5367.5  583.74  5431.5  585.24  5481.6  587.00
  5489.0  588.15  5524.2  588.08  5546.0  589.26  5552.9  591.24  5561.9  591.26
#Mann=6,-1,0
  4528.9    0.08       0  4624.4    0.05       0  4995.3    0.03       0
  5001.3    0.05       0  5050.9    0.16       0  5159.9    0.05       0
Bank Sta=4917.7,5205.9
Exp/Cntr=0.3,0.1

Type RM Length L Ch R = 1,104273,280,280,280
BEGIN DESCRIPTION:
Mapping XS aefce8de
END DESCRIPTION:
XS GIS Cut Line= 3
      2788627.84      7106848.12      2788422.09      7106501.73
      2787818.95      7106226.16
#Sta/Elev= 30
  4577.2  588.17  4755.3  585.25  4770.8  586.35  4792.2  584.66  4821.5  584.71
  4887.7  584.41  4928.4  581.73  4967.5  579.11  4980.1  579.12  4995.9  574.23
  4996.4  573.43  5001.4  573.43  5001.9  574.23  5011.8  577.96  5057.9  578.93
  5086.8  582.28  5170.1  582.62  5222.1  582.34  5284.7  580.24  5314.0  581.73
  5350.4  582.63  5396.7  584.24  5437.3  583.04  5465.8  583.34  5488.9  584.82
  5534.9  584.88  5540.4  584.13  5632.5  587.72  5638.0  589.89  5643.2  589.88
#Mann=7,-1,0
  4577.2    0.05       0  4821.5    0.16       0  4995.9    0.07       0
  5001.9    0.16       0  5170.1    0.05       0  5222.1    0.16       0
  5350.4    0.05       0
Bank Sta=4928.4,5314
Exp/Cntr=0.3,0.1

Type RM Length L Ch R = 1,103993,106,106,106
BEGIN DESCRIPTION:
Mapping XS fe39889e
END DESCRIPTION:
XS GIS Cut Line= 6
      2789244.98      7106506.93      2788867.40      7106366.32
      2788633.03      7106345.48      2788534.07      7106329.86
      2788073.13      7106306.42      2787919.75      7106199.83
#Sta/Elev= 30
  4314.5  585.33  4589.4  584.98  4602.6  582.03  4619.7  583.39  4623.2  581.51
  4644.7  582.03  4650.1  579.93  4688.0  577.99  4710.7  583.44  4852.8  578.70
  4930.6  577.24  4960.8  578.91  4971.0  575.18  4981.1  577.12  4989.1  574.22
  4989.6  573.42  4995.1  574.22  5049.4  574.56  5052.4  578.49  5082.0  579.25
  5162.1  577.80  5202.2  580.89  5281.4  581.51  5402.2  581.66  5501.3  583.53
  5591.7  583.18  5629.3  586.41  5635.4  588.56  5671.2  586.06  5701.2  587.22
#Mann=7,-1,0
  4314.5    0.05       0  4852.8    0.16       0  4989.1    0.07       0
  4995.1    0.16       0  5402.2    0.05       0  5501.3    0.16       0
  5591.7    0.05       0
Bank Sta=4623.2,5281.4
Exp/Cntr=0.3,0.1

Type RM Length L Ch R = 1,103887,550,550,550
BEGIN DESCRIPTION:
Mapping XS b86fc9da
END DESCRIPTION:
XS GIS Cut Line= 3
      2789261.41      7106288.17      2788606.99      7106238.71
      2787971.60      7106191.84
#Sta/Elev= 30
  4346.9  584.53  4403.5  585.78  4452.0  583.36  4513.8  582.67  4674.2  584.68
  4764.5  583.55  4789.5  581.36  4804.6  579.83  4851.6  578.67  4856.6  581.69
  4878.1  580.46  4975.1  577.12  4983.1  574.12  4988.1  573.66  4992.0  571.09
  4992.5  570.29  4998.2  571.09  5015.2  571.58  5025.2  576.23  5045.3  578.34
  5055.3  577.62  5075.4  579.79  5095.4  580.12  5121.0  578.10  5126.1  580.79
  5175.6  580.23  5205.2  581.36  5513.9  585.79  5530.5  585.21  5640.3  587.73
#Mann=5,-1,0
  4346.9    0.05       0  4878.1    0.16       0  4992.0    0.07       0
  4998.2    0.16       0  5513.9    0.05       0
Bank Sta=4789.5,5205.2
Exp/Cntr=0.3,0.1

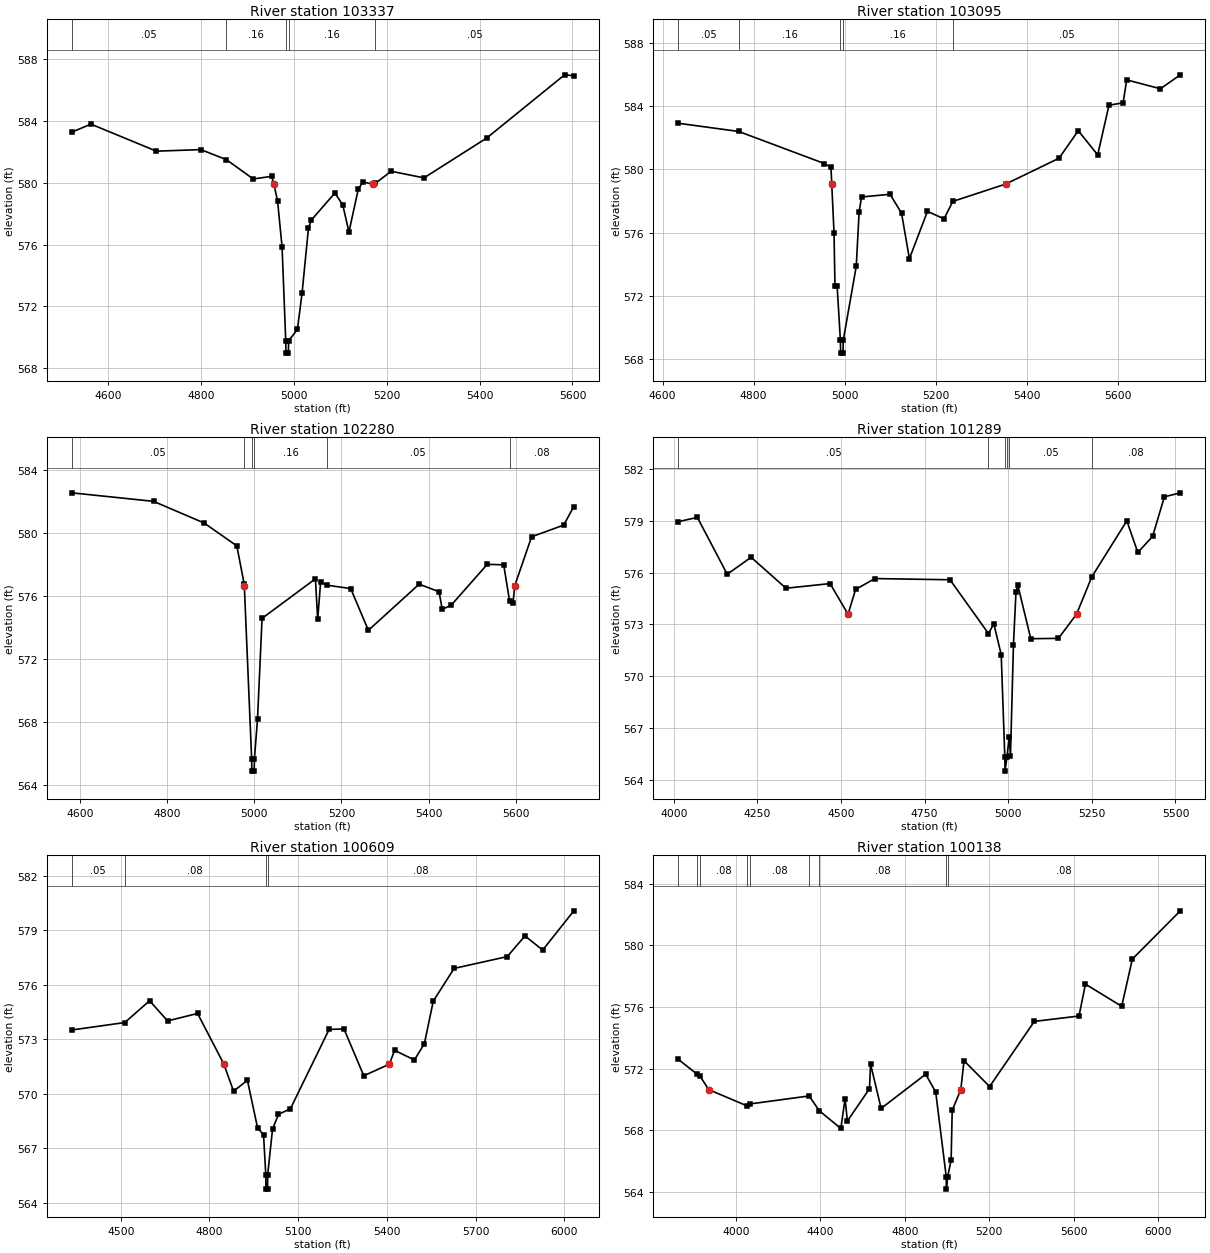
Type RM Length L Ch R = 1,103337,242,242,242
BEGIN DESCRIPTION:
Mapping XS 15d20a93
END DESCRIPTION:
XS GIS Cut Line= 3
      2789153.01      7106170.14      2788732.85      7105965.27
      2788125.22      7105885.41
#Sta/Elev= 30
  4522.6  583.28  4563.9  583.80  4704.7  582.05  4800.4  582.15  4855.4  581.50
  4913.1  580.25  4952.6  580.42  4957.6  579.91  4965.4  578.83  4975.1  575.85
  4983.0  569.78  4983.5  568.98  4988.7  568.98  4989.2  569.78  5008.1  570.51
  5018.1  572.86  5031.9  577.07  5038.3  577.60  5088.7  579.34  5105.6  578.58
  5119.0  576.82  5139.2  579.61  5149.3  580.06  5170.6  579.91  5175.5  579.96
  5209.8  580.75  5280.4  580.32  5415.4  582.90  5583.0  586.99  5602.9  586.93
#Mann=5,-1,0
  4522.6    0.05       0  4855.4    0.16       0  4983.0    0.07       0
  4989.2    0.16       0  5175.5    0.05       0
Bank Sta=4957.6,5170.6
Exp/Cntr=0.3,0.1

Type RM Length L Ch R = 1,103095,815,815,815
BEGIN DESCRIPTION:
Mapping XS a2b2a5be
END DESCRIPTION:
XS GIS Cut Line= 3
      2789087.03      7106059.03      2788889.10      7105777.77
      2788173.85      7105527.78
#Sta/Elev= 30
  4634.5  582.92  4767.2  582.40  4955.4  580.37  4969.6  580.13  4971.3  579.08
  4976.3  576.00  4978.4  572.61  4983.2  572.61  4990.3  569.19  4990.8  568.39
  4996.0  568.39  4996.5  569.19  5025.1  573.88  5031.4  577.32  5036.7  578.26
  5099.3  578.43  5124.5  577.23  5141.7  574.36  5181.3  577.35  5217.6  576.88
  5237.0  577.98  5353.3  579.08  5470.1  580.71  5512.2  582.45  5554.8  580.92
  5579.6  584.06  5610.6  584.21  5618.4  585.66  5692.5  585.10  5736.1  585.98
#Mann=5,-1,0
  4634.5    0.05       0  4767.2    0.16       0  4990.3    0.07       0
  4996.5    0.16       0  5237.0    0.05       0
Bank Sta=4971.3,5353.3
Exp/Cntr=0.3,0.1

Type RM Length L Ch R = 1,102280,991,991,991
BEGIN DESCRIPTION:
Mapping XS 62f713c7
END DESCRIPTION:
XS GIS Cut Line= 4
      2789184.24      7106066.00      2789236.33      7105690.97
      2789083.55      7105104.16      2788996.76      7104961.83
#Sta/Elev= 30
  4581.4  582.52  4768.9  581.98  4885.3  580.60  4960.0  579.15  4977.1  576.70
  4977.2  576.63  4994.0  565.65  4994.5  564.85  4999.9  564.85  5000.4  565.65
  5007.5  568.16  5017.9  574.55  5140.3  577.06  5145.5  574.49  5152.2  576.84
  5165.8  576.66  5221.3  576.44  5261.8  573.79  5378.2  576.72  5423.9  576.24
  5431.2  575.12  5451.9  575.39  5534.5  577.98  5572.2  577.95  5585.8  575.63
  5593.6  575.52  5597.6  576.63  5636.2  579.73  5709.7  580.47  5733.1  581.65
#Mann=6,-1,0
  4581.4    0.05       0  4977.1    0.16       0  4994.0    0.07       0
  5000.4    0.16       0  5165.8    0.05       0  5585.8    0.08       0
Bank Sta=4977.2,5597.6
Exp/Cntr=0.3,0.1

Type RM Length L Ch R = 1,101289,680,680,680
BEGIN DESCRIPTION:
Mapping XS bea34bd5
END DESCRIPTION:
XS GIS Cut Line= 4
      2790170.86      7105925.49      2789927.82      7105469.79
      2789571.92      7105244.09      2789072.77      7104983.67
#Sta/Elev= 30
  4013.6  578.94  4070.8  579.19  4160.0  575.90  4231.5  576.88  4335.7  575.09
  4467.5  575.36  4521.2  573.59  4543.8  575.02  4601.4  575.65  4826.0  575.58
  4941.0  572.47  4957.0  573.03  4979.1  571.25  4989.9  565.31  4990.4  564.51
  4996.3  565.31  5002.7  566.48  5006.8  565.41  5015.7  571.82  5023.3  574.90
  5028.9  575.26  5067.4  572.17  5150.2  572.19  5204.3  573.59  5250.2  575.76
  5354.6  578.99  5387.5  577.16  5431.7  578.09  5466.9  580.38  5514.5  580.61
#Mann=6,-1,0
  4013.6    0.05       0  4941.0    0.16       0  4989.9    0.07       0
  4996.3    0.16       0  5002.7    0.05       0  5250.2    0.08       0
Bank Sta=4521.2,5204.3
Exp/Cntr=0.3,0.1

Type RM Length L Ch R = 1,100609,471,471,471
BEGIN DESCRIPTION:
Mapping XS e1c0100e
END DESCRIPTION:
XS GIS Cut Line= 4
      2790804.52      7105239.75      2790140.49      7105126.91
      2789402.65      7105040.10      2789124.90      7104992.36
#Sta/Elev= 30
  4334.3  573.51  4513.6  573.92  4597.5  575.12  4658.4  574.01  4759.8  574.42
  4848.8  571.63  4881.6  570.14  4928.4  570.74  4962.7  568.13  4983.0  567.74
  4990.5  565.55  4991.0  564.75  4996.5  564.75  4997.0  565.55  5013.4  568.05
  5033.5  568.87  5073.8  569.17  5204.7  573.54  5255.0  573.57  5322.1  570.99
  5408.7  571.63  5426.2  572.39  5493.3  571.86  5526.9  572.75  5557.1  575.10
  5627.6  576.90  5807.3  577.55  5867.3  578.69  5927.2  577.91  6032.6  580.07
#Mann=4,-1,0
  4334.3    0.05       0  4513.6    0.08       0  4990.5    0.07       0
  4997.0    0.08       0
Bank Sta=4848.8,5408.7
Exp/Cntr=0.3,0.1

Type RM Length L Ch R = 1,100138,360,360,360
BEGIN DESCRIPTION:
Mapping XS 72b847ef
END DESCRIPTION:
XS GIS Cut Line= 3
      2791781.47      7104963.13      2790591.88      7104853.47
      2789419.98      7104697.21
#Sta/Elev= 30
  3727.8  572.60  3817.3  571.63  3831.3  571.50  3872.2  570.63  4054.5  569.57
  4066.6  569.70  4347.5  570.22  4395.5  569.26  4497.5  568.11  4517.6  570.03
  4528.6  568.59  4633.2  570.69  4638.3  572.29  4688.3  569.41  4899.2  571.63
  4946.6  570.48  4996.6  564.97  4997.1  564.17  5003.3  564.97  5019.7  566.06
  5024.8  569.29  5065.6  570.63  5080.7  572.51  5201.8  570.83  5413.6  575.06
  5625.0  575.41  5655.7  577.48  5827.2  576.04  5877.7  579.11  6104.7  582.24
#Mann=9,-1,0
  3727.8    0.08       0  3817.3     0.1       0  3831.3    0.08       0
  4054.5     0.1       0  4066.6    0.08       0  4347.5     0.1       0
  4395.5    0.08       0  4996.6    0.07       0  5003.3    0.08       0
Bank Sta=3872.2,5065.6
Exp/Cntr=0.3,0.1