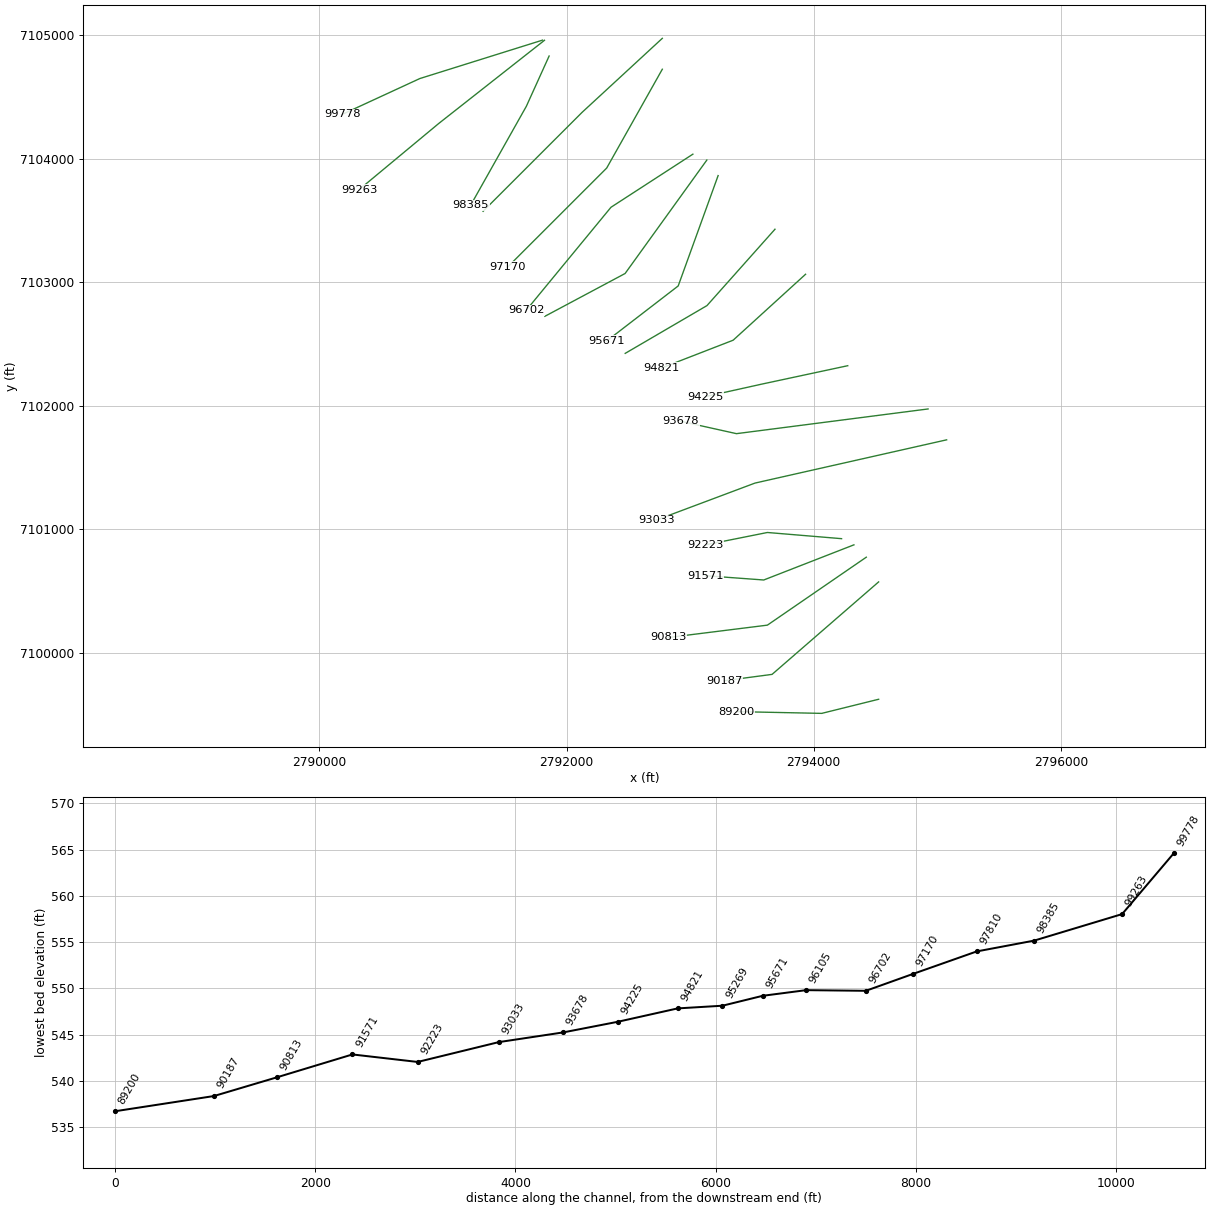
HEC-RAS study BIG CREEK.prj: BIG CREEK Base Level Engineering

--- BIG CREEK.g01 (geometry) --- (continued)

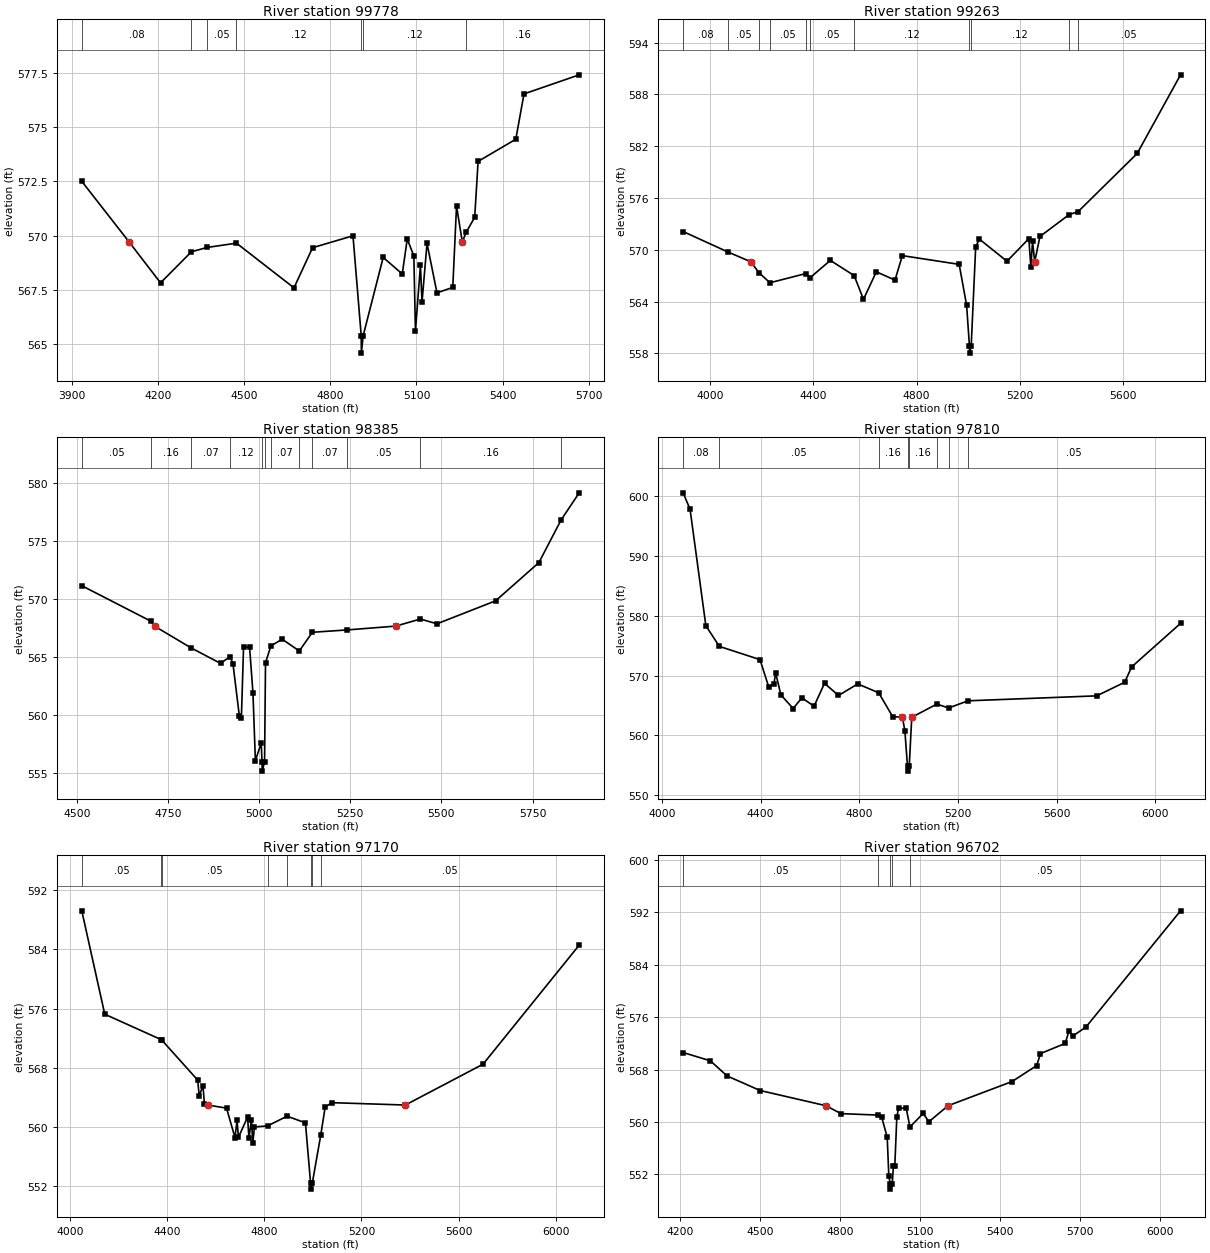
Type RM Length L Ch R = 1,99778,515,515,515
BEGIN DESCRIPTION:
Mapping XS 8090c9d8
END DESCRIPTION:
XS GIS Cut Line= 3
      2791806.18      7104960.52      2790813.24      7104649.48
      2790185.35      7104359.35
#Sta/Elev= 30
  3934.6  572.50  4099.7  569.70  4208.8  567.82  4316.1  569.25  4370.1  569.45
  4473.2  569.65  4673.5  567.59  4738.3  569.44  4879.0  569.99  4907.7  565.38
  4908.2  564.58  4914.4  565.38  4984.2  568.99  5050.6  568.23  5068.0  569.84
  5091.0  569.06  5096.5  565.60  5113.9  568.62  5119.4  566.93  5136.8  569.64
  5171.5  567.36  5226.5  567.61  5239.6  571.36  5259.8  569.70  5273.0  570.15
  5302.9  570.84  5314.7  573.42  5446.0  574.44  5474.5  576.53  5666.8  577.41
#Mann=7,-1,0
  3934.6    0.08       0  4316.1    0.16       0  4370.1    0.05       0
  4473.2    0.12       0  4907.7    0.07       0  4914.4    0.12       0
  5273.0    0.16       0
Bank Sta=4099.7,5259.8
Exp/Cntr=0.3,0.1

Type RM Length L Ch R = 1,99263,878,878,878
BEGIN DESCRIPTION:
Mapping XS c1566dca
END DESCRIPTION:
XS GIS Cut Line= 3
      2791821.77      7104959.19      2790965.15      7104284.89
      2790322.80      7103751.05
#Sta/Elev= 30
  3896.3  572.11  4069.2  569.75  4157.3  568.62  4191.2  567.31  4232.3  566.18
  4370.7  567.24  4388.5  566.78  4466.1  568.77  4558.3  567.01  4594.4  564.26
  4644.1  567.45  4716.3  566.49  4744.9  569.32  4964.8  568.31  4993.7  563.56
  5004.6  558.83  5005.1  558.03  5011.3  558.83  5028.8  570.36  5043.1  571.23
  5149.9  568.67  5234.5  571.29  5242.3  568.01  5248.8  570.97  5257.2  568.62
  5277.5  571.54  5390.5  574.07  5425.0  574.41  5653.8  581.15  5821.7  590.26
#Mann=11,-1,0
  3896.3    0.08       0  4069.2    0.05       0  4191.2    0.16       0
  4232.3    0.05       0  4370.7    0.07       0  4388.5    0.05       0
  4558.3    0.12       0  5004.6    0.07       0  5011.3    0.12       0
  5390.5    0.16       0  5425.0    0.05       0
Bank Sta=4157.3,5257.2
Exp/Cntr=0.3,0.1

Type RM Length L Ch R = 1,98385,575,575,575
BEGIN DESCRIPTION:
BIG CREEK 83.0
END DESCRIPTION:
XS GIS Cut Line= 3
      2791859.26      7104831.80      2791675.00      7104425.00
      2791224.98      7103624.97
#Sta/Elev= 30
  4513.5  571.14  4703.3  568.08  4713.0  567.66  4811.9  565.81  4894.1  564.45
  4920.4  565.03  4928.2  564.42  4945.8  559.90  4951.3  559.77  4957.3  565.87
  4973.8  565.83  4983.0  561.94  4989.7  556.08  5005.7  557.59  5007.9  555.97
  5008.4  555.17  5014.9  555.97  5017.5  564.50  5032.3  565.96  5063.3  566.53
  5110.2  565.52  5146.0  567.13  5240.9  567.33  5374.7  567.66  5442.2  568.27
  5487.9  567.86  5648.8  569.84  5767.4  573.13  5828.4  576.81  5878.0  579.14
#Mann=12,-1,0
  4513.5    0.05       0  4703.3    0.16       0  4811.9    0.07       0
  4920.4    0.12       0  5007.9    0.07       0  5014.9    0.12       0
  5032.3    0.07       0  5110.2    0.05       0  5146.0    0.07       0
  5240.9    0.05       0  5442.2    0.16       0  5828.4    0.05       0
Bank Sta=4713,5374.7
Exp/Cntr=0.3,0.1

Type RM Length L Ch R = 1,97810,640,640,640
BEGIN DESCRIPTION:
BIG CREEK 82.0
END DESCRIPTION:
XS GIS Cut Line= 3
      2792775.00      7104975.00      2792125.00      7104375.00
      2791324.97      7103574.97
#Sta/Elev= 30
  4086.4  600.58  4114.5  597.83  4178.5  578.34  4233.2  574.88  4398.0  572.66
  4433.1  568.12  4454.1  568.56  4461.5  570.43  4482.5  566.77  4532.4  564.48
  4567.5  566.26  4617.1  564.87  4659.4  568.70  4716.1  566.66  4794.1  568.60
  4879.1  567.11  4935.5  563.13  4975.4  563.01  4985.1  560.72  4995.8  554.80
  4996.3  554.00  5002.8  554.80  5013.0  563.01  5114.7  565.22  5162.4  564.57
  5241.1  565.77  5762.9  566.60  5876.1  568.88  5904.4  571.45  6102.4  578.73
#Mann=8,-1,0
  4086.4    0.08       0  4233.2    0.05       0  4879.1    0.16       0
  4995.8    0.07       0  5002.8    0.16       0  5114.7    0.05       0
  5162.4    0.16       0  5241.1    0.05       0
Bank Sta=4975.4,5013
Exp/Cntr=0.3,0.1

Type RM Length L Ch R = 1,97170,468,468,468
BEGIN DESCRIPTION:
BIG CREEK 81.0
END DESCRIPTION:
XS GIS Cut Line= 3
      2792774.99      7104724.98      2792325.00      7103925.00
      2791525.02      7103125.02
#Sta/Elev= 30
  4047.9  589.22  4142.5  575.23  4375.0  571.79  4378.0  571.71  4525.6  566.31
  4531.4  564.21  4547.3  565.52  4553.0  563.10  4566.7  562.94  4644.2  562.52
  4678.9  558.54  4687.5  560.85  4693.3  558.58  4730.9  561.30  4736.6  558.42
  4746.8  560.98  4752.5  557.83  4759.2  559.97  4813.6  560.12  4893.6  561.43
  4969.3  560.53  4990.5  552.36  4991.0  551.56  4997.5  552.36  5032.4  558.88
  5050.6  562.68  5078.9  563.26  5380.8  562.94  5701.1  568.47  6097.1  584.58
#Mann=8,-1,0
  4047.9    0.05       0  4375.0    0.16       0  4378.0    0.05       0
  4813.6    0.16       0  4893.6    0.12       0  4990.5    0.07       0
  4997.5    0.12       0  5032.4    0.05       0
Bank Sta=4566.7,5380.8
Exp/Cntr=0.3,0.1

Type RM Length L Ch R = 1,96702,597,597,597
BEGIN DESCRIPTION:
BIG CREEK 80.0
END DESCRIPTION:
XS GIS Cut Line= 3
      2793022.44      7104037.50      2792359.70      7103607.53
      2791675.02      7102775.02
#Sta/Elev= 30
  4210.0  570.61  4312.0  569.35  4375.3  567.03  4499.2  564.81  4746.1  562.49
  4803.0  561.28  4940.7  561.06  4955.3  560.79  4976.4  557.67  4982.4  551.76
  4987.9  550.55  4988.5  549.75  4995.2  550.55  4999.8  553.31  5004.9  553.31
  5012.5  560.80  5019.0  562.11  5047.7  562.11  5061.7  559.24  5111.5  561.31
  5132.8  560.04  5205.0  562.49  5445.2  566.18  5537.7  568.62  5552.0  570.45
  5644.6  572.00  5658.9  573.87  5673.3  573.13  5722.8  574.51  6077.9  592.25
#Mann=5,-1,0
  4210.0    0.05       0  4940.7    0.12       0  4987.9    0.07       0
  4995.2    0.12       0  5061.7    0.05       0
Bank Sta=4746.1,5205
Exp/Cntr=0.3,0.1

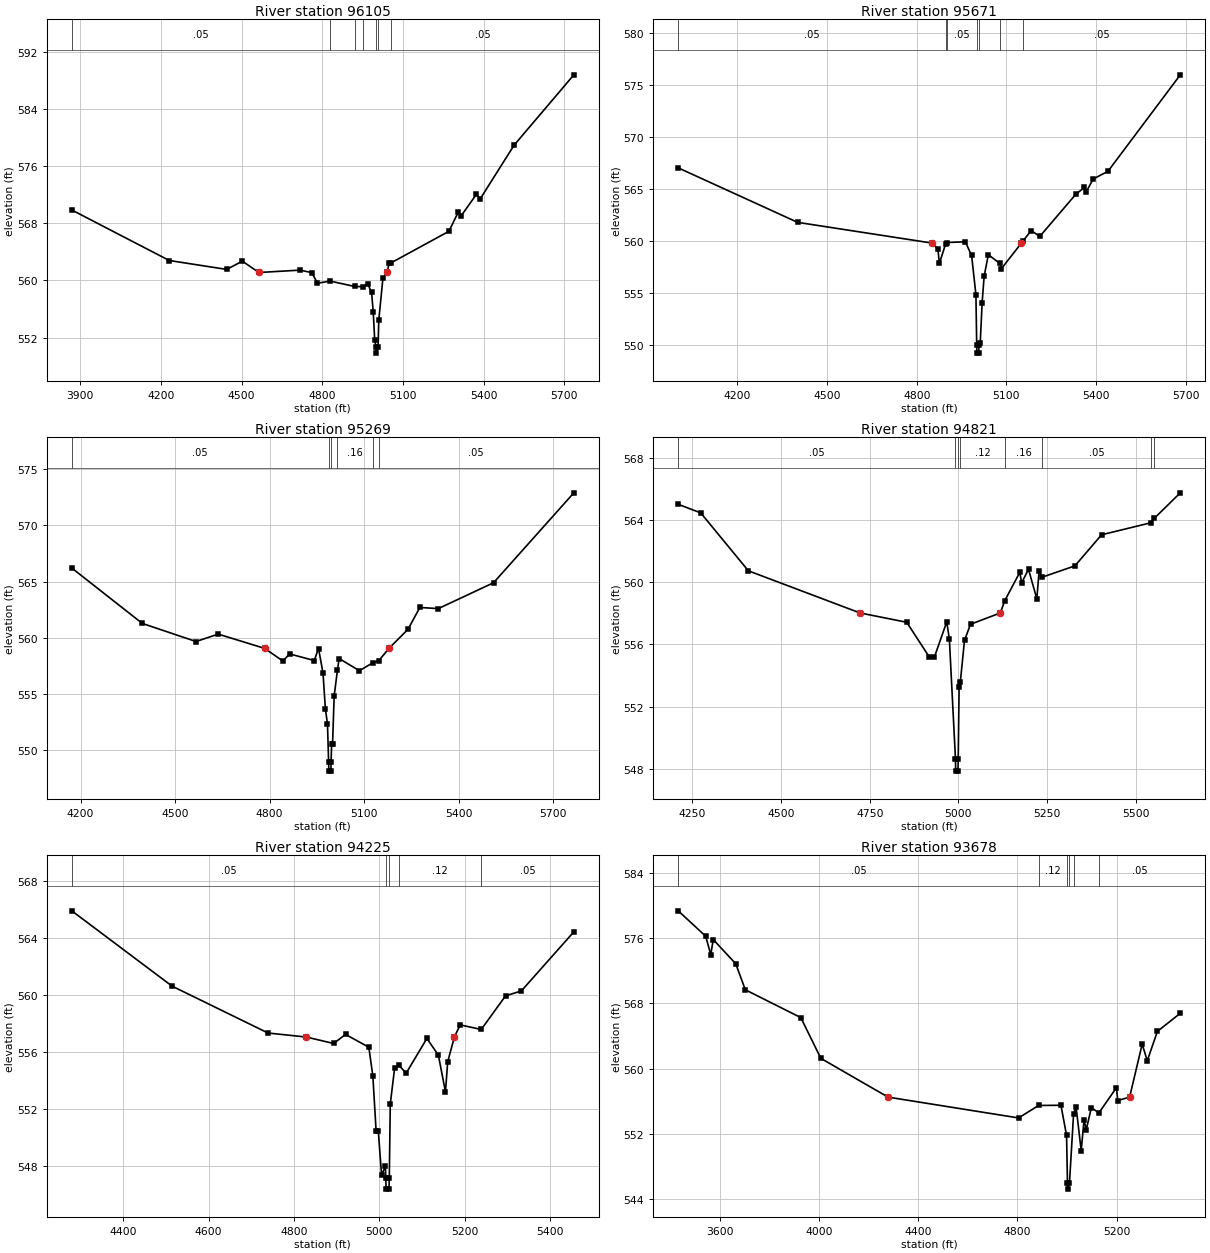
Type RM Length L Ch R = 1,96105,434,434,434
BEGIN DESCRIPTION:
BIG CREEK 79.0
END DESCRIPTION:
XS GIS Cut Line= 3
      2793135.29      7103989.76      2792473.87      7103071.35
      2791825.02      7102725.01
#Sta/Elev= 30
  3868.2  569.88  4230.9  562.80  4444.5  561.55  4502.6  562.71  4564.1  561.12
  4717.0  561.45  4761.1  561.10  4782.0  559.61  4828.5  559.92  4920.4  559.16
  4951.1  559.13  4968.5  559.54  4983.2  558.35  4989.4  555.59  4994.8  551.70
  4999.9  550.62  5000.5  549.82  5007.3  550.62  5010.1  554.48  5025.6  560.38
  5042.1  561.12  5047.5  562.41  5057.1  562.50  5270.8  566.89  5305.3  569.55
  5315.9  569.03  5372.8  572.06  5387.5  571.45  5513.5  578.97  5735.5  588.82
#Mann=7,-1,0
  3868.2    0.05       0  4828.5    0.07       0  4920.4    0.05       0
  4951.1    0.16       0  4999.9    0.07       0  5007.3    0.16       0
  5057.1    0.05       0
Bank Sta=4564.1,5042.1
Exp/Cntr=0.3,0.1

Type RM Length L Ch R = 1,95671,402,402,402
BEGIN DESCRIPTION:
BIG CREEK 78.0
END DESCRIPTION:
XS GIS Cut Line= 3
      2793226.43      7103863.88      2792903.47      7102970.66
      2792325.03      7102525.03
#Sta/Elev= 30
  4002.0  567.03  4401.4  561.79  4850.2  559.80  4870.6  559.26  4875.9  557.84
  4896.9  559.74  4900.9  559.85  4962.5  559.92  4983.6  558.61  4998.1  554.83
  5000.7  550.01  5001.2  549.21  5007.5  549.21  5008.1  550.01  5012.6  550.23
  5018.9  554.07  5025.6  556.61  5039.7  558.68  5077.8  557.84  5083.2  557.33
  5150.5  559.80  5155.9  560.01  5182.9  560.99  5211.9  560.44  5332.3  564.49
  5361.3  565.15  5367.6  564.74  5390.3  565.95  5440.2  566.71  5682.0  575.98
#Mann=7,-1,0
  4002.0    0.05       0  4896.9    0.16       0  4900.9    0.05       0
  5000.7    0.03       0  5008.1    0.05       0  5077.8    0.07       0
  5155.9    0.05       0
Bank Sta=4850.2,5150.5
Exp/Cntr=0.3,0.1

Type RM Length L Ch R = 1,95269,448,448,448
BEGIN DESCRIPTION:
BIG CREEK 77.0
END DESCRIPTION:
XS GIS Cut Line= 3
      2793686.52      7103429.88      2793136.15      7102811.54
      2792474.96      7102424.98
#Sta/Elev= 30
  4172.2  566.21  4396.1  561.28  4566.7  559.67  4636.9  560.33  4784.5  559.06
  4842.6  557.93  4863.5  558.57  4941.8  557.98  4955.5  559.05  4969.7  556.86
  4977.2  553.68  4983.9  552.34  4987.5  548.94  4988.2  548.14  4994.7  548.14
  4995.3  548.94  4997.1  550.55  5000.0  550.55  5005.1  554.84  5015.6  557.13
  5020.8  558.16  5085.3  557.07  5128.8  557.80  5146.3  557.95  5179.0  559.06
  5239.8  560.77  5277.0  562.70  5335.7  562.60  5511.0  564.90  5765.9  572.90
#Mann=6,-1,0
  4172.2    0.05       0  4987.5    0.03       0  4995.3    0.05       0
  5015.6    0.16       0  5128.8    0.07       0  5146.3    0.05       0
Bank Sta=4784.5,5179
Exp/Cntr=0.3,0.1

Type RM Length L Ch R = 1,94821,596,596,596
BEGIN DESCRIPTION:
Mapping XS 2d47751f
END DESCRIPTION:
XS GIS Cut Line= 3
      2793933.87      7103065.25      2793347.96      7102531.42
      2792768.21      7102306.44
#Sta/Elev= 30
  4210.6  565.02  4273.9  564.47  4408.3  560.74  4722.7  558.03  4854.3  557.43
  4917.8  555.20  4932.0  555.17  4967.1  557.46  4974.5  556.33  4991.6  548.65
  4992.2  547.85  4998.7  547.85  4999.4  548.65  5001.9  553.27  5005.2  553.56
  5017.1  556.26  5034.0  557.30  5118.0  558.03  5130.5  558.82  5172.8  560.64
  5178.2  559.97  5197.4  560.84  5220.9  558.93  5227.3  560.75  5235.8  560.33
  5328.2  561.06  5403.3  563.06  5541.6  563.83  5551.8  564.12  5625.1  565.76
#Mann=8,-1,0
  4210.6    0.05       0  4991.6    0.03       0  4999.4    0.05       0
  5005.2    0.12       0  5130.5    0.16       0  5235.8    0.05       0
  5541.6     0.1       0  5551.8    0.05       0
Bank Sta=4722.7,5118
Exp/Cntr=0.3,0.1

Type RM Length L Ch R = 1,94225,547,547,547
BEGIN DESCRIPTION:
BIG CREEK 76.0
END DESCRIPTION:
XS GIS Cut Line= 3
      2794275.02      7102325.00      2793575.00      7102175.00
      2793124.99      7102075.00
#Sta/Elev= 30
  4279.1  565.88  4514.3  560.61  4739.3  557.33  4829.0  557.05  4892.7  556.60
  4920.9  557.23  4975.4  556.34  4984.8  554.34  4992.5  550.48  4997.6  550.48
  5005.3  547.39  5014.2  548.01  5015.2  547.21  5015.9  546.41  5022.7  546.41
  5023.4  547.21  5025.7  552.37  5036.0  554.90  5046.2  555.07  5062.9  554.52
  5111.5  556.95  5138.4  555.79  5155.1  553.21  5160.2  555.30  5175.9  557.05
  5189.6  557.90  5238.9  557.58  5295.9  559.93  5333.1  560.28  5456.0  564.41
#Mann=5,-1,0
  4279.1    0.05       0  5015.2    0.03       0  5023.4    0.05       0
  5046.2    0.12       0  5238.9    0.05       0
Bank Sta=4829,5175.9
Exp/Cntr=0.3,0.1

Type RM Length L Ch R = 1,93678,645,645,645
BEGIN DESCRIPTION:
BIG CREEK 75.0
END DESCRIPTION:
XS GIS Cut Line= 3
      2794925.02      7101975.00      2793375.00      7101775.00
      2792924.95      7101875.01
#Sta/Elev= 30
  3433.1  579.35  3544.0  576.23  3564.2  573.98  3574.3  575.83  3665.0  572.86
  3703.5  569.68  3927.2  566.27  4007.9  561.28  4279.0  556.53  4805.0  553.98
  4885.9  555.51  4975.8  555.53  4998.5  551.84  5002.1  546.06  5002.8  545.26
  5010.3  546.06  5026.8  554.50  5037.0  555.30  5057.4  549.98  5069.0  553.74
  5077.9  552.55  5098.4  555.24  5128.8  554.60  5199.6  557.69  5204.7  556.11
  5252.6  556.53  5303.3  563.02  5323.8  560.99  5364.8  564.59  5457.0  566.80
#Mann=6,-1,0
  3433.1    0.05       0  4885.9    0.12       0  5002.1    0.07       0
  5010.3    0.12       0  5026.8    0.16       0  5128.8    0.05       0
Bank Sta=4279,5252.6
Exp/Cntr=0.3,0.1

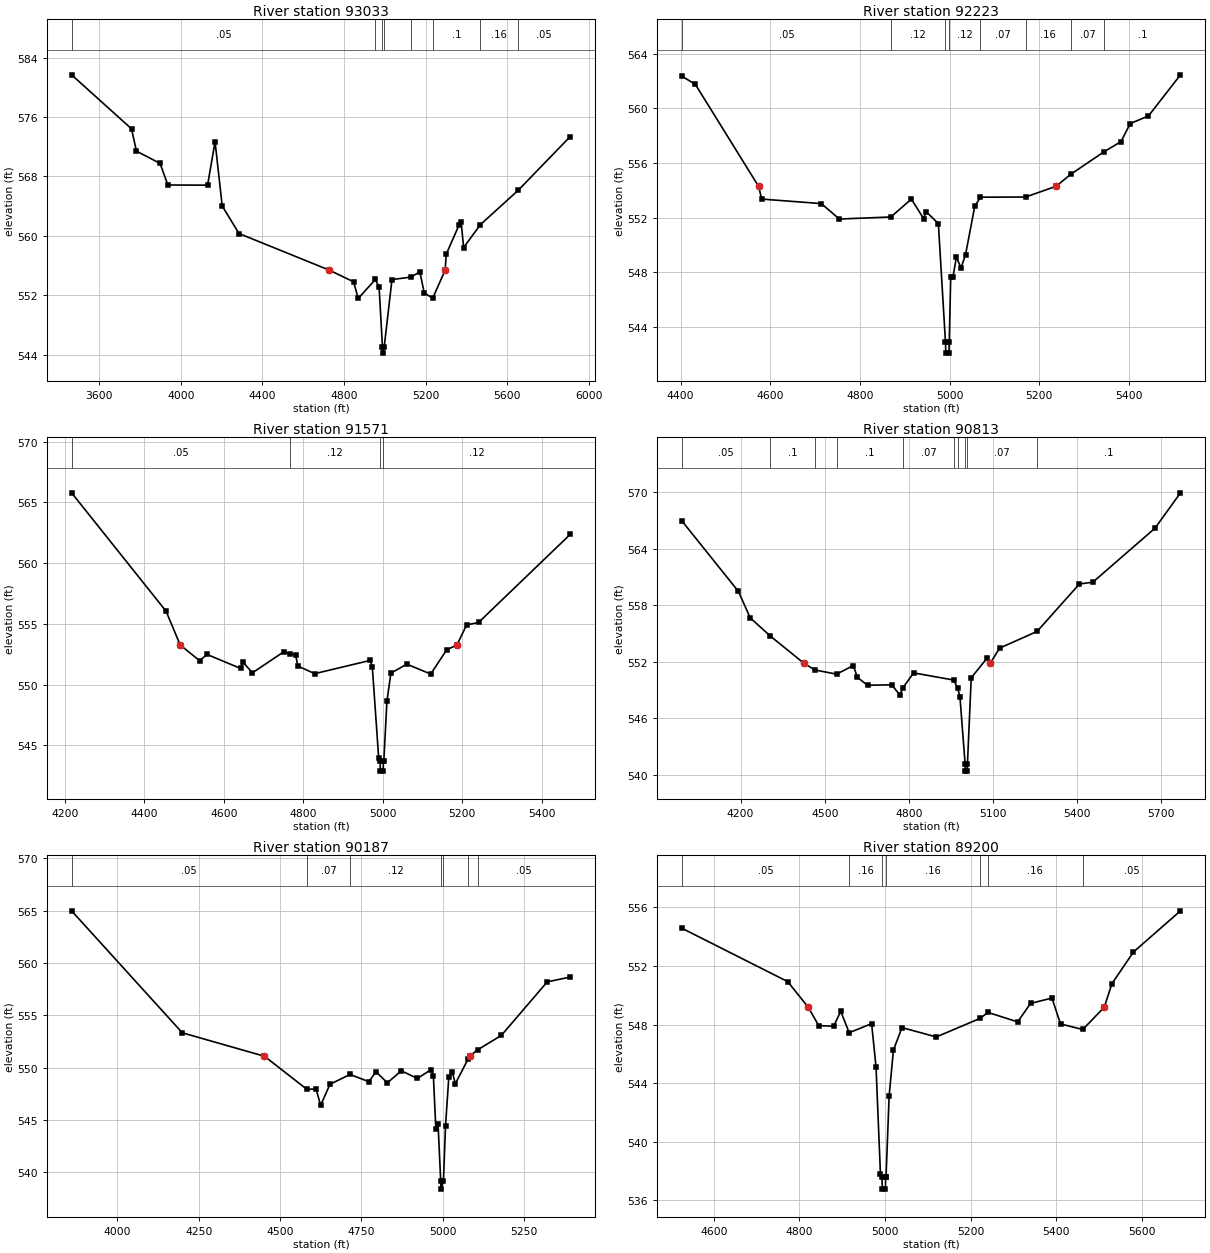
Type RM Length L Ch R = 1,93033,810,810,810
BEGIN DESCRIPTION:
BIG CREEK 74.0
END DESCRIPTION:
XS GIS Cut Line= 3
      2795075.01      7101725.00      2793525.00      7101375.00
      2792725.03      7101075.01
#Sta/Elev= 30
  3464.5  581.67  3758.2  574.40  3782.3  571.40  3898.0  569.75  3936.1  566.84
  4130.9  566.82  4167.5  572.66  4202.6  564.02  4284.7  560.31  4725.8  555.40
  4846.3  553.81  4869.0  551.57  4953.3  554.13  4971.5  553.05  4987.9  545.01
  4988.6  544.21  4996.2  545.01  5034.5  554.11  5129.1  554.45  5171.0  555.17
  5192.4  552.33  5234.0  551.60  5295.4  555.40  5300.1  557.50  5363.3  561.46
  5373.9  561.80  5385.5  558.42  5467.9  561.51  5653.5  566.14  5907.9  573.36
#Mann=8,-1,0
  3464.5    0.05       0  4953.3    0.12       0  4987.9    0.07       0
  4996.2    0.12       0  5129.1    0.07       0  5234.0     0.1       0
  5467.9    0.16       0  5653.5    0.05       0
Bank Sta=4725.8,5295.4
Exp/Cntr=0.3,0.1

Type RM Length L Ch R = 1,92223,652,652,652
BEGIN DESCRIPTION:
BIG CREEK 73.0
END DESCRIPTION:
XS GIS Cut Line= 3
      2794225.01      7100925.00      2793625.00      7100975.00
      2793124.99      7100875.00
#Sta/Elev= 30
  4403.0  562.35  4433.1  561.75  4573.9  554.29  4581.1  553.35  4714.1  553.02
  4754.2  551.89  4869.1  552.04  4914.8  553.35  4942.4  551.91  4947.4  552.44
  4975.0  551.56  4990.9  542.87  4991.6  542.07  4998.5  542.07  4999.3  542.87
  5002.6  547.66  5007.6  547.66  5015.3  549.10  5025.5  548.31  5035.7  549.29
  5056.1  552.81  5068.9  553.49  5169.5  553.50  5237.7  554.29  5270.0  555.16
  5344.7  556.82  5382.4  557.56  5402.8  558.88  5443.6  559.44  5515.0  562.45
#Mann=8,-1,0
  4403.0    0.05       0  4869.1    0.12       0  4990.9    0.07       0
  4999.3    0.12       0  5068.9    0.07       0  5169.5    0.16       0
  5270.0    0.07       0  5344.7     0.1       0
Bank Sta=4573.9,5237.7
Exp/Cntr=0.3,0.1

Type RM Length L Ch R = 1,91571,758,758,758
BEGIN DESCRIPTION:
BIG CREEK 72.0
END DESCRIPTION:
XS GIS Cut Line= 3
      2794324.98      7100874.99      2793595.59      7100590.52
      2793124.96      7100625.00
#Sta/Elev= 30
  4217.1  565.78  4454.8  556.04  4490.4  553.26  4539.1  551.97  4558.1  552.48
  4642.4  551.33  4647.7  551.87  4672.2  550.97  4751.1  552.70  4767.7  552.49
  4780.9  552.46  4786.3  551.53  4828.9  550.90  4968.4  551.99  4973.9  551.45
  4989.9  543.97  4993.4  543.68  4994.2  542.88  5001.1  542.88  5001.8  543.68
  5002.8  543.68  5010.6  548.61  5020.7  550.95  5060.8  551.68  5120.9  550.87
  5161.0  552.86  5186.8  553.26  5211.2  554.91  5241.2  555.11  5471.9  562.36
#Mann=4,-1,0
  4217.1    0.05       0  4767.7    0.12       0  4993.4    0.07       0
  5001.8    0.12       0
Bank Sta=4490.4,5186.8
Exp/Cntr=0.3,0.1

Type RM Length L Ch R = 1,90813,626,626,626
BEGIN DESCRIPTION:
BIG CREEK 71.0
END DESCRIPTION:
XS GIS Cut Line= 3
      2794424.96      7100774.97      2793625.00      7100225.00
      2792825.00      7100125.00
#Sta/Elev= 30
  3991.0  566.97  4192.6  559.48  4234.5  556.68  4305.9  554.75  4426.5  551.84
  4465.1  551.14  4542.5  550.70  4601.9  551.61  4616.7  550.35  4652.6  549.52
  4739.2  549.56  4767.6  548.49  4779.1  549.27  4817.0  550.83  4959.9  550.07
  4973.9  549.21  4981.9  548.32  5000.4  541.20  5001.1  540.40  5008.1  540.40
  5008.8  541.20  5022.2  550.31  5080.2  552.45  5089.9  551.84  5123.0  553.45
  5257.2  555.24  5407.7  560.27  5455.6  560.46  5677.3  566.20  5768.0  569.95
#Mann=10,-1,0
  3991.0    0.05       0  4305.9     0.1       0  4465.1    0.05       0
  4542.5     0.1       0  4779.1    0.07       0  4959.9     0.1       0
  4973.9    0.07       0  5000.4    0.07       0  5008.8    0.07       0
  5257.2     0.1       0
Bank Sta=4426.5,5089.9
Exp/Cntr=0.3,0.1

Type RM Length L Ch R = 1,90187,987,987,987
BEGIN DESCRIPTION:
BIG CREEK 70.0
END DESCRIPTION:
XS GIS Cut Line= 3
      2794524.97      7100574.97      2793662.82      7099826.39
      2793275.00      7099775.00
#Sta/Elev= 30
  3859.0  564.99  4199.4  553.33  4452.0  551.09  4582.0  547.94  4610.6  547.95
  4624.8  546.40  4653.3  548.41  4715.2  549.35  4772.9  548.66  4794.8  549.61
  4829.9  548.55  4872.7  549.70  4922.0  548.97  4964.8  549.82  4971.4  549.17
  4979.0  544.09  4985.7  544.64  4993.8  539.19  4994.5  538.39  5002.3  539.19
  5008.7  544.46  5018.8  549.12  5028.9  549.63  5038.9  548.47  5077.5  550.79
  5082.5  551.09  5108.7  551.73  5180.2  553.08  5321.4  558.20  5392.0  558.66
#Mann=7,-1,0
  3859.0    0.05       0  4582.0    0.07       0  4715.2    0.12       0
  4993.8    0.07       0  5002.3    0.12       0  5077.5     0.1       0
  5108.7    0.05       0
Bank Sta=4452,5082.5
Exp/Cntr=0.3,0.1

Type RM Length L Ch R = 1,89200,332,332,332
BEGIN DESCRIPTION:
BIG CREEK 69.0
END DESCRIPTION:
XS GIS Cut Line= 3
      2794524.97      7099624.99      2794064.63      7099510.76
      2793374.97      7099525.00
#Sta/Elev= 30
  4525.7  554.58  4772.9  550.93  4820.7  549.18  4845.1  547.93  4879.9  547.88
  4896.6  548.90  4916.3  547.44  4968.7  548.06  4979.0  545.09  4989.3  537.78
  4992.9  537.55  4993.7  536.75  5000.8  536.75  5001.5  537.55  5002.3  537.55
  5009.6  543.13  5019.6  546.25  5039.6  547.79  5119.7  547.15  5222.8  548.43
  5240.0  548.83  5309.7  548.18  5339.7  549.44  5389.7  549.81  5409.7  548.04
  5461.6  547.66  5511.8  549.18  5529.7  550.79  5579.8  552.95  5689.8  555.77
#Mann=7,-1,0
  4525.7    0.05       0  4916.3    0.16       0  4992.9    0.07       0
  5001.5    0.16       0  5222.8    0.12       0  5240.0    0.16       0
  5461.6    0.05       0
Bank Sta=4820.7,5511.8
Exp/Cntr=0.3,0.1