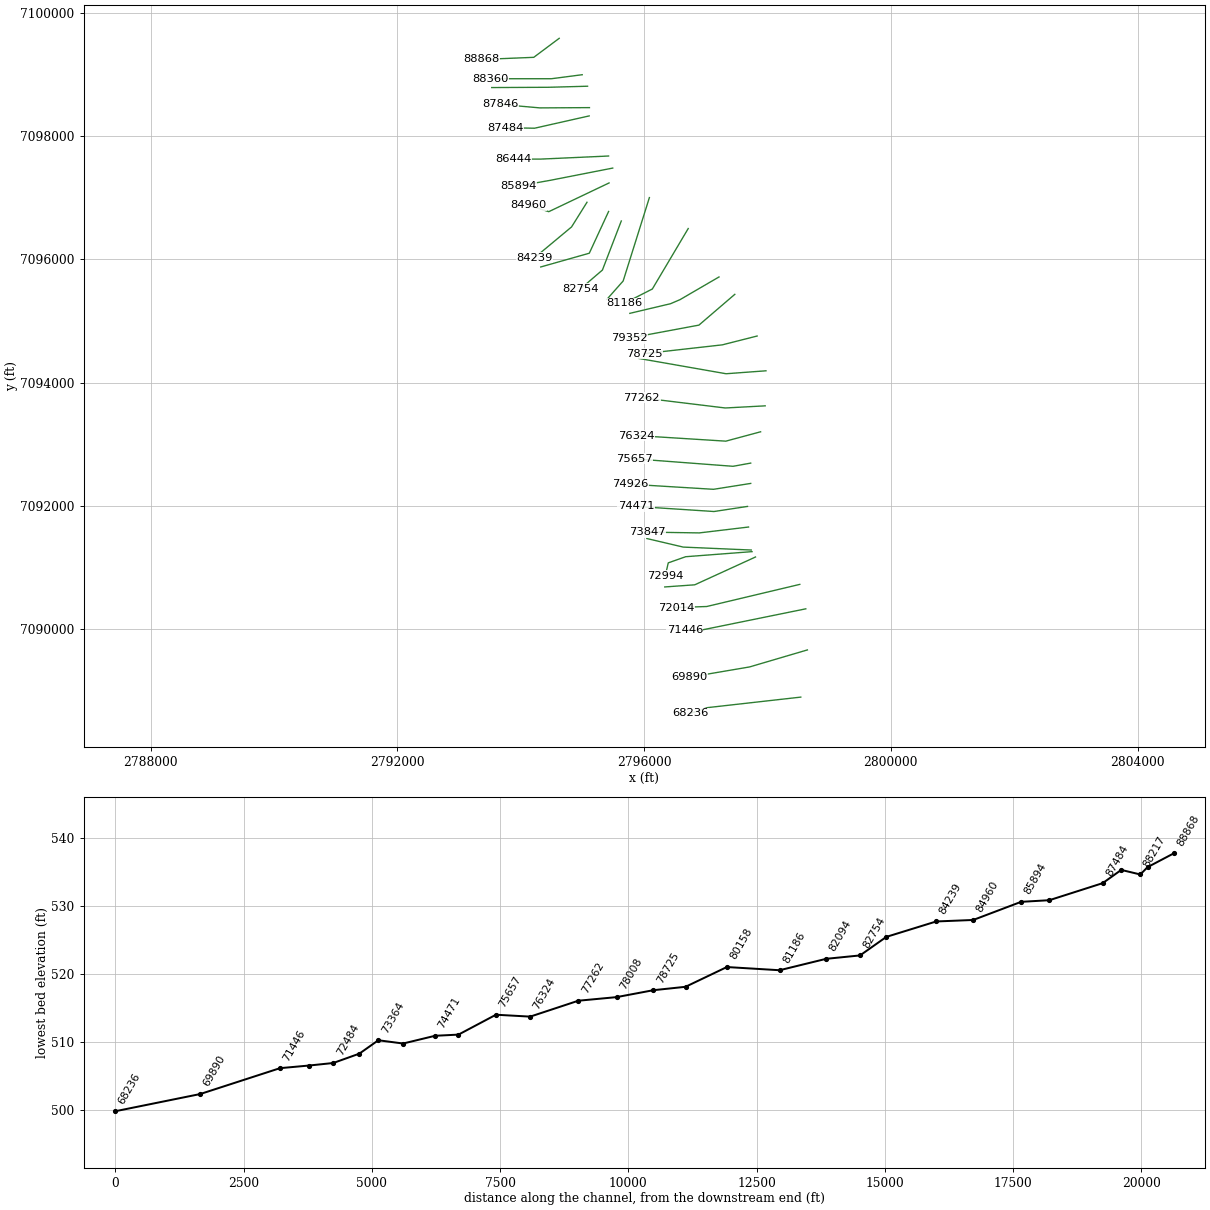
HEC-RAS study BIG CREEK.prj: BIG CREEK Base Level Engineering

--- BIG CREEK.g01 (geometry) --- (continued)

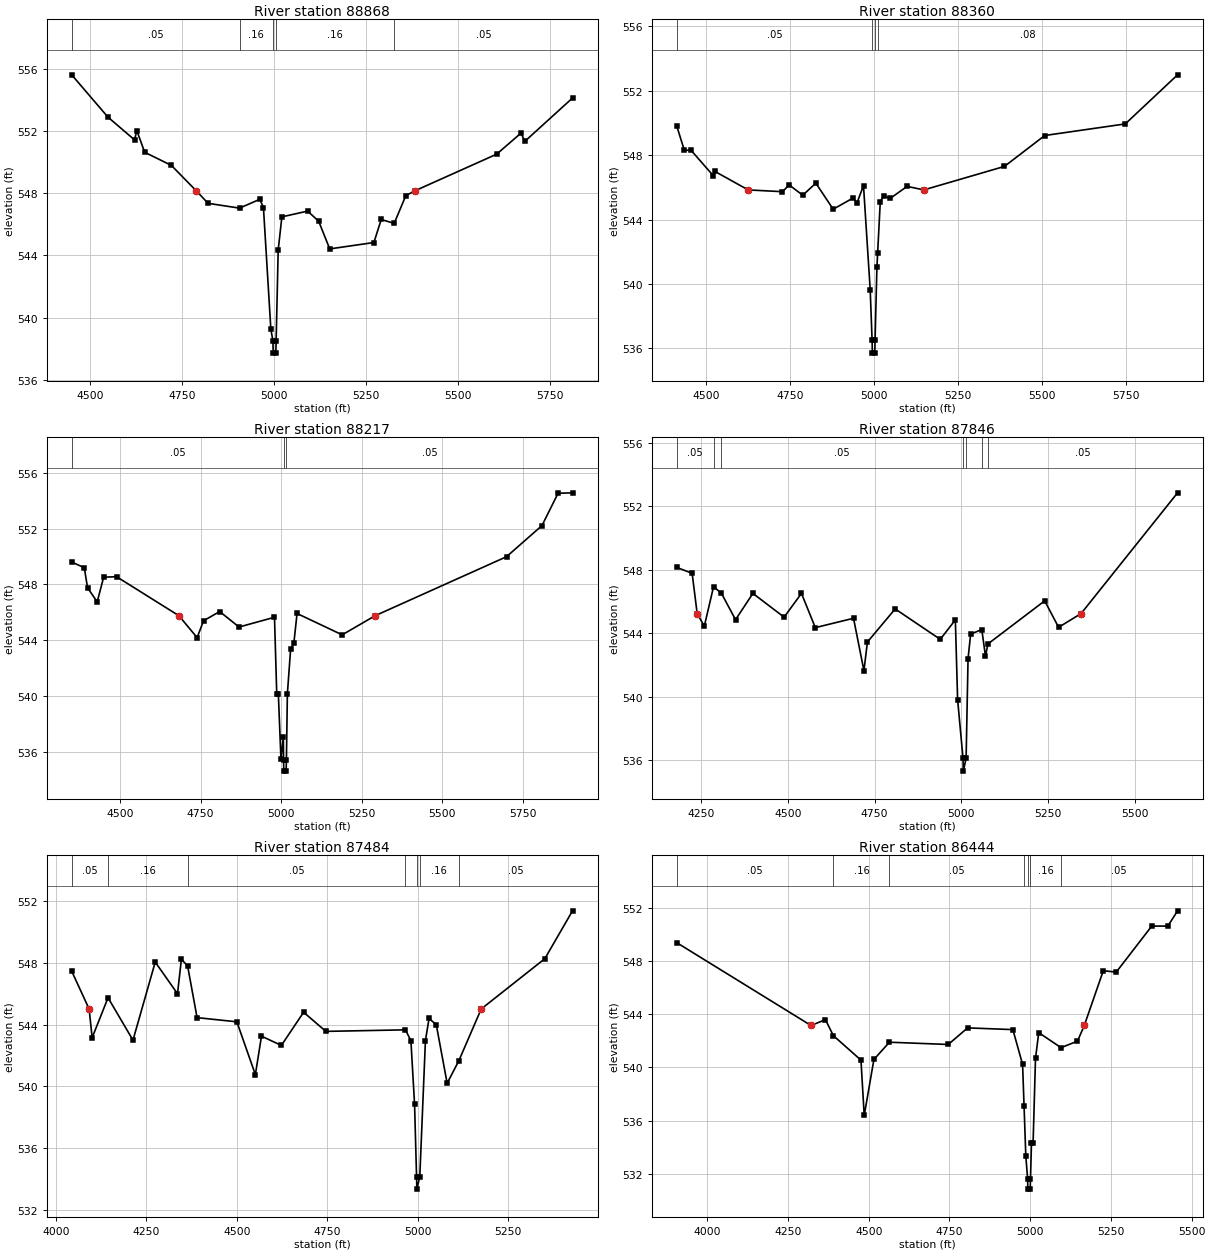
Type RM Length L Ch R = 1,88868,508,508,508
BEGIN DESCRIPTION:
Mapping XS 75e72014
END DESCRIPTION:
XS GIS Cut Line= 3
      2794624.01      7099584.38      2794211.67      7099276.21
      2793365.35      7099241.49
#Sta/Elev= 30
  4449.3  555.61  4547.9  552.89  4620.1  551.43  4626.4  552.02  4647.8  550.63
  4720.2  549.79  4787.8  548.16  4820.2  547.35  4905.6  547.04  4960.9  547.61
  4970.7  547.07  4990.8  539.27  4996.4  538.52  4997.2  537.72  5004.4  537.72
  5005.2  538.52  5010.8  544.35  5020.8  546.48  5090.8  546.85  5120.9  546.20
  5150.9  544.42  5271.0  544.83  5291.0  546.31  5326.2  546.06  5357.8  547.84
  5383.0  548.16  5604.9  550.51  5671.3  551.87  5681.3  551.33  5811.1  554.12
#Mann=5,-1,0
  4449.3    0.05       0  4905.6    0.16       0  4996.4    0.07       0
  5005.2    0.16       0  5326.2    0.05       0
Bank Sta=4787.8,5383
Exp/Cntr=0.3,0.1

Type RM Length L Ch R = 1,88360,143,143,143
BEGIN DESCRIPTION:
Mapping XS d64ee1c3
END DESCRIPTION:
XS GIS Cut Line= 4
      2794997.22      7098994.09      2794498.13      7098928.99
      2794324.52      7098928.99      2793509.25      7098928.99
#Sta/Elev= 30
  4411.8  549.81  4434.2  548.31  4454.4  548.30  4520.3  546.73  4525.4  546.99
  4624.6  545.84  4726.7  545.73  4746.8  546.15  4787.2  545.51  4826.2  546.26
  4877.9  544.64  4938.2  545.35  4948.2  545.00  4968.2  546.11  4988.2  539.63
  4993.8  536.50  4994.6  535.70  5001.8  535.70  5002.6  536.50  5008.2  541.05
  5010.3  541.90  5018.2  545.12  5028.2  545.46  5048.2  545.32  5098.2  546.06
  5147.9  545.84  5388.2  547.30  5508.2  549.22  5748.2  549.94  5904.0  552.99
#Mann=4,-1,0
  4411.8    0.05       0  4993.8    0.04       0  5002.6    0.05       0
  5010.3    0.08       0
Bank Sta=4624.6,5147.9
Exp/Cntr=0.3,0.1

Type RM Length L Ch R = 1,88217,371,371,371
BEGIN DESCRIPTION:
Mapping XS 0ed01aa5
END DESCRIPTION:
XS GIS Cut Line= 3
      2795084.08      7098807.46      2794446.05      7098790.10
      2793530.22      7098785.76
#Sta/Elev= 30
  4350.2  549.61  4389.3  549.20  4399.3  547.77  4429.3  546.75  4449.3  548.52
  4489.3  548.56  4682.9  545.76  4739.4  544.19  4759.4  545.40  4809.4  546.06
  4869.5  544.95  4979.5  545.65  4986.5  540.14  4991.5  540.14  4999.5  535.49
  5007.0  537.09  5007.6  535.42  5008.4  534.62  5015.6  534.62  5016.5  535.42
  5019.5  540.17  5029.5  543.35  5039.5  543.78  5049.5  545.92  5189.5  544.39
  5291.7  545.76  5699.5  549.99  5809.5  552.22  5859.5  554.54  5904.3  554.57
#Mann=3,-1,0
  4350.2    0.05       0  5007.6    0.03       0  5016.5    0.05       0
Bank Sta=4682.9,5291.7
Exp/Cntr=0.3,0.1

Type RM Length L Ch R = 1,87846,362,362,362
BEGIN DESCRIPTION:
Mapping XS 5cf285d9
END DESCRIPTION:
XS GIS Cut Line= 3
      2795114.44      7098460.24      2794311.50      7098455.90
      2793673.44      7098512.33
#Sta/Elev= 30
  4179.7  548.15  4224.0  547.78  4238.5  545.24  4259.1  544.44  4285.7  546.93
  4308.1  546.53  4349.1  544.85  4399.1  546.51  4489.1  545.01  4539.1  546.51
  4579.1  544.35  4689.2  544.94  4719.2  541.63  4729.2  543.44  4809.2  545.53
  4939.2  543.61  4982.7  544.84  4989.2  539.81  5004.8  536.09  5005.6  535.29
  5013.7  536.09  5019.3  542.40  5026.8  543.94  5058.9  544.23  5069.5  542.55
  5076.6  543.32  5240.2  546.04  5280.3  544.37  5345.2  545.24  5623.2  552.86
#Mann=7,-1,0
  4179.7    0.05       0  4285.7    0.16       0  4308.1    0.05       0
  5004.8    0.03       0  5013.7    0.05       0  5058.9    0.16       0
  5076.6    0.05       0
Bank Sta=4238.5,5345.2
Exp/Cntr=0.3,0.1

Type RM Length L Ch R = 1,87484,1040,1040,1040
BEGIN DESCRIPTION:
Mapping XS f8ebf9d9
END DESCRIPTION:
XS GIS Cut Line= 3
      2795110.11      7098325.69      2794224.69      7098126.04
      2793748.62      7098134.69
#Sta/Elev= 30
  4043.5  547.46  4091.6  545.01  4100.0  543.15  4143.9  545.74  4212.8  542.99
  4274.3  548.05  4335.8  546.00  4346.6  548.23  4363.8  547.80  4389.9  544.45
  4499.8  544.18  4551.0  540.76  4567.9  543.25  4622.8  542.65  4684.3  544.80
  4745.8  543.56  4965.8  543.66  4980.8  542.95  4990.9  538.83  4996.4  534.14
  4997.2  533.34  5005.3  534.14  5020.9  542.96  5030.9  544.40  5050.9  543.99
  5080.9  540.20  5113.1  541.65  5175.0  545.01  5350.9  548.27  5427.3  551.37
#Mann=7,-1,0
  4043.5    0.05       0  4143.9    0.16       0  4363.8    0.05       0
  4965.8    0.16       0  4996.4    0.07       0  5005.3    0.16       0
  5113.1    0.05       0
Bank Sta=4091.6,5175
Exp/Cntr=0.3,0.1

Type RM Length L Ch R = 1,86444,550,550,550
BEGIN DESCRIPTION:
BIG CREEK 66.0
END DESCRIPTION:
XS GIS Cut Line= 3
      2795424.96      7097675.00      2794325.00      7097625.00
      2793874.99      7097625.00
#Sta/Elev= 30
  3905.3  549.40  4321.1  543.16  4365.7  543.60  4390.5  542.39  4475.8  540.55
  4485.9  536.38  4515.9  540.60  4563.9  541.90  4746.1  541.73  4806.2  542.98
  4946.3  542.85  4976.4  540.23  4980.9  537.12  4986.4  533.32  4991.9  531.63
  4992.7  530.83  5000.0  530.83  5000.9  531.63  5003.9  534.29  5008.9  534.29
  5016.4  540.68  5026.4  542.62  5095.5  541.49  5146.4  541.98  5167.5  543.16
  5226.4  547.29  5266.4  547.18  5376.4  550.65  5426.4  550.65  5456.4  551.80
#Mann=7,-1,0
  3905.3    0.05       0  4390.5    0.16       0  4563.9    0.05       0
  4980.9    0.16       0  4991.9    0.07       0  5000.9    0.16       0
  5095.5    0.05       0
Bank Sta=4321.1,5167.5
Exp/Cntr=0.3,0.1

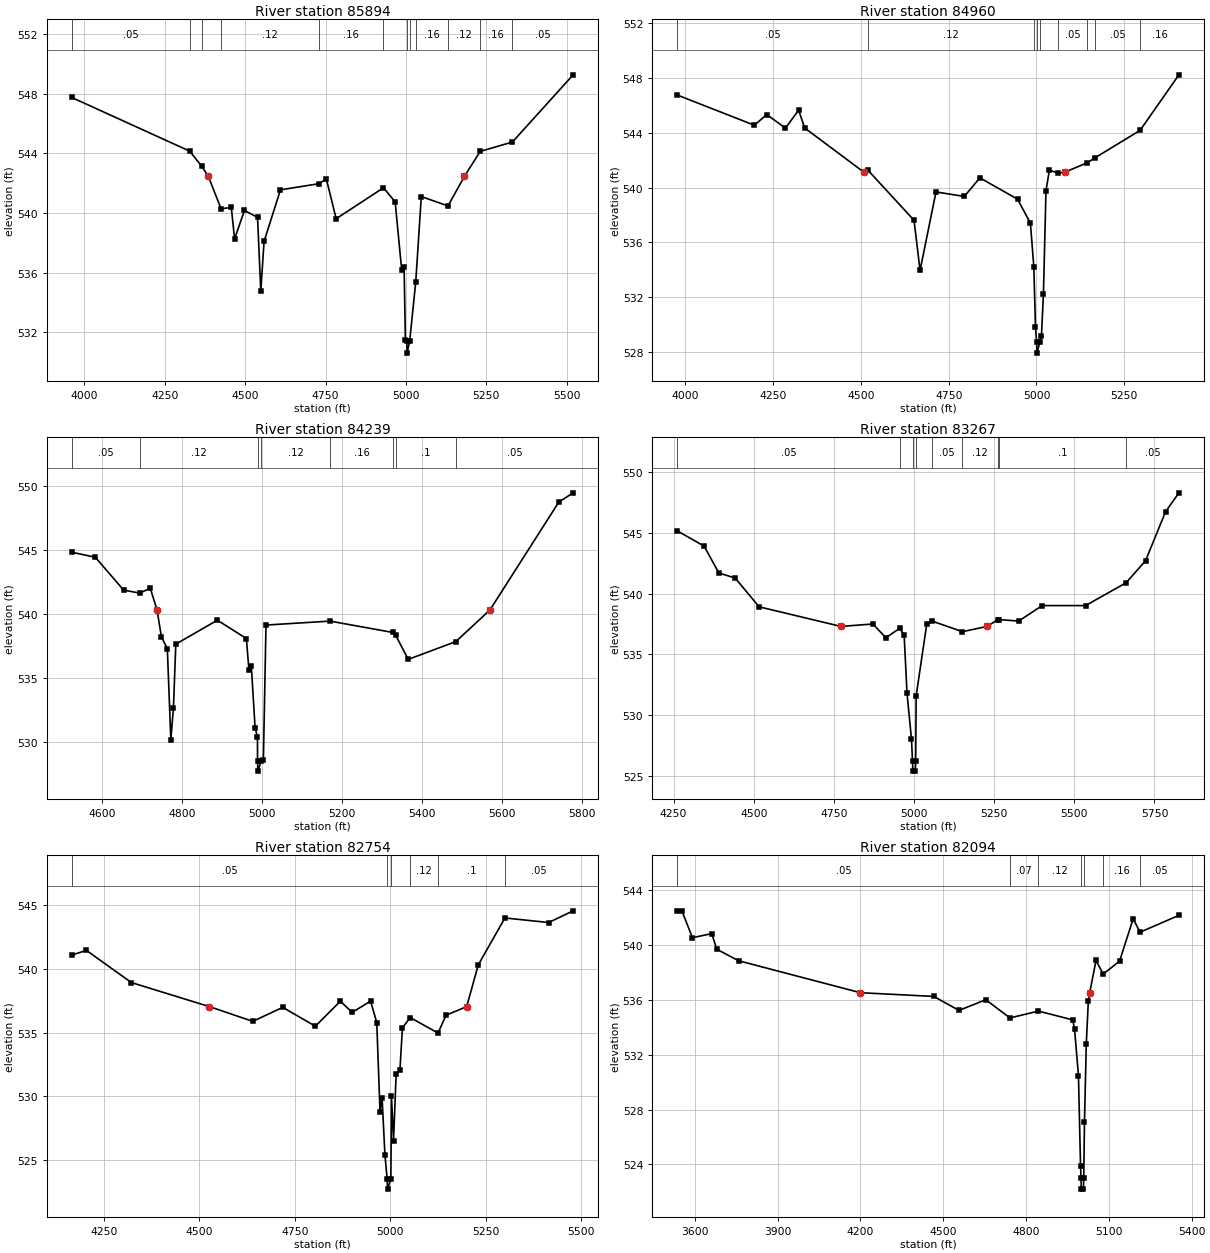
Type RM Length L Ch R = 1,85894,934,934,934
BEGIN DESCRIPTION:
BIG CREEK 65.0
END DESCRIPTION:
XS GIS Cut Line= 3
      2795492.06      7097479.34      2794472.18      7097279.39
      2793959.97      7097188.54
#Sta/Elev= 30
  3960.7  547.75  4327.3  544.15  4365.1  543.13  4385.6  542.45  4425.2  540.28
  4457.0  540.37  4467.2  538.25  4497.8  540.17  4538.6  539.70  4548.7  534.74
  4558.9  538.09  4609.9  541.55  4729.3  541.96  4752.6  542.28  4783.1  539.61
  4930.3  541.69  4966.6  540.74  4986.9  536.17  4994.4  536.39  4998.4  531.47
  5002.8  531.39  5003.6  530.59  5011.8  531.39  5030.7  535.39  5047.9  541.10
  5130.9  540.47  5181.9  542.45  5231.1  544.13  5331.3  544.76  5520.2  549.27
#Mann=12,-1,0
  3960.7    0.05       0  4327.3    0.12       0  4365.1    0.05       0
  4425.2    0.12       0  4729.3    0.16       0  4930.3    0.12       0
  5002.8    0.07       0  5011.8    0.12       0  5030.7    0.16       0
  5130.9    0.12       0  5231.1    0.16       0  5331.3    0.05       0
Bank Sta=4385.6,5181.9
Exp/Cntr=0.3,0.1

Type RM Length L Ch R = 1,84960,721,721,721
BEGIN DESCRIPTION:
BIG CREEK 64.0
END DESCRIPTION:
XS GIS Cut Line= 3
      2795432.67      7097238.14      2794455.88      7096772.22
      2794125.00      7096875.00
#Sta/Elev= 30
  3977.2  546.76  4196.2  544.56  4231.7  545.34  4284.8  544.35  4322.5  545.66
  4339.6  544.36  4507.4  541.15  4518.7  541.31  4651.2  537.62  4668.4  533.96
  4713.8  539.69  4794.5  539.36  4838.8  540.72  4946.2  539.16  4982.8  537.41
  4992.6  534.21  4997.2  529.83  5000.5  528.72  5001.3  527.92  5009.6  528.72
  5014.3  529.19  5019.9  532.24  5027.2  539.78  5037.0  541.29  5061.6  541.05
  5082.4  541.15  5145.1  541.82  5166.1  542.17  5295.2  544.18  5405.9  548.24
#Mann=9,-1,0
  3977.2    0.05       0  4518.7    0.12       0  4992.6    0.16       0
  5000.5    0.07       0  5009.6    0.16       0  5061.6    0.05       0
  5145.1    0.16       0  5166.1    0.05       0  5295.2    0.16       0
Bank Sta=4507.4,5082.4
Exp/Cntr=0.3,0.1

Type RM Length L Ch R = 1,84239,972,972,972
BEGIN DESCRIPTION:
BIG CREEK 63.0
END DESCRIPTION:
XS GIS Cut Line= 3
      2795074.98      7096924.97      2794825.00      7096525.00
      2794224.99      7096024.99
#Sta/Elev= 30
  4525.0  544.80  4583.9  544.41  4654.7  541.84  4694.5  541.61  4721.3  541.98
  4738.1  540.29  4749.0  538.20  4763.8  537.27  4772.6  530.17  4779.1  532.64
  4785.0  537.62  4888.8  539.49  4961.3  538.06  4967.8  535.57  4973.7  535.90
  4983.1  531.06  4989.0  530.38  4989.2  528.50  4990.0  527.70  4998.3  528.50
  5003.8  528.58  5010.3  539.11  5170.2  539.42  5327.5  538.53  5334.0  538.33
  5365.7  536.43  5484.7  537.82  5569.8  540.29  5741.9  548.72  5777.7  549.44
#Mann=8,-1,0
  4525.0    0.05       0  4694.5    0.12       0  4989.2    0.07       0
  4998.3    0.12       0  5170.2    0.16       0  5327.5    0.05       0
  5334.0     0.1       0  5484.7    0.05       0
Bank Sta=4738.1,5569.8
Exp/Cntr=0.3,0.1

Type RM Length L Ch R = 1,83267,513,513,513
BEGIN DESCRIPTION:
BIG CREEK 62.0
END DESCRIPTION:
XS GIS Cut Line= 3
      2795425.01      7096775.02      2795112.29      7096098.08
      2794324.97      7095874.99
#Sta/Elev= 30
  4262.2  545.13  4345.3  543.89  4391.1  541.69  4442.5  541.26  4516.8  538.91
  4772.0  537.30  4871.9  537.50  4912.1  536.37  4955.7  537.15  4969.2  536.57
  4978.2  531.80  4992.1  528.05  4995.4  526.23  4996.4  525.43  5004.2  525.43
  5005.1  526.23  5006.8  531.63  5039.5  537.46  5056.1  537.74  5151.2  536.87
  5227.6  537.30  5262.2  537.86  5264.8  537.86  5326.5  537.74  5399.6  539.01
  5535.1  539.01  5661.4  540.88  5722.2  542.69  5784.6  546.71  5826.2  548.26
#Mann=9,-1,0
  4262.2    0.05       0  4955.7    0.12       0  4995.4    0.07       0
  5005.1    0.12       0  5056.1    0.05       0  5151.2    0.12       0
  5262.2    0.05       0  5264.8     0.1       0  5661.4    0.05       0
Bank Sta=4772,5227.6
Exp/Cntr=0.3,0.1

Type RM Length L Ch R = 1,82754,660,660,660
BEGIN DESCRIPTION:
BIG CREEK 61.0
END DESCRIPTION:
XS GIS Cut Line= 3
      2795630.81      7096620.89      2795325.00      7095825.00
      2794975.00      7095525.00
#Sta/Elev= 30
  4165.3  541.10  4203.7  541.47  4321.6  538.94  4525.9  537.05  4639.6  535.89
  4718.0  536.99  4803.6  535.51  4868.9  537.47  4900.1  536.60  4948.3  537.48
  4964.4  535.79  4972.9  528.79  4978.3  529.88  4985.8  525.40  4991.6  523.50
  4992.6  522.70  5001.3  523.50  5002.9  530.01  5008.3  526.51  5015.2  531.76
  5025.1  532.07  5031.6  535.38  5052.1  536.19  5124.9  534.97  5145.8  536.37
  5200.0  537.05  5230.3  540.33  5300.2  544.02  5414.7  543.66  5478.9  544.58
#Mann=6,-1,0
  4165.3    0.05       0  4991.6    0.03       0  5001.3    0.05       0
  5052.1    0.12       0  5124.9     0.1       0  5300.2    0.05       0
Bank Sta=4525.9,5200
Exp/Cntr=0.3,0.1

Type RM Length L Ch R = 1,82094,908,908,908
BEGIN DESCRIPTION:
Mapping XS b3b457f6
END DESCRIPTION:
XS GIS Cut Line= 3
      2796086.57      7097000.66      2795661.33      7095647.74
      2795397.37      7095349.17
#Sta/Elev= 30
  3537.2  542.49  3553.6  542.47  3591.4  540.53  3661.4  540.83  3679.4  539.69
  3758.6  538.85  4200.1  536.52  4465.6  536.25  4557.1  535.23  4654.3  536.01
  4741.8  534.68  4845.1  535.18  4969.1  534.54  4975.8  533.88  4990.0  530.48
  4997.5  523.89  4999.4  523.00  5000.3  522.20  5008.1  522.20  5009.1  523.00
  5011.8  527.07  5018.4  532.80  5025.8  535.92  5030.8  536.52  5053.6  538.87
  5079.7  537.88  5138.9  538.82  5188.2  541.91  5213.1  540.93  5353.9  542.16
#Mann=7,-1,0
  3537.2    0.05       0  4741.8    0.07       0  4845.1    0.12       0
  4999.4    0.07       0  5009.1    0.12       0  5079.7    0.16       0
  5213.1    0.05       0
Bank Sta=4200.1,5030.8
Exp/Cntr=0.3,0.1

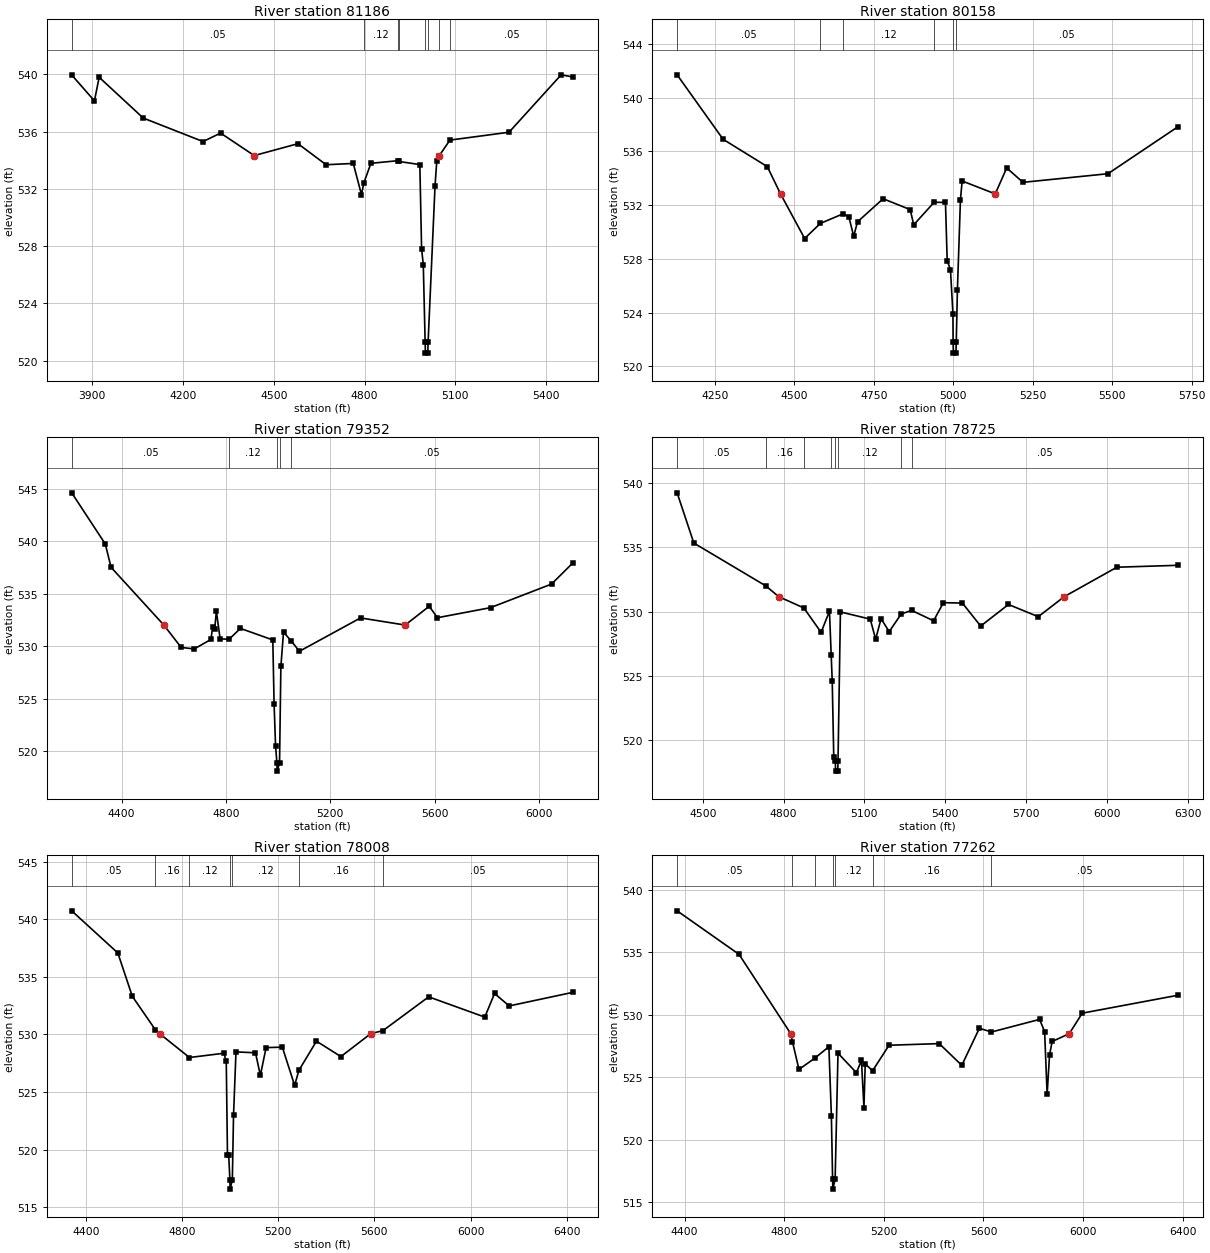
Type RM Length L Ch R = 1,81186,1028,1028,1028
BEGIN DESCRIPTION:
Mapping XS 4ce0e33d
END DESCRIPTION:
XS GIS Cut Line= 3
      2796716.00      7096498.41      2796134.42      7095517.53
      2795674.31      7095283.14
#Sta/Elev= 30
  3832.0  539.95  3907.1  538.14  3922.7  539.79  4068.5  536.94  4266.1  535.30
  4324.2  535.89  4435.4  534.32  4580.0  535.15  4673.0  533.68  4762.8  533.77
  4790.0  531.59  4797.9  532.42  4821.2  533.78  4909.7  533.96  4913.2  533.91
  4982.9  533.69  4988.7  527.81  4994.3  526.71  5000.4  521.32  5001.4  520.52
  5009.3  520.52  5010.3  521.32  5033.2  532.22  5039.0  533.96  5045.4  534.23
  5047.4  534.32  5082.4  535.40  5277.8  535.95  5450.1  539.96  5488.7  539.81
#Mann=8,-1,0
  3832.0    0.05       0  4797.9    0.12       0  4909.7    0.16       0
  4913.2    0.07       0  5000.4    0.07       0  5010.3    0.07       0
  5045.4    0.16       0  5082.4    0.05       0
Bank Sta=4435.4,5047.4
Exp/Cntr=0.3,0.1

Type RM Length L Ch R = 1,80158,806,806,806
BEGIN DESCRIPTION:
Mapping XS 26c2677e
END DESCRIPTION:
XS GIS Cut Line= 4
      2797215.11      7095712.82      2796581.47      7095343.92
      2796429.56      7095278.82      2795769.89      7095122.58
#Sta/Elev= 30
  4131.4  541.70  4276.2  536.90  4415.1  534.87  4456.7  532.84  4532.6  529.52
  4581.8  530.64  4653.8  531.36  4671.6  531.14  4686.9  529.69  4698.9  530.76
  4779.5  532.48  4864.6  531.67  4875.8  530.54  4940.1  532.22  4975.6  532.20
  4981.0  527.86  4991.3  527.21  4999.1  523.90  4999.6  521.79  5000.6  520.99
  5008.6  520.99  5009.5  521.79  5013.1  525.66  5022.7  532.42  5028.1  533.80
  5132.2  532.84  5168.2  534.77  5219.5  533.70  5486.7  534.34  5707.8  537.85
#Mann=6,-1,0
  4131.4    0.05       0  4581.8     0.1       0  4653.8    0.12       0
  4940.1    0.05       0  4999.6    0.03       0  5009.5    0.05       0
Bank Sta=4456.7,5132.2
Exp/Cntr=0.3,0.1

Type RM Length L Ch R = 1,79352,627,627,627
BEGIN DESCRIPTION:
Mapping XS 8ade61d0
END DESCRIPTION:
XS GIS Cut Line= 3
      2797471.25      7095430.75      2796889.63      7094931.59
      2795754.90      7094719.68
#Sta/Elev= 30
  4209.1  544.62  4337.8  539.74  4359.8  537.52  4562.2  532.01  4628.6  529.88
  4678.6  529.73  4742.8  530.64  4749.4  531.86  4757.0  531.61  4763.6  533.32
  4777.9  530.70  4812.0  530.65  4855.8  531.69  4979.9  530.59  4984.8  524.51
  4990.4  520.49  4995.6  518.88  4996.5  518.08  5005.7  518.88  5010.8  528.06
  5021.0  531.34  5049.8  530.51  5082.0  529.51  5316.1  532.69  5487.4  532.01
  5579.4  533.80  5611.0  532.71  5814.4  533.67  6048.4  535.92  6129.9  537.93
#Mann=5,-1,0
  4209.1    0.05       0  4812.0    0.12       0  4995.6    0.07       0
  5005.7    0.12       0  5049.8    0.05       0
Bank Sta=4562.2,5487.4
Exp/Cntr=0.3,0.1

Type RM Length L Ch R = 1,78725,717,717,717
BEGIN DESCRIPTION:
Mapping XS 18e7dcb5
END DESCRIPTION:
XS GIS Cut Line= 3
      2797833.21      7094754.51      2797268.97      7094611.28
      2795998.64      7094468.21
#Sta/Elev= 30
  4404.6  539.24  4466.7  535.33  4733.7  532.00  4781.7  531.16  4875.1  530.28
  4939.2  528.38  4970.2  530.03  4976.7  526.59  4980.5  524.58  4986.2  518.65
  4991.9  518.38  4992.9  517.58  5001.1  517.58  5002.0  518.38  5010.9  529.97
  5121.6  529.41  5141.7  527.85  5161.8  529.44  5192.0  528.44  5236.6  529.81
  5275.2  530.09  5356.8  529.28  5393.3  530.69  5463.7  530.66  5531.7  528.87
  5634.8  530.55  5745.5  529.60  5842.0  531.16  6037.3  533.45  6265.1  533.60
#Mann=8,-1,0
  4404.6    0.05       0  4733.7    0.16       0  4875.1    0.05       0
  4976.7    0.12       0  4991.9    0.07       0  5002.0    0.12       0
  5236.6    0.16       0  5275.2    0.05       0
Bank Sta=4781.7,5842
Exp/Cntr=0.3,0.1

Type RM Length L Ch R = 1,78008,746,746,746
BEGIN DESCRIPTION:
Mapping XS f5553853
END DESCRIPTION:
XS GIS Cut Line= 3
      2797976.41      7094190.27      2797329.73      7094142.53
      2795914.10      7094390.96
#Sta/Elev= 30
  4340.2  540.73  4532.1  537.07  4592.3  533.31  4688.0  530.41  4705.7  530.07
  4830.2  527.99  4973.3  528.36  4983.4  527.67  4988.5  519.51  4993.6  519.51
  4998.5  517.36  4999.4  516.56  5008.7  517.36  5013.7  522.98  5023.9  528.48
  5105.1  528.40  5125.4  526.44  5149.2  528.85  5216.8  528.89  5268.0  525.57
  5285.6  526.87  5358.9  529.41  5460.5  528.07  5585.2  530.07  5635.3  530.32
  5826.0  533.26  6059.5  531.50  6100.1  533.55  6161.0  532.47  6425.9  533.65
#Mann=7,-1,0
  4340.2    0.05       0  4688.0    0.16       0  4830.2    0.12       0
  4998.5    0.07       0  5008.7    0.12       0  5285.6    0.16       0
  5635.3    0.05       0
Bank Sta=4705.7,5585.2
Exp/Cntr=0.3,0.1

Type RM Length L Ch R = 1,77262,938,938,938
BEGIN DESCRIPTION:
Mapping XS 5f10af8f
END DESCRIPTION:
XS GIS Cut Line= 3
      2797963.37      7093621.70      2797316.71      7093586.98
      2795962.51      7093751.91
#Sta/Elev= 30
  4370.0  538.33  4618.7  534.84  4826.0  528.49  4833.2  527.84  4859.1  525.62
  4923.1  526.53  4979.3  527.44  4989.3  521.90  4994.2  516.83  4995.1  516.03
  5004.4  516.83  5015.9  526.92  5089.8  525.36  5110.0  526.34  5120.1  522.56
  5125.2  526.07  5154.6  525.51  5220.8  527.56  5422.3  527.69  5512.9  525.95
  5583.5  528.92  5632.1  528.62  5825.2  529.63  5845.4  528.66  5855.5  523.62
  5865.1  526.76  5875.6  527.86  5944.5  528.49  5996.5  530.13  6381.8  531.57
#Mann=7,-1,0
  4370.0    0.05       0  4833.2    0.16       0  4923.1    0.12       0
  4994.2    0.07       0  5004.4    0.12       0  5154.6    0.16       0
  5632.1    0.05       0
Bank Sta=4826,5944.5
Exp/Cntr=0.3,0.1

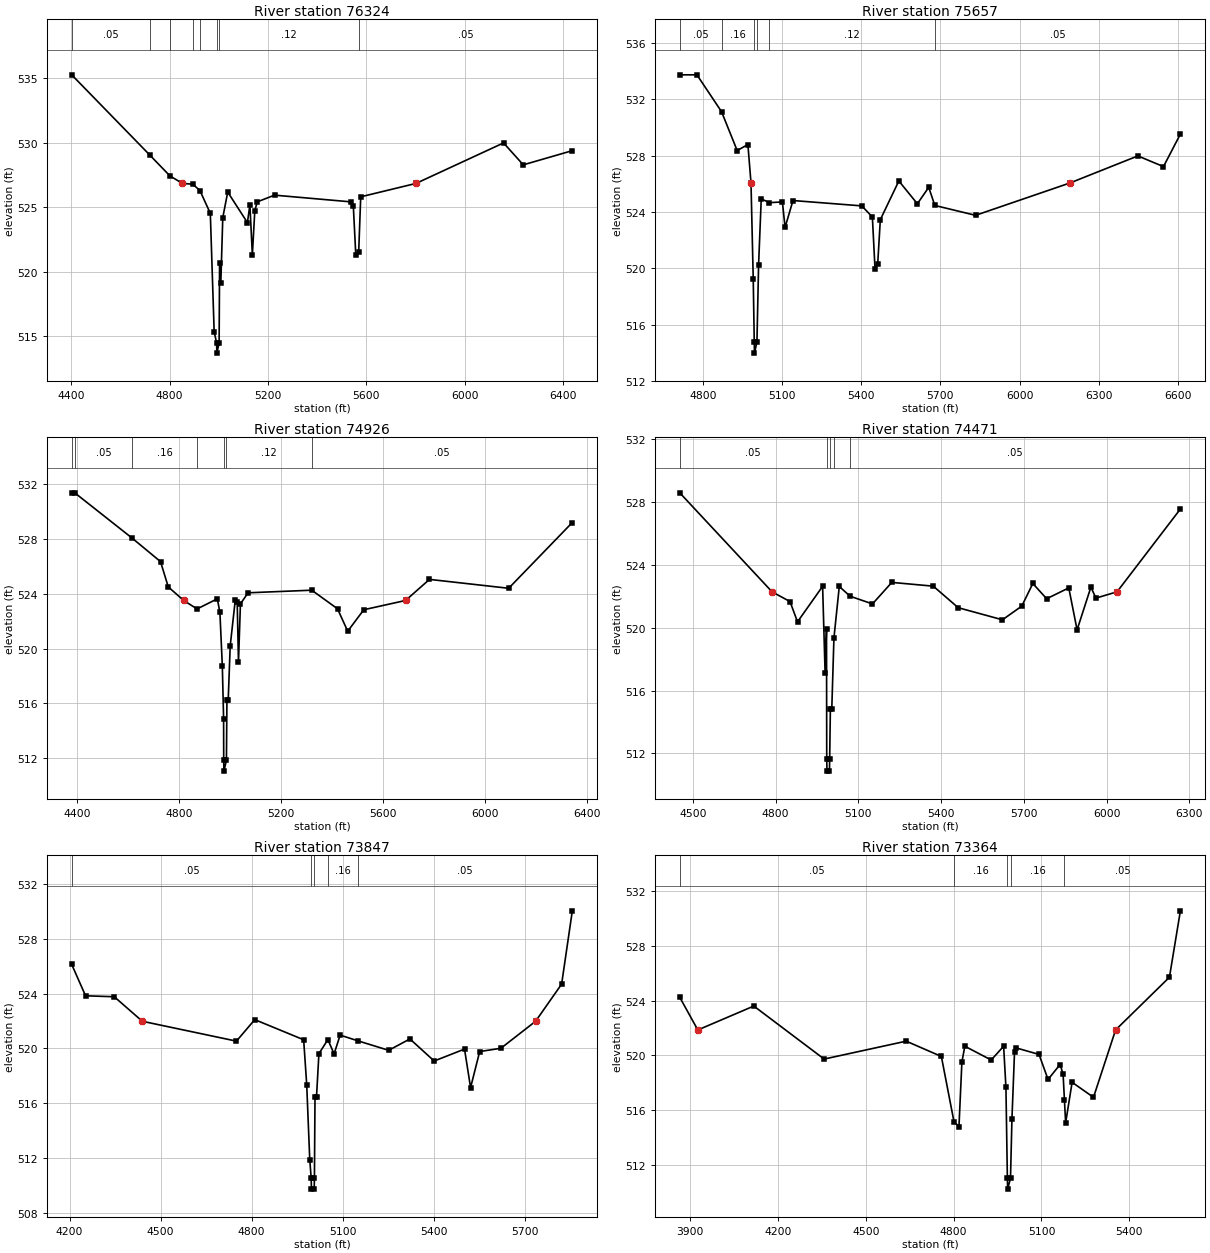
Type RM Length L Ch R = 1,76324,667,667,667
BEGIN DESCRIPTION:
Mapping XS f7d19d8f
END DESCRIPTION:
XS GIS Cut Line= 3
      2797889.60      7093200.68      2797325.39      7093048.78
      2795875.75      7093139.93
#Sta/Elev= 30
  4401.8  535.27  4719.0  529.06  4801.5  527.43  4852.5  526.85  4894.2  526.79
  4923.4  526.30  4965.8  524.53  4981.4  515.34  4991.4  514.49  4992.4  513.69
  5001.6  514.49  5003.5  520.68  5008.5  519.16  5016.5  524.20  5036.6  526.18
  5116.7  523.81  5126.8  525.19  5136.8  521.31  5146.8  524.74  5156.8  525.42
  5227.0  525.94  5537.6  525.42  5547.6  525.09  5557.6  521.31  5569.5  521.57
  5577.7  525.81  5802.6  526.85  6158.8  529.99  6239.0  528.29  6438.6  529.39
#Mann=8,-1,0
  4401.8    0.05       0  4719.0    0.16       0  4801.5    0.05       0
  4894.2    0.16       0  4923.4    0.12       0  4991.4    0.07       0
  5001.6    0.12       0  5569.5    0.05       0
Bank Sta=4852.5,5802.6
Exp/Cntr=0.3,0.1

Type RM Length L Ch R = 1,75657,731,731,731
BEGIN DESCRIPTION:
Mapping XS 1e893c90
END DESCRIPTION:
XS GIS Cut Line= 3
      2797729.06      7092692.88      2797442.58      7092640.79
      2795841.06      7092762.32
#Sta/Elev= 30
  4712.2  533.74  4777.3  533.74  4870.6  531.12  4929.8  528.36  4970.4  528.79
  4982.2  526.06  4990.7  519.21  4994.5  514.77  4995.4  513.97  5004.7  514.77
  5011.0  520.26  5021.0  524.93  5051.8  524.66  5101.2  524.71  5111.3  522.90
  5141.3  524.81  5402.1  524.43  5442.2  523.64  5452.2  519.96  5462.3  520.28
  5472.3  523.45  5542.5  526.20  5612.7  524.58  5655.8  525.75  5678.8  524.46
  5833.3  523.76  6191.3  526.06  6448.4  527.98  6545.4  527.22  6609.5  529.53
#Mann=6,-1,0
  4712.2    0.05       0  4870.6    0.16       0  4994.5    0.07       0
  5004.7    0.16       0  5051.8    0.12       0  5678.8    0.05       0
Bank Sta=4982.2,6191.3
Exp/Cntr=0.3,0.1

Type RM Length L Ch R = 1,74926,455,455,455
BEGIN DESCRIPTION:
Mapping XS 430e5c39
END DESCRIPTION:
XS GIS Cut Line= 3
      2797729.06      7092363.02      2797125.74      7092267.53
      2795775.89      7092350.00
#Sta/Elev= 30
  4380.2  531.39  4394.2  531.36  4616.4  528.09  4728.5  526.36  4758.9  524.51
  4819.3  523.52  4871.8  522.90  4951.3  523.64  4961.4  522.64  4970.9  518.74
  4975.9  514.88  4976.3  511.84  4977.2  511.04  4987.0  511.84  4988.9  516.22
  4993.9  516.22  5001.8  520.20  5021.8  523.58  5029.2  523.44  5034.2  519.01
  5041.9  523.27  5071.9  524.08  5321.6  524.27  5422.6  522.91  5462.6  521.27
  5525.6  522.84  5689.6  523.52  5783.2  525.06  6093.8  524.41  6343.4  529.22
#Mann=7,-1,0
  4380.2    0.16       0  4394.2    0.05       0  4616.4    0.16       0
  4871.8    0.12       0  4976.3    0.07       0  4987.0    0.12       0
  5321.6    0.05       0
Bank Sta=4819.3,5689.6
Exp/Cntr=0.3,0.1

Type RM Length L Ch R = 1,74471,624,624,624
BEGIN DESCRIPTION:
Mapping XS 3ad3f8cc
END DESCRIPTION:
XS GIS Cut Line= 3
      2797676.95      7091989.75      2797134.42      7091907.29
      2795871.37      7091989.76
#Sta/Elev= 30
  4452.8  528.58  4787.4  522.28  4852.4  521.66  4879.6  520.37  4970.6  522.63
  4979.6  517.12  4984.7  519.90  4985.5  511.67  4986.4  510.87  4995.4  510.87
  4996.2  511.67  4998.7  514.82  5003.8  514.82  5011.6  519.34  5031.0  522.62
  5070.2  522.00  5151.3  521.51  5221.4  522.88  5371.8  522.64  5462.0  521.27
  5622.3  520.50  5692.4  521.37  5732.5  522.81  5782.6  521.84  5862.8  522.53
  5892.9  519.86  5943.0  522.58  5961.1  521.88  6037.7  522.28  6267.3  527.55
#Mann=5,-1,0
  4452.8    0.05       0  4985.5    0.03       0  4996.2    0.05       0
  5011.6    0.16       0  5070.2    0.05       0
Bank Sta=4787.4,6037.7
Exp/Cntr=0.3,0.1

Type RM Length L Ch R = 1,73847,483,483,483
BEGIN DESCRIPTION:
Mapping XS 09b4c1a4
END DESCRIPTION:
XS GIS Cut Line= 3
      2797694.27      7091655.55      2796895.70      7091560.07
      2796049.66      7091573.08
#Sta/Elev= 30
  4207.0  526.13  4252.7  523.84  4347.3  523.77  4439.8  521.98  4750.1  520.53
  4810.5  522.10  4971.7  520.63  4981.8  517.34  4991.8  511.88  4996.5  510.53
  4997.4  509.73  5006.4  509.73  5007.2  510.53  5009.1  516.48  5014.1  516.48
  5022.0  519.62  5051.6  520.64  5072.0  519.60  5092.0  520.97  5150.8  520.55
  5252.0  519.86  5322.0  520.69  5402.0  519.08  5502.0  519.95  5522.0  517.14
  5552.0  519.77  5622.0  520.01  5736.3  521.98  5822.1  524.69  5857.4  530.04
#Mann=5,-1,0
  4207.0    0.05       0  4996.5    0.03       0  5007.2    0.05       0
  5051.6    0.16       0  5150.8    0.05       0
Bank Sta=4439.8,5736.3
Exp/Cntr=0.3,0.1

Type RM Length L Ch R = 1,73364,370,370,370
BEGIN DESCRIPTION:
Mapping XS bf8b25bc
END DESCRIPTION:
XS GIS Cut Line= 3
      2797737.67      7091282.29      2796635.29      7091330.03
      2796045.02      7091468.92
#Sta/Elev= 30
  3864.7  524.25  3926.4  521.86  4117.6  523.61  4357.8  519.73  4638.1  521.04
  4758.2  519.92  4801.3  515.14  4818.3  514.79  4828.3  519.51  4838.3  520.67
  4928.4  519.66  4970.8  520.67  4978.7  517.65  4983.6  511.01  4984.5  510.21
  4994.3  511.01  4999.2  515.33  5008.0  520.22  5013.1  520.55  5091.7  520.07
  5122.5  518.24  5163.6  519.33  5173.9  518.63  5178.6  516.70  5182.6  515.06
  5204.7  518.03  5277.7  516.93  5353.2  521.86  5537.1  525.72  5574.5  530.58
#Mann=5,-1,0
  3864.7    0.05       0  4801.3    0.16       0  4983.6    0.07       0
  4994.3    0.16       0  5178.6    0.05       0
Bank Sta=3926.4,5353.2
Exp/Cntr=0.3,0.1

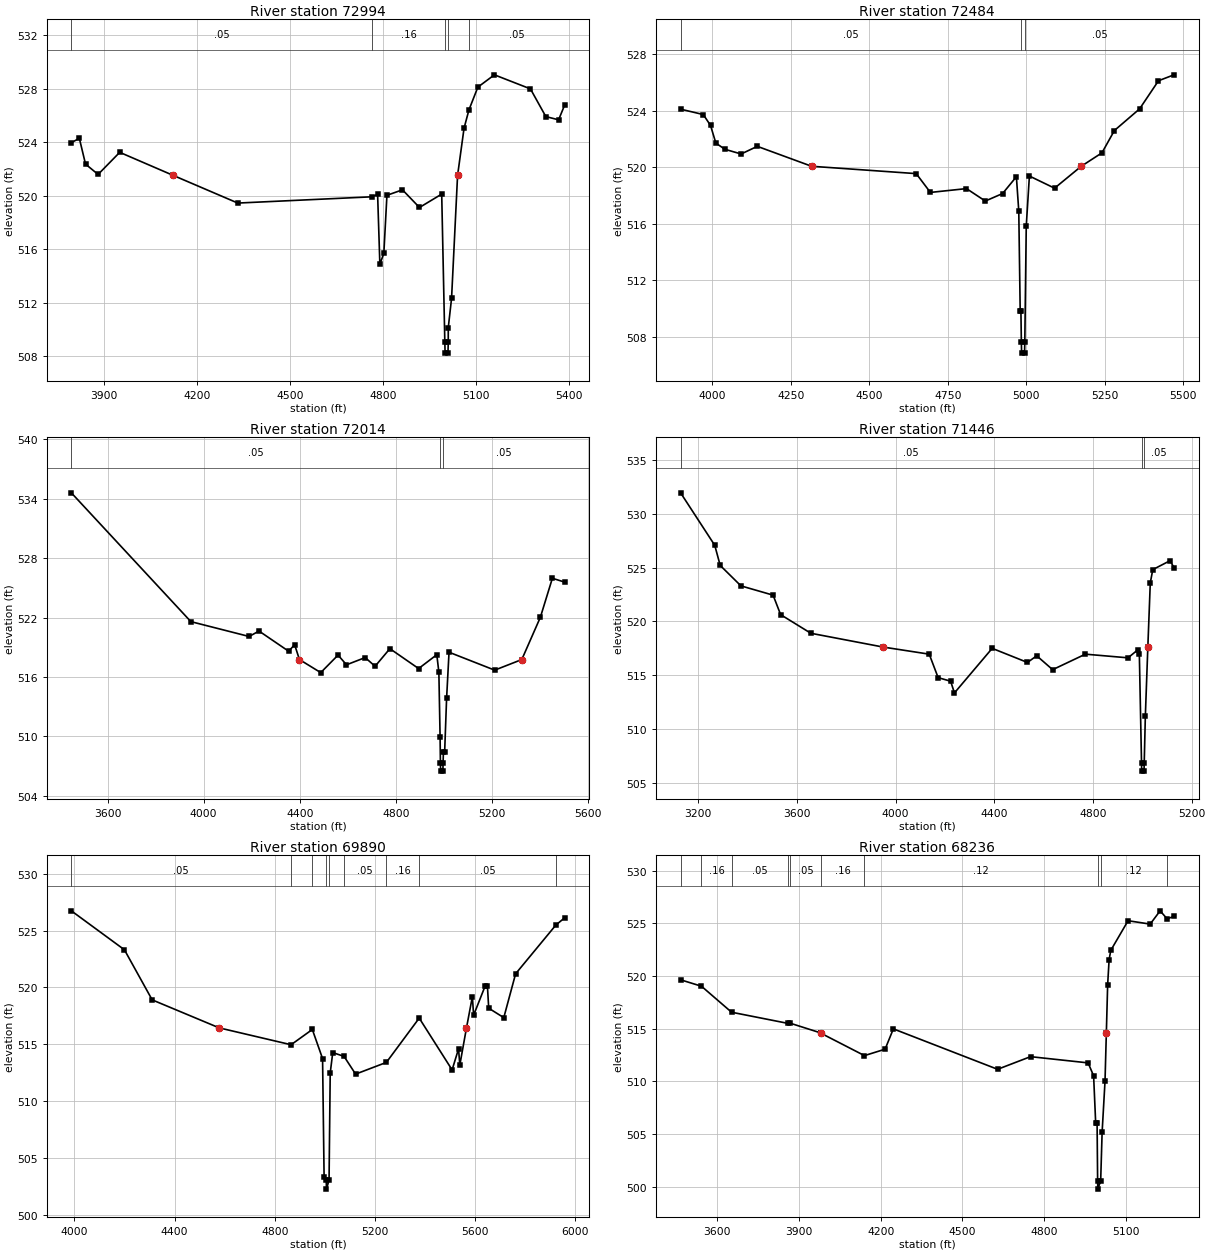
Type RM Length L Ch R = 1,72994,510,510,510
BEGIN DESCRIPTION:
Mapping XS 13e564c6
END DESCRIPTION:
XS GIS Cut Line= 4
      2797750.71      7091256.24      2796674.35      7091173.78
      2796392.23      7091073.95      2796344.49      7090865.63
#Sta/Elev= 30
  3793.6  523.96  3819.4  524.29  3839.4  522.36  3880.0  521.59  3949.8  523.24
  4123.1  521.51  4330.9  519.45  4765.5  519.92  4782.2  520.11  4789.5  514.87
  4802.3  515.70  4812.3  520.03  4862.4  520.44  4917.3  519.12  4989.1  520.12
  4999.2  509.04  5000.0  508.24  5009.4  508.24  5010.2  509.04  5010.3  510.15
  5020.9  512.33  5040.3  521.51  5061.2  525.04  5077.0  526.41  5105.8  528.11
  5159.2  529.03  5275.5  527.98  5325.2  525.91  5366.4  525.67  5386.1  526.78
#Mann=5,-1,0
  3793.6    0.05       0  4765.5    0.16       0  4999.2    0.07       0
  5010.2    0.16       0  5077.0    0.05       0
Bank Sta=4123.1,5040.3
Exp/Cntr=0.3,0.1

Type RM Length L Ch R = 1,72484,470,470,470
BEGIN DESCRIPTION:
Mapping XS dad80b7b
END DESCRIPTION:
XS GIS Cut Line= 3
      2797807.14      7091169.43      2796821.92      7090718.05
      2796335.86      7090683.33
#Sta/Elev= 30
  3898.9  524.12  3971.2  523.74  3994.2  522.97  4011.2  521.72  4040.2  521.28
  4091.7  520.95  4143.2  521.49  4316.2  520.08  4649.2  519.56  4694.3  518.23
  4809.3  518.50  4869.2  517.62  4924.2  518.15  4968.2  519.34  4975.8  516.91
  4980.3  509.86  4982.6  509.86  4984.0  507.66  4984.8  506.86  4994.2  506.86
  4995.0  507.66  4999.6  515.84  5009.6  519.39  5089.8  518.53  5174.7  520.08
  5240.6  521.03  5280.3  522.61  5360.5  524.14  5420.6  526.13  5469.9  526.55
#Mann=3,-1,0
  3898.9    0.05       0  4984.0    0.03       0  4995.0    0.05       0
Bank Sta=4316.2,5174.7
Exp/Cntr=0.3,0.1

Type RM Length L Ch R = 1,72014,568,568,568
BEGIN DESCRIPTION:
BIG CREEK 51.0
END DESCRIPTION:
XS GIS Cut Line= 3
      2798525.01      7090725.00      2797016.54      7090366.00
      2796513.73      7090349.13
#Sta/Elev= 30
  3449.4  534.60  3947.0  521.59  4189.5  520.09  4230.6  520.64  4354.0  518.60
  4378.9  519.26  4398.9  517.76  4487.6  516.44  4559.6  518.21  4594.8  517.23
  4672.6  517.96  4713.8  517.08  4775.4  518.86  4895.0  516.85  4970.7  518.25
  4979.3  516.48  4984.4  509.92  4985.8  507.29  4986.6  506.49  4996.1  506.49
  4996.8  507.29  4998.2  508.38  5003.3  508.38  5011.5  513.84  5021.6  518.50
  5211.7  516.69  5324.5  517.76  5401.8  522.03  5451.8  525.97  5503.1  525.58
#Mann=3,-1,0
  3449.4    0.05       0  4985.8    0.03       0  4996.8    0.05       0
Bank Sta=4398.9,5324.5
Exp/Cntr=0.3,0.1

Type RM Length L Ch R = 1,71446,1556,1556,1556
BEGIN DESCRIPTION:
Mapping XS 28357d05
END DESCRIPTION:
XS GIS Cut Line= 3
      2798622.25      7090328.29      2796882.68      7089974.13
      2796659.38      7089989.71
#Sta/Elev= 30
  3128.9  531.94  3267.3  527.07  3289.4  525.20  3373.5  523.30  3503.7  522.44
  3534.3  520.63  3656.8  518.90  3949.6  517.62  4136.4  516.96  4172.5  514.78
  4223.1  514.45  4238.5  513.36  4391.5  517.50  4534.4  516.19  4572.0  516.81
  4636.5  515.52  4769.1  516.96  4941.9  516.62  4982.0  517.37  4987.8  516.93
  4996.6  506.90  4997.3  506.10  5006.8  506.10  5007.6  506.90  5012.1  511.21
  5022.2  517.62  5032.1  523.57  5042.2  524.81  5112.3  525.64  5128.0  525.00
#Mann=3,-1,0
  3128.9    0.05       0  4996.6    0.03       0  5007.6    0.05       0
Bank Sta=3949.6,5022.2
Exp/Cntr=0.3,0.1

Type RM Length L Ch R = 1,69890,1654,1654,1654
BEGIN DESCRIPTION:
Mapping XS 944c5427
END DESCRIPTION:
XS GIS Cut Line= 3
      2798648.35      7089661.64      2797710.81      7089385.59
      2796731.63      7089218.92
#Sta/Elev= 30
  3987.4  526.73  4199.4  523.31  4310.3  518.91  4578.2  516.45  4865.1  514.97
  4950.0  516.31  4990.9  513.75  4997.0  503.35  5005.6  503.09  5006.4  502.29
  5016.8  503.09  5021.4  512.48  5031.5  514.28  5076.6  513.95  5122.8  512.39
  5245.8  513.42  5376.9  517.31  5508.3  512.76  5534.0  514.61  5539.1  513.19
  5565.7  516.45  5589.2  519.19  5594.2  517.56  5640.1  520.12  5649.4  520.10
  5654.5  518.18  5714.7  517.35  5761.9  521.20  5922.7  525.48  5958.0  526.12
#Mann=9,-1,0
  3987.4    0.05       0  4865.1    0.16       0  4950.0    0.12       0
  5005.6    0.07       0  5016.8    0.12       0  5076.6    0.05       0
  5245.8    0.16       0  5376.9    0.05       0  5922.7    0.12       0
Bank Sta=4578.2,5565.7
Exp/Cntr=0.3,0.1

Type RM Length L Ch R = 1,68236,734,734,734
BEGIN DESCRIPTION:
BIG CREEK 49.0
END DESCRIPTION:
XS GIS Cut Line= 3
      2798540.62      7088896.00      2797025.00      7088725.00
      2796755.92      7088632.11
#Sta/Elev= 30
  3465.8  519.64  3542.4  519.03  3652.9  516.56  3859.9  515.50  3868.8  515.51
  3980.5  514.59  3981.8  514.55  4140.3  512.44  4216.1  513.05  4246.3  514.98
  4628.8  511.14  4749.5  512.34  4960.8  511.75  4981.0  510.52  4988.5  506.08
  4993.7  506.08  4995.7  500.56  4996.4  499.76  5006.9  500.56  5012.2  505.17
  5022.8  509.99  5027.7  514.58  5032.5  519.17  5037.8  521.53  5043.9  522.43
  5107.4  525.25  5188.5  524.93  5225.0  526.19  5250.6  525.43  5275.7  525.66
#Mann=10,-1,0
  3465.8    0.05       0  3542.4    0.16       0  3652.9    0.05       0
  3859.9    0.16       0  3868.8    0.05       0  3981.8    0.16       0
  4140.3    0.12       0  4995.7    0.07       0  5006.9    0.12       0
  5250.6    0.12       0
Bank Sta=3980.5,5027.7
Exp/Cntr=0.3,0.1