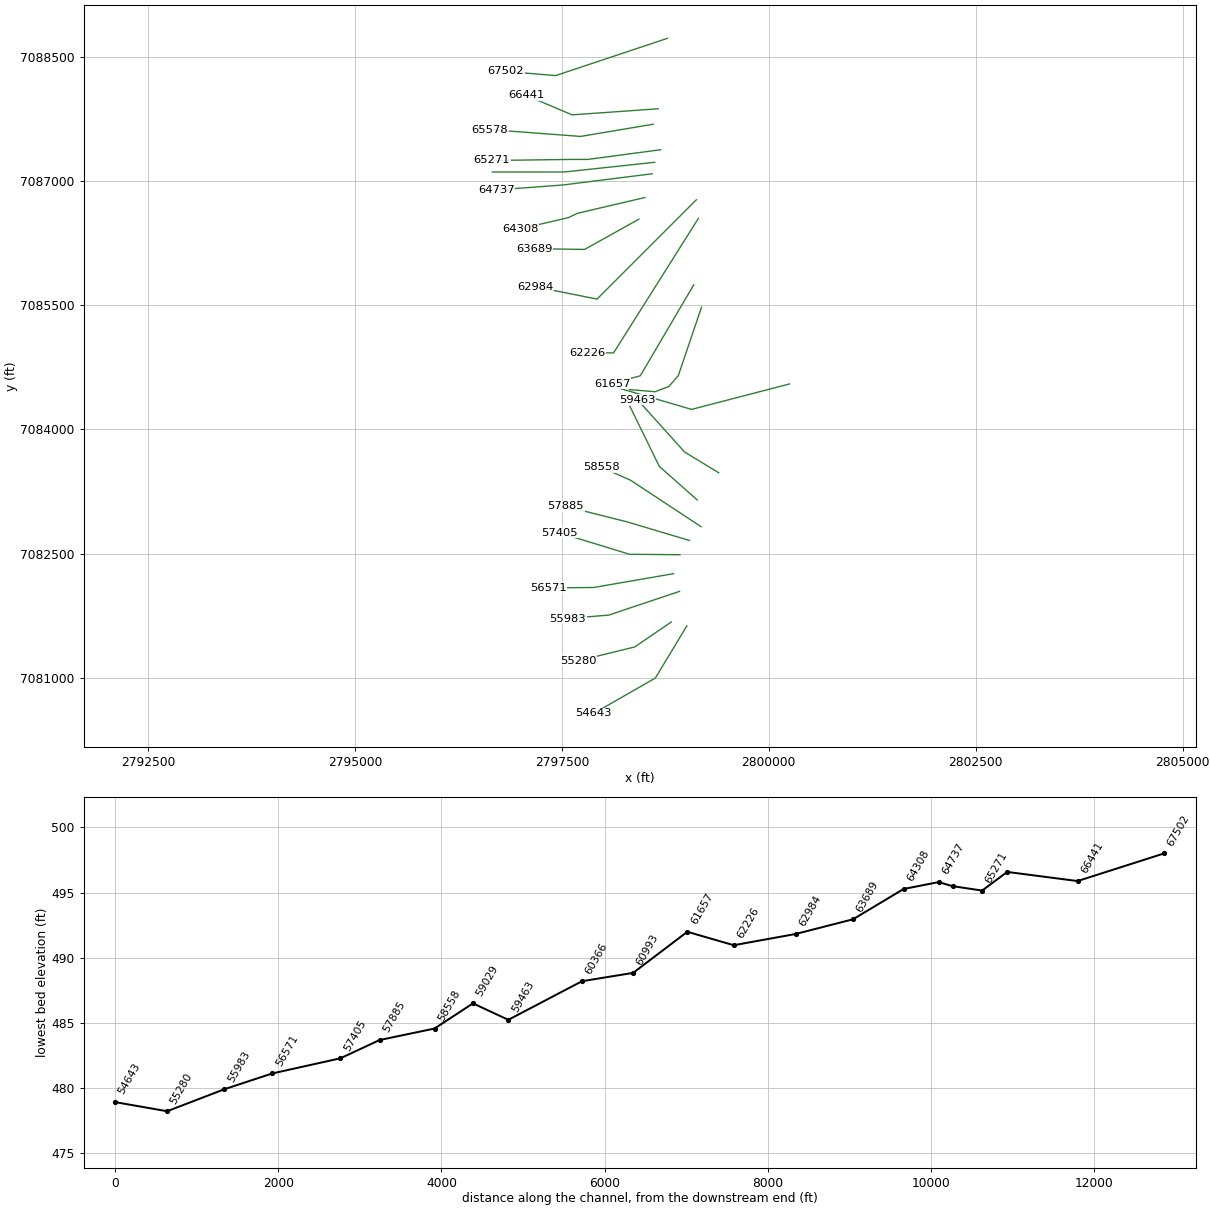
HEC-RAS study BIG CREEK.prj: BIG CREEK Base Level Engineering

--- BIG CREEK.g01 (geometry) --- (continued)

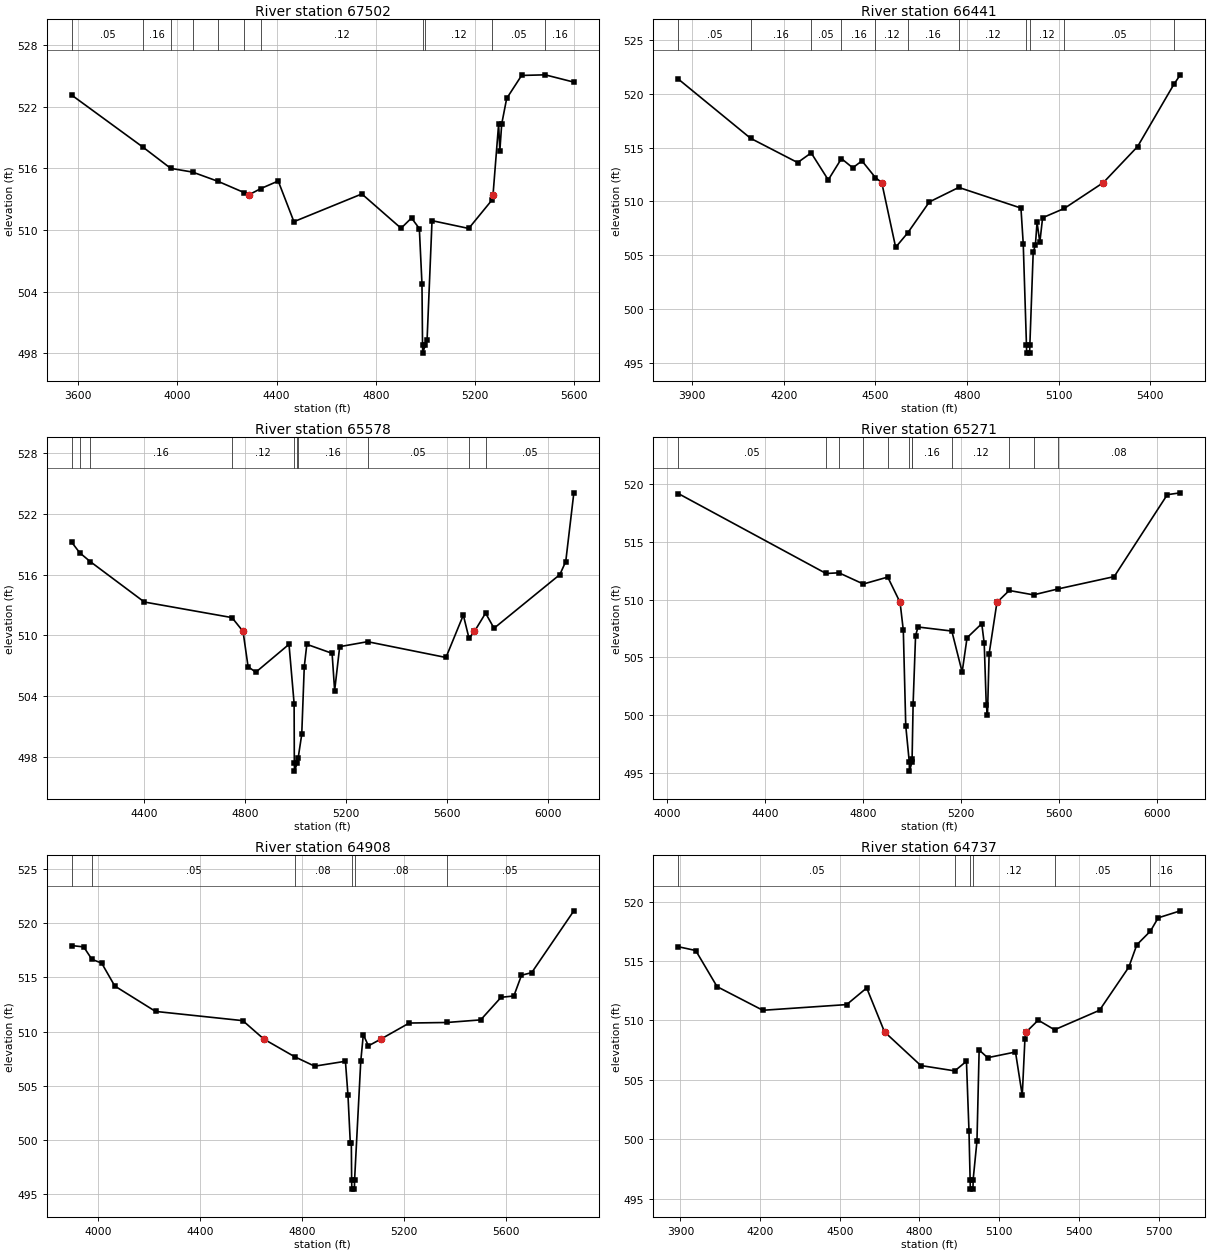
Type RM Length L Ch R = 1,67502,1061,1061,1061
BEGIN DESCRIPTION:
BIG CREEK 48.0
END DESCRIPTION:
XS GIS Cut Line= 3
      2798775.00      7088725.00      2797425.00      7088275.00
      2796825.01      7088325.00
#Sta/Elev= 30
  3573.6  523.12  3860.6  518.06  3972.8  515.99  4060.8  515.63  4164.4  514.72
  4268.1  513.64  4287.4  513.41  4336.7  514.03  4406.3  514.76  4469.6  510.80
  4743.6  513.50  4901.8  510.16  4943.9  511.16  4975.5  510.13  4986.1  504.76
  4988.4  498.80  4989.1  498.00  4999.6  498.80  5006.7  499.29  5026.7  510.90
  5174.7  510.14  5269.2  512.93  5272.7  513.41  5295.2  520.28  5300.2  517.70
  5307.7  520.31  5327.8  522.80  5388.0  525.04  5482.9  525.10  5598.7  524.39
#Mann=11,-1,0
  3573.6    0.05       0  3860.6    0.16       0  3972.8    0.05       0
  4060.8    0.16       0  4164.4    0.12       0  4268.1    0.16       0
  4336.7    0.12       0  4988.4    0.07       0  4999.6    0.12       0
  5269.2    0.05       0  5482.9    0.16       0
Bank Sta=4287.4,5272.7
Exp/Cntr=0.3,0.1

Type RM Length L Ch R = 1,66441,863,863,863
BEGIN DESCRIPTION:
Mapping XS f2c32ce8
END DESCRIPTION:
XS GIS Cut Line= 3
      2798664.81      7087874.30      2797623.13      7087800.52
      2797071.88      7088034.91
#Sta/Elev= 30
  3855.0  521.37  4091.7  515.86  4245.8  513.60  4290.1  514.50  4346.0  511.99
  4389.2  513.97  4426.2  513.11  4456.3  513.76  4500.2  512.21  4521.1  511.74
  4566.6  505.72  4606.3  507.07  4676.9  509.94  4773.1  511.29  4976.7  509.37
  4984.2  506.05  4994.7  496.68  4995.4  495.88  5005.2  495.88  5005.9  496.68
  5016.8  505.26  5024.0  505.94  5029.4  508.05  5038.5  506.18  5047.6  508.47
  5118.2  509.33  5246.5  511.74  5358.5  515.09  5477.5  520.89  5498.3  521.76
#Mann=11,-1,0
  3855.0    0.05       0  4091.7    0.16       0  4290.1    0.05       0
  4389.2    0.16       0  4500.2    0.12       0  4606.3    0.16       0
  4773.1    0.12       0  4994.7    0.07       0  5005.9    0.12       0
  5118.2    0.05       0  5477.5    0.16       0
Bank Sta=4521.1,5246.5
Exp/Cntr=0.3,0.1

Type RM Length L Ch R = 1,65578,307,307,307
BEGIN DESCRIPTION:
Mapping XS 508d1801
END DESCRIPTION:
XS GIS Cut Line= 3
      2798604.01      7087687.67      2797727.30      7087540.10
      2796629.63      7087622.53
#Sta/Elev= 30
  4112.5  519.19  4144.2  518.15  4185.5  517.29  4400.1  513.29  4747.5  511.75
  4791.2  510.39  4811.2  506.91  4841.6  506.35  4973.4  509.11  4993.7  503.26
  4994.5  497.38  4995.2  496.58  5005.8  497.38  5009.4  497.83  5023.9  500.21
  5033.9  506.88  5044.0  509.11  5144.2  508.22  5154.3  504.53  5174.3  508.88
  5284.7  509.37  5595.5  507.81  5664.3  512.00  5686.9  509.70  5708.5  510.39
  5752.5  512.19  5786.0  510.70  6046.8  516.00  6070.2  517.29  6102.3  524.08
#Mann=10,-1,0
  4112.5    0.16       0  4144.2    0.05       0  4185.5    0.16       0
  4747.5    0.12       0  4994.5    0.07       0  5005.8    0.12       0
  5009.4    0.16       0  5284.7    0.05       0  5686.9    0.12       0
  5752.5    0.05       0
Bank Sta=4791.2,5708.5
Exp/Cntr=0.3,0.1

Type RM Length L Ch R = 1,65271,363,363,363
BEGIN DESCRIPTION:
Mapping XS 398639ce
END DESCRIPTION:
XS GIS Cut Line= 4
      2798695.23      7087379.52      2797814.10      7087262.32
      2797614.45      7087262.32      2796655.27      7087249.30
#Sta/Elev= 30
  4047.1  519.17  4650.1  512.25  4702.4  512.31  4802.0  511.34  4901.6  511.94
  4951.9  509.75  4965.1  507.34  4975.1  499.06  4989.4  495.95  4990.1  495.15
  5000.7  495.95  5000.9  496.18  5005.1  500.97  5015.1  506.87  5025.1  507.62
  5162.9  507.27  5205.1  503.72  5225.1  506.69  5285.1  507.91  5295.1  506.21
  5303.4  500.88  5308.4  500.01  5315.1  505.30  5347.0  509.75  5397.1  510.78
  5496.2  510.40  5595.2  510.91  5825.2  511.98  6041.8  519.07  6094.9  519.23
#Mann=12,-1,0
  4047.1    0.05       0  4650.1    0.08       0  4702.4    0.05       0
  4802.0    0.08       0  4901.6    0.05       0  4989.4    0.04       0
  5000.7    0.05       0  5000.9    0.16       0  5162.9    0.12       0
  5397.1    0.16       0  5496.2    0.05       0  5595.2    0.08       0
Bank Sta=4951.9,5347
Exp/Cntr=0.3,0.1

Type RM Length L Ch R = 1,64908,171,171,171
BEGIN DESCRIPTION:
Mapping XS f50b4867
END DESCRIPTION:
XS GIS Cut Line= 3
      2798621.41      7087227.60      2797531.99      7087110.41
      2796659.80      7087110.41
#Sta/Elev= 30
  3897.1  517.91  3943.8  517.79  3976.2  516.64  4014.2  516.30  4065.6  514.19
  4225.4  511.85  4567.4  511.00  4650.1  509.30  4771.3  507.67  4849.0  506.81
  4969.7  507.26  4979.7  504.13  4988.8  499.76  4992.8  499.76  4994.1  496.29
  4994.8  495.49  5004.9  495.49  5005.5  496.29  5029.8  507.26  5039.8  509.71
  5059.8  508.68  5108.5  509.30  5219.8  510.78  5366.5  510.83  5499.8  511.07
  5579.8  513.15  5629.8  513.27  5659.8  515.18  5699.8  515.42  5865.0  521.11
#Mann=6,-1,0
  3897.1    0.08       0  3976.2    0.05       0  4771.3    0.08       0
  4994.1    0.07       0  5005.5    0.08       0  5366.5    0.05       0
Bank Sta=4650.1,5108.5
Exp/Cntr=0.3,0.1

Type RM Length L Ch R = 1,64737,429,429,429
BEGIN DESCRIPTION:
Mapping XS 1939a7dd
END DESCRIPTION:
XS GIS Cut Line= 3
      2798591.05      7087088.72      2797518.97      7086954.16
      2796711.64      7086893.40
#Sta/Elev= 30
  3891.8  516.20  3957.6  515.88  4038.0  512.84  4210.3  510.85  4525.9  511.33
  4601.3  512.73  4668.4  509.03  4805.0  506.20  4932.8  505.75  4976.8  506.56
  4986.3  500.72  4990.6  496.60  4991.3  495.80  5001.4  495.80  5002.0  496.60
  5016.4  499.85  5024.6  507.51  5056.5  506.86  5161.4  507.34  5186.9  503.68
  5196.9  508.42  5202.1  509.03  5247.0  510.02  5308.4  509.21  5477.7  510.85
  5588.0  514.48  5618.1  516.36  5669.3  517.51  5698.6  518.63  5781.9  519.22
#Mann=6,-1,0
  3891.8    0.05       0  4932.8    0.12       0  4990.6    0.07       0
  5002.0    0.12       0  5308.4    0.05       0  5669.3    0.16       0
Bank Sta=4668.4,5202.1
Exp/Cntr=0.3,0.1

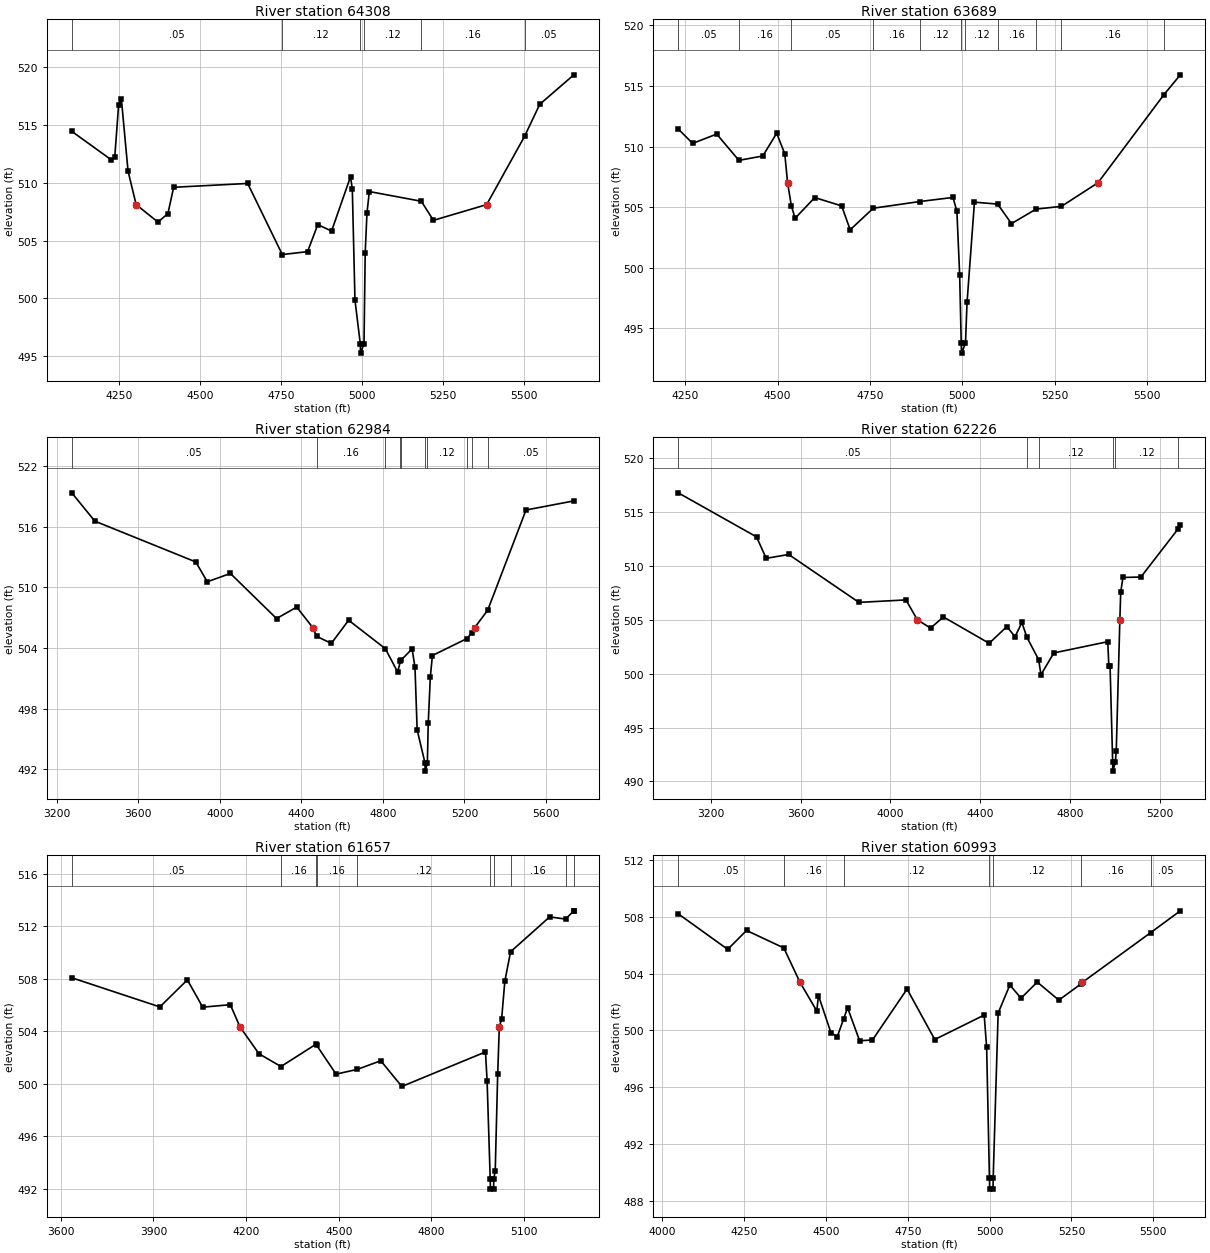
Type RM Length L Ch R = 1,64308,619,619,619
BEGIN DESCRIPTION:
Mapping XS 0b059ed0
END DESCRIPTION:
XS GIS Cut Line= 4
      2798504.21      7086802.25      2797688.24      7086611.28
      2797579.73      7086559.20      2797002.48      7086424.65
#Sta/Elev= 30
  4103.5  514.46  4225.9  511.99  4236.2  512.20  4248.3  516.77  4256.7  517.27
  4277.3  511.03  4302.4  508.12  4369.7  506.61  4400.5  507.34  4418.2  509.62
  4647.0  509.95  4753.8  503.80  4831.9  504.05  4863.6  506.39  4906.1  505.83
  4964.7  510.54  4970.2  509.47  4978.4  499.86  4994.9  496.07  4995.5  495.27
  5006.3  496.07  5010.0  503.93  5015.5  507.39  5022.8  509.25  5183.4  508.41
  5220.8  506.76  5385.3  508.12  5502.2  514.02  5549.3  516.80  5654.6  519.35
#Mann=6,-1,0
  4103.5    0.05       0  4753.8    0.12       0  4994.9    0.07       0
  5006.3    0.12       0  5183.4    0.16       0  5502.2    0.05       0
Bank Sta=4302.4,5385.3
Exp/Cntr=0.3,0.1

Type RM Length L Ch R = 1,63689,705,705,705
BEGIN DESCRIPTION:
BIG CREEK 46.0
END DESCRIPTION:
XS GIS Cut Line= 3
      2798431.09      7086540.51      2797775.00      7086175.00
      2797168.40      7086183.70
#Sta/Elev= 30
  4231.5  511.45  4270.4  510.26  4335.5  511.03  4395.5  508.86  4460.1  509.22
  4497.8  511.10  4519.6  509.40  4527.2  507.01  4537.4  505.11  4547.5  504.08
  4600.7  505.79  4673.5  505.10  4696.4  503.13  4758.9  504.91  4884.0  505.46
  4974.5  505.80  4985.0  504.67  4992.5  499.43  4996.8  493.75  4997.5  492.95
  5008.2  493.75  5012.5  497.14  5032.5  505.41  5095.2  505.25  5132.6  503.64
  5199.3  504.84  5267.6  505.06  5366.5  507.01  5544.6  514.27  5589.2  515.92
#Mann=11,-1,0
  4231.5    0.05       0  4395.5    0.16       0  4537.4    0.05       0
  4758.9    0.16       0  4884.0    0.12       0  4996.8    0.07       0
  5008.2    0.12       0  5095.2    0.16       0  5199.3    0.12       0
  5267.6    0.16       0  5544.6    0.05       0
Bank Sta=4527.2,5366.5
Exp/Cntr=0.3,0.1

Type RM Length L Ch R = 1,62984,758,758,758
BEGIN DESCRIPTION:
BIG CREEK 45.0
END DESCRIPTION:
XS GIS Cut Line= 3
      2799124.97      7086774.97      2797925.00      7085575.00
      2797174.97      7085725.01
#Sta/Elev= 30
  3274.6  519.36  3387.7  516.56  3882.7  512.52  3939.2  510.56  4052.4  511.38
  4278.7  506.92  4377.7  508.05  4457.0  506.01  4475.2  505.16  4547.4  504.46
  4632.2  506.75  4811.9  503.94  4872.6  501.63  4885.8  502.68  4887.5  502.77
  4943.3  503.91  4957.5  502.11  4968.1  495.91  5006.7  492.62  5007.3  491.82
  5018.2  492.62  5022.6  496.60  5032.8  501.15  5043.0  503.26  5212.5  504.94
  5236.6  505.52  5249.8  506.01  5314.0  507.74  5501.9  517.66  5736.5  518.56
#Mann=10,-1,0
  3274.6    0.05       0  4475.2    0.16       0  4811.9    0.12       0
  4885.8    0.16       0  4887.5    0.12       0  5006.7    0.07       0
  5018.2    0.12       0  5212.5    0.05       0  5236.6    0.12       0
  5314.0    0.05       0
Bank Sta=4457,5249.8
Exp/Cntr=0.3,0.1

Type RM Length L Ch R = 1,62226,569,569,569
BEGIN DESCRIPTION:
BIG CREEK 44.0
END DESCRIPTION:
XS GIS Cut Line= 3
      2799150.00      7086550.00      2798125.00      7084925.00
      2797809.46      7084926.38
#Sta/Elev= 30
  3055.2  516.74  3404.0  512.66  3447.1  510.67  3547.2  511.03  3860.2  506.59
  4069.7  506.82  4120.1  504.99  4179.1  504.21  4236.8  505.24  4440.4  502.80
  4519.2  504.35  4555.7  503.41  4586.3  504.73  4607.8  503.39  4661.0  501.28
  4671.1  499.89  4728.7  501.91  4968.8  502.95  4973.5  500.72  4979.0  500.72
  4990.7  491.76  4991.4  490.96  5002.2  491.76  5006.5  492.78  5022.7  504.99
  5026.5  507.55  5036.5  508.90  5116.5  508.94  5281.5  513.38  5292.0  513.78
#Mann=6,-1,0
  3055.2    0.05       0  4607.8    0.16       0  4661.0    0.12       0
  4990.7    0.07       0  5002.2    0.12       0  5281.5    0.05       0
Bank Sta=4120.1,5022.7
Exp/Cntr=0.3,0.1

Type RM Length L Ch R = 1,61657,664,664,664
BEGIN DESCRIPTION:
Mapping XS c3c46e3b
END DESCRIPTION:
XS GIS Cut Line= 3
      2799093.62      7085747.58      2798447.79      7084648.61
      2798109.60      7084554.96
#Sta/Elev= 30
  3635.7  508.09  3921.0  505.87  4009.9  507.93  4059.7  505.85  4149.0  506.04
  4180.1  504.36  4241.8  502.30  4313.1  501.33  4427.2  503.04  4428.2  502.96
  4491.4  500.75  4560.0  501.11  4636.2  501.77  4704.3  499.81  4975.2  502.44
  4980.4  500.26  4990.5  492.79  4991.2  491.99  5001.4  491.99  5002.0  492.79
  5006.7  493.35  5014.7  500.73  5020.0  504.36  5027.4  504.93  5037.8  507.82
  5056.4  510.07  5183.1  512.73  5234.5  512.56  5260.7  513.18  5261.3  513.19
#Mann=10,-1,0
  3635.7    0.05       0  4313.1    0.16       0  4427.2    0.12       0
  4428.2    0.16       0  4560.0    0.12       0  4990.5    0.07       0
  5002.0    0.12       0  5056.4    0.16       0  5234.5    0.12       0
  5260.7    0.16       0
Bank Sta=4180.1,5020
Exp/Cntr=0.3,0.1

Type RM Length L Ch R = 1,60993,627,627,627
BEGIN DESCRIPTION:
Mapping XS ac7e529e
END DESCRIPTION:
XS GIS Cut Line= 5
      2799187.36      7085476.70      2798906.12      7084648.61
      2798791.54      7084518.40      2798624.87      7084455.90
      2798318.76      7084481.84
#Sta/Elev= 30
  4049.1  508.20  4200.2  505.70  4257.7  507.03  4371.5  505.80  4421.0  503.38
  4472.1  501.37  4477.4  502.45  4515.6  499.82  4534.9  499.57  4553.9  500.79
  4566.3  501.59  4603.0  499.27  4642.3  499.33  4747.9  502.91  4832.4  499.36
  4983.4  501.08  4990.9  498.80  4999.4  489.64  5000.1  488.84  5010.3  488.84
  5010.9  489.64  5026.0  501.22  5061.7  503.19  5096.0  502.27  5145.5  503.40
  5211.3  502.13  5278.4  503.26  5283.3  503.38  5491.4  506.87  5582.3  508.41
#Mann=7,-1,0
  4049.1    0.05       0  4371.5    0.16       0  4553.9    0.12       0
  4999.4    0.07       0  5010.9    0.12       0  5278.4    0.16       0
  5491.4    0.05       0
Bank Sta=4421,5283.3
Exp/Cntr=0.3,0.1

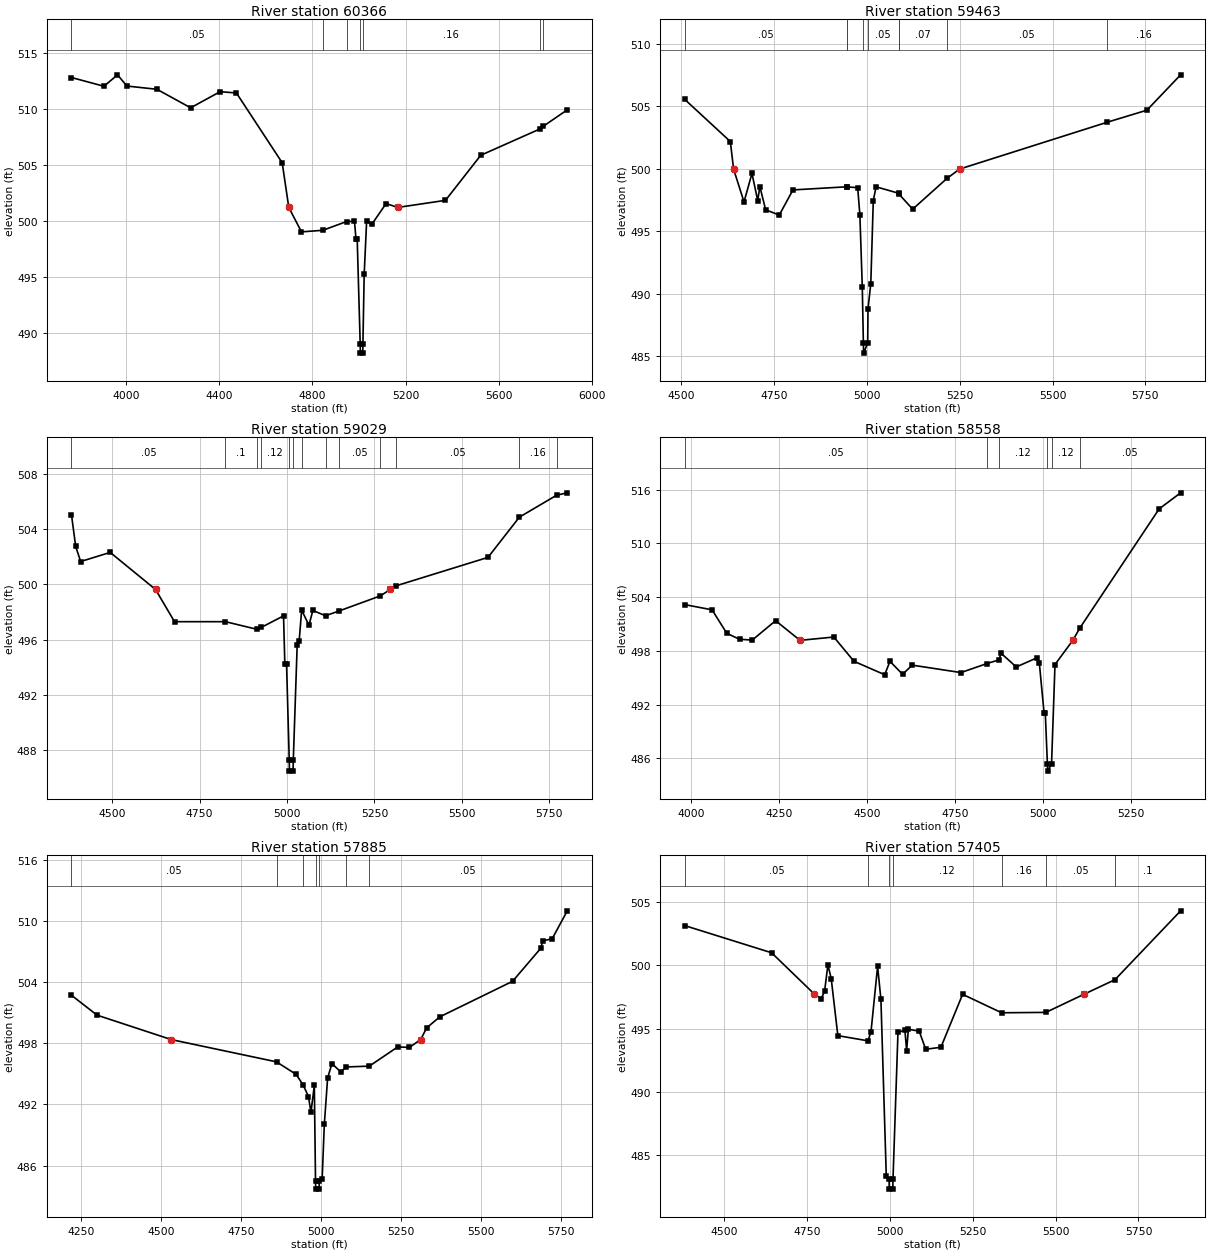
Type RM Length L Ch R = 1,60366,903,903,903
BEGIN DESCRIPTION:
Mapping XS 71355f7c
END DESCRIPTION:
XS GIS Cut Line= 3
      2800250.02      7084550.00      2799067.58      7084242.36
      2798198.90      7084497.24
#Sta/Elev= 30
  3766.6  512.77  3906.1  511.99  3964.1  513.01  4004.6  512.01  4133.4  511.72
  4277.9  510.07  4404.7  511.51  4474.4  511.39  4670.7  505.17  4698.9  501.19
  4753.4  499.01  4844.9  499.15  4946.6  499.93  4980.7  499.95  4987.2  498.38
  4992.4  498.38  5005.3  489.00  5005.9  488.20  5016.3  488.20  5016.9  489.00
  5022.4  495.22  5032.8  499.94  5055.0  499.68  5116.2  501.53  5166.8  501.19
  5371.1  501.82  5522.6  505.84  5774.9  508.17  5790.4  508.42  5893.7  509.89
#Mann=7,-1,0
  3766.6    0.05       0  4844.9     0.1       0  4946.6    0.16       0
  5005.3    0.07       0  5016.9    0.16       0  5774.9    0.05       0
  5790.4    0.12       0
Bank Sta=4698.9,5166.8
Exp/Cntr=0.3,0.1

Type RM Length L Ch R = 1,59463,434,434,434
BEGIN DESCRIPTION:
Mapping XS b191299d
END DESCRIPTION:
XS GIS Cut Line= 3
      2799395.68      7083476.75      2798984.24      7083726.73
      2798412.32      7084361.04
#Sta/Elev= 30
  4509.5  505.54  4632.2  502.17  4640.9  499.97  4669.0  497.34  4690.4  499.62
  4705.9  497.45  4711.7  498.57  4727.2  496.71  4764.0  496.29  4800.8  498.30
  4945.7  498.55  4946.9  498.54  4975.2  498.48  4981.1  496.29  4987.6  490.50
  4990.5  486.04  4991.1  485.24  5002.1  486.04  5003.0  488.79  5010.5  490.81
  5017.2  497.45  5024.7  498.55  5086.0  498.03  5087.1  497.94  5123.3  496.76
  5216.0  499.23  5249.8  499.97  5647.6  503.72  5754.1  504.68  5845.0  507.51
#Mann=9,-1,0
  4509.5    0.05       0  4945.7    0.16       0  4946.9    0.05       0
  4990.5   0.035       0  5002.1    0.05       0  5086.0    0.16       0
  5087.1    0.07       0  5216.0    0.05       0  5647.6    0.16       0
Bank Sta=4640.9,5249.8
Exp/Cntr=0.3,0.1

Type RM Length L Ch R = 1,59029,471,471,471
BEGIN DESCRIPTION:
Mapping XS b3b0782a
END DESCRIPTION:
XS GIS Cut Line= 3
      2799135.25      7083148.64      2798676.95      7083554.86
      2798322.77      7084278.85
#Sta/Elev= 30
  4383.4  505.05  4395.5  502.75  4409.7  501.66  4494.2  502.32  4623.9  499.64
  4678.2  497.31  4823.8  497.31  4913.7  496.76  4925.9  496.89  4990.1  497.73
  4993.8  494.24  4998.7  494.24  5006.4  487.30  5007.0  486.50  5017.4  486.50
  5018.0  487.30  5029.1  495.60  5034.7  495.88  5041.9  498.15  5062.8  497.05
  5073.9  498.12  5110.2  497.74  5149.6  498.09  5267.4  499.18  5295.3  499.64
  5312.8  499.91  5574.9  501.96  5664.7  504.87  5771.5  506.46  5801.8  506.63
#Mann=13,-1,0
  4383.4    0.05       0  4823.8     0.1       0  4913.7    0.07       0
  4925.9    0.12       0  5006.4    0.07       0  5018.0    0.12       0
  5041.9    0.07       0  5110.2    0.16       0  5149.6    0.05       0
  5267.4    0.07       0  5312.8    0.05       0  5664.7    0.16       0
  5771.5    0.05       0
Bank Sta=4623.9,5295.3
Exp/Cntr=0.3,0.1

Type RM Length L Ch R = 1,58558,673,673,673
BEGIN DESCRIPTION:
Mapping XS 0c8c0e33
END DESCRIPTION:
XS GIS Cut Line= 3
      2799182.13      7082825.71      2798327.99      7083388.19
      2797973.84      7083544.43
#Sta/Elev= 30
  3981.0  503.17  4058.5  502.59  4100.6  499.96  4136.7  499.30  4172.9  499.21
  4239.2  501.38  4308.6  499.18  4404.8  499.55  4462.0  496.84  4549.4  495.34
  4564.3  496.84  4600.2  495.39  4627.7  496.41  4766.2  495.58  4840.3  496.59
  4873.7  496.99  4880.7  497.72  4923.5  496.21  4983.1  497.24  4989.1  496.63
  5002.5  491.07  5006.0  491.07  5012.0  485.37  5012.6  484.57  5023.8  485.37
  5033.6  496.48  5084.3  499.18  5104.5  500.57  5329.8  513.87  5390.8  515.66
#Mann=6,-1,0
  3981.0    0.05       0  4840.3    0.07       0  4873.7    0.12       0
  5012.0    0.07       0  5023.8    0.12       0  5104.5    0.05       0
Bank Sta=4308.6,5084.3
Exp/Cntr=0.3,0.1

Type RM Length L Ch R = 1,57885,480,480,480
BEGIN DESCRIPTION:
Mapping XS 58d989e8
END DESCRIPTION:
XS GIS Cut Line= 3
      2799041.56      7082659.02      2798291.54      7082882.98
      2797549.35      7083069.83
#Sta/Elev= 30
  4221.2  502.70  4301.1  500.75  4533.4  498.35  4861.4  496.17  4922.8  494.94
  4944.9  493.89  4961.2  492.76  4969.0  491.23  4979.5  493.86  4983.2  484.49
  4983.8  483.69  4994.5  483.69  4995.0  484.49  5004.0  484.73  5010.7  490.03
  5021.0  494.59  5034.6  496.00  5062.3  495.17  5078.7  495.67  5151.2  495.75
  5240.1  497.64  5276.1  497.58  5311.4  498.35  5330.4  499.51  5371.6  500.59
  5598.5  504.07  5687.1  507.33  5692.3  508.02  5722.2  508.25  5769.3  510.98
#Mann=7,-1,0
  4221.2    0.05       0  4861.4    0.12       0  4944.9    0.16       0
  4983.2    0.07       0  4995.0    0.16       0  5078.7    0.12       0
  5151.2    0.05       0
Bank Sta=4533.4,5311.4
Exp/Cntr=0.3,0.1

Type RM Length L Ch R = 1,57405,834,834,834
BEGIN DESCRIPTION:
Mapping XS 28298158
END DESCRIPTION:
XS GIS Cut Line= 3
      2798926.99      7082487.15      2798317.58      7082492.36
      2797469.32      7082752.56
#Sta/Elev= 30
  4380.5  503.15  4642.5  501.00  4771.9  497.72  4792.5  497.37  4802.5  497.96
  4812.5  500.05  4822.5  498.95  4842.5  494.44  4933.3  494.03  4942.5  494.73
  4962.5  499.92  4972.5  497.32  4988.7  483.32  4997.2  483.09  4997.7  482.29
  5008.4  482.29  5009.0  483.09  5024.0  494.69  5044.9  494.88  5050.1  493.25
  5055.4  494.95  5088.1  494.79  5107.7  493.36  5153.6  493.52  5219.1  497.71
  5336.9  496.25  5470.4  496.28  5585.9  497.72  5679.1  498.87  5877.2  504.32
#Mann=7,-1,0
  4380.5    0.05       0  4933.3    0.12       0  4997.2    0.07       0
  5009.0    0.12       0  5336.9    0.16       0  5470.4    0.05       0
  5679.1     0.1       0
Bank Sta=4771.9,5585.9
Exp/Cntr=0.3,0.1

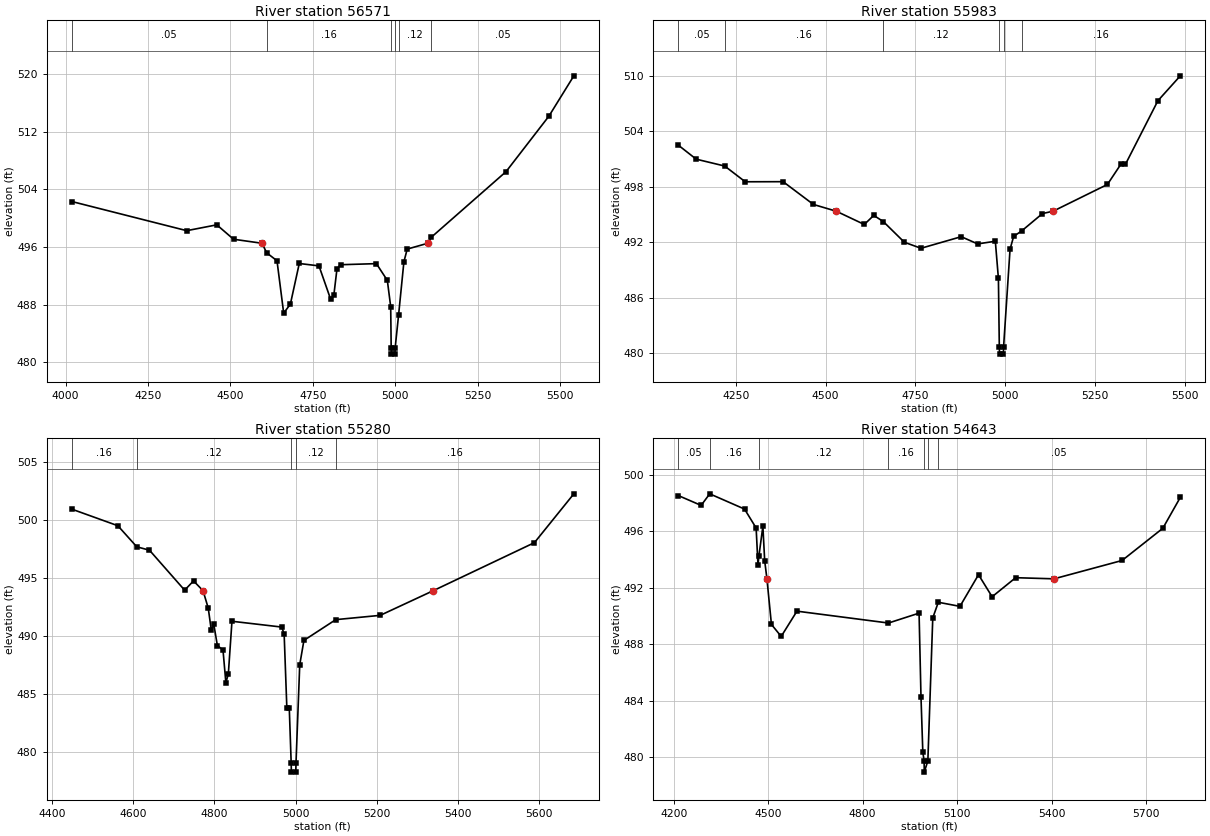
Type RM Length L Ch R = 1,56571,588,588,588
BEGIN DESCRIPTION:
Mapping XS 4aedcd58
END DESCRIPTION:
XS GIS Cut Line= 3
      2798848.79      7082257.98      2797885.29      7082091.32
      2797339.22      7082086.12
#Sta/Elev= 30
  4018.5  502.33  4367.4  498.28  4458.7  499.09  4509.5  497.09  4595.9  496.53
  4610.2  495.20  4641.4  494.10  4661.7  486.83  4682.0  488.07  4709.0  493.72
  4768.8  493.39  4803.8  488.81  4813.9  489.30  4823.5  492.99  4834.2  493.55
  4943.1  493.70  4976.3  491.37  4986.5  487.73  4988.0  481.93  4988.5  481.13
  4999.3  481.13  4999.9  481.93  5010.6  486.63  5026.6  493.96  5036.6  495.72
  5098.9  496.53  5109.6  497.36  5336.6  506.48  5466.6  514.18  5542.4  519.79
#Mann=6,-1,0
  4018.5    0.05       0  4610.2    0.16       0  4988.0    0.07       0
  4999.9    0.16       0  5010.6    0.12       0  5109.6    0.05       0
Bank Sta=4595.9,5098.9
Exp/Cntr=0.3,0.1

Type RM Length L Ch R = 1,55983,703,703,703
BEGIN DESCRIPTION:
Mapping XS 217b606d
END DESCRIPTION:
XS GIS Cut Line= 3
      2798921.78      7082044.45      2798067.58      7081757.98
      2797572.78      7081716.32
#Sta/Elev= 30
  4089.6  502.49  4139.6  500.97  4218.9  500.23  4276.1  498.53  4381.5  498.54
  4465.9  496.08  4529.6  495.35  4607.5  493.92  4633.8  494.90  4660.2  494.24
  4719.0  492.00  4765.3  491.35  4877.3  492.60  4923.0  491.82  4972.2  492.11
  4980.8  488.09  4983.3  480.72  4983.9  479.92  4994.7  479.92  4995.2  480.72
  5013.2  491.25  5023.2  492.63  5046.1  493.24  5103.5  495.10  5132.9  495.35
  5284.2  498.24  5321.7  500.43  5334.3  500.41  5424.7  507.28  5487.1  509.97
#Mann=6,-1,0
  4089.6    0.05       0  4218.9    0.16       0  4660.2    0.12       0
  4983.3    0.07       0  4995.2    0.12       0  5046.1    0.16       0
Bank Sta=4529.6,5132.9
Exp/Cntr=0.3,0.1

Type RM Length L Ch R = 1,55280,637,637,637
BEGIN DESCRIPTION:
Mapping XS a264df13
END DESCRIPTION:
XS GIS Cut Line= 3
      2798822.77      7081674.64      2798380.08      7081372.57
      2797698.94      7081206.18
#Sta/Elev= 30
  4448.6  500.91  4562.1  499.48  4608.8  497.66  4640.0  497.37  4726.7  493.92
  4748.6  494.72  4772.0  493.88  4784.9  492.37  4792.4  490.46  4798.5  490.98
  4807.4  489.14  4821.2  488.77  4828.3  485.94  4834.4  486.71  4843.3  491.24
  4965.9  490.74  4971.9  490.14  4978.5  483.80  4984.5  483.80  4989.2  479.03
  4989.7  478.23  5000.5  478.23  5001.1  479.03  5010.3  487.49  5020.6  489.59
  5099.1  491.38  5208.6  491.75  5339.5  493.88  5588.6  498.02  5685.7  502.23
#Mann=5,-1,0
  4448.6    0.16       0  4608.8    0.12       0  4989.2    0.07       0
  5001.1    0.12       0  5099.1    0.16       0
Bank Sta=4772,5339.5
Exp/Cntr=0.3,0.1

Type RM Length L Ch R = 1,54643,476,476,476
BEGIN DESCRIPTION:
Mapping XS 06a56ee8
END DESCRIPTION:
XS GIS Cut Line= 3
      2799010.29      7081627.78      2798630.08      7080997.57
      2797885.27      7080570.47
#Sta/Elev= 30
  4214.2  498.52  4286.9  497.82  4314.2  498.64  4424.8  497.56  4461.6  496.22
  4467.5  493.60  4470.6  494.26  4483.0  496.34  4488.8  493.89  4495.9  492.62
  4510.2  489.39  4541.2  488.54  4591.2  490.33  4881.9  489.49  4979.1  490.19
  4985.2  484.25  4991.0  480.35  4995.1  479.73  4995.6  478.93  5007.0  479.73
  5022.6  489.85  5040.2  490.96  5108.9  490.67  5167.9  492.91  5211.1  491.35
  5285.8  492.70  5407.7  492.62  5623.9  493.92  5753.3  496.20  5808.8  498.39
#Mann=7,-1,0
  4214.2    0.05       0  4314.2    0.16       0  4470.6    0.12       0
  4881.9    0.16       0  4995.1    0.07       0  5007.0    0.16       0
  5040.2    0.05       0
Bank Sta=4495.9,5407.7
Exp/Cntr=0.3,0.1