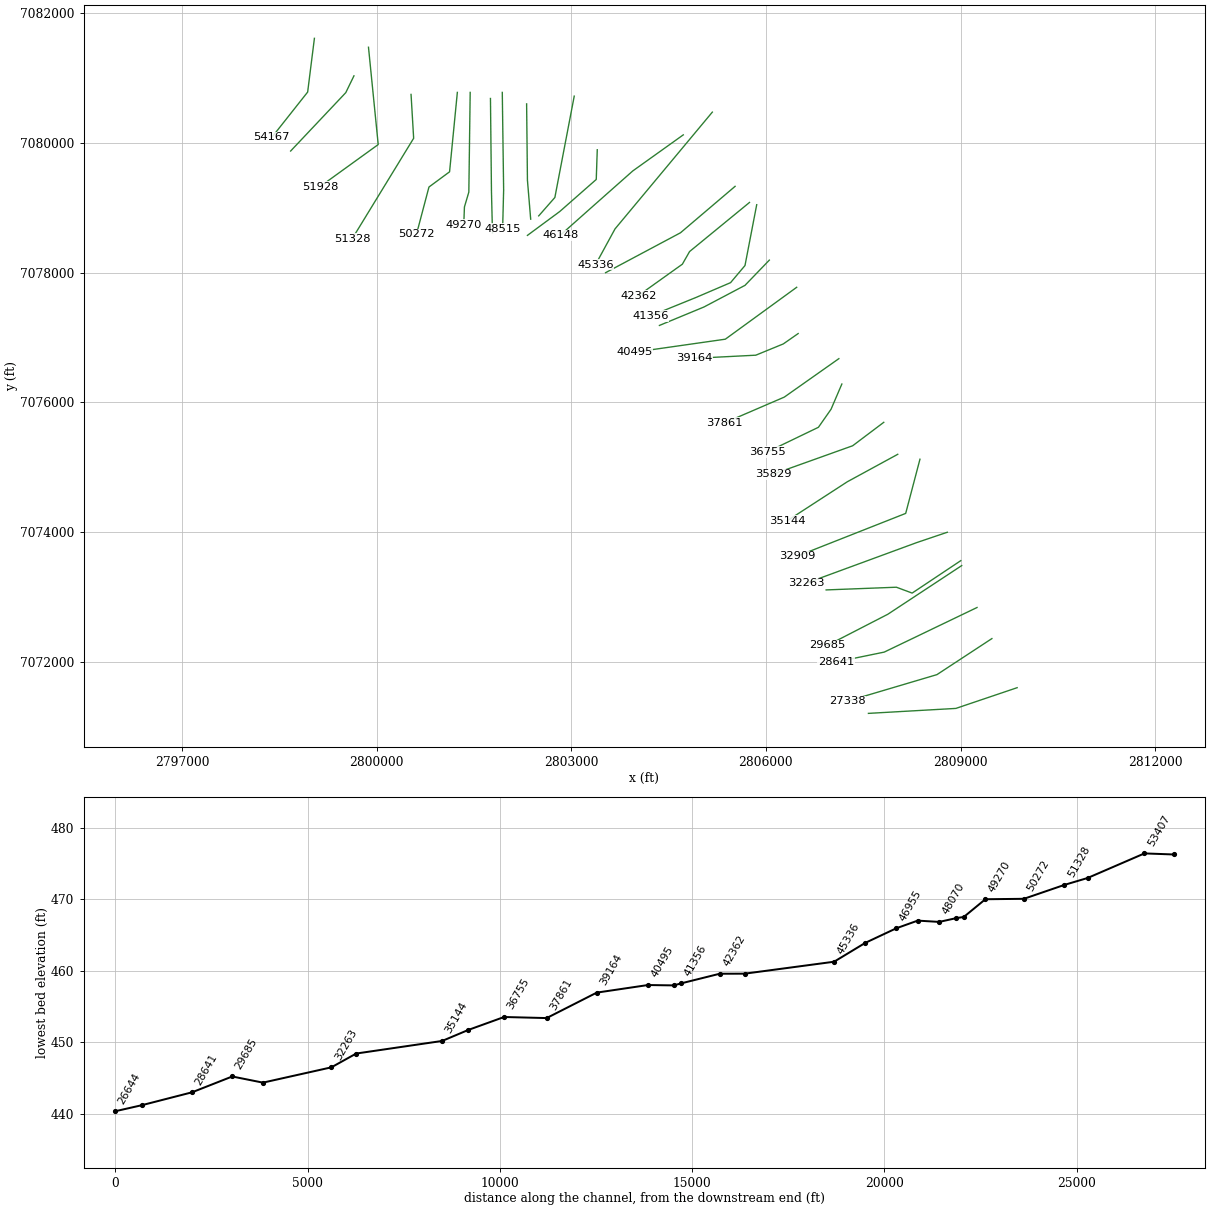
HEC-RAS study BIG CREEK.prj: BIG CREEK Base Level Engineering

--- BIG CREEK.g01 (geometry) --- (continued)

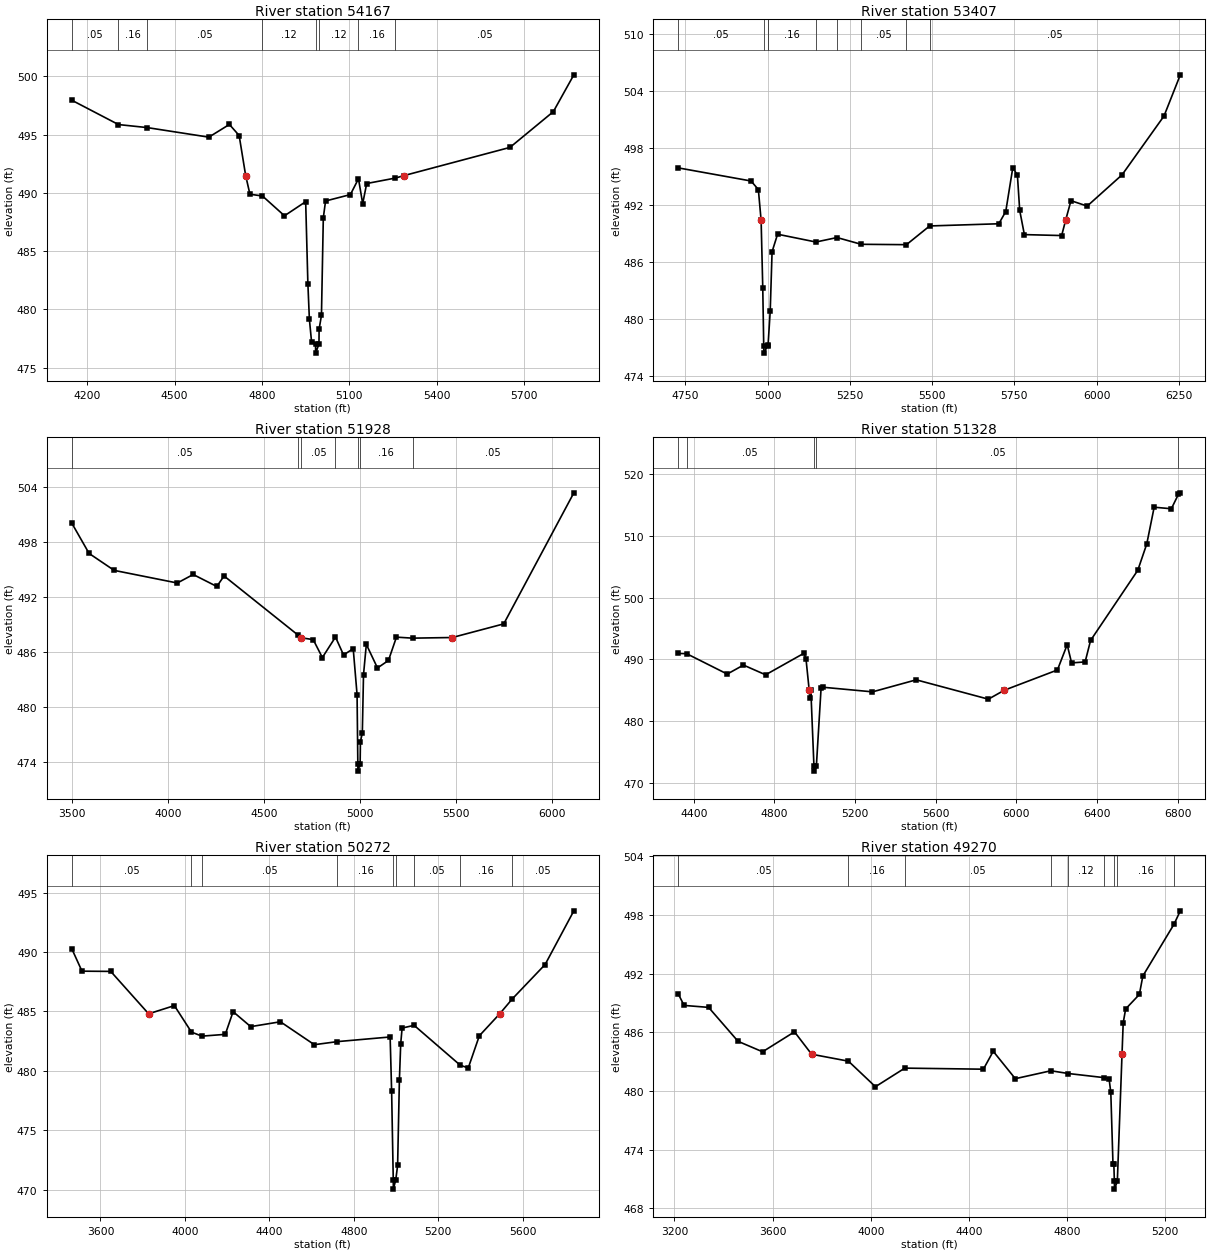
Type RM Length L Ch R = 1,54167,760,760,760
BEGIN DESCRIPTION:
Mapping XS 30c262aa
END DESCRIPTION:
XS GIS Cut Line= 3
      2799041.54      7081612.15      2798937.37      7080784.02
      2798385.31      7080086.13
#Sta/Elev= 30
  4146.7  497.95  4307.2  495.86  4406.0  495.60  4617.5  494.78  4688.1  495.87
  4721.6  494.92  4744.0  491.48  4758.6  489.88  4801.6  489.73  4877.3  488.03
  4950.1  489.24  4957.7  482.19  4962.8  479.16  4970.3  477.21  4983.9  477.04
  4984.4  476.24  4995.8  477.04  4996.2  478.29  5004.3  479.48  5010.7  487.86
  5018.4  489.30  5103.7  489.85  5131.5  491.21  5145.9  489.07  5159.7  490.80
  5258.6  491.27  5287.8  491.48  5651.8  493.90  5800.8  496.97  5871.2  500.13
#Mann=8,-1,0
  4146.7    0.05       0  4307.2    0.16       0  4406.0    0.05       0
  4801.6    0.12       0  4983.9    0.07       0  4995.8    0.12       0
  5131.5    0.16       0  5258.6    0.05       0
Bank Sta=4744,5287.8
Exp/Cntr=0.3,0.1

Type RM Length L Ch R = 1,53407,1479,1479,1479
BEGIN DESCRIPTION:
BIG CREEK 38.0
END DESCRIPTION:
XS GIS Cut Line= 3
      2799650.90      7081034.01      2799525.00      7080775.00
      2798675.02      7079875.02
#Sta/Elev= 30
  4728.4  495.88  4949.7  494.50  4971.9  493.60  4980.3  490.35  4985.3  483.25
  4988.2  477.19  4988.7  476.39  5000.2  477.19  5001.4  477.24  5007.9  480.79
  5013.6  487.06  5030.3  488.90  5146.8  488.08  5211.0  488.55  5284.4  487.84
  5422.0  487.80  5492.5  489.77  5702.7  490.00  5723.8  491.29  5745.2  495.90
  5759.2  495.11  5766.2  491.40  5780.4  488.86  5893.7  488.76  5905.6  490.35
  5922.0  492.43  5971.3  491.86  6077.3  495.15  6204.8  501.34  6254.3  505.67
#Mann=9,-1,0
  4728.4    0.05       0  4988.2    0.03       0  5000.2    0.05       0
  5001.4    0.16       0  5146.8     0.1       0  5211.0    0.07       0
  5284.4    0.05       0  5422.0    0.07       0  5492.5    0.05       0
Bank Sta=4980.3,5905.6
Exp/Cntr=0.3,0.1

Type RM Length L Ch R = 1,51928,600,600,600
BEGIN DESCRIPTION:
BIG CREEK 37.0
END DESCRIPTION:
XS GIS Cut Line= 3
      2799875.00      7081474.97      2800025.00      7079975.00
      2799125.03      7079325.02
#Sta/Elev= 30
  3496.8  500.07  3587.2  496.75  3717.9  494.90  4047.0  493.52  4129.9  494.45
  4253.0  493.14  4290.7  494.29  4675.5  487.84  4690.8  487.56  4693.0  487.53
  4755.5  487.33  4803.3  485.37  4871.7  487.61  4913.8  485.65  4964.1  486.34
  4984.2  481.32  4988.2  473.75  4988.7  472.95  5000.2  473.75  5001.7  476.18
  5011.6  477.11  5017.8  483.49  5032.5  486.81  5090.6  484.23  5147.8  485.05
  5189.5  487.60  5273.3  487.49  5480.7  487.56  5748.9  489.05  6114.4  503.38
#Mann=7,-1,0
  3496.8    0.05       0  4675.5    0.16       0  4693.0    0.05       0
  4871.7    0.16       0  4988.2    0.07       0  5000.2    0.16       0
  5273.3    0.05       0
Bank Sta=4690.8,5480.7
Exp/Cntr=0.3,0.1

Type RM Length L Ch R = 1,51328,1056,1056,1056
BEGIN DESCRIPTION:
BIG CREEK 36.0
END DESCRIPTION:
XS GIS Cut Line= 3
      2800531.12      7080747.59      2800571.20      7080071.98
      2799625.01      7078525.01
#Sta/Elev= 30
  4323.2  490.98  4364.7  490.94  4566.2  487.65  4646.7  489.10  4756.6  487.53
  4946.9  491.01  4956.9  490.08  4972.8  485.04  4975.8  483.73  4980.8  485.11
  4996.3  472.79  4996.8  471.99  5008.3  472.79  5031.6  485.34  5039.1  485.53
  5286.7  484.78  5503.5  486.72  5861.4  483.60  5940.3  485.04  6203.9  488.31
  6252.3  492.38  6274.2  489.45  6341.3  489.61  6368.4  493.08  6602.4  504.39
  6647.0  508.64  6683.7  514.57  6768.9  514.32  6804.2  516.66  6813.4  516.89
#Mann=5,-1,0
  4323.2    0.16       0  4364.7    0.05       0  4996.3    0.03       0
  5008.3    0.05       0  6804.2    0.08       0
Bank Sta=4972.8,5940.3
Exp/Cntr=0.3,0.1

Type RM Length L Ch R = 1,50272,1002,1002,1002
BEGIN DESCRIPTION:
Mapping XS 00d59622
END DESCRIPTION:
XS GIS Cut Line= 4
      2801244.66      7080778.79      2801124.87      7079554.86
      2800807.16      7079320.48      2800614.45      7078591.31
#Sta/Elev= 30
  3464.0  490.28  3512.4  488.39  3648.7  488.37  3828.2  484.80  3950.1  485.49
  4031.1  483.26  4080.6  482.92  4191.3  483.07  4228.4  484.98  4311.8  483.72
  4452.5  484.13  4613.3  482.20  4723.0  482.46  4972.4  482.85  4979.4  478.33
  4987.2  470.84  4987.7  470.04  4999.2  470.84  5007.8  472.03  5016.3  479.24
  5022.5  482.28  5029.1  483.60  5086.0  483.83  5304.7  480.47  5342.5  480.24
  5395.0  482.95  5491.6  484.80  5551.4  486.06  5706.7  488.95  5842.8  493.47
#Mann=9,-1,0
  3464.0    0.05       0  4031.1    0.16       0  4080.6    0.05       0
  4723.0    0.16       0  4987.2    0.07       0  4999.2    0.16       0
  5086.0    0.05       0  5304.7    0.16       0  5551.4    0.05       0
Bank Sta=3828.2,5491.6
Exp/Cntr=0.3,0.1

Type RM Length L Ch R = 1,49270,561,561,561
BEGIN DESCRIPTION:
Mapping XS 74c61925
END DESCRIPTION:
XS GIS Cut Line= 4
      2801442.58      7080778.77      2801421.74      7079242.36
      2801354.04      7079013.19      2801343.62      7078742.40
#Sta/Elev= 30
  3215.4  489.94  3239.2  488.76  3339.2  488.56  3459.2  485.09  3559.2  484.02
  3689.2  486.06  3759.1  483.77  3909.2  483.06  4019.2  480.45  4138.9  482.35
  4459.3  482.24  4499.3  484.07  4589.3  481.27  4734.4  482.08  4805.0  481.80
  4950.3  481.38  4971.6  481.25  4978.6  479.86  4987.4  472.59  4990.9  472.59
  4993.1  470.78  4993.6  469.98  5005.2  470.78  5024.3  483.77  5029.1  486.98
  5039.1  488.40  5095.0  489.88  5109.2  491.77  5236.0  497.05  5261.9  498.43
#Mann=9,-1,0
  3215.4    0.05       0  3909.2    0.16       0  4138.9    0.05       0
  4734.4    0.16       0  4805.0    0.12       0  4950.3    0.16       0
  4993.1    0.07       0  5005.2    0.16       0  5236.0    0.05       0
Bank Sta=3759.1,5024.3
Exp/Cntr=0.3,0.1

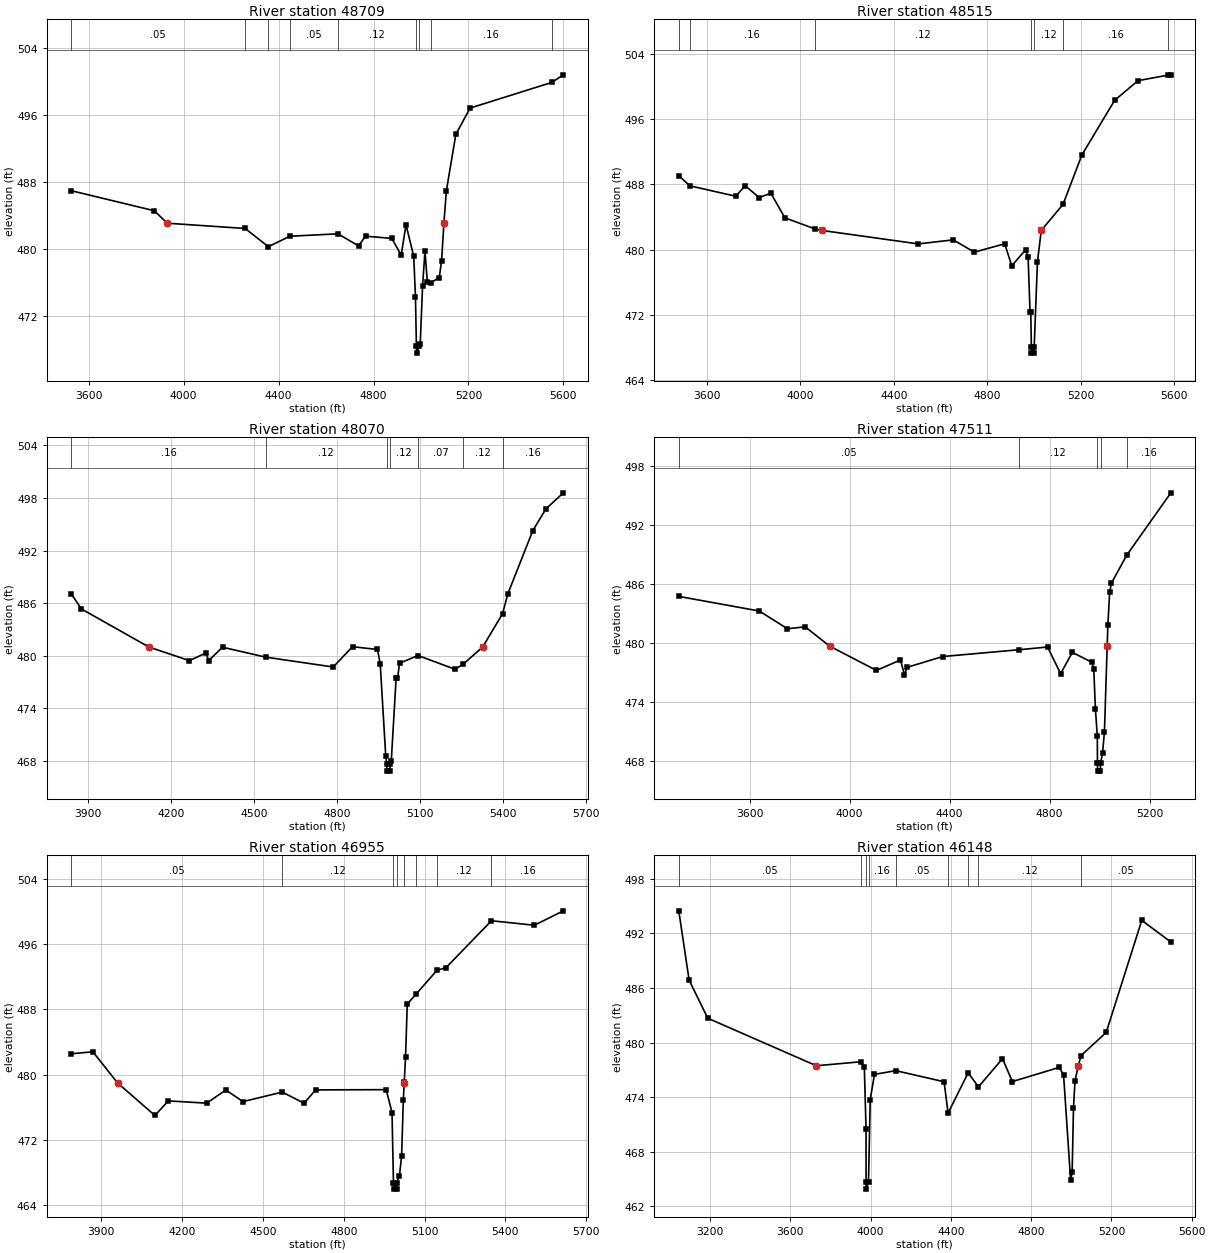
Type RM Length L Ch R = 1,48709,194,194,194
BEGIN DESCRIPTION:
Mapping XS 2c825a9b
END DESCRIPTION:
XS GIS Cut Line= 3
      2801755.08      7080685.05      2801770.70      7079242.36
      2801786.33      7078612.13
#Sta/Elev= 30
  3526.7  486.94  3876.8  484.54  3930.7  483.05  4259.2  482.42  4357.0  480.24
  4447.5  481.49  4650.3  481.78  4736.8  480.34  4766.8  481.50  4876.8  481.23
  4916.8  479.23  4936.8  482.88  4969.5  479.08  4976.8  474.22  4980.8  468.30
  4981.3  467.50  4992.9  468.30  4996.8  468.58  5006.8  475.57  5016.9  479.73
  5026.9  476.00  5041.5  475.93  5076.9  476.54  5086.9  478.58  5096.6  483.05
  5106.9  486.92  5146.9  493.68  5206.9  496.83  5551.2  499.90  5599.9  500.81
#Mann=9,-1,0
  3526.7    0.05       0  4259.2    0.12       0  4357.0    0.16       0
  4447.5    0.05       0  4650.3    0.12       0  4980.8    0.07       0
  4992.9    0.12       0  5041.5    0.16       0  5551.2    0.05       0
Bank Sta=3930.7,5096.6
Exp/Cntr=0.3,0.1

Type RM Length L Ch R = 1,48515,445,445,445
BEGIN DESCRIPTION:
Mapping XS f08b43e3
END DESCRIPTION:
XS GIS Cut Line= 3
      2801937.37      7080778.79      2801958.20      7079273.61
      2801942.58      7078674.64
#Sta/Elev= 30
  3480.7  489.06  3527.5  487.82  3724.5  486.54  3764.5  487.83  3824.5  486.38
  3874.5  486.91  3934.5  483.90  4061.2  482.56  4091.7  482.36  4504.6  480.71
  4654.6  481.20  4744.6  479.70  4874.6  480.72  4904.6  478.03  4964.6  480.00
  4974.6  479.09  4982.8  472.43  4986.0  472.43  4988.5  468.14  4989.0  467.34
  5000.2  467.34  5000.7  468.14  5014.6  478.54  5031.0  482.36  5124.1  485.55
  5204.7  491.60  5344.8  498.28  5444.8  500.69  5574.6  501.37  5585.2  501.40
#Mann=7,-1,0
  3480.7    0.05       0  3527.5    0.16       0  4061.2    0.12       0
  4988.5    0.07       0  5000.7    0.12       0  5124.1    0.16       0
  5574.6    0.05       0
Bank Sta=4091.7,5031
Exp/Cntr=0.3,0.1

Type RM Length L Ch R = 1,48070,559,559,559
BEGIN DESCRIPTION:
BIG CREEK 33.0
END DESCRIPTION:
XS GIS Cut Line= 3
      2802312.37      7080601.73      2802325.00      7079425.00
      2802375.00      7078824.98
#Sta/Elev= 30
  3838.6  487.05  3875.3  485.33  4119.4  480.98  4265.4  479.43  4325.4  480.30
  4335.4  479.43  4385.4  480.96  4540.9  479.83  4785.4  478.70  4855.4  481.02
  4945.4  480.70  4955.4  479.07  4975.4  468.52  4979.3  467.61  4979.8  466.81
  4991.0  466.81  4991.5  467.61  4995.4  467.96  5012.9  477.41  5017.9  477.41
  5025.4  479.14  5092.2  480.01  5226.1  478.44  5255.8  479.04  5325.9  480.98
  5397.9  484.80  5416.8  487.06  5507.1  494.28  5554.8  496.77  5617.5  498.59
#Mann=7,-1,0
  3838.6    0.16       0  4540.9    0.12       0  4979.3    0.07       0
  4991.5    0.12       0  5092.2    0.07       0  5255.8    0.12       0
  5397.9    0.16       0
Bank Sta=4119.4,5325.9
Exp/Cntr=0.3,0.1

Type RM Length L Ch R = 1,47511,556,556,556
BEGIN DESCRIPTION:
Mapping XS 19f0f226
END DESCRIPTION:
XS GIS Cut Line= 3
      2803046.32      7080721.57      2802747.70      7079159.02
      2802498.83      7078875.60
#Sta/Elev= 30
  3316.8  484.77  3639.1  483.28  3751.1  481.48  3822.4  481.67  3920.1  479.71
  4107.4  477.24  4203.5  478.30  4219.4  476.78  4229.6  477.55  4372.1  478.65
  4676.5  479.34  4791.7  479.62  4843.8  476.91  4890.8  479.07  4968.8  478.07
  4976.4  477.38  4983.0  473.33  4990.6  470.52  4991.2  467.79  4991.7  466.99
  5002.9  466.99  5003.4  467.79  5011.5  468.80  5019.1  470.99  5030.1  479.71
  5032.7  481.82  5040.0  485.18  5046.6  486.10  5108.4  488.97  5284.8  495.31
#Mann=5,-1,0
  3316.8    0.05       0  4676.5    0.12       0  4991.2    0.07       0
  5003.4    0.12       0  5108.4    0.16       0
Bank Sta=3920.1,5030.1
Exp/Cntr=0.3,0.1

Type RM Length L Ch R = 1,46955,807,807,807
BEGIN DESCRIPTION:
BIG CREEK 32.0
END DESCRIPTION:
XS GIS Cut Line= 4
      2803401.32      7079895.13      2803385.60      7079437.04
      2802824.09      7078943.75      2802325.01      7078575.01
#Sta/Elev= 30
  3788.8  482.55  3869.0  482.79  3960.6  478.97  4099.1  474.97  4149.1  476.76
  4291.3  476.48  4362.5  478.10  4426.1  476.67  4571.7  477.84  4652.9  476.47
  4695.5  478.11  4957.4  478.14  4979.2  475.33  4984.5  466.72  4985.0  465.92
  4996.2  465.92  4996.7  466.72  5006.5  467.48  5014.9  470.05  5021.1  476.86
  5024.4  478.97  5024.6  479.10  5029.5  482.21  5035.7  488.65  5067.7  489.85
  5145.7  492.79  5179.9  493.14  5348.2  498.89  5507.6  498.34  5615.1  500.11
#Mann=8,-1,0
  3788.8    0.05       0  4571.7    0.12       0  4984.5    0.07       0
  4996.7    0.12       0  5024.6    0.07       0  5067.7    0.05       0
  5145.7    0.12       0  5348.2    0.16       0
Bank Sta=3960.6,5024.4
Exp/Cntr=0.3,0.1

Type RM Length L Ch R = 1,46148,812,812,812
BEGIN DESCRIPTION:
double BIG CREEK 31.0
END DESCRIPTION:
XS GIS Cut Line= 4
      2804726.89      7080124.32      2803949.09      7079568.75
      2803278.55      7078975.00      2802829.26      7078575.63
#Sta/Elev= 30
  3043.8  494.49  3095.3  486.87  3188.2  482.68  3729.5  477.45  3952.2  477.89
  3968.5  477.33  3977.1  470.51  3977.2  464.68  3977.7  463.88  3989.4  464.68
  3998.0  473.73  4019.0  476.50  4125.3  476.91  4366.1  475.69  4385.9  472.24
  4486.1  476.67  4537.5  475.13  4657.2  478.23  4706.5  475.71  4940.2  477.27
  4961.6  476.44  4996.7  464.88  5004.3  465.73  5011.0  472.82  5018.5  475.77
  5034.9  477.45  5048.5  478.57  5174.0  481.11  5351.3  493.44  5496.4  491.06
#Mann=9,-1,0
  3043.8    0.05       0  3952.2    0.16       0  3977.2    0.07       0
  3989.4    0.16       0  4125.3    0.05       0  4385.9    0.12       0
  4486.1    0.16       0  4537.5    0.12       0  5048.5    0.05       0
Bank Sta=3729.5,5034.9
Exp/Cntr=0.3,0.1

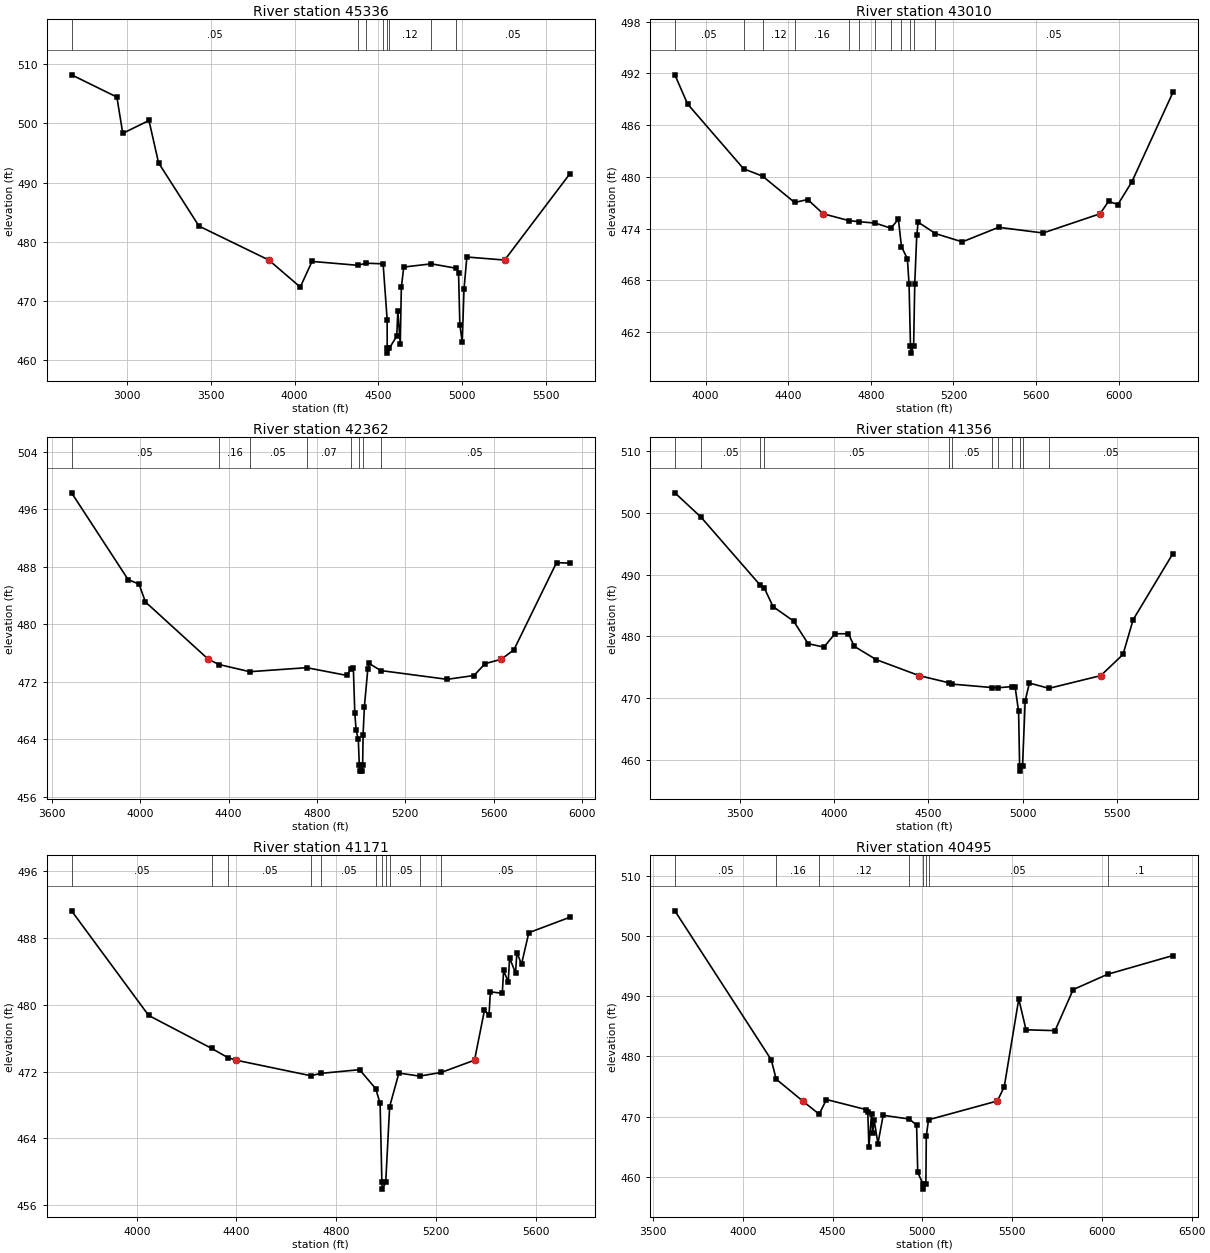
Type RM Length L Ch R = 1,45336,2326,2326,2326
BEGIN DESCRIPTION:
double BIG CREEK 30.0
END DESCRIPTION:
XS GIS Cut Line= 3
      2805175.03      7080475.03      2803675.00      7078675.00
      2803375.01      7078125.01
#Sta/Elev= 30
  2670.7  508.18  2940.8  504.43  2976.0  498.31  3132.2  500.48  3189.5  493.33
  3430.3  482.67  3846.8  476.94  4034.3  472.38  4104.6  476.71  4377.8  476.05
  4426.4  476.41  4528.3  476.30  4552.4  466.89  4552.7  462.04  4553.2  461.24
  4565.0  462.04  4609.6  464.11  4616.1  468.30  4630.5  462.77  4637.0  472.31
  4651.3  475.76  4816.0  476.30  4964.7  475.55  4978.0  474.80  4985.8  466.04
  5000.1  463.07  5010.6  472.01  5027.6  477.45  5253.0  476.94  5640.3  491.43
#Mann=8,-1,0
  2670.7    0.05       0  4377.8    0.12       0  4426.4    0.16       0
  4528.3    0.12       0  4552.7    0.03       0  4565.0    0.12       0
  4816.0    0.07       0  4964.7    0.05       0
Bank Sta=3846.8,5253
Exp/Cntr=0.3,0.1

Type RM Length L Ch R = 1,43010,648,648,648
BEGIN DESCRIPTION:
BIG CREEK 29.0
END DESCRIPTION:
XS GIS Cut Line= 3
      2805525.57      7079330.82      2804683.69      7078614.96
      2803529.72      7078000.19
#Sta/Elev= 30
  3850.8  491.84  3912.2  488.46  4183.5  480.95  4275.6  480.09  4430.9  477.04
  4494.3  477.38  4568.7  475.73  4693.4  474.94  4741.5  474.81  4820.9  474.65
  4896.8  474.06  4933.6  475.09  4948.4  471.92  4977.1  470.51  4985.2  467.55
  4992.1  460.37  4993.5  459.57  5007.3  460.37  5012.8  467.63  5022.4  473.21
  5029.1  474.76  5113.1  473.43  5243.1  472.47  5419.0  474.16  5634.2  473.50
  5910.6  475.73  5951.5  477.17  5996.8  476.80  6064.8  479.45  6263.4  489.80
#Mann=12,-1,0
  3850.8    0.05       0  4183.5    0.16       0  4275.6    0.12       0
  4430.9    0.16       0  4693.4    0.07       0  4741.5    0.05       0
  4820.9    0.12       0  4896.8    0.07       0  4948.4    0.12       0
  4992.1    0.07       0  5007.3    0.12       0  5113.1    0.05       0
Bank Sta=4568.7,5910.6
Exp/Cntr=0.3,0.1

Type RM Length L Ch R = 1,42362,1006,1006,1006
BEGIN DESCRIPTION:
Mapping XS 699f5577
END DESCRIPTION:
XS GIS Cut Line= 4
      2805747.71      7079082.64      2804824.09      7078325.69
      2804712.98      7078131.25      2804032.39      7077645.12
#Sta/Elev= 30
  3689.4  498.30  3945.5  486.22  3995.0  485.59  4023.7  483.11  4308.5  475.13
  4356.9  474.40  4496.1  473.40  4753.8  473.96  4934.2  472.89  4955.4  473.77
  4965.0  473.85  4971.6  467.62  4977.4  465.28  4987.4  463.97  4991.9  460.36
  4993.3  459.56  5005.7  459.56  5007.1  460.36  5009.0  464.60  5014.8  468.49
  5030.6  473.82  5036.4  474.55  5088.9  473.56  5389.4  472.34  5511.1  472.87
  5561.4  474.52  5634.2  475.13  5691.7  476.44  5884.6  488.58  5943.9  488.52
#Mann=8,-1,0
  3689.4    0.05       0  4356.9    0.16       0  4496.1    0.05       0
  4753.8    0.07       0  4955.4    0.12       0  4991.9    0.07       0
  5007.1    0.12       0  5088.9    0.05       0
Bank Sta=4308.5,5634.2
Exp/Cntr=0.3,0.1

Type RM Length L Ch R = 1,41356,185,185,185
BEGIN DESCRIPTION:
Mapping XS 07613938
END DESCRIPTION:
XS GIS Cut Line= 5
      2805858.81      7079047.93      2805678.25      7078110.41
      2805456.03      7077846.52      2804921.31      7077617.36
      2804219.99      7077332.66
#Sta/Elev= 30
  3157.1  503.22  3295.6  499.28  3610.5  488.24  3630.6  487.84  3677.0  484.82
  3785.9  482.48  3862.8  478.82  3946.7  478.27  4005.3  480.43  4076.6  480.43
  4107.2  478.40  4223.9  476.24  4450.7  473.66  4608.6  472.50  4622.8  472.29
  4836.2  471.73  4871.4  471.70  4942.9  471.88  4959.8  471.77  4977.9  467.87
  4983.4  459.01  4984.8  458.21  4998.8  459.01  5012.8  469.60  5035.2  472.45
  5139.1  471.60  5413.4  473.66  5531.1  477.08  5584.8  482.70  5795.5  493.40
#Mann=12,-1,0
  3157.1    0.08       0  3295.6    0.05       0  3610.5    0.08       0
  3630.6    0.05       0  4608.6    0.08       0  4622.8    0.05       0
  4836.2    0.12       0  4871.4    0.05       0  4942.9    0.12       0
  4983.4    0.07       0  4998.8    0.12       0  5139.1    0.05       0
Bank Sta=4450.7,5413.4
Exp/Cntr=0.3,0.1

Type RM Length L Ch R = 1,41171,676,676,676
BEGIN DESCRIPTION:
Mapping XS f1a8231e
END DESCRIPTION:
XS GIS Cut Line= 4
      2806053.27      7078193.77      2805678.25      7077804.86
      2805046.31      7077471.52      2804359.42      7077187.06
#Sta/Elev= 30
  3738.3  491.25  4047.4  478.73  4300.1  474.78  4365.8  473.67  4398.2  473.37
  4697.7  471.51  4739.0  471.79  4893.8  472.23  4958.5  469.96  4976.2  468.19
  4983.3  458.73  4984.7  457.93  4998.7  458.73  5014.5  467.81  5051.6  471.83
  5134.3  471.46  5221.5  471.90  5355.0  473.37  5394.9  479.34  5413.2  478.78
  5418.6  481.55  5466.4  481.38  5471.8  484.11  5490.3  482.74  5495.7  485.62
  5519.6  483.80  5525.0  486.26  5543.5  484.86  5572.8  488.63  5736.5  490.47
#Mann=11,-1,0
  3738.3    0.05       0  4300.1     0.1       0  4365.8    0.05       0
  4697.7    0.08       0  4739.0    0.05       0  4958.5    0.12       0
  4983.3    0.07       0  4998.7    0.12       0  5014.5    0.05       0
  5134.3    0.08       0  5221.5    0.05       0
Bank Sta=4398.2,5355
Exp/Cntr=0.3,0.1

Type RM Length L Ch R = 1,40495,1331,1331,1331
BEGIN DESCRIPTION:
BIG CREEK 26.0
END DESCRIPTION:
XS GIS Cut Line= 3
      2806475.01      7077775.01      2805375.00      7076975.00
      2803974.97      7076775.00
#Sta/Elev= 30
  3621.3  504.16  4158.0  479.45  4185.6  476.23  4333.0  472.61  4425.0  470.41
  4465.6  472.85  4687.4  471.17  4695.9  470.82  4702.1  464.97  4716.8  470.44
  4723.0  467.30  4731.5  469.44  4752.3  465.52  4781.7  470.23  4927.7  469.61
  4967.9  468.59  4974.1  460.77  5004.1  458.78  5005.5  457.98  5019.5  458.78
  5021.9  466.82  5034.3  469.49  5418.0  472.61  5456.2  474.99  5537.0  489.53
  5577.4  484.42  5739.1  484.28  5840.1  491.09  6031.7  493.63  6395.7  496.74
#Mann=8,-1,0
  3621.3    0.05       0  4185.6    0.16       0  4425.0    0.12       0
  4927.7    0.07       0  5004.1    0.07       0  5019.5    0.07       0
  5034.3    0.05       0  6031.7     0.1       0
Bank Sta=4333,5418
Exp/Cntr=0.3,0.1

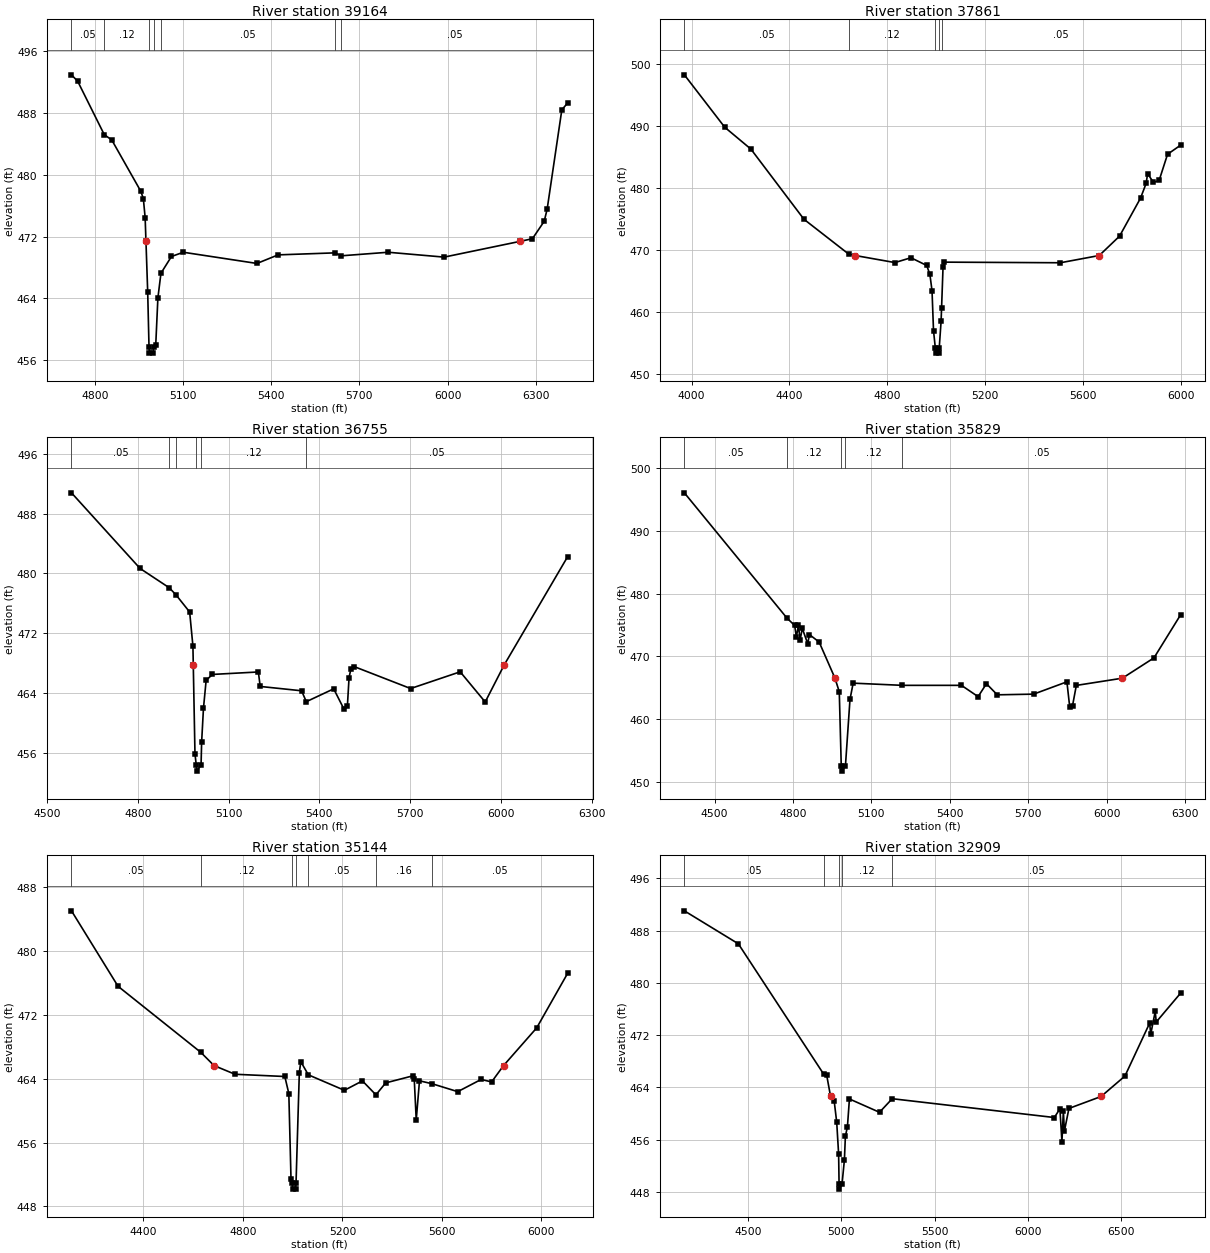
Type RM Length L Ch R = 1,39164,1303,1303,1303
BEGIN DESCRIPTION:
Mapping XS 7c7fc799
END DESCRIPTION:
XS GIS Cut Line= 4
      2806497.73      7077061.82      2806268.53      7076902.08
      2805844.92      7076728.47      2804894.94      7076679.93
#Sta/Elev= 30
  4720.3  492.95  4741.4  492.12  4831.8  485.21  4857.5  484.51  4956.1  477.88
  4964.8  476.93  4970.9  474.47  4973.7  471.41  4979.6  464.85  4984.1  457.72
  4985.6  456.92  4998.1  456.92  4999.6  457.72  5007.0  457.99  5014.3  464.07
  5024.7  467.26  5060.4  469.43  5100.8  469.98  5351.3  468.53  5423.3  469.64
  5616.2  469.90  5638.4  469.52  5797.8  469.98  5988.1  469.35  6247.7  471.40
  6288.5  471.73  6328.5  473.98  6338.6  475.54  6388.6  488.42  6408.7  489.32
#Mann=7,-1,0
  4720.3    0.05       0  4831.8    0.12       0  4984.1    0.07       0
  4999.6    0.12       0  5024.7    0.05       0  5616.2    0.07       0
  5638.4    0.05       0
Bank Sta=4973.7,6247.7
Exp/Cntr=0.3,0.1

Type RM Length L Ch R = 1,37861,1106,1106,1106
BEGIN DESCRIPTION:
BIG CREEK 24.0
END DESCRIPTION:
XS GIS Cut Line= 3
      2807125.04      7076675.03      2806283.64      7076082.14
      2805365.76      7075686.80
#Sta/Elev= 30
  3970.7  498.23  4135.8  489.78  4242.9  486.25  4459.7  474.94  4642.1  469.34
  4669.1  469.10  4831.6  467.96  4897.0  468.74  4961.6  467.49  4974.5  466.04
  4983.2  463.43  4989.3  456.97  4996.8  454.16  4998.4  453.36  5011.0  453.36
  5012.6  454.16  5020.3  458.50  5022.2  460.59  5028.2  467.18  5033.7  468.03
  5507.9  467.93  5666.9  469.10  5749.8  472.22  5835.6  478.35  5858.7  480.75
  5864.5  482.32  5888.1  480.88  5911.6  481.20  5946.0  485.42  5999.4  486.89
#Mann=5,-1,0
  3970.7    0.05       0  4642.1    0.12       0  4996.8    0.07       0
  5012.6    0.12       0  5022.2    0.05       0
Bank Sta=4669.1,5666.9
Exp/Cntr=0.3,0.1

Type RM Length L Ch R = 1,36755,926,926,926
BEGIN DESCRIPTION:
Mapping XS 7f453781
END DESCRIPTION:
XS GIS Cut Line= 4
      2807171.29      7076283.99      2807004.64      7075895.14
      2806810.20      7075617.36      2806019.27      7075235.77
#Sta/Elev= 30
  4580.8  490.78  4807.6  480.65  4903.8  478.07  4926.4  477.11  4971.4  474.82
  4982.2  470.27  4983.4  467.75  4989.0  455.81  4993.3  454.31  4994.9  453.51
  5009.1  454.31  5011.0  457.40  5017.1  461.95  5025.9  465.67  5046.8  466.46
  5198.5  466.79  5204.6  464.85  5341.3  464.27  5357.0  462.81  5447.5  464.53
  5481.9  461.78  5492.7  462.17  5498.3  466.03  5504.1  467.14  5515.2  467.51
  5701.8  464.57  5865.6  466.81  5948.3  462.77  6011.3  467.75  6221.1  482.25
#Mann=6,-1,0
  4580.8    0.05       0  4903.8    0.16       0  4926.4    0.12       0
  4993.3    0.07       0  5009.1    0.12       0  5357.0    0.05       0
Bank Sta=4983.4,6011.3
Exp/Cntr=0.3,0.1

Type RM Length L Ch R = 1,35829,685,685,685
BEGIN DESCRIPTION:
Mapping XS 1cba9c3c
END DESCRIPTION:
XS GIS Cut Line= 3
      2807817.15      7075693.75      2807337.98      7075332.64
      2806115.73      7074895.13
#Sta/Elev= 30
  4384.6  496.06  4776.3  476.14  4806.5  474.92  4813.0  473.10  4821.1  474.95
  4827.3  472.57  4835.6  474.46  4856.5  472.03  4863.1  473.47  4900.2  472.28
  4960.8  466.52  4977.2  464.35  4984.8  452.51  4986.5  451.71  5000.7  452.51
  5018.2  463.15  5030.3  465.73  5218.5  465.38  5444.5  465.38  5508.2  463.58
  5540.1  465.64  5581.6  463.87  5720.6  463.98  5847.9  465.94  5858.7  461.92
  5869.3  462.11  5883.9  465.37  6060.0  466.52  6181.0  469.76  6282.8  476.62
#Mann=5,-1,0
  4384.6    0.05       0  4776.3    0.12       0  4984.8    0.07       0
  5000.7    0.12       0  5218.5    0.05       0
Bank Sta=4960.8,6060
Exp/Cntr=0.3,0.1

Type RM Length L Ch R = 1,35144,2235,2235,2235
BEGIN DESCRIPTION:
Mapping XS e8b0dbb0
END DESCRIPTION:
XS GIS Cut Line= 3
      2808032.39      7075200.67      2807254.64      7074777.08
      2806324.09      7074172.91
#Sta/Elev= 30
  4110.5  485.05  4297.7  475.59  4630.4  467.31  4683.6  465.65  4768.0  464.56
  4968.2  464.28  4984.3  462.14  4993.1  451.40  4997.4  450.96  4999.1  450.16
  5011.7  450.16  5013.3  450.96  5026.5  464.73  5032.5  466.14  5062.7  464.49
  5207.7  462.55  5280.2  463.73  5334.5  461.98  5373.8  463.48  5482.6  464.36
  5488.5  463.98  5496.5  458.84  5509.6  463.74  5560.5  463.37  5663.4  462.38
  5757.4  463.91  5799.6  463.60  5847.6  465.65  5980.9  470.38  6105.6  477.24
#Mann=7,-1,0
  4110.5    0.05       0  4630.4    0.12       0  4997.4    0.07       0
  5013.3    0.12       0  5062.7    0.05       0  5334.5    0.16       0
  5560.5    0.05       0
Bank Sta=4683.6,5847.6
Exp/Cntr=0.3,0.1

Type RM Length L Ch R = 1,32909,646,646,646
BEGIN DESCRIPTION:
BIG CREEK 21.0
END DESCRIPTION:
XS GIS Cut Line= 3
      2808375.01      7075125.04      2808155.13      7074289.92
      2806483.06      7073630.19
#Sta/Elev= 30
  4158.3  491.03  4447.8  485.98  4904.6  466.05  4921.3  465.90  4942.5  462.59
  4961.6  461.94  4975.3  458.66  4985.6  453.75  4988.0  449.20  4989.7  448.40
  5003.9  449.20  5016.6  452.88  5021.8  456.48  5032.8  457.96  5043.5  462.21
  5204.8  460.17  5272.9  462.25  6142.1  459.37  6172.3  460.69  6183.0  455.69
  6190.8  460.32  6196.2  457.29  6220.6  460.76  6393.0  462.59  6520.9  465.72
  6653.6  473.84  6658.9  472.09  6683.3  475.62  6688.7  474.00  6819.4  478.42
#Mann=5,-1,0
  4158.3    0.05       0  4904.6    0.12       0  4988.0    0.07       0
  5003.9    0.12       0  5272.9    0.05       0
Bank Sta=4942.5,6393
Exp/Cntr=0.3,0.1

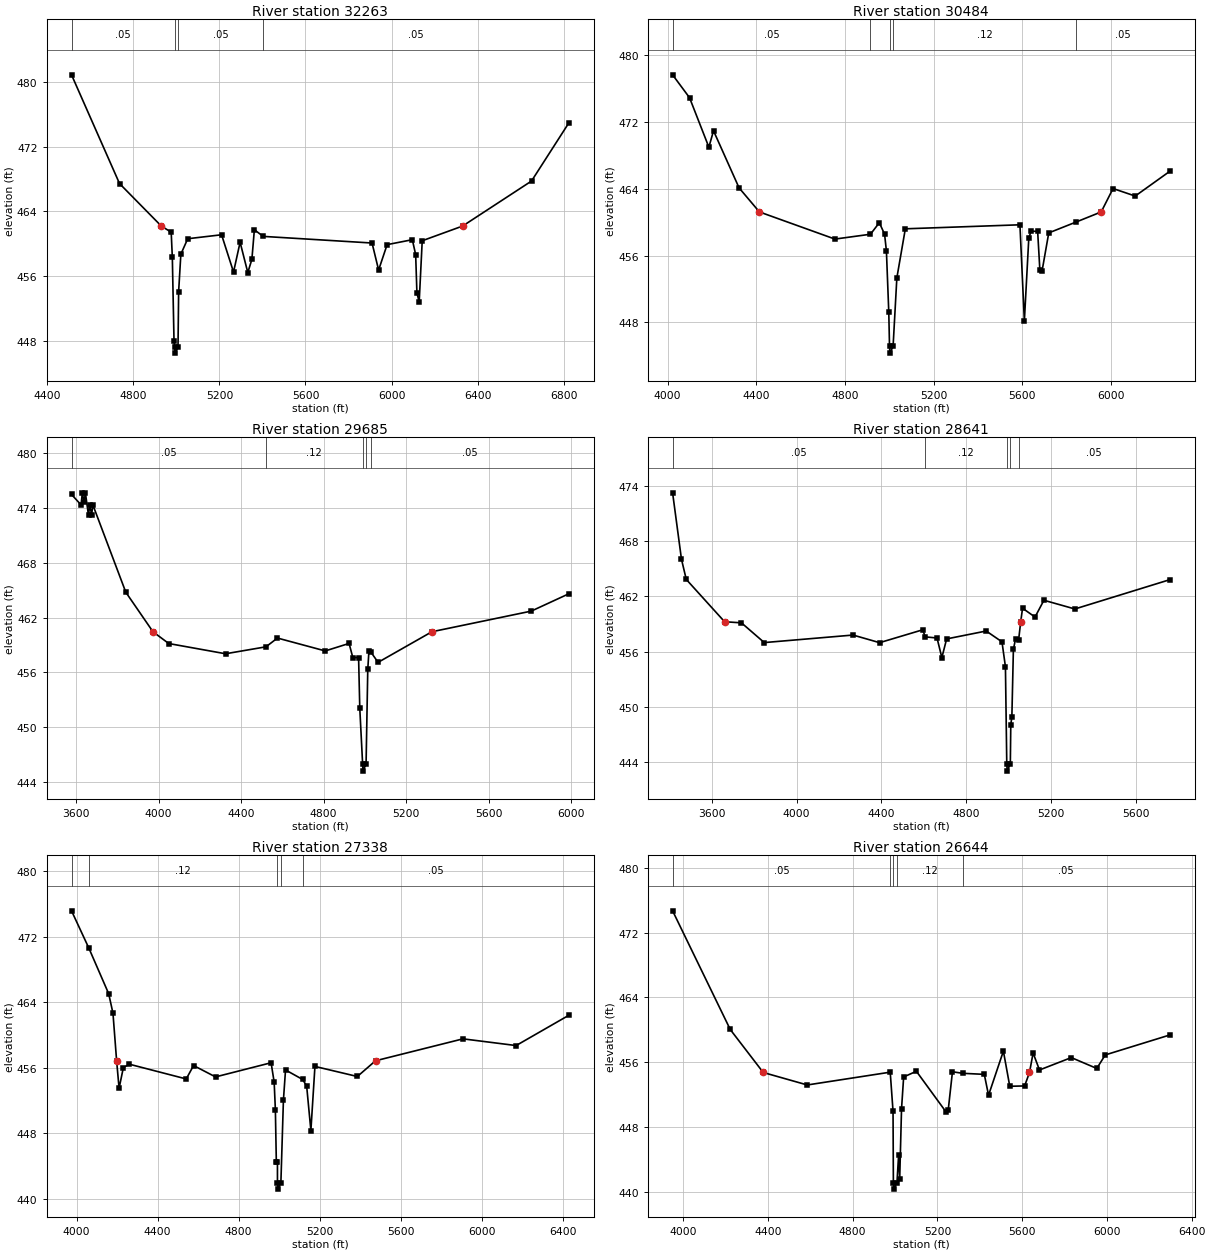
Type RM Length L Ch R = 1,32263,1779,1779,1779
BEGIN DESCRIPTION:
Mapping XS 55c91563
END DESCRIPTION:
XS GIS Cut Line= 3
      2808796.32      7073999.30      2808324.09      7073839.58
      2806622.67      7073214.57
#Sta/Elev= 30
  4512.4  480.87  4735.5  467.43  4929.7  462.18  4975.7  461.42  4981.0  458.31
  4988.8  447.96  4991.4  447.27  4993.1  446.47  5007.4  447.27  5010.3  454.08
  5020.6  458.70  5052.6  460.61  5209.9  461.10  5265.5  456.49  5296.0  460.18
  5331.8  456.43  5350.8  458.06  5362.3  461.72  5403.3  460.90  5909.4  460.08
  5939.9  456.74  5979.4  459.88  6096.6  460.49  6112.1  458.65  6117.9  453.92
  6128.5  452.79  6142.6  460.36  6330.5  462.18  6650.6  467.74  6823.5  474.90
#Mann=4,-1,0
  4512.4    0.05       0  4991.4    0.07       0  5007.4    0.05       0
  5403.3    0.05       0
Bank Sta=4929.7,6330.5
Exp/Cntr=0.3,0.1

Type RM Length L Ch R = 1,30484,799,799,799
BEGIN DESCRIPTION:
Mapping XS 62da19d6
END DESCRIPTION:
XS GIS Cut Line= 4
      2809004.65      7073561.80      2808254.64      7073061.80
      2808011.59      7073152.08      2806929.16      7073110.45
#Sta/Elev= 30
  4022.4  477.64  4098.9  474.90  4186.1  468.98  4207.1  470.94  4322.4  464.11
  4414.2  461.23  4755.1  457.98  4915.4  458.56  4955.4  459.94  4979.1  458.57
  4987.4  456.56  4998.1  449.22  5001.4  445.13  5003.1  444.33  5017.5  445.13
  5034.5  453.33  5072.8  459.21  5590.0  459.69  5610.0  448.18  5630.0  458.08
  5640.0  458.92  5670.0  458.91  5680.0  454.26  5690.0  454.18  5720.1  458.72
  5844.3  460.03  5956.8  461.23  6010.3  464.03  6110.3  463.13  6266.3  466.09
#Mann=5,-1,0
  4022.4    0.05       0  4915.4    0.12       0  5001.4    0.07       0
  5017.5    0.12       0  5844.3    0.05       0
Bank Sta=4414.2,5956.8
Exp/Cntr=0.3,0.1

Type RM Length L Ch R = 1,29685,1044,1044,1044
BEGIN DESCRIPTION:
Mapping XS 9a81c411
END DESCRIPTION:
XS GIS Cut Line= 3
      2809018.54      7073485.42      2807879.64      7072735.41
      2806949.58      7072256.50
#Sta/Elev= 30
  3578.3  475.48  3624.5  474.34  3630.5  475.61  3639.6  474.67  3645.5  475.66
  3660.6  473.19  3666.6  474.36  3675.7  473.27  3681.7  474.34  3841.3  464.78
  3973.1  460.45  4049.5  459.16  4324.9  458.04  4520.8  458.80  4576.4  459.76
  4808.1  458.35  4923.6  459.17  4941.8  457.62  4969.7  457.63  4975.5  452.06
  4989.2  445.99  4991.2  445.19  5006.0  445.99  5014.2  456.32  5019.8  458.34
  5029.7  458.21  5064.2  457.10  5325.1  460.45  5806.7  462.71  5988.1  464.60
#Mann=5,-1,0
  3578.3    0.05       0  4520.8    0.12       0  4989.2    0.07       0
  5006.0    0.12       0  5029.7    0.05       0
Bank Sta=3973.1,5325.1
Exp/Cntr=0.3,0.1

Type RM Length L Ch R = 1,28641,1303,1303,1303
BEGIN DESCRIPTION:
Mapping XS 09948bee
END DESCRIPTION:
XS GIS Cut Line= 3
      2809254.63      7072839.57      2807824.09      7072152.08
      2807082.76      7071999.66
#Sta/Elev= 30
  3415.2  473.29  3457.0  466.06  3479.6  463.86  3660.3  459.25  3739.8  459.13
  3847.4  456.98  4266.0  457.80  4391.1  456.97  4594.0  458.37  4606.7  457.60
  4661.9  457.48  4684.6  455.34  4707.2  457.38  4893.8  458.24  4968.1  457.06
  4984.4  454.35  4990.7  443.78  4992.7  442.98  5007.5  443.78  5009.6  448.05
  5014.7  448.87  5021.9  456.24  5032.1  457.38  5046.5  457.25  5056.4  459.25
  5065.1  460.72  5123.9  459.76  5165.8  461.59  5311.7  460.64  5759.2  463.83
#Mann=5,-1,0
  3415.2    0.05       0  4606.7    0.12       0  4990.7    0.07       0
  5007.5    0.12       0  5046.5    0.05       0
Bank Sta=3660.3,5056.4
Exp/Cntr=0.3,0.1

Type RM Length L Ch R = 1,27338,694,694,694
BEGIN DESCRIPTION:
Mapping XS 7520acbc
END DESCRIPTION:
XS GIS Cut Line= 3
      2809483.80      7072360.41      2808636.59      7071804.86
      2807254.67      7071395.14
#Sta/Elev= 30
  3975.3  475.18  4061.5  470.59  4158.8  465.05  4179.9  462.67  4197.9  456.86
  4210.1  453.50  4231.2  456.03  4260.9  456.44  4541.6  454.64  4577.8  456.28
  4686.3  454.89  4960.6  456.62  4975.7  454.25  4981.7  450.87  4986.4  444.48
  4991.9  444.48  4992.0  441.98  4994.0  441.18  5008.9  441.98  5021.4  452.05
  5031.8  455.74  5116.1  454.58  5136.1  453.78  5157.0  448.34  5177.0  456.17
  5386.4  454.94  5476.0  456.86  5907.9  459.54  6170.2  458.72  6429.8  462.41
#Mann=5,-1,0
  3975.3    0.05       0  4061.5    0.12       0  4992.0    0.07       0
  5008.9    0.12       0  5116.1    0.05       0
Bank Sta=4197.9,5476
Exp/Cntr=0.3,0.1

Type RM Length L Ch R = 1,26644,1271,1271,1271
BEGIN DESCRIPTION:
Mapping XS 45d7c825
END DESCRIPTION:
XS GIS Cut Line= 3
      2809872.66      7071603.46      2808928.25      7071284.02
      2807581.08      7071207.64
#Sta/Elev= 30
  3950.4  474.69  4222.4  460.04  4378.2  454.73  4586.0  453.19  4977.4  454.77
  4990.7  449.94  4992.3  441.13  4994.3  440.33  5009.2  441.13  5017.1  444.56
  5022.1  441.56  5030.8  450.25  5040.8  454.18  5100.9  454.88  5241.1  449.85
  5251.1  450.09  5271.1  454.82  5319.2  454.63  5421.4  454.50  5441.4  451.92
  5511.5  457.37  5541.6  453.03  5611.7  453.07  5634.7  454.73  5651.7  457.14
  5681.8  455.04  5832.0  456.57  5952.2  455.23  5992.3  456.90  6296.7  459.36
#Mann=5,-1,0
  3950.4    0.05       0  4977.4    0.12       0  4992.3    0.07       0
  5009.2    0.12       0  5319.2    0.05       0
Bank Sta=4378.2,5634.7
Exp/Cntr=0.3,0.1