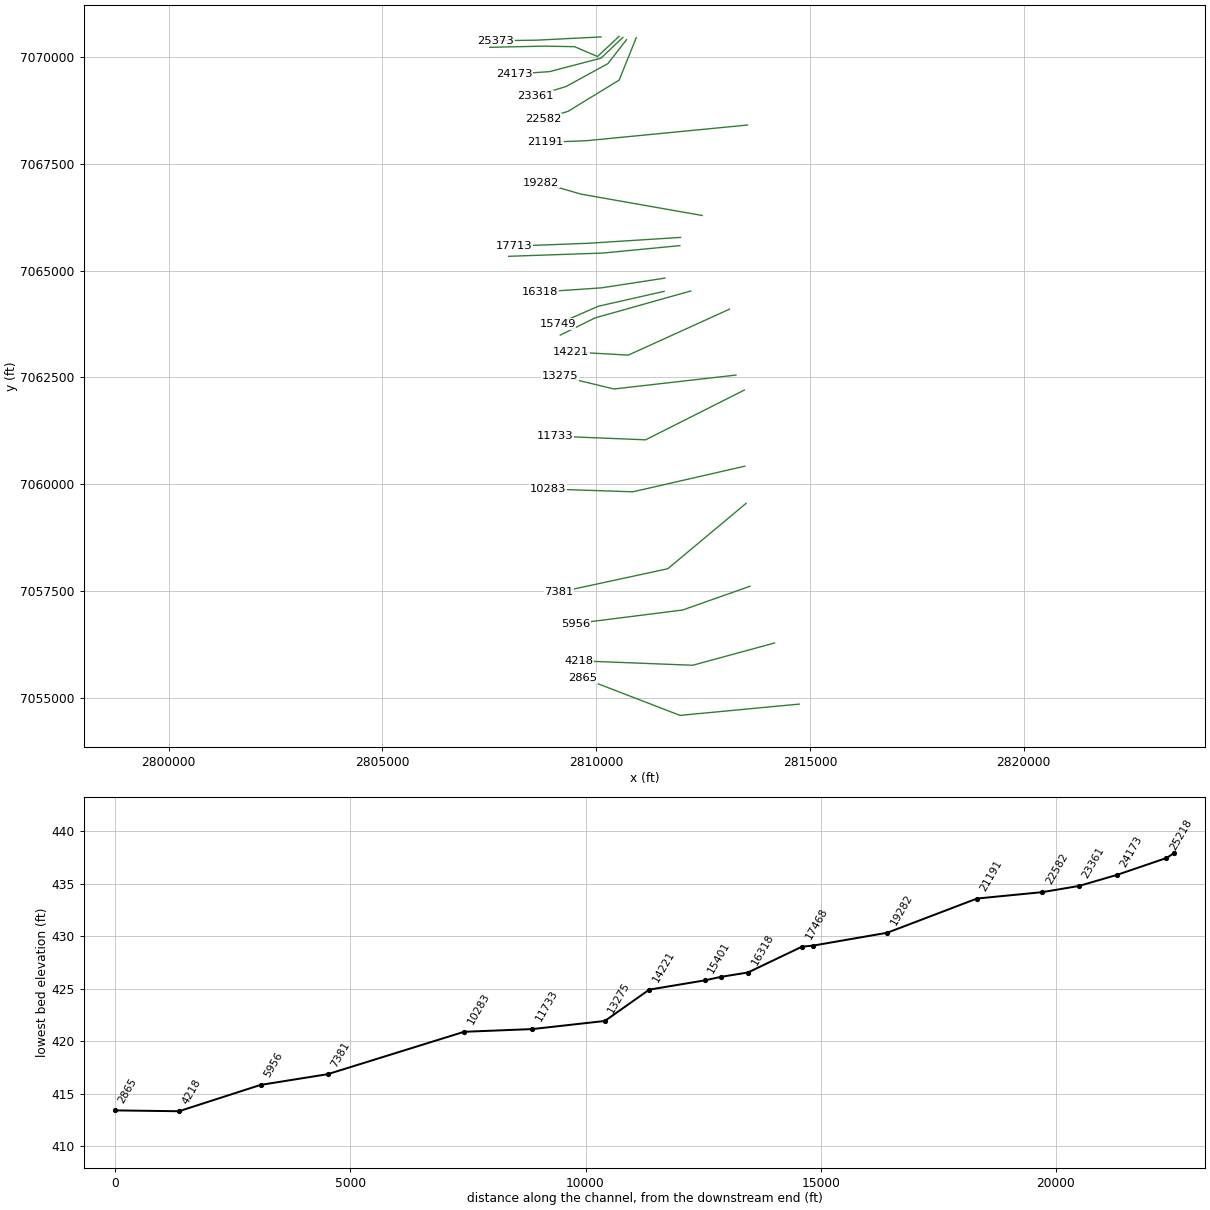
HEC-RAS study BIG CREEK.prj: BIG CREEK Base Level Engineering

--- BIG CREEK.g01 (geometry) --- (continued)

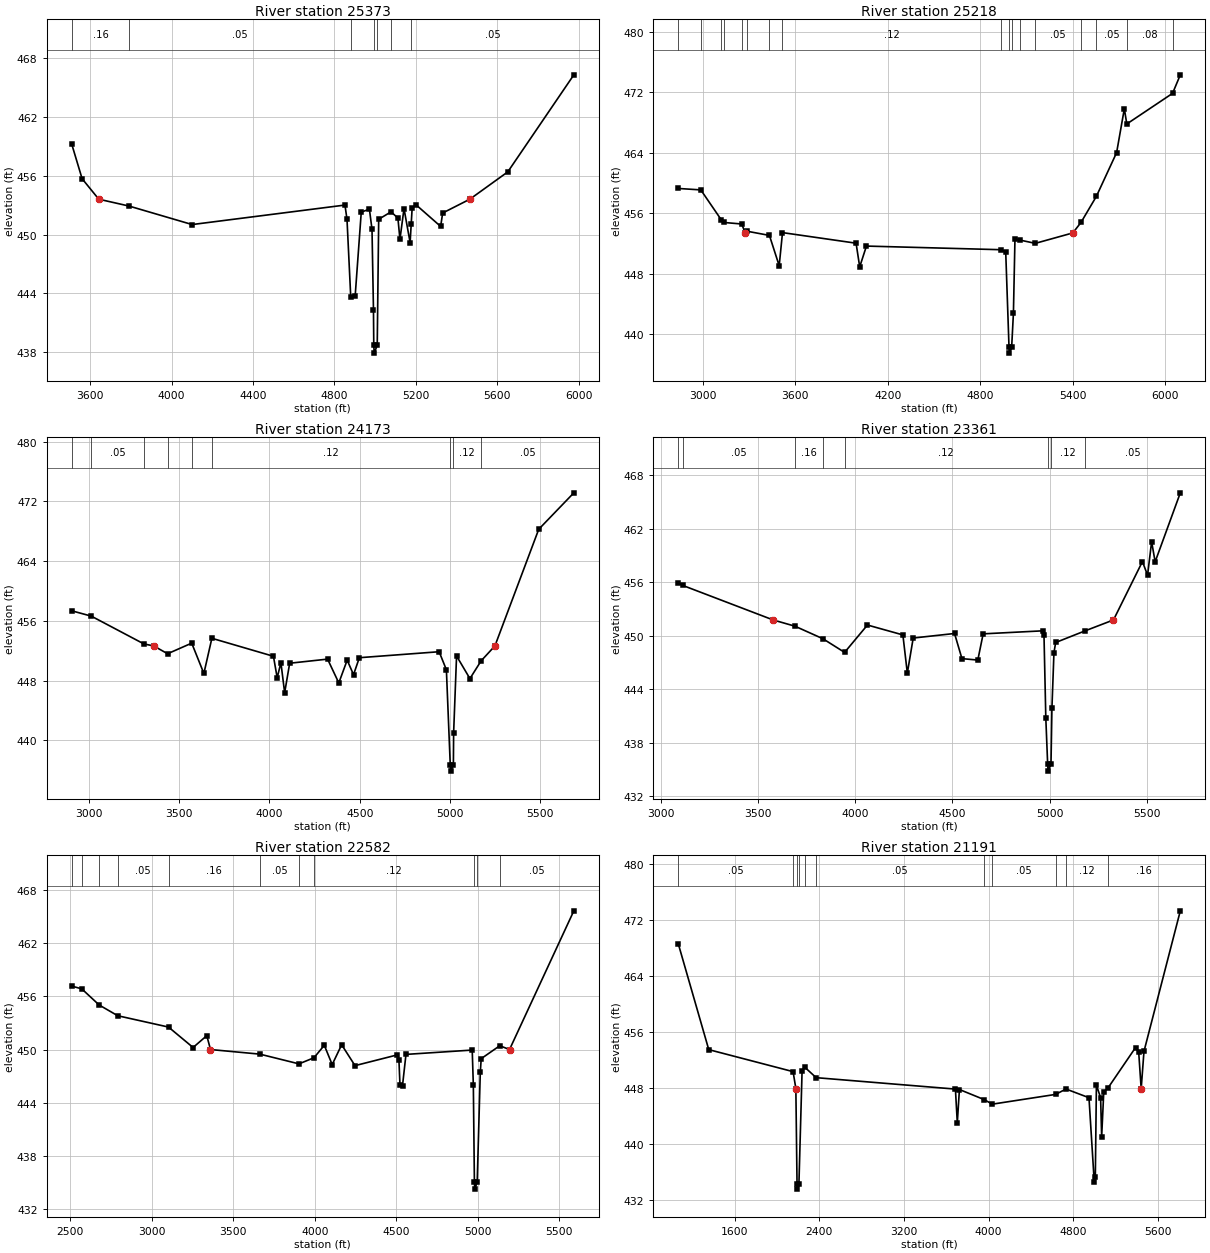
Type RM Length L Ch R = 1,25373,155,155,155
BEGIN DESCRIPTION:
Mapping XS c7361c4b
END DESCRIPTION:
XS GIS Cut Line= 3
      2810115.73      7070464.58      2808608.81      7070388.19
      2807650.47      7070374.30
#Sta/Elev= 30
  3509.2  459.24  3560.0  455.72  3641.9  453.63  3790.4  452.93  4100.7  451.04
  4851.7  453.03  4861.7  451.58  4880.2  443.62  4901.7  443.70  4931.8  452.31
  4971.8  452.61  4984.6  450.56  4991.8  442.32  4993.3  438.71  4995.4  437.91
  5010.3  438.71  5017.5  451.58  5078.3  452.34  5111.9  451.70  5121.9  449.53
  5141.9  452.67  5171.9  449.20  5177.4  451.14  5181.9  452.73  5201.9  453.04
  5321.9  450.85  5331.9  452.22  5465.5  453.63  5651.9  456.42  5976.5  466.33
#Mann=7,-1,0
  3509.2    0.16       0  3790.4    0.05       0  4880.2    0.07       0
  4993.3    0.07       0  5010.3    0.07       0  5078.3    0.12       0
  5177.4    0.05       0
Bank Sta=3641.9,5465.5
Exp/Cntr=0.3,0.1

Type RM Length L Ch R = 1,25218,1045,1045,1045
BEGIN DESCRIPTION:
Mapping XS cff7b81d
END DESCRIPTION:
XS GIS Cut Line= 6
      2810538.09      7070478.27      2810032.42      7070006.25
      2809497.70      7070235.41      2808789.37      7070249.30
      2808504.64      7070242.36      2807511.54      7070221.52
#Sta/Elev= 30
  2839.6  459.25  2986.2  459.06  3118.8  455.11  3137.6  454.75  3251.4  454.55
  3275.0  453.37  3284.6  453.60  3431.7  453.04  3495.1  449.03  3516.6  453.41
  3994.4  452.01  4017.9  448.88  4061.6  451.63  4932.6  451.15  4966.0  450.87
  4987.4  438.27  4989.6  437.47  5004.6  438.27  5016.0  442.73  5026.0  452.54
  5059.1  452.42  5158.1  451.99  5401.9  453.37  5455.2  454.77  5554.3  458.19
  5686.1  463.99  5736.2  469.79  5752.3  467.78  6049.4  471.83  6099.7  474.28
#Mann=17,-1,0
  2839.6    0.16       0  2986.2    0.05       0  3118.8    0.08       0
  3137.6    0.05       0  3251.4    0.08       0  3284.6    0.05       0
  3431.7    0.08       0  3516.6    0.12       0  4932.6    0.05       0
  4987.4    0.04       0  5004.6    0.05       0  5059.1    0.08       0
  5158.1    0.05       0  5455.2    0.08       0  5554.3    0.05       0
  5752.3    0.08       0  6049.4    0.05       0
Bank Sta=3275,5401.9
Exp/Cntr=0.3,0.1

Type RM Length L Ch R = 1,24173,812,812,812
BEGIN DESCRIPTION:
Mapping XS 25cac6d4
END DESCRIPTION:
XS GIS Cut Line= 4
      2810624.91      7070452.24      2810112.52      7069967.10
      2808907.42      7069652.08      2808081.00      7069596.52
#Sta/Elev= 30
  2905.7  457.34  3013.5  456.63  3305.4  452.90  3359.1  452.64  3436.2  451.59
  3569.7  453.01  3637.0  448.95  3681.3  453.66  4022.2  451.25  4042.9  448.37
  4063.5  450.40  4084.2  446.36  4112.0  450.32  4321.9  450.87  4384.0  447.68
  4430.3  450.73  4465.6  448.79  4497.7  451.06  4939.5  451.86  4979.6  449.44
  5001.1  436.67  5003.3  435.87  5018.3  436.67  5019.7  441.02  5035.9  451.29
  5109.9  448.26  5171.9  450.64  5248.3  452.64  5490.8  468.26  5685.2  473.14
#Mann=9,-1,0
  2905.7    0.16       0  3013.5    0.05       0  3305.4    0.16       0
  3436.2    0.05       0  3569.7    0.08       0  3681.3    0.12       0
  5001.1    0.07       0  5018.3    0.12       0  5171.9    0.05       0
Bank Sta=3359.1,5248.3
Exp/Cntr=0.3,0.1

Type RM Length L Ch R = 1,23361,779,779,779
BEGIN DESCRIPTION:
Mapping XS 446c1a6e
END DESCRIPTION:
XS GIS Cut Line= 4
      2810711.76      7070400.21      2810272.69      7069837.88
      2809296.31      7069304.86      2808574.06      7069082.63
#Sta/Elev= 30
  3089.9  455.93  3113.4  455.64  3577.9  451.77  3689.9  451.07  3833.9  449.66
  3945.3  448.13  4062.7  451.20  4245.0  450.09  4267.8  445.80  4298.0  449.74
  4510.6  450.25  4548.6  447.43  4630.2  447.27  4657.7  450.21  4965.2  450.55
  4970.5  450.04  4979.9  440.73  4989.3  435.61  4991.5  434.81  5006.5  435.61
  5011.3  441.88  5021.7  448.11  5030.6  449.24  5182.2  450.55  5327.8  451.77
  5476.6  458.32  5503.0  456.79  5523.9  460.55  5542.0  458.29  5671.4  466.03
#Mann=8,-1,0
  3089.9    0.16       0  3113.4    0.05       0  3689.9    0.16       0
  3833.9    0.05       0  3945.3    0.12       0  4989.3    0.07       0
  5006.5    0.12       0  5182.2    0.05       0
Bank Sta=3577.9,5327.8
Exp/Cntr=0.3,0.1

Type RM Length L Ch R = 1,22582,1391,1391,1391
BEGIN DESCRIPTION:
Mapping XS 60b2edb5
END DESCRIPTION:
XS GIS Cut Line= 4
      2810937.44      7070443.61      2810538.12      7069453.99
      2809337.98      7068721.52      2808754.62      7068547.91
#Sta/Elev= 30
  2508.9  457.17  2570.2  456.86  2676.7  455.04  2791.1  453.82  3102.7  452.54
  3253.6  450.23  3337.7  451.57  3360.4  450.00  3663.3  449.48  3903.5  448.38
  3995.6  449.07  4058.9  450.48  4107.4  448.30  4165.5  450.54  4247.5  448.18
  4508.1  449.40  4516.9  448.87  4523.5  445.99  4539.0  445.92  4560.3  449.45
  4966.9  449.94  4973.8  445.95  4980.3  435.02  4982.5  434.22  4997.5  435.02
  5016.5  447.45  5022.1  448.97  5136.0  450.43  5195.9  450.00  5590.7  465.68
#Mann=11,-1,0
  2508.9    0.16       0  2570.2    0.12       0  2676.7    0.16       0
  2791.1    0.05       0  3102.7    0.16       0  3663.3    0.05       0
  3903.5    0.16       0  3995.6    0.12       0  4980.3    0.07       0
  4997.5    0.12       0  5136.0    0.05       0
Bank Sta=3360.4,5195.9
Exp/Cntr=0.3,0.1

Type RM Length L Ch R = 1,21191,1909,1909,1909
BEGIN DESCRIPTION:
double BIG CREEK 11.0
END DESCRIPTION:
XS GIS Cut Line= 3
      2813542.39      7068403.96      2809755.51      7068035.04
      2808811.48      7068002.48
#Sta/Elev= 30
  1064.4  468.63  1353.1  453.51  2150.8  450.37  2177.0  447.96  2188.1  434.41
  2190.6  433.61  2206.1  434.41  2236.0  450.52  2262.1  450.99  2369.1  449.51
  3686.4  447.88  3704.2  443.07  3724.3  447.82  3957.1  446.39  4035.4  445.73
  4633.4  447.12  4732.7  447.89  4949.8  446.65  4999.8  434.61  5009.8  435.32
  5020.1  448.46  5059.8  446.65  5069.8  441.09  5089.8  447.51  5129.2  448.03
  5390.0  453.80  5420.0  453.19  5443.6  447.93  5470.1  453.26  5813.8  473.31
#Mann=11,-1,0
  1064.4    0.05       0  2150.8    0.07       0  2188.1    0.07       0
  2206.1    0.07       0  2262.1    0.12       0  2369.1    0.05       0
  3957.1    0.16       0  4035.4    0.05       0  4633.4    0.07       0
  4732.7    0.12       0  5129.2    0.16       0
Bank Sta=2177,5443.6
Exp/Cntr=0.3,0.1

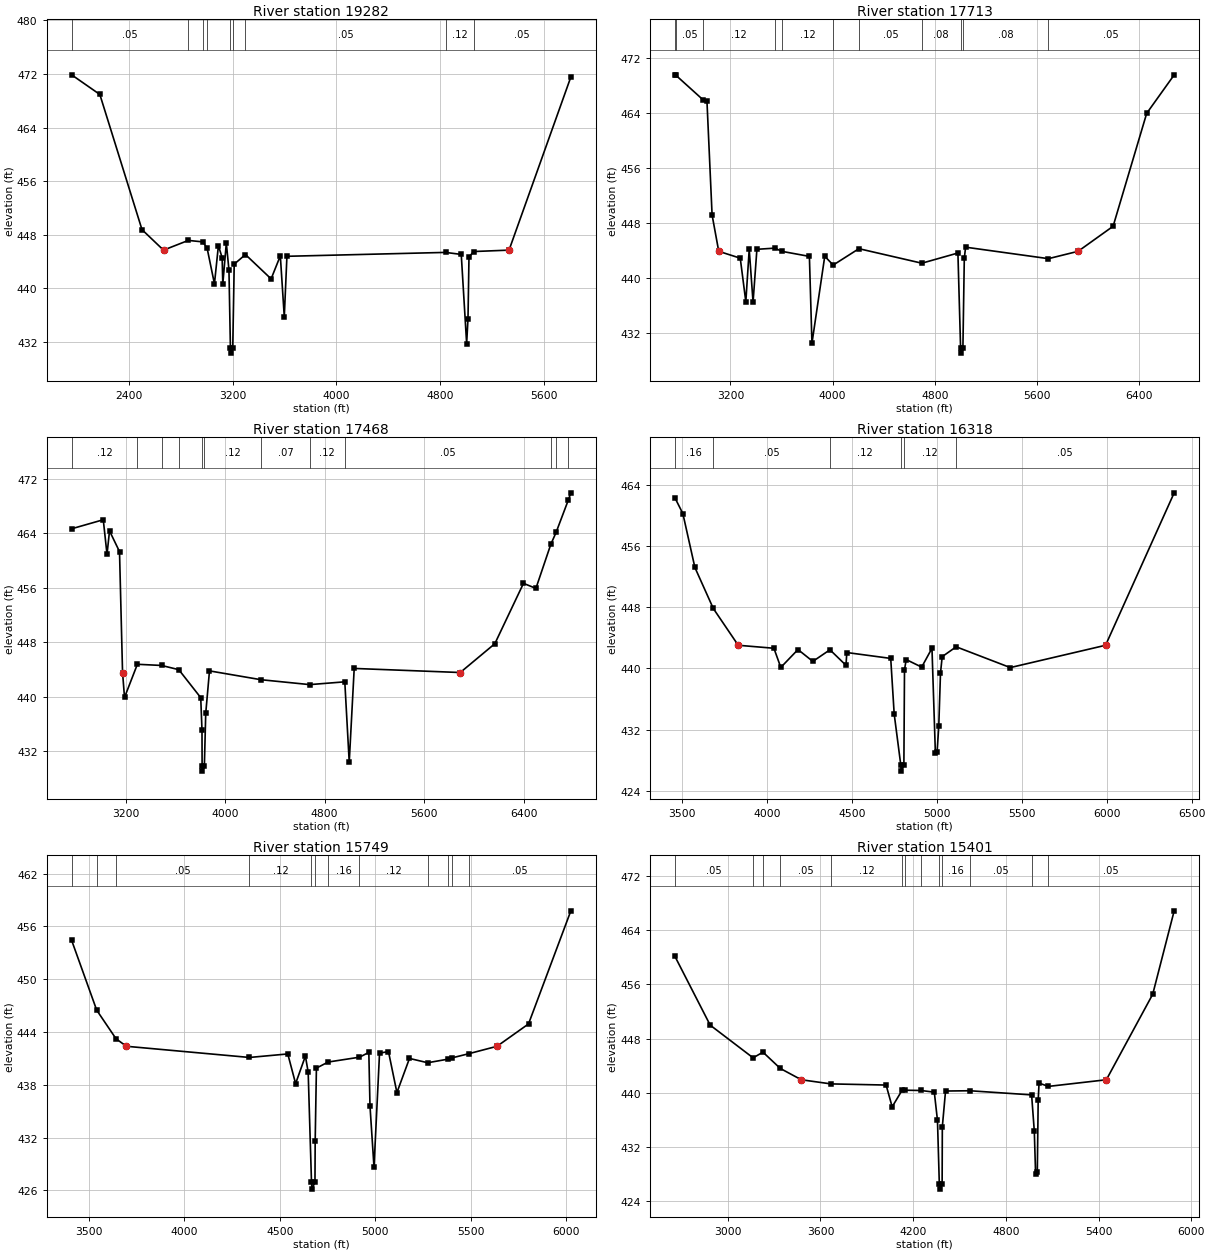
Type RM Length L Ch R = 1,19282,1569,1569,1569
BEGIN DESCRIPTION:
double BIG CREEK 10.0
END DESCRIPTION:
XS GIS Cut Line= 3
      2812479.07      7066288.07      2809647.00      7066787.21
      2808713.85      7067058.47
#Sta/Elev= 30
  1959.8  471.88  2177.2  468.95  2502.1  448.78  2667.9  445.72  2859.1  447.17
  2971.3  446.95  3004.2  445.99  3060.5  440.69  3091.0  446.40  3119.8  444.59
  3124.9  440.66  3152.0  446.77  3172.3  442.75  3183.6  431.15  3186.1  430.35
  3201.6  431.15  3212.9  443.63  3299.5  445.06  3497.2  441.43  3568.3  444.87
  3598.7  435.76  3619.1  444.80  4841.6  445.38  4962.6  445.08  5004.2  431.76
  5014.6  435.49  5022.2  444.67  5057.4  445.51  5330.9  445.72  5807.3  471.56
#Mann=9,-1,0
  1959.8    0.05       0  2859.1    0.12       0  2971.3    0.05       0
  3004.2    0.12       0  3183.6    0.07       0  3201.6    0.12       0
  3299.5    0.05       0  4841.6    0.12       0  5057.4    0.05       0
Bank Sta=2667.9,5330.9
Exp/Cntr=0.3,0.1

Type RM Length L Ch R = 1,17713,245,245,245
BEGIN DESCRIPTION:
doubleBIG CREEK 9.0
END DESCRIPTION:
XS GIS Cut Line= 3
      2811974.99      7065775.00      2809798.91      7065637.03
      2808073.69      7065571.93
#Sta/Elev= 30
  2766.0  469.58  2772.4  469.53  2988.1  465.91  3016.5  465.72  3056.6  449.21
  3108.6  443.93  3277.0  442.93  3320.6  436.60  3347.2  444.21  3377.2  436.53
  3407.3  444.22  3548.8  444.39  3600.7  443.93  3818.1  443.19  3838.1  430.56
  3938.3  443.21  4004.3  441.93  4205.6  444.31  4698.1  442.20  4980.4  443.68
  5001.3  429.93  5003.8  429.13  5019.5  429.93  5030.4  442.90  5040.4  444.53
  5688.7  442.86  5921.0  443.93  6195.0  447.57  6457.7  463.98  6672.9  469.57
#Mann=11,-1,0
  2766.0    0.08       0  2772.4    0.05       0  2988.1    0.12       0
  3548.8    0.07       0  3600.7    0.12       0  4004.3    0.08       0
  4205.6    0.05       0  4698.1    0.08       0  5001.3    0.07       0
  5019.5    0.08       0  5688.7    0.05       0
Bank Sta=3108.6,5921
Exp/Cntr=0.3,0.1

Type RM Length L Ch R = 1,17468,1150,1150,1150
BEGIN DESCRIPTION:
double BIG CREEK 8.0
END DESCRIPTION:
XS GIS Cut Line= 3
      2811958.23      7065582.78      2810156.99      7065409.17
      2807954.28      7065333.21
#Sta/Elev= 30
  2766.5  464.68  3020.9  466.01  3051.0  460.91  3071.1  464.37  3151.5  461.32
  3175.9  443.53  3191.7  439.86  3295.0  444.74  3489.3  444.57  3628.0  443.95
  3804.5  439.83  3814.6  435.00  3815.5  429.82  3818.0  429.02  3833.7  429.82
  3844.7  437.53  3874.8  443.77  4289.3  442.47  4680.5  441.75  4962.7  442.16
  4998.3  430.34  5038.3  444.13  5891.0  443.53  6169.0  447.77  6399.2  456.65
  6499.2  455.91  6618.9  462.39  6661.3  464.14  6760.4  468.94  6780.1  469.97
#Mann=12,-1,0
  2766.5    0.12       0  3295.0    0.05       0  3489.3    0.08       0
  3628.0    0.12       0  3815.5    0.03       0  3833.7    0.12       0
  4289.3    0.07       0  4680.5    0.12       0  4962.7    0.05       0
  6618.9    0.08       0  6661.3    0.05       0  6760.4    0.08       0
Bank Sta=3175.9,5891
Exp/Cntr=0.3,0.1

Type RM Length L Ch R = 1,16318,569,569,569
BEGIN DESCRIPTION:
double BIG CREEK 7.0
END DESCRIPTION:
XS GIS Cut Line= 3
      2811611.02      7064823.24      2810124.43      7064595.37
      2808692.11      7064497.71
#Sta/Elev= 30
  3457.5  462.32  3504.1  460.26  3574.9  453.21  3683.1  447.85  3830.1  443.03
  4040.2  442.64  4080.7  440.13  4181.9  442.47  4269.4  440.92  4370.1  442.44
  4464.5  440.41  4469.5  442.08  4728.0  441.31  4748.4  434.04  4787.3  427.36
  4789.8  426.56  4805.5  427.36  4809.1  439.82  4819.2  441.16  4910.3  440.17
  4970.9  442.64  4990.9  428.97  5001.0  429.02  5011.0  432.47  5021.0  439.35
  5031.0  441.54  5113.4  442.83  5432.0  440.11  5993.1  443.03  6397.1  462.98
#Mann=6,-1,0
  3457.5    0.16       0  3683.1    0.05       0  4370.1    0.12       0
  4787.3    0.07       0  4805.5    0.12       0  5113.4    0.05       0
Bank Sta=3830.1,5993.1
Exp/Cntr=0.3,0.1

Type RM Length L Ch R = 1,15749,348,348,348
BEGIN DESCRIPTION:
double BIG CREEK 6.0
END DESCRIPTION:
XS GIS Cut Line= 3
      2811589.26      7064512.90      2810052.82      7064165.68
      2809100.07      7063749.93
#Sta/Elev= 30
  3409.9  454.42  3541.3  446.48  3642.3  443.24  3696.6  442.38  4341.2  441.11
  4542.0  441.51  4583.0  438.14  4634.3  441.27  4648.8  439.44  4666.2  426.95
  4668.7  426.15  4684.4  426.95  4685.5  431.57  4692.0  439.90  4753.5  440.59
  4917.4  441.14  4966.5  441.68  4972.6  435.60  4993.6  428.64  5022.6  441.60
  5069.4  441.78  5113.6  437.12  5179.4  441.00  5274.8  440.51  5381.8  440.92
  5401.7  441.06  5488.7  441.53  5638.0  442.38  5802.9  444.92  6024.6  457.77
#Mann=12,-1,0
  3409.9    0.12       0  3541.3    0.16       0  3642.3    0.05       0
  4341.2    0.12       0  4666.2    0.07       0  4684.4    0.12       0
  4753.5    0.16       0  4917.4    0.12       0  5274.8    0.07       0
  5381.8    0.05       0  5401.7    0.12       0  5488.7    0.05       0
Bank Sta=3696.6,5638
Exp/Cntr=0.3,0.1

Type RM Length L Ch R = 1,15401,1180,1180,1180
BEGIN DESCRIPTION:
double BIG CREEK 5.0
END DESCRIPTION:
XS GIS Cut Line= 3
      2812209.97      7064521.59      2809974.69      7063892.24
      2809160.92      7063490.78
#Sta/Elev= 30
  2658.5  460.11  2886.4  449.98  3164.2  445.16  3227.8  446.00  3339.8  443.60
  3476.0  441.93  3667.4  441.32  4024.5  441.15  4063.7  437.94  4127.6  440.37
  4147.9  440.39  4250.1  440.35  4336.3  440.10  4356.8  435.94  4368.7  426.61
  4371.2  425.81  4386.9  426.61  4388.2  435.00  4409.0  440.27  4566.5  440.31
  4965.8  439.70  4983.2  434.35  4991.5  428.11  5002.6  428.30  5008.3  438.89
  5013.9  441.44  5074.0  440.95  5449.3  441.93  5749.2  454.53  5888.1  466.83
#Mann=13,-1,0
  2658.5    0.05       0  3164.2    0.16       0  3227.8    0.12       0
  3339.8    0.05       0  3667.4    0.12       0  4127.6    0.16       0
  4147.9    0.05       0  4250.1    0.16       0  4368.7    0.07       0
  4386.9    0.16       0  4566.5    0.05       0  4965.8    0.12       0
  5074.0    0.05       0
Bank Sta=3476,5449.3
Exp/Cntr=0.3,0.1

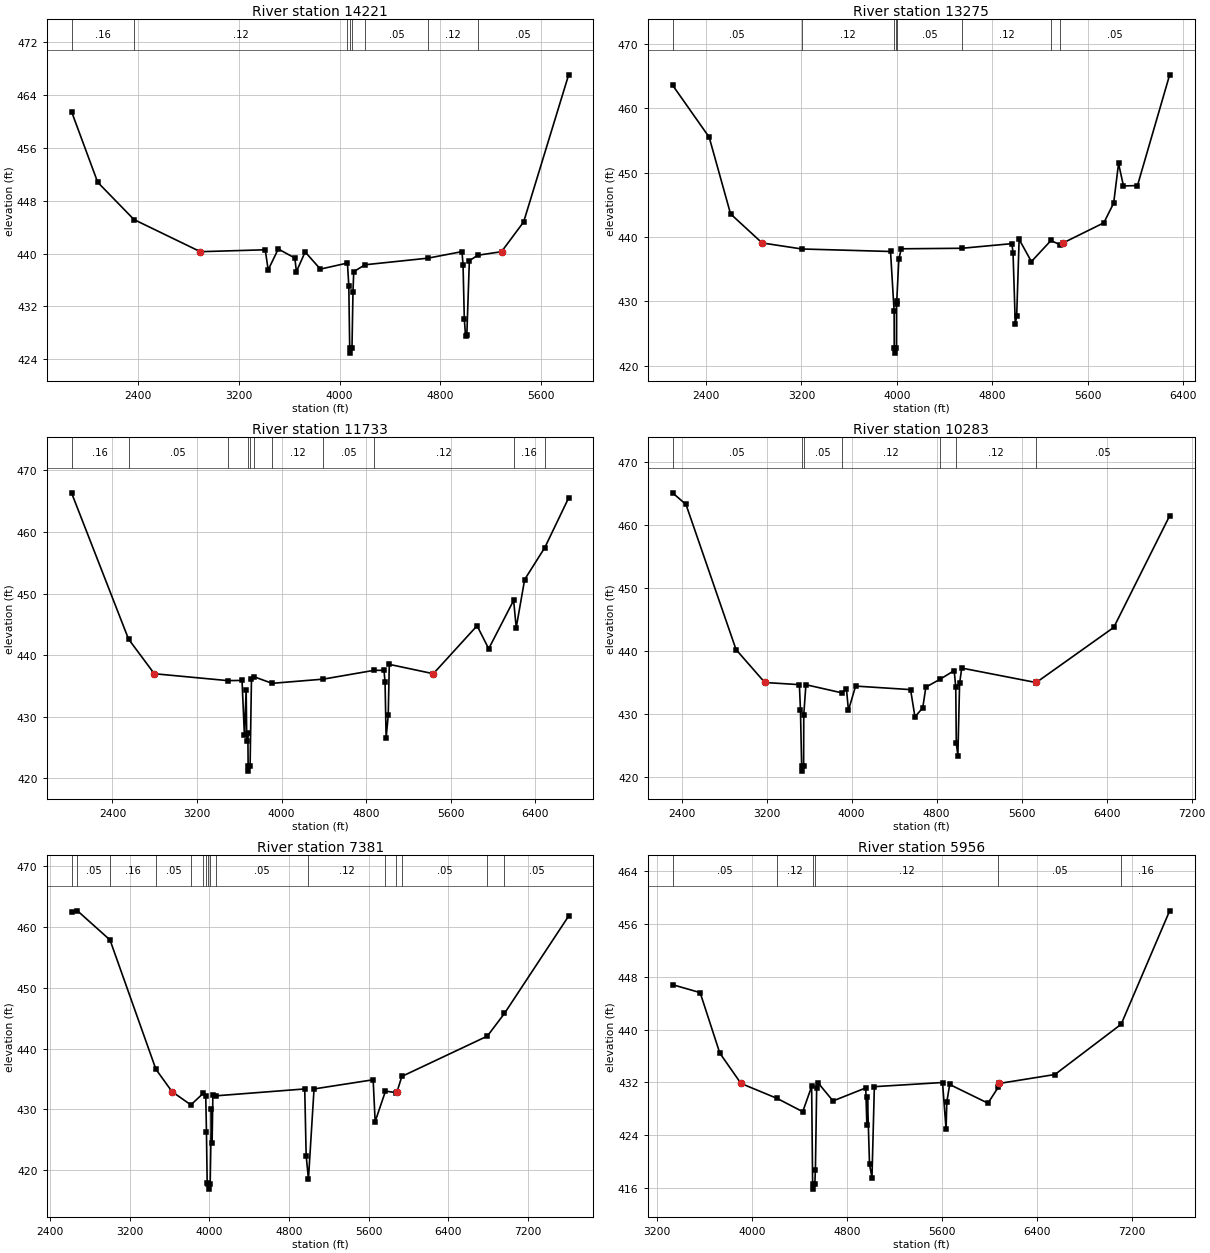
Type RM Length L Ch R = 1,14221,946,946,946
BEGIN DESCRIPTION:
double BIG CREEK 4.0
END DESCRIPTION:
XS GIS Cut Line= 3
      2813118.13      7064096.23      2810752.69      7063022.02
      2809408.56      7063097.89
#Sta/Elev= 30
  1872.6  461.54  2080.2  450.82  2368.1  445.17  2894.8  440.30  3409.7  440.59
  3432.8  437.54  3513.0  440.71  3644.3  439.34  3656.9  437.28  3726.2  440.26
  3847.0  437.66  4061.8  438.58  4072.6  435.10  4079.7  425.73  4082.2  424.93
  4097.9  425.73  4105.6  434.17  4111.8  437.28  4201.5  438.32  4700.8  439.32
  4970.5  440.31  4979.0  438.33  4989.0  430.11  4999.1  427.48  5009.1  427.71
  5029.1  438.92  5094.7  439.76  5284.2  440.30  5459.8  444.81  5816.8  467.10
#Mann=8,-1,0
  1872.6    0.16       0  2368.1    0.12       0  4061.8    0.16       0
  4079.7    0.07       0  4097.9    0.16       0  4201.5    0.05       0
  4700.8    0.12       0  5094.7    0.05       0
Bank Sta=2894.8,5284.2
Exp/Cntr=0.3,0.1

Type RM Length L Ch R = 1,13275,1542,1542,1542
BEGIN DESCRIPTION:
double BIG CREEK 3.0
END DESCRIPTION:
XS GIS Cut Line= 3
      2813270.05      7062555.44      2810416.32      7062229.92
      2809158.77      7062533.46
#Sta/Elev= 30
  2120.4  463.63  2427.4  455.53  2606.6  443.60  2870.9  439.08  3204.2  438.14
  3947.2  437.75  3977.4  428.42  3978.2  422.74  3980.7  421.94  3996.7  422.74
  3997.5  429.52  3999.4  430.04  4017.0  436.64  4037.8  438.17  4545.5  438.25
  4963.8  438.97  4973.8  437.59  4992.6  426.53  5004.3  427.67  5024.9  439.64
  5127.7  436.18  5291.7  439.46  5365.8  438.81  5393.5  439.08  5734.7  442.21
  5817.0  445.27  5858.1  451.44  5899.3  447.94  6016.7  448.01  6286.3  465.23
#Mann=8,-1,0
  2120.4    0.05       0  3204.2    0.12       0  3978.2    0.07       0
  3996.7    0.12       0  3999.4    0.05       0  4545.5    0.12       0
  5291.7    0.07       0  5365.8    0.05       0
Bank Sta=2870.9,5393.5
Exp/Cntr=0.3,0.1

Type RM Length L Ch R = 1,11733,1450,1450,1450
BEGIN DESCRIPTION:
double BIG CREEK 2.0
END DESCRIPTION:
XS GIS Cut Line= 3
      2813465.36      7062203.87      2811156.34      7061040.68
      2809039.17      7061127.45
#Sta/Elev= 30
  2012.3  466.37  2552.0  442.61  2795.5  436.99  3490.5  435.87  3626.0  435.90
  3648.3  427.03  3665.0  434.38  3670.6  426.08  3681.1  427.38  3683.7  421.97
  3686.2  421.17  3702.2  421.97  3715.2  436.20  3740.7  436.49  3910.3  435.43
  4394.3  436.11  4878.4  437.55  4969.4  437.53  4979.4  435.61  4989.4  426.53
  5009.4  430.23  5019.5  438.51  5436.2  436.99  5850.1  444.78  5960.2  441.05
  6196.1  448.90  6220.5  444.47  6300.5  452.29  6490.9  457.47  6716.7  465.54
#Mann=11,-1,0
  2012.3    0.16       0  2552.0    0.05       0  3490.5    0.12       0
  3683.7    0.07       0  3702.2    0.12       0  3740.7    0.05       0
  3910.3    0.12       0  4394.3    0.05       0  4878.4    0.12       0
  6196.1    0.16       0  6490.9    0.05       0
Bank Sta=2795.5,5436.2
Exp/Cntr=0.3,0.1

Type RM Length L Ch R = 1,10283,2902,2902,2902
BEGIN DESCRIPTION:
double Mapping XS 4097b718
END DESCRIPTION:
XS GIS Cut Line= 3
      2813478.42      7060424.37      2810861.20      7059825.40
      2808869.54      7059890.49
#Sta/Elev= 30
  2314.7  465.09  2441.3  463.24  2912.5  440.20  3182.9  434.98  3508.2  434.64
  3518.5  430.59  3529.7  421.71  3532.2  420.91  3548.2  421.71  3549.5  429.86
  3569.7  434.63  3907.1  433.34  3951.2  433.99  3969.8  430.56  4037.1  434.41
  4554.6  433.85  4595.6  429.53  4668.9  430.95  4698.2  434.24  4833.1  435.51
  4964.9  436.87  4979.6  434.25  4984.9  425.30  4999.6  423.38  5015.8  434.84
  5035.8  437.27  5736.6  434.97  5737.2  434.98  6466.6  443.73  6992.3  461.44
#Mann=7,-1,0
  2314.7    0.05       0  3529.7    0.07       0  3548.2    0.05       0
  3907.1    0.12       0  4833.1    0.05       0  4984.9    0.12       0
  5736.6    0.05       0
Bank Sta=3182.9,5737.2
Exp/Cntr=0.3,0.1

Type RM Length L Ch R = 1,7381,1425,1425,1425
BEGIN DESCRIPTION:
double BIG CREEK 1.0
END DESCRIPTION:
XS GIS Cut Line= 3
      2813505.93      7059553.27      2811675.00      7058025.00
      2809124.98      7057475.00
#Sta/Elev= 30
  2615.7  462.44  2675.4  462.65  3002.2  457.86  3463.3  436.59  3625.2  432.91
  3814.3  430.73  3940.9  432.66  3964.0  432.13  3971.1  426.30  3978.3  417.90
  3989.8  417.67  3992.3  416.87  4008.4  417.67  4021.2  430.10  4027.8  424.44
  4035.6  432.42  4067.4  432.22  4958.3  433.35  4972.7  422.39  4995.6  418.52
  5051.8  433.35  5645.6  434.86  5665.6  427.98  5769.5  432.99  5870.3  432.76
  5886.0  432.91  5933.6  435.41  6792.5  442.04  6964.5  445.77  7609.3  461.79
#Mann=16,-1,0
  2615.7    0.08       0  2675.4    0.05       0  3002.2    0.16       0
  3463.3    0.05       0  3814.3     0.1       0  3940.9    0.16       0
  3971.1    0.12       0  3989.8    0.07       0  4008.4    0.12       0
  4067.4    0.05       0  4995.6    0.12       0  5769.5    0.05       0
  5870.3    0.07       0  5933.6    0.05       0  6792.5    0.16       0
  6964.5    0.05       0
Bank Sta=3625.2,5886
Exp/Cntr=0.3,0.1

Type RM Length L Ch R = 1,5956,1738,1738,1738
BEGIN DESCRIPTION:
double Mapping XS 19810154
END DESCRIPTION:
XS GIS Cut Line= 3
      2813600.75      7057617.06      2812025.08      7057060.44
      2809525.24      7056744.67
#Sta/Elev= 30
  3328.9  446.80  3561.6  445.60  3727.4  436.44  3905.8  431.85  4212.2  429.57
  4426.5  427.57  4501.6  431.39  4509.9  416.65  4512.4  415.85  4528.5  416.65
  4533.4  418.82  4544.0  431.21  4555.5  431.94  4681.9  429.20  4957.7  431.17
  4967.1  425.60  4972.4  429.79  4989.5  419.58  5010.2  417.59  5030.3  431.36
  5604.8  431.99  5635.1  424.88  5641.0  429.03  5665.3  431.69  5987.9  428.86
  6073.7  431.24  6083.7  431.85  6552.3  433.20  7110.9  440.81  7519.7  457.98
#Mann=6,-1,0
  3328.9    0.05       0  4212.2    0.12       0  4509.9    0.07       0
  4528.5    0.12       0  6073.7    0.05       0  7110.9    0.16       0
Bank Sta=3905.8,6083.7
Exp/Cntr=0.3,0.1

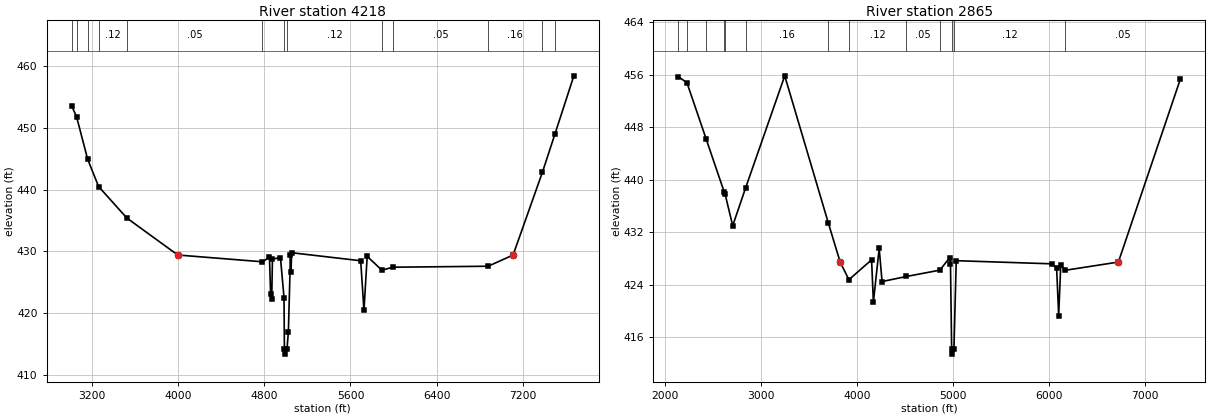
Type RM Length L Ch R = 1,4218,1353,1353,1353
BEGIN DESCRIPTION:
Mapping XS 885ade04
END DESCRIPTION:
XS GIS Cut Line= 3
      2814173.72      7056288.95      2812259.63      7055768.11
      2809590.35      7055872.28
#Sta/Elev= 30
  3016.3  453.57  3061.0  451.81  3163.0  444.97  3265.0  440.51  3527.4  435.40
  3999.0  429.41  4784.6  428.31  4849.3  429.03  4859.7  423.10  4870.1  422.21
  4876.9  428.76  4951.2  428.98  4984.1  422.52  4987.8  414.14  4991.4  413.34
  5011.7  414.14  5024.6  416.96  5044.0  429.46  5049.1  426.65  5054.7  429.78
  5695.1  428.48  5725.2  420.44  5755.2  429.19  5892.2  426.94  5991.4  427.43
  6877.0  427.59  7108.1  429.41  7380.5  442.86  7495.6  449.00  7671.3  458.46
#Mann=13,-1,0
  3016.3    0.05       0  3061.0    0.16       0  3163.0    0.05       0
  3265.0    0.12       0  3527.4    0.05       0  4784.6    0.12       0
  4987.8    0.07       0  5011.7    0.12       0  5892.2    0.07       0
  5991.4    0.05       0  6877.0    0.16       0  7380.5    0.05       0
  7495.6    0.16       0
Bank Sta=3999,7108.1
Exp/Cntr=0.3,0.1

Type RM Length L Ch R = 1,2865,338,338,338
BEGIN DESCRIPTION:
double Mapping XS 092f2145
END DESCRIPTION:
XS GIS Cut Line= 3
      2814750.16      7054859.50      2811961.97      7054595.64
      2809692.00      7055470.31
#Sta/Elev= 30
  2136.7  455.72  2227.9  454.77  2426.4  446.26  2616.3  438.11  2625.0  437.82
  2704.4  432.99  2840.3  438.81  3246.8  455.83  3702.0  433.36  3824.6  427.45
  3915.6  424.76  4152.0  427.79  4170.9  421.35  4231.2  429.52  4261.3  424.48
  4514.4  425.25  4864.2  426.22  4966.3  428.13  4974.4  427.21  4986.5  414.22
  4990.1  413.42  5010.4  414.22  5034.4  427.66  6033.4  427.18  6080.8  426.53
  6102.2  419.28  6123.7  427.02  6167.4  426.19  6724.5  427.45  7370.0  455.31
#Mann=13,-1,0
  2136.7    0.05       0  2227.9    0.16       0  2426.4    0.12       0
  2616.3    0.16       0  2625.0    0.12       0  2840.3    0.16       0
  3702.0    0.05       0  3915.6    0.12       0  4514.4    0.05       0
  4864.2    0.12       0  4986.5    0.07       0  5010.4    0.12       0
  6167.4    0.05       0
Bank Sta=3824.6,6724.5
Exp/Cntr=0.3,0.1