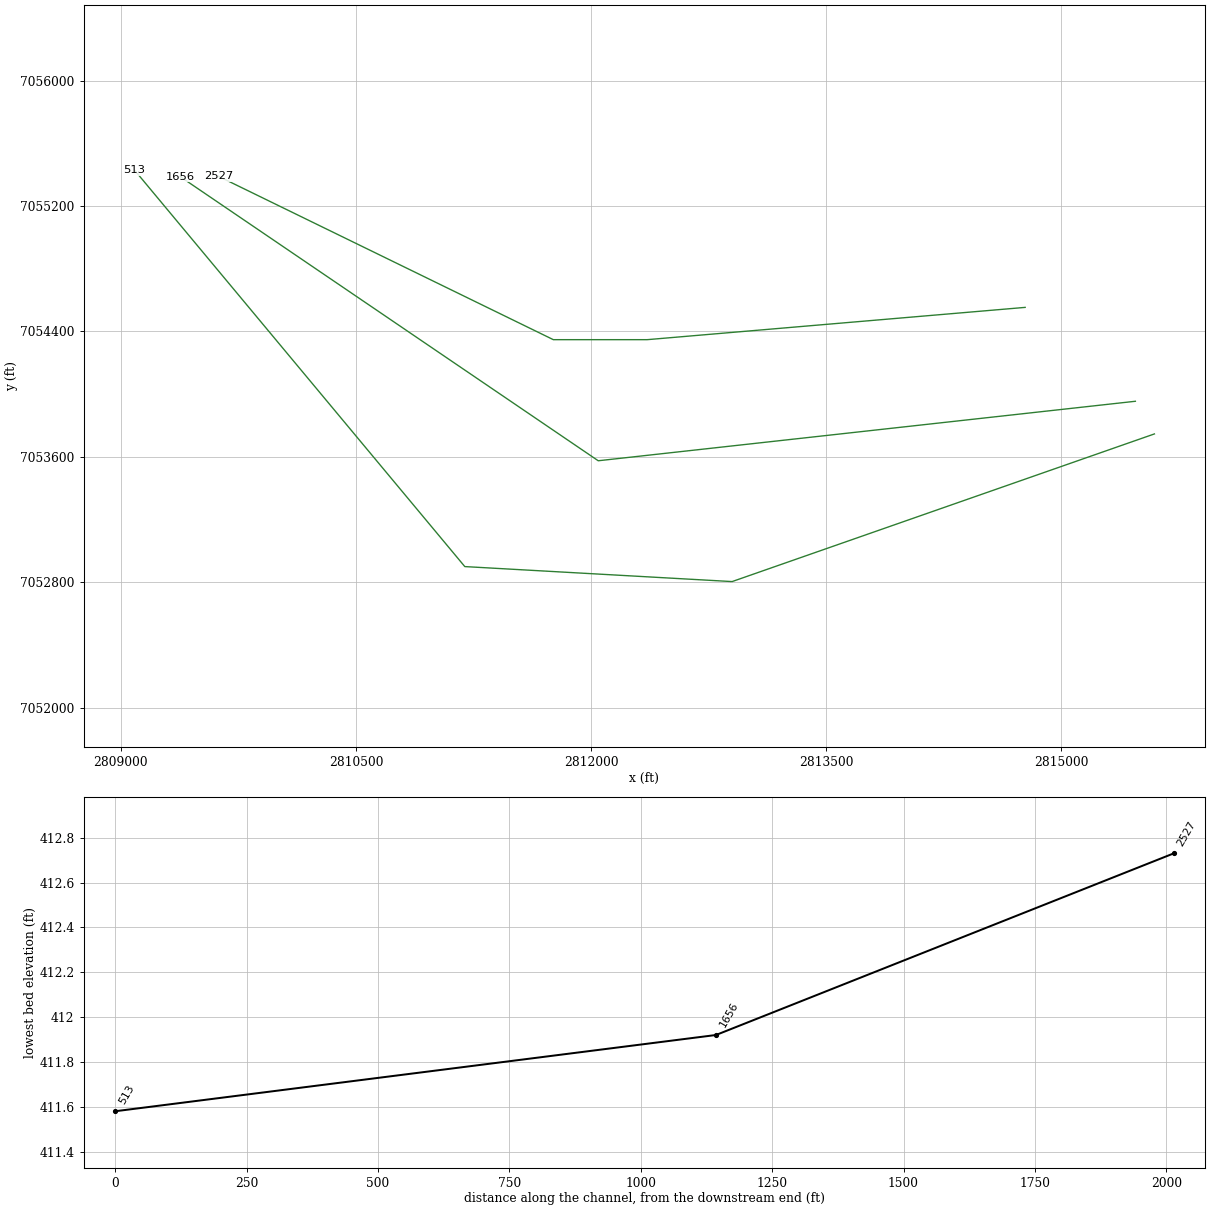
HEC-RAS study BIG CREEK.prj: BIG CREEK Base Level Engineering

--- BIG CREEK.g01 (geometry) --- (continued)

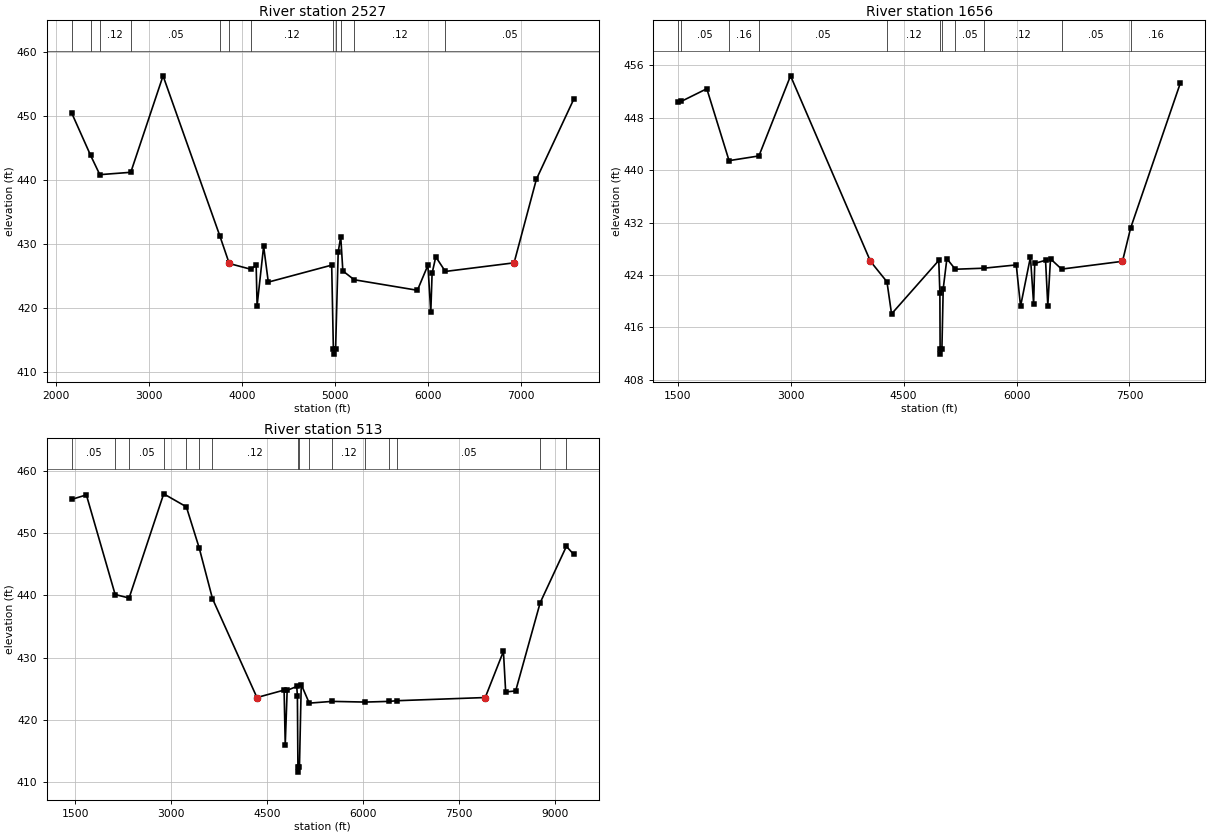
Type RM Length L Ch R = 1,2527,871,871,871
BEGIN DESCRIPTION:
double Mapping XS ae919395
END DESCRIPTION:
XS GIS Cut Line= 4
      2814769.15      7054553.32      2812357.80      7054347.38
      2811758.85      7054347.38      2809623.44      7055389.04
#Sta/Elev= 30
  2170.4  450.47  2372.5  443.87  2471.7  440.84  2804.6  441.21  3151.3  456.32
  3761.6  431.24  3860.0  427.03  3860.8  426.93  4095.6  426.02  4151.7  426.66
  4161.8  420.32  4232.0  429.62  4282.2  424.01  4963.3  426.67  4981.4  413.53
  4985.0  412.73  5005.3  413.53  5033.3  428.73  5060.5  431.12  5083.3  425.76
  5205.2  424.38  5884.4  422.73  5997.1  426.65  6028.2  419.27  6042.2  425.38
  6081.7  427.97  6184.5  425.68  6923.2  427.03  7163.1  440.13  7565.4  452.69
#Mann=12,-1,0
  2170.4    0.05       0  2372.5    0.07       0  2471.7    0.12       0
  2804.6    0.05       0  3761.6    0.08       0  3860.8    0.05       0
  4095.6    0.12       0  4981.4    0.07       0  5005.3    0.12       0
  5060.5    0.05       0  5205.2    0.12       0  6184.5    0.05       0
Bank Sta=3860,6923.2
Exp/Cntr=0.3,0.1

Type RM Length L Ch R = 1,1656,1143,1143,1143
BEGIN DESCRIPTION:
double Mapping XS 7f85c1d6
END DESCRIPTION:
XS GIS Cut Line= 3
      2815472.28      7053954.36      2812045.30      7053574.81
      2809379.34      7055386.83
#Sta/Elev= 30
  1504.6  450.37  1547.1  450.52  1884.2  452.44  2179.9  441.46  2576.9  442.18
  2996.8  454.41  4058.8  426.09  4278.1  422.96  4339.1  418.06  4966.4  426.22
  4981.3  421.24  4984.3  412.72  4987.9  411.92  5008.2  412.72  5025.4  421.88
  5074.2  426.49  5185.9  424.88  5567.1  425.04  5996.2  425.54  6053.2  419.23
  6184.7  426.75  6226.7  419.61  6241.6  425.77  6385.3  426.25  6415.2  419.34
  6451.1  426.47  6598.2  424.90  7407.5  426.09  7515.5  431.16  8176.0  453.29
#Mann=11,-1,0
  1504.6    0.16       0  1547.1    0.05       0  2179.9    0.16       0
  2576.9    0.05       0  4278.1    0.12       0  4984.3    0.07       0
  5008.2    0.12       0  5185.9    0.05       0  5567.1    0.12       0
  6598.2    0.05       0  7515.5    0.16       0
Bank Sta=4058.8,7407.5
Exp/Cntr=0.3,0.1

Type RM Length L Ch R = 1,513,0,0,0
BEGIN DESCRIPTION:
double Mapping XS 14581cc2
END DESCRIPTION:
XS GIS Cut Line= 4
      2815593.75      7053746.01      2812899.47      7052803.98
      2811194.05      7052899.64      2809086.99      7055428.96
#Sta/Elev= 30
  1445.4  455.46  1673.8  456.18  2124.0  440.15  2342.3  439.59  2883.3  456.35
  3237.9  454.26  3438.5  447.66  3646.9  439.48  4342.2  423.58  4767.0  424.78
  4784.8  416.00  4814.9  424.74  4965.1  425.36  4975.1  423.79  4983.2  412.38
  4986.8  411.58  5007.1  412.38  5035.2  425.67  5160.5  422.68  5517.7  422.96
  6035.4  422.85  6410.0  422.96  6535.1  423.07  7913.5  423.58  8198.1  431.01
  8233.2  424.48  8389.4  424.64  8772.6  438.82  9183.1  447.90  9299.7  446.59
#Mann=16,-1,0
  1445.4    0.05       0  2124.0    0.16       0  2342.3    0.05       0
  2883.3    0.16       0  3237.9    0.05       0  3438.5    0.16       0
  3646.9    0.12       0  4983.2    0.07       0  5007.1    0.12       0
  5160.5    0.05       0  5517.7    0.12       0  6035.4    0.05       0
  6410.0    0.12       0  6535.1    0.05       0  8772.6    0.16       0
  9183.1    0.05       0
Bank Sta=4342.2,7913.5
Exp/Cntr=0.3,0.1

Chan Stop Cuts=-1