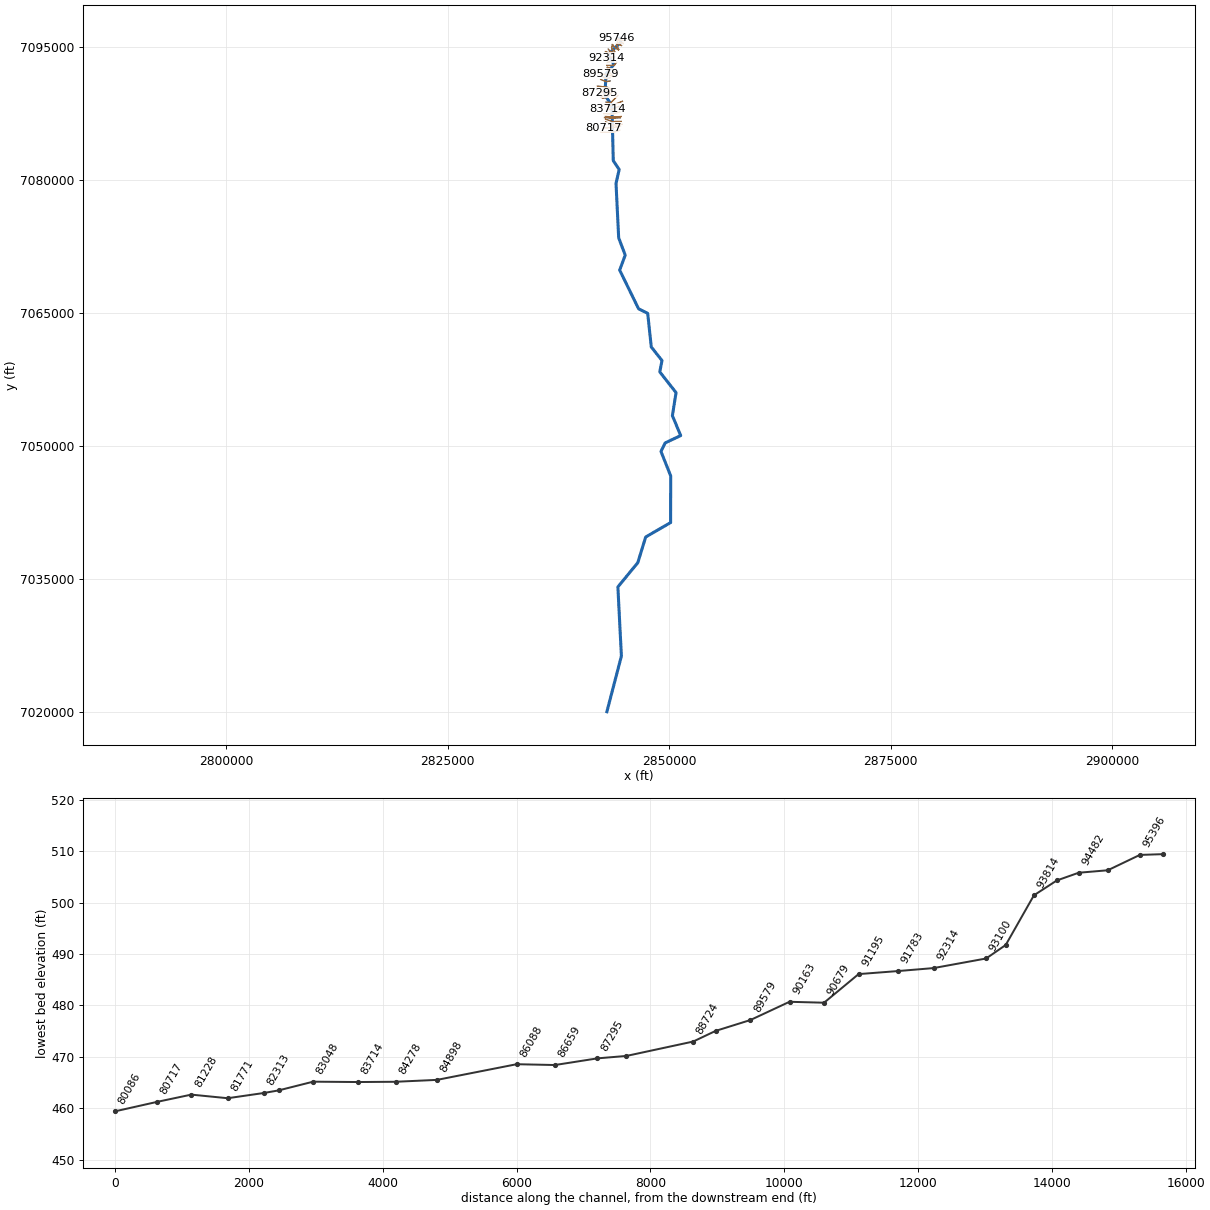
--- BIRCH CREEK.prj (project) ---

Proj Title=BIRCH CREEK Base Level Engineering
Current Plan=p01
Default Exp/Contr=0.3,0.1
English Units
Geom File=g01
Flow File=f01
Plan File=p01
Y Axis Title=Elevation
X Axis Title(PF)=Main Channel Distance
X Axis Title(XS)=Station
BEGIN DESCRIPTION:
BIRCH CREEK
END DESCRIPTION:
DSS Export Rating Curves= 0
DSS Export Rating Curve Sorted= 0
DSS Export Volume Flow Curves= 0
DXF OffsetX= 0
DXF OffsetY= 0
DXF ScaleX= 1
DXF ScaleY= 10

--- BIRCH CREEK.p01 (plan) ---

Plan Title=Multiple Run
Short Identifier=Multiple
Geom File=g01
Flow File=f01
Subcritical Flow
K Sum by GR= 0
Std Step Tol= 0.01
Critical Tol= 0.01
Num of Std Step Trials= 20
Max Error Tol= 0.3
Flow Tol Ratio= 0.001
Split Flow NTrial= 30
Split Flow Tol= 0.02
Split Flow Ratio= 0.02
Log Output Level= 0
Friction Slope Method= 1
Unsteady Friction Slope Method= 2
Unsteady Bridges Friction Slope Method= 1
Parabolic Critical Depth
Global Vel Dist=  1 , 1 , 1
Global Log Level= 0
CheckData=True
Encroach Param= -1, 0, 0, 0
BEGIN DESCRIPTION:
Multiple Run
END DESCRIPTION:

--- BIRCH CREEK.f01 (steady flow) ---

Flow Title=Multiple
Program Version=5.07
Number of Profiles= 7
Profile Names=10-year,25-year,50-year,1pct_min,100-year,1pct_plu,500-year
River Rch & RM=BIRCH CREEK,Reach-1         ,95746
     433     561     660     387     772    1540    1050
River Rch & RM=BIRCH CREEK,Reach-1         ,95396
     894    1214    1476     890    1776    3544    2566
River Rch & RM=BIRCH CREEK,Reach-1         ,92314
    1395    1937    2392    1462    2916    5819    4329
River Rch & RM=BIRCH CREEK,Reach-1         ,89579
    1968    2769    3449    2122    4235    8449    6376
River Rch & RM=BIRCH CREEK,Reach-1         ,83048
    2569    3653    4580    2835    5657   11288    8621
River Rch & RM=BIRCH CREEK,Reach-1         ,80717
    2817    4016    5046    3128    6242   12454    9541
River Rch & RM=BIRCH CREEK,Reach-1         ,76566
    2971    4242    5333    3309    6602   13173   10105
River Rch & RM=BIRCH CREEK,Reach-1         ,73220
    3195    4569    5751    3571    7125   14216   10922
River Rch & RM=BIRCH CREEK,Reach-1         ,68169
    3182    4541    5706    3537    7057   14080   10780
River Rch & RM=BIRCH CREEK,Reach-1         ,66049
    5252    7645    9739    6111   12194   24330   19094
River Rch & RM=BIRCH CREEK,Reach-1         ,62917
    5233    7599    9664    6053   12078   24099   18842
River Rch & RM=BIRCH CREEK,Reach-1         ,59949
    5524    8028   10216    6401   12772   25484   19939
River Rch & RM=BIRCH CREEK,Reach-1         ,54477
    5645    8210   10453    6552   13074   26086   20428
River Rch & RM=BIRCH CREEK,Reach-1         ,53160
    5713    8310   10581    6634   13236   26409   20685
River Rch & RM=BIRCH CREEK,Reach-1         ,52815
    8029   11773   15074    9495   18945   37801   29880
River Rch & RM=BIRCH CREEK,Reach-1         ,45288
    8008   11730   15008    9447   18849   37609   29687
River Rch & RM=BIRCH CREEK,Reach-1         ,41654
    7858   11488   14678    9225   18407   36727   28909
River Rch & RM=BIRCH CREEK,Reach-1         ,40673
    8194   11960   15265    9585   19125   38159   29984
River Rch & RM=BIRCH CREEK,Reach-1         ,29830
    8197   11956   15254    9574   19102   38114   29924
River Rch & RM=BIRCH CREEK,Reach-1         ,28118
    8433   12308   15711    9867   19687   39282   30884
River Rch & RM=BIRCH CREEK,Reach-1         ,27265
    8328   12116   15431    9670   19294   38497   30137
River Rch & RM=BIRCH CREEK,Reach-1         ,20510
    8457   12301   15665    9816   19585   39076   30587
River Rch & RM=BIRCH CREEK,Reach-1         ,18723
    8599   12507   15928    9981   19914   39734   31110
River Rch & RM=BIRCH CREEK,Reach-1         ,17885
    8765   12731   16200   10143   20239   40382   31572
River Rch & RM=BIRCH CREEK,Reach-1         ,13102
    8761   12705   16150   10102   20156   40216   31375
River Rch & RM=BIRCH CREEK,Reach-1         ,8349
    8731   12654   16077   10051   20054   40012   31186
River Rch & RM=BIRCH CREEK,Reach-1         ,6636
    8675   12545   15915    9935   19823   39551   30737
Boundary for River Rch & Prof#=BIRCH CREEK,Reach-1         , 1
Up Type= 0
Dn Type= 3
Dn Slope=0.00015
Boundary for River Rch & Prof#=BIRCH CREEK,Reach-1         , 2
Up Type= 0
Dn Type= 3
Dn Slope=0.00015
Boundary for River Rch & Prof#=BIRCH CREEK,Reach-1         , 3
Up Type= 0
Dn Type= 3
Dn Slope=0.00015
Boundary for River Rch & Prof#=BIRCH CREEK,Reach-1         , 4
Up Type= 0
Dn Type= 3
Dn Slope=0.00015
Boundary for River Rch & Prof#=BIRCH CREEK,Reach-1         , 5
Up Type= 0
Dn Type= 3
Dn Slope=0.00015
Boundary for River Rch & Prof#=BIRCH CREEK,Reach-1         , 6
Up Type= 0
Dn Type= 3
Dn Slope=0.00015
Boundary for River Rch & Prof#=BIRCH CREEK,Reach-1         , 7
Up Type= 0
Dn Type= 3
Dn Slope=0.00015
DSS Import GetInterval= 0
DSS Import GetPeak= 0
DSS Import FillOption= 0

--- BIRCH CREEK.g01 (geometry) ---

Geom Title=Existing Conditions

River Reach=BIRCH CREEK,Reach-1
Reach XY= 30
      2844384.40      7096042.19      2844556.12      7095597.77
      2843106.71      7094205.03      2843775.35      7093086.27
      2842894.96      7092030.72      2842737.75      7089630.53
      2843543.87      7088455.25      2843695.51      7082216.72
      2844361.49      7081215.78      2844005.30      7079640.68
      2844305.69      7073503.10      2845044.30      7071545.70
      2844418.25      7069856.41      2846550.84      7065488.22
      2847581.70      7064969.10      2847984.78      7061175.01
      2849194.05      7059640.48      2848946.12      7058358.64
      2850781.33      7056017.34      2850367.26      7053415.32
      2851305.32      7051168.59      2849558.28      7050341.73
      2849079.07      7049375.52      2850177.35      7046614.14
      2850166.89      7041342.41      2847353.21      7039710.68
      2846464.13      7036813.33      2844215.27      7034072.86
      2844612.74      7026259.41      2842973.01      7019978.75

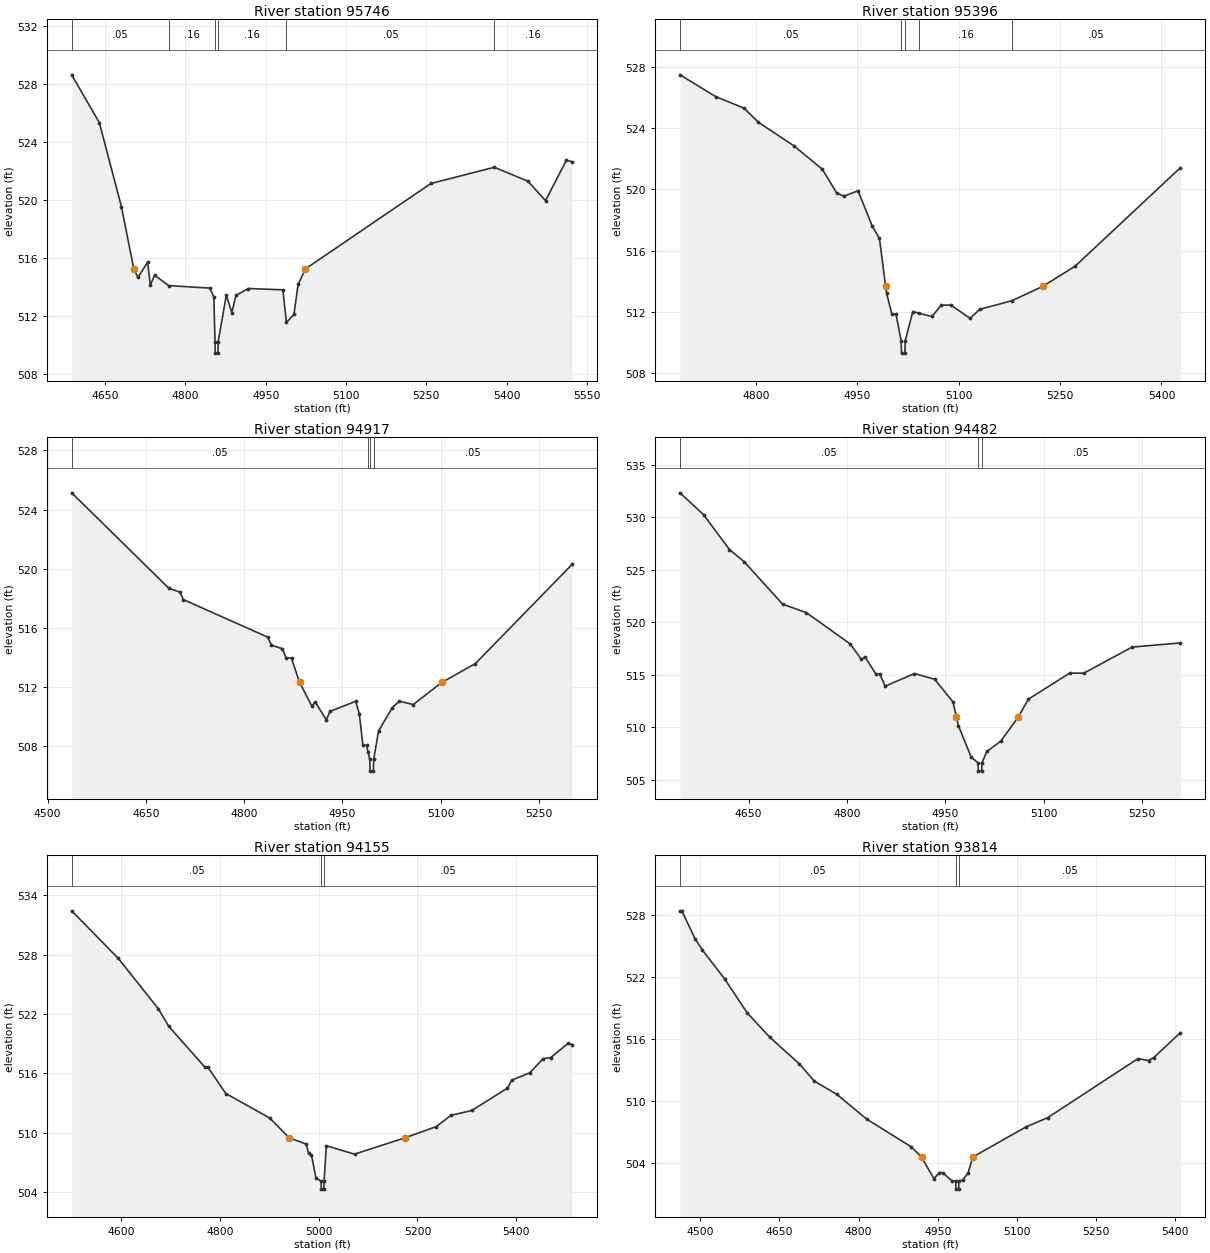
Type RM Length L Ch R = 1,95746,350,350,350
BEGIN DESCRIPTION:
BIRCH CREEK 118.0
END DESCRIPTION:
XS GIS Cut Line= 3
      2844925.04      7095774.99      2844525.00      7095875.00
      2844024.97      7096025.01
#Sta/Elev= 30
  4587.7  528.66  4639.3  525.36  4680.5  519.57  4703.7  515.27  4711.4  514.68
  4729.5  515.72  4734.6  514.13  4742.4  514.83  4768.9  514.11  4845.4  513.94
  4853.2  513.33  4855.3  510.25  4855.8  509.45  4860.8  509.45  4861.3  510.25
  4876.4  513.45  4886.7  512.25  4894.4  513.43  4917.6  513.91  4982.0  513.82
  4988.8  511.57  5002.7  512.12  5010.5  514.19  5024.3  515.27  5258.5  521.16
  5377.0  522.28  5439.4  521.32  5472.5  519.98  5511.6  522.77  5522.1  522.66
#Mann=6,-1,0
  4587.7    0.05       0  4768.9    0.16       0  4855.3    0.03       0
  4861.3    0.16       0  4988.8    0.05       0  5377.0    0.16       0
Bank Sta=4703.7,5024.3
Exp/Cntr=0.3,0.1

Type RM Length L Ch R = 1,95396,479,479,479
BEGIN DESCRIPTION:
BIRCH CREEK 117.0
END DESCRIPTION:
XS GIS Cut Line= 3
      2844824.96      7095475.01      2844525.00      7095575.00
      2844224.97      7095875.03
#Sta/Elev= 30
  4687.5  527.49  4740.2  526.07  4782.3  525.31  4803.4  524.39  4856.1  522.85
  4898.3  521.31  4919.4  519.76  4929.9  519.56  4951.0  519.91  4972.1  517.59
  4982.6  516.81  4991.8  513.67  4993.1  513.24  5001.1  511.84  5007.2  511.84
  5014.8  510.10  5015.3  509.30  5020.3  509.30  5020.8  510.10  5032.0  512.02
  5041.7  511.90  5060.3  511.70  5074.4  512.44  5088.5  512.44  5116.8  511.57
  5131.0  512.16  5178.8  512.73  5224.6  513.67  5272.4  514.99  5428.0  521.42
#Mann=5,-1,0
  4687.5    0.05       0  5014.8    0.03       0  5020.8    0.05       0
  5041.7    0.16       0  5178.8    0.05       0
Bank Sta=4991.8,5224.6
Exp/Cntr=0.3,0.1

Type RM Length L Ch R = 1,94917,435,435,435
BEGIN DESCRIPTION:
BIRCH CREEK 116.0
END DESCRIPTION:
XS GIS Cut Line= 3
      2844625.02      7095224.99      2844225.00      7095425.00
      2844124.99      7095725.04
#Sta/Elev= 30
  4536.9  525.13  4685.1  518.68  4701.8  518.42  4707.4  517.91  4836.0  515.37
  4841.6  514.83  4858.4  514.59  4863.9  513.99  4872.3  513.94  4884.6  512.31
  4903.1  510.73  4908.7  510.97  4925.4  509.78  4931.0  510.35  4970.2  511.03
  4975.7  510.19  4981.3  508.06  4986.8  508.06  4989.1  507.61  4991.7  507.11
  4992.2  506.31  4997.2  506.31  4997.7  507.11  5005.2  509.04  5026.3  510.61
  5036.8  511.04  5057.9  510.81  5101.7  512.31  5152.8  513.58  5300.4  520.29
#Mann=4,-1,0
  4536.9    0.05       0  4989.1    0.16       0  4991.7    0.03       0
  4997.7    0.05       0
Bank Sta=4884.6,5101.7
Exp/Cntr=0.3,0.1

Type RM Length L Ch R = 1,94482,327,327,327
BEGIN DESCRIPTION:
BIRCH CREEK 115.0
END DESCRIPTION:
XS GIS Cut Line= 3
      2844324.98      7094775.04      2844125.00      7095175.00
      2844025.00      7095475.00
#Sta/Elev= 30
  4545.3  532.33  4581.6  530.23  4620.7  526.93  4643.1  525.78  4701.8  521.73
  4738.1  520.92  4805.2  517.93  4822.0  516.47  4827.6  516.69  4844.3  515.07
  4849.9  515.10  4858.3  513.92  4903.0  515.12  4933.8  514.58  4961.7  512.43
  4967.1  510.97  4970.1  510.15  4989.7  507.14  5000.0  506.63  5000.5  505.83
  5005.5  505.83  5006.0  506.63  5013.6  507.71  5034.6  508.68  5061.3  510.97
  5076.8  512.68  5140.0  515.17  5161.1  515.15  5234.9  517.64  5308.7  518.04
#Mann=3,-1,0
  4545.3    0.05       0  5000.0    0.03       0  5006.0    0.05       0
Bank Sta=4967.1,5061.3
Exp/Cntr=0.3,0.1

Type RM Length L Ch R = 1,94155,341,341,341
BEGIN DESCRIPTION:
BIRCH CREEK 114.0
END DESCRIPTION:
XS GIS Cut Line= 3
      2844274.99      7094725.01      2843875.00      7094975.00
      2843575.01      7095424.98
#Sta/Elev= 30
  4500.4  532.41  4594.7  527.61  4675.5  522.54  4696.7  520.76  4769.8  516.64
  4775.7  516.65  4812.3  513.97  4900.7  511.51  4940.8  509.49  4975.1  508.87
  4979.6  507.95  4985.6  507.76  4994.6  505.47  5005.1  505.12  5005.6  504.32
  5010.6  504.32  5011.1  505.12  5015.7  508.70  5072.7  507.85  5174.2  509.49
  5238.0  510.63  5268.0  511.77  5310.1  512.26  5382.2  514.52  5391.2  515.33
  5427.3  516.06  5454.3  517.49  5469.4  517.59  5505.4  519.05  5512.9  518.91
#Mann=3,-1,0
  4500.4    0.05       0  5005.1    0.03       0  5011.1    0.05       0
Bank Sta=4940.8,5174.2
Exp/Cntr=0.3,0.1

Type RM Length L Ch R = 1,93814,421,421,421
BEGIN DESCRIPTION:
BIRCH CREEK 113.0
END DESCRIPTION:
XS GIS Cut Line= 3
      2843874.99      7094525.01      2843525.00      7094875.00
      2843575.00      7095324.97
#Sta/Elev= 30
  4461.9  528.38  4465.4  528.38  4490.2  525.70  4504.3  524.58  4546.7  521.77
  4589.2  518.50  4631.6  516.16  4688.2  513.55  4716.4  511.89  4758.9  510.62
  4815.4  508.22  4900.3  505.52  4919.3  504.55  4942.7  502.46  4953.3  503.04
  4959.4  503.04  4977.0  502.24  4984.0  502.24  4984.5  501.44  4989.5  501.44
  4990.0  502.24  4997.1  502.32  5007.2  502.97  5016.4  504.55  5117.8  507.48
  5158.1  508.35  5329.1  514.07  5349.3  513.89  5359.3  514.18  5409.6  516.58
#Mann=3,-1,0
  4461.9    0.05       0  4984.0    0.03       0  4990.0    0.05       0
Bank Sta=4919.3,5016.4
Exp/Cntr=0.3,0.1

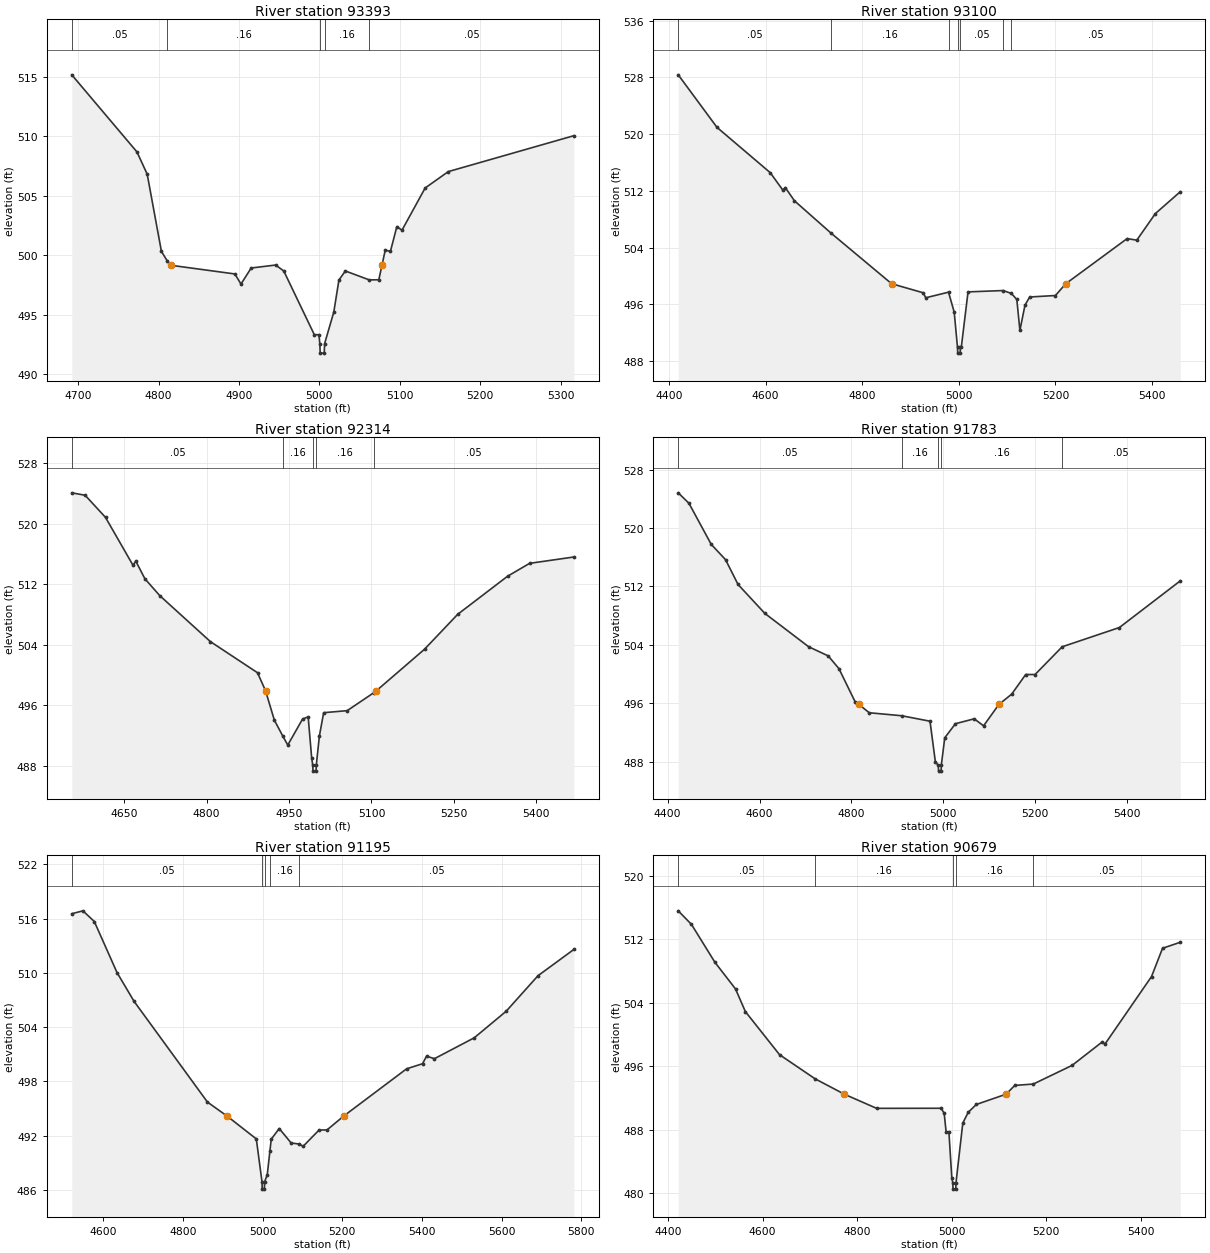
Type RM Length L Ch R = 1,93393,293,293,293
BEGIN DESCRIPTION:
BIRCH CREEK 112.0
END DESCRIPTION:
XS GIS Cut Line= 3
      2843625.03      7094525.00      2843325.00      7094575.00
      2843125.01      7094824.98
#Sta/Elev= 30
  4692.1  515.18  4773.2  508.69  4785.9  506.82  4803.6  500.32  4810.9  499.52
  4815.3  499.16  4894.9  498.43  4902.5  497.58  4915.2  498.93  4945.6  499.18
  4955.7  498.68  4993.7  493.32  4999.5  493.32  5000.5  492.57  5001.0  491.77
  5006.0  491.77  5006.5  492.57  5017.9  495.22  5024.3  497.92  5032.3  498.68
  5062.0  497.93  5073.9  497.94  5077.8  499.16  5081.9  500.44  5088.3  500.32
  5096.3  502.41  5102.7  502.11  5131.5  505.66  5160.3  507.04  5316.4  510.06
#Mann=5,-1,0
  4692.1    0.05       0  4810.9    0.16       0  5000.5    0.07       0
  5006.5    0.16       0  5062.0    0.05       0
Bank Sta=4815.3,5077.8
Exp/Cntr=0.3,0.1

Type RM Length L Ch R = 1,93100,786,786,786
BEGIN DESCRIPTION:
BIRCH CREEK 111.0
END DESCRIPTION:
XS GIS Cut Line= 3
      2843825.01      7094425.00      2843240.44      7094384.67
      2842809.32      7094525.49
#Sta/Elev= 30
  4419.0  528.36  4499.2  520.96  4609.5  514.57  4635.7  512.10  4640.7  512.47
  4659.6  510.61  4735.4  506.05  4860.8  498.92  4926.4  497.64  4931.4  496.94
  4978.6  497.73  4990.4  494.91  4997.2  489.94  4997.7  489.14  5002.7  489.14
  5003.2  489.94  5005.0  489.94  5019.0  497.77  5091.7  497.96  5108.8  497.55
  5120.0  496.70  5126.4  492.35  5136.9  495.90  5146.6  497.05  5200.0  497.26
  5221.3  498.92  5348.4  505.28  5368.4  505.06  5406.9  508.81  5458.5  511.89
#Mann=7,-1,0
  4419.0    0.05       0  4735.4    0.16       0  4978.6    0.05       0
  4997.2    0.03       0  5003.2    0.05       0  5091.7    0.16       0
  5108.8    0.05       0
Bank Sta=4860.8,5221.3
Exp/Cntr=0.3,0.1

Type RM Length L Ch R = 1,92314,531,531,531
BEGIN DESCRIPTION:
BIRCH CREEK 110.0
END DESCRIPTION:
XS GIS Cut Line= 3
      2843824.95      7093974.99      2843375.00      7093875.00
      2842925.00      7093825.00
#Sta/Elev= 30
  4554.6  524.09  4578.9  523.77  4616.0  520.84  4666.0  514.51  4671.1  515.05
  4687.7  512.72  4714.6  510.50  4806.8  504.41  4892.6  500.29  4907.2  497.91
  4923.3  494.01  4938.9  491.87  4947.7  490.72  4974.6  494.16  4984.8  494.45
  4991.2  489.00  4993.1  488.07  4993.6  487.27  4999.1  487.27  4999.6  488.07
  5005.3  491.95  5013.0  495.00  5055.8  495.27  5104.8  497.67  5109.0  497.91
  5196.6  503.40  5257.0  508.02  5347.6  513.05  5387.8  514.76  5468.3  515.60
#Mann=5,-1,0
  4554.6    0.05       0  4938.9    0.16       0  4993.1    0.07       0
  4999.6    0.16       0  5104.8    0.05       0
Bank Sta=4907.2,5109
Exp/Cntr=0.3,0.1

Type RM Length L Ch R = 1,91783,588,588,588
BEGIN DESCRIPTION:
BIRCH CREEK 109.0
END DESCRIPTION:
XS GIS Cut Line= 3
      2843824.99      7093924.99      2843525.00      7093425.00
      2843024.98      7093325.00
#Sta/Elev= 30
  4423.0  524.83  4446.3  523.40  4494.9  517.76  4526.0  515.67  4553.2  512.27
  4611.5  508.31  4706.8  503.74  4749.5  502.48  4772.8  500.74  4807.8  496.23
  4816.3  495.83  4838.9  494.69  4909.6  494.28  4971.1  493.53  4982.8  487.95
  4989.2  487.49  4989.7  486.69  4995.2  486.69  4995.7  487.49  5003.2  491.26
  5026.5  493.19  5067.3  493.86  5087.7  492.90  5121.1  495.83  5148.9  497.24
  5179.4  499.93  5199.8  499.93  5258.8  503.73  5383.4  506.37  5516.0  512.77
#Mann=5,-1,0
  4423.0    0.05       0  4909.6    0.16       0  4989.2    0.07       0
  4995.7    0.16       0  5258.8    0.05       0
Bank Sta=4816.3,5121.1
Exp/Cntr=0.3,0.1

Type RM Length L Ch R = 1,91195,516,516,516
BEGIN DESCRIPTION:
BIRCH CREEK 108.0
END DESCRIPTION:
XS GIS Cut Line= 3
      2844075.02      7093325.02      2843775.00      7092975.00
      2842975.00      7092975.00
#Sta/Elev= 30
  4520.4  516.54  4548.4  516.86  4577.0  515.68  4634.0  510.04  4676.8  506.86
  4861.2  495.72  4910.6  494.17  4983.9  491.65  4998.2  486.90  4998.7  486.10
  5004.2  486.10  5004.7  486.90  5011.4  487.70  5018.0  490.29  5021.4  491.62
  5041.4  492.80  5071.4  491.20  5092.2  491.08  5101.4  490.83  5141.4  492.63
  5161.4  492.64  5203.2  494.17  5361.4  499.40  5401.4  499.96  5411.4  500.79
  5431.4  500.52  5531.4  502.83  5611.4  505.76  5691.4  509.69  5781.4  512.59
#Mann=5,-1,0
  4520.4    0.05       0  4998.2    0.03       0  5004.7    0.05       0
  5018.0    0.16       0  5092.2    0.05       0
Bank Sta=4910.6,5203.2
Exp/Cntr=0.3,0.1

Type RM Length L Ch R = 1,90679,516,516,516
BEGIN DESCRIPTION:
BIRCH CREEK 107.0
END DESCRIPTION:
XS GIS Cut Line= 3
      2843924.97      7092225.02      2843475.00      7092575.00
      2843025.00      7092775.00
#Sta/Elev= 30
  4421.4  515.60  4449.4  513.89  4499.2  509.10  4542.6  505.76  4563.4  502.91
  4635.8  497.47  4711.1  494.43  4773.0  492.49  4841.2  490.71  4977.9  490.72
  4984.2  490.08  4988.3  487.74  4994.2  487.74  5000.3  481.99  5002.4  481.33
  5002.9  480.53  5008.7  480.53  5009.2  481.33  5023.6  488.86  5035.2  490.22
  5052.3  491.20  5115.0  492.49  5133.7  493.60  5172.8  493.77  5254.8  496.12
  5319.1  499.10  5324.5  498.81  5423.0  507.32  5446.3  510.88  5483.9  511.64
#Mann=5,-1,0
  4421.4    0.05       0  4711.1    0.16       0  5002.4    0.07       0
  5009.2    0.16       0  5172.8    0.05       0
Bank Sta=4773,5115
Exp/Cntr=0.3,0.1

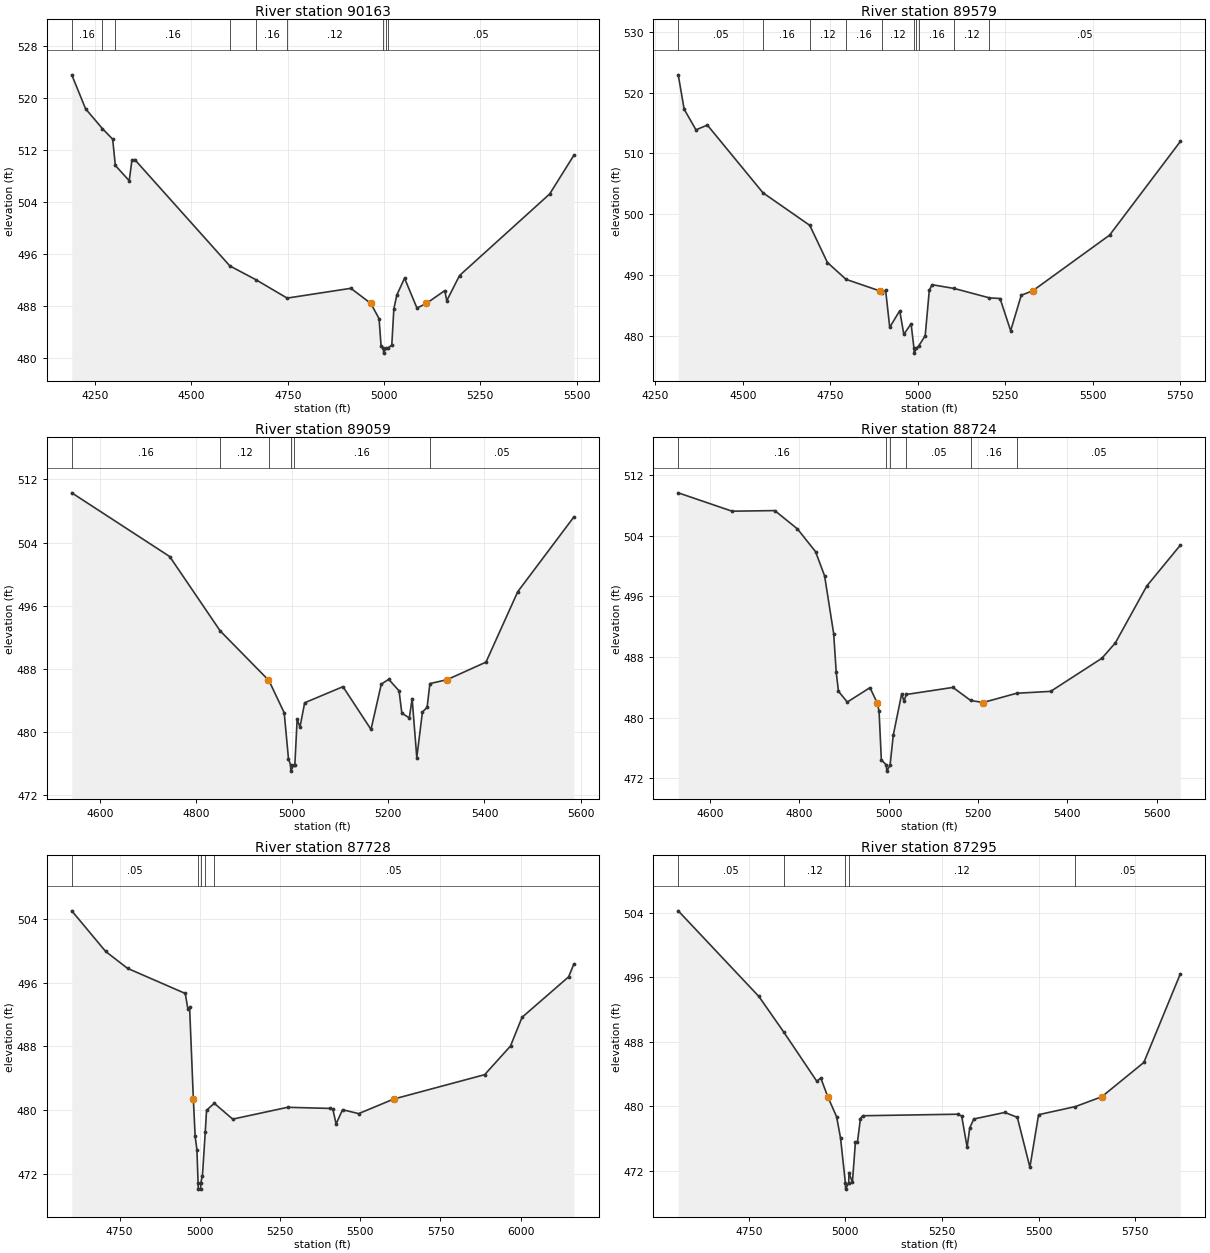
Type RM Length L Ch R = 1,90163,584,584,584
BEGIN DESCRIPTION:
BIRCH CREEK 106.0
END DESCRIPTION:
XS GIS Cut Line= 3
      2843775.02      7091724.98      2843175.00      7092225.00
      2843024.99      7092725.03
#Sta/Elev= 30
  4189.5  523.60  4225.3  518.37  4269.2  515.30  4295.6  513.68  4302.6  509.63
  4338.6  507.28  4345.7  510.46  4352.9  510.54  4599.8  494.15  4667.6  492.02
  4748.4  489.19  4913.9  490.70  4965.8  488.36  4987.1  486.02  4992.3  481.83
  4998.4  481.51  4998.9  480.71  5005.3  481.51  5011.3  481.54  5020.1  481.95
  5025.4  487.51  5033.2  489.67  5053.2  492.26  5085.4  487.66  5109.7  488.36
  5157.6  490.35  5162.8  488.79  5195.9  492.67  5429.9  505.24  5492.6  511.20
#Mann=9,-1,0
  4189.5    0.16       0  4269.2    0.05       0  4302.6    0.16       0
  4599.8    0.12       0  4667.6    0.16       0  4748.4    0.12       0
  4998.4    0.07       0  5005.3    0.12       0  5011.3    0.05       0
Bank Sta=4965.8,5109.7
Exp/Cntr=0.3,0.1

Type RM Length L Ch R = 1,89579,520,520,520
BEGIN DESCRIPTION:
double BIRCH CREEK 105.0
END DESCRIPTION:
XS GIS Cut Line= 3
      2843674.97      7091725.01      2842975.00      7091925.00
      2842274.98      7092025.00
#Sta/Elev= 30
  4315.6  522.92  4332.5  517.27  4366.3  513.87  4398.8  514.66  4557.9  503.52
  4691.6  498.17  4742.0  492.06  4795.3  489.29  4890.9  487.41  4899.1  487.04
  4908.4  487.50  4920.1  481.41  4948.7  484.13  4960.4  480.25  4981.2  481.99
  4989.4  477.96  4989.9  477.16  4996.3  477.96  5002.8  478.33  5021.5  480.02
  5033.2  487.48  5041.0  488.41  5104.5  487.79  5204.9  486.25  5235.5  486.14
  5265.8  480.84  5296.1  486.68  5328.9  487.41  5548.7  496.57  5750.7  511.96
#Mann=10,-1,0
  4315.6    0.05       0  4557.9    0.16       0  4691.6    0.12       0
  4795.3    0.16       0  4899.1    0.12       0  4989.4    0.07       0
  4996.3    0.12       0  5002.8    0.16       0  5104.5    0.12       0
  5204.9    0.05       0
Bank Sta=4890.9,5328.9
Exp/Cntr=0.3,0.1

Type RM Length L Ch R = 1,89059,335,335,335
BEGIN DESCRIPTION:
double BIRCH CREEK 104.0
END DESCRIPTION:
XS GIS Cut Line= 3
      2843324.99      7091575.00      2842875.00      7091475.00
      2842374.97      7091775.02
#Sta/Elev= 30
  4541.8  510.30  4745.4  502.23  4850.4  492.81  4950.0  486.63  4951.4  486.57
  4983.6  482.43  4992.5  476.58  4996.8  475.84  4997.3  475.04  5003.7  475.84
  5005.7  475.84  5010.5  481.61  5016.4  480.62  5026.1  483.70  5105.8  485.74
  5164.1  480.32  5185.5  486.07  5201.0  486.67  5222.4  485.21  5228.2  482.39
  5243.8  481.78  5249.6  484.23  5259.3  476.75  5271.0  482.53  5280.7  483.11
  5286.6  486.13  5322.4  486.63  5403.2  488.85  5469.2  497.77  5585.9  507.24
#Mann=6,-1,0
  4541.8    0.16       0  4850.4    0.12       0  4951.4    0.16       0
  4996.8    0.07       0  5003.7    0.16       0  5286.6    0.05       0
Bank Sta=4950,5322.4
Exp/Cntr=0.3,0.1

Type RM Length L Ch R = 1,88724,996,996,996
BEGIN DESCRIPTION:
Mapping XS 636d17ed
END DESCRIPTION:
XS GIS Cut Line= 3
      2843347.87      7091220.86      2842899.95      7091142.74
      2842274.98      7091382.31
#Sta/Elev= 30
  4529.1  509.64  4649.6  507.22  4745.2  507.30  4795.9  504.89  4836.5  501.89
  4856.8  498.69  4877.1  491.08  4882.8  485.98  4887.8  483.49  4907.6  482.07
  4958.4  483.97  4974.1  482.01  4978.7  480.89  4983.8  474.46  4995.1  473.77
  4995.9  472.97  5003.4  473.77  5010.5  477.71  5029.3  483.15  5034.6  482.18
  5039.6  483.07  5144.1  484.00  5183.8  482.28  5211.6  482.01  5286.7  483.23
  5362.9  483.48  5477.7  487.85  5507.7  489.87  5578.1  497.37  5653.1  502.74
#Mann=6,-1,0
  4529.1    0.16       0  4995.1    0.07       0  5003.4    0.16       0
  5039.6    0.05       0  5183.8    0.16       0  5286.7    0.05       0
Bank Sta=4974.1,5211.6
Exp/Cntr=0.3,0.1

Type RM Length L Ch R = 1,87728,433,433,433
BEGIN DESCRIPTION:
BIRCH CREEK 103.0
END DESCRIPTION:
XS GIS Cut Line= 3
      2843425.03      7090324.99      2843034.54      7090508.72
      2841908.94      7090638.40
#Sta/Elev= 30
  4601.0  504.96  4706.4  499.89  4774.8  497.77  4954.7  494.63  4962.7  492.72
  4968.2  492.89  4979.9  481.43  4985.5  476.76  4991.0  475.11  4994.6  470.97
  4995.3  470.17  5002.4  470.17  5003.2  470.97  5008.2  471.86  5017.0  477.31
  5021.0  480.03  5045.1  480.90  5102.6  478.92  5273.7  480.40  5404.5  480.26
  5414.6  480.16  5424.7  478.32  5444.8  480.10  5495.1  479.61  5604.2  481.43
  5887.7  484.48  5968.2  488.06  6004.2  491.65  6149.4  496.71  6165.6  498.31
#Mann=5,-1,0
  4601.0    0.05       0  4994.6    0.03       0  5003.2    0.05       0
  5017.0    0.12       0  5045.1    0.05       0
Bank Sta=4979.9,5604.2
Exp/Cntr=0.3,0.1

Type RM Length L Ch R = 1,87295,636,636,636
BEGIN DESCRIPTION:
BIRCH CREEK 102.0
END DESCRIPTION:
XS GIS Cut Line= 3
      2843425.01      7090225.00      2842975.00      7090125.00
      2842175.03      7089875.01
#Sta/Elev= 30
  4567.4  504.21  4776.1  493.59  4840.4  489.18  4925.9  483.08  4936.2  483.48
  4954.4  481.15  4977.2  478.67  4987.4  476.02  4999.8  470.50  5000.5  469.70
  5008.4  470.50  5009.2  471.69  5018.1  470.56  5025.8  475.51  5031.0  475.51
  5038.9  478.45  5044.6  478.80  5290.3  478.99  5300.8  478.76  5314.9  474.90
  5321.7  477.30  5332.2  478.40  5412.4  479.21  5444.8  478.60  5477.3  472.42
  5499.8  478.93  5595.3  479.94  5663.1  481.15  5772.2  485.41  5866.5  496.39
#Mann=5,-1,0
  4567.4    0.05       0  4840.4    0.12       0  4999.8    0.07       0
  5008.4    0.12       0  5595.3    0.05       0
Bank Sta=4954.4,5663.1
Exp/Cntr=0.3,0.1

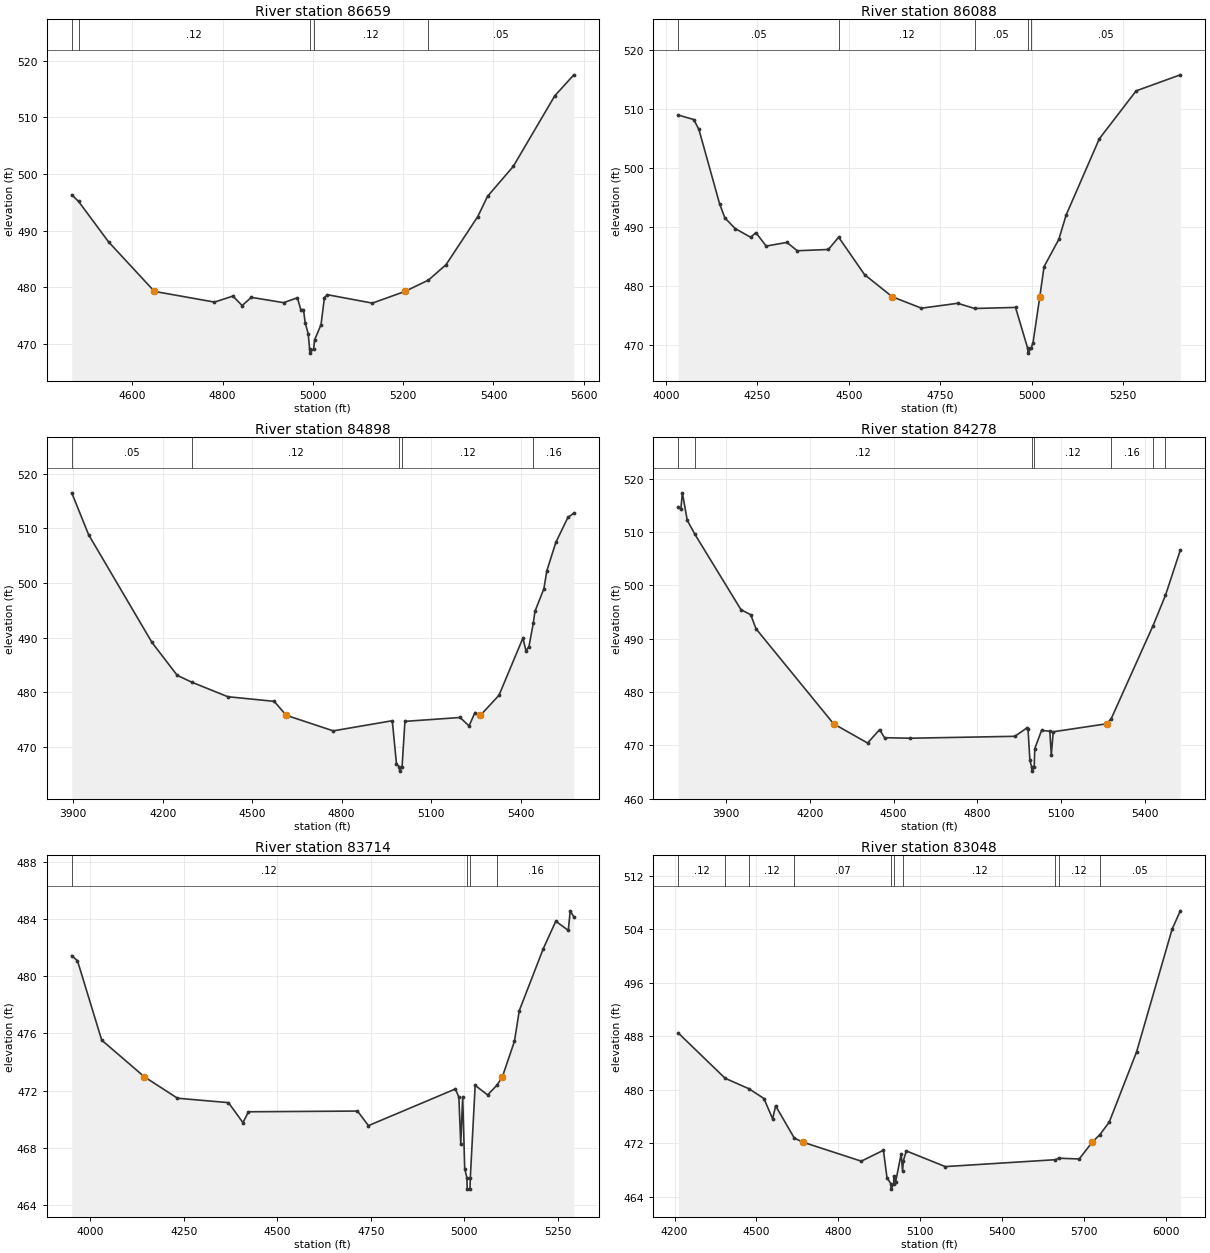
Type RM Length L Ch R = 1,86659,571,571,571
BEGIN DESCRIPTION:
BIRCH CREEK 101.0
END DESCRIPTION:
XS GIS Cut Line= 3
      2843274.99      7089875.00      2842775.00      7089775.00
      2842324.98      7089374.98
#Sta/Elev= 30
  4466.0  496.35  4481.2  495.17  4547.6  488.03  4649.0  479.30  4782.1  477.41
  4822.9  478.47  4843.3  476.80  4863.7  478.25  4935.1  477.31  4965.7  478.17
  4973.3  476.07  4979.2  476.07  4983.0  473.77  4989.7  471.81  4992.7  469.20
  4993.6  468.40  5001.7  469.20  5003.9  470.74  5018.1  473.45  5025.6  478.22
  5032.3  478.71  5131.8  477.23  5204.1  479.30  5255.9  481.29  5294.9  484.01
  5365.1  492.49  5386.9  496.09  5443.8  501.36  5535.7  513.82  5578.0  517.53
#Mann=5,-1,0
  4466.0    0.05       0  4481.2    0.12       0  4992.7    0.07       0
  5001.7    0.12       0  5255.9    0.05       0
Bank Sta=4649,5204.1
Exp/Cntr=0.3,0.1

Type RM Length L Ch R = 1,86088,1190,1190,1190
BEGIN DESCRIPTION:
BIRCH CREEK 100.0
END DESCRIPTION:
XS GIS Cut Line= 3
      2843574.98      7089974.98      2842925.00      7089325.00
      2842474.99      7089275.00
#Sta/Elev= 30
  4033.8  508.92  4076.2  508.16  4090.3  506.48  4146.9  493.86  4161.1  491.50
  4189.3  489.68  4231.8  488.20  4245.9  488.99  4274.2  486.71  4330.8  487.33
  4359.0  485.92  4443.9  486.13  4472.2  488.21  4542.9  481.87  4618.8  478.11
  4698.5  476.18  4797.5  477.01  4843.7  476.13  4955.5  476.31  4988.8  469.36
  4989.6  468.56  4997.8  469.36  5003.3  470.31  5021.8  478.11  5033.5  483.23
  5073.8  487.85  5093.9  491.99  5184.4  504.89  5285.0  513.02  5405.8  515.74
#Mann=5,-1,0
  4033.8    0.05       0  4472.2    0.12       0  4843.7    0.05       0
  4988.8    0.03       0  4997.8    0.05       0
Bank Sta=4618.8,5021.8
Exp/Cntr=0.3,0.1

Type RM Length L Ch R = 1,84898,620,620,620
BEGIN DESCRIPTION:
BIRCH CREEK 99.0
END DESCRIPTION:
XS GIS Cut Line= 3
      2844224.97      7089574.97      2843425.00      7088775.00
      2842875.00      7088825.00
#Sta/Elev= 30
  3895.0  516.52  3951.5  508.84  4163.7  489.12  4248.5  483.07  4297.1  481.82
  4418.2  479.15  4573.8  478.30  4614.1  475.75  4771.8  472.89  4969.8  474.75
  4983.9  466.81  4993.5  466.31  4994.3  465.51  5002.6  466.31  5012.2  474.63
  5197.0  475.34  5227.2  473.80  5247.2  476.25  5265.5  475.75  5327.6  479.42
  5407.9  489.91  5417.9  487.59  5428.0  488.32  5442.6  492.63  5448.1  494.78
  5478.2  498.96  5488.2  502.27  5518.3  507.44  5558.5  512.00  5578.6  512.80
#Mann=5,-1,0
  3895.0    0.05       0  4297.1    0.12       0  4993.5    0.07       0
  5002.6    0.12       0  5442.6    0.16       0
Bank Sta=4614.1,5265.5
Exp/Cntr=0.3,0.1

Type RM Length L Ch R = 1,84278,564,564,564
BEGIN DESCRIPTION:
BIRCH CREEK 98.0
END DESCRIPTION:
XS GIS Cut Line= 3
      2844724.97      7088924.99      2843475.00      7088425.00
      2843025.03      7088475.00
#Sta/Elev= 30
  3728.4  514.70  3737.8  514.28  3743.2  517.33  3760.7  512.19  3787.8  509.58
  3953.2  495.42  3988.2  494.47  4007.0  491.84  4285.0  474.02  4406.9  470.41
  4450.0  472.93  4467.5  471.41  4557.7  471.31  4934.6  471.67  4976.4  473.20
  4981.8  472.98  4988.5  467.15  4994.7  465.94  4995.6  465.14  5003.8  465.94
  5006.0  469.36  5030.2  472.77  5059.8  472.63  5065.2  468.16  5072.0  472.52
  5263.8  474.02  5279.9  474.98  5429.8  492.44  5474.2  498.11  5527.4  506.59
#Mann=7,-1,0
  3728.4    0.05       0  3787.8    0.12       0  4994.7    0.07       0
  5003.8    0.12       0  5279.9    0.16       0  5429.8    0.12       0
  5474.2    0.16       0
Bank Sta=4285,5263.8
Exp/Cntr=0.3,0.1

Type RM Length L Ch R = 1,83714,666,666,666
BEGIN DESCRIPTION:
BIRCH CREEK 97.0
END DESCRIPTION:
XS GIS Cut Line= 3
      2844349.17      7088357.77      2843390.00      7087967.16
      2843094.86      7088053.96
#Sta/Elev= 30
  3950.2  481.45  3965.5  481.09  4030.3  475.53  4144.5  472.96  4233.0  471.46
  4369.5  471.15  4408.2  469.75  4423.0  470.51  4714.6  470.56  4744.0  469.54
  4976.7  472.11  4985.9  471.53  4990.9  468.27  4996.1  471.57  5001.5  466.53
  5007.4  465.89  5008.2  465.09  5015.6  465.09  5016.5  465.89  5029.5  472.36
  5062.8  471.69  5088.0  472.38  5102.3  472.96  5134.7  475.46  5147.4  477.59
  5211.9  481.95  5245.2  483.86  5278.6  483.22  5283.8  484.59  5293.5  484.17
#Mann=4,-1,0
  3950.2    0.12       0  5007.4    0.07       0  5016.5    0.12       0
  5088.0    0.16       0
Bank Sta=4144.5,5102.3
Exp/Cntr=0.3,0.1

Type RM Length L Ch R = 1,83048,517,517,517
BEGIN DESCRIPTION:
BIRCH CREEK 96.0
END DESCRIPTION:
XS GIS Cut Line= 3
      2844425.02      7087725.01      2843625.00      7087475.00
      2842625.02      7087525.00
#Sta/Elev= 30
  4213.4  488.51  4385.3  481.73  4472.4  480.17  4527.2  478.71  4559.2  475.68
  4570.2  477.61  4638.6  472.79  4670.4  472.18  4883.9  469.34  4965.1  470.97
  4978.2  466.87  4992.4  465.96  4993.3  465.16  5002.8  465.96  5002.9  467.16
  5009.7  466.22  5030.1  470.41  5035.3  467.91  5038.4  469.44  5049.0  470.87
  5191.7  468.53  5595.2  469.56  5606.9  469.78  5682.4  469.67  5730.1  472.18
  5758.4  473.32  5792.5  475.19  5892.6  485.68  6022.8  504.03  6052.8  506.77
#Mann=10,-1,0
  4213.4    0.12       0  4385.3    0.16       0  4472.4    0.12       0
  4638.6    0.07       0  4992.4    0.07       0  5002.8    0.07       0
  5038.4    0.12       0  5595.2    0.16       0  5606.9    0.12       0
  5758.4    0.05       0
Bank Sta=4670.4,5730.1
Exp/Cntr=0.3,0.1

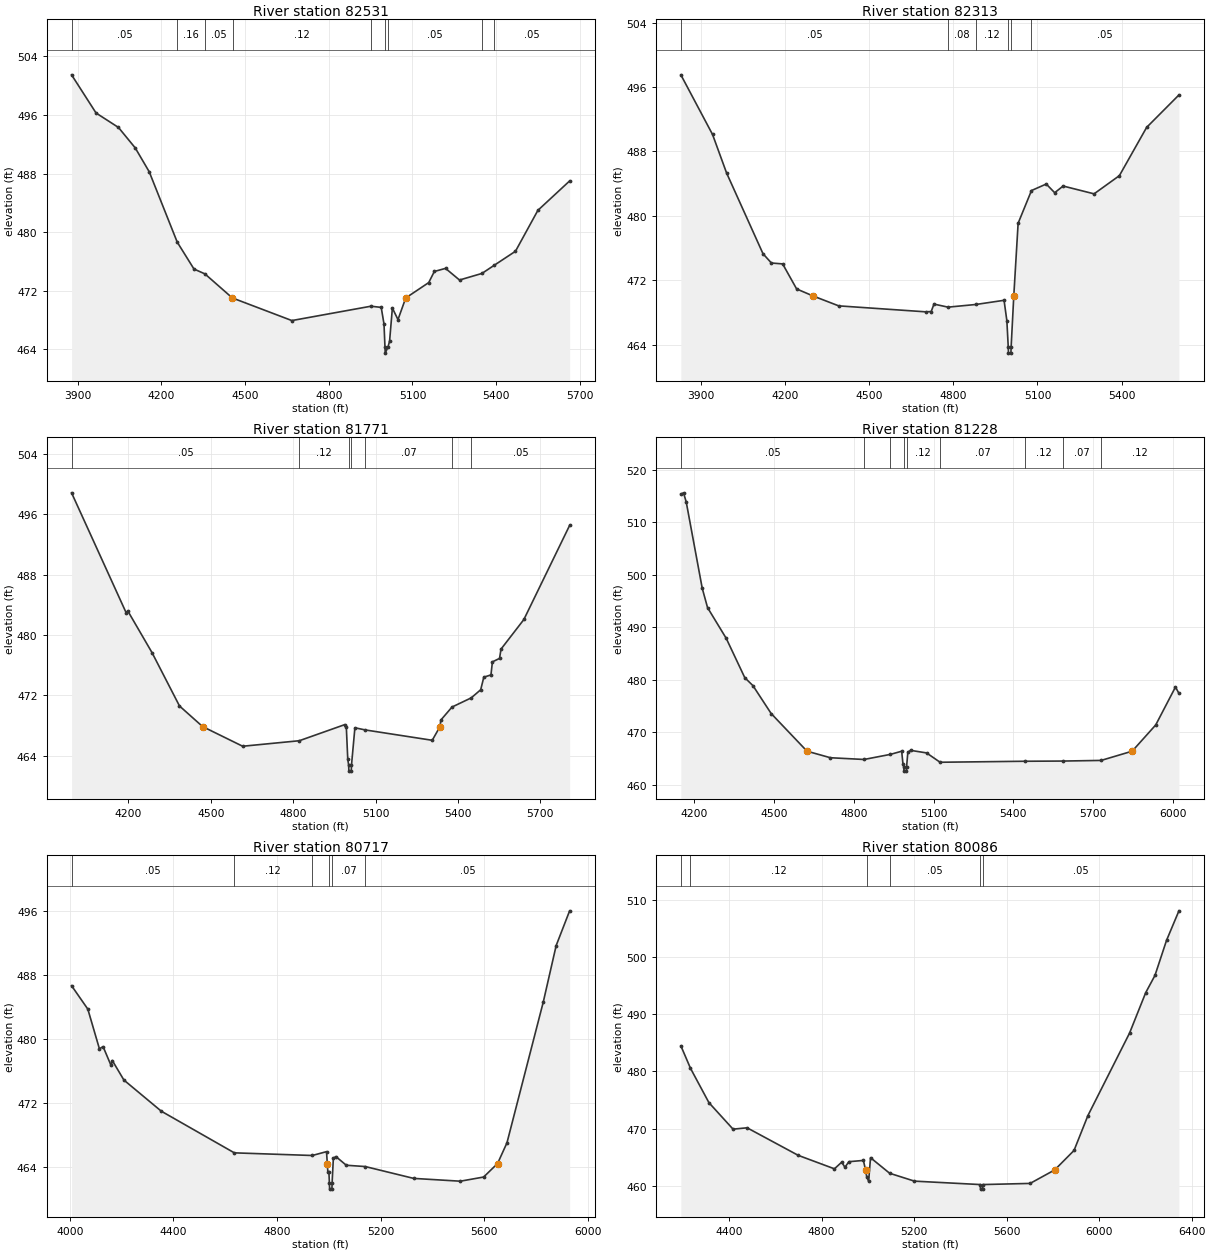
Type RM Length L Ch R = 1,82531,218,218,218
BEGIN DESCRIPTION:
Mapping XS c78240d1
END DESCRIPTION:
XS GIS Cut Line= 4
      2844592.61      7087200.02      2843842.66      7087147.94
      2843462.45      7087158.36      2842811.45      7087205.23
#Sta/Elev= 30
  3878.5  501.49  3966.3  496.27  4046.5  494.30  4106.7  491.50  4156.8  488.24
  4257.1  478.63  4317.2  474.95  4356.3  474.29  4454.6  471.00  4455.4  470.99
  4667.9  467.91  4951.2  469.87  4988.1  469.71  4998.1  467.44  5001.6  464.26
  5002.5  463.46  5012.0  464.26  5018.1  465.09  5028.1  469.62  5048.2  468.04
  5076.0  471.00  5158.4  473.10  5178.5  474.62  5218.6  475.04  5268.7  473.45
  5349.0  474.35  5393.7  475.48  5469.2  477.38  5549.5  482.97  5663.3  486.99
#Mann=9,-1,0
  3878.5    0.05       0  4257.1    0.16       0  4356.3    0.05       0
  4455.4    0.12       0  4951.2    0.05       0  5001.6    0.04       0
  5012.0    0.05       0  5349.0    0.08       0  5393.7    0.05       0
Bank Sta=4454.6,5076
Exp/Cntr=0.3,0.1

Type RM Length L Ch R = 1,82313,542,542,542
BEGIN DESCRIPTION:
Mapping XS 0fdcca6f
END DESCRIPTION:
XS GIS Cut Line= 3
      2844478.12      7087048.99      2843342.66      7087022.94
      2842703.37      7087080.12
#Sta/Elev= 30
  3827.3  497.52  3940.4  490.11  3990.5  485.33  4120.5  475.30  4150.5  474.15
  4190.5  474.04  4240.5  470.93  4299.7  470.05  4390.6  468.83  4700.6  468.09
  4720.7  468.12  4730.7  469.05  4780.8  468.67  4879.9  469.00  4980.8  469.52
  4990.8  466.99  4995.7  463.76  4996.6  462.96  5005.2  462.96  5006.1  463.76
  5015.5  470.05  5031.0  479.09  5078.7  483.15  5131.4  483.96  5161.5  482.88
  5191.6  483.71  5302.1  482.74  5392.4  485.00  5489.6  490.99  5604.9  495.02
#Mann=6,-1,0
  3827.3    0.05       0  4780.8    0.08       0  4879.9    0.12       0
  4995.7    0.07       0  5006.1    0.12       0  5078.7    0.05       0
Bank Sta=4299.7,5015.5
Exp/Cntr=0.3,0.1

Type RM Length L Ch R = 1,81771,543,543,543
BEGIN DESCRIPTION:
Mapping XS 5802c658
END DESCRIPTION:
XS GIS Cut Line= 3
      2844597.91      7086653.15      2843603.08      7086637.53
      2842828.55      7086902.64
#Sta/Elev= 30
  3992.8  498.85  4192.1  482.90  4197.1  483.21  4285.7  477.66  4385.8  470.58
  4469.9  467.85  4615.8  465.24  4821.9  465.97  4987.8  468.11  4993.2  467.84
  4998.5  463.53  5001.7  462.74  5002.6  461.94  5011.2  461.94  5012.1  462.74
  5024.5  467.69  5062.6  467.40  5306.1  466.03  5334.4  467.85  5337.4  468.71
  5378.1  470.44  5447.8  471.65  5482.5  472.73  5493.9  474.40  5519.9  474.70
  5525.2  476.43  5551.2  476.89  5556.5  478.12  5639.8  482.05  5806.4  494.53
#Mann=7,-1,0
  3992.8    0.05       0  4821.9    0.12       0  5001.7    0.07       0
  5012.1    0.12       0  5062.6    0.07       0  5378.1    0.12       0
  5447.8    0.05       0
Bank Sta=4469.9,5334.4
Exp/Cntr=0.3,0.1

Type RM Length L Ch R = 1,81228,511,511,511
BEGIN DESCRIPTION:
BIRCH CREEK 93.0
END DESCRIPTION:
XS GIS Cut Line= 3
      2844624.99      7086325.00      2843660.37      7086226.07
      2842838.71      7086605.70
#Sta/Elev= 30
  4149.0  515.40  4159.0  515.65  4169.1  513.93  4229.4  497.48  4249.5  493.78
  4319.9  487.92  4389.6  480.44  4420.4  478.92  4488.9  473.61  4623.8  466.44
  4711.9  465.19  4838.4  464.86  4937.8  465.83  4980.2  466.43  4985.2  463.93
  4988.1  463.44  4989.0  462.64  4997.8  462.64  4998.6  463.44  5003.4  466.21
  5013.5  466.60  5073.8  466.11  5124.8  464.33  5442.7  464.52  5589.1  464.56
  5731.0  464.68  5847.9  466.44  5936.5  471.44  6010.8  478.66  6023.8  477.45
#Mann=9,-1,0
  4149.0    0.05       0  4838.4    0.07       0  4937.8    0.12       0
  4988.1    0.07       0  4998.6    0.12       0  5124.8    0.07       0
  5442.7    0.12       0  5589.1    0.07       0  5731.0    0.12       0
Bank Sta=4623.8,5847.9
Exp/Cntr=0.3,0.1

Type RM Length L Ch R = 1,80717,631,631,631
BEGIN DESCRIPTION:
double BIRCH CREEK 92.0
END DESCRIPTION:
XS GIS Cut Line= 3
      2844504.12      7086132.32      2843532.19      7085927.85
      2842603.10      7085923.99
#Sta/Elev= 30
  4006.8  486.63  4069.5  483.71  4114.2  478.76  4128.5  479.02  4158.9  476.69
  4164.0  477.29  4208.8  474.85  4353.2  470.96  4635.0  465.76  4935.7  465.43
  4990.8  465.91  4993.8  464.43  4996.0  463.34  5000.0  463.34  5001.9  462.03
  5002.8  461.23  5011.6  461.23  5012.4  462.03  5017.2  465.10  5027.2  465.29
  5067.2  464.21  5140.2  464.05  5327.2  462.57  5507.2  462.22  5597.2  462.74
  5651.0  464.43  5687.2  467.01  5827.2  484.57  5877.2  491.65  5929.1  495.98
#Mann=6,-1,0
  4006.8    0.05       0  4635.0    0.12       0  4935.7    0.07       0
  5001.9    0.07       0  5012.4    0.07       0  5140.2    0.05       0
Bank Sta=4993.8,5651
Exp/Cntr=0.3,0.1

Type RM Length L Ch R = 1,80086,572,572,572
BEGIN DESCRIPTION:
double BIRCH CREEK 91.0
END DESCRIPTION:
XS GIS Cut Line= 3
      2844431.21      7085653.15      2843656.42      7085421.07
      2842311.39      7085434.40
#Sta/Elev= 30
  4191.2  484.50  4232.7  480.57  4312.5  474.54  4416.9  469.89  4477.6  470.13
  4698.8  465.30  4855.3  462.94  4886.7  464.10  4900.7  463.22  4918.0  464.19
  4980.6  464.41  4989.8  462.75  4994.8  461.58  5003.2  460.75  5011.4  464.89
  5094.1  462.16  5201.4  460.78  5486.2  460.18  5487.0  459.38  5495.8  459.38
  5496.7  460.18  5701.5  460.38  5808.0  462.75  5891.5  466.16  5951.5  472.27
  6131.5  486.72  6201.5  493.82  6241.5  496.84  6291.5  502.98  6345.1  508.16
#Mann=6,-1,0
  4191.2    0.16       0  4232.7    0.12       0  4994.8    0.07       0
  5094.1    0.05       0  5486.2    0.07       0  5496.7    0.05       0
Bank Sta=4989.8,5808
Exp/Cntr=0.3,0.1