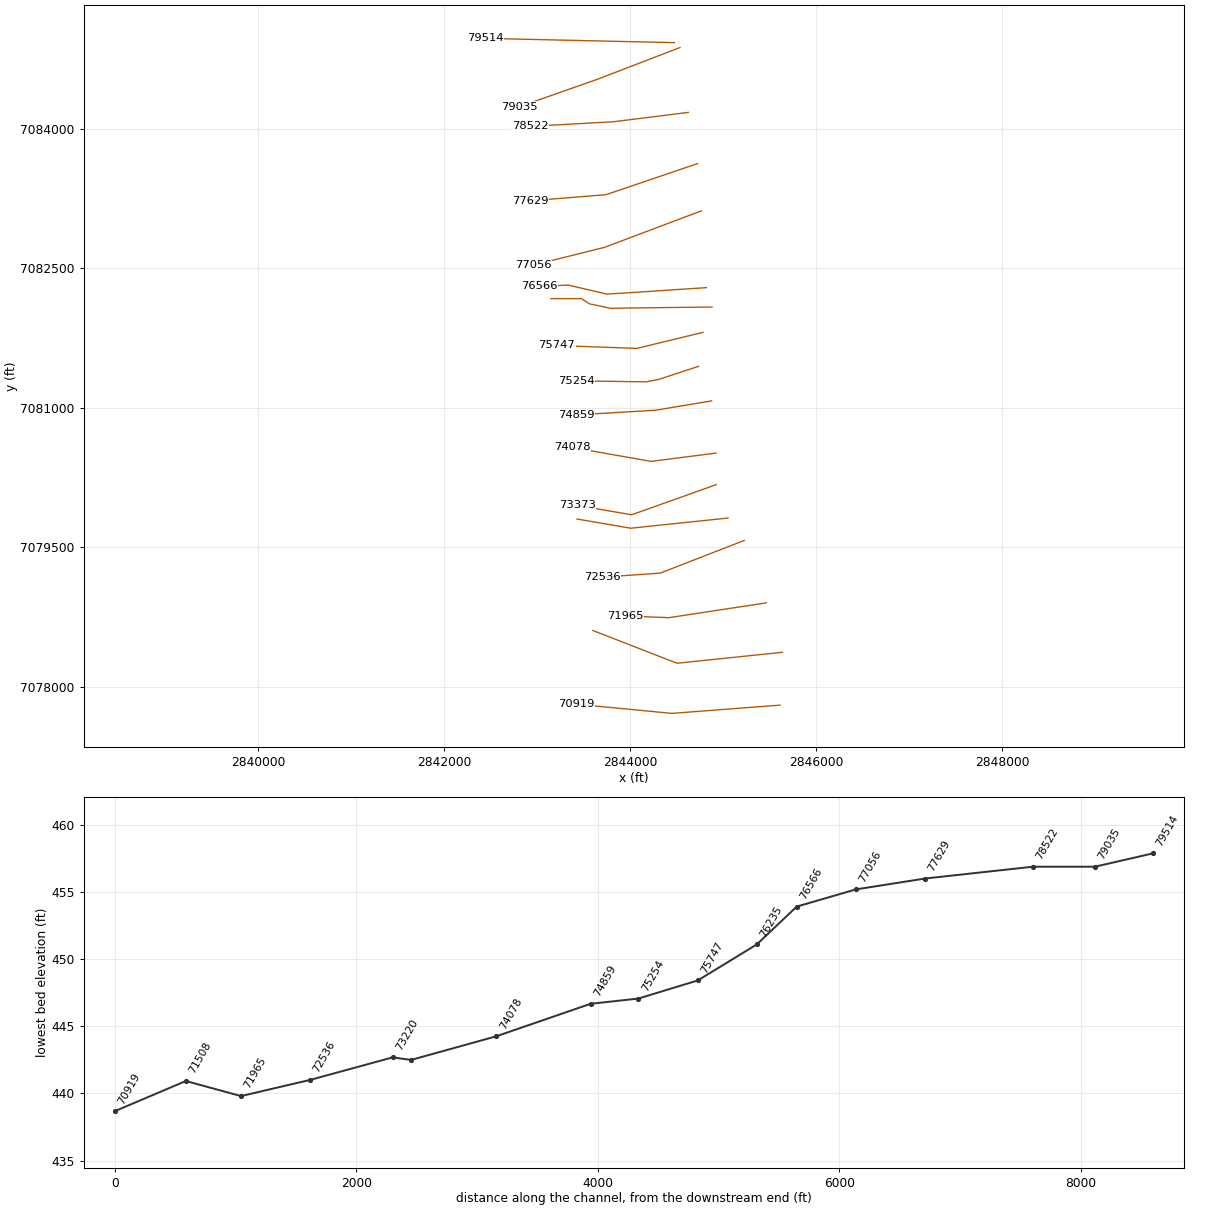
HEC-RAS study BIRCH CREEK.prj: BIRCH CREEK Base Level Engineering

--- BIRCH CREEK.g01 (geometry) --- (continued)

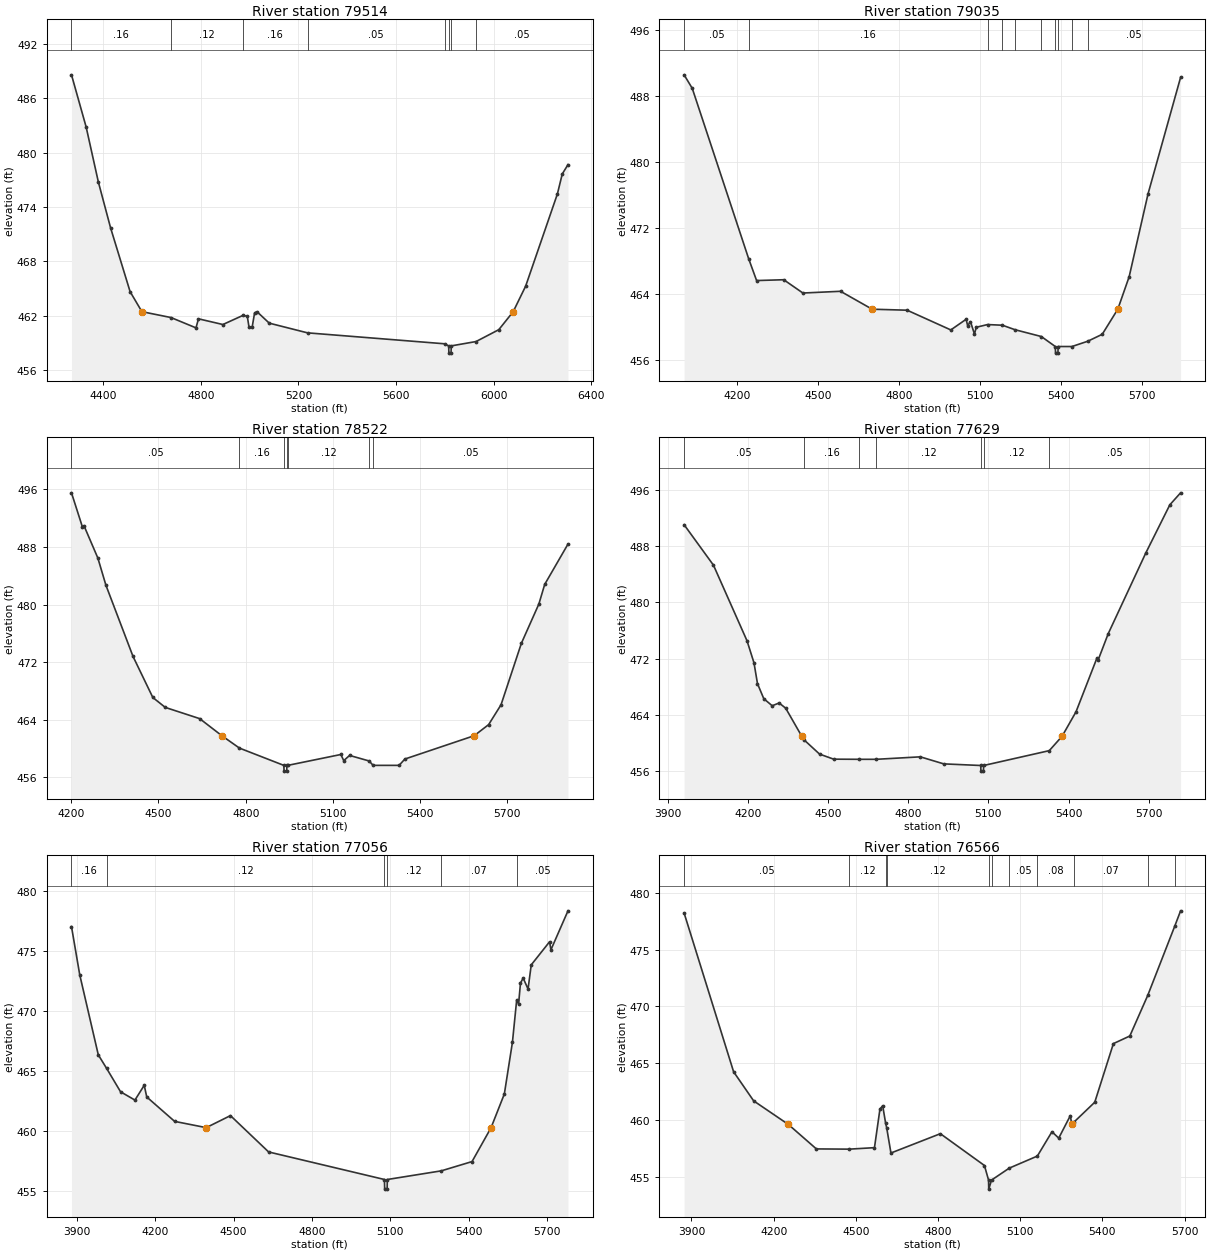
Type RM Length L Ch R = 1,79514,479,479,479
BEGIN DESCRIPTION:
double BIRCH CREEK 90.0
END DESCRIPTION:
XS GIS Cut Line= 3
      2844475.02      7084925.00      2843745.59      7084940.71
      2842441.64      7084970.86
#Sta/Elev= 30
  4270.4  488.61  4330.4  482.85  4380.4  476.78  4430.5  471.71  4510.5  464.66
  4558.8  462.45  4678.1  461.80  4780.5  460.66  4790.5  461.66  4890.6  461.03
  4973.8  462.05  4990.6  461.93  4997.8  460.71  5010.6  460.76  5020.6  462.32
  5030.6  462.44  5080.6  461.18  5237.3  460.11  5799.4  458.90  5815.6  458.67
  5816.4  457.87  5825.2  457.87  5826.1  458.67  5927.7  459.15  6020.9  460.46
  6079.9  462.45  6130.9  465.27  6260.9  475.45  6280.9  477.66  6304.3  478.69
#Mann=8,-1,0
  4270.4    0.16       0  4678.1    0.12       0  4973.8    0.16       0
  5237.3    0.05       0  5799.4    0.07       0  5815.6    0.07       0
  5826.1    0.07       0  5927.7    0.05       0
Bank Sta=4558.8,6079.9
Exp/Cntr=0.3,0.1

Type RM Length L Ch R = 1,79035,513,513,513
BEGIN DESCRIPTION:
double Mapping XS 45c23713
END DESCRIPTION:
XS GIS Cut Line= 3
      2844535.38      7084871.91      2843655.16      7084533.36
      2842811.44      7084236.50
#Sta/Elev= 30
  4005.3  490.59  4035.5  488.95  4244.3  468.31  4273.6  465.67  4374.0  465.77
  4445.0  464.16  4584.3  464.37  4701.3  462.20  4830.7  462.08  4992.4  459.69
  5049.1  460.98  5054.6  460.21  5065.2  460.69  5080.0  459.18  5086.4  460.01
  5128.2  460.34  5183.4  460.26  5229.6  459.72  5327.5  458.89  5379.1  457.68
  5380.0  456.88  5388.8  456.88  5389.6  457.68  5440.7  457.68  5499.2  458.32
  5552.8  459.16  5610.4  462.20  5652.5  466.14  5722.4  476.18  5842.8  490.28
#Mann=10,-1,0
  4005.3    0.05       0  4244.3    0.16       0  5128.2    0.07       0
  5183.4    0.05       0  5229.6    0.07       0  5327.5    0.05       0
  5379.1    0.07       0  5389.6    0.05       0  5440.7    0.07       0
  5499.2    0.05       0
Bank Sta=4701.3,5610.4
Exp/Cntr=0.3,0.1

Type RM Length L Ch R = 1,78522,893,893,893
BEGIN DESCRIPTION:
double BIRCH CREEK 89.0
END DESCRIPTION:
XS GIS Cut Line= 3
      2844624.99      7084175.00      2843825.00      7084075.00
      2842925.01      7084025.00
#Sta/Elev= 30
  4200.8  495.53  4238.6  490.76  4243.6  490.98  4291.5  486.47  4319.2  482.70
  4412.4  472.81  4480.5  467.11  4523.3  465.73  4641.7  464.17  4717.9  461.80
  4778.4  460.08  4931.1  457.68  4932.0  456.88  4941.0  456.88  4941.8  457.68
  4944.7  457.68  5127.2  459.19  5137.2  458.34  5157.3  459.06  5224.5  458.29
  5238.2  457.68  5327.5  457.68  5347.5  458.56  5585.9  461.80  5635.5  463.34
  5678.1  466.09  5748.2  474.64  5808.3  480.09  5828.3  482.81  5908.4  488.41
#Mann=7,-1,0
  4200.8    0.05       0  4778.4    0.16       0  4931.1    0.07       0
  4941.8    0.16       0  4944.7    0.12       0  5224.5    0.07       0
  5238.2    0.05       0
Bank Sta=4717.9,5585.9
Exp/Cntr=0.3,0.1

Type RM Length L Ch R = 1,77629,573,573,573
BEGIN DESCRIPTION:
BIRCH CREEK 88.0
END DESCRIPTION:
XS GIS Cut Line= 3
      2844725.01      7083625.00      2843741.50      7083290.93
      2842924.96      7083225.00
#Sta/Elev= 30
  3961.3  491.01  4071.2  485.26  4196.7  474.52  4222.8  471.39  4235.9  468.43
  4259.5  466.29  4290.9  465.29  4317.0  465.68  4341.5  464.94  4401.7  460.95
  4408.8  460.49  4468.2  458.42  4521.0  457.70  4616.4  457.68  4680.3  457.68
  4845.3  458.03  4932.9  457.03  5071.3  456.80  5072.0  456.00  5081.4  456.00
  5082.2  456.80  5327.8  458.91  5375.7  460.95  5427.9  464.43  5505.8  472.03
  5510.9  471.81  5548.3  475.52  5688.7  486.97  5779.0  493.84  5819.2  495.54
#Mann=7,-1,0
  3961.3    0.05       0  4408.8    0.16       0  4616.4    0.07       0
  4680.3    0.12       0  5071.3    0.07       0  5082.2    0.12       0
  5327.8    0.05       0
Bank Sta=4401.7,5375.7
Exp/Cntr=0.3,0.1

Type RM Length L Ch R = 1,77056,490,490,490
BEGIN DESCRIPTION:
BIRCH CREEK 87.0
END DESCRIPTION:
XS GIS Cut Line= 3
      2844764.56      7083116.70      2843725.00      7082725.00
      2842958.62      7082533.70
#Sta/Elev= 30
  3879.5  477.01  3911.1  473.00  3982.1  466.35  4014.1  465.22  4067.4  463.28
  4122.4  462.59  4158.0  463.82  4167.6  462.85  4274.4  460.82  4395.3  460.30
  4488.1  461.30  4634.2  458.28  5077.7  455.99  5078.5  455.19  5087.9  455.19
  5088.6  455.99  5295.4  456.71  5413.0  457.48  5485.9  460.30  5536.7  463.10
  5567.6  467.39  5584.0  470.93  5591.2  470.58  5598.5  472.32  5608.8  472.73
  5627.4  471.82  5639.7  473.83  5709.9  475.75  5715.0  475.08  5780.3  478.32
#Mann=6,-1,0
  3879.5    0.16       0  4014.1    0.12       0  5077.7    0.07       0
  5088.6    0.12       0  5295.4    0.07       0  5584.0    0.05       0
Bank Sta=4395.3,5485.9
Exp/Cntr=0.3,0.1

Type RM Length L Ch R = 1,76566,331,331,331
BEGIN DESCRIPTION:
Mapping XS 0737fa02
END DESCRIPTION:
XS GIS Cut Line= 6
      2844818.37      7082292.04      2844082.24      7082243.43
      2843748.91      7082222.60      2843585.72      7082260.79
      2843335.72      7082319.82      2843019.91      7082305.94
#Sta/Elev= 30
  3873.0  478.22  4053.7  464.24  4126.9  461.68  4253.8  459.60  4355.8  457.45
  4476.2  457.43  4567.9  457.56  4587.9  460.96  4597.9  461.25  4608.5  459.73
  4612.4  459.32  4628.0  457.09  4808.4  458.79  4969.3  455.99  4984.3  454.71
  4985.0  453.91  4995.4  454.71  5060.0  455.76  5162.4  456.82  5215.8  458.96
  5240.5  458.40  5282.8  460.38  5288.1  459.60  5295.2  459.79  5372.0  461.56
  5440.0  466.72  5500.0  467.39  5565.3  470.96  5664.3  477.08  5685.3  478.41
#Mann=11,-1,0
  3873.0    0.05       0  4476.2    0.12       0  4608.5    0.16       0
  4612.4    0.12       0  4984.3    0.07       0  4995.4    0.12       0
  5060.0    0.05       0  5162.4    0.08       0  5295.2    0.07       0
  5565.3    0.08       0  5664.3    0.05       0
Bank Sta=4253.8,5288.1
Exp/Cntr=0.3,0.1

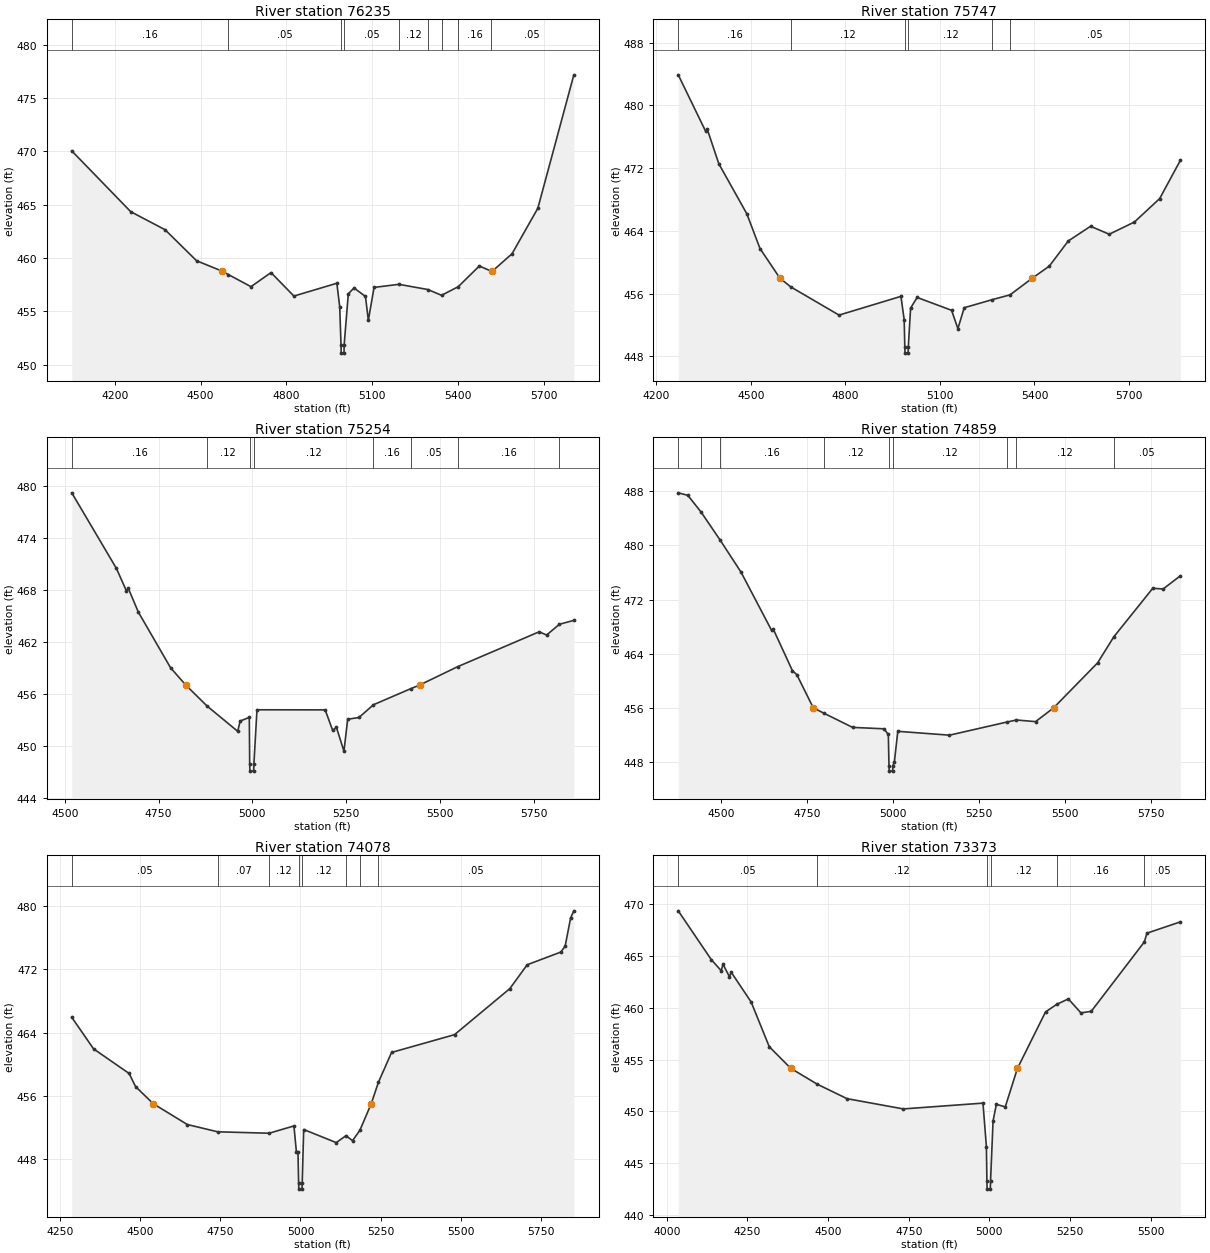
Type RM Length L Ch R = 1,76235,488,488,488
BEGIN DESCRIPTION:
Mapping XS 800dc53c
END DESCRIPTION:
XS GIS Cut Line= 6
      2844880.84      7082083.71      2843991.97      7082073.29
      2843790.58      7082069.82      2843561.41      7082118.43
      2843478.08      7082173.99      2843149.15      7082173.99
#Sta/Elev= 30
  4050.2  470.05  4256.1  464.35  4376.1  462.66  4486.1  459.75  4575.8  458.77
  4597.0  458.46  4676.1  457.32  4746.1  458.64  4826.1  456.44  4976.1  457.64
  4986.1  455.43  4990.6  451.89  4991.3  451.09  5001.0  451.09  5001.7  451.89
  5016.1  456.65  5036.1  457.20  5076.1  456.40  5086.1  454.17  5106.1  457.25
  5192.7  457.54  5294.4  457.05  5341.7  456.51  5400.2  457.32  5473.8  459.26
  5512.8  458.80  5519.1  458.77  5588.1  460.41  5678.1  464.67  5803.9  477.18
#Mann=9,-1,0
  4050.2    0.16       0  4597.0    0.05       0  4990.6    0.04       0
  5001.7    0.05       0  5192.7    0.12       0  5294.4    0.16       0
  5341.7    0.08       0  5400.2    0.16       0  5512.8    0.05       0
Bank Sta=4575.8,5519.1
Exp/Cntr=0.3,0.1

Type RM Length L Ch R = 1,75747,493,493,493
BEGIN DESCRIPTION:
BIRCH CREEK 85.0
END DESCRIPTION:
XS GIS Cut Line= 3
      2844781.93      7081811.15      2844071.76      7081639.15
      2843209.53      7081670.49
#Sta/Elev= 30
  4269.3  483.90  4356.4  476.69  4361.5  476.95  4398.2  472.55  4487.0  466.18
  4528.8  461.75  4592.0  457.97  4626.3  456.86  4779.7  453.26  4976.1  455.65
  4986.4  452.68  4988.4  449.21  4989.1  448.41  4998.8  448.41  4999.5  449.21
  5006.8  454.16  5027.6  455.51  5136.9  453.87  5156.9  451.53  5176.9  454.20
  5266.7  455.24  5322.3  455.84  5393.1  457.97  5447.1  459.51  5507.1  462.71
  5578.0  464.59  5637.2  463.57  5717.2  465.13  5797.3  468.12  5862.8  472.98
#Mann=6,-1,0
  4269.3    0.16       0  4626.3    0.12       0  4988.4    0.07       0
  4999.5    0.12       0  5266.7    0.16       0  5322.3    0.05       0
Bank Sta=4592,5393.1
Exp/Cntr=0.3,0.1

Type RM Length L Ch R = 1,75254,395,395,395
BEGIN DESCRIPTION:
Mapping XS 7fbc0667
END DESCRIPTION:
XS GIS Cut Line= 4
      2844735.02      7081446.55      2844307.94      7081305.93
      2844172.52      7081279.89      2843422.52      7081290.31
#Sta/Elev= 30
  4518.7  479.18  4637.7  470.45  4664.2  467.87  4669.5  468.14  4696.0  465.42
  4781.9  458.99  4822.5  456.99  4879.0  454.58  4960.9  451.65  4967.2  452.84
  4991.7  453.26  4992.7  447.86  4993.4  447.06  5003.2  447.06  5003.9  447.86
  5012.1  454.14  5193.8  454.13  5213.8  451.76  5223.8  452.11  5243.8  449.36
  5253.8  453.05  5283.8  453.25  5322.4  454.72  5421.5  456.57  5445.2  456.99
  5546.5  459.11  5763.8  463.14  5783.8  462.77  5817.9  464.01  5856.3  464.46
#Mann=8,-1,0
  4518.7    0.16       0  4879.0    0.12       0  4992.7    0.07       0
  5003.9    0.12       0  5322.4    0.16       0  5421.5    0.05       0
  5546.5    0.16       0  5817.9    0.05       0
Bank Sta=4822.5,5445.2
Exp/Cntr=0.3,0.1

Type RM Length L Ch R = 1,74859,781,781,781
BEGIN DESCRIPTION:
BIRCH CREEK 84.0
END DESCRIPTION:
XS GIS Cut Line= 3
      2844875.00      7081075.00      2844275.00      7080975.00
      2843425.05      7080925.00
#Sta/Elev= 30
  4375.0  487.77  4402.9  487.40  4441.0  484.96  4497.4  480.75  4557.5  476.06
  4646.2  467.48  4651.3  467.64  4707.0  461.50  4719.7  460.92  4767.6  456.02
  4797.5  455.25  4881.9  453.13  4973.1  452.92  4985.8  452.09  4987.7  447.47
  4988.4  446.67  4998.2  446.67  4998.9  447.47  5003.3  447.97  5013.3  452.55
  5163.6  451.98  5329.9  453.91  5358.4  454.22  5414.0  453.98  5466.4  456.02
  5594.3  462.66  5641.3  466.50  5754.6  473.67  5784.7  473.57  5834.7  475.51
#Mann=9,-1,0
  4375.0    0.16       0  4441.0    0.05       0  4497.4    0.16       0
  4797.5    0.12       0  4987.7    0.07       0  4998.9    0.12       0
  5329.9    0.05       0  5358.4    0.12       0  5641.3    0.05       0
Bank Sta=4767.6,5466.4
Exp/Cntr=0.3,0.1

Type RM Length L Ch R = 1,74078,705,705,705
BEGIN DESCRIPTION:
BIRCH CREEK 83.0
END DESCRIPTION:
XS GIS Cut Line= 3
      2844922.49      7080514.26      2844225.00      7080425.00
      2843375.01      7080575.00
#Sta/Elev= 30
  4286.6  465.92  4354.6  461.94  4465.5  458.84  4485.7  457.18  4540.9  455.02
  4647.0  452.40  4741.7  451.48  4902.3  451.30  4979.7  452.22  4987.3  448.98
  4992.3  448.98  4994.3  445.05  4995.0  444.25  5004.8  444.25  5005.5  445.05
  5010.1  451.77  5111.6  450.12  5142.2  450.99  5162.4  450.36  5185.4  451.67
  5220.8  455.02  5243.2  457.72  5284.3  461.49  5480.6  463.73  5653.2  469.54
  5707.4  472.55  5812.3  474.15  5825.8  474.90  5842.8  478.45  5852.9  479.35
#Mann=8,-1,0
  4286.6    0.05       0  4741.7    0.07       0  4902.3    0.12       0
  4994.3    0.07       0  5005.5    0.12       0  5142.2    0.07       0
  5185.4    0.12       0  5243.2    0.05       0
Bank Sta=4540.9,5220.8
Exp/Cntr=0.3,0.1

Type RM Length L Ch R = 1,73373,153,153,153
BEGIN DESCRIPTION:
BIRCH CREEK 82.0
END DESCRIPTION:
XS GIS Cut Line= 3
      2844925.00      7080175.00      2844016.35      7079851.25
      2843432.95      7079951.76
#Sta/Elev= 30
  4035.4  469.38  4138.0  464.66  4168.8  463.59  4174.1  464.23  4194.3  463.00
  4199.6  463.45  4261.3  460.58  4317.6  456.25  4384.3  454.16  4466.3  452.63
  4558.8  451.23  4733.2  450.24  4980.2  450.80  4990.8  446.60  4992.4  443.29
  4993.1  442.49  5003.0  442.49  5003.7  443.29  5011.5  449.09  5021.7  450.68
  5049.3  450.44  5087.1  454.16  5174.1  459.61  5208.6  460.34  5244.9  460.87
  5283.8  459.52  5315.9  459.67  5480.6  466.38  5488.4  467.22  5592.0  468.31
#Mann=6,-1,0
  4035.4    0.05       0  4466.3    0.12       0  4992.4    0.07       0
  5003.7    0.12       0  5208.6    0.16       0  5480.6    0.05       0
Bank Sta=4384.3,5087.1
Exp/Cntr=0.3,0.1

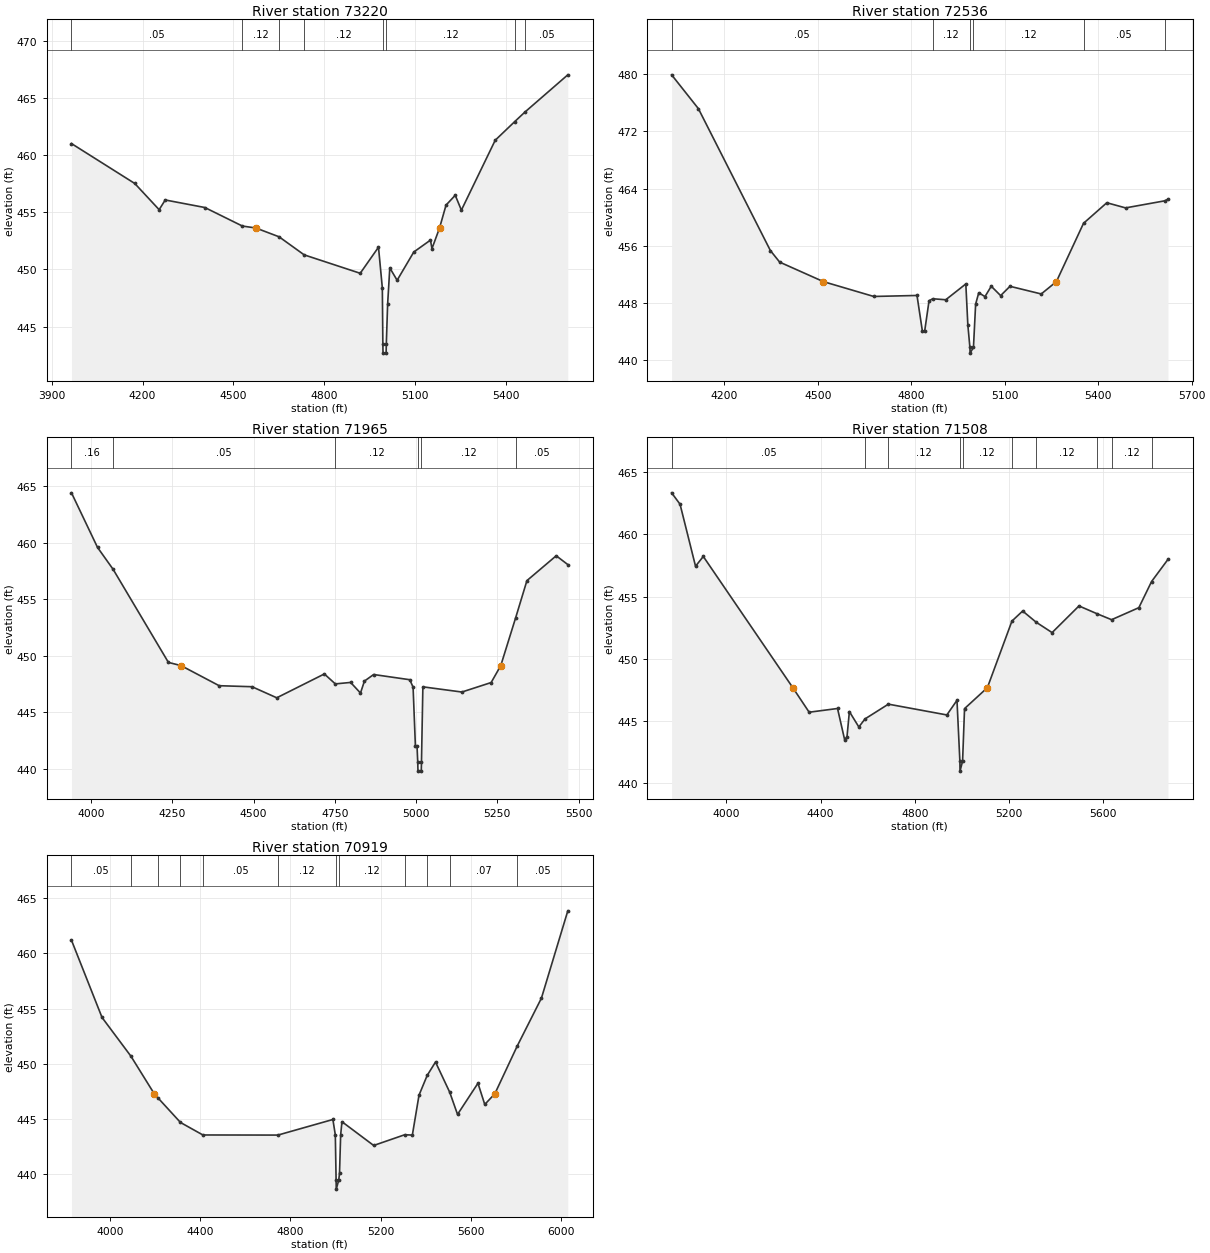
Type RM Length L Ch R = 1,73220,684,684,684
BEGIN DESCRIPTION:
Mapping XS 7757066a
END DESCRIPTION:
XS GIS Cut Line= 3
      2845052.73      7079816.35      2844005.86      7079706.97
      2843428.82      7079805.74
#Sta/Elev= 30
  3965.4  461.00  4174.3  457.51  4254.7  455.22  4274.8  456.07  4405.5  455.41
  4529.4  453.79  4573.8  453.62  4650.5  452.85  4733.4  451.27  4918.3  449.66
  4978.6  451.94  4991.3  448.38  4993.0  443.48  4993.6  442.68  5003.8  442.68
  5004.4  443.48  5008.8  446.98  5015.9  450.13  5040.1  449.05  5095.1  451.52
  5150.1  452.56  5155.1  451.82  5180.1  453.62  5201.5  455.62  5231.9  456.48
  5252.2  455.18  5363.8  461.29  5428.2  462.92  5462.1  463.76  5603.4  467.01
#Mann=8,-1,0
  3965.4    0.05       0  4529.4    0.12       0  4650.5    0.07       0
  4733.4    0.12       0  4993.0    0.07       0  5004.4    0.12       0
  5428.2    0.16       0  5462.1    0.05       0
Bank Sta=4573.8,5180.1
Exp/Cntr=0.3,0.1

Type RM Length L Ch R = 1,72536,571,571,571
BEGIN DESCRIPTION:
BIRCH CREEK 81.0
END DESCRIPTION:
XS GIS Cut Line= 3
      2845224.98      7079574.99      2844325.00      7079225.00
      2843699.29      7079180.98
#Sta/Elev= 30
  4031.0  479.90  4116.8  475.18  4347.9  455.34  4377.8  453.72  4518.4  450.99
  4679.7  448.92  4818.5  449.06  4835.7  444.10  4843.0  444.04  4857.2  448.32
  4869.1  448.60  4910.8  448.46  4975.2  450.67  4981.7  444.93  4988.3  441.80
  4988.9  441.00  4999.7  441.80  5006.7  447.85  5016.7  449.44  5036.7  448.90
  5056.8  450.35  5086.9  449.04  5116.9  450.34  5217.2  449.27  5265.8  450.99
  5353.0  459.15  5427.7  462.02  5487.9  461.30  5613.8  462.29  5623.9  462.51
#Mann=6,-1,0
  4031.0    0.05       0  4869.1    0.12       0  4988.3    0.07       0
  4999.7    0.12       0  5353.0    0.05       0  5613.8    0.16       0
Bank Sta=4518.4,5265.8
Exp/Cntr=0.3,0.1

Type RM Length L Ch R = 1,71965,457,457,457
BEGIN DESCRIPTION:
BIRCH CREEK 80.0
END DESCRIPTION:
XS GIS Cut Line= 3
      2845464.24      7078904.90      2844415.86      7078745.68
      2843949.33      7078764.23
#Sta/Elev= 30
  3939.6  464.43  4019.7  459.60  4067.7  457.66  4237.9  449.42  4276.7  449.14
  4394.0  447.36  4495.1  447.27  4571.3  446.29  4717.7  448.40  4751.5  447.52
  4798.6  447.65  4828.9  446.71  4841.1  447.77  4869.4  448.35  4980.6  447.89
  4990.8  447.23  4997.9  442.03  5002.9  442.03  5005.1  440.60  5005.8  439.80
  5016.0  439.80  5016.6  440.60  5020.9  447.26  5141.0  446.80  5231.0  447.64
  5260.6  449.14  5306.6  453.39  5341.1  456.66  5431.2  458.86  5466.9  458.08
#Mann=6,-1,0
  3939.6    0.16       0  4067.7    0.05       0  4751.5    0.12       0
  5005.1    0.07       0  5016.6    0.12       0  5306.6    0.05       0
Bank Sta=4276.7,5260.6
Exp/Cntr=0.3,0.1

Type RM Length L Ch R = 1,71508,589,589,589
BEGIN DESCRIPTION:
BIRCH CREEK 79.0
END DESCRIPTION:
XS GIS Cut Line= 3
      2845636.08      7078373.64      2844503.26      7078256.14
      2843599.83      7078607.92
#Sta/Elev= 30
  3766.9  463.36  3802.7  462.44  3868.5  457.44  3901.4  458.23  4281.7  447.65
  4351.1  445.67  4471.7  445.97  4501.9  443.45  4512.0  443.71  4522.0  445.72
  4562.2  444.48  4588.4  445.13  4687.7  446.32  4936.1  445.45  4979.1  446.63
  4991.4  441.72  4992.0  440.92  5002.9  441.72  5011.2  445.96  5108.2  447.65
  5212.6  453.02  5258.1  453.83  5315.3  452.93  5383.2  452.09  5497.4  454.24
  5575.3  453.60  5635.9  453.13  5751.7  454.10  5805.8  456.21  5875.3  457.99
#Mann=10,-1,0
  3766.9    0.05       0  4588.4    0.07       0  4687.7    0.12       0
  4991.4    0.07       0  5002.9    0.12       0  5212.6    0.07       0
  5315.3    0.12       0  5575.3    0.16       0  5635.9    0.12       0
  5805.8    0.16       0
Bank Sta=4281.7,5108.2
Exp/Cntr=0.3,0.1

Type RM Length L Ch R = 1,70919,471,471,471
BEGIN DESCRIPTION:
Mapping XS 75920cd0
END DESCRIPTION:
XS GIS Cut Line= 3
      2845610.05      7077805.93      2844448.56      7077717.39
      2843418.65      7077816.22
#Sta/Elev= 30
  3830.2  461.19  3965.6  454.20  4093.5  450.70  4196.9  447.30  4214.1  446.91
  4313.3  444.70  4412.5  443.57  4745.0  443.56  4988.6  444.97  4999.4  443.58
  5002.9  439.47  5003.6  438.67  5014.4  439.47  5018.0  440.10  5023.1  443.58
  5028.8  444.77  5169.4  442.62  5306.9  443.59  5340.8  443.56  5370.3  447.17
  5406.6  448.96  5443.4  450.17  5506.3  447.44  5541.0  445.43  5631.5  448.25
  5661.7  446.33  5706.4  447.30  5805.6  451.62  5912.8  455.95  6029.7  463.85
#Mann=12,-1,0
  3830.2    0.05       0  4093.5    0.07       0  4214.1    0.12       0
  4313.3    0.07       0  4412.5    0.05       0  4745.0    0.12       0
  5002.9    0.07       0  5014.4    0.12       0  5306.9    0.07       0
  5406.6    0.05       0  5506.3    0.07       0  5805.6    0.05       0
Bank Sta=4196.9,5706.4
Exp/Cntr=0.3,0.1