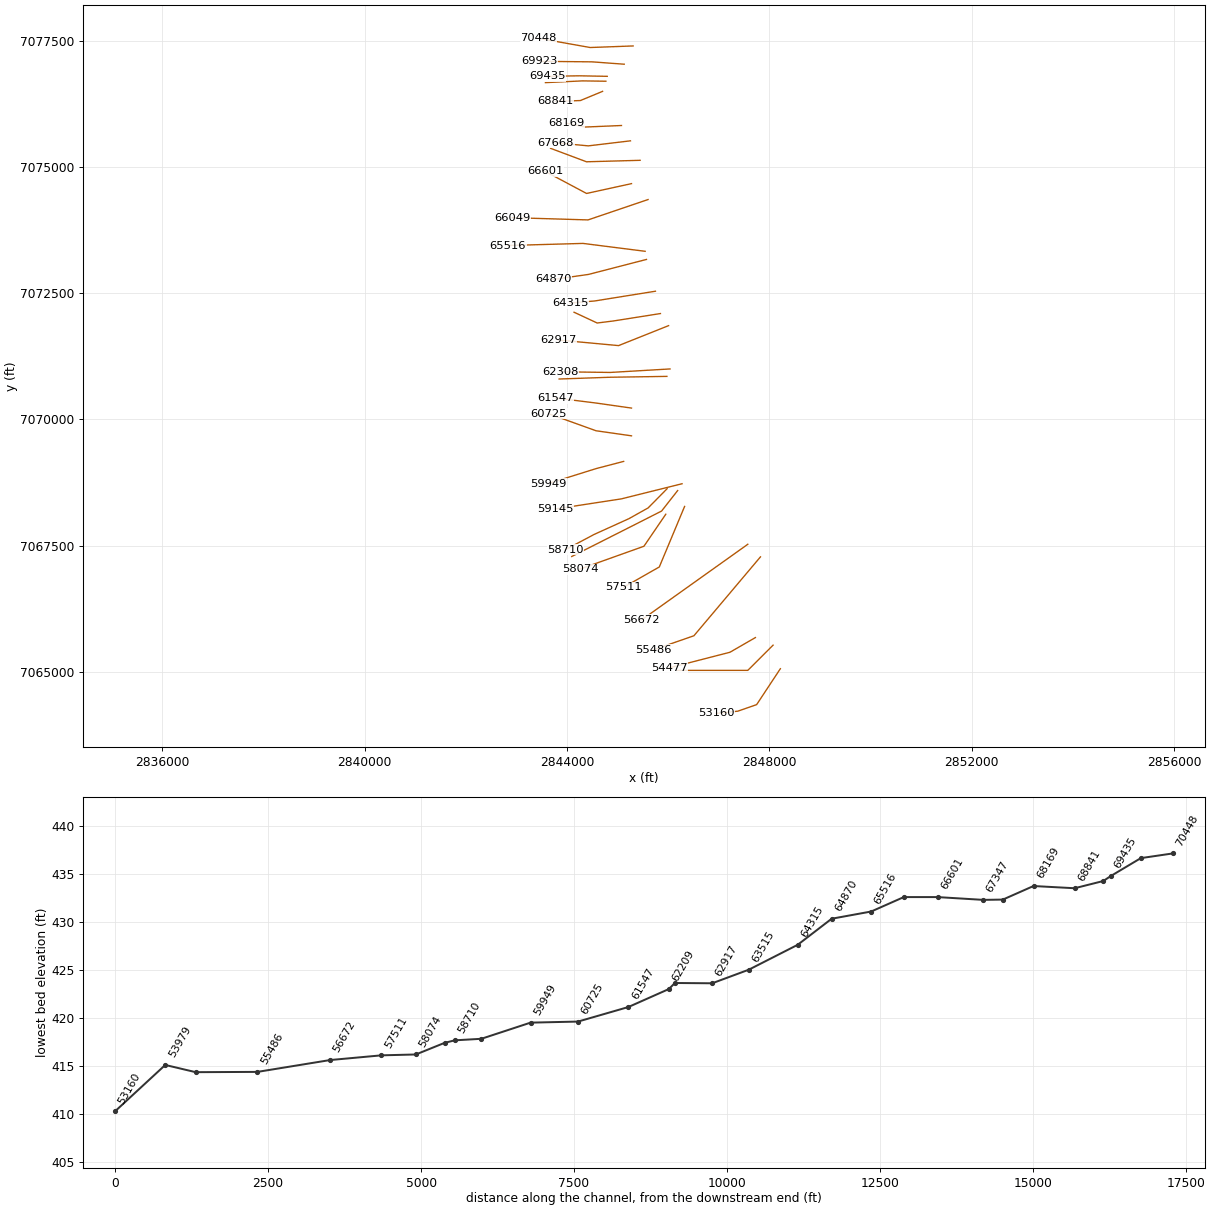
HEC-RAS study BIRCH CREEK.prj: BIRCH CREEK Base Level Engineering

--- BIRCH CREEK.g01 (geometry) --- (continued)

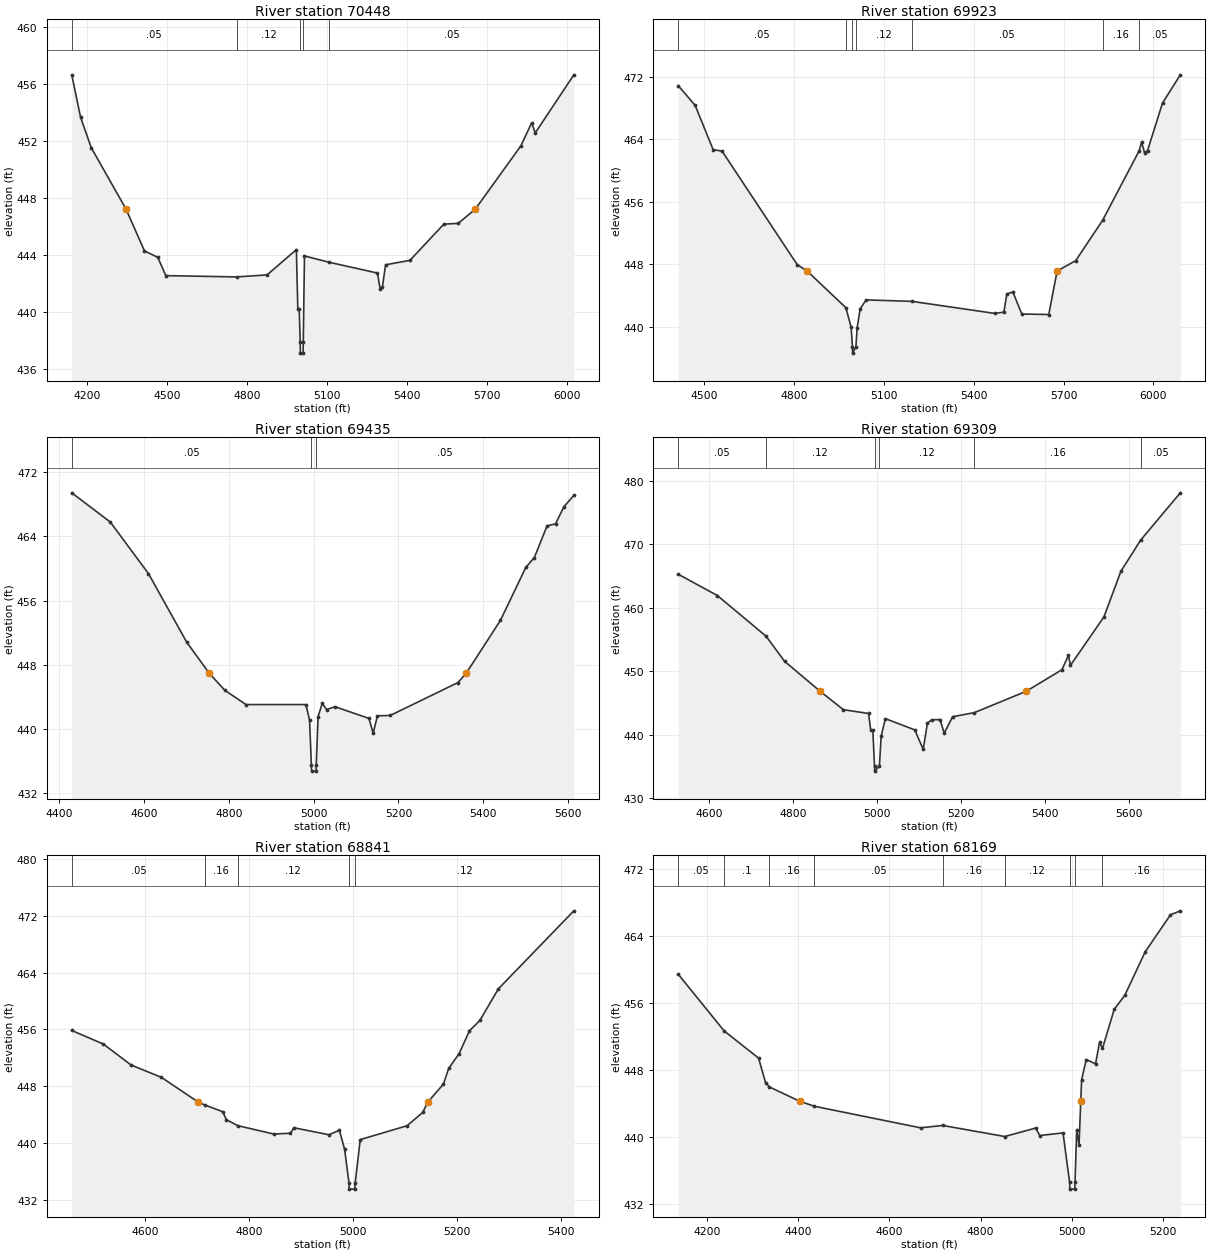
Type RM Length L Ch R = 1,70448,525,525,525
BEGIN DESCRIPTION:
Mapping XS f3d94e8b
END DESCRIPTION:
XS GIS Cut Line= 3
      2845307.92      7077404.89      2844458.98      7077373.64
      2843439.03      7077555.77
#Sta/Elev= 30
  4141.5  456.61  4174.4  453.66  4214.5  451.52  4345.3  447.21  4414.6  444.28
  4464.6  443.83  4494.7  442.55  4760.5  442.46  4874.9  442.60  4985.0  444.37
  4990.5  440.22  4995.6  440.22  4999.5  437.92  5000.1  437.12  5010.3  437.12
  5011.0  437.92  5015.4  443.93  5107.2  443.49  5289.6  442.73  5299.8  441.60
  5308.3  441.78  5320.1  443.31  5411.5  443.62  5538.9  446.16  5592.7  446.21
  5657.1  447.21  5828.4  451.65  5868.7  453.26  5882.2  452.55  6027.1  456.62
#Mann=5,-1,0
  4141.5    0.05       0  4760.5    0.12       0  4999.5    0.07       0
  5011.0    0.12       0  5107.2    0.05       0
Bank Sta=4345.3,5657.1
Exp/Cntr=0.3,0.1

Type RM Length L Ch R = 1,69923,488,488,488
BEGIN DESCRIPTION:
Mapping XS d80a84f4
END DESCRIPTION:
XS GIS Cut Line= 3
      2845131.22      7077042.73      2844495.79      7077089.61
      2843455.50      7077100.01
#Sta/Elev= 30
  4412.6  470.84  4469.0  468.33  4529.1  462.67  4559.2  462.46  4809.9  447.96
  4843.4  447.13  4972.9  442.43  4990.4  439.91  4994.6  437.43  4995.2  436.63
  5006.2  437.43  5010.4  439.88  5020.5  442.30  5040.5  443.44  5193.9  443.25
  5470.6  441.71  5500.6  441.87  5510.6  444.21  5530.6  444.45  5560.6  441.63
  5650.6  441.57  5678.5  447.13  5740.6  448.46  5830.2  453.60  5952.2  462.48
  5960.6  463.62  5970.6  462.27  5980.6  462.53  6030.6  468.62  6090.1  472.23
#Mann=7,-1,0
  4412.6    0.05       0  4972.9    0.12       0  4994.6    0.07       0
  5006.2    0.12       0  5193.9    0.05       0  5830.2    0.16       0
  5952.2    0.05       0
Bank Sta=4843.4,5678.5
Exp/Cntr=0.3,0.1

Type RM Length L Ch R = 1,69435,126,126,126
BEGIN DESCRIPTION:
Mapping XS 960308f1
END DESCRIPTION:
XS GIS Cut Line= 3
      2844795.81      7076802.46      2844243.70      7076812.87
      2843611.79      7076802.46
#Sta/Elev= 30
  4429.5  469.40  4520.3  465.77  4610.3  459.36  4700.4  450.84  4753.4  446.98
  4790.4  444.84  4840.4  443.06  4981.7  443.06  4990.4  441.13  4994.6  435.58
  4995.2  434.78  5005.6  434.78  5006.2  435.58  5010.4  441.54  5020.4  443.22
  5030.4  442.44  5050.4  442.79  5130.4  441.34  5140.4  439.49  5150.4  441.66
  5180.4  441.70  5340.5  445.80  5360.1  446.98  5440.5  453.53  5500.5  460.13
  5520.5  461.34  5550.5  465.29  5570.5  465.54  5590.5  467.69  5613.7  469.07
#Mann=3,-1,0
  4429.5    0.05       0  4994.6    0.04       0  5006.2    0.05       0
Bank Sta=4753.4,5360.1
Exp/Cntr=0.3,0.1

Type RM Length L Ch R = 1,69309,468,468,468
BEGIN DESCRIPTION:
Mapping XS 684ce27c
END DESCRIPTION:
XS GIS Cut Line= 3
      2844768.05      7076705.24      2844309.68      7076712.18
      2843573.53      7076677.46
#Sta/Elev= 30
  4526.4  465.29  4619.5  461.94  4735.7  455.51  4779.5  451.57  4864.5  446.83
  4919.5  443.94  4979.5  443.34  4984.7  440.71  4989.7  440.71  4993.7  435.05
  4994.2  434.25  5005.4  435.05  5009.5  439.73  5019.5  442.53  5089.6  440.75
  5109.6  437.68  5119.7  441.81  5129.7  442.34  5149.7  442.38  5159.7  440.23
  5179.7  442.83  5231.2  443.47  5354.7  446.83  5440.0  450.24  5455.3  452.49
  5460.3  450.94  5540.1  458.58  5580.2  465.74  5627.4  470.68  5721.8  478.13
#Mann=6,-1,0
  4526.4    0.05       0  4735.7    0.12       0  4993.7    0.07       0
  5005.4    0.12       0  5231.2    0.16       0  5627.4    0.05       0
Bank Sta=4864.5,5354.7
Exp/Cntr=0.3,0.1

Type RM Length L Ch R = 1,68841,672,672,672
BEGIN DESCRIPTION:
Mapping XS f2f39cda
END DESCRIPTION:
XS GIS Cut Line= 3
      2844703.25      7076504.54      2844264.88      7076322.25
      2843774.45      7076304.89
#Sta/Elev= 30
  4458.8  455.86  4519.6  453.94  4572.7  451.00  4631.2  449.25  4702.5  445.74
  4714.9  445.35  4749.3  444.41  4755.9  443.30  4777.7  442.45  4846.8  441.27
  4879.3  441.37  4886.0  442.15  4953.5  441.16  4973.5  441.80  4983.5  439.10
  4992.0  434.30  4992.5  433.50  5003.1  433.50  5003.7  434.30  5013.5  440.48
  5103.5  442.43  5133.6  444.30  5143.2  445.74  5173.6  448.31  5183.6  450.51
  5203.6  452.59  5223.6  455.82  5243.6  457.27  5279.2  461.73  5424.3  472.72
#Mann=5,-1,0
  4458.8    0.05       0  4714.9    0.16       0  4777.7    0.12       0
  4992.0    0.07       0  5003.7    0.12       0
Bank Sta=4702.5,5143.2
Exp/Cntr=0.3,0.1

Type RM Length L Ch R = 1,68169,501,501,501
BEGIN DESCRIPTION:
Mapping XS 96121fb8
END DESCRIPTION:
XS GIS Cut Line= 3
      2845076.56      7075827.46      2844360.37      7075797.08
      2843982.80      7075875.19
#Sta/Elev= 30
  4136.2  459.38  4237.1  452.61  4312.6  449.37  4327.9  446.45  4336.2  445.93
  4403.0  444.22  4435.2  443.62  4668.2  441.05  4716.9  441.33  4853.2  440.01
  4920.9  441.02  4930.0  440.13  4981.1  440.44  4995.6  434.53  4996.1  433.73
  5006.8  433.73  5007.4  434.53  5011.1  440.82  5016.2  438.98  5020.0  444.22
  5021.9  446.79  5032.1  449.20  5052.5  448.68  5061.3  451.27  5067.7  450.52
  5093.4  455.18  5116.6  456.86  5161.7  462.08  5217.0  466.47  5238.6  466.95
#Mann=9,-1,0
  4136.2    0.05       0  4237.1     0.1       0  4336.2    0.16       0
  4435.2    0.05       0  4716.9    0.16       0  4853.2    0.12       0
  4995.6    0.07       0  5007.4    0.12       0  5067.7    0.16       0
Bank Sta=4403,5020
Exp/Cntr=0.3,0.1

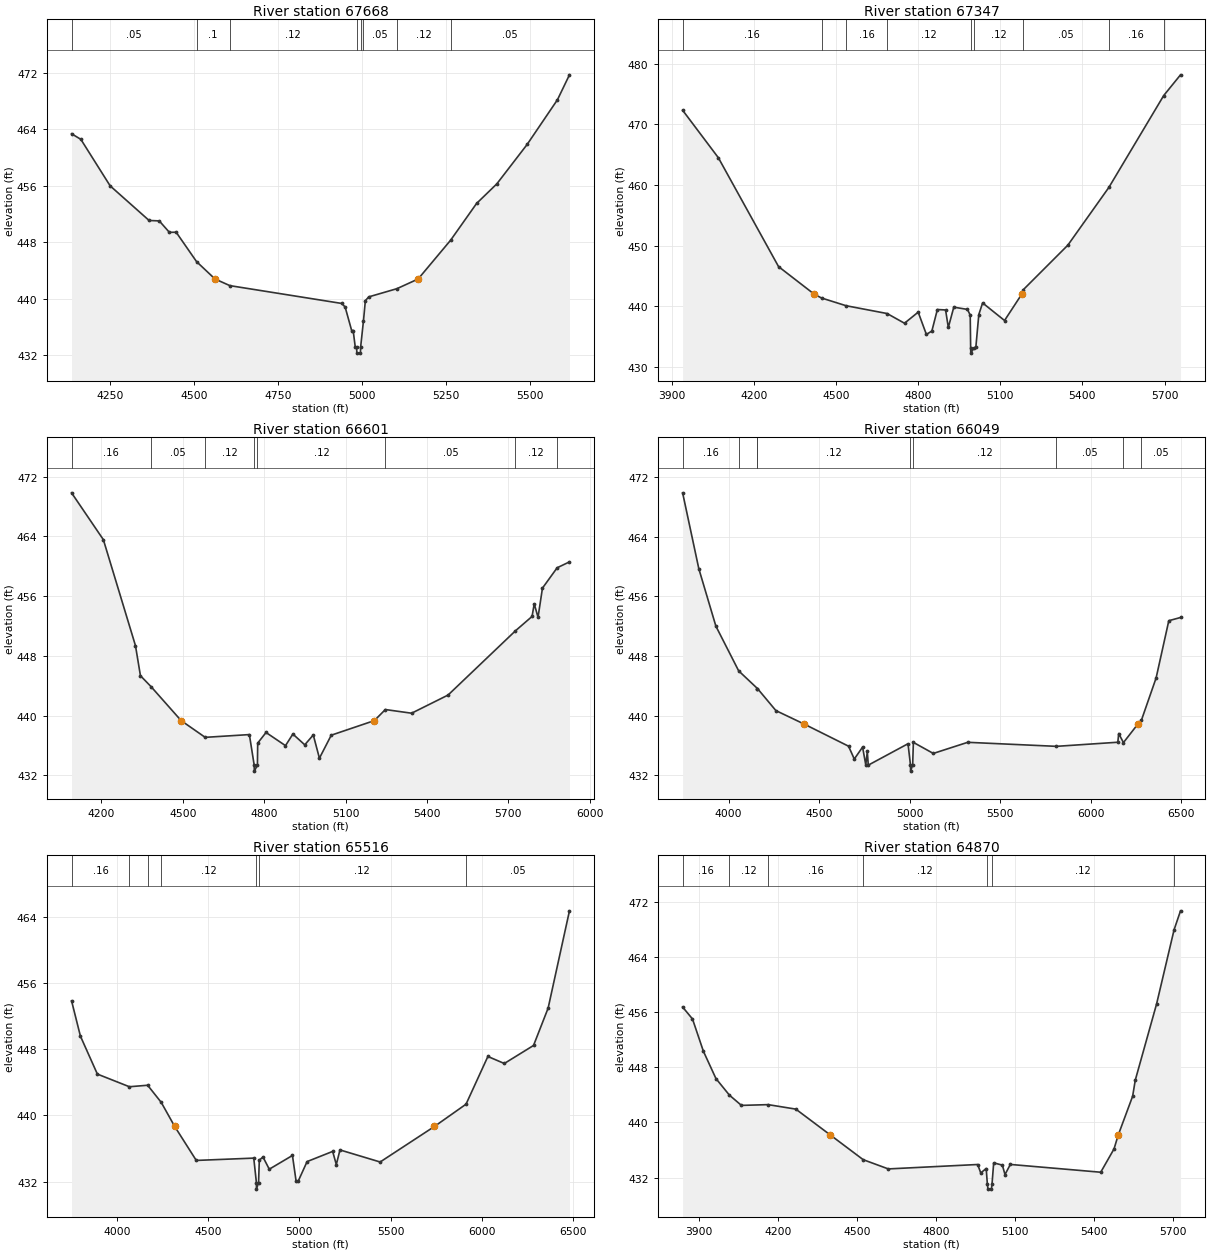
Type RM Length L Ch R = 1,67668,321,321,321
BEGIN DESCRIPTION:
Mapping XS 4b8c5992
END DESCRIPTION:
XS GIS Cut Line= 3
      2845254.51      7075523.64      2844421.13      7075423.81
      2843779.43      7075484.51
#Sta/Elev= 30
  4135.1  463.36  4162.8  462.57  4250.1  455.99  4366.2  451.09  4396.5  451.03
  4426.7  449.41  4446.8  449.43  4507.6  445.27  4562.6  442.81  4607.0  441.87
  4940.3  439.35  4950.4  438.85  4970.0  435.50  4974.4  435.50  4980.6  433.19
  4984.7  433.12  4985.3  432.32  4996.0  432.32  4996.5  433.12  5005.1  436.90
  5010.7  439.74  5020.8  440.28  5104.8  441.44  5168.0  442.81  5265.0  448.31
  5342.2  453.50  5402.5  456.27  5492.9  461.85  5583.3  468.18  5619.0  471.70
#Mann=8,-1,0
  4135.1    0.05       0  4507.6     0.1       0  4607.0    0.12       0
  4984.7    0.07       0  4996.5    0.12       0  5005.1    0.05       0
  5104.8    0.12       0  5265.0    0.05       0
Bank Sta=4562.6,5168
Exp/Cntr=0.3,0.1

Type RM Length L Ch R = 1,67347,746,746,746
BEGIN DESCRIPTION:
BIRCH CREEK 74.0
END DESCRIPTION:
XS GIS Cut Line= 3
      2845445.40      7075137.35      2844385.00      7075108.30
      2843675.04      7075374.99
#Sta/Elev= 30
  3939.2  472.35  4069.7  464.52  4289.7  446.56  4420.7  441.99  4446.9  441.38
  4536.4  440.11  4686.4  438.82  4749.9  437.22  4799.9  439.05  4829.9  435.37
  4849.9  435.94  4870.0  439.48  4900.0  439.41  4910.0  436.52  4930.0  439.87
  4980.0  439.50  4990.0  438.55  4991.6  433.09  4992.2  432.29  5003.4  433.09
  5010.7  433.32  5021.4  438.65  5035.3  440.57  5115.4  437.67  5178.0  441.99
  5183.1  442.71  5346.6  450.09  5496.6  459.62  5697.1  474.78  5758.4  478.19
#Mann=9,-1,0
  3939.2    0.16       0  4446.9    0.05       0  4536.4    0.16       0
  4686.4    0.12       0  4991.6    0.07       0  5003.4    0.12       0
  5183.1    0.05       0  5496.6    0.16       0  5697.1    0.05       0
Bank Sta=4420.7,5178
Exp/Cntr=0.3,0.1

Type RM Length L Ch R = 1,66601,552,552,552
BEGIN DESCRIPTION:
BIRCH CREEK 73.0
END DESCRIPTION:
XS GIS Cut Line= 3
      2845275.00      7074675.00      2844386.50      7074480.19
      2843570.48      7074915.98
#Sta/Elev= 30
  4090.4  469.82  4207.6  463.55  4325.9  449.37  4344.2  445.35  4383.7  443.87
  4494.2  439.34  4582.8  437.10  4745.6  437.47  4763.4  433.38  4763.9  432.58
  4775.3  433.38  4776.3  436.33  4807.0  437.75  4878.7  435.99  4905.9  437.54
  4949.7  436.10  4981.1  437.42  5003.7  434.31  5047.4  437.39  5206.1  439.34
  5246.7  440.82  5343.4  440.33  5477.8  442.76  5726.2  451.36  5787.3  453.28
  5795.3  454.97  5809.3  453.16  5825.6  457.07  5879.7  459.79  5925.1  460.58
#Mann=8,-1,0
  4090.4    0.16       0  4383.7    0.05       0  4582.8    0.12       0
  4763.4    0.07       0  4775.3    0.12       0  5246.7    0.05       0
  5726.2    0.12       0  5879.7    0.16       0
Bank Sta=4494.2,5206.1
Exp/Cntr=0.3,0.1

Type RM Length L Ch R = 1,66049,533,533,533
BEGIN DESCRIPTION:
double BIRCH CREEK 72.0
END DESCRIPTION:
XS GIS Cut Line= 3
      2845602.60      7074359.59      2844415.53      7073955.69
      2842920.30      7074000.20
#Sta/Elev= 30
  3746.1  469.86  3835.7  459.68  3929.8  452.00  4055.7  446.01  4159.5  443.64
  4159.6  443.64  4261.2  440.69  4417.7  438.88  4662.5  435.92  4694.2  434.20
  4740.0  435.80  4757.6  433.42  4766.1  435.21  4771.4  433.38  4990.9  436.25
  5004.6  433.38  5005.1  432.58  5016.5  433.38  5020.5  436.43  5130.6  434.95
  5320.7  436.44  5810.2  435.90  6149.6  436.45  6154.6  437.62  6180.6  436.40
  6260.3  438.88  6279.8  439.39  6361.1  445.06  6431.2  452.73  6495.9  453.16
#Mann=9,-1,0
  3746.1    0.16       0  4055.7    0.12       0  4159.5    0.16       0
  4159.6    0.12       0  5004.6    0.07       0  5016.5    0.12       0
  5810.2    0.05       0  6180.6    0.12       0  6279.8    0.05       0
Bank Sta=4417.7,6260.3
Exp/Cntr=0.3,0.1

Type RM Length L Ch R = 1,65516,646,646,646
BEGIN DESCRIPTION:
double Mapping XS 0d3bfa49
END DESCRIPTION:
XS GIS Cut Line= 3
      2845545.29      7073333.53      2844316.10      7073489.78
      2842828.27      7073448.17
#Sta/Elev= 30
  3752.3  453.85  3800.8  449.58  3893.7  444.99  4069.0  443.46  4169.1  443.64
  4243.5  441.57  4317.2  438.66  4435.5  434.55  4750.4  434.83  4764.8  431.88
  4765.3  431.08  4776.7  431.88  4780.8  434.59  4801.0  434.96  4835.4  433.49
  4962.3  435.15  4982.4  432.03  4994.4  432.07  5042.5  434.41  5182.6  435.64
  5202.6  434.05  5222.6  435.82  5442.7  434.36  5740.4  438.66  5913.2  441.35
  6032.9  447.12  6122.9  446.27  6283.0  448.45  6363.0  452.97  6479.8  464.73
#Mann=7,-1,0
  3752.3    0.16       0  4069.0    0.12       0  4169.1    0.16       0
  4243.5    0.12       0  4764.8    0.07       0  4776.7    0.12       0
  5913.2    0.05       0
Bank Sta=4317.2,5740.4
Exp/Cntr=0.3,0.1

Type RM Length L Ch R = 1,64870,555,555,555
BEGIN DESCRIPTION:
double BIRCH CREEK 71.0
END DESCRIPTION:
XS GIS Cut Line= 3
      2845571.29      7073172.07      2844425.00      7072875.00
      2843724.97      7072775.00
#Sta/Elev= 30
  3837.4  456.73  3874.9  455.00  3916.2  450.33  3964.0  446.36  4015.3  443.95
  4060.8  442.47  4162.2  442.58  4267.4  441.93  4398.1  438.19  4523.3  434.60
  4618.7  433.26  4958.1  433.90  4969.9  432.68  4990.6  433.32  4994.8  431.13
  4997.3  430.33  5010.3  430.33  5012.8  431.13  5019.0  434.14  5051.9  433.81
  5062.0  432.44  5082.2  433.91  5425.6  432.78  5476.1  436.16  5492.3  438.19
  5546.8  443.80  5556.9  446.14  5637.8  457.18  5704.3  467.94  5728.7  470.68
#Mann=7,-1,0
  3837.4    0.16       0  4015.3    0.12       0  4162.2    0.16       0
  4523.3    0.12       0  4994.8    0.07       0  5012.8    0.12       0
  5704.3    0.16       0
Bank Sta=4398.1,5492.3
Exp/Cntr=0.3,0.1

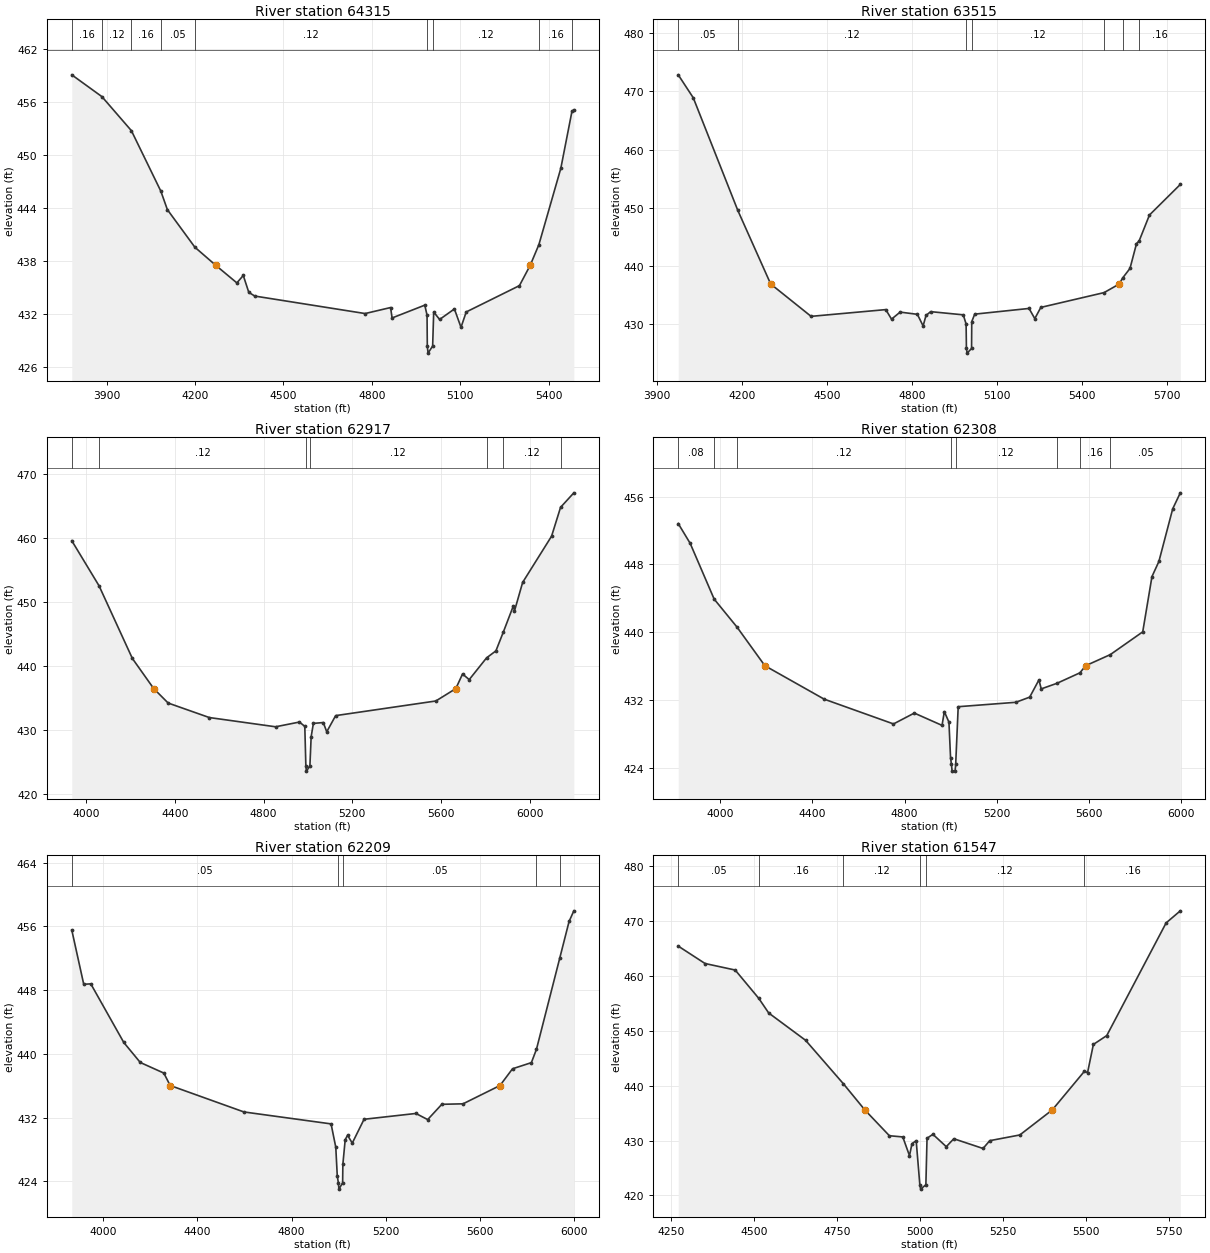
Type RM Length L Ch R = 1,64315,800,800,800
BEGIN DESCRIPTION:
BIRCH CREEK 70.0
END DESCRIPTION:
XS GIS Cut Line= 3
      2845748.36      7072541.86      2844545.20      7072348.44
      2844060.93      7072307.50
#Sta/Elev= 30
  3781.4  459.12  3883.8  456.65  3983.8  452.80  4083.7  445.96  4106.0  443.86
  4199.3  439.61  4269.5  437.58  4341.9  435.57  4363.7  436.41  4382.4  434.50
  4402.6  434.08  4777.4  432.10  4863.8  432.78  4868.9  431.60  4979.9  433.05
  4987.6  431.92  4988.5  428.42  4991.0  427.62  5006.6  428.42  5010.2  432.27
  5030.3  431.43  5080.5  432.62  5102.9  430.54  5120.6  432.28  5301.3  435.26
  5338.1  437.58  5367.2  439.89  5441.8  448.54  5479.6  454.99  5486.0  455.15
#Mann=9,-1,0
  3781.4    0.16       0  3883.8    0.12       0  3983.8    0.16       0
  4083.7    0.05       0  4199.3    0.12       0  4988.5    0.07       0
  5006.6    0.12       0  5367.2    0.16       0  5479.6    0.12       0
Bank Sta=4269.5,5338.1
Exp/Cntr=0.3,0.1

Type RM Length L Ch R = 1,63515,598,598,598
BEGIN DESCRIPTION:
Mapping XS cc15d66c
END DESCRIPTION:
XS GIS Cut Line= 4
      2845847.34      7072099.16      2844925.47      7071953.33
      2844597.35      7071911.66      2844139.49      7072124.98
#Sta/Elev= 30
  3976.4  472.86  4029.4  468.91  4186.4  449.55  4302.2  436.91  4444.5  431.35
  4707.7  432.51  4728.0  430.87  4758.3  432.08  4819.1  431.70  4839.3  429.70
  4849.5  431.50  4865.8  432.16  4980.8  431.61  4990.8  430.03  4991.9  425.83
  4994.4  425.03  5010.0  425.83  5010.7  430.44  5021.1  431.73  5212.6  432.71
  5232.8  430.96  5254.1  432.89  5476.9  435.43  5530.5  436.91  5542.0  437.92
  5568.3  439.59  5591.2  443.84  5600.4  444.30  5636.9  448.77  5745.6  454.02
#Mann=7,-1,0
  3976.4    0.05       0  4186.4    0.12       0  4991.9    0.07       0
  5010.0    0.12       0  5476.9    0.16       0  5542.0    0.12       0
  5600.4    0.16       0
Bank Sta=4302.2,5530.5
Exp/Cntr=0.3,0.1

Type RM Length L Ch R = 1,62917,609,609,609
BEGIN DESCRIPTION:
BIRCH CREEK 69.0
END DESCRIPTION:
XS GIS Cut Line= 3
      2846008.79      7071859.57      2845019.48      7071463.63
      2843824.96      7071575.00
#Sta/Elev= 30
  3934.4  459.53  4057.5  452.50  4207.8  441.18  4304.2  436.48  4369.3  434.23
  4555.0  431.97  4854.0  430.53  4961.7  431.27  4985.8  430.59  4990.6  424.42
  4993.1  423.62  5008.8  424.42  5014.5  429.00  5024.6  431.06  5069.2  431.19
  5084.8  429.75  5125.0  432.27  5577.0  434.55  5667.2  436.48  5697.5  438.76
  5727.6  437.88  5805.9  441.27  5848.1  442.36  5882.2  445.35  5926.9  449.38
  5931.9  448.59  5968.7  453.03  6099.2  460.23  6139.8  464.73  6199.7  466.99
#Mann=7,-1,0
  3934.4    0.05       0  4057.5    0.12       0  4990.6    0.07       0
  5008.8    0.12       0  5805.9    0.16       0  5882.2    0.12       0
  6139.8    0.16       0
Bank Sta=4304.2,5667.2
Exp/Cntr=0.3,0.1

Type RM Length L Ch R = 1,62308,99,99,99
BEGIN DESCRIPTION:
Mapping XS b0601622
END DESCRIPTION:
XS GIS Cut Line= 3
      2846036.62      7071001.07      2844856.03      7070931.62
      2843862.14      7070944.65
#Sta/Elev= 30
  3818.8  452.82  3870.5  450.49  3974.5  443.92  4073.6  440.62  4194.4  436.07
  4451.5  432.13  4752.0  429.21  4842.2  430.49  4962.4  429.04  4972.4  430.66
  4992.4  429.42  4999.4  425.20  5003.4  424.45  5005.9  423.65  5019.1  423.65
  5021.6  424.45  5032.5  431.24  5282.5  431.76  5342.5  432.37  5382.5  434.40
  5392.5  433.34  5460.9  434.00  5560.0  435.23  5585.1  436.07  5692.0  437.38
  5832.5  440.06  5872.5  446.57  5902.5  448.35  5962.5  454.56  5995.4  456.44
#Mann=8,-1,0
  3818.8    0.08       0  3974.5    0.05       0  4073.6    0.12       0
  5003.4    0.07       0  5021.6    0.12       0  5460.9    0.05       0
  5560.0    0.16       0  5692.0    0.05       0
Bank Sta=4194.4,5585.1
Exp/Cntr=0.3,0.1

Type RM Length L Ch R = 1,62209,662,662,662
BEGIN DESCRIPTION:
Mapping XS 843d0cfa
END DESCRIPTION:
XS GIS Cut Line= 3
      2845975.83      7070853.50      2844847.35      7070836.14
      2843844.76      7070801.42
#Sta/Elev= 30
  3866.7  455.55  3917.5  448.74  3947.5  448.79  4087.6  441.43  4157.6  438.92
  4257.6  437.59  4284.5  436.03  4597.6  432.71  4967.7  431.21  4987.7  428.28
  4994.0  424.68  4998.6  423.82  5001.1  423.02  5016.8  423.82  5017.7  426.12
  5027.7  429.23  5037.7  429.78  5057.7  428.80  5107.7  431.79  5327.9  432.52
  5377.9  431.75  5437.9  433.67  5528.0  433.73  5685.0  436.03  5738.1  438.13
  5818.2  438.90  5839.8  440.58  5938.8  452.04  5978.3  456.63  5998.5  457.96
#Mann=5,-1,0
  3866.7    0.05       0  4998.6    0.04       0  5016.8    0.05       0
  5839.8    0.07       0  5938.8    0.16       0
Bank Sta=4284.5,5685
Exp/Cntr=0.3,0.1

Type RM Length L Ch R = 1,61547,822,822,822
BEGIN DESCRIPTION:
BIRCH CREEK 67.0
END DESCRIPTION:
XS GIS Cut Line= 3
      2845275.00      7070225.00      2844575.00      7070325.00
      2843775.04      7070425.00
#Sta/Elev= 30
  4270.4  465.39  4351.2  462.22  4442.1  461.03  4513.2  455.87  4543.1  453.21
  4654.3  448.24  4768.3  440.32  4832.8  435.57  4906.8  430.87  4947.2  430.65
  4967.4  427.24  4975.0  429.43  4987.6  429.96  4998.6  421.95  5001.1  421.15
  5016.8  421.95  5020.3  430.41  5038.0  431.13  5078.3  428.88  5101.0  430.32
  5189.1  428.55  5209.3  429.97  5300.0  431.01  5397.8  435.57  5494.9  442.62
  5504.1  442.35  5521.7  447.49  5562.0  449.10  5740.9  469.61  5783.7  471.81
#Mann=6,-1,0
  4270.4    0.05       0  4513.2    0.16       0  4768.3    0.12       0
  4998.6    0.07       0  5016.8    0.12       0  5494.9    0.16       0
Bank Sta=4832.8,5397.8
Exp/Cntr=0.3,0.1

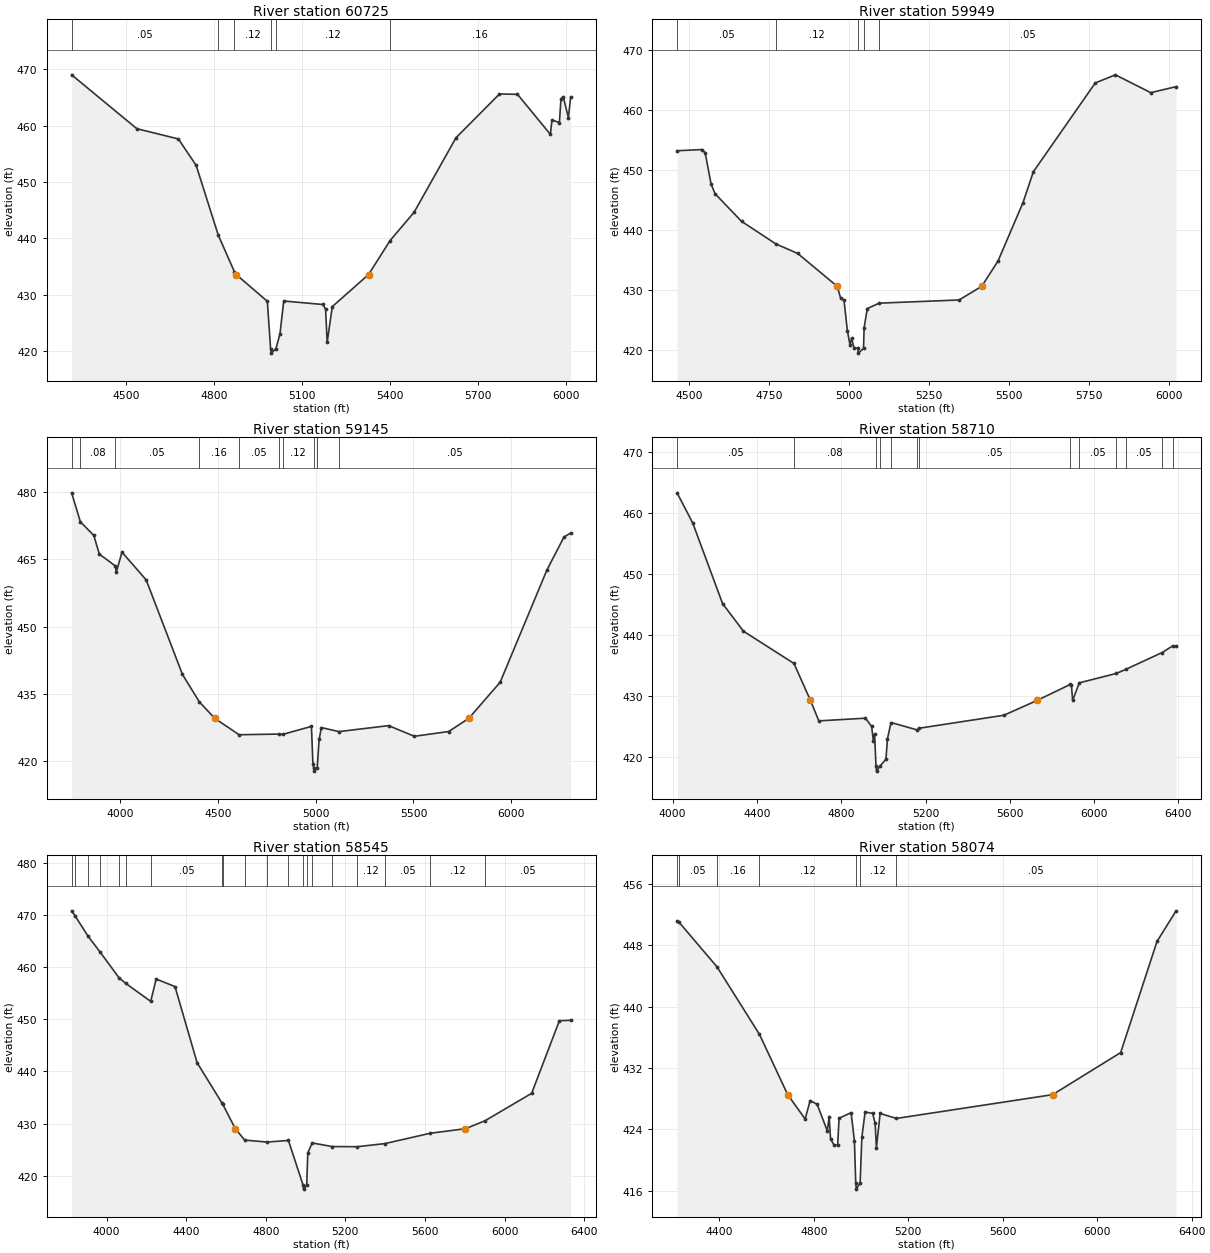
Type RM Length L Ch R = 1,60725,776,776,776
BEGIN DESCRIPTION:
BIRCH CREEK 66.0
END DESCRIPTION:
XS GIS Cut Line= 3
      2845275.01      7069675.00      2844575.00      7069775.00
      2843641.36      7070111.95
#Sta/Elev= 30
  4314.6  469.03  4536.8  459.47  4678.3  457.65  4738.9  452.95  4814.2  440.57
  4868.9  434.10  4875.2  433.59  4981.3  428.84  4992.4  420.44  4994.9  419.64
  5010.6  420.44  5024.4  423.06  5037.1  428.89  5170.6  428.27  5179.8  427.43
  5185.1  421.54  5202.5  427.89  5326.1  433.59  5399.3  439.61  5481.2  444.64
  5624.0  457.87  5772.1  465.63  5833.4  465.57  5945.5  458.46  5950.8  461.02
  5976.2  460.55  5981.5  464.74  5989.2  465.14  6006.8  461.43  6014.3  465.02
#Mann=6,-1,0
  4314.6    0.05       0  4814.2    0.16       0  4868.9    0.12       0
  4992.4    0.07       0  5010.6    0.12       0  5399.3    0.16       0
Bank Sta=4875.2,5326.1
Exp/Cntr=0.3,0.1

Type RM Length L Ch R = 1,59949,804,804,804
BEGIN DESCRIPTION:
BIRCH CREEK 65.0
END DESCRIPTION:
XS GIS Cut Line= 3
      2845119.88      7069167.73      2844575.00      7069025.00
      2843623.99      7068726.56
#Sta/Elev= 30
  4462.1  453.22  4539.5  453.42  4549.8  452.90  4568.4  447.68  4580.9  446.06
  4663.6  441.47  4770.6  437.72  4839.3  436.12  4962.5  430.66  4973.7  428.65
  4984.0  428.32  4994.4  423.29  5002.6  420.90  5007.7  421.99  5015.0  420.44
  5026.6  420.33  5029.1  419.53  5045.0  420.33  5046.8  423.74  5056.8  426.95
  5094.0  427.85  5343.8  428.38  5414.7  430.66  5465.6  434.88  5543.6  444.59
  5576.0  449.73  5769.5  464.51  5832.4  465.86  5943.1  462.89  6022.1  463.89
#Mann=5,-1,0
  4462.1    0.05       0  4770.6    0.12       0  5026.6    0.07       0
  5045.0    0.12       0  5094.0    0.05       0
Bank Sta=4962.5,5414.7
Exp/Cntr=0.3,0.1

Type RM Length L Ch R = 1,59145,435,435,435
BEGIN DESCRIPTION:
BIRCH CREEK 64.0
END DESCRIPTION:
XS GIS Cut Line= 3
      2846275.02      7068725.01      2845075.00      7068425.00
      2843775.05      7068225.01
#Sta/Elev= 30
  3751.4  479.81  3796.1  473.36  3864.8  470.32  3893.2  466.17  3972.9  463.60
  3980.8  462.27  4009.1  466.60  4132.8  460.42  4318.4  439.37  4405.2  433.24
  4484.2  429.58  4608.2  425.95  4811.2  426.10  4831.6  426.04  4978.0  427.81
  4985.8  419.34  4989.3  418.65  4991.8  417.85  5007.7  418.65  5017.4  424.91
  5028.8  427.55  5118.2  426.65  5372.8  427.98  5504.4  425.61  5680.1  426.67
  5782.5  429.58  5943.2  437.63  6182.2  462.61  6269.5  469.95  6303.6  470.86
#Mann=10,-1,0
  3751.4    0.16       0  3796.1    0.08       0  3972.9    0.05       0
  4405.2    0.16       0  4608.2    0.05       0  4811.2    0.07       0
  4831.6    0.12       0  4989.3    0.07       0  5007.7    0.12       0
  5118.2    0.05       0
Bank Sta=4484.2,5782.5
Exp/Cntr=0.3,0.1

Type RM Length L Ch R = 1,58710,165,165,165
BEGIN DESCRIPTION:
Mapping XS 6d04a7b1
END DESCRIPTION:
XS GIS Cut Line= 5
      2845979.32      7068626.10      2845604.29      7068245.86
      2845224.08      7068032.32      2844536.58      7067719.82
      2843969.41      7067418.02
#Sta/Elev= 30
  4020.9  463.26  4095.4  458.30  4236.8  445.12  4335.9  440.60  4575.6  435.32
  4653.9  429.26  4693.5  425.92  4914.8  426.36  4944.1  425.01  4952.4  422.65
  4958.1  423.77  4964.8  418.49  4967.3  417.69  4983.3  418.49  5012.0  419.65
  5019.2  422.96  5035.9  425.65  5159.5  424.45  5170.6  424.72  5571.7  426.84
  5728.8  429.26  5887.0  431.89  5892.2  431.77  5897.9  429.26  5929.5  432.15
  6104.9  433.68  6151.2  434.37  6322.8  437.11  6372.8  438.20  6388.7  438.12
#Mann=13,-1,0
  4020.9    0.05       0  4575.6    0.08       0  4964.8    0.07       0
  4983.3    0.08       0  5035.9    0.12       0  5159.5    0.08       0
  5170.6    0.05       0  5887.0    0.08       0  5929.5    0.05       0
  6104.9    0.08       0  6151.2    0.05       0  6322.8    0.08       0
  6372.8    0.05       0
Bank Sta=4653.9,5728.8
Exp/Cntr=0.3,0.1

Type RM Length L Ch R = 1,58545,471,471,471
BEGIN DESCRIPTION:
Mapping XS 239583dc
END DESCRIPTION:
XS GIS Cut Line= 4
      2846187.64      7068589.63      2845869.92      7068183.36
      2845276.17      7067881.28      2844093.86      7067282.31
#Sta/Elev= 30
  3824.6  470.76  3842.5  469.77  3906.7  465.93  3969.0  462.80  4062.8  457.93
  4095.5  456.89  4222.1  453.41  4249.4  457.69  4344.1  456.24  4455.2  441.65
  4581.2  433.87  4584.5  433.65  4647.1  429.01  4694.3  426.83  4807.4  426.45
  4914.0  426.76  4987.4  418.23  4989.9  417.43  5005.9  418.23  5011.4  424.38
  5033.6  426.28  5133.6  425.59  5260.6  425.56  5399.4  426.16  5626.9  428.14
  5803.7  429.01  5901.8  430.53  6136.2  435.79  6275.4  449.69  6331.9  449.79
#Mann=20,-1,0
  3824.6    0.05       0  3842.5    0.16       0  3906.7    0.05       0
  3969.0    0.16       0  4062.8    0.08       0  4095.5    0.05       0
  4222.1    0.05       0  4581.2    0.12       0  4584.5    0.16       0
  4694.3    0.05       0  4807.4    0.12       0  4914.0    0.05       0
  4987.4    0.04       0  5005.9    0.05       0  5033.6    0.12       0
  5133.6    0.05       0  5260.6    0.12       0  5399.4    0.05       0
  5626.9    0.12       0  5901.8    0.05       0
Bank Sta=4647.1,5803.7
Exp/Cntr=0.3,0.1

Type RM Length L Ch R = 1,58074,563,563,563
BEGIN DESCRIPTION:
Mapping XS adcd0f0a
END DESCRIPTION:
XS GIS Cut Line= 3
      2845953.26      7068120.88      2845520.96      7067485.44
      2844255.37      7067032.33
#Sta/Elev= 30
  4221.3  451.13  4229.7  450.99  4390.4  445.18  4570.2  436.38  4689.7  428.53
  4763.5  425.36  4784.8  427.76  4814.4  427.27  4857.3  423.81  4865.2  425.66
  4871.3  422.75  4886.2  421.96  4901.2  421.95  4907.2  425.46  4958.1  426.18
  4972.2  422.52  4977.8  417.02  4980.3  416.22  4996.4  417.02  5003.7  422.97
  5017.4  426.26  5049.3  426.10  5059.9  424.81  5065.3  421.61  5081.1  426.08
  5150.0  425.43  5811.5  428.53  6099.6  434.01  6253.4  448.49  6334.1  452.48
#Mann=7,-1,0
  4221.3    0.16       0  4229.7    0.05       0  4390.4    0.16       0
  4570.2    0.12       0  4977.8    0.07       0  4996.4    0.12       0
  5150.0    0.05       0
Bank Sta=4689.7,5811.5
Exp/Cntr=0.3,0.1

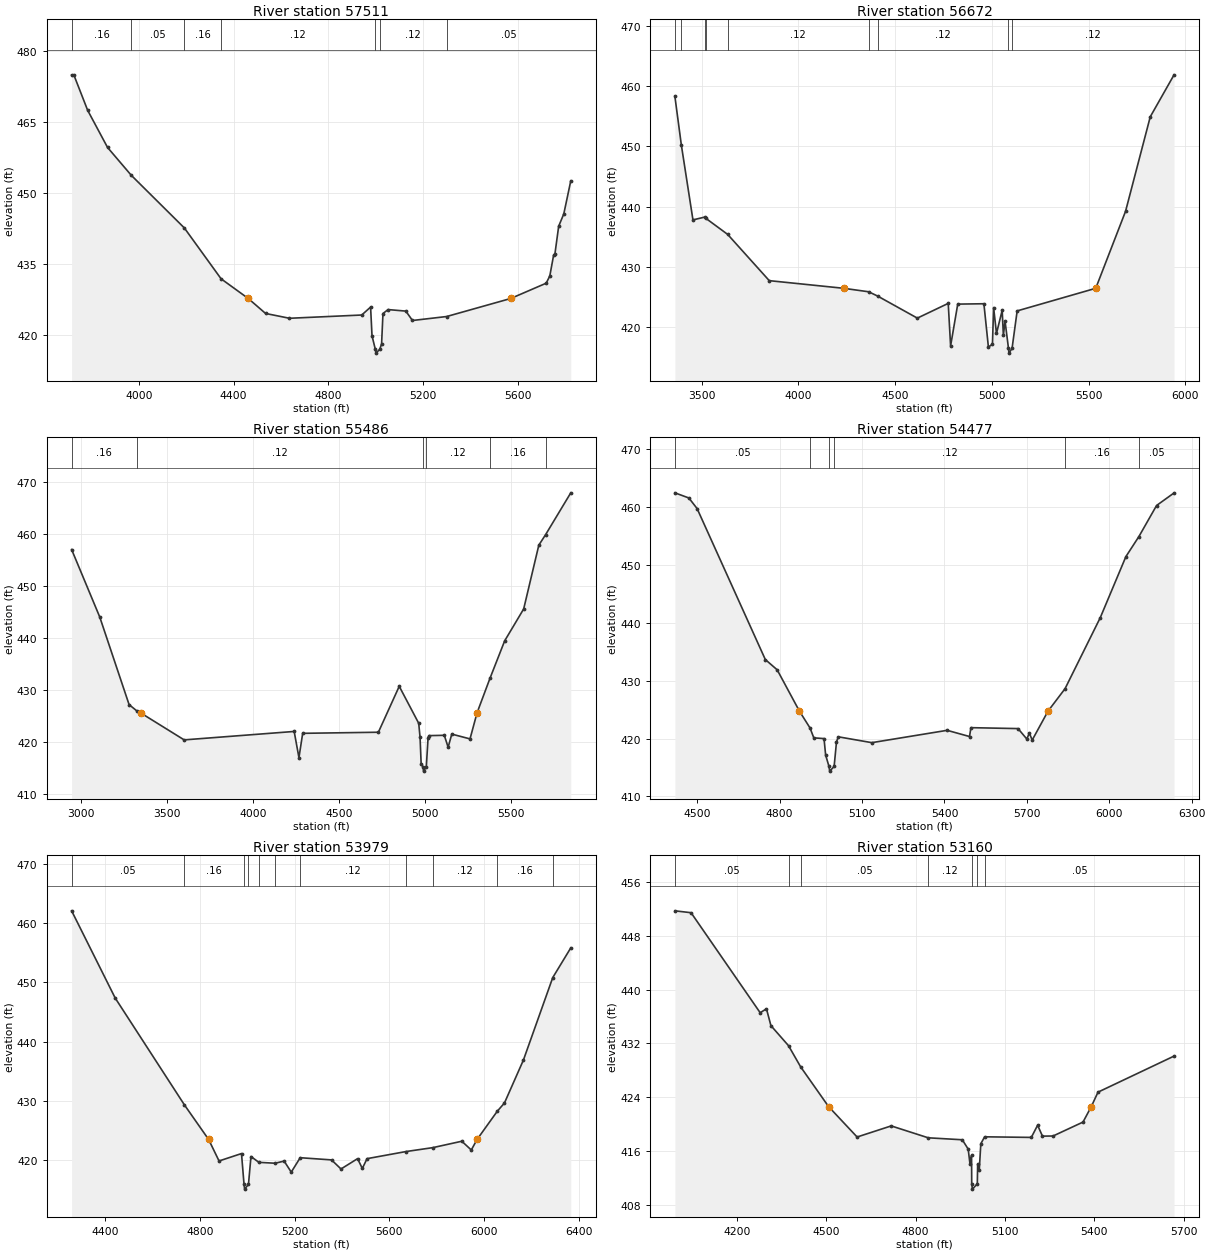
Type RM Length L Ch R = 1,57511,839,839,839
BEGIN DESCRIPTION:
BIRCH CREEK 62.0
END DESCRIPTION:
XS GIS Cut Line= 3
      2846324.99      7068274.98      2845825.00      7067075.00
      2845125.01      7066675.00
#Sta/Elev= 30
  3716.9  475.01  3726.1  475.06  3784.6  467.54  3868.5  459.68  3968.7  453.78
  4192.6  442.63  4347.5  431.87  4462.2  427.70  4535.3  424.53  4636.1  423.51
  4941.0  424.20  4978.4  425.88  4984.4  419.80  4998.4  416.93  5000.9  416.13
  5017.0  416.93  5024.8  418.09  5030.6  424.52  5052.2  425.35  5127.0  425.03
  5155.1  423.04  5299.2  423.88  5569.8  427.70  5719.4  430.94  5734.6  432.48
  5750.4  436.81  5756.2  437.14  5772.0  443.00  5793.6  445.61  5823.1  452.62
#Mann=7,-1,0
  3716.9    0.16       0  3968.7    0.05       0  4192.6    0.16       0
  4347.5    0.12       0  4998.4    0.07       0  5017.0    0.12       0
  5299.2    0.05       0
Bank Sta=4462.2,5569.8
Exp/Cntr=0.3,0.1

Type RM Length L Ch R = 1,56672,1186,1186,1186
BEGIN DESCRIPTION:
BIRCH CREEK 61.0
END DESCRIPTION:
XS GIS Cut Line= 3
      2847574.98      7067524.99      2846175.00      7066525.00
      2845474.98      7066024.99
#Sta/Elev= 30
  3361.2  458.33  3394.7  450.22  3454.6  437.79  3514.4  438.25  3522.2  438.03
  3634.1  435.38  3849.1  427.69  4233.5  426.42  4363.2  425.84  4409.8  425.12
  4614.7  421.46  4774.4  423.91  4786.7  416.84  4823.6  423.79  4958.8  423.85
  4982.1  416.65  5003.0  417.12  5009.1  423.21  5023.9  418.91  5053.4  422.76
  5059.5  418.58  5068.1  420.99  5085.9  416.44  5088.4  415.64  5104.5  416.44
  5130.8  422.66  5537.1  426.42  5691.2  439.22  5819.0  454.94  5941.9  461.91
#Mann=9,-1,0
  3361.2    0.05       0  3394.7    0.07       0  3514.4    0.12       0
  3522.2    0.16       0  3634.1    0.12       0  4363.2    0.16       0
  4409.8    0.12       0  5085.9    0.07       0  5104.5    0.12       0
Bank Sta=4233.5,5537.1
Exp/Cntr=0.3,0.1

Type RM Length L Ch R = 1,55486,1009,1009,1009
BEGIN DESCRIPTION:
BIRCH CREEK 60.0
END DESCRIPTION:
XS GIS Cut Line= 3
      2847825.02      7067275.02      2846509.10      7065710.76
      2845702.49      7065429.75
#Sta/Elev= 30
  2946.4  456.97  3109.7  444.01  3280.0  427.19  3325.9  425.95  3347.0  425.60
  3599.8  420.41  4238.6  422.03  4266.3  417.00  4288.0  421.67  4727.6  421.88
  4848.6  430.70  4961.7  423.60  4969.5  420.92  4976.0  415.72  4987.2  415.21
  4989.7  414.41  5005.8  415.21  5016.1  420.84  5022.3  421.23  5110.3  421.29
  5132.6  418.99  5153.7  421.52  5259.6  420.60  5300.4  425.60  5375.2  432.21
  5460.8  439.43  5571.2  445.56  5659.1  457.81  5698.7  459.84  5844.7  467.86
#Mann=6,-1,0
  2946.4    0.16       0  3325.9    0.12       0  4987.2    0.07       0
  5005.8    0.12       0  5375.2    0.16       0  5698.7    0.05       0
Bank Sta=3347,5300.4
Exp/Cntr=0.3,0.1

Type RM Length L Ch R = 1,54477,498,498,498
BEGIN DESCRIPTION:
BIRCH CREEK 59.0
END DESCRIPTION:
XS GIS Cut Line= 3
      2847724.99      7065674.99      2847221.68      7065383.75
      2846024.97      7065074.99
#Sta/Elev= 30
  4418.5  462.47  4469.4  461.58  4499.4  459.75  4747.8  433.66  4790.9  431.89
  4871.9  424.75  4910.5  421.84  4924.3  420.13  4961.5  420.00  4967.4  417.16
  4979.6  415.18  4982.1  414.38  4998.3  415.18  5006.9  419.43  5013.5  420.31
  5135.5  419.30  5409.7  421.43  5491.2  420.36  5496.4  421.89  5667.9  421.73
  5699.7  419.94  5709.2  420.94  5719.5  419.75  5777.1  424.75  5839.1  428.63
  5967.4  440.91  6060.6  451.45  6108.0  454.92  6172.3  460.28  6235.9  462.45
#Mann=6,-1,0
  4418.5    0.05       0  4910.5    0.12       0  4979.6    0.07       0
  4998.3    0.12       0  5839.1    0.16       0  6108.0    0.05       0
Bank Sta=4871.9,5777.1
Exp/Cntr=0.3,0.1

Type RM Length L Ch R = 1,53979,819,819,819
BEGIN DESCRIPTION:
BIRCH CREEK 58.0
END DESCRIPTION:
XS GIS Cut Line= 3
      2848075.01      7065525.01      2847575.00      7065025.00
      2846175.02      7065025.00
#Sta/Elev= 30
  4258.7  462.08  4442.6  447.37  4734.7  429.35  4837.0  423.51  4881.0  419.88
  4975.8  421.13  4986.5  415.93  4989.0  415.13  5005.2  415.93  5015.8  420.63
  5049.1  419.65  5117.5  419.50  5155.8  419.86  5185.8  418.00  5223.6  420.43
  5355.8  420.06  5395.8  418.53  5465.8  420.27  5485.8  418.62  5505.8  420.27
  5670.2  421.47  5783.4  422.13  5905.8  423.21  5945.8  421.73  5970.2  423.51
  6055.9  428.29  6085.8  429.66  6165.8  436.90  6289.7  450.82  6365.8  455.83
#Mann=11,-1,0
  4258.7    0.05       0  4734.7    0.16       0  4986.5    0.07       0
  5005.2    0.16       0  5049.1    0.12       0  5117.5    0.16       0
  5223.6    0.12       0  5670.2    0.05       0  5783.4    0.12       0
  6055.9    0.16       0  6289.7    0.05       0
Bank Sta=4837,5970.2
Exp/Cntr=0.3,0.1

Type RM Length L Ch R = 1,53160,345,345,345
BEGIN DESCRIPTION:
Mapping XS 003ef52c
END DESCRIPTION:
XS GIS Cut Line= 4
      2848218.42      7065057.46      2847749.69      7064345.69
      2847376.43      7064215.48      2846951.11      7064172.08
#Sta/Elev= 30
  3992.2  451.70  4046.5  451.42  4278.4  436.55  4299.5  437.13  4314.5  434.63
  4373.5  431.65  4414.1  428.51  4508.0  422.59  4603.7  418.07  4718.1  419.72
  4842.5  417.95  4956.7  417.66  4976.5  416.27  4982.5  414.07  4987.8  415.33
  4988.3  411.12  4990.8  410.32  5007.1  411.12  5008.3  414.03  5013.6  413.13
  5018.9  417.07  5031.7  418.10  5188.3  418.01  5209.5  419.82  5225.7  418.20
  5261.3  418.22  5361.8  420.29  5389.7  422.60  5412.1  424.74  5667.3  430.10
#Mann=7,-1,0
  3992.2    0.05       0  4373.5    0.16       0  4414.1    0.05       0
  4842.5    0.12       0  4988.3    0.07       0  5007.1    0.12       0
  5031.7    0.05       0
Bank Sta=4508,5389.7
Exp/Cntr=0.3,0.1