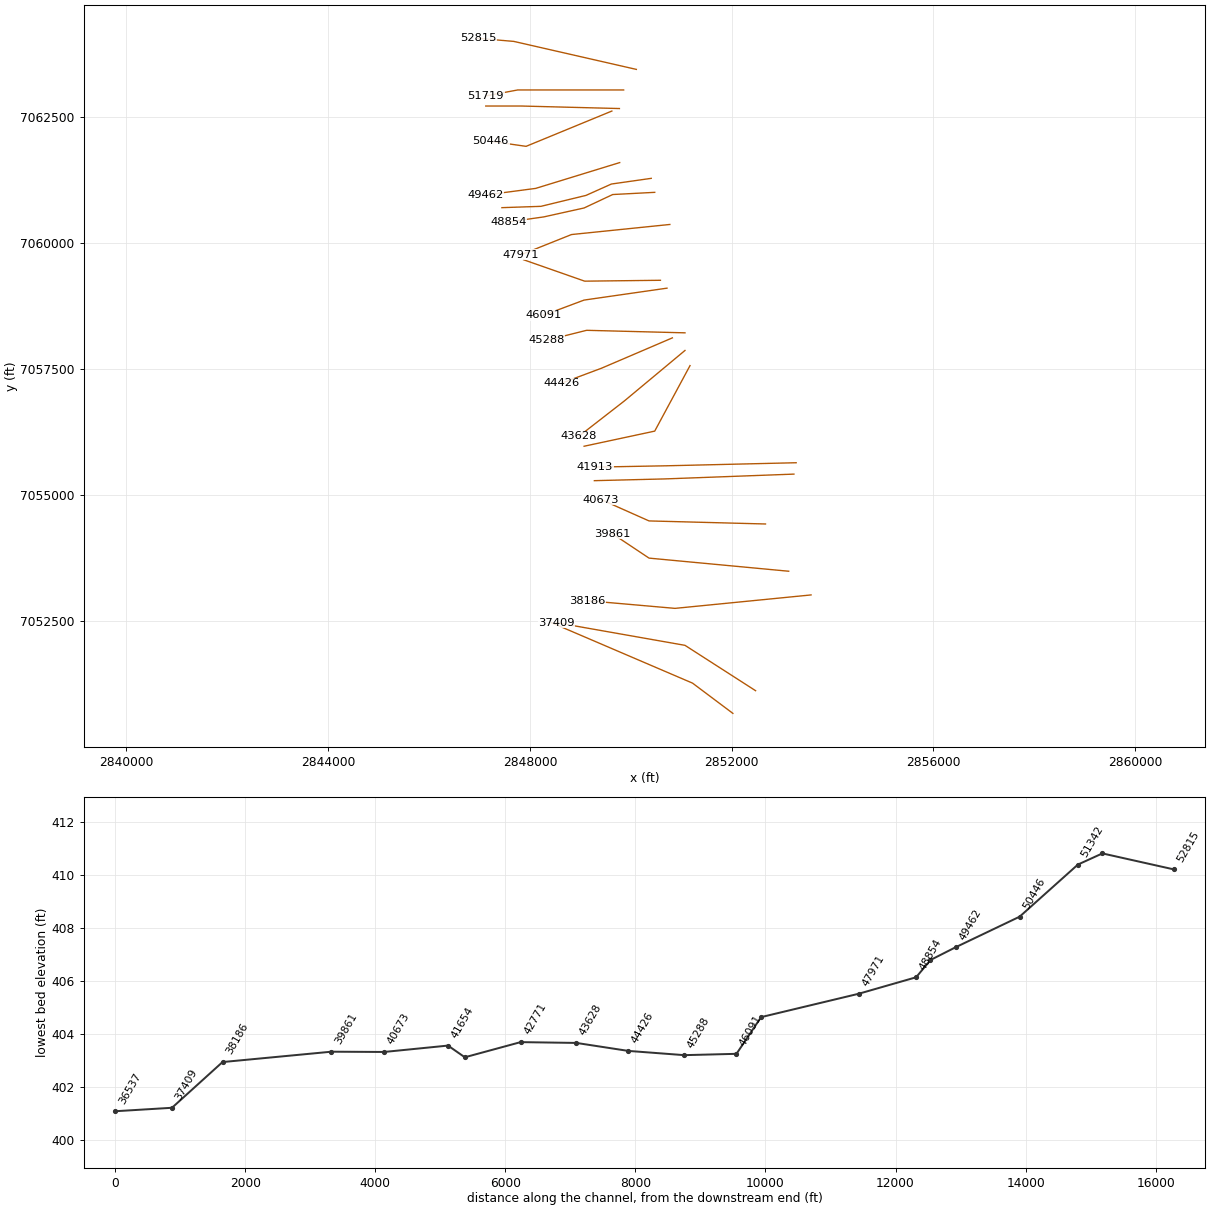
HEC-RAS study BIRCH CREEK.prj: BIRCH CREEK Base Level Engineering

--- BIRCH CREEK.g01 (geometry) --- (continued)

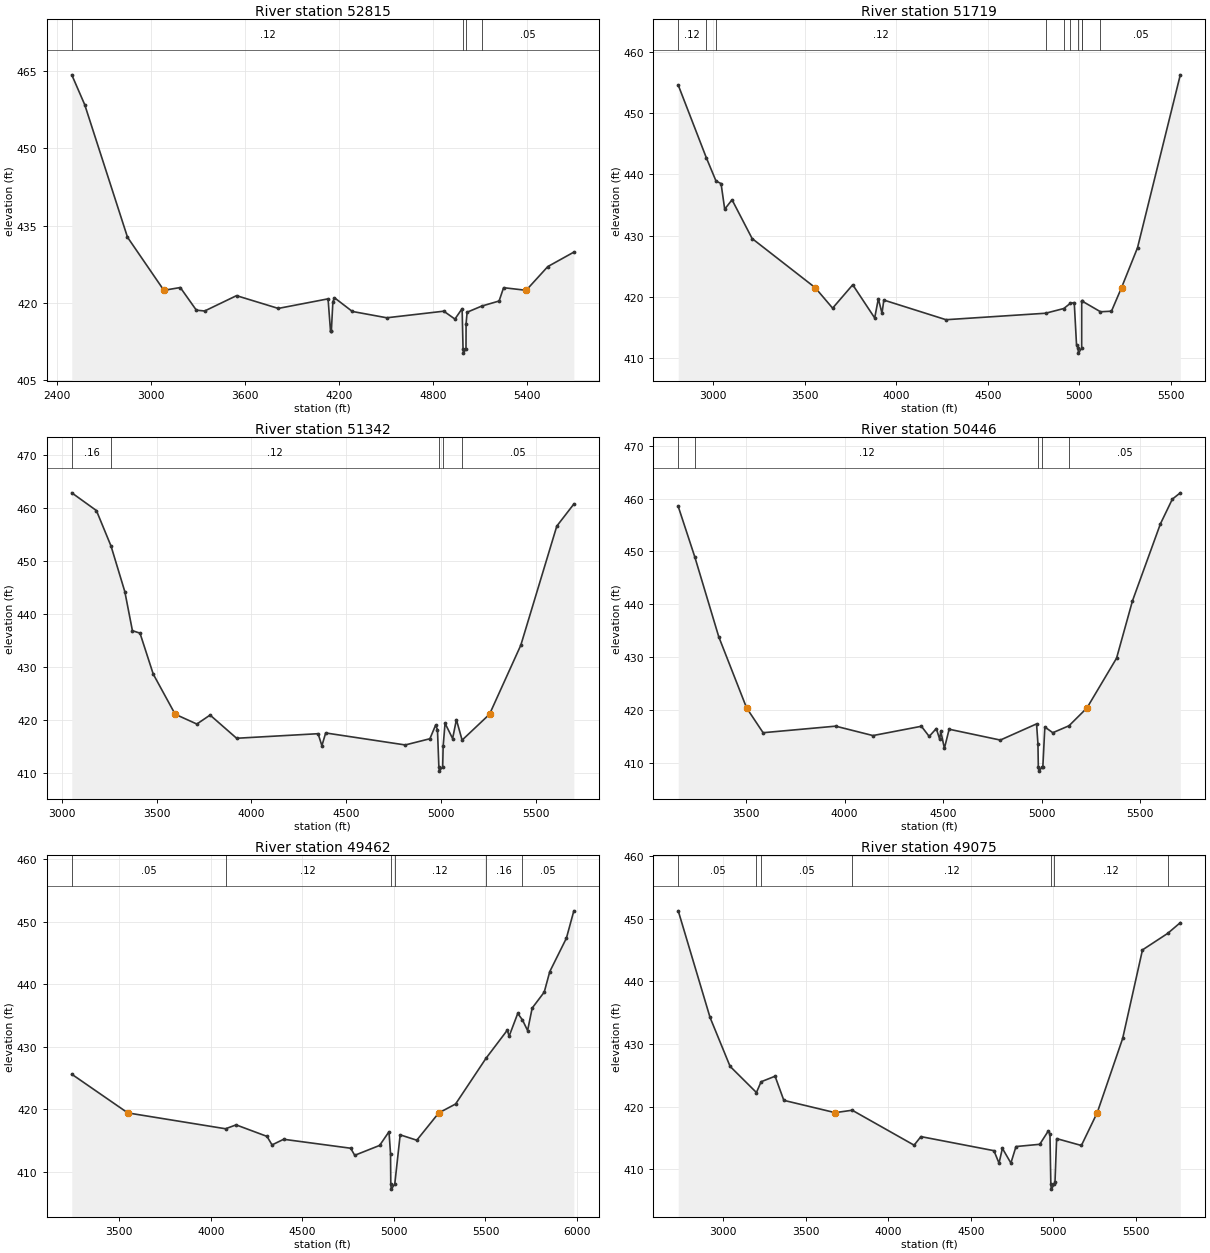
Type RM Length L Ch R = 1,52815,1096,1096,1096
BEGIN DESCRIPTION:
BIRCH CREEK 57.0
END DESCRIPTION:
XS GIS Cut Line= 3
      2850110.83      7063451.58      2847680.25      7064007.15
      2846969.20      7064067.84
#Sta/Elev= 30
  2492.7  464.29  2575.5  458.48  2848.6  432.73  3081.0  422.41  3186.0  422.95
  3288.4  418.55  3341.6  418.39  3545.0  421.37  3811.7  418.89  4129.7  420.75
  4145.6  414.43  4150.7  414.47  4160.5  420.19  4170.7  420.96  4284.7  418.30
  4504.6  417.07  4868.8  418.35  4940.1  416.82  4986.0  418.85  4991.9  411.00
  4994.4  410.20  5010.7  411.00  5011.3  415.93  5017.9  418.15  5110.8  419.34
  5222.1  420.33  5250.9  422.92  5395.0  422.41  5533.2  427.02  5699.6  429.83
#Mann=4,-1,0
  2492.7    0.12       0  4991.9    0.07       0  5010.7    0.12       0
  5110.8    0.05       0
Bank Sta=3081,5395
Exp/Cntr=0.3,0.1

Type RM Length L Ch R = 1,51719,377,377,377
BEGIN DESCRIPTION:
BIRCH CREEK 56.0
END DESCRIPTION:
XS GIS Cut Line= 3
      2849859.10      7063043.60      2847758.37      7063043.60
      2847125.01      7062925.00
#Sta/Elev= 30
  2808.0  454.60  2961.7  442.72  3014.6  438.92  3042.1  438.51  3062.1  434.32
  3102.1  435.86  3212.1  429.52  3556.7  421.50  3652.1  418.15  3762.1  421.97
  3882.1  416.55  3902.1  419.69  3922.1  417.31  3932.1  419.47  4272.1  416.26
  4816.9  417.32  4916.0  418.09  4951.0  418.92  4973.2  419.06  4985.6  412.20
  4993.7  411.60  4996.2  410.80  5013.8  411.60  5013.9  419.24  5016.4  419.30
  5116.7  417.56  5176.7  417.65  5231.7  421.50  5319.1  428.02  5553.1  456.28
#Mann=10,-1,0
  2808.0    0.12       0  2961.7    0.16       0  3014.6    0.12       0
  4816.9    0.07       0  4916.0    0.12       0  4951.0    0.07       0
  4993.7    0.07       0  5013.8    0.07       0  5016.4    0.12       0
  5116.7    0.05       0
Bank Sta=3556.7,5231.7
Exp/Cntr=0.3,0.1

Type RM Length L Ch R = 1,51342,896,896,896
BEGIN DESCRIPTION:
BIRCH CREEK 55.0
END DESCRIPTION:
XS GIS Cut Line= 3
      2849775.05      7062675.00      2847825.00      7062725.00
      2847124.99      7062725.00
#Sta/Elev= 30
  3051.3  462.80  3181.4  459.46  3258.6  452.77  3331.4  444.19  3371.5  436.83
  3411.5  436.37  3481.5  428.65  3597.1  421.10  3711.6  419.25  3781.6  420.94
  3921.6  416.57  4351.8  417.43  4371.8  415.16  4391.8  417.57  4811.9  415.31
  4942.0  416.48  4972.0  419.02  4982.0  418.21  4989.4  411.18  4991.9  410.38
  5009.5  411.18  5012.0  415.07  5022.0  419.39  5062.0  416.52  5082.0  420.07
  5112.1  416.22  5256.9  421.10  5422.0  434.10  5612.0  456.53  5702.0  460.69
#Mann=5,-1,0
  3051.3    0.16       0  3258.6    0.12       0  4989.4    0.07       0
  5009.5    0.12       0  5112.1    0.05       0
Bank Sta=3597.1,5256.9
Exp/Cntr=0.3,0.1

Type RM Length L Ch R = 1,50446,984,984,984
BEGIN DESCRIPTION:
BIRCH CREEK 54.0
END DESCRIPTION:
XS GIS Cut Line= 3
      2849625.00      7062625.00      2847925.00      7061925.00
      2847224.98      7062025.00
#Sta/Elev= 30
  3156.8  458.51  3240.6  448.98  3362.3  433.84  3503.5  420.38  3587.1  415.69
  3954.8  416.93  4144.0  415.15  4389.7  416.91  4429.1  414.99  4465.4  416.48
  4482.4  414.45  4487.8  415.99  4506.3  412.74  4530.3  416.35  4789.8  414.30
  4973.6  417.36  4980.6  413.58  4982.5  409.22  4985.0  408.42  5002.6  409.22
  5005.4  409.22  5015.5  416.77  5055.9  415.69  5138.2  417.01  5229.1  420.38
  5379.1  429.79  5459.9  440.65  5601.4  455.21  5662.0  459.90  5702.4  461.09
#Mann=5,-1,0
  3156.8    0.16       0  3240.6    0.12       0  4982.5    0.07       0
  5002.6    0.12       0  5138.2    0.05       0
Bank Sta=3503.5,5229.1
Exp/Cntr=0.3,0.1

Type RM Length L Ch R = 1,49462,387,387,387
BEGIN DESCRIPTION:
BIRCH CREEK 53.0
END DESCRIPTION:
XS GIS Cut Line= 3
      2849780.92      7061602.62      2848114.28      7061090.48
      2847124.66      7060960.27
#Sta/Elev= 30
  3240.9  425.62  3547.0  419.44  4080.6  416.91  4138.3  417.53  4307.1  415.69
  4334.5  414.33  4397.9  415.23  4764.0  413.80  4786.0  412.67  4922.1  414.25
  4973.2  416.44  4981.5  412.95  4983.0  408.07  4985.7  407.27  5004.7  408.07
  5034.2  415.94  5124.9  415.08  5245.0  419.44  5336.7  420.86  5502.6  428.15
  5619.2  432.65  5629.2  431.69  5676.3  435.33  5702.1  434.28  5730.1  432.59
  5755.0  436.18  5820.9  438.73  5851.1  442.00  5941.9  447.34  5982.6  451.71
#Mann=6,-1,0
  3240.9    0.05       0  4080.6    0.12       0  4983.0    0.07       0
  5004.7    0.12       0  5502.6    0.16       0  5702.1    0.05       0
Bank Sta=3547,5245
Exp/Cntr=0.3,0.1

Type RM Length L Ch R = 1,49075,221,221,221
BEGIN DESCRIPTION:
Mapping XS f80fd247
END DESCRIPTION:
XS GIS Cut Line= 5
      2850405.98      7061290.14      2849616.01      7061177.28
      2849112.54      7060951.59      2848218.44      7060734.58
      2847445.87      7060708.53
#Sta/Elev= 30
  2727.2  451.30  2920.1  434.24  3041.3  426.43  3201.1  422.24  3229.3  423.96
  3314.1  424.85  3367.1  420.99  3678.2  419.02  3781.4  419.41  4156.7  413.82
  4197.9  415.19  4640.4  412.94  4671.2  410.95  4691.8  413.31  4743.3  410.96
  4774.1  413.60  4918.2  413.96  4969.3  416.07  4980.0  415.63  4985.3  407.59
  4988.1  406.79  5007.1  407.59  5010.4  407.86  5020.4  414.87  5170.5  413.77
  5266.5  419.02  5420.7  430.90  5540.7  445.05  5693.4  447.69  5770.0  449.41
#Mann=7,-1,0
  2727.2    0.05       0  3201.1    0.16       0  3229.3    0.05       0
  3781.4    0.12       0  4985.3    0.07       0  5007.1    0.12       0
  5693.4    0.16       0
Bank Sta=3678.2,5266.5
Exp/Cntr=0.3,0.1

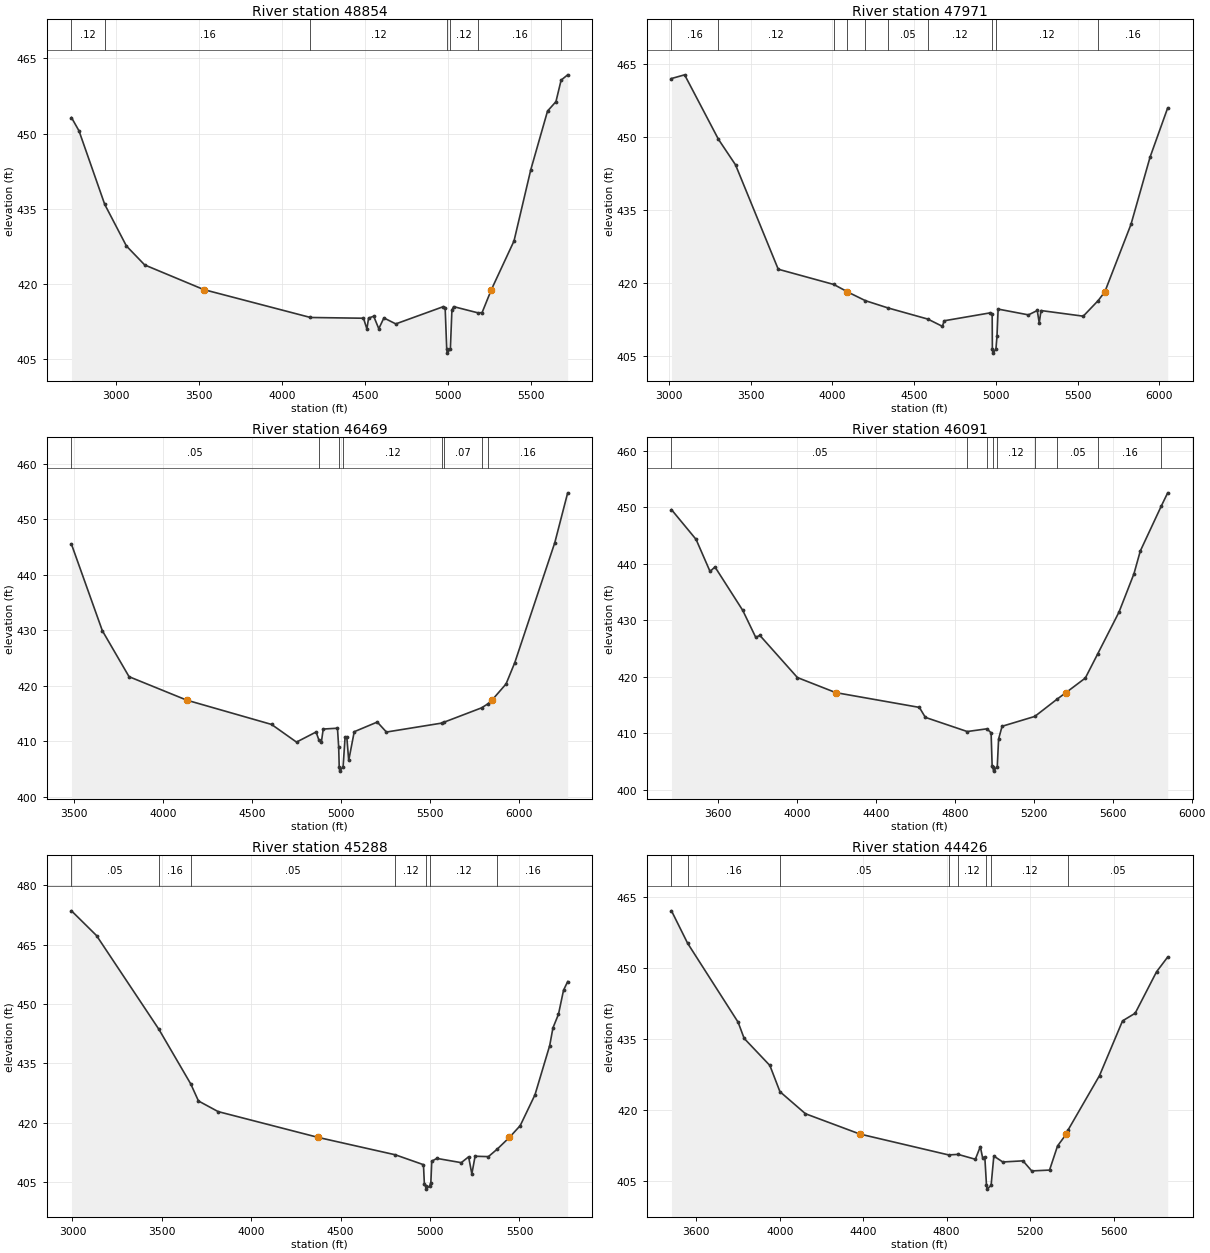
Type RM Length L Ch R = 1,48854,883,883,883
BEGIN DESCRIPTION:
BIRCH CREEK 52.0
END DESCRIPTION:
XS GIS Cut Line= 5
      2850475.36      7061012.35      2849642.05      7060968.95
      2849075.36      7060702.27      2848275.00      7060525.00
      2847575.00      7060425.00
#Sta/Elev= 30
  2732.1  453.20  2777.4  450.54  2932.3  435.85  3062.9  427.54  3173.1  423.75
  3528.9  418.83  4170.9  413.26  4490.2  413.11  4510.7  410.98  4521.0  413.14
  4551.7  413.51  4582.4  411.02  4613.1  413.17  4684.8  411.98  4971.6  415.43
  4981.9  415.24  4991.5  406.94  4994.3  406.14  5013.3  406.94  5022.7  414.75
  5032.8  415.43  5181.5  414.17  5204.5  414.25  5260.3  418.83  5396.5  428.54
  5497.5  442.77  5598.5  454.50  5649.0  456.37  5680.2  460.67  5719.7  461.73
#Mann=7,-1,0
  2732.1    0.12       0  2932.3    0.16       0  4170.9    0.12       0
  4991.5    0.07       0  5013.3    0.12       0  5181.5    0.16       0
  5680.2    0.05       0
Bank Sta=3528.9,5260.3
Exp/Cntr=0.3,0.1

Type RM Length L Ch R = 1,47971,1502,1502,1502
BEGIN DESCRIPTION:
BIRCH CREEK 51.0
END DESCRIPTION:
XS GIS Cut Line= 3
      2850774.98      7060375.00      2848825.00      7060175.00
      2847825.04      7059775.02
#Sta/Elev= 30
  3014.7  462.08  3095.1  462.84  3302.3  449.55  3406.7  444.30  3668.1  422.80
  4008.1  419.66  4089.3  418.20  4091.6  418.14  4201.9  416.32  4339.7  414.83
  4584.0  412.53  4673.3  411.03  4683.4  412.18  4964.9  413.81  4977.6  413.53
  4978.8  406.32  4981.6  405.52  5000.6  406.32  5007.2  409.10  5014.0  414.59
  5199.7  413.40  5253.6  414.30  5265.7  411.72  5276.5  414.29  5535.0  413.13
  5626.4  416.34  5667.0  418.14  5827.1  432.03  5944.2  445.91  6051.9  456.03
#Mann=10,-1,0
  3014.7    0.16       0  3302.3    0.12       0  4008.1    0.16       0
  4089.3    0.12       0  4201.9    0.16       0  4339.7    0.05       0
  4584.0    0.12       0  4978.8    0.07       0  5000.6    0.12       0
  5626.4    0.16       0
Bank Sta=4091.6,5667
Exp/Cntr=0.3,0.1

Type RM Length L Ch R = 1,46469,378,378,378
BEGIN DESCRIPTION:
BIRCH CREEK 50.0
END DESCRIPTION:
XS GIS Cut Line= 3
      2850588.23      7059267.56      2849086.50      7059250.20
      2847874.95      7059675.02
#Sta/Elev= 30
  3486.2  445.51  3659.4  429.94  3809.5  421.65  4134.0  417.42  4609.5  413.05
  4749.5  409.87  4859.5  411.69  4874.6  410.30  4889.5  409.95  4899.5  412.22
  4979.5  412.37  4986.3  408.98  4989.3  405.44  4992.1  404.64  5011.2  405.44
  5022.2  410.75  5032.0  410.74  5042.6  406.57  5073.6  411.74  5202.9  413.48
  5254.3  411.68  5564.6  413.29  5579.1  413.47  5788.5  416.04  5826.9  416.82
  5846.7  417.42  5925.9  420.34  5975.1  424.20  6199.6  445.80  6271.9  454.77
#Mann=8,-1,0
  3486.2    0.05       0  4874.6    0.12       0  4989.3    0.07       0
  5011.2    0.12       0  5564.6    0.16       0  5579.1    0.07       0
  5788.5    0.05       0  5826.9    0.16       0
Bank Sta=4134,5846.7
Exp/Cntr=0.3,0.1

Type RM Length L Ch R = 1,46091,803,803,803
BEGIN DESCRIPTION:
BIRCH CREEK 49.0
END DESCRIPTION:
XS GIS Cut Line= 3
      2850718.45      7059111.31      2849075.00      7058875.00
      2848274.96      7058574.98
#Sta/Elev= 30
  3363.7  449.62  3488.4  444.34  3559.1  438.66  3584.1  439.46  3725.0  431.75
  3790.5  426.99  3811.7  427.32  4001.9  419.85  4196.3  417.18  4619.9  414.56
  4650.3  412.79  4862.5  410.28  4962.2  410.76  4983.6  410.05  4988.8  404.15
  4992.9  404.06  4995.8  403.26  5014.8  404.06  5021.5  408.95  5039.2  411.21
  5205.1  412.96  5318.3  416.03  5363.1  417.18  5461.0  419.76  5524.6  424.10
  5631.9  431.47  5707.6  438.26  5739.6  442.28  5846.1  450.26  5878.5  452.60
#Mann=9,-1,0
  3363.7    0.05       0  4862.5    0.07       0  4962.2    0.12       0
  4992.9    0.07       0  5014.8    0.12       0  5205.1     0.1       0
  5318.3    0.05       0  5524.6    0.16       0  5846.1    0.05       0
Bank Sta=4196.3,5363.1
Exp/Cntr=0.3,0.1

Type RM Length L Ch R = 1,45288,862,862,862
BEGIN DESCRIPTION:
BIRCH CREEK 48.0
END DESCRIPTION:
XS GIS Cut Line= 3
      2851074.97      7058225.00      2849125.00      7058275.00
      2848325.03      7058075.01
#Sta/Elev= 30
  2994.5  473.57  3134.5  467.32  3483.6  443.60  3662.1  429.76  3704.7  425.50
  3814.7  422.81  4375.7  416.27  4805.7  411.89  4963.1  409.39  4968.3  404.44
  4975.4  404.01  4978.2  403.21  4997.3  404.01  5004.4  404.79  5009.5  410.27
  5037.9  410.98  5174.5  409.90  5215.7  411.38  5233.7  407.05  5251.8  411.52
  5326.5  411.43  5376.5  413.36  5443.5  416.27  5504.3  419.27  5586.8  427.06
  5669.2  439.52  5687.3  443.98  5718.2  447.42  5746.5  453.50  5769.7  455.69
#Mann=7,-1,0
  2994.5    0.05       0  3483.6    0.16       0  3662.1    0.05       0
  4805.7    0.12       0  4975.4    0.07       0  4997.3    0.12       0
  5376.5    0.16       0
Bank Sta=4375.7,5443.5
Exp/Cntr=0.3,0.1

Type RM Length L Ch R = 1,44426,798,798,798
BEGIN DESCRIPTION:
BIRCH CREEK 47.0
END DESCRIPTION:
XS GIS Cut Line= 3
      2850825.03      7058125.01      2849425.00      7057525.00
      2848624.99      7057225.00
#Sta/Elev= 30
  3481.5  462.10  3558.9  455.25  3800.7  438.60  3829.7  435.18  3953.0  429.46
  4001.1  423.94  4123.4  419.28  4383.7  415.00  4809.2  410.59  4854.8  410.70
  4937.6  409.67  4961.2  412.35  4972.1  410.03  4982.9  410.10  4990.9  404.17
  4993.8  403.37  5013.0  404.17  5026.0  410.35  5068.8  409.10  5165.8  409.34
  5207.6  407.21  5293.0  407.39  5331.3  412.48  5373.4  415.00  5381.7  415.84
  5532.5  427.34  5642.8  438.88  5703.3  440.49  5805.7  449.24  5859.1  452.35
#Mann=8,-1,0
  3481.5    0.05       0  3558.9    0.16       0  4001.1    0.05       0
  4809.2    0.07       0  4854.8    0.12       0  4990.9    0.07       0
  5013.0    0.12       0  5381.7    0.05       0
Bank Sta=4383.7,5373.4
Exp/Cntr=0.3,0.1

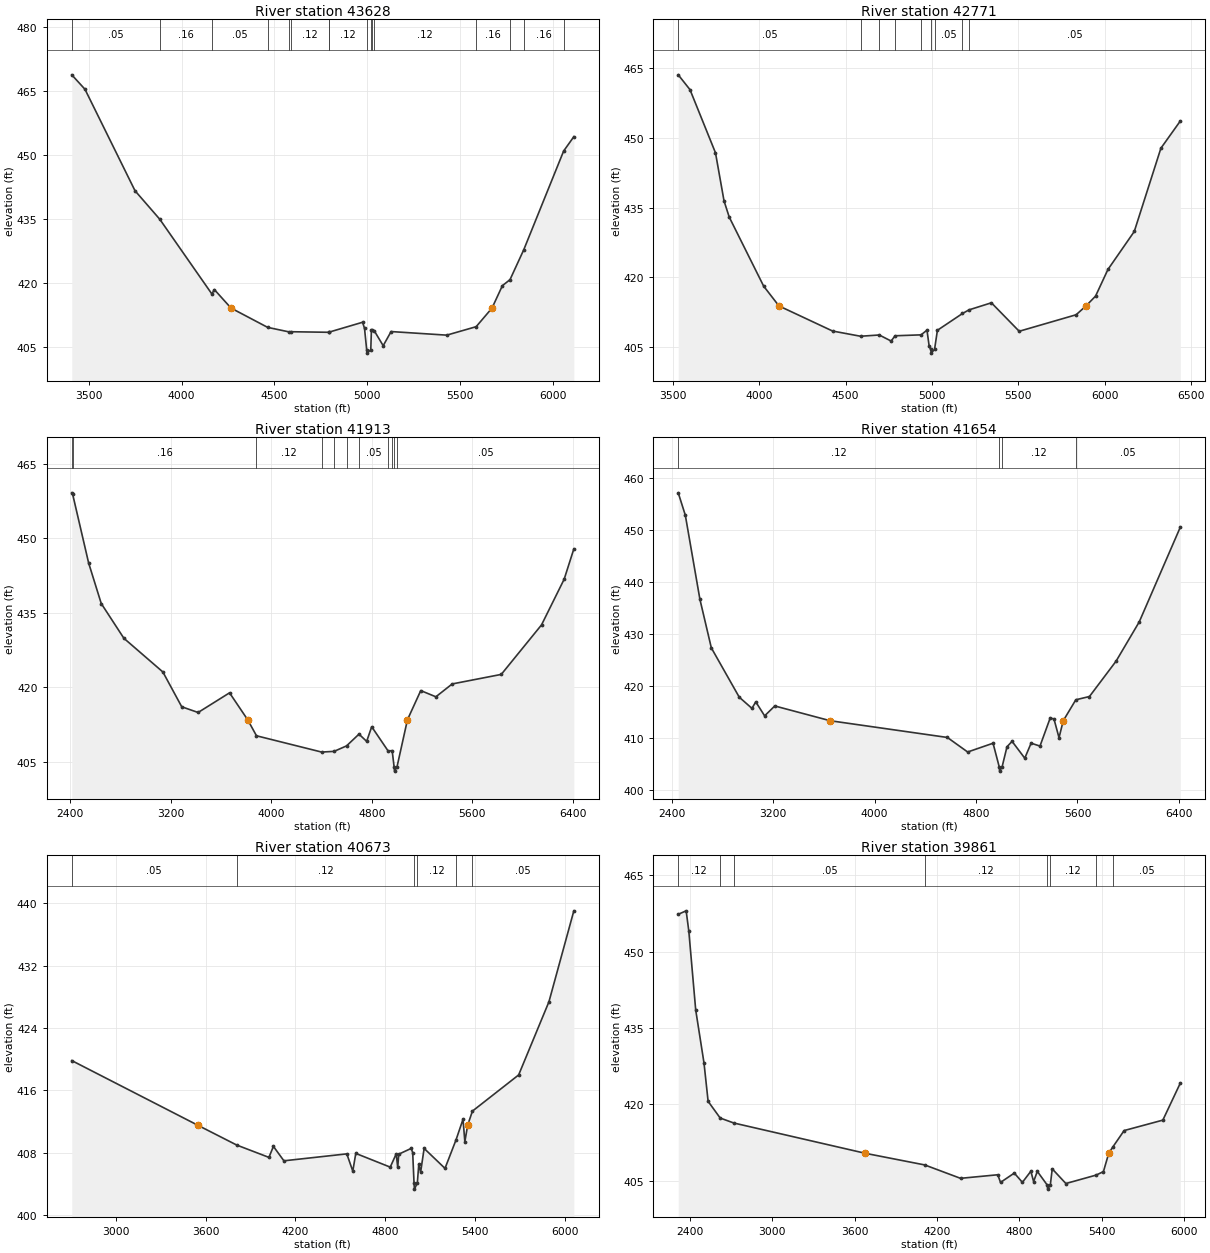
Type RM Length L Ch R = 1,43628,857,857,857
BEGIN DESCRIPTION:
BIRCH CREEK 46.0
END DESCRIPTION:
XS GIS Cut Line= 3
      2851075.01      7057875.01      2849875.00      7056875.00
      2848975.03      7056175.03
#Sta/Elev= 30
  3409.4  468.83  3480.4  465.45  3749.8  441.69  3883.3  435.00  4163.4  417.52
  4176.8  418.55  4266.5  414.22  4463.6  409.70  4578.9  408.64  4590.0  408.68
  4791.4  408.55  4791.5  408.55  4974.6  410.90  4985.0  409.47  4996.6  404.47
  4999.5  403.67  5018.7  404.47  5022.1  409.07  5027.0  409.10  5037.0  408.93
  5085.5  405.41  5128.0  408.72  5427.5  407.88  5585.8  409.86  5671.2  414.22
  5727.1  419.47  5768.0  420.87  5842.1  427.88  6056.7  450.99  6111.6  454.35
#Mann=16,-1,0
  3409.4    0.05       0  3883.3    0.16       0  4163.4    0.05       0
  4463.6    0.16       0  4578.9    0.07       0  4590.0    0.12       0
  4791.4    0.16       0  4791.5    0.12       0  4996.6    0.07       0
  5018.7    0.12       0  5027.0    0.07       0  5037.0    0.12       0
  5585.8    0.16       0  5768.0    0.05       0  5842.1    0.16       0
  6056.7    0.05       0
Bank Sta=4266.5,5671.2
Exp/Cntr=0.3,0.1

Type RM Length L Ch R = 1,42771,858,858,858
BEGIN DESCRIPTION:
BIRCH CREEK 45.0
END DESCRIPTION:
XS GIS Cut Line= 3
      2851174.99      7057574.98      2850475.00      7056275.00
      2849075.04      7055975.01
#Sta/Elev= 30
  3530.8  463.53  3598.9  460.34  3746.6  446.76  3796.1  436.42  3826.1  432.95
  4025.6  418.10  4114.1  413.85  4424.8  408.45  4586.7  407.33  4695.1  407.60
  4763.9  406.30  4787.0  407.43  4937.5  407.63  4971.6  408.64  4984.5  405.14
  4993.4  404.50  4996.3  403.70  5015.5  404.50  5032.0  408.61  5177.3  412.22
  5215.0  413.00  5344.7  414.52  5505.8  408.40  5835.6  411.95  5892.7  413.85
  5948.1  415.96  6019.7  421.68  6172.3  429.85  6326.5  447.75  6439.0  453.60
#Mann=9,-1,0
  3530.8    0.05       0  4586.7    0.12       0  4695.1    0.07       0
  4787.0    0.12       0  4937.5    0.05       0  4993.4    0.03       0
  5015.5    0.05       0  5177.3    0.07       0  5215.0    0.05       0
Bank Sta=4114.1,5892.7
Exp/Cntr=0.3,0.1

Type RM Length L Ch R = 1,41913,259,259,259
BEGIN DESCRIPTION:
BIRCH CREEK 44.0
END DESCRIPTION:
XS GIS Cut Line= 3
      2853279.19      7055647.77      2850701.08      7055587.01
      2849288.04      7055561.00
#Sta/Elev= 30
  2414.3  459.18  2420.3  459.01  2548.5  445.04  2648.6  436.89  2828.6  429.89
  3138.7  423.10  3288.7  416.09  3418.8  414.94  3668.8  418.90  3812.9  413.48
  3883.0  410.25  4400.9  406.97  4499.9  407.11  4599.0  408.21  4698.0  410.58
  4759.1  409.12  4799.1  412.07  4929.4  407.20  4961.8  407.25  4977.6  403.93
  4980.5  403.13  4999.8  403.93  5083.4  413.48  5189.2  419.35  5309.3  418.10
  5439.3  420.69  5829.3  422.61  6149.4  432.58  6329.4  441.78  6406.4  447.89
#Mann=11,-1,0
  2414.3    0.05       0  2420.3    0.16       0  3883.0    0.12       0
  4400.9    0.07       0  4499.9    0.12       0  4599.0    0.07       0
  4698.0    0.05       0  4929.4    0.12       0  4961.8    0.05       0
  4977.6    0.03       0  4999.8    0.05       0
Bank Sta=3812.9,5083.4
Exp/Cntr=0.3,0.1

Type RM Length L Ch R = 1,41654,981,981,981
BEGIN DESCRIPTION:
BIRCH CREEK 43.0
END DESCRIPTION:
XS GIS Cut Line= 3
      2853235.85      7055422.08      2850675.04      7055326.59
      2849278.76      7055291.90
#Sta/Elev= 30
  2451.7  457.13  2507.5  452.83  2622.7  436.63  2712.7  427.29  2932.9  417.80
  3033.0  415.65  3063.0  416.90  3133.0  414.21  3213.1  416.11  3649.8  413.27
  4574.0  410.05  4734.1  407.25  4934.3  408.94  4983.2  404.37  4986.2  403.57
  5005.4  404.37  5044.3  408.26  5084.3  409.30  5184.4  406.06  5234.4  408.95
  5304.4  408.39  5384.4  413.76  5414.5  413.63  5454.5  410.00  5487.9  413.27
  5587.0  417.30  5694.5  417.93  5904.6  424.74  6087.3  432.30  6411.0  450.52
#Mann=4,-1,0
  2451.7    0.12       0  4983.2    0.07       0  5005.4    0.12       0
  5587.0    0.05       0
Bank Sta=3649.8,5487.9
Exp/Cntr=0.3,0.1

Type RM Length L Ch R = 1,40673,812,812,812
BEGIN DESCRIPTION:
double Mapping XS fd41a36e
END DESCRIPTION:
XS GIS Cut Line= 3
      2852671.53      7054432.49      2850362.54      7054493.26
      2849408.87      7054918.07
#Sta/Elev= 30
  2706.3  419.81  3549.3  411.51  3808.3  408.98  4023.3  407.40  4053.3  408.81
  4123.3  406.96  4543.5  407.85  4583.5  405.64  4603.5  407.91  4833.6  406.15
  4873.6  407.85  4883.6  406.12  4890.4  407.81  4973.6  408.55  4983.6  408.02
  4992.5  404.13  4995.5  403.33  5014.7  404.13  5024.3  406.53  5036.7  405.52
  5060.0  408.55  5199.4  405.99  5273.0  409.64  5319.9  412.29  5332.0  409.40
  5350.7  411.51  5382.5  413.33  5691.4  417.97  5893.7  427.35  6060.1  439.01
#Mann=6,-1,0
  2706.3    0.05       0  3808.3    0.12       0  4992.5    0.07       0
  5014.7    0.12       0  5273.0    0.16       0  5382.5    0.05       0
Bank Sta=3549.3,5350.7
Exp/Cntr=0.3,0.1

Type RM Length L Ch R = 1,39861,1675,1675,1675
BEGIN DESCRIPTION:
double BIRCH CREEK 42.0
END DESCRIPTION:
XS GIS Cut Line= 3
      2853131.64      7053494.99      2850362.54      7053755.41
      2849634.51      7054240.76
#Sta/Elev= 30
  2315.3  457.31  2373.0  457.99  2392.3  454.01  2442.5  438.52  2502.8  428.14
  2532.9  420.58  2620.8  417.30  2720.5  416.32  3676.8  410.38  4110.5  408.09
  4371.0  405.46  4642.2  406.16  4662.3  404.66  4762.7  406.49  4821.6  404.67
  4883.2  406.85  4903.3  404.82  4930.2  406.83  5002.6  404.14  5005.6  403.34
  5024.9  404.14  5038.9  407.32  5138.3  404.44  5359.1  406.10  5411.8  406.79
  5450.4  410.38  5480.0  411.61  5562.4  414.84  5844.4  416.89  5971.6  424.16
#Mann=8,-1,0
  2315.3    0.12       0  2620.8    0.16       0  2720.5    0.05       0
  4110.5    0.12       0  5002.6    0.07       0  5024.9    0.12       0
  5359.1    0.16       0  5480.0    0.05       0
Bank Sta=3676.8,5450.4
Exp/Cntr=0.3,0.1

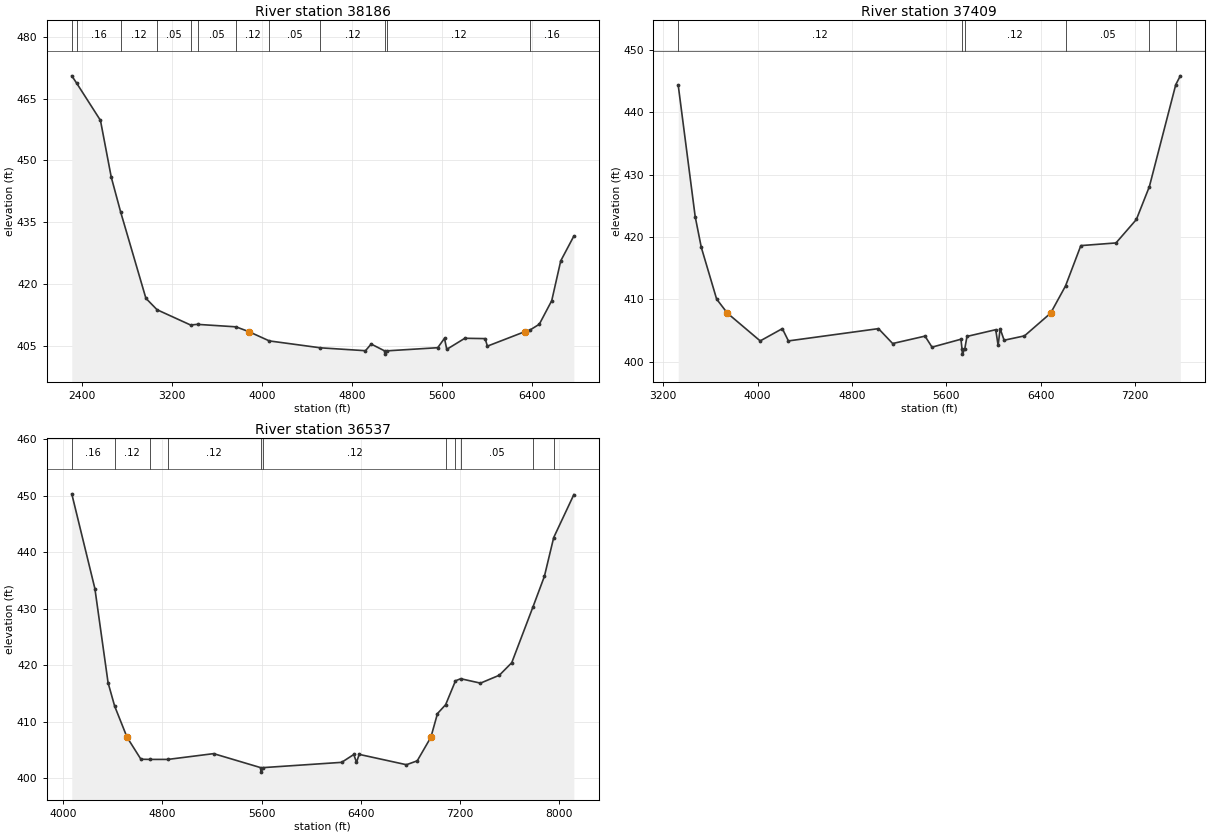
Type RM Length L Ch R = 1,38186,777,777,777
BEGIN DESCRIPTION:
double BIRCH CREEK 41.0
END DESCRIPTION:
XS GIS Cut Line= 3
      2853574.95      7053025.00      2850877.66      7052758.36
      2849128.91      7052911.76
#Sta/Elev= 30
  2306.4  470.55  2348.9  468.81  2561.5  459.73  2657.6  445.94  2740.8  437.51
  2965.8  416.51  3065.2  413.73  3362.8  410.03  3424.9  410.18  3766.9  409.58
  3879.4  408.44  4063.6  406.16  4518.8  404.48  4919.0  403.78  4969.3  405.40
  5088.4  403.75  5091.6  402.95  5111.2  403.75  5561.6  404.51  5621.8  406.79
  5641.9  404.11  5802.5  406.80  5983.2  406.72  6003.3  404.89  6339.6  408.44
  6383.0  408.82  6465.0  410.21  6575.5  415.93  6655.8  425.61  6772.3  431.62
#Mann=12,-1,0
  2306.4    0.12       0  2348.9    0.16       0  2740.8    0.12       0
  3065.2    0.05       0  3362.8    0.12       0  3424.9    0.05       0
  3766.9    0.12       0  4063.6    0.05       0  4518.8    0.12       0
  5088.4    0.07       0  5111.2    0.12       0  6383.0    0.16       0
Bank Sta=3879.4,6339.6
Exp/Cntr=0.3,0.1

Type RM Length L Ch R = 1,37409,872,872,872
BEGIN DESCRIPTION:
double BIRCH CREEK 40.0
END DESCRIPTION:
XS GIS Cut Line= 3
      2852474.99      7051125.01      2851075.00      7052025.00
      2848525.02      7052475.00
#Sta/Elev= 30
  3328.2  444.36  3471.8  423.30  3523.4  418.37  3653.5  410.06  3744.9  407.80
  4022.6  403.35  4210.2  405.32  4261.7  403.35  5024.7  405.32  5144.8  402.93
  5419.0  404.12  5478.2  402.35  5723.6  403.62  5732.6  402.03  5735.7  401.23
  5755.4  402.03  5774.4  404.07  6018.1  405.15  6038.4  402.62  6055.4  405.31
  6089.2  403.46  6261.8  404.16  6483.1  407.80  6609.4  412.17  6739.1  418.64
  7037.0  419.07  7209.6  422.83  7319.8  428.11  7543.4  444.47  7581.9  445.88
#Mann=6,-1,0
  3328.2    0.12       0  5732.6    0.07       0  5755.4    0.12       0
  6609.4    0.05       0  7319.8    0.16       0  7543.4    0.05       0
Bank Sta=3744.9,6483.1
Exp/Cntr=0.3,0.1

Type RM Length L Ch R = 1,36537,718,718,718
BEGIN DESCRIPTION:
double BIRCH CREEK 39.0
END DESCRIPTION:
XS GIS Cut Line= 3
      2852024.96      7050675.03      2851225.00      7051275.00
      2848424.97      7052475.01
#Sta/Elev= 30
  4070.1  450.32  4256.5  433.55  4362.8  416.90  4415.6  412.78  4515.5  407.27
  4627.3  403.38  4697.2  403.35  4845.3  403.35  5213.3  404.37  5591.8  401.90
  5594.9  401.10  5614.6  401.90  6245.1  402.83  6343.0  404.22  6364.7  402.83
  6386.5  404.24  6767.3  402.41  6854.3  403.10  6964.2  407.27  7017.5  411.46
  7083.2  413.03  7162.6  417.25  7204.4  417.62  7363.9  416.84  7516.2  418.24
  7615.9  420.45  7787.5  430.35  7878.8  435.71  7954.1  442.59  8116.4  450.18
#Mann=11,-1,0
  4070.1    0.16       0  4415.6    0.12       0  4697.2    0.05       0
  4845.3    0.12       0  5591.8    0.07       0  5614.6    0.12       0
  7083.2    0.16       0  7162.6    0.12       0  7204.4    0.05       0
  7787.5    0.16       0  7954.1    0.05       0
Bank Sta=4515.5,6964.2
Exp/Cntr=0.3,0.1