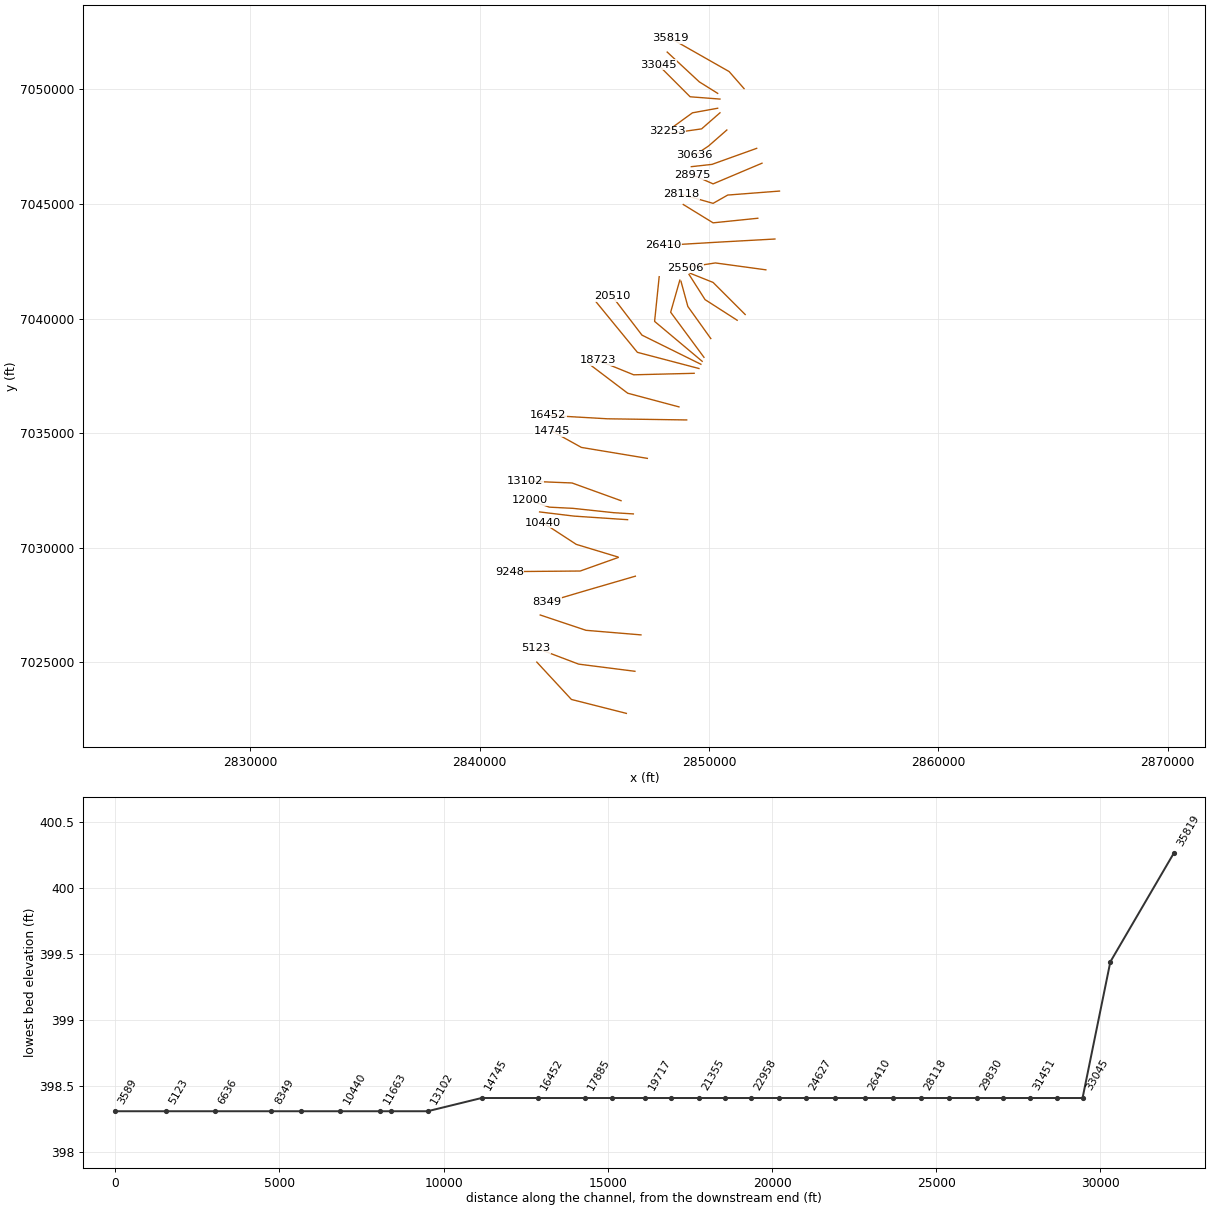
HEC-RAS study BIRCH CREEK.prj: BIRCH CREEK Base Level Engineering

--- BIRCH CREEK.g01 (geometry) --- (continued)

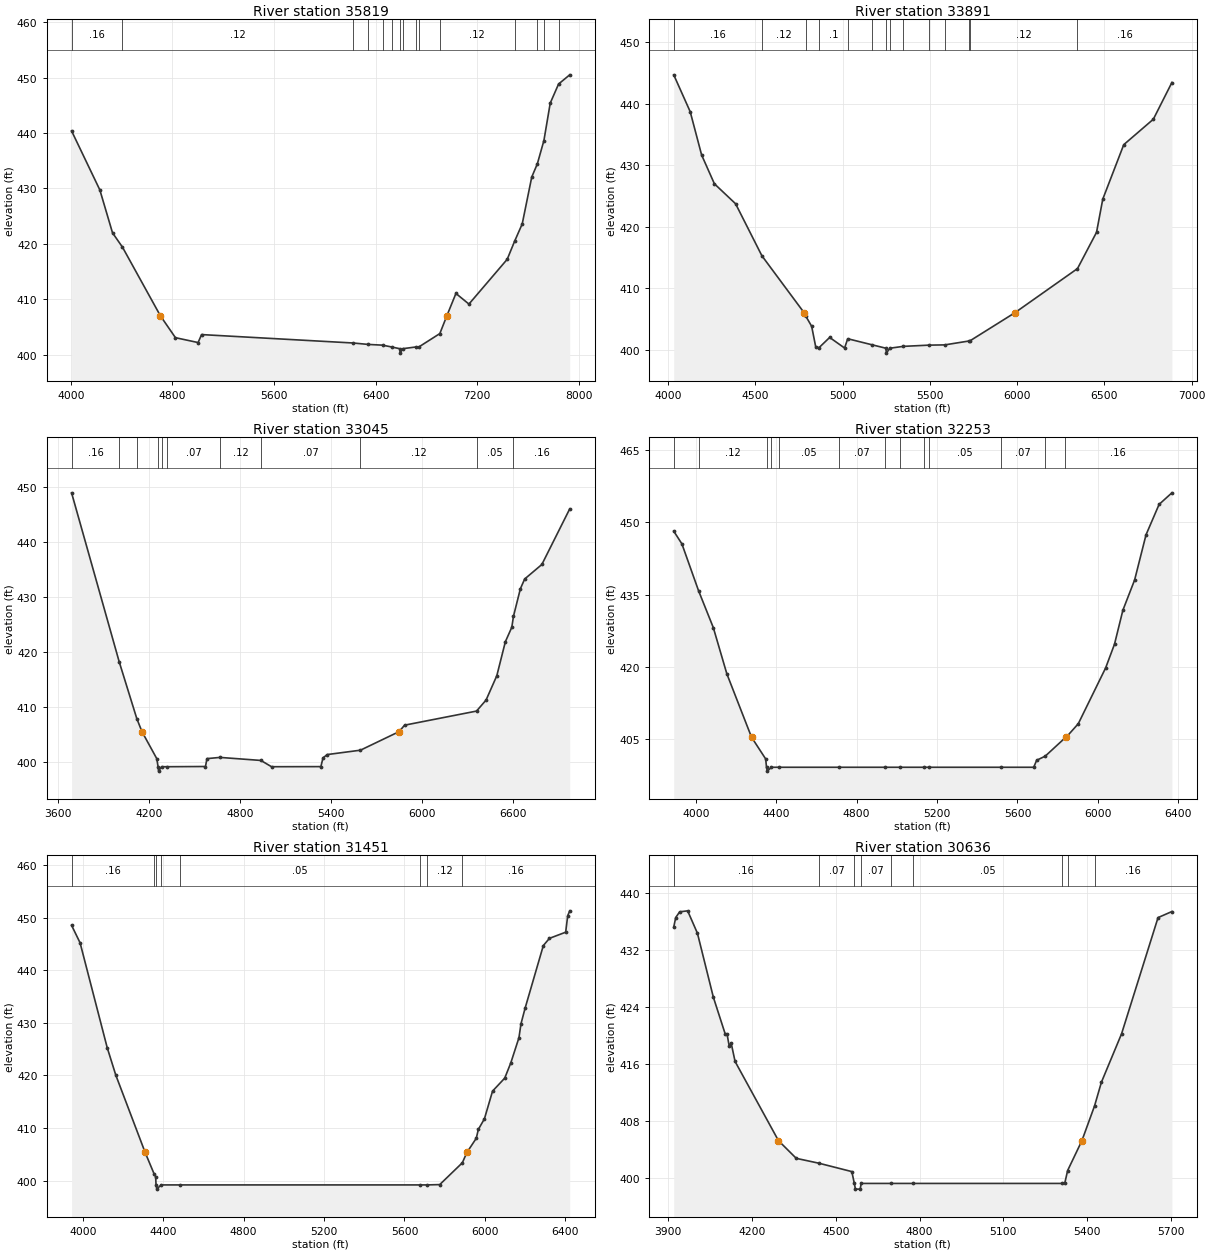
Type RM Length L Ch R = 1,35819,1928,1928,1928
BEGIN DESCRIPTION:
double BIRCH CREEK 38.0
END DESCRIPTION:
XS GIS Cut Line= 3
      2851525.75      7050031.43      2850875.00      7050775.00
      2848325.03      7052224.98
#Sta/Elev= 30
  4006.5  440.40  4229.2  429.73  4328.8  421.99  4407.2  419.40  4706.0  406.99
  4824.2  403.05  5002.5  402.17  5029.9  403.61  6223.4  402.09  6342.6  401.83
  6454.4  401.70  6532.6  401.34  6589.7  401.06  6592.9  400.26  6612.7  401.06
  6716.7  401.37  6739.8  401.37  6905.4  403.79  6960.4  406.99  7032.1  411.04
  7134.5  409.12  7435.8  417.21  7493.7  420.45  7554.0  423.60  7628.9  432.06
  7673.0  434.45  7724.7  438.66  7774.5  445.42  7840.2  448.87  7928.0  450.53
#Mann=15,-1,0
  4006.5    0.16       0  4407.2    0.12       0  6223.4    0.07       0
  6342.6    0.12       0  6454.4    0.05       0  6532.6    0.07       0
  6589.7    0.07       0  6612.7    0.07       0  6716.7    0.05       0
  6739.8    0.07       0  6905.4    0.12       0  7493.7    0.16       0
  7673.0    0.12       0  7724.7    0.16       0  7840.2    0.05       0
Bank Sta=4706,6960.4
Exp/Cntr=0.3,0.1

Type RM Length L Ch R = 1,33891,846,846,846
BEGIN DESCRIPTION:
double BIRCH CREEK 37.0
END DESCRIPTION:
XS GIS Cut Line= 3
      2850375.01      7049824.99      2849575.00      7050325.00
      2848175.01      7051624.99
#Sta/Elev= 30
  4032.9  444.70  4127.3  438.70  4192.7  431.66  4265.8  426.98  4387.3  423.73
  4538.0  415.27  4780.1  406.00  4787.8  405.53  4823.0  403.81  4846.6  400.42
  4866.1  400.35  4926.2  401.99  5011.7  400.27  5029.6  401.78  5171.2  400.78
  5248.0  400.24  5251.2  399.44  5271.0  400.24  5348.5  400.54  5495.9  400.74
  5585.7  400.78  5723.9  401.41  5727.8  401.40  5986.8  406.00  6346.0  413.19
  6455.1  419.09  6490.8  424.48  6611.0  433.34  6780.5  437.48  6886.8  443.45
#Mann=14,-1,0
  4032.9    0.16       0  4538.0    0.12       0  4787.8    0.16       0
  4866.1     0.1       0  5029.6    0.16       0  5171.2    0.05       0
  5248.0    0.07       0  5271.0    0.05       0  5348.5    0.12       0
  5495.9    0.07       0  5585.7    0.12       0  5723.9    0.07       0
  5727.8    0.12       0  6346.0    0.16       0
Bank Sta=4780.1,5986.8
Exp/Cntr=0.3,0.1

Type RM Length L Ch R = 1,33045,792,792,792
BEGIN DESCRIPTION:
double BIRCH CREEK 36.0
END DESCRIPTION:
XS GIS Cut Line= 3
      2850475.00      7049575.00      2849175.00      7049675.00
      2847775.03      7051074.97
#Sta/Elev= 30
  3691.3  448.93  4005.2  418.26  4121.1  407.96  4155.1  405.59  4253.0  400.67
  4261.5  399.21  4264.8  398.41  4284.5  399.21  4320.2  399.21  4573.9  399.25
  4583.9  400.68  4669.5  400.90  4939.1  400.35  5009.3  399.21  5334.6  399.23
  5348.7  400.82  5377.0  401.42  5595.3  402.21  5851.0  405.59  5886.1  406.75
  6360.6  409.31  6423.5  411.31  6494.2  415.72  6550.8  421.91  6593.2  424.53
  6604.3  426.54  6649.8  431.53  6678.1  433.29  6791.2  435.92  6975.0  446.02
#Mann=11,-1,0
  3691.3    0.16       0  4005.2    0.12       0  4121.1    0.16       0
  4261.5    0.07       0  4284.5    0.16       0  4320.2    0.07       0
  4669.5    0.12       0  4939.1    0.07       0  5595.3    0.12       0
  6360.6    0.05       0  6604.3    0.16       0
Bank Sta=4155.1,5851
Exp/Cntr=0.3,0.1

Type RM Length L Ch R = 1,32253,802,802,802
BEGIN DESCRIPTION:
BIRCH CREEK 35.0
END DESCRIPTION:
XS GIS Cut Line= 3
      2850374.96      7049174.99      2849275.00      7048975.00
      2848175.03      7048175.02
#Sta/Elev= 30
  3890.0  448.15  3930.6  445.51  4013.3  435.82  4086.9  428.15  4154.2  418.58
  4276.9  405.45  4347.3  400.94  4351.5  399.21  4355.4  398.41  4376.1  399.21
  4412.8  399.21  4713.5  399.21  4940.2  399.21  5015.6  399.21  5136.0  399.21
  5161.3  399.21  5519.6  399.21  5680.7  399.21  5695.4  400.66  5738.2  401.52
  5834.3  405.21  5842.8  405.45  5902.5  408.24  6038.5  419.80  6082.6  424.72
  6124.3  431.76  6182.7  438.03  6239.5  447.40  6304.4  453.69  6368.1  456.09
#Mann=13,-1,0
  3890.0    0.16       0  4013.3    0.12       0  4351.5   0.035       0
  4376.1    0.12       0  4412.8    0.05       0  4713.5    0.07       0
  4940.2    0.05       0  5015.6    0.12       0  5136.0    0.07       0
  5161.3    0.05       0  5519.6    0.07       0  5738.2    0.12       0
  5834.3    0.16       0
Bank Sta=4276.9,5842.8
Exp/Cntr=0.3,0.1

Type RM Length L Ch R = 1,31451,815,815,815
BEGIN DESCRIPTION:
BIRCH CREEK 34.0
END DESCRIPTION:
XS GIS Cut Line= 3
      2850475.01      7048975.01      2849675.00      7048275.00
      2848275.05      7048075.01
#Sta/Elev= 30
  3944.6  448.53  3986.9  445.20  4121.6  425.31  4164.3  420.09  4310.5  405.37
  4354.4  401.36  4362.7  400.77  4364.6  399.21  4368.5  398.41  4389.3  399.21
  4483.4  399.21  5677.5  399.21  5709.6  399.21  5775.3  399.27  5887.7  403.41
  5910.4  405.37  5957.2  408.08  5967.3  409.75  5997.6  411.77  6038.0  417.03
  6098.6  419.50  6128.9  422.41  6169.3  427.18  6179.4  429.82  6199.6  432.75
  6290.5  444.68  6320.8  446.05  6401.6  447.22  6411.7  450.35  6421.8  451.28
#Mann=8,-1,0
  3944.6    0.16       0  4354.4    0.07       0  4364.6   0.033       0
  4389.3    0.07       0  4483.4    0.05       0  5677.5    0.07       0
  5709.6    0.12       0  5887.7    0.16       0
Bank Sta=4310.5,5910.4
Exp/Cntr=0.3,0.1

Type RM Length L Ch R = 1,30636,806,806,806
BEGIN DESCRIPTION:
BIRCH CREEK 33.0
END DESCRIPTION:
XS GIS Cut Line= 3
      2850774.98      7048224.99      2849975.00      7047525.00
      2849375.00      7047125.00
#Sta/Elev= 30
  3919.4  435.18  3926.5  436.54  3940.7  437.34  3969.2  437.48  4004.3  434.33
  4061.3  425.35  4104.0  420.16  4110.6  420.13  4118.2  418.46  4124.9  418.95
  4139.1  416.33  4294.6  405.21  4358.3  402.73  4439.1  402.05  4557.2  400.87
  4566.2  399.21  4570.1  398.41  4587.0  398.41  4590.9  399.21  4697.0  399.21
  4777.6  399.21  5309.1  399.21  5320.4  399.34  5330.1  401.02  5381.2  405.21
  5426.4  410.08  5451.1  413.42  5523.2  420.21  5653.9  436.53  5703.5  437.38
#Mann=9,-1,0
  3919.4    0.16       0  4439.1    0.07       0  4566.2   0.033       0
  4590.9    0.07       0  4697.0    0.07       0  4777.6    0.05       0
  5309.1    0.16       0  5330.1    0.12       0  5426.4    0.16       0
Bank Sta=4294.6,5381.2
Exp/Cntr=0.3,0.1

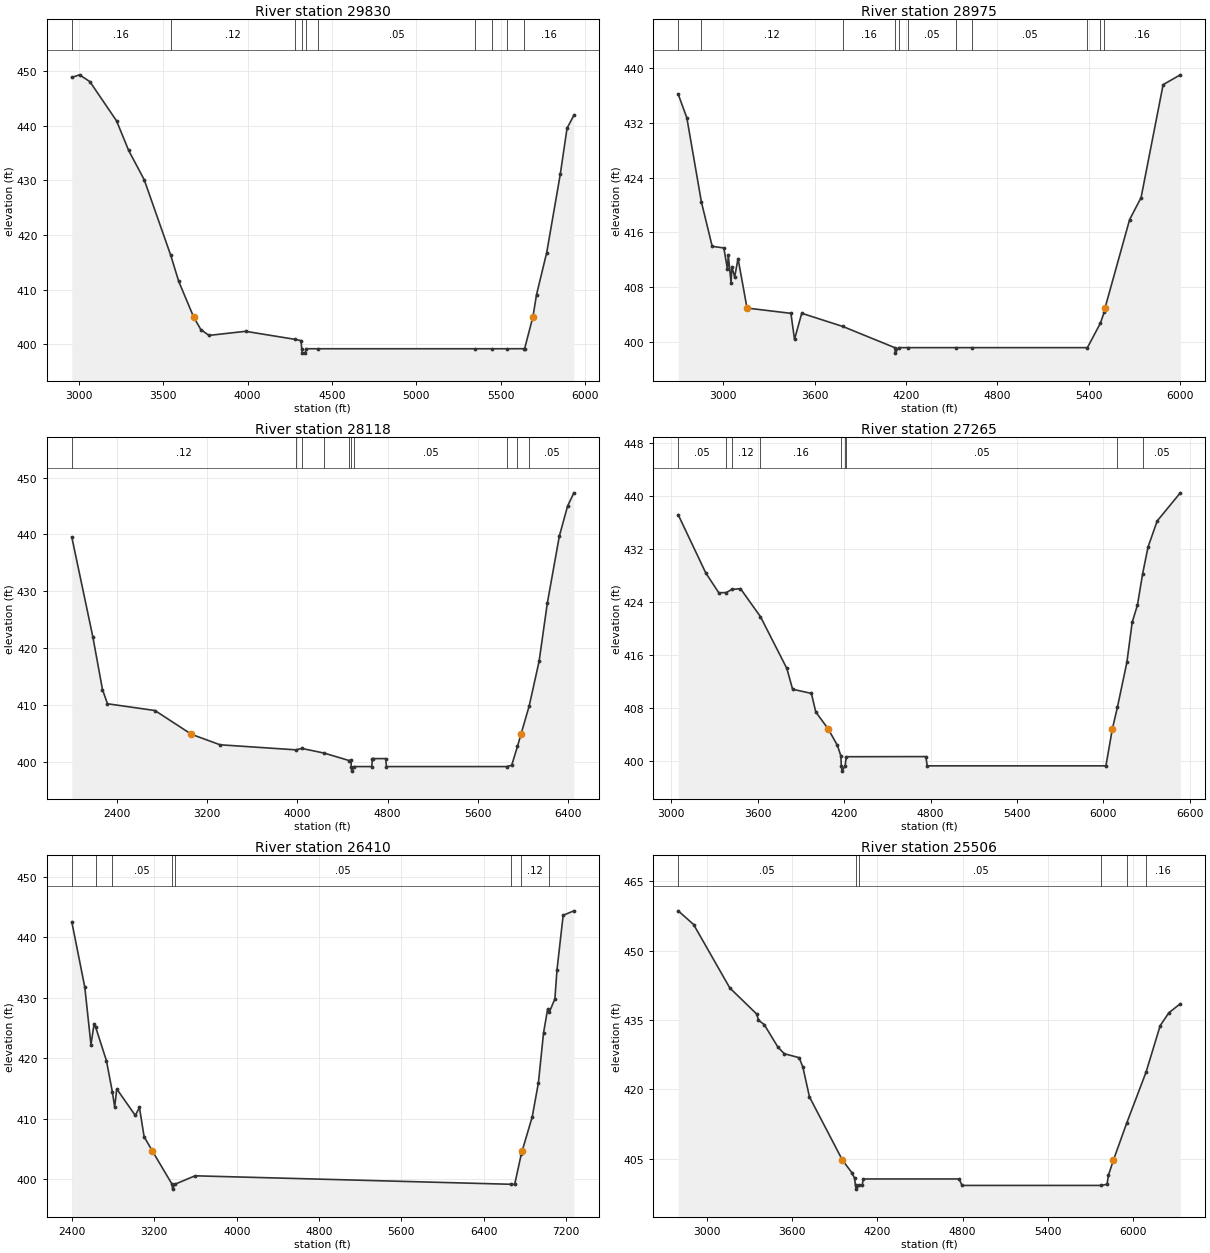
Type RM Length L Ch R = 1,29830,855,855,855
BEGIN DESCRIPTION:
BIRCH CREEK 32.0
END DESCRIPTION:
XS GIS Cut Line= 3
      2852075.01      7047425.00      2850125.00      7046725.00
      2849224.98      7046625.00
#Sta/Elev= 30
  2957.0  448.83  3003.1  449.31  3064.6  448.06  3222.6  440.89  3294.5  435.47
  3386.7  430.12  3544.2  416.27  3591.3  411.52  3678.9  405.08  3722.0  402.73
  3770.4  401.65  3987.6  402.40  4282.9  400.92  4317.0  400.69  4320.6  399.21
  4324.6  398.41  4341.6  398.41  4345.6  399.21  4414.4  399.21  5349.5  399.21
  5449.5  399.21  5537.1  399.21  5636.5  399.22  5642.6  399.24  5691.9  405.08
  5713.0  409.09  5773.4  416.79  5853.9  431.11  5894.1  439.55  5934.4  441.89
#Mann=10,-1,0
  2957.0    0.16       0  3544.2    0.12       0  4282.9    0.07       0
  4320.6   0.033       0  4345.6    0.07       0  4414.4    0.05       0
  5349.5    0.07       0  5449.5    0.05       0  5537.1    0.12       0
  5636.5    0.16       0
Bank Sta=3678.9,5691.9
Exp/Cntr=0.3,0.1

Type RM Length L Ch R = 1,28975,857,857,857
BEGIN DESCRIPTION:
BIRCH CREEK 31.0
END DESCRIPTION:
XS GIS Cut Line= 3
      2852307.01      7046776.26      2850175.00      7045875.00
      2849274.97      7046275.01
#Sta/Elev= 30
  2703.3  436.14  2759.8  432.72  2855.4  420.46  2926.4  413.98  3003.0  413.74
  3026.7  410.65  3032.1  412.69  3050.4  408.70  3055.8  410.99  3074.1  409.50
  3096.3  412.20  3155.4  404.98  3443.8  404.21  3467.5  400.41  3514.9  404.22
  3784.5  402.30  4126.1  399.21  4130.1  398.41  4151.1  399.21  4210.5  399.21
  4530.0  399.21  4636.5  399.21  5392.3  399.21  5478.3  402.80  5501.8  404.34
  5507.9  404.98  5669.8  417.88  5745.0  421.08  5890.0  437.55  6002.9  438.98
#Mann=11,-1,0
  2703.3    0.16       0  2855.4    0.12       0  3784.5    0.16       0
  4126.1   0.033       0  4151.1    0.16       0  4210.5    0.05       0
  4530.0    0.07       0  4636.5    0.05       0  5392.3    0.16       0
  5478.3    0.07       0  5501.8    0.16       0
Bank Sta=3155.4,5507.9
Exp/Cntr=0.3,0.1

Type RM Length L Ch R = 1,28118,853,853,853
BEGIN DESCRIPTION:
BIRCH CREEK 30.0
END DESCRIPTION:
XS GIS Cut Line= 4
      2853070.84      7045560.96      2850813.93      7045387.35
      2850175.00      7045025.00      2848775.03      7045424.99
#Sta/Elev= 30
  1998.7  439.56  2185.1  422.06  2271.2  412.74  2315.5  410.25  2736.7  409.06
  3060.8  404.88  3314.3  403.04  3986.9  402.15  4039.4  402.40  4237.7  401.58
  4459.2  400.27  4476.8  400.37  4478.0  399.21  4482.3  398.41  4504.0  399.21
  4660.0  399.21  4665.8  400.60  4674.9  400.61  4784.0  400.61  4789.9  399.21
  5856.3  399.21  5901.6  399.44  5952.7  402.77  5983.7  404.88  6056.4  409.85
  6144.7  417.73  6217.5  427.93  6324.1  439.71  6396.9  444.97  6452.8  447.32
#Mann=10,-1,0
  1998.7    0.12       0  3986.9    0.16       0  4039.4    0.12       0
  4237.7     0.1       0  4459.2    0.05       0  4478.0   0.033       0
  4504.0    0.05       0  5856.3    0.07       0  5952.7    0.16       0
  6056.4    0.05       0
Bank Sta=3060.8,5983.7
Exp/Cntr=0.3,0.1

Type RM Length L Ch R = 1,27265,855,855,855
BEGIN DESCRIPTION:
BIRCH CREEK 29.0
END DESCRIPTION:
XS GIS Cut Line= 3
      2852125.02      7044375.00      2850175.00      7044175.00
      2848874.98      7044975.01
#Sta/Elev= 30
  3047.5  437.19  3238.5  428.41  3329.0  425.40  3380.4  425.43  3420.0  425.90
  3479.8  426.02  3618.6  421.78  3801.5  413.96  3841.7  410.80  3972.3  410.17
  4002.5  407.37  4088.7  404.80  4153.3  402.29  4176.5  400.74  4180.3  399.21
  4184.7  398.41  4206.7  399.21  4214.7  400.59  4767.1  400.61  4776.5  399.21
  6017.5  399.21  6062.3  404.80  6097.5  408.09  6163.2  414.88  6199.9  420.92
  6236.6  423.55  6272.6  428.29  6310.0  432.31  6373.8  436.27  6534.2  440.52
#Mann=9,-1,0
  3047.5    0.05       0  3380.4    0.16       0  3420.0    0.12       0
  3618.6    0.16       0  4180.3   0.033       0  4206.7    0.16       0
  4214.7    0.05       0  6097.5    0.16       0  6272.6    0.05       0
Bank Sta=4088.7,6062.3
Exp/Cntr=0.3,0.1

Type RM Length L Ch R = 1,26410,904,904,904
BEGIN DESCRIPTION:
BIRCH CREEK 28.0
END DESCRIPTION:
XS GIS Cut Line= 3
      2852871.26      7043468.95      2850275.00      7043325.00
      2848001.38      7043191.17
#Sta/Elev= 30
  2397.7  442.57  2524.2  431.77  2584.2  422.26  2614.3  425.67  2630.1  425.14
  2734.5  419.62  2792.3  414.45  2814.6  411.96  2834.6  414.96  3014.9  410.58
  3055.0  411.90  3100.7  407.06  3178.9  404.76  3372.3  399.21  3376.7  398.41
  3398.7  399.21  3595.8  400.61  6665.1  399.21  6700.9  399.21  6764.2  404.15
  6773.9  404.76  6871.2  410.34  6931.3  415.99  6981.4  424.25  7021.4  428.17
  7038.4  427.68  7091.6  429.85  7111.6  434.59  7171.7  443.63  7275.5  444.37
#Mann=8,-1,0
  2397.7    0.05       0  2630.1    0.16       0  2792.3    0.05       0
  3372.3   0.033       0  3398.7    0.05       0  6665.1    0.16       0
  6764.2    0.12       0  7038.4    0.05       0
Bank Sta=3178.9,6773.9
Exp/Cntr=0.3,0.1

Type RM Length L Ch R = 1,25506,879,879,879
BEGIN DESCRIPTION:
BIRCH CREEK 27.0
END DESCRIPTION:
XS GIS Cut Line= 3
      2852475.00      7042125.00      2850275.00      7042425.00
      2848974.96      7042224.99
#Sta/Elev= 30
  2797.2  458.65  2905.7  455.68  3160.5  441.95  3349.8  436.31  3362.4  434.98
  3402.8  434.03  3499.5  429.14  3544.1  427.72  3649.2  426.86  3675.3  424.77
  3721.5  418.36  3953.2  404.70  4020.9  401.93  4038.6  400.78  4045.6  399.21
  4050.0  398.41  4072.0  399.21  4093.3  399.21  4099.1  400.61  4775.3  400.61
  4795.5  399.21  5777.7  399.21  5816.9  399.47  5827.0  401.44  5861.9  404.70
  5954.5  412.63  6091.7  423.74  6191.2  433.80  6251.9  436.57  6332.9  438.54
#Mann=6,-1,0
  2797.2    0.05       0  4045.6   0.033       0  4072.0    0.05       0
  5777.7    0.16       0  5954.5    0.12       0  6091.7    0.16       0
Bank Sta=3953.2,5861.9
Exp/Cntr=0.3,0.1

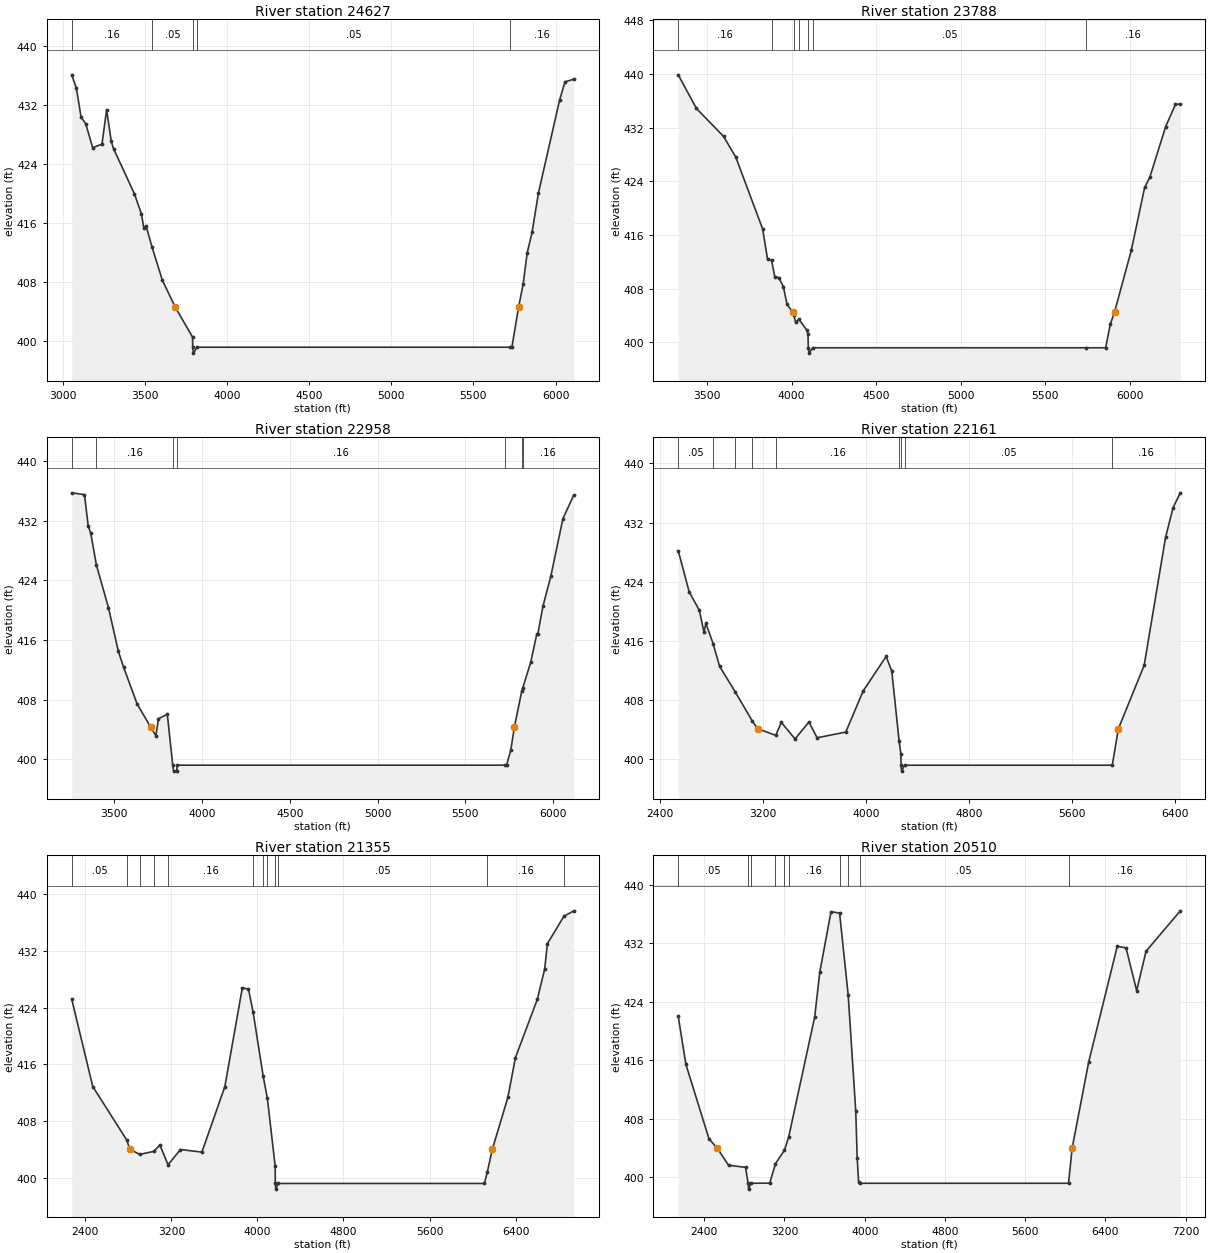
Type RM Length L Ch R = 1,24627,839,839,839
BEGIN DESCRIPTION:
BIRCH CREEK 26.0
END DESCRIPTION:
XS GIS Cut Line= 3
      2851575.02      7040174.98      2850175.00      7041575.00
      2849174.96      7041975.02
#Sta/Elev= 30
  3054.5  436.05  3082.8  434.21  3111.1  430.32  3139.4  429.44  3181.8  426.20
  3238.4  426.67  3266.7  431.33  3294.9  427.04  3309.1  426.06  3436.4  419.93
  3478.8  417.22  3492.9  415.35  3507.1  415.62  3542.8  412.78  3606.1  408.27
  3684.8  404.62  3789.9  400.58  3790.8  399.21  3795.3  398.41  3817.3  399.21
  5723.9  399.21  5734.5  399.23  5775.0  404.62  5803.2  407.78  5827.4  411.96
  5857.0  414.73  5896.0  420.08  6025.3  432.69  6057.6  435.10  6111.5  435.46
#Mann=5,-1,0
  3054.5    0.16       0  3542.8    0.05       0  3790.8   0.033       0
  3817.3    0.05       0  5723.9    0.16       0
Bank Sta=3684.8,5775
Exp/Cntr=0.3,0.1

Type RM Length L Ch R = 1,23788,830,830,830
BEGIN DESCRIPTION:
BIRCH CREEK 25.0
END DESCRIPTION:
XS GIS Cut Line= 3
      2851224.98      7039925.01      2849825.00      7040825.00
      2849124.97      7041925.04
#Sta/Elev= 30
  3329.6  439.87  3436.9  434.87  3597.4  430.70  3670.0  427.60  3828.9  416.88
  3857.6  412.38  3881.1  412.24  3900.2  409.81  3924.0  409.67  3951.4  408.29
  3972.5  405.69  4006.0  404.55  4013.0  404.02  4024.0  403.00  4042.3  403.47
  4090.4  401.80  4096.7  401.26  4098.6  399.21  4103.1  398.41  4125.2  399.21
  5742.1  399.21  5856.6  399.21  5883.7  402.70  5909.2  404.55  6008.2  413.74
  6086.9  423.09  6117.4  424.60  6211.4  432.17  6269.0  435.46  6297.8  435.52
#Mann=7,-1,0
  3329.6    0.16       0  3881.1    0.12       0  4013.0    0.16       0
  4042.3    0.05       0  4098.6   0.033       0  4125.2    0.05       0
  5742.1    0.16       0
Bank Sta=4006,5909.2
Exp/Cntr=0.3,0.1

Type RM Length L Ch R = 1,22958,797,797,797
BEGIN DESCRIPTION:
BIRCH CREEK 24.0
END DESCRIPTION:
XS GIS Cut Line= 3
      2850074.97      7039125.04      2849075.00      7040525.00
      2848775.00      7041625.00
#Sta/Elev= 30
  3257.7  435.73  3330.2  435.49  3351.1  431.32  3365.8  430.32  3398.4  426.01
  3466.6  420.35  3523.1  414.47  3552.6  412.37  3630.0  407.42  3706.3  404.35
  3736.9  403.17  3751.7  405.44  3802.1  406.03  3833.0  399.21  3837.6  398.41
  3855.1  398.41  3859.6  399.21  5727.2  399.21  5734.8  399.21  5759.0  401.23
  5779.7  404.35  5821.9  409.17  5828.0  409.62  5873.0  413.05  5907.5  416.82
  5912.7  416.74  5942.1  420.51  5987.0  424.53  6056.1  432.27  6118.3  435.46
#Mann=7,-1,0
  3257.7    0.05       0  3398.4    0.16       0  3833.0   0.033       0
  3859.6    0.16       0  5727.2    0.07       0  5821.9    0.05       0
  5828.0    0.16       0
Bank Sta=3706.3,5779.7
Exp/Cntr=0.3,0.1

Type RM Length L Ch R = 1,22161,806,806,806
BEGIN DESCRIPTION:
BIRCH CREEK 23.0
END DESCRIPTION:
XS GIS Cut Line= 3
      2849777.75      7038307.81      2848325.00      7040275.00
      2848725.00      7041675.00
#Sta/Elev= 30
  2541.8  428.21  2626.9  422.64  2706.2  420.14  2741.7  417.18  2756.4  418.39
  2812.8  415.64  2862.8  412.59  2985.7  409.09  3118.1  405.16  3158.7  404.14
  3299.2  403.25  3343.1  405.00  3449.5  402.76  3557.7  405.05  3620.7  402.92
  3843.6  403.69  3979.9  409.28  4157.3  413.91  4201.2  411.93  4258.1  402.48
  4272.2  400.70  4273.4  399.21  4278.0  398.41  4300.1  399.21  5914.6  399.21
  5962.0  404.14  6162.5  412.71  6328.9  430.03  6387.4  434.04  6443.3  436.03
#Mann=9,-1,0
  2541.8    0.05       0  2812.8    0.12       0  2985.7    0.16       0
  3118.1    0.12       0  3299.2    0.16       0  4258.1    0.05       0
  4273.4   0.033       0  4300.1    0.05       0  5914.6    0.16       0
Bank Sta=3158.7,5962
Exp/Cntr=0.3,0.1

Type RM Length L Ch R = 1,21355,845,845,845
BEGIN DESCRIPTION:
BIRCH CREEK 22.0
END DESCRIPTION:
XS GIS Cut Line= 3
      2849698.91      7038134.18      2847625.00      7039875.00
      2847825.00      7041824.98
#Sta/Elev= 30
  2274.1  425.19  2469.2  412.89  2787.5  405.28  2812.1  404.05  2905.1  403.31
  3037.0  403.74  3093.6  404.63  3169.0  401.85  3284.8  404.00  3483.8  403.63
  3697.2  412.86  3859.8  426.82  3917.0  426.64  3960.4  423.35  4053.8  414.33
  4092.3  411.25  4165.5  401.63  4166.4  399.21  4171.0  398.41  4193.1  399.21
  6110.8  399.21  6138.2  400.89  6184.6  404.05  6328.8  411.36  6398.6  416.95
  6602.1  425.17  6670.6  429.45  6696.4  433.05  6849.7  436.91  6942.0  437.68
#Mann=12,-1,0
  2274.1    0.05       0  2787.5    0.16       0  2905.1    0.07       0
  3037.0    0.12       0  3169.0    0.16       0  3960.4    0.12       0
  4053.8    0.16       0  4092.3    0.05       0  4166.4   0.033       0
  4193.1    0.05       0  6138.2    0.16       0  6849.7    0.05       0
Bank Sta=2812.1,6184.6
Exp/Cntr=0.3,0.1

Type RM Length L Ch R = 1,20510,793,793,793
BEGIN DESCRIPTION:
BIRCH CREEK 21.0
END DESCRIPTION:
XS GIS Cut Line= 3
      2849644.69      7038003.96      2847075.00      7039275.00
      2845774.97      7040975.04
#Sta/Elev= 30
  2140.4  421.99  2217.1  415.44  2447.1  405.28  2530.8  403.98  2642.1  401.66
  2811.6  401.39  2837.1  399.21  2842.0  398.41  2864.6  399.21  3052.8  399.23
  3110.3  401.89  3199.6  403.72  3242.5  405.57  3501.1  421.91  3551.9  428.02
  3664.1  436.30  3749.7  436.09  3835.3  424.90  3910.8  409.05  3925.1  402.63
  3938.9  399.45  3952.2  399.21  6032.9  399.21  6068.4  403.98  6234.2  415.80
  6518.9  431.57  6606.0  431.35  6712.1  425.52  6805.5  430.89  7147.4  436.41
#Mann=10,-1,0
  2140.4    0.05       0  2837.1   0.033       0  2864.6    0.05       0
  3110.3    0.16       0  3199.6    0.12       0  3242.5    0.16       0
  3749.7    0.12       0  3835.3    0.16       0  3952.2    0.05       0
  6032.9    0.16       0
Bank Sta=2530.8,6068.4
Exp/Cntr=0.3,0.1

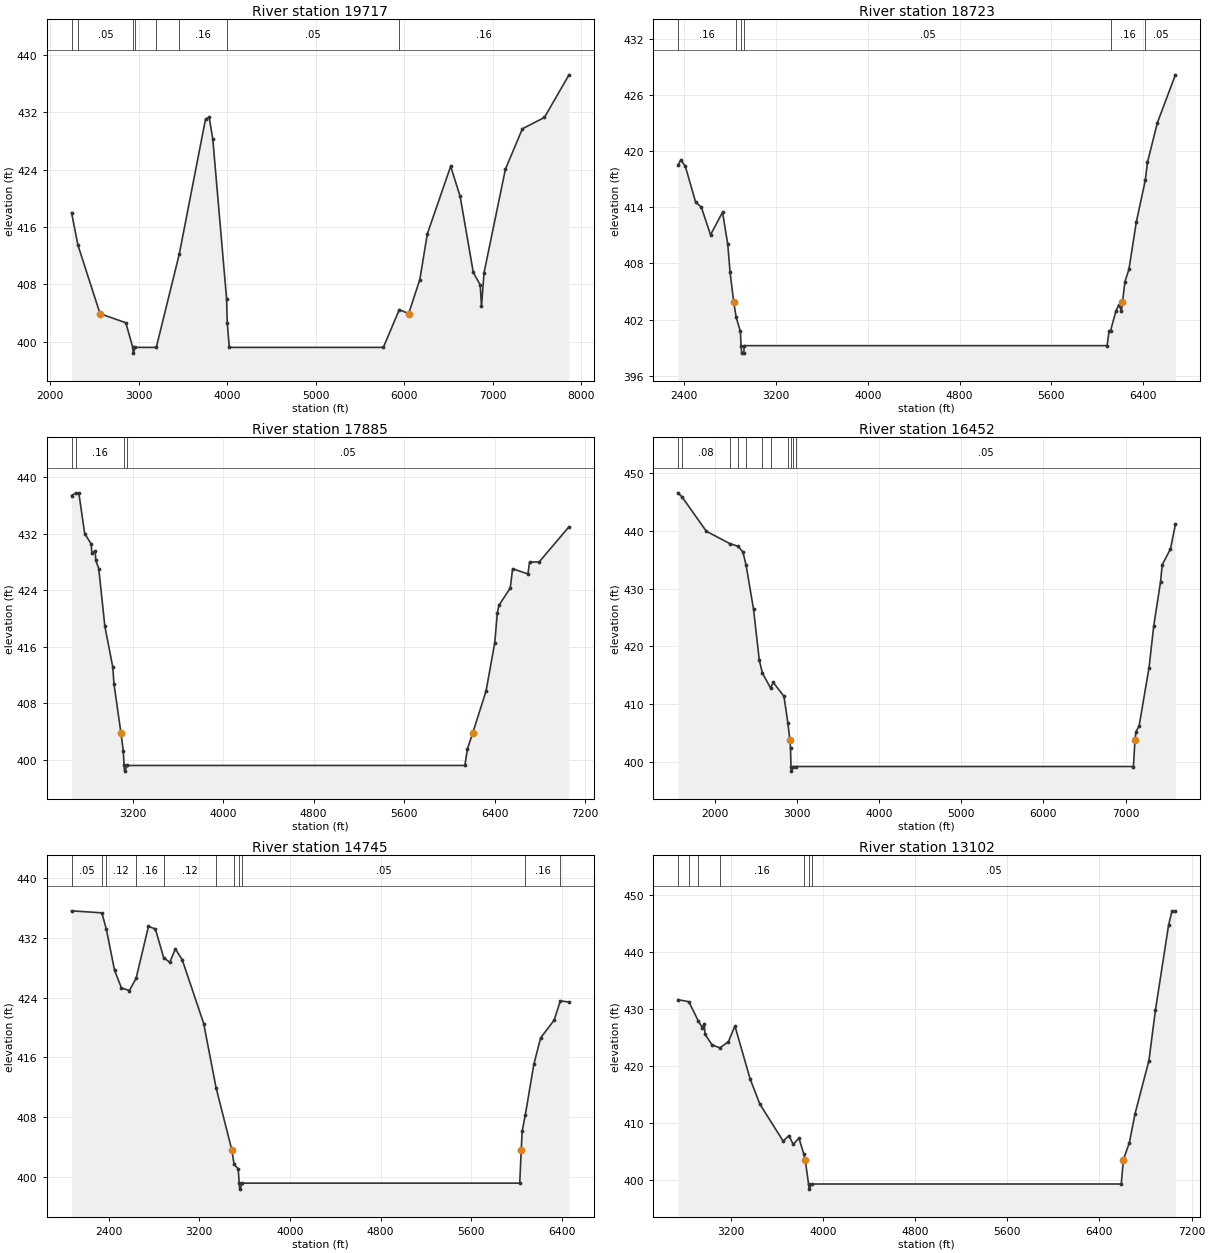
Type RM Length L Ch R = 1,19717,994,994,994
BEGIN DESCRIPTION:
BIRCH CREEK 20.0
END DESCRIPTION:
XS GIS Cut Line= 3
      2849557.83      7037819.52      2846875.00      7038525.00
      2845074.98      7040725.02
#Sta/Elev= 30
  2243.7  418.00  2316.1  413.46  2565.4  403.91  2856.7  402.64  2935.2  399.21
  2940.1  398.41  2962.7  399.21  3200.6  399.21  3460.1  412.21  3756.3  431.01
  3797.6  431.30  3839.0  428.19  3994.1  406.01  4002.2  402.59  4025.1  399.21
  5764.3  399.21  5944.8  404.48  6049.8  403.91  6176.3  408.67  6261.0  415.03
  6524.4  424.45  6631.4  420.25  6780.0  409.65  6858.2  407.91  6872.6  404.91
  6901.3  409.62  7142.5  424.04  7334.1  429.68  7583.2  431.26  7860.3  437.20
#Mann=8,-1,0
  2243.7    0.16       0  2316.1    0.05       0  2935.2   0.033       0
  2962.7    0.05       0  3200.6    0.12       0  3460.1    0.16       0
  4002.2    0.05       0  5944.8    0.16       0
Bank Sta=2565.4,6049.8
Exp/Cntr=0.3,0.1

Type RM Length L Ch R = 1,18723,838,838,838
BEGIN DESCRIPTION:
BIRCH CREEK 19.0
END DESCRIPTION:
XS GIS Cut Line= 3
      2849349.06      7037609.58      2846712.37      7037544.47
      2845139.49      7038184.47
#Sta/Elev= 30
  2345.9  418.49  2370.0  419.06  2410.0  418.41  2500.0  414.55  2550.0  414.01
  2630.0  411.06  2734.5  413.48  2780.1  410.05  2800.1  407.06  2832.2  403.85
  2853.7  402.22  2890.1  400.73  2896.1  399.21  2901.1  398.41  2919.1  398.41
  2924.2  399.21  6086.5  399.21  6103.4  400.77  6116.3  400.80  6164.1  402.95
  6188.2  403.55  6211.3  402.96  6220.4  403.85  6241.7  406.05  6276.6  407.37
  6340.9  412.42  6419.0  416.88  6438.0  418.81  6524.4  423.04  6681.5  428.17
#Mann=6,-1,0
  2345.9    0.16       0  2853.7    0.05       0  2896.1   0.033       0
  2924.2    0.05       0  6116.3    0.16       0  6419.0    0.05       0
Bank Sta=2832.2,6220.4
Exp/Cntr=0.3,0.1

Type RM Length L Ch R = 1,17885,1433,1433,1433
BEGIN DESCRIPTION:
BIRCH CREEK 18.0
END DESCRIPTION:
XS GIS Cut Line= 3
      2848687.24      7036144.72      2846451.95      7036741.52
      2844791.91      7038000.11
#Sta/Elev= 30
  2660.0  437.37  2700.2  437.75  2724.4  437.73  2776.2  431.99  2834.3  430.51
  2839.5  429.23  2869.2  429.53  2874.4  428.21  2900.4  427.05  2954.6  418.88
  3024.4  413.13  3034.9  410.78  3096.8  403.80  3117.7  401.25  3124.3  399.21
  3129.3  398.41  3152.6  399.21  6136.8  399.21  6159.2  401.56  6206.1  403.80
  6323.6  409.72  6400.6  416.53  6423.4  420.74  6438.0  421.86  6537.8  424.28
  6558.6  427.02  6693.9  426.28  6708.4  427.95  6793.7  427.99  7056.8  432.95
#Mann=4,-1,0
  2660.0    0.05       0  2700.2    0.16       0  3124.3   0.033       0
  3152.6    0.05       0
Bank Sta=3096.8,6206.1
Exp/Cntr=0.3,0.1

Type RM Length L Ch R = 1,16452,1707,1707,1707
BEGIN DESCRIPTION:
BIRCH CREEK 16.0
END DESCRIPTION:
XS GIS Cut Line= 3
      2849024.99      7035575.00      2845575.00      7035625.00
      2842974.97      7035775.00
#Sta/Elev= 30
  1551.2  446.57  1601.8  445.85  1896.2  439.93  2183.0  437.78  2282.1  437.32
  2341.3  436.35  2381.2  434.03  2471.3  426.41  2541.3  417.62  2579.4  415.37
  2678.5  412.80  2711.3  413.76  2841.3  411.36  2888.6  406.81  2914.1  403.74
  2921.3  402.37  2927.2  399.21  2932.2  398.41  2955.5  399.21  2993.3  399.21
  7095.0  399.21  7114.1  403.74  7125.1  405.18  7165.1  406.28  7285.3  416.34
  7342.9  423.59  7425.6  431.21  7445.6  434.12  7545.8  436.85  7605.9  441.09
#Mann=11,-1,0
  1551.2    0.05       0  1601.8    0.08       0  2183.0    0.05       0
  2282.1    0.08       0  2381.2    0.05       0  2579.4    0.08       0
  2678.5    0.05       0  2888.6    0.16       0  2927.2   0.033       0
  2955.5    0.16       0  2993.3    0.05       0
Bank Sta=2914.1,7114.1
Exp/Cntr=0.3,0.1

Type RM Length L Ch R = 1,14745,1643,1643,1643
BEGIN DESCRIPTION:
BIRCH CREEK 15.0
END DESCRIPTION:
XS GIS Cut Line= 3
      2847308.92      7033898.53      2844433.72      7034376.07
      2843142.50      7035092.21
#Sta/Elev= 30
  2071.8  435.60  2339.4  435.33  2379.5  433.11  2451.4  427.66  2512.4  425.29
  2582.6  424.95  2641.8  426.58  2751.0  433.53  2811.9  433.17  2884.7  429.36
  2938.9  428.71  2988.1  430.51  3048.9  429.06  3238.4  420.54  3347.4  411.98
  3486.4  403.65  3507.2  401.72  3543.1  401.12  3551.7  399.21  3556.8  398.41
  3580.1  399.21  6028.3  399.21  6041.4  403.65  6050.0  406.20  6077.4  408.32
  6153.0  415.10  6212.6  418.62  6331.6  420.98  6386.9  423.57  6462.9  423.41
#Mann=11,-1,0
  2071.8    0.05       0  2339.4    0.16       0  2379.5    0.12       0
  2641.8    0.16       0  2884.7    0.12       0  3347.4    0.16       0
  3507.2    0.05       0  3551.7   0.033       0  3580.1    0.05       0
  6077.4    0.16       0  6386.9    0.05       0
Bank Sta=3486.4,6041.4
Exp/Cntr=0.3,0.1

Type RM Length L Ch R = 1,13102,1102,1102,1102
BEGIN DESCRIPTION:
BIRCH CREEK 14.0
END DESCRIPTION:
XS GIS Cut Line= 3
      2846163.07      7032051.31      2844025.00      7032825.00
      2841985.79      7032906.89
#Sta/Elev= 30
  2743.9  431.61  2838.4  431.25  2919.2  427.92  2954.5  426.70  2972.8  427.35
  2978.1  425.56  3039.6  423.66  3108.4  423.14  3182.0  424.23  3238.0  426.99
  3369.3  417.72  3454.4  413.25  3656.4  406.75  3707.1  407.72  3743.0  406.18
  3793.7  407.25  3835.3  404.49  3847.6  403.50  3876.6  399.21  3881.8  398.31
  3905.2  399.21  6588.9  399.21  6607.6  403.50  6659.0  406.45  6709.0  411.60
  6829.1  420.91  6885.5  429.78  6999.2  444.67  7029.3  447.22  7058.5  447.18
#Mann=7,-1,0
  2743.9    0.05       0  2838.4    0.16       0  2919.2    0.05       0
  3108.4    0.16       0  3835.3    0.05       0  3876.6   0.033       0
  3905.2    0.05       0
Bank Sta=3847.6,6607.6
Exp/Cntr=0.3,0.1

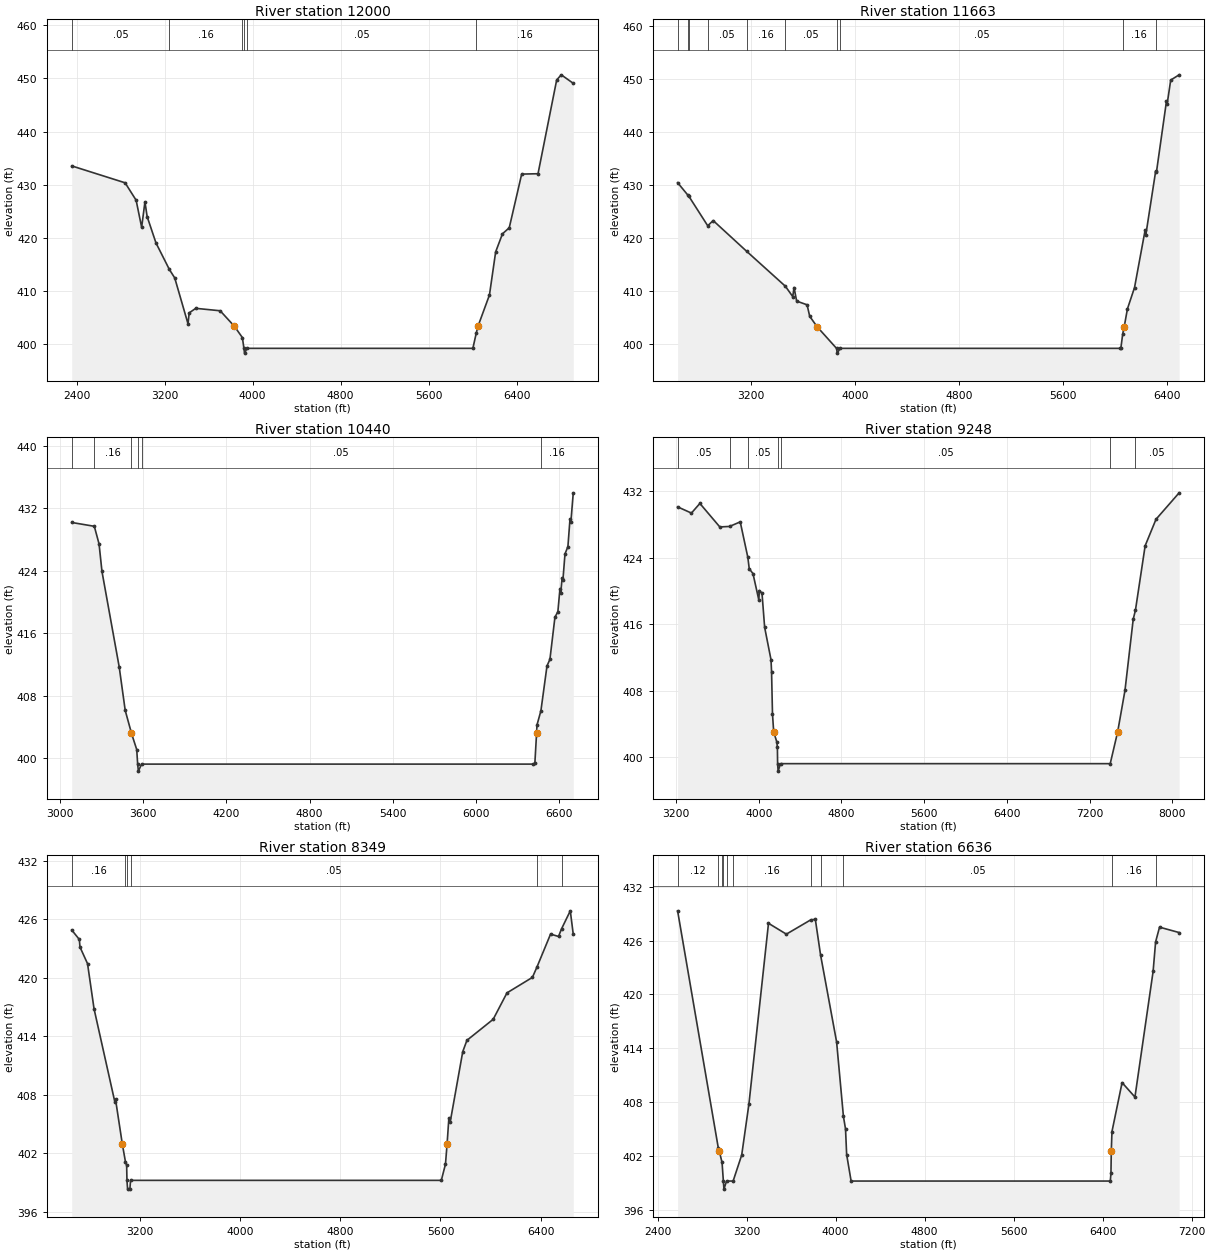
Type RM Length L Ch R = 1,12000,337,337,337
BEGIN DESCRIPTION:
BIRCH CREEK 13.0
END DESCRIPTION:
XS GIS Cut Line= 5
      2846699.34      7031474.59      2845857.33      7031526.68
      2844069.14      7031717.65      2843036.15      7031769.73
      2842202.85      7032064.86
#Sta/Elev= 30
  2355.8  433.54  2841.1  430.36  2941.3  427.08  2991.4  421.99  3021.4  426.77
  3041.4  424.01  3121.6  419.05  3243.3  414.06  3292.3  412.46  3413.0  403.83
  3423.5  405.88  3483.4  406.74  3705.6  406.28  3834.8  403.36  3907.3  401.24
  3921.6  399.21  3926.8  398.31  3950.2  399.21  6003.2  399.21  6033.6  402.04
  6049.7  403.36  6154.0  409.25  6210.5  417.37  6272.3  420.76  6334.0  421.90
  6447.0  432.00  6595.6  432.07  6765.3  449.72  6807.1  450.68  6916.1  449.08
#Mann=6,-1,0
  2355.8    0.05       0  3243.3    0.16       0  3907.3    0.05       0
  3921.6   0.033       0  3950.2    0.05       0  6033.6    0.16       0
Bank Sta=3834.8,6049.7
Exp/Cntr=0.3,0.1

Type RM Length L Ch R = 1,11663,1223,1223,1223
BEGIN DESCRIPTION:
BIRCH CREEK 12.0
END DESCRIPTION:
XS GIS Cut Line= 3
      2846447.58      7031222.86      2844112.54      7031379.11
      2842610.83      7031561.40
#Sta/Elev= 30
  2637.3  430.42  2715.9  428.08  2722.9  427.89  2868.7  422.30  2910.5  423.28
  3166.9  417.51  3465.2  410.91  3521.9  408.96  3531.9  410.67  3551.9  408.11
  3632.1  407.41  3652.1  405.25  3708.4  403.30  3858.3  399.21  3863.5  398.31
  3886.9  399.21  6032.8  399.21  6042.9  399.28  6057.1  401.95  6068.6  403.30
  6093.2  406.65  6147.7  410.66  6229.5  421.52  6234.5  420.60  6310.4  432.63
  6316.3  432.45  6393.1  445.75  6398.1  445.20  6425.7  449.74  6490.3  450.73
#Mann=10,-1,0
  2637.3    0.16       0  2715.9    0.05       0  2722.9    0.16       0
  2868.7    0.05       0  3166.9    0.16       0  3465.2    0.05       0
  3858.3   0.033       0  3886.9    0.05       0  6057.1    0.16       0
  6310.4    0.05       0
Bank Sta=3708.4,6068.6
Exp/Cntr=0.3,0.1

Type RM Length L Ch R = 1,10440,1192,1192,1192
BEGIN DESCRIPTION:
BIRCH CREEK 10.0
END DESCRIPTION:
XS GIS Cut Line= 3
      2846013.59      7029599.59      2844208.03      7030146.47
      2842759.19      7031092.11
#Sta/Elev= 30
  3084.7  430.18  3247.5  429.69  3281.7  427.43  3302.6  423.91  3426.9  411.67
  3470.3  406.09  3515.0  403.20  3515.6  403.15  3553.4  401.07  3560.0  399.21
  3565.2  398.31  3588.6  399.21  6409.3  399.21  6424.4  399.30  6436.8  403.15
  6439.6  404.21  6468.1  406.05  6512.0  411.80  6533.1  412.64  6569.3  418.05
  6590.4  418.74  6605.5  421.70  6611.4  421.18  6620.6  423.02  6626.6  422.75
  6641.7  426.15  6662.8  427.09  6677.9  430.63  6683.9  430.19  6701.4  433.98
#Mann=6,-1,0
  3084.7    0.05       0  3247.5    0.16       0  3515.0    0.05       0
  3560.0   0.033       0  3588.6    0.05       0  6468.1    0.16       0
Bank Sta=3515.6,6436.8
Exp/Cntr=0.3,0.1

Type RM Length L Ch R = 1,9248,899,899,899
BEGIN DESCRIPTION:
Mapping XS c9c6aaf6
END DESCRIPTION:
XS GIS Cut Line= 3
      2846039.58      7029573.54      2844381.64      7028983.27
      2841291.32      7028957.23
#Sta/Elev= 30
  3215.0  430.15  3348.7  429.40  3430.5  430.56  3623.2  427.73  3717.4  427.79
  3820.7  428.34  3894.2  424.07  3907.9  422.69  3944.0  422.11  4000.4  418.94
  4005.7  420.06  4031.2  419.76  4056.7  415.64  4118.4  411.73  4123.7  410.27
  4132.7  405.19  4144.4  403.03  4174.8  401.81  4180.1  401.16  4182.1  399.21
  4187.3  398.31  4210.7  399.21  7398.9  399.21  7470.7  403.03  7541.6  408.03
  7621.6  416.63  7642.8  417.69  7736.7  425.46  7841.6  428.65  8065.3  431.84
#Mann=7,-1,0
  3215.0    0.05       0  3717.4    0.16       0  3894.2    0.05       0
  4182.1   0.033       0  4210.7    0.05       0  7398.9    0.16       0
  7642.8    0.05       0
Bank Sta=4144.4,7470.7
Exp/Cntr=0.3,0.1

Type RM Length L Ch R = 1,8349,1713,1713,1713
BEGIN DESCRIPTION:
Mapping XS 2c461107
END DESCRIPTION:
XS GIS Cut Line= 3
      2846786.10      7028757.57      2844668.10      7028141.26
      2842942.21      7027629.56
#Sta/Elev= 30
  2654.9  424.90  2715.6  423.93  2720.8  423.15  2781.0  421.45  2833.1  416.81
  2999.3  407.25  3004.5  407.53  3059.1  402.92  3084.0  401.11  3093.5  400.77
  3095.9  399.21  3101.1  398.31  3119.4  398.31  3124.6  399.21  5606.9  399.21
  5640.1  400.87  5653.0  402.92  5667.1  405.57  5678.5  405.24  5778.2  412.42
  5811.5  413.58  6021.3  415.74  6131.5  418.45  6334.6  420.04  6372.2  421.14
  6479.5  424.48  6543.3  424.24  6567.3  425.02  6637.1  426.87  6660.9  424.46
#Mann=6,-1,0
  2654.9    0.16       0  3084.0    0.05       0  3095.9   0.033       0
  3124.6    0.05       0  6372.2    0.08       0  6567.3    0.05       0
Bank Sta=3059.1,5653
Exp/Cntr=0.3,0.1

Type RM Length L Ch R = 1,6636,1513,1513,1513
BEGIN DESCRIPTION:
Mapping XS 5a6431e9
END DESCRIPTION:
XS GIS Cut Line= 3
      2847029.22      7026196.81      2844633.37      7026396.47
      2842638.45      7027064.33
#Sta/Elev= 30
  2579.1  429.32  2944.9  402.90  2953.1  402.57  2978.7  401.28  2990.4  399.21
  2995.6  398.31  3019.2  399.21  3078.2  399.21  3155.3  402.11  3220.0  407.77
  3396.1  427.93  3556.7  426.72  3775.3  428.31  3817.1  428.37  3864.0  424.41
  4008.3  414.71  4069.6  406.41  4088.5  405.01  4098.6  402.16  4138.7  399.21
  6468.5  399.21  6474.3  400.08  6477.3  402.57  6483.5  404.73  6574.3  410.18
  6689.9  408.57  6853.1  422.56  6875.6  425.86  6911.0  427.50  7087.0  426.90
#Mann=11,-1,0
  2579.1    0.12       0  2944.9    0.16       0  2978.7    0.05       0
  2990.4   0.033       0  3019.2    0.05       0  3078.2    0.16       0
  3775.3    0.05       0  3864.0    0.16       0  4069.6    0.05       0
  6483.5    0.16       0  6875.6    0.05       0
Bank Sta=2953.1,6477.3
Exp/Cntr=0.3,0.1

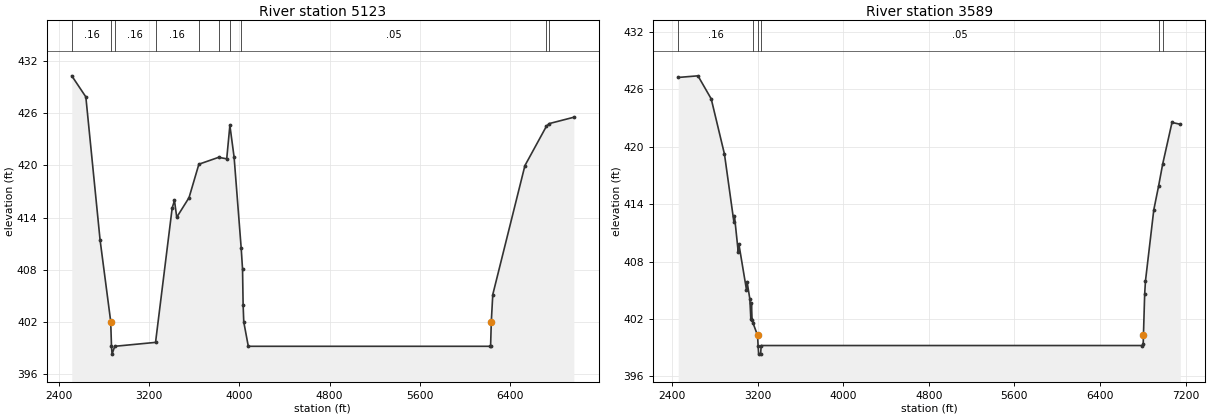
Type RM Length L Ch R = 1,5123,1534,1534,1534
BEGIN DESCRIPTION:
Mapping XS 0296918e
END DESCRIPTION:
XS GIS Cut Line= 3
      2846768.82      7024608.27      2844312.19      7024920.77
      2842463.20      7025623.91
#Sta/Elev= 30
  2511.9  430.30  2636.7  427.88  2763.0  411.44  2857.4  402.06  2864.3  399.21
  2869.5  398.31  2893.1  399.21  3255.2  399.66  3402.8  415.11  3423.0  415.97
  3443.2  414.04  3552.4  416.30  3639.6  420.14  3814.6  420.93  3886.7  420.76
  3914.7  424.60  3952.1  420.96  4014.8  410.54  4027.0  408.09  4032.1  404.01
  4037.9  402.01  4078.2  399.21  6222.5  399.21  6227.9  399.23  6234.2  402.06
  6247.3  405.16  6532.4  419.98  6723.8  424.52  6748.1  424.81  6966.5  425.54
#Mann=10,-1,0
  2511.9    0.16       0  2864.3   0.033       0  2893.1    0.16       0
  3255.2    0.16       0  3639.6     0.1       0  3814.6    0.05       0
  3914.7    0.16       0  4014.8    0.05       0  6723.8    0.16       0
  6748.1    0.05       0
Bank Sta=2857.4,6234.2
Exp/Cntr=0.3,0.1

Type RM Length L Ch R = 1,3589,0,0,0
BEGIN DESCRIPTION:
BIRCH CREEK 3.0
END DESCRIPTION:
XS GIS Cut Line= 3
      2846393.74      7022772.06      2843997.96      7023379.69
      2842489.50      7025009.51
#Sta/Elev= 30
  2458.1  427.26  2642.5  427.43  2766.3  425.02  2890.1  419.24  2978.2  412.15
  2983.3  412.80  3019.1  408.98  3024.3  409.86  3095.9  405.05  3101.1  405.90
  3127.4  404.08  3136.9  401.94  3142.0  403.70  3148.0  401.91  3155.8  401.60
  3199.3  400.28  3204.4  399.21  3209.6  398.31  3228.0  398.31  3233.2  399.21
  6796.7  399.21  6803.7  399.40  6805.9  400.28  6817.6  404.64  6825.0  405.98
  6902.7  413.41  6947.4  415.89  6985.6  418.19  7072.8  422.55  7150.5  422.36
#Mann=6,-1,0
  2458.1    0.16       0  3155.8    0.05       0  3204.4   0.033       0
  3233.2    0.05       0  6947.4    0.16       0  6985.6    0.05       0
Bank Sta=3199.3,6805.9
Exp/Cntr=0.3,0.1

Chan Stop Cuts=-1