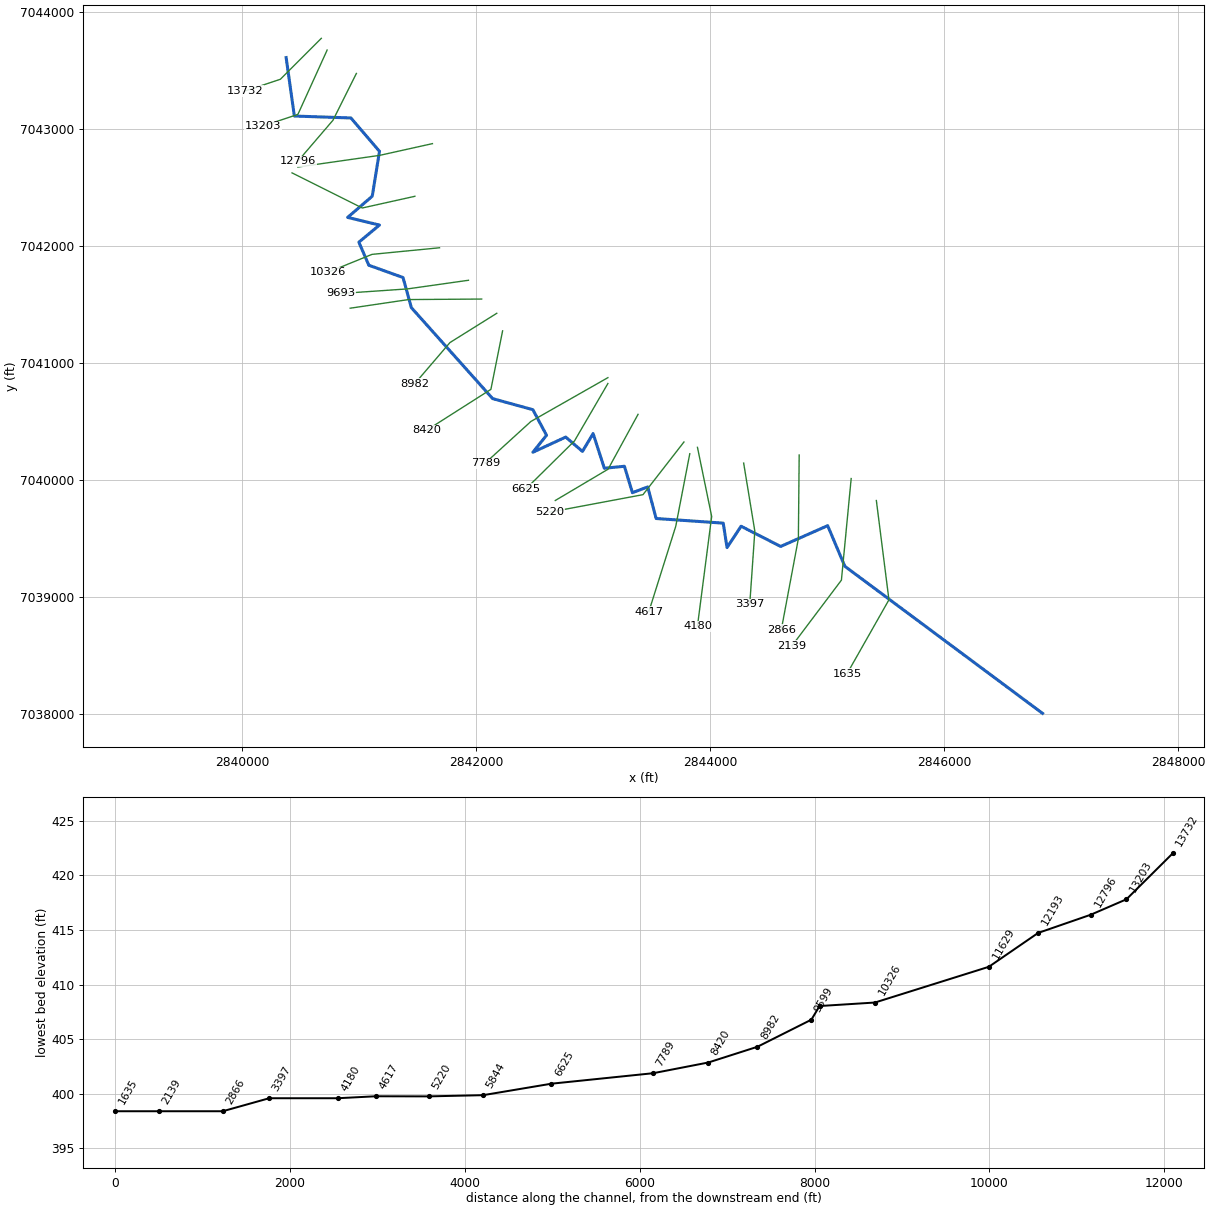
--- BRIER BRANCH.prj (project) ---

Proj Title=BRIER BRANCH Base Level Engineering
Current Plan=p01
Default Exp/Contr=0.3,0.1
English Units
Geom File=g01
Flow File=f01
Plan File=p01
BEGIN DESCRIPTION:
BRIER BRANCH
END DESCRIPTION:

--- BRIER BRANCH.p01 (plan) ---

Plan Title=Multiple Run
Short Identifier=Multiple
Geom File=g01
Flow File=f01
Subcritical Flow
K Sum by GR= 0
Std Step Tol= 0.01
Critical Tol= 0.01
Num of Std Step Trials= 20
Max Error Tol= 0.3
Flow Tol Ratio= 0.001
Split Flow NTrial= 30
Split Flow Tol= 0.02
Split Flow Ratio= 0.02
Log Output Level= 0
Friction Slope Method= 1
Unsteady Friction Slope Method= 2
Unsteady Bridges Friction Slope Method= 1
Parabolic Critical Depth
Global Vel Dist=  1 , 1 , 1
Global Log Level= 0
CheckData=True
Encroach Param= -1, 0, 0, 0
BEGIN DESCRIPTION:
Multiple Run
END DESCRIPTION:

--- BRIER BRANCH.f01 (steady flow) ---

Flow Title=Multiple
Number of Profiles=7
Profile Names=10-year,25-year,50-year,1pct_min,100-year,1pct_plu,500-year
River Rch & RM= BRIER BRANCH,Reach-1,13732
     507     670     800     475     948    1892    1334
River Rch & RM= BRIER BRANCH,Reach-1,12193
     776    1048    1271     765    1527    3046    2207
River Rch & RM= BRIER BRANCH,Reach-1,7789
     848    1150    1397     842    1680    3352    2435
River Rch & RM= BRIER BRANCH,Reach-1,2139
     961    1309    1594     963    1922    3835    2799
Boundary for River Rch & Prof#=BRIER BRANCH,Reach-1,1
Up Type=0
Dn Type=3
Dn Slope=0.005
Boundary for River Rch & Prof#=BRIER BRANCH,Reach-1,2
Up Type=0
Dn Type=3
Dn Slope=0.005
Boundary for River Rch & Prof#=BRIER BRANCH,Reach-1,3
Up Type=0
Dn Type=3
Dn Slope=0.005
Boundary for River Rch & Prof#=BRIER BRANCH,Reach-1,4
Up Type=0
Dn Type=3
Dn Slope=0.005
Boundary for River Rch & Prof#=BRIER BRANCH,Reach-1,5
Up Type=0
Dn Type=3
Dn Slope=0.005
Boundary for River Rch & Prof#=BRIER BRANCH,Reach-1,6
Up Type=0
Dn Type=3
Dn Slope=0.005
Boundary for River Rch & Prof#=BRIER BRANCH,Reach-1,7
Up Type=0
Dn Type=3
Dn Slope=0.005

--- BRIER BRANCH.g01 (geometry) ---

Geom Title=Existing Conditions

River Reach=BRIER BRANCH,Reach-1
Reach XY= 30
      2840374.48      7043610.70      2840444.68      7043110.95
      2840928.26      7043094.45      2841172.53      7042809.12
      2841110.54      7042425.60      2840900.24      7042244.55
      2841172.52      7042179.09      2840996.34      7042032.86
      2841081.30      7041835.79      2841373.77      7041730.64
      2841444.78      7041473.46      2842139.54      7040695.91
      2842483.91      7040601.11      2842600.31      7040382.73
      2842483.91      7040237.54      2842764.70      7040367.13
      2842907.49      7040244.74      2842998.68      7040397.13
      2843094.67      7040100.75      2843266.26      7040117.55
      2843334.66      7039891.96      2843465.45      7039941.16
      2843537.44      7039671.18      2844111.01      7039631.58
      2844143.41      7039422.79      2844263.40      7039605.18
      2844601.78      7039432.39      2845003.75      7039609.98
      2845150.29      7039263.14      2846840.68      7038005.74

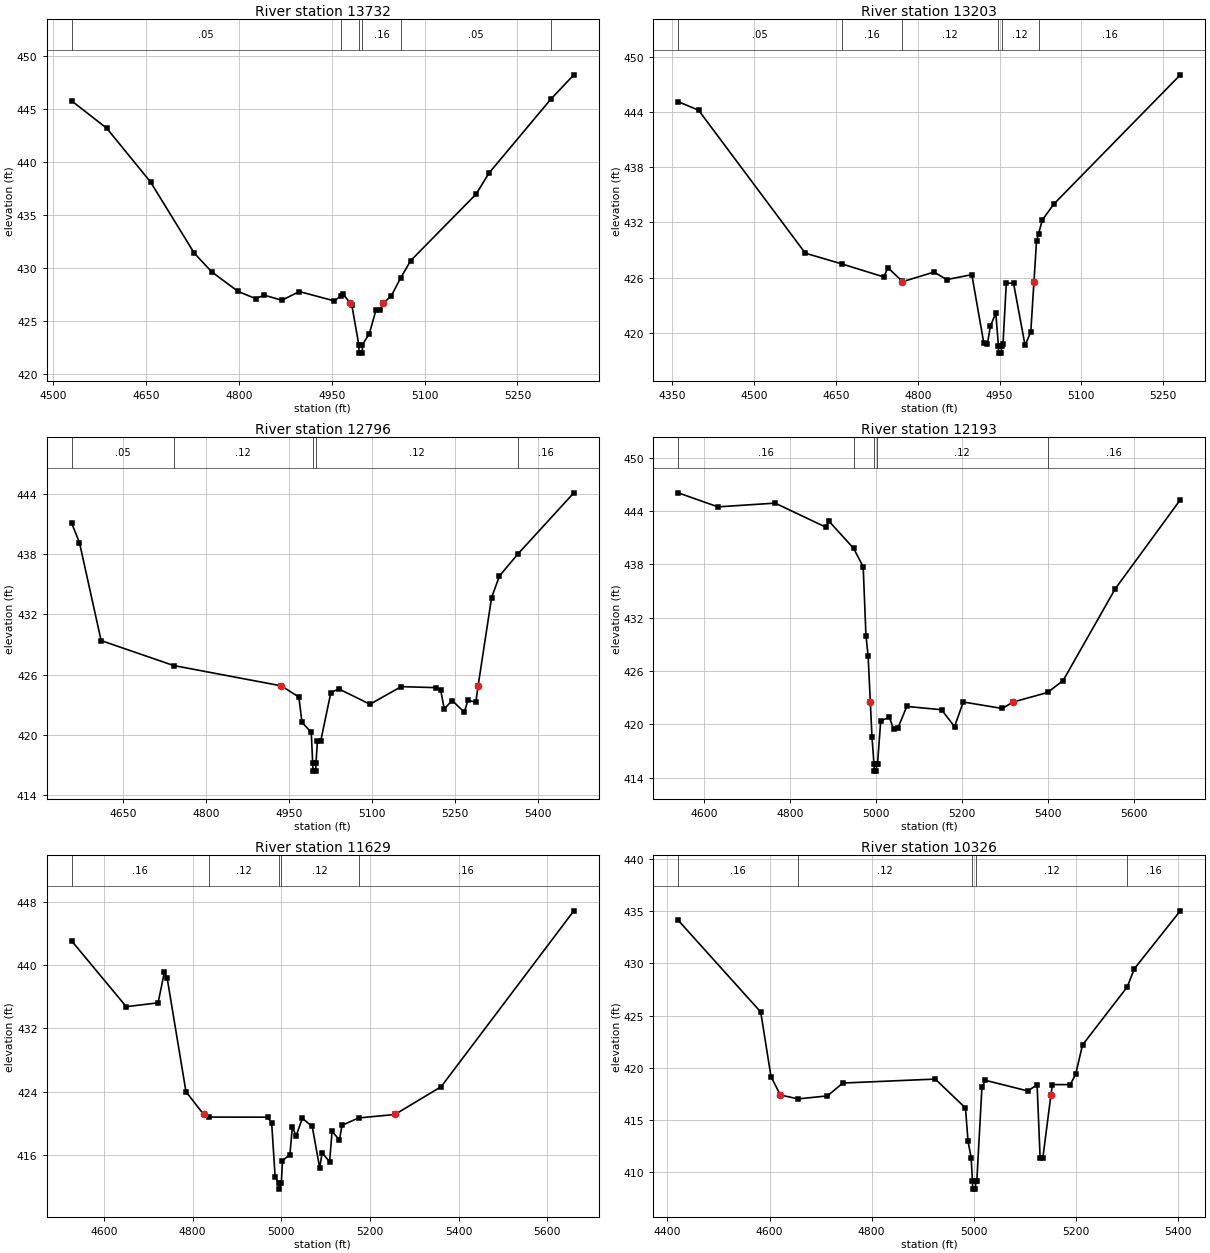
Type RM Length L Ch R = 1,13732,529,529,529
BEGIN DESCRIPTION:
BRIER BRANCH 15.0
END DESCRIPTION:
XS GIS Cut Line= 3
      2840675.00      7043775.00      2840325.00      7043425.00
      2840025.00      7043325.00
#Sta/Elev= 30
  4530.0  445.77  4586.6  443.19  4657.3  438.13  4728.0  431.42  4756.3  429.66
  4798.7  427.82  4827.0  427.15  4841.1  427.47  4869.4  426.99  4897.7  427.81
  4954.3  426.93  4964.2  427.39  4968.4  427.58  4980.0  426.72  4982.5  426.53
  4993.7  422.81  4994.2  422.01  4999.2  422.01  4999.7  422.81  5010.8  423.85
  5021.4  426.05  5027.6  426.05  5033.3  426.72  5046.1  427.39  5061.7  429.13
  5077.7  430.73  5183.1  436.98  5204.2  438.98  5304.5  445.97  5341.2  448.23
#Mann=6,-1,0
  4530.0    0.05       0  4964.2    0.16       0  4993.7    0.07       0
  4999.7    0.16       0  5061.7    0.05       0  5304.5    0.16       0
Bank Sta=4980,5033.3
Exp/Cntr=0.3,0.1

Type RM Length L Ch R = 1,13203,407,407,407
BEGIN DESCRIPTION:
BRIER BRANCH 14.0
END DESCRIPTION:
XS GIS Cut Line= 3
      2840724.99      7043674.98      2840475.00      7043125.00
      2840174.96      7043024.99
#Sta/Elev= 30
  4360.9  445.10  4398.2  444.18  4593.8  428.66  4661.6  427.48  4737.7  426.08
  4745.3  427.09  4770.2  425.68  4771.9  425.56  4829.9  426.61  4853.0  425.79
  4899.1  426.33  4921.1  418.89  4927.7  418.82  4933.2  420.75  4943.1  422.16
  4947.8  418.61  4948.3  417.81  4953.3  417.81  4953.8  418.61  4956.2  418.75
  4962.3  425.41  4975.6  425.40  4996.7  418.65  5007.2  420.12  5013.0  425.56
  5017.7  429.95  5021.4  430.76  5028.3  432.26  5049.4  433.99  5281.3  448.02
#Mann=6,-1,0
  4360.9    0.05       0  4661.6    0.16       0  4770.2    0.12       0
  4947.8    0.07       0  4953.8    0.12       0  5021.4    0.16       0
Bank Sta=4771.9,5013
Exp/Cntr=0.3,0.1

Type RM Length L Ch R = 1,12796,603,603,603
BEGIN DESCRIPTION:
BRIER BRANCH 13.0
END DESCRIPTION:
XS GIS Cut Line= 3
      2840974.99      7043474.97      2840775.00      7043075.00
      2840474.97      7042724.97
#Sta/Elev= 30
  4557.2  441.03  4571.1  439.12  4610.3  429.38  4741.4  426.90  4936.1  424.88
  4968.0  423.77  4973.6  421.25  4990.4  420.26  4993.0  417.20  4993.5  416.40
  4998.5  416.40  4999.0  417.20  5001.6  419.44  5007.7  419.44  5025.8  424.20
  5040.1  424.58  5096.6  423.05  5153.1  424.80  5216.8  424.70  5224.4  424.48
  5231.0  422.59  5245.3  423.42  5267.2  422.26  5273.8  423.44  5288.1  423.25
  5292.2  424.88  5316.6  433.65  5330.9  435.81  5363.9  437.97  5465.4  444.07
#Mann=5,-1,0
  4557.2    0.05       0  4741.4    0.12       0  4993.0    0.07       0
  4999.0    0.12       0  5363.9    0.16       0
Bank Sta=4936.1,5292.2
Exp/Cntr=0.3,0.1

Type RM Length L Ch R = 1,12193,564,564,564
BEGIN DESCRIPTION:
BRIER BRANCH 12.0
END DESCRIPTION:
XS GIS Cut Line= 3
      2841625.05      7042875.01      2841175.00      7042775.00
      2840475.03      7042675.00
#Sta/Elev= 30
  4539.5  446.05  4631.7  444.47  4764.9  444.89  4884.0  442.16  4889.1  442.91
  4947.3  439.82  4969.8  437.73  4976.2  429.99  4981.3  427.67  4986.4  422.50
  4990.3  418.54  4994.9  415.53  4995.4  414.73  5000.5  414.73  5001.0  415.53
  5003.1  415.53  5010.6  420.41  5030.8  420.77  5040.9  419.42  5051.0  419.63
  5071.2  422.01  5152.0  421.64  5182.4  419.74  5202.6  422.51  5293.5  421.78
  5318.3  422.50  5398.7  423.58  5434.9  424.92  5556.1  435.24  5707.6  445.27
#Mann=5,-1,0
  4539.5    0.16       0  4947.3    0.12       0  4994.9    0.07       0
  5001.0    0.12       0  5398.7    0.16       0
Bank Sta=4986.4,5318.3
Exp/Cntr=0.3,0.1

Type RM Length L Ch R = 1,11629,1303,1303,1303
BEGIN DESCRIPTION:
BRIER BRANCH 11.0
END DESCRIPTION:
XS GIS Cut Line= 3
      2841475.00      7042425.00      2841025.00      7042325.00
      2840425.00      7042625.00
#Sta/Elev= 30
  4527.8  443.07  4650.7  434.75  4722.4  435.24  4736.5  439.10  4742.9  438.35
  4785.2  423.99  4825.2  421.09  4836.6  420.76  4969.6  420.75  4978.5  419.96
  4986.2  413.18  4994.1  412.43  4994.6  411.63  5000.2  412.43  5002.8  415.24
  5019.5  416.00  5025.1  419.54  5033.5  418.36  5047.5  420.60  5069.8  419.59
  5086.6  414.34  5092.2  416.22  5109.0  415.11  5114.6  418.96  5131.3  417.85
  5136.9  419.72  5174.4  420.65  5256.2  421.09  5360.5  424.61  5659.6  446.90
#Mann=5,-1,0
  4527.8    0.16       0  4836.6    0.12       0  4994.1    0.07       0
  5000.2    0.12       0  5174.4    0.16       0
Bank Sta=4825.2,5256.2
Exp/Cntr=0.3,0.1

Type RM Length L Ch R = 1,10326,633,633,633
BEGIN DESCRIPTION:
Mapping XS cc1d0124
END DESCRIPTION:
XS GIS Cut Line= 3
      2841685.76      7041985.10      2841108.52      7041928.68
      2840735.24      7041776.76
#Sta/Elev= 30
  4421.3  434.13  4582.8  425.34  4602.9  419.15  4621.1  417.39  4655.8  417.01
  4713.4  417.30  4743.6  418.53  4924.5  418.91  4983.7  416.14  4988.7  412.93
  4994.8  411.39  4997.3  409.16  4997.8  408.36  5003.3  408.36  5003.8  409.16
  5005.9  409.16  5015.9  418.12  5022.8  418.79  5105.8  417.77  5123.9  418.37
  5129.8  411.39  5135.2  411.37  5151.0  417.39  5153.9  418.38  5188.8  418.38
  5199.4  419.37  5212.8  422.18  5300.3  427.74  5314.5  429.50  5404.3  435.04
#Mann=5,-1,0
  4421.3    0.16       0  4655.8    0.12       0  4997.3    0.07       0
  5003.8    0.12       0  5300.3    0.16       0
Bank Sta=4621.1,5151
Exp/Cntr=0.3,0.1

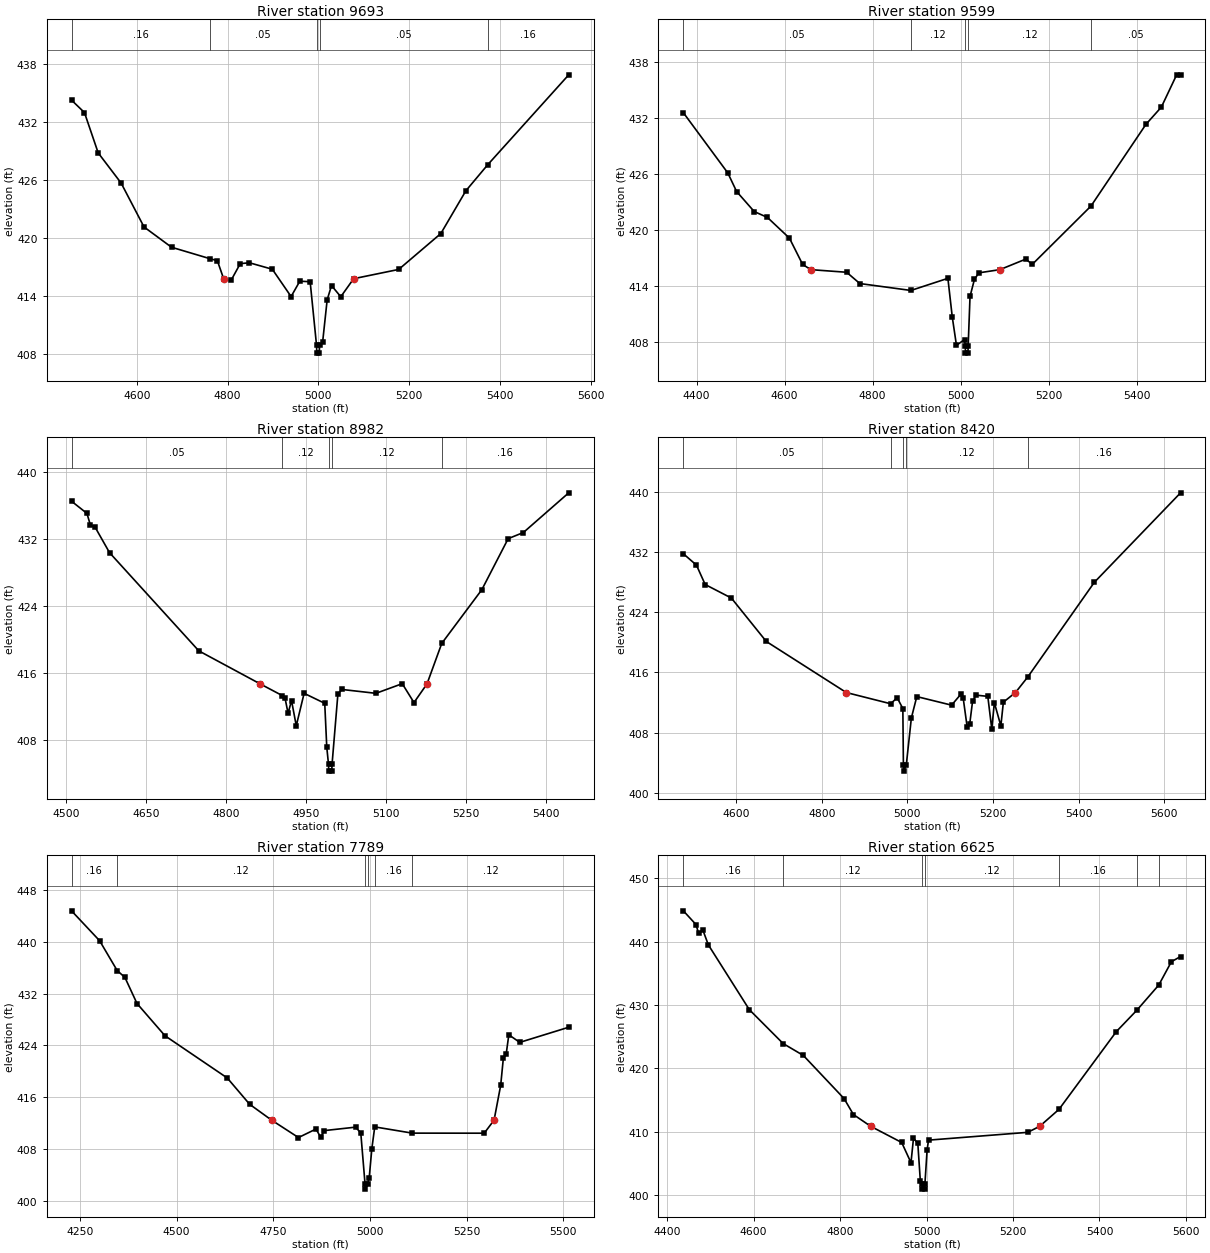
Type RM Length L Ch R = 1,9693,94,94,94
BEGIN DESCRIPTION:
BRIER BRANCH 9.0
END DESCRIPTION:
XS GIS Cut Line= 3
      2841933.19      7041707.32      2841412.34      7041633.54
      2840843.73      7041594.47
#Sta/Elev= 30
  4455.9  434.25  4484.4  432.96  4514.7  428.78  4565.2  425.66  4615.7  421.11
  4676.3  419.01  4761.3  417.82  4777.3  417.62  4791.2  415.75  4807.6  415.58
  4827.8  417.31  4848.0  417.40  4898.5  416.73  4939.9  413.90  4959.1  415.49
  4981.9  415.44  4996.0  408.84  4996.5  408.04  5002.1  408.04  5002.6  408.84
  5009.4  409.18  5019.4  413.56  5029.0  415.04  5049.4  413.88  5077.8  415.75
  5177.1  416.71  5270.0  420.43  5325.2  424.86  5373.6  427.57  5551.9  436.87
#Mann=5,-1,0
  4455.9    0.16       0  4761.3    0.05       0  4996.0    0.04       0
  5002.6    0.05       0  5373.6    0.16       0
Bank Sta=4791.2,5077.8
Exp/Cntr=0.3,0.1

Type RM Length L Ch R = 1,9599,617,617,617
BEGIN DESCRIPTION:
Mapping XS 5b50ea44
END DESCRIPTION:
XS GIS Cut Line= 3
      2842046.02      7041546.73      2841421.02      7041542.39
      2840921.86      7041468.60
#Sta/Elev= 30
  4370.0  432.57  4471.0  426.11  4491.0  424.12  4531.0  421.97  4561.0  421.34
  4611.0  419.12  4641.0  416.30  4659.7  415.74  4741.0  415.46  4771.0  414.25
  4887.0  413.51  4971.0  414.81  4981.0  410.65  4990.5  407.62  5008.8  408.25
  5010.5  407.59  5011.0  406.79  5016.6  406.79  5017.1  407.59  5021.3  412.87
  5031.4  414.71  5041.5  415.40  5089.1  415.74  5147.9  416.87  5162.8  416.31
  5296.1  422.56  5421.1  431.33  5456.0  433.17  5490.7  436.63  5499.6  436.57
#Mann=5,-1,0
  4370.0    0.05       0  4887.0    0.12       0  5010.5    0.07       0
  5017.1    0.12       0  5296.1    0.05       0
Bank Sta=4659.7,5089.1
Exp/Cntr=0.3,0.1

Type RM Length L Ch R = 1,8982,562,562,562
BEGIN DESCRIPTION:
BRIER BRANCH 8.0
END DESCRIPTION:
XS GIS Cut Line= 3
      2842174.99      7041425.00      2841775.00      7041175.00
      2841474.98      7040824.98
#Sta/Elev= 30
  4509.6  436.47  4538.5  435.02  4545.0  433.62  4553.8  433.38  4580.9  430.34
  4748.4  418.64  4863.6  414.70  4905.3  413.30  4909.9  413.08  4915.8  411.20
  4922.3  412.71  4931.2  409.72  4945.9  413.58  4984.6  412.39  4988.4  407.16
  4991.7  405.11  4992.2  404.31  4997.8  404.31  4998.3  405.11  5009.3  413.52
  5017.0  414.04  5080.6  413.58  5130.0  414.73  5152.0  412.48  5176.4  414.70
  5204.1  419.53  5279.3  425.93  5328.7  432.01  5357.2  432.74  5442.3  437.47
#Mann=5,-1,0
  4509.6    0.05       0  4905.3    0.12       0  4991.7    0.07       0
  4998.3    0.12       0  5204.1    0.16       0
Bank Sta=4863.6,5176.4
Exp/Cntr=0.3,0.1

Type RM Length L Ch R = 1,8420,631,631,631
BEGIN DESCRIPTION:
BRIER BRANCH 7.0
END DESCRIPTION:
XS GIS Cut Line= 3
      2842225.00      7041275.02      2842125.00      7040775.00
      2841575.03      7040425.02
#Sta/Elev= 30
  4476.5  431.77  4507.1  430.26  4527.5  427.68  4588.7  425.88  4670.3  420.11
  4857.2  413.32  4960.7  411.83  4976.2  412.62  4989.4  411.19  4990.7  403.67
  4991.2  402.87  4997.4  403.67  5009.3  409.94  5022.0  412.78  5103.3  411.64
  5124.4  413.06  5130.4  412.58  5139.7  408.73  5145.6  409.12  5152.4  412.20
  5160.8  412.97  5187.9  412.81  5197.2  408.46  5203.2  411.97  5218.4  408.89
  5224.3  412.04  5252.6  413.32  5281.6  415.41  5436.8  427.97  5638.3  439.87
#Mann=5,-1,0
  4476.5    0.05       0  4960.7    0.12       0  4990.7    0.07       0
  4997.4    0.12       0  5281.6    0.16       0
Bank Sta=4857.2,5252.6
Exp/Cntr=0.3,0.1

Type RM Length L Ch R = 1,7789,1164,1164,1164
BEGIN DESCRIPTION:
BRIER BRANCH 6.0
END DESCRIPTION:
XS GIS Cut Line= 3
      2843124.96      7040874.98      2842467.03      7040500.72
      2842076.38      7040144.81
#Sta/Elev= 30
  4228.6  444.73  4301.3  440.12  4346.6  435.54  4366.6  434.48  4397.9  430.46
  4470.2  425.50  4631.2  419.00  4689.1  414.95  4745.6  412.52  4815.3  409.83
  4860.6  411.14  4872.8  409.87  4882.2  410.90  4962.9  411.43  4976.4  410.54
  4987.4  402.69  4987.9  401.89  4994.3  402.69  4998.2  403.66  5005.0  408.13
  5012.5  411.47  5109.4  410.51  5295.5  410.50  5321.0  412.51  5338.1  417.88
  5344.9  422.01  5352.3  422.68  5359.1  425.65  5387.4  424.48  5514.0  426.81
#Mann=6,-1,0
  4228.6    0.16       0  4346.6    0.12       0  4987.4    0.07       0
  4994.3    0.12       0  5012.5    0.16       0  5109.4    0.12       0
Bank Sta=4745.6,5321
Exp/Cntr=0.3,0.1

Type RM Length L Ch R = 1,6625,781,781,781
BEGIN DESCRIPTION:
BRIER BRANCH 5.0
END DESCRIPTION:
XS GIS Cut Line= 3
      2843124.98      7040824.97      2842839.43      7040334.19
      2842425.00      7039925.00
#Sta/Elev= 30
  4437.4  444.84  4466.7  442.67  4472.5  441.31  4482.5  441.82  4495.2  439.47
  4590.0  429.25  4668.2  423.90  4715.0  422.02  4809.3  415.21  4830.8  412.70
  4870.9  410.84  4942.5  408.29  4964.0  405.10  4969.8  408.96  4979.8  408.14
  4985.6  402.25  4989.3  401.73  4989.8  400.93  4995.7  400.93  4996.2  401.73
  5001.3  407.13  5004.6  408.66  5234.1  409.89  5261.7  410.84  5306.4  413.52
  5439.1  425.79  5486.4  429.15  5537.2  433.13  5566.4  436.81  5587.6  437.63
#Mann=7,-1,0
  4437.4    0.16       0  4668.2    0.12       0  4989.3    0.07       0
  4996.2    0.12       0  5306.4    0.16       0  5486.4    0.12       0
  5537.2    0.16       0
Bank Sta=4870.9,5261.7
Exp/Cntr=0.3,0.1

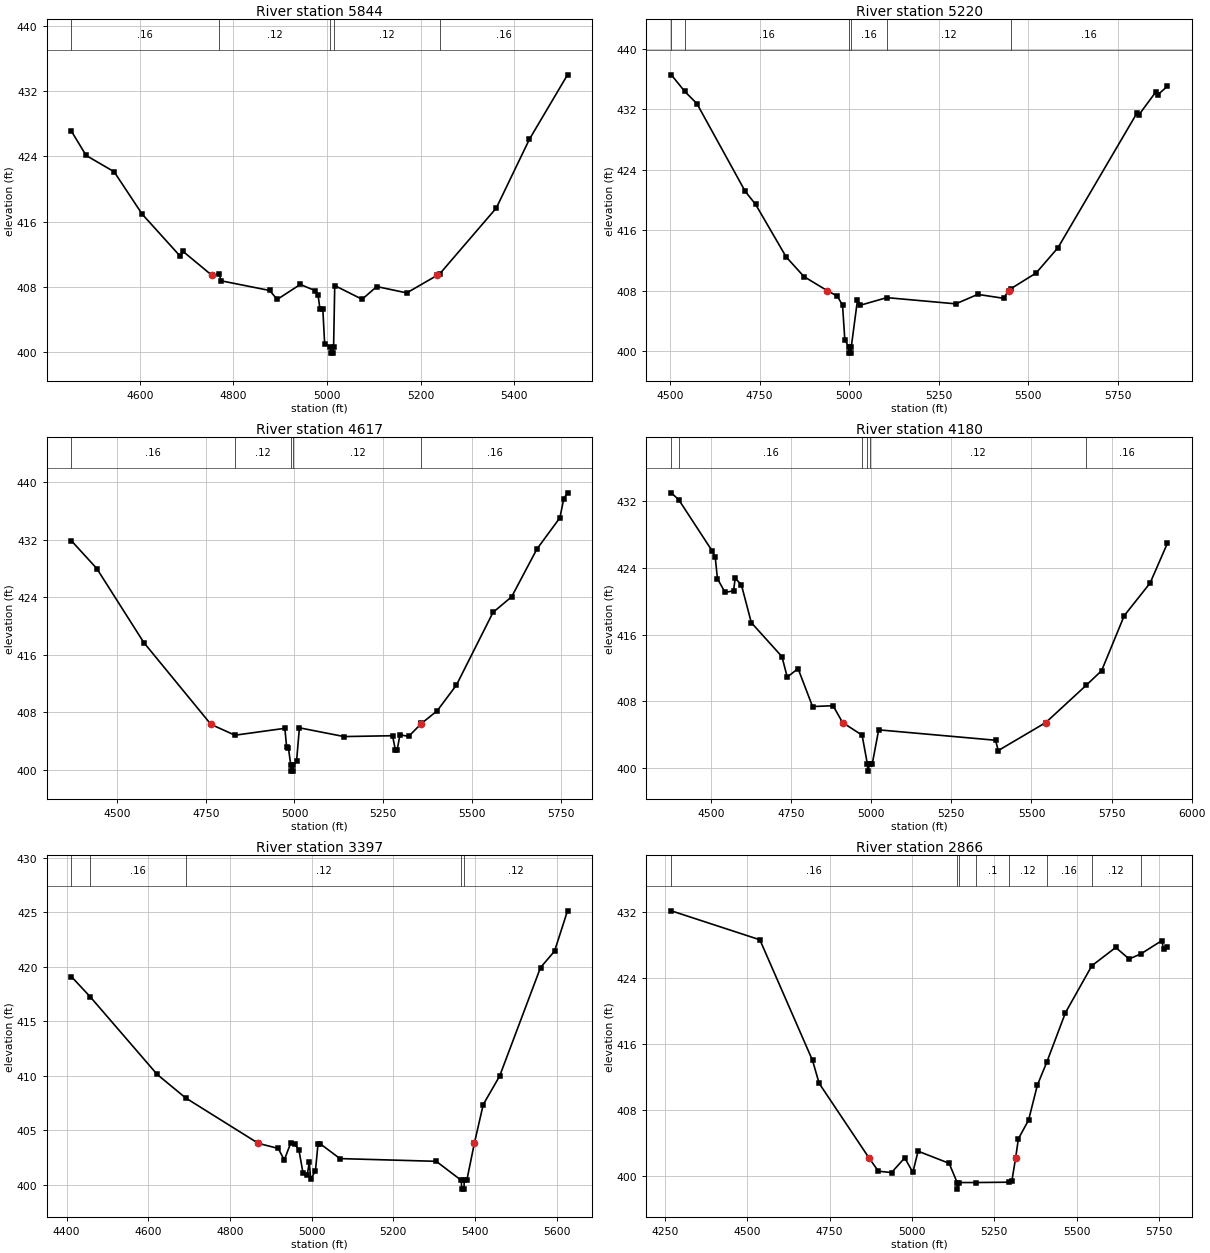
Type RM Length L Ch R = 1,5844,624,624,624
BEGIN DESCRIPTION:
BRIER BRANCH 4.0
END DESCRIPTION:
XS GIS Cut Line= 3
      2843382.83      7040561.49      2843126.75      7040092.74
      2842674.97      7039824.98
#Sta/Elev= 30
  4454.2  427.07  4485.5  424.11  4545.3  422.11  4605.1  416.92  4686.7  411.74
  4692.4  412.35  4753.8  409.43  4769.5  409.55  4774.0  408.74  4877.4  407.56
  4893.5  406.46  4942.9  408.30  4974.4  407.54  4980.8  407.00  4984.9  405.25
  4991.0  405.25  4994.9  400.99  5007.1  400.68  5007.6  399.88  5013.5  399.88
  5014.0  400.68  5016.4  408.16  5074.9  406.48  5106.1  408.04  5170.2  407.26
  5235.6  409.43  5240.4  409.58  5361.5  417.67  5432.1  426.09  5513.5  433.99
#Mann=5,-1,0
  4454.2    0.16       0  4769.5    0.12       0  5007.1    0.07       0
  5014.0    0.12       0  5240.4    0.16       0
Bank Sta=4753.8,5235.6
Exp/Cntr=0.3,0.1

Type RM Length L Ch R = 1,5220,603,603,603
BEGIN DESCRIPTION:
BRIER BRANCH 3.0
END DESCRIPTION:
XS GIS Cut Line= 3
      2843775.01      7040325.01      2843425.00      7039875.00
      2842625.04      7039725.01
#Sta/Elev= 30
  4503.7  436.53  4541.2  434.34  4575.2  432.72  4710.0  421.13  4739.0  419.41
  4824.1  412.48  4873.8  409.88  4938.5  408.03  4967.0  407.29  4981.5  406.10
  4987.8  401.56  4998.8  400.57  4999.3  399.77  5005.3  399.77  5005.8  400.57
  5023.1  406.76  5031.3  406.10  5105.0  407.10  5297.6  406.28  5358.7  407.53
  5430.8  407.01  5444.7  408.03  5451.0  408.28  5521.5  410.35  5582.5  413.69
  5803.8  431.55  5808.9  431.28  5856.4  434.32  5861.5  433.92  5887.7  435.01
#Mann=6,-1,0
  4503.7    0.05       0  4541.2    0.16       0  4998.8    0.07       0
  5005.8    0.16       0  5105.0    0.12       0  5451.0    0.16       0
Bank Sta=4938.5,5444.7
Exp/Cntr=0.3,0.1

Type RM Length L Ch R = 1,4617,437,437,437
BEGIN DESCRIPTION:
BRIER BRANCH 2.0
END DESCRIPTION:
XS GIS Cut Line= 3
      2843824.99      7040224.97      2843705.23      7039605.23
      2843474.99      7038874.97
#Sta/Elev= 30
  4372.0  431.84  4443.3  427.98  4575.7  417.68  4764.7  406.29  4832.4  404.78
  4972.9  405.74  4978.0  403.08  4983.1  402.95  4989.8  400.58  4990.3  399.78
  4996.3  399.78  4996.8  400.58  5005.9  401.18  5013.9  405.81  5139.8  404.59
  5276.1  404.71  5284.0  402.79  5289.2  402.73  5297.0  404.83  5321.6  404.62
  5355.1  406.29  5357.6  406.42  5401.9  408.18  5456.2  411.77  5559.2  421.88
  5611.6  424.05  5682.7  430.69  5747.4  435.04  5758.4  437.71  5768.9  438.52
#Mann=5,-1,0
  4372.0    0.16       0  4832.4    0.12       0  4989.8    0.07       0
  4996.8    0.12       0  5357.6    0.16       0
Bank Sta=4764.7,5355.1
Exp/Cntr=0.3,0.1

Type RM Length L Ch R = 1,4180,783,783,783
BEGIN DESCRIPTION:
Mapping XS 10d0a494
END DESCRIPTION:
XS GIS Cut Line= 3
      2843890.63      7040279.41      2844012.17      7039689.09
      2843890.64      7038751.64
#Sta/Elev= 30
  4376.1  433.04  4399.7  432.19  4503.1  426.09  4513.3  425.28  4520.1  422.72
  4544.0  421.07  4570.4  421.27  4575.5  422.80  4595.0  421.96  4625.8  417.44
  4721.4  413.36  4737.9  410.90  4771.7  411.92  4816.9  407.36  4880.9  407.46
  4910.6  405.44  4971.5  403.92  4988.3  400.40  4988.8  399.60  4995.3  400.40
  5003.1  400.45  5023.3  404.56  5388.0  403.31  5396.4  402.07  5544.9  405.44
  5670.2  409.89  5719.0  411.67  5789.6  418.28  5870.3  422.20  5924.1  426.96
#Mann=6,-1,0
  4376.1    0.05       0  4399.7    0.16       0  4971.5    0.12       0
  4988.3    0.07       0  4995.3    0.12       0  5670.2    0.16       0
Bank Sta=4910.6,5544.9
Exp/Cntr=0.3,0.1

Type RM Length L Ch R = 1,3397,531,531,531
BEGIN DESCRIPTION:
Mapping XS 35899285
END DESCRIPTION:
XS GIS Cut Line= 3
      2844285.61      7040144.78      2844381.09      7039563.22
      2844337.75      7038939.07
#Sta/Elev= 30
  4411.9  419.08  4457.5  417.25  4621.8  410.12  4691.3  407.97  4869.5  403.80
  4918.4  403.33  4933.2  402.27  4948.8  403.82  4958.9  403.72  4969.0  403.20
  4979.2  401.04  4989.3  400.89  4994.4  402.06  4997.9  400.50  5009.5  401.28
  5015.7  403.72  5020.7  403.77  5069.6  402.40  5305.4  402.15  5366.9  400.40
  5367.4  399.60  5373.4  399.60  5373.9  400.40  5380.4  400.43  5398.7  403.80
  5420.5  407.36  5460.6  409.96  5560.8  419.92  5595.1  421.42  5626.9  425.12
#Mann=5,-1,0
  4411.9    0.05       0  4457.5    0.16       0  4691.3    0.12       0
  5366.9    0.07       0  5373.9    0.12       0
Bank Sta=4869.5,5398.7
Exp/Cntr=0.3,0.1

Type RM Length L Ch R = 1,2866,727,727,727
BEGIN DESCRIPTION:
Mapping XS 80bd098d
END DESCRIPTION:
XS GIS Cut Line= 3
      2844760.22      7040213.95      2844753.28      7039498.66
      2844607.44      7038720.84
#Sta/Elev= 30
  4269.1  432.15  4538.1  428.64  4698.1  414.01  4718.1  411.24  4869.7  402.19
  4898.1  400.58  4938.1  400.42  4978.1  402.20  5002.8  400.45  5018.7  403.01
  5113.0  401.54  5137.3  399.21  5137.8  398.41  5144.3  399.21  5195.5  399.21
  5295.5  399.25  5303.6  399.41  5315.0  402.19  5323.3  404.51  5354.4  406.79
  5381.0  411.02  5409.7  413.81  5466.3  419.80  5546.4  425.49  5619.0  427.71
  5659.7  426.31  5695.4  426.93  5759.1  428.54  5764.2  427.47  5775.8  427.75
#Mann=8,-1,0
  4269.1    0.16       0  5137.3    0.07       0  5144.3    0.16       0
  5195.5     0.1       0  5295.5    0.12       0  5409.7    0.16       0
  5546.4    0.12       0  5695.4    0.16       0
Bank Sta=4869.7,5315
Exp/Cntr=0.3,0.1

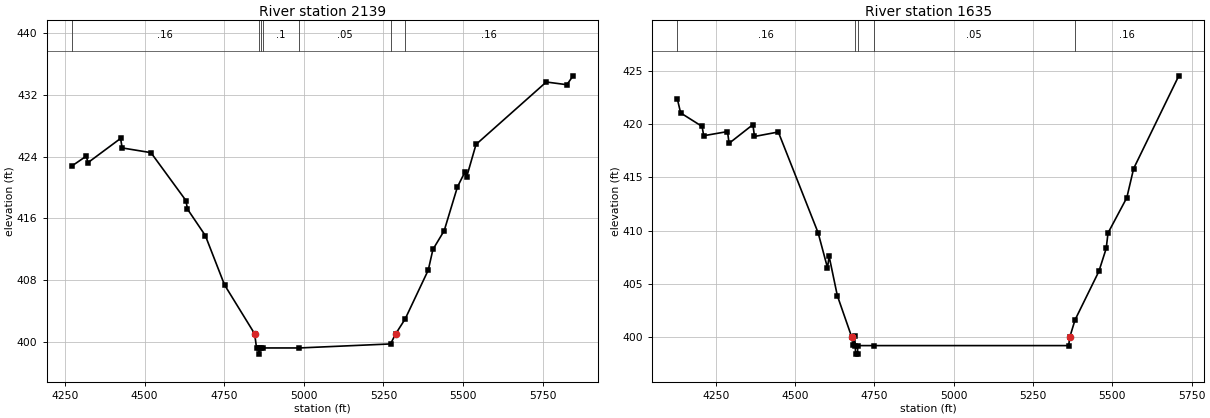
Type RM Length L Ch R = 1,2139,504,504,504
BEGIN DESCRIPTION:
Mapping XS 4099a3d8
END DESCRIPTION:
XS GIS Cut Line= 3
      2845204.67      7040012.60      2845121.33      7039144.49
      2844698.84      7038583.48
#Sta/Elev= 30
  4271.0  422.77  4316.8  424.06  4321.9  423.21  4424.4  426.35  4429.4  425.12
  4519.7  424.51  4629.5  418.31  4634.5  417.19  4690.5  413.77  4750.8  407.38
  4845.4  401.04  4851.3  399.22  4857.5  399.21  4858.1  398.41  4865.1  399.21
  4870.1  399.21  4985.8  399.21  5272.1  399.73  5288.3  401.04  5318.0  402.96
  5390.6  409.30  5405.2  411.97  5440.6  414.40  5482.2  420.07  5505.1  421.95
  5511.4  421.40  5540.5  425.57  5761.2  433.66  5825.8  433.31  5845.4  434.46
#Mann=7,-1,0
  4271.0    0.16       0  4857.5   0.033       0  4865.1    0.16       0
  4870.1     0.1       0  4985.8    0.05       0  5272.1    0.12       0
  5318.0    0.16       0
Bank Sta=4845.4,5288.3
Exp/Cntr=0.3,0.1

Type RM Length L Ch R = 1,1635,0,0,0
BEGIN DESCRIPTION:
BRIER BRANCH 1.0
END DESCRIPTION:
XS GIS Cut Line= 3
      2845419.95      7039825.00      2845527.55      7038976.42
      2845169.98      7038345.94
#Sta/Elev= 30
  4129.3  422.32  4139.4  421.04  4207.1  419.77  4212.1  418.90  4287.1  419.29
  4292.2  418.19  4367.2  419.94  4372.2  418.83  4447.3  419.25  4572.8  409.79
  4602.3  406.51  4607.4  407.59  4633.3  403.90  4678.7  400.01  4682.4  399.31
  4687.5  400.08  4690.0  399.21  4690.6  398.41  4697.0  398.41  4697.6  399.21
  4747.5  399.21  5362.4  399.21  5366.0  400.01  5382.5  401.62  5457.7  406.18
  5480.7  408.32  5486.4  409.77  5545.6  413.08  5567.2  415.82  5709.5  424.52
#Mann=5,-1,0
  4129.3    0.16       0  4690.0   0.033       0  4697.6    0.16       0
  4747.5    0.05       0  5382.5    0.16       0
Bank Sta=4678.7,5366
Exp/Cntr=0.3,0.1

Chan Stop Cuts=-1