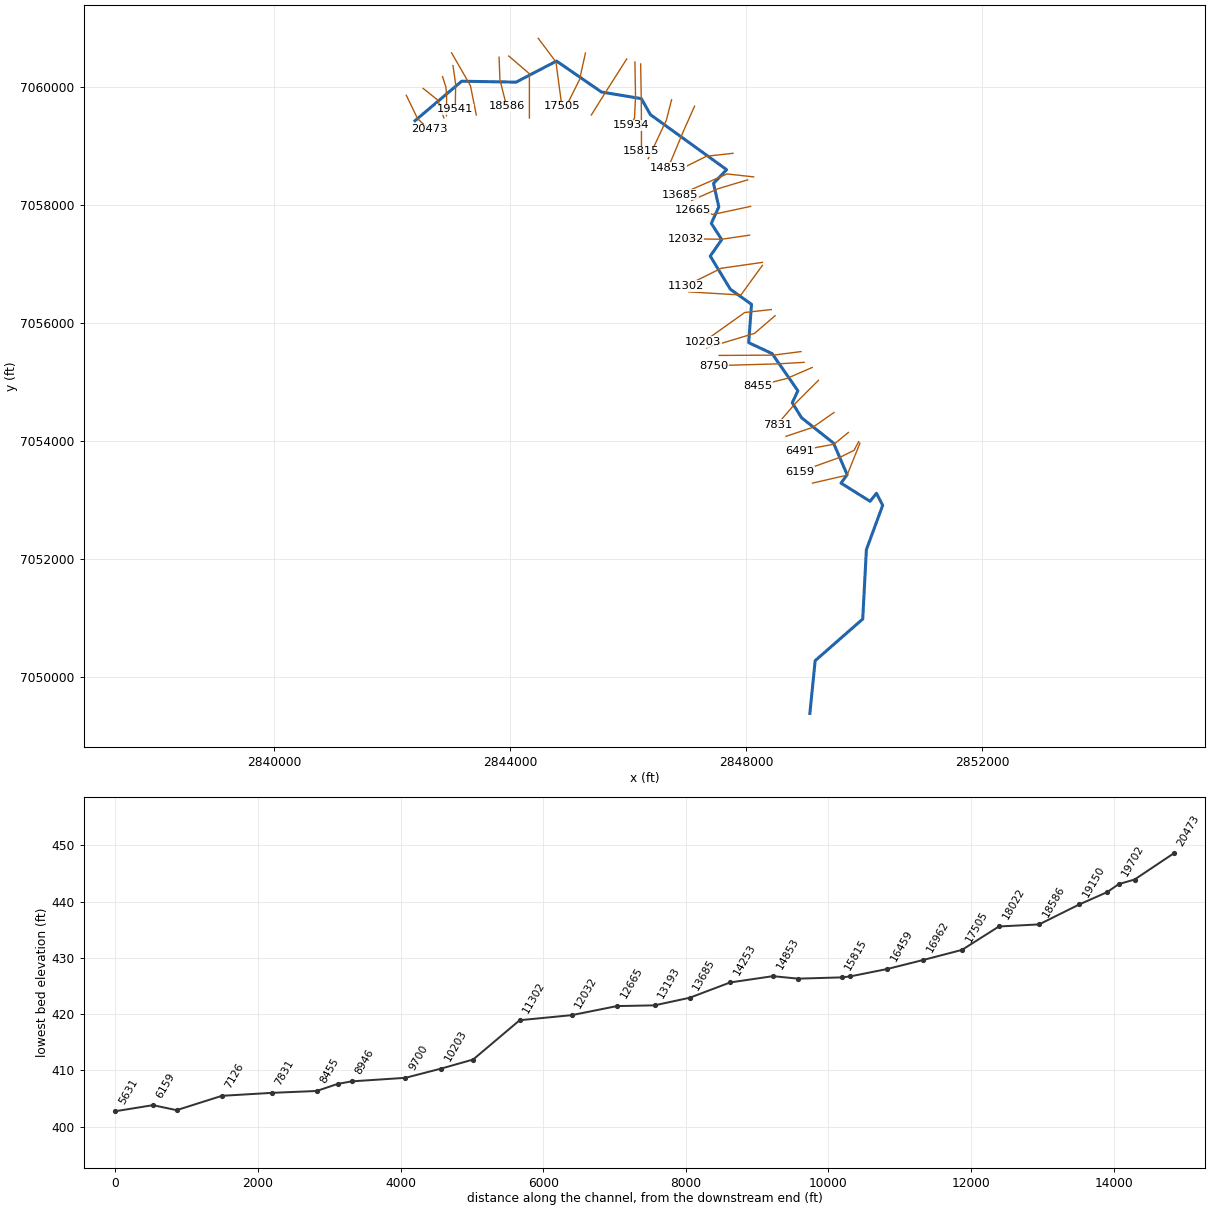
--- BRUSHY BRANCH.prj (project) ---

Proj Title=BRUSHY BRANCH Base Level Engineering
Current Plan=p01
Default Exp/Contr=0.3,0.1
English Units
Geom File=g01
Flow File=f01
Plan File=p01
BEGIN DESCRIPTION:
BRUSHY BRANCH
END DESCRIPTION:

--- BRUSHY BRANCH.p01 (plan) ---

Plan Title=Multiple Run
Short Identifier=Multiple
Geom File=g01
Flow File=f01
Subcritical Flow
K Sum by GR= 0
Std Step Tol= 0.01
Critical Tol= 0.01
Num of Std Step Trials= 20
Max Error Tol= 0.3
Flow Tol Ratio= 0.001
Split Flow NTrial= 30
Split Flow Tol= 0.02
Split Flow Ratio= 0.02
Log Output Level= 0
Friction Slope Method= 1
Unsteady Friction Slope Method= 2
Unsteady Bridges Friction Slope Method= 1
Parabolic Critical Depth
Global Vel Dist=  1 , 1 , 1
Global Log Level= 0
CheckData=True
Encroach Param= -1, 0, 0, 0
BEGIN DESCRIPTION:
Multiple Run
END DESCRIPTION:

--- BRUSHY BRANCH.f01 (steady flow) ---

Flow Title=Multiple
Number of Profiles=7
Profile Names=10-year,25-year,50-year,1pct_min,100-year,1pct_plu,500-year
River Rch & RM= BRUSHY BRANCH,Reach-1,20473
     671     900    1086     651    1299    2591    1856
River Rch & RM= BRUSHY BRANCH,Reach-1,18586
    1242    1714    2107    1283    2559    5106    3774
River Rch & RM= BRUSHY BRANCH,Reach-1,8946
    1423    1975    2436    1488    2968    5923    4410
Boundary for River Rch & Prof#=BRUSHY BRANCH,Reach-1,1
Up Type=0
Dn Type=3
Dn Slope=0.005
Boundary for River Rch & Prof#=BRUSHY BRANCH,Reach-1,2
Up Type=0
Dn Type=3
Dn Slope=0.005
Boundary for River Rch & Prof#=BRUSHY BRANCH,Reach-1,3
Up Type=0
Dn Type=3
Dn Slope=0.005
Boundary for River Rch & Prof#=BRUSHY BRANCH,Reach-1,4
Up Type=0
Dn Type=3
Dn Slope=0.005
Boundary for River Rch & Prof#=BRUSHY BRANCH,Reach-1,5
Up Type=0
Dn Type=3
Dn Slope=0.005
Boundary for River Rch & Prof#=BRUSHY BRANCH,Reach-1,6
Up Type=0
Dn Type=3
Dn Slope=0.005
Boundary for River Rch & Prof#=BRUSHY BRANCH,Reach-1,7
Up Type=0
Dn Type=3
Dn Slope=0.005

--- BRUSHY BRANCH.g01 (geometry) ---

Geom Title=Existing Conditions

River Reach=BRUSHY BRANCH,Reach-1
Reach XY= 30
      2842386.37      7059427.43      2843177.12      7060097.45
      2844100.24      7060082.22      2844784.91      7060439.56
      2845547.09      7059914.32      2846222.48      7059802.26
      2846375.72      7059531.24      2847667.89      7058597.62
      2847446.21      7058364.18      2847535.53      7057965.95
      2847408.25      7057686.48      2847584.78      7057411.32
      2847390.56      7057131.86      2847731.28      7056569.17
      2848089.74      7056313.31      2848042.02      7055663.21
      2848438.95      7055477.63      2848875.91      7054846.96
      2848780.55      7054644.07      2848936.52      7054391.62
      2849480.59      7053958.65      2849710.88      7053424.00
      2849607.18      7053281.25      2850099.41      7052972.18
      2850207.82      7053108.87      2850312.86      7052903.50
      2850036.79      7052152.03      2849974.84      7050975.67
      2849168.83      7050269.32      2849079.07      7049375.52

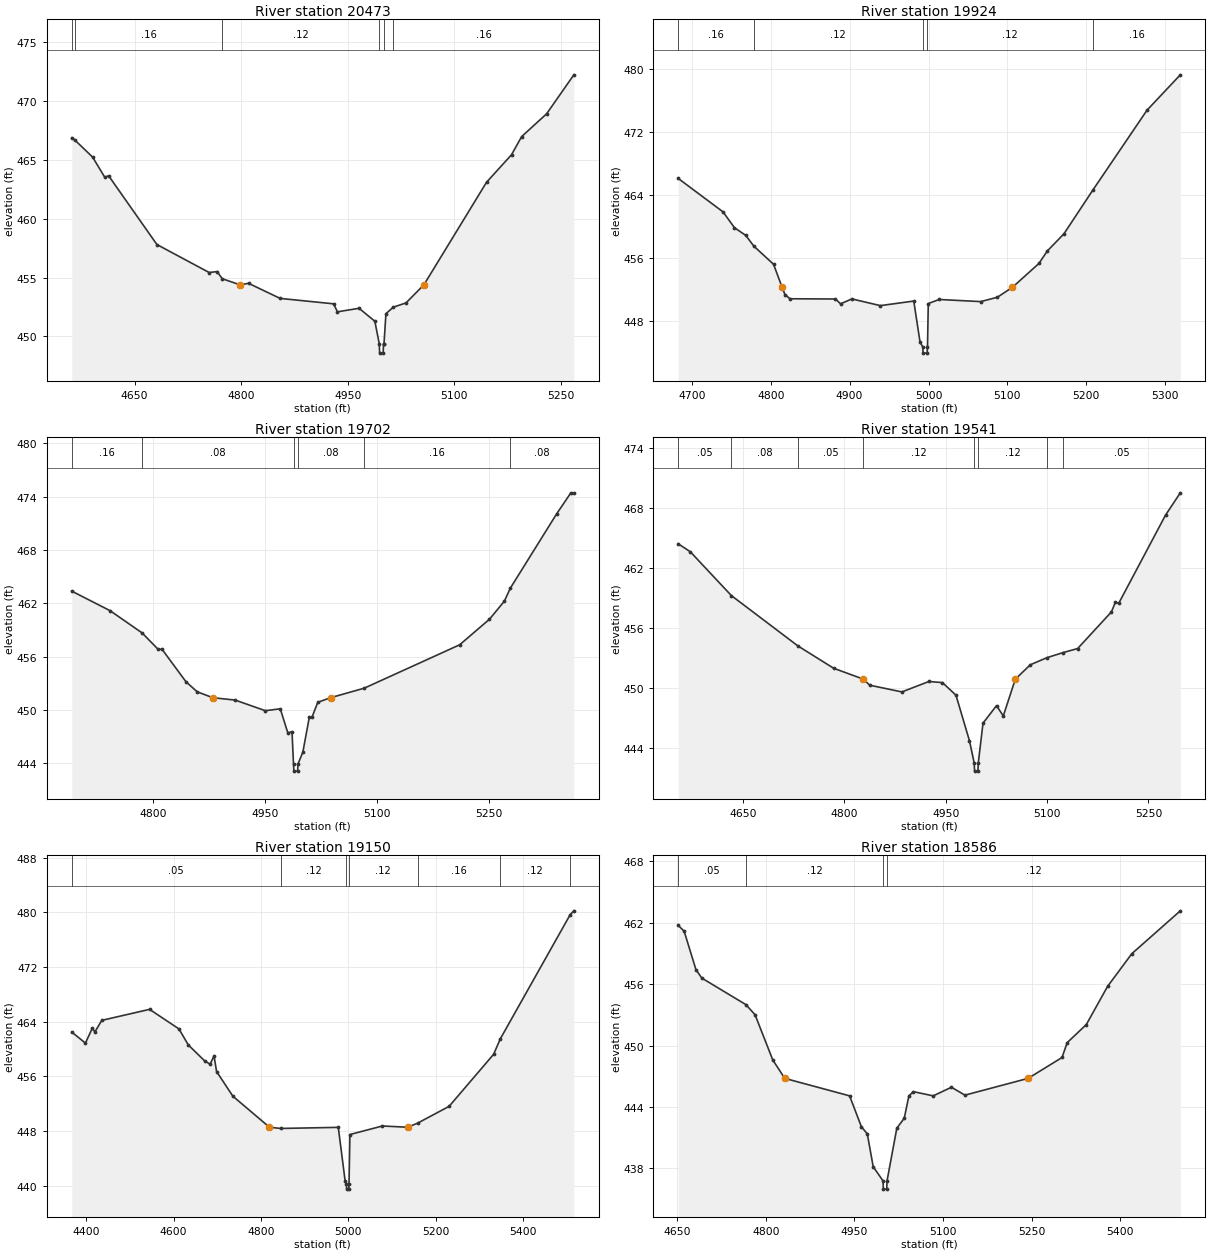
Type RM Length L Ch R = 1,20473,549,549,549
BEGIN DESCRIPTION:
BRUSHY BRANCH 26.0
END DESCRIPTION:
XS GIS Cut Line= 3
      2842238.59      7059859.19      2842429.55      7059463.38
      2842623.64      7059279.68
#Sta/Elev= 30
  4561.6  466.88  4565.7  466.70  4590.9  465.24  4608.0  463.53  4613.5  463.65
  4681.4  457.81  4755.0  455.43  4766.1  455.51  4773.5  454.90  4798.2  454.39
  4810.5  454.51  4854.9  453.23  4930.1  452.77  4935.6  452.09  4966.0  452.39
  4988.2  451.29  4994.4  449.38  4994.9  448.58  4999.9  448.58  5000.4  449.38
  5001.1  449.38  5003.8  451.93  5014.0  452.48  5032.1  452.85  5057.3  454.39
  5145.4  463.10  5180.6  465.44  5194.8  466.98  5230.0  468.92  5268.3  472.23
#Mann=6,-1,0
  4561.6    0.05       0  4565.7    0.16       0  4773.5    0.12       0
  4994.4    0.07       0  5000.4    0.12       0  5014.0    0.16       0
Bank Sta=4798.2,5057.3
Exp/Cntr=0.3,0.1

Type RM Length L Ch R = 1,19924,222,222,222
BEGIN DESCRIPTION:
BRUSHY BRANCH 25.0
END DESCRIPTION:
XS GIS Cut Line= 3
      2842525.04      7059974.97      2842775.00      7059775.00
      2842874.99      7059475.04
#Sta/Elev= 30
  4682.8  466.07  4739.6  461.83  4754.0  459.83  4768.4  458.85  4778.6  457.49
  4803.6  455.19  4814.5  452.26  4818.0  451.36  4824.4  450.82  4882.1  450.79
  4888.5  450.18  4902.9  450.80  4938.9  449.95  4981.3  450.53  4989.3  445.30
  4992.7  444.73  4993.2  443.93  4998.2  443.93  4998.7  444.73  4999.7  450.21
  5013.5  450.73  5066.2  450.46  5087.2  451.01  5106.2  452.26  5139.9  455.29
  5150.5  456.87  5171.6  459.05  5208.1  464.57  5277.0  474.73  5319.1  479.20
#Mann=5,-1,0
  4682.8    0.16       0  4778.6    0.12       0  4992.7    0.07       0
  4998.7    0.12       0  5208.1    0.16       0
Bank Sta=4814.5,5106.2
Exp/Cntr=0.3,0.1

Type RM Length L Ch R = 1,19702,161,161,161
BEGIN DESCRIPTION:
Mapping XS 73c758ed
END DESCRIPTION:
XS GIS Cut Line= 4
      2842853.17      7060175.15      2842908.72      7060001.57
      2842922.61      7059862.68      2842919.13      7059512.03
#Sta/Elev= 30
  4691.4  463.37  4742.7  461.17  4785.6  458.67  4807.0  456.83  4812.3  456.83
  4844.4  453.17  4859.5  452.04  4880.4  451.38  4910.4  451.11  4950.6  449.92
  4970.7  450.13  4980.8  447.42  4986.4  447.56  4988.4  443.92  4988.9  443.12
  4993.9  443.12  4994.4  443.92  5000.9  445.25  5009.6  449.19  5013.2  449.19
  5020.9  450.86  5038.0  451.38  5083.1  452.45  5210.9  457.33  5250.9  460.21
  5270.9  462.25  5278.8  463.70  5340.9  472.07  5359.9  474.43  5363.9  474.43
#Mann=6,-1,0
  4691.4    0.16       0  4785.6    0.08       0  4988.4    0.07       0
  4994.4    0.08       0  5083.1    0.16       0  5278.8    0.08       0
Bank Sta=4880.4,5038
Exp/Cntr=0.3,0.1

Type RM Length L Ch R = 1,19541,391,391,391
BEGIN DESCRIPTION:
Mapping XS 14b1174d
END DESCRIPTION:
XS GIS Cut Line= 3
      2843030.25      7060362.64      2843075.38      7060046.71
      2843068.44      7059623.11
#Sta/Elev= 30
  4554.3  464.40  4572.1  463.61  4632.9  459.23  4731.4  454.20  4784.3  451.97
  4828.0  450.89  4828.1  450.88  4837.6  450.28  4885.2  449.61  4925.2  450.65
  4945.2  450.54  4965.2  449.28  4985.2  444.72  4992.2  442.50  4992.7  441.70
  4997.7  441.70  4998.2  442.50  5005.2  446.49  5025.2  448.24  5035.2  447.21
  5053.0  450.88  5075.2  452.32  5099.4  453.02  5123.8  453.54  5145.2  453.94
  5195.2  457.60  5201.0  458.56  5206.0  458.46  5275.2  467.26  5297.1  469.49
#Mann=8,-1,0
  4554.3    0.05       0  4632.9    0.08       0  4731.4    0.05       0
  4828.1    0.12       0  4992.2    0.07       0  4998.2    0.12       0
  5099.4    0.08       0  5123.8    0.05       0
Bank Sta=4828,5053
Exp/Cntr=0.3,0.1

Type RM Length L Ch R = 1,19150,564,564,564
BEGIN DESCRIPTION:
BRUSHY BRANCH 23.0
END DESCRIPTION:
XS GIS Cut Line= 3
      2843005.67      7060579.39      2843325.00      7060025.00
      2843425.00      7059524.98
#Sta/Elev= 30
  4366.9  462.50  4398.2  460.88  4414.0  463.08  4419.8  462.51  4435.6  464.21
  4545.1  465.82  4612.3  462.96  4633.8  460.61  4671.2  458.28  4683.6  457.80
  4692.7  459.00  4698.5  456.72  4735.8  453.11  4819.6  448.57  4845.2  448.39
  4977.2  448.55  4993.0  440.64  4995.8  440.31  4996.3  439.51  5001.3  439.51
  5001.8  440.31  5003.8  447.50  5078.1  448.75  5135.9  448.57  5158.7  449.16
  5231.0  451.63  5333.0  459.25  5348.0  461.48  5508.3  479.69  5516.6  480.24
#Mann=7,-1,0
  4366.9    0.05       0  4845.2    0.12       0  4995.8    0.07       0
  5001.8    0.12       0  5158.7    0.16       0  5348.0    0.12       0
  5508.3    0.05       0
Bank Sta=4819.6,5135.9
Exp/Cntr=0.3,0.1

Type RM Length L Ch R = 1,18586,564,564,564
BEGIN DESCRIPTION:
BRUSHY BRANCH 22.0
END DESCRIPTION:
XS GIS Cut Line= 3
      2843811.50      7060505.01      2843825.00      7060125.00
      2843939.73      7059669.16
#Sta/Elev= 30
  4651.5  461.74  4661.5  461.18  4681.5  457.42  4691.5  456.59  4766.1  454.00
  4781.6  453.01  4811.6  448.59  4831.9  446.79  4941.7  445.08  4961.7  442.06
  4971.7  441.36  4981.7  438.15  4998.4  436.76  4998.9  435.96  5004.6  435.96
  5005.1  436.76  5021.7  441.92  5034.3  442.89  5042.1  445.07  5049.7  445.49
  5083.3  445.08  5114.2  445.92  5137.1  445.15  5244.1  446.79  5301.5  448.83
  5310.2  450.28  5342.6  452.05  5378.6  455.78  5419.7  458.98  5501.8  463.17
#Mann=4,-1,0
  4651.5    0.05       0  4766.1    0.12       0  4998.4    0.07       0
  5005.1    0.12       0
Bank Sta=4831.9,5244.1
Exp/Cntr=0.3,0.1

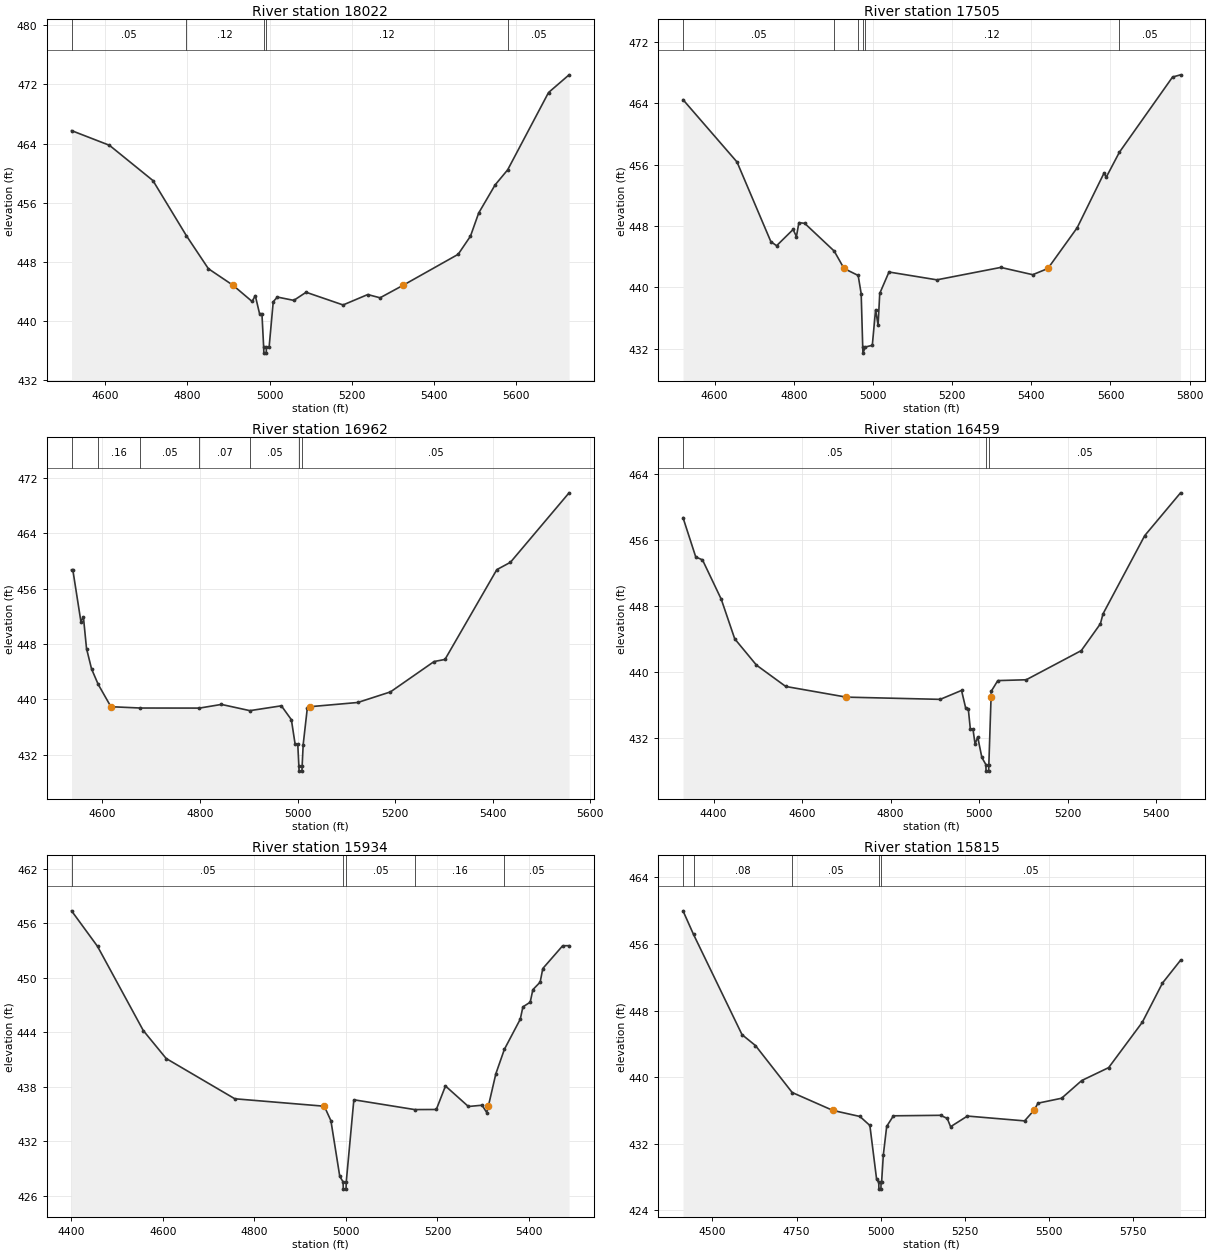
Type RM Length L Ch R = 1,18022,517,517,517
BEGIN DESCRIPTION:
BRUSHY BRANCH 21.0
END DESCRIPTION:
XS GIS Cut Line= 3
      2843975.03      7060524.98      2844325.00      7060225.00
      2844325.00      7059475.04
#Sta/Elev= 30
  4517.9  465.75  4610.1  463.76  4716.0  458.98  4797.6  451.49  4851.0  447.03
  4910.8  444.79  4957.4  442.59  4965.1  443.39  4975.5  440.93  4981.3  440.93
  4985.5  436.39  4986.0  435.59  4991.7  435.59  4992.2  436.39  4998.8  436.42
  5008.8  442.56  5018.8  443.19  5058.8  442.74  5088.8  443.84  5178.8  442.12
  5238.8  443.53  5268.8  443.09  5325.0  444.79  5458.8  448.98  5488.8  451.44
  5508.8  454.58  5548.8  458.39  5579.3  460.43  5678.8  470.91  5728.8  473.31
#Mann=5,-1,0
  4517.9    0.05       0  4797.6    0.12       0  4985.5    0.07       0
  4992.2    0.12       0  5579.3    0.05       0
Bank Sta=4910.8,5325
Exp/Cntr=0.3,0.1

Type RM Length L Ch R = 1,17505,543,543,543
BEGIN DESCRIPTION:
BRUSHY BRANCH 20.0
END DESCRIPTION:
XS GIS Cut Line= 3
      2844475.01      7060824.98      2844775.00      7060425.00
      2844875.00      7059675.02
#Sta/Elev= 30
  4520.3  464.49  4656.7  456.36  4742.2  445.97  4756.7  445.44  4798.4  447.56
  4806.7  446.63  4813.0  448.45  4827.6  448.36  4902.2  444.74  4927.0  442.47
  4962.7  441.56  4970.3  439.18  4974.2  432.23  4974.7  431.43  4981.0  432.23
  4998.4  432.45  5006.7  437.10  5013.0  435.10  5017.2  439.22  5040.5  442.01
  5161.5  440.99  5322.9  442.61  5403.6  441.66  5441.9  442.47  5515.9  447.79
  5584.0  454.95  5589.0  454.35  5622.3  457.62  5756.7  467.44  5776.9  467.73
#Mann=6,-1,0
  4520.3    0.05       0  4902.2    0.16       0  4962.7    0.12       0
  4974.2    0.07       0  4981.0    0.12       0  5622.3    0.05       0
Bank Sta=4927,5441.9
Exp/Cntr=0.3,0.1

Type RM Length L Ch R = 1,16962,503,503,503
BEGIN DESCRIPTION:
BRUSHY BRANCH 19.0
END DESCRIPTION:
XS GIS Cut Line= 3
      2845275.00      7060575.00      2845175.00      7060125.00
      2844925.00      7059624.99
#Sta/Elev= 30
  4536.7  458.74  4539.3  458.74  4555.9  451.25  4561.0  451.93  4567.4  447.36
  4577.7  444.42  4591.4  442.17  4617.4  438.95  4677.7  438.76  4799.0  438.75
  4844.0  439.28  4902.3  438.38  4966.9  439.08  4987.4  437.07  4995.1  433.52
  5000.5  433.52  5002.7  430.44  5003.2  429.64  5009.0  429.64  5009.5  430.44
  5011.6  433.48  5020.0  438.71  5025.2  438.95  5123.5  439.56  5190.5  441.09
  5280.0  445.48  5302.3  445.78  5408.6  458.76  5436.5  459.82  5556.7  469.86
#Mann=7,-1,0
  4536.7    0.05       0  4591.4    0.16       0  4677.7    0.05       0
  4799.0    0.07       0  4902.3    0.05       0  5002.7    0.03       0
  5009.5    0.05       0
Bank Sta=4617.4,5025.2
Exp/Cntr=0.3,0.1

Type RM Length L Ch R = 1,16459,525,525,525
BEGIN DESCRIPTION:
BRUSHY BRANCH 18.0
END DESCRIPTION:
XS GIS Cut Line= 3
      2845974.98      7060474.98      2845625.00      7059925.00
      2845375.00      7059524.99
#Sta/Elev= 30
  4331.0  458.70  4359.8  453.94  4375.0  453.59  4417.3  448.84  4447.8  444.04
  4496.9  440.86  4563.0  438.28  4699.7  436.99  4911.8  436.72  4960.0  437.80
  4969.3  435.69  4975.3  435.55  4979.9  433.13  4985.8  433.13  4990.6  431.31
  4996.5  432.17  5005.9  429.69  5014.9  428.84  5015.4  428.04  5021.2  428.04
  5021.7  428.84  5026.7  436.99  5027.1  437.70  5041.9  438.99  5106.1  439.09
  5230.5  442.62  5273.6  445.86  5279.5  447.06  5373.8  456.53  5454.6  461.70
#Mann=3,-1,0
  4331.0    0.05       0  5014.9    0.03       0  5021.7    0.05       0
Bank Sta=4699.7,5026.7
Exp/Cntr=0.3,0.1

Type RM Length L Ch R = 1,15934,119,119,119
BEGIN DESCRIPTION:
Mapping XS 9be63081
END DESCRIPTION:
XS GIS Cut Line= 4
      2846113.58      7060421.74      2846123.99      7059831.43
      2846106.63      7059470.32      2846040.65      7059352.24
#Sta/Elev= 30
  4400.5  457.39  4457.3  453.47  4557.3  444.19  4607.3  441.11  4757.3  436.67
  4952.8  435.85  4967.3  434.25  4986.6  428.12  4993.9  427.51  4994.4  426.71
  5000.3  426.71  5000.8  427.51  5017.4  436.56  5150.3  435.48  5197.6  435.49
  5217.6  438.08  5267.7  435.82  5297.7  435.96  5307.7  435.15  5311.3  435.85
  5327.7  439.43  5346.4  442.13  5381.1  445.45  5386.8  446.80  5402.8  447.32
  5408.6  448.70  5424.5  449.53  5430.3  451.03  5473.7  453.54  5487.7  453.55
#Mann=5,-1,0
  4400.5    0.05       0  4993.9    0.03       0  5000.8    0.05       0
  5150.3    0.16       0  5346.4    0.05       0
Bank Sta=4952.8,5311.3
Exp/Cntr=0.3,0.1

Type RM Length L Ch R = 1,15815,612,612,612
BEGIN DESCRIPTION:
Mapping XS bbda46d3
END DESCRIPTION:
XS GIS Cut Line= 4
      2846210.80      7060390.48      2846221.22      7059800.18
      2846224.69      7059293.24      2846224.69      7058911.28
#Sta/Elev= 30
  4412.4  459.98  4443.6  457.15  4587.9  445.10  4627.9  443.79  4737.0  438.15
  4857.8  436.00  4938.4  435.27  4968.0  434.19  4988.0  427.73  4994.4  427.34
  4994.9  426.54  5000.8  426.54  5001.3  427.34  5002.8  427.34  5008.0  430.65
  5018.0  434.08  5038.0  435.35  5178.0  435.41  5198.0  435.04  5208.0  434.04
  5258.0  435.32  5428.0  434.74  5455.6  436.00  5468.0  436.87  5538.0  437.46
  5598.0  439.59  5678.0  441.14  5778.0  446.59  5838.0  451.30  5891.7  454.04
#Mann=5,-1,0
  4412.4    0.05       0  4443.6    0.08       0  4737.0    0.05       0
  4994.4    0.04       0  5001.3    0.05       0
Bank Sta=4857.8,5455.6
Exp/Cntr=0.3,0.1

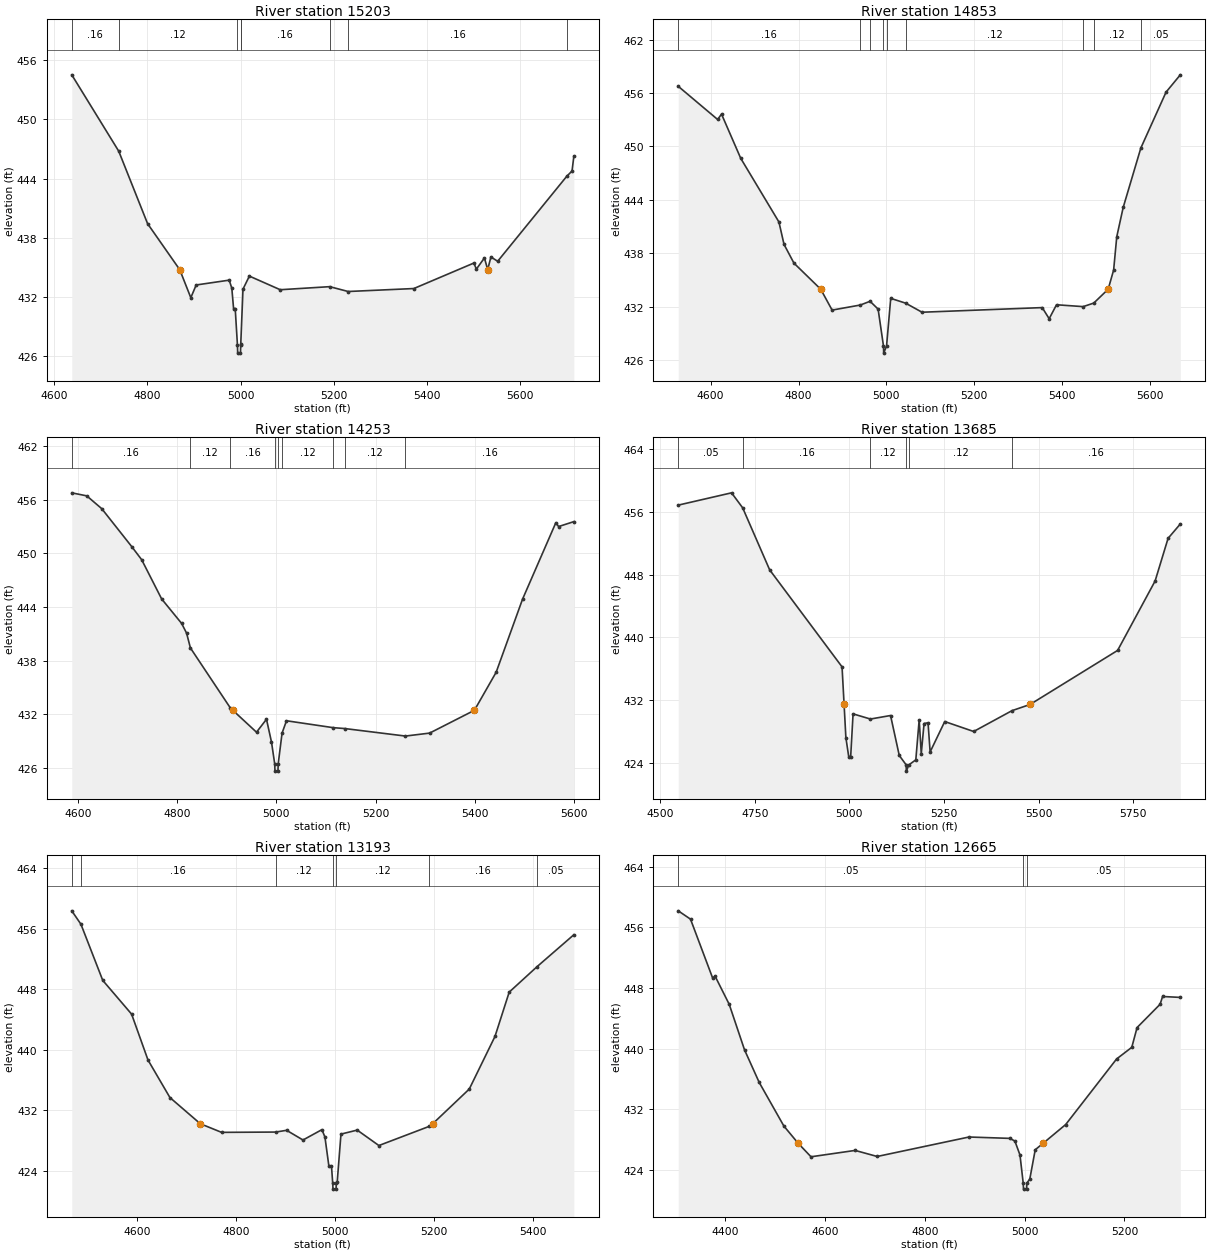
Type RM Length L Ch R = 1,15203,350,350,350
BEGIN DESCRIPTION:
Mapping XS c9bed82c
END DESCRIPTION:
XS GIS Cut Line= 3
      2846735.11      7059782.83      2846648.30      7059442.55
      2846339.65      7058783.64
#Sta/Elev= 30
  4637.4  454.50  4738.3  446.77  4800.3  439.43  4869.4  434.77  4893.2  431.93
  4904.7  433.22  4975.7  433.71  4981.3  432.89  4985.1  430.82  4988.6  430.82
  4993.4  427.12  4993.9  426.32  4999.9  426.32  5000.4  427.12  5000.5  427.24
  5005.3  432.80  5019.0  434.12  5085.3  432.74  5191.6  433.05  5231.3  432.56
  5372.4  432.86  5501.3  435.44  5506.8  434.83  5524.1  435.96  5531.1  434.77
  5538.0  436.06  5552.5  435.62  5701.2  444.24  5712.3  444.76  5716.2  446.25
#Mann=8,-1,0
  4637.4    0.16       0  4738.3    0.12       0  4993.4    0.07       0
  5000.4    0.12       0  5000.5    0.16       0  5191.6    0.12       0
  5231.3    0.16       0  5701.2    0.05       0
Bank Sta=4869.4,5531.1
Exp/Cntr=0.3,0.1

Type RM Length L Ch R = 1,14853,600,600,600
BEGIN DESCRIPTION:
BRUSHY BRANCH 15.0
END DESCRIPTION:
XS GIS Cut Line= 3
      2847124.99      7059674.97      2846925.00      7059225.00
      2846675.00      7058625.01
#Sta/Elev= 30
  4526.3  456.77  4615.9  453.04  4624.8  453.64  4668.5  448.67  4755.4  441.51
  4767.0  438.99  4789.6  436.88  4850.5  433.95  4876.4  431.60  4940.6  432.17
  4962.8  432.59  4981.1  431.71  4993.3  427.56  4993.8  426.76  5000.3  427.56
  5009.8  432.92  5043.7  432.38  5081.0  431.36  5354.5  431.88  5370.3  430.63
  5387.0  432.20  5447.6  431.99  5471.8  432.39  5504.6  433.95  5517.0  436.11
  5524.1  439.85  5538.7  443.14  5578.9  449.83  5636.2  456.11  5668.7  458.06
#Mann=9,-1,0
  4526.3    0.16       0  4940.6    0.12       0  4962.8    0.16       0
  4993.3    0.07       0  5000.3    0.16       0  5043.7    0.12       0
  5447.6    0.16       0  5471.8    0.12       0  5578.9    0.05       0
Bank Sta=4850.5,5504.6
Exp/Cntr=0.3,0.1

Type RM Length L Ch R = 1,14253,568,568,568
BEGIN DESCRIPTION:
BRUSHY BRANCH 14.0
END DESCRIPTION:
XS GIS Cut Line= 3
      2847775.02      7058875.00      2847325.00      7058825.00
      2846825.00      7058575.00
#Sta/Elev= 30
  4587.7  456.75  4617.9  456.41  4648.1  454.98  4708.5  450.74  4728.6  449.27
  4768.8  444.89  4809.1  442.15  4819.1  441.06  4826.8  439.41  4906.8  432.74
  4912.3  432.44  4960.0  429.99  4980.1  431.44  4990.2  428.89  4996.7  426.44
  4997.2  425.64  5003.2  425.64  5003.7  426.44  5011.5  429.89  5020.4  431.27
  5114.4  430.50  5137.8  430.40  5260.1  429.56  5308.8  429.89  5399.1  432.44
  5443.0  436.70  5496.1  444.86  5563.2  453.41  5568.8  452.98  5599.5  453.53
#Mann=9,-1,0
  4587.7    0.16       0  4826.8    0.12       0  4906.8    0.16       0
  4996.7    0.07       0  5003.7    0.16       0  5011.5    0.12       0
  5114.4    0.16       0  5137.8    0.12       0  5260.1    0.16       0
Bank Sta=4912.3,5399.1
Exp/Cntr=0.3,0.1

Type RM Length L Ch R = 1,13685,492,492,492
BEGIN DESCRIPTION:
BRUSHY BRANCH 13.0
END DESCRIPTION:
XS GIS Cut Line= 3
      2848124.95      7058475.01      2847675.00      7058525.00
      2846875.03      7058175.01
#Sta/Elev= 30
  4548.1  456.88  4688.9  458.45  4718.3  456.53  4789.5  448.62  4980.7  436.23
  4986.1  431.43  4990.8  427.21  4998.3  424.77  5003.5  424.77  5009.8  430.23
  5055.6  429.57  5108.8  430.02  5131.8  424.92  5150.0  423.72  5150.5  422.92
  5157.2  423.72  5175.5  424.36  5184.4  429.47  5189.9  425.14  5197.3  429.00
  5207.8  429.09  5213.3  425.37  5251.9  429.25  5328.3  427.98  5429.5  430.64
  5477.2  431.43  5708.4  438.33  5807.4  447.19  5841.7  452.64  5874.0  454.47
#Mann=6,-1,0
  4548.1    0.05       0  4718.3    0.16       0  5055.6    0.12       0
  5150.0    0.07       0  5157.2    0.12       0  5429.5    0.16       0
Bank Sta=4986.1,5477.2
Exp/Cntr=0.3,0.1

Type RM Length L Ch R = 1,13193,528,528,528
BEGIN DESCRIPTION:
BRUSHY BRANCH 12.0
END DESCRIPTION:
XS GIS Cut Line= 3
      2848024.97      7058424.99      2847525.00      7058275.00
      2847075.02      7058075.01
#Sta/Elev= 30
  4468.2  458.34  4486.7  456.57  4530.8  449.15  4589.1  444.69  4622.2  438.63
  4666.5  433.67  4727.9  430.21  4770.9  429.07  4880.1  429.11  4902.3  429.34
  4935.4  428.06  4973.6  429.43  4979.7  428.45  4987.6  424.65  4992.9  424.65
  4995.4  422.37  4996.0  421.57  5002.2  421.57  5002.7  422.37  5004.5  422.52
  5012.1  428.84  5044.9  429.37  5088.7  427.33  5189.9  429.85  5197.5  430.21
  5271.3  434.79  5323.3  441.75  5352.0  447.60  5408.4  450.97  5482.6  455.18
#Mann=7,-1,0
  4468.2    0.05       0  4486.7    0.16       0  4880.1    0.12       0
  4995.4    0.07       0  5002.7    0.12       0  5189.9    0.16       0
  5408.4    0.05       0
Bank Sta=4727.9,5197.5
Exp/Cntr=0.3,0.1

Type RM Length L Ch R = 1,12665,633,633,633
BEGIN DESCRIPTION:
BRUSHY BRANCH 11.0
END DESCRIPTION:
XS GIS Cut Line= 3
      2848074.96      7057974.99      2847439.97      7057838.38
      2847089.59      7057907.76
#Sta/Elev= 30
  4305.4  458.18  4330.0  457.08  4374.3  449.32  4379.4  449.54  4407.6  445.84
  4438.3  439.83  4467.8  435.52  4517.2  429.77  4545.8  427.50  4571.6  425.71
  4660.1  426.55  4704.3  425.75  4888.4  428.32  4970.2  428.14  4980.4  427.79
  4990.6  425.95  4997.1  422.24  4997.7  421.44  5003.9  421.44  5004.4  422.24
  5010.3  422.77  5021.2  426.64  5037.2  427.50  5082.3  429.97  5184.3  438.62
  5214.8  440.16  5225.4  442.77  5271.5  445.84  5276.6  446.87  5312.1  446.75
#Mann=3,-1,0
  4305.4    0.05       0  4997.1    0.03       0  5004.4    0.05       0
Bank Sta=4545.8,5037.2
Exp/Cntr=0.3,0.1

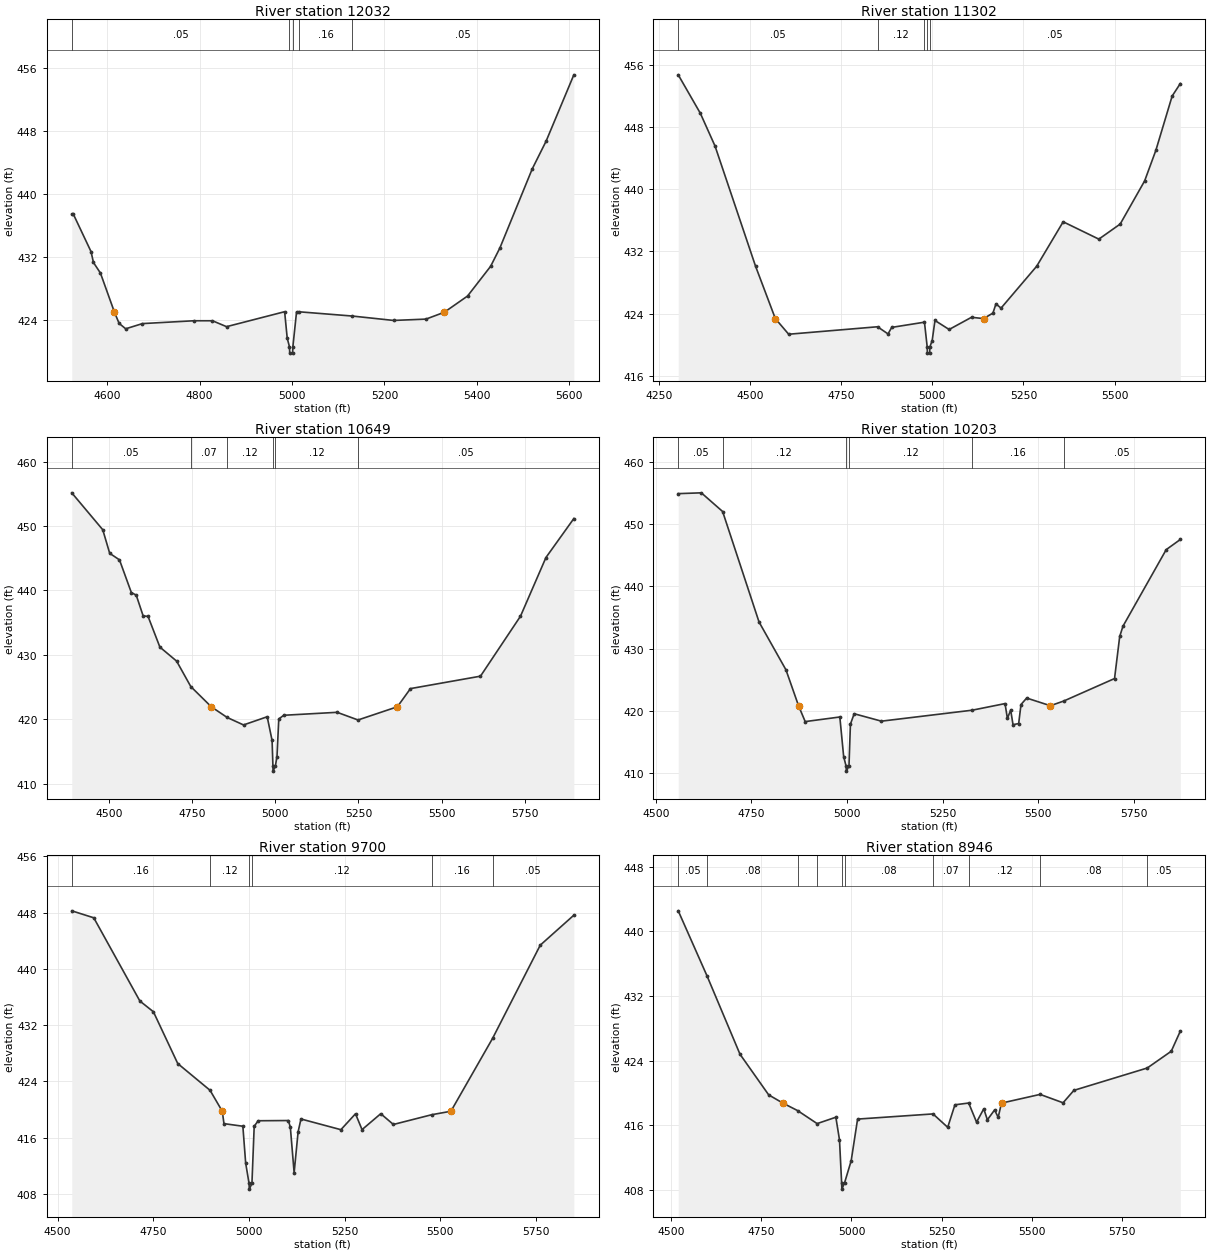
Type RM Length L Ch R = 1,12032,730,730,730
BEGIN DESCRIPTION:
BRUSHY BRANCH 10.0
END DESCRIPTION:
XS GIS Cut Line= 3
      2848056.30      7057486.82      2847583.20      7057417.37
      2846975.02      7057425.00
#Sta/Elev= 30
  4523.5  437.50  4526.7  437.50  4565.2  432.72  4570.4  431.34  4585.5  430.00
  4615.9  425.02  4625.9  423.61  4640.2  422.92  4676.4  423.58  4787.6  423.94
  4828.0  423.94  4858.4  423.19  4984.1  425.09  4989.7  421.72  4994.6  420.63
  4995.1  419.83  5001.3  419.83  5001.9  420.63  5009.9  425.07  5015.1  425.08
  5130.4  424.54  5219.9  423.98  5289.9  424.15  5329.6  425.02  5379.9  427.08
  5429.9  430.86  5449.9  433.19  5519.9  443.23  5549.9  446.75  5609.9  455.17
#Mann=5,-1,0
  4523.5    0.05       0  4994.6    0.03       0  5001.9    0.05       0
  5015.1    0.16       0  5130.4    0.05       0
Bank Sta=4615.9,5329.6
Exp/Cntr=0.3,0.1

Type RM Length L Ch R = 1,11302,653,653,653
BEGIN DESCRIPTION:
BRUSHY BRANCH 9.0
END DESCRIPTION:
XS GIS Cut Line= 3
      2848275.03      7057025.00      2847575.00      7056925.00
      2846974.96      7056624.98
#Sta/Elev= 30
  4302.6  454.72  4363.2  449.78  4403.6  445.56  4514.8  430.11  4569.1  423.37
  4605.7  421.36  4849.6  422.32  4878.4  421.40  4888.5  422.24  4978.4  422.91
  4985.9  419.73  4986.4  418.93  4992.6  418.93  4993.2  419.73  4999.6  420.55
  5007.2  423.13  5046.1  421.97  5107.6  423.54  5140.6  423.37  5166.3  424.08
  5174.6  425.26  5188.6  424.72  5286.5  430.11  5359.1  435.82  5457.0  433.59
  5515.6  435.53  5582.7  441.08  5613.5  445.01  5658.2  451.99  5680.6  453.60
#Mann=5,-1,0
  4302.6    0.05       0  4849.6    0.12       0  4978.4    0.05       0
  4985.9    0.03       0  4993.2    0.05       0
Bank Sta=4569.1,5140.6
Exp/Cntr=0.3,0.1

Type RM Length L Ch R = 1,10649,446,446,446
BEGIN DESCRIPTION:
BRUSHY BRANCH 8.0
END DESCRIPTION:
XS GIS Cut Line= 3
      2848274.98      7056974.98      2847909.76      7056471.24
      2847024.99      7056525.00
#Sta/Elev= 30
  4388.6  455.14  4481.7  449.41  4502.6  445.75  4532.0  444.73  4567.6  439.66
  4582.3  439.26  4603.1  436.03  4617.8  435.96  4653.4  431.19  4703.6  429.02
  4746.2  425.07  4807.8  421.93  4855.5  420.27  4904.7  419.11  4975.8  420.38
  4990.5  416.70  4993.0  412.74  4993.5  411.94  5000.4  412.74  5005.2  414.18
  5010.6  420.04  5025.6  420.61  5185.9  421.07  5248.7  419.88  5366.9  421.93
  5406.3  424.75  5616.7  426.68  5736.9  435.99  5813.4  445.10  5897.2  451.15
#Mann=6,-1,0
  4388.6    0.05       0  4746.2    0.07       0  4855.5    0.12       0
  4993.0    0.07       0  5000.4    0.12       0  5248.7    0.05       0
Bank Sta=4807.8,5366.9
Exp/Cntr=0.3,0.1

Type RM Length L Ch R = 1,10203,503,503,503
BEGIN DESCRIPTION:
BRUSHY BRANCH 7.0
END DESCRIPTION:
XS GIS Cut Line= 3
      2848425.00      7056225.00      2847975.00      7056175.00
      2847275.00      7055675.00
#Sta/Elev= 30
  4558.9  454.88  4619.3  455.01  4675.0  452.01  4770.2  434.28  4840.6  426.60
  4873.5  420.84  4890.9  418.29  4981.5  419.03  4991.5  412.68  4997.9  411.14
  4998.5  410.34  5005.4  411.14  5009.2  417.88  5019.0  419.55  5090.3  418.36
  5327.6  420.12  5413.5  421.18  5419.7  418.80  5428.3  420.14  5434.4  417.79
  5449.2  417.98  5455.3  421.03  5470.1  422.07  5532.1  420.84  5567.0  421.59
  5699.9  425.20  5713.4  431.95  5722.0  433.61  5835.0  445.89  5871.9  447.52
#Mann=6,-1,0
  4558.9    0.05       0  4675.0    0.12       0  4997.9    0.07       0
  5005.4    0.12       0  5327.6    0.16       0  5567.0    0.05       0
Bank Sta=4873.5,5532.1
Exp/Cntr=0.3,0.1

Type RM Length L Ch R = 1,9700,754,754,754
BEGIN DESCRIPTION:
BRUSHY BRANCH 6.0
END DESCRIPTION:
XS GIS Cut Line= 3
      2848490.11      7056120.49      2848140.10      7055820.49
      2847324.96      7055574.99
#Sta/Elev= 30
  4537.0  448.25  4594.5  447.26  4715.0  435.43  4750.4  433.90  4814.0  426.54
  4898.4  422.74  4930.4  419.76  4934.8  418.00  4984.2  417.63  4991.5  412.41
  5000.4  409.49  5001.0  408.69  5007.9  409.49  5013.8  417.62  5024.2  418.41
  5103.1  418.44  5108.3  417.49  5118.2  411.03  5128.6  416.84  5136.1  418.66
  5240.4  417.14  5278.6  419.40  5295.7  417.15  5344.6  419.41  5377.6  417.88
  5478.0  419.27  5528.0  419.76  5637.1  430.14  5761.5  443.37  5849.3  447.63
#Mann=6,-1,0
  4537.0    0.16       0  4898.4    0.12       0  5000.4    0.07       0
  5007.9    0.12       0  5478.0    0.16       0  5637.1    0.05       0
Bank Sta=4930.4,5528
Exp/Cntr=0.3,0.1

Type RM Length L Ch R = 1,8946,196,196,196
BEGIN DESCRIPTION:
Mapping XS 897db8d4
END DESCRIPTION:
XS GIS Cut Line= 3
      2848928.66      7055511.99      2848455.59      7055451.23
      2847539.85      7055446.89
#Sta/Elev= 30
  4519.4  442.55  4599.5  434.46  4690.7  424.78  4770.3  419.74  4809.8  418.72
  4850.6  417.79  4904.7  416.18  4956.6  416.97  4966.7  414.17  4972.6  408.86
  4973.3  408.06  4980.9  408.86  4999.1  411.57  5016.9  416.74  5226.1  417.38
  5266.9  415.72  5286.9  418.51  5325.1  418.73  5346.9  416.36  5366.9  418.01
  5376.9  416.65  5396.9  417.87  5406.9  416.96  5416.1  418.72  5523.2  419.80
  5586.9  418.76  5616.9  420.30  5820.4  423.07  5887.0  425.15  5912.1  427.64
#Mann=10,-1,0
  4519.4    0.05       0  4599.5    0.08       0  4850.6    0.05       0
  4904.7    0.08       0  4972.6    0.07       0  4980.9    0.08       0
  5226.1    0.07       0  5325.1    0.12       0  5523.2    0.08       0
  5820.4    0.05       0
Bank Sta=4809.8,5416.1
Exp/Cntr=0.3,0.1

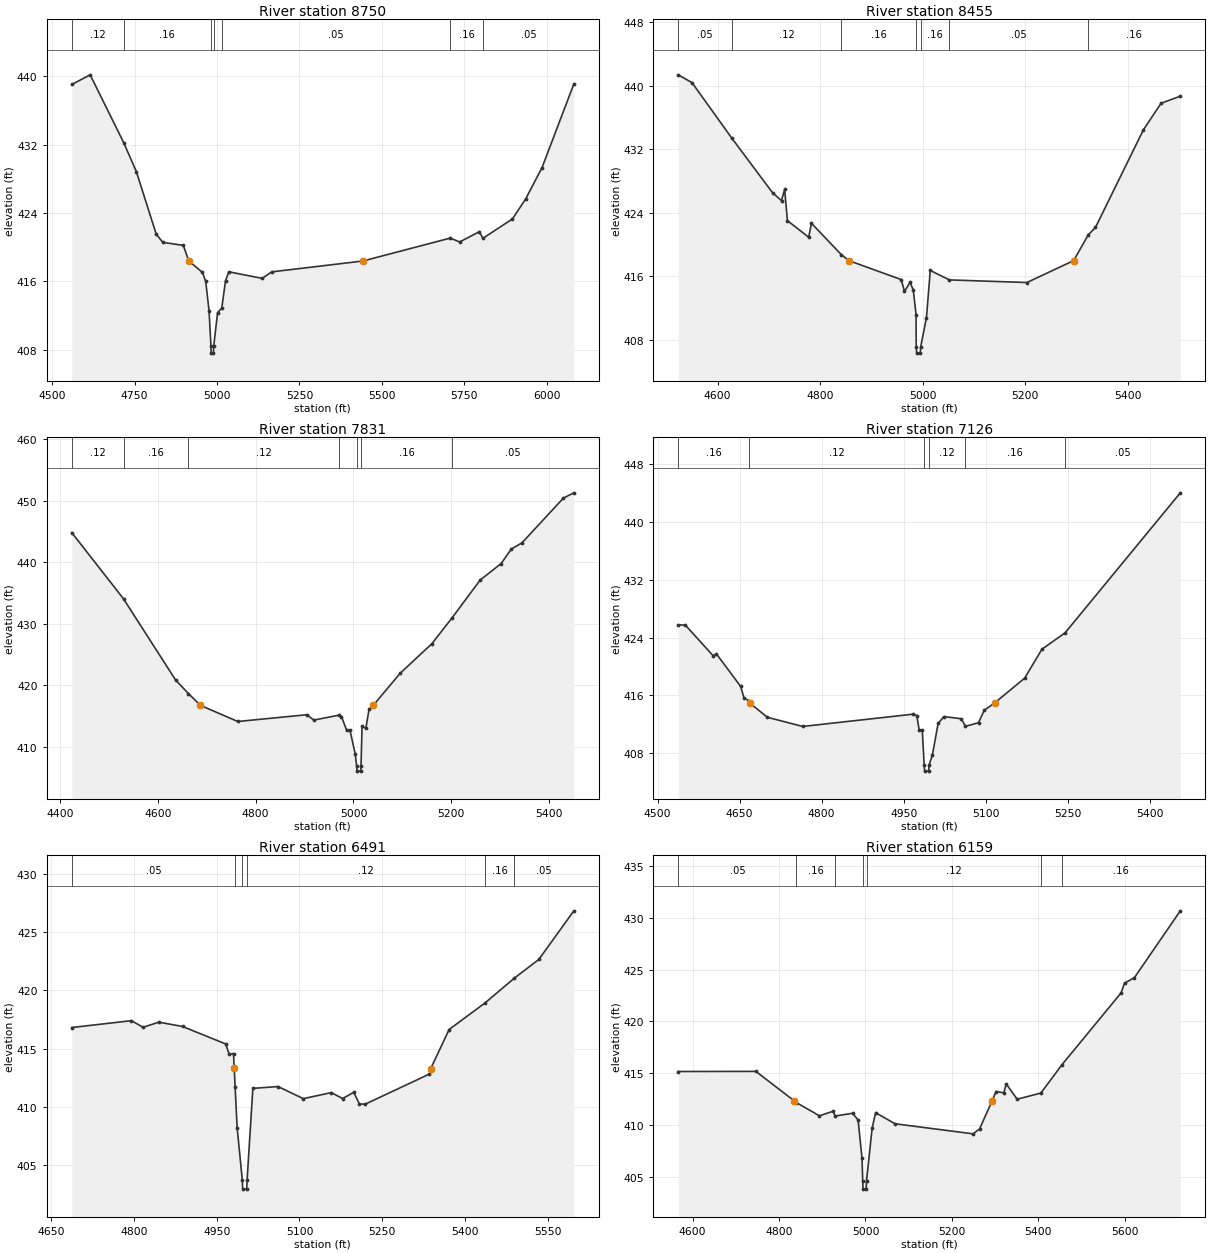
Type RM Length L Ch R = 1,8750,295,295,295
BEGIN DESCRIPTION:
Mapping XS ada2febe
END DESCRIPTION:
XS GIS Cut Line= 3
      2848980.73      7055329.70      2848538.06      7055303.66
      2847458.63      7055273.31
#Sta/Elev= 30
  4559.4  439.02  4615.2  440.15  4717.2  432.20  4755.5  428.82  4815.6  421.52
  4835.6  420.56  4897.8  420.21  4914.4  418.38  4955.8  417.06  4965.8  415.99
  4975.9  412.56  4981.7  408.41  4982.4  407.61  4989.3  407.61  4990.0  408.41
  5001.9  412.36  5014.4  412.85  5025.9  416.07  5035.9  417.12  5137.0  416.35
  5166.0  417.11  5442.6  418.38  5707.6  421.06  5736.2  420.61  5796.2  421.81
  5806.7  421.03  5896.3  423.30  5936.3  425.62  5986.3  429.31  6082.7  439.08
#Mann=7,-1,0
  4559.4    0.12       0  4717.2    0.16       0  4981.7    0.07       0
  4990.0    0.16       0  5014.4    0.05       0  5707.6    0.16       0
  5806.7    0.05       0
Bank Sta=4914.4,5442.6
Exp/Cntr=0.3,0.1

Type RM Length L Ch R = 1,8455,624,624,624
BEGIN DESCRIPTION:
Mapping XS ed63b1a1
END DESCRIPTION:
XS GIS Cut Line= 3
      2849119.69      7055242.91      2848689.97      7055056.26
      2848195.14      7054930.38
#Sta/Elev= 30
  4523.1  441.39  4550.0  440.40  4627.3  433.44  4707.1  426.54  4724.5  425.55
  4730.6  426.96  4736.0  423.03  4777.5  420.95  4782.9  422.70  4841.1  418.75
  4855.7  418.00  4958.0  415.61  4964.3  414.11  4975.2  415.27  4981.4  414.31
  4986.9  411.21  4987.2  407.15  4988.0  406.35  4995.1  406.35  4995.9  407.15
  5007.1  410.78  5014.6  416.76  5051.8  415.57  5203.1  415.24  5294.2  418.00
  5322.8  421.25  5336.8  422.18  5430.1  434.45  5464.7  437.81  5502.2  438.70
#Mann=7,-1,0
  4523.1    0.05       0  4627.3    0.12       0  4841.1    0.16       0
  4987.2    0.07       0  4995.9    0.16       0  5051.8    0.05       0
  5322.8    0.16       0
Bank Sta=4855.7,5294.2
Exp/Cntr=0.3,0.1

Type RM Length L Ch R = 1,7831,705,705,705
BEGIN DESCRIPTION:
BRUSHY BRANCH 3.0
END DESCRIPTION:
XS GIS Cut Line= 3
      2849224.97      7055024.97      2848825.00      7054625.00
      2848525.02      7054275.02
#Sta/Elev= 30
  4424.0  444.80  4529.9  434.02  4636.1  420.86  4662.4  418.64  4687.2  416.71
  4763.4  414.09  4904.8  415.19  4918.9  414.32  4969.6  415.11  4975.5  414.90
  4986.1  412.65  4992.9  412.65  5003.4  408.87  5006.6  406.82  5007.4  406.02
  5014.6  406.02  5015.4  406.82  5017.6  413.28  5025.3  412.97  5031.9  416.08
  5040.4  416.71  5095.6  421.94  5160.3  426.74  5201.1  430.89  5259.1  437.09
  5301.9  439.77  5322.8  442.13  5344.7  443.15  5429.2  450.41  5450.6  451.27
#Mann=7,-1,0
  4424.0    0.12       0  4529.9    0.16       0  4662.4    0.12       0
  4969.6    0.16       0  5006.6    0.07       0  5015.4    0.16       0
  5201.1    0.05       0
Bank Sta=4687.2,5040.4
Exp/Cntr=0.3,0.1

Type RM Length L Ch R = 1,7126,635,635,635
BEGIN DESCRIPTION:
BRUSHY BRANCH 2.0
END DESCRIPTION:
XS GIS Cut Line= 3
      2849488.55      7054478.99      2849125.00      7054225.00
      2848675.03      7054075.01
#Sta/Elev= 30
  4537.8  425.77  4550.9  425.72  4601.5  421.49  4607.6  421.74  4651.9  417.23
  4658.1  415.60  4666.4  415.27  4668.3  414.95  4700.7  412.95  4765.4  411.68
  4967.8  413.39  4973.9  413.18  4978.2  411.20  4983.9  411.20  4987.4  406.29
  4988.2  405.49  4995.4  405.49  4996.2  406.29  5002.4  407.72  5012.9  412.11
  5023.4  413.05  5055.1  412.75  5062.9  411.70  5086.7  412.20  5097.2  413.92
  5116.4  414.95  5171.0  418.37  5202.6  422.38  5245.0  424.66  5455.6  444.06
#Mann=6,-1,0
  4537.8    0.16       0  4666.4    0.12       0  4987.4    0.07       0
  4996.2    0.12       0  5062.9    0.16       0  5245.0    0.05       0
Bank Sta=4668.3,5116.4
Exp/Cntr=0.3,0.1

Type RM Length L Ch R = 1,6491,332,332,332
BEGIN DESCRIPTION:
Mapping XS ad2cdbe6
END DESCRIPTION:
XS GIS Cut Line= 3
      2849731.64      7054140.47      2849488.58      7053940.81
      2848902.60      7053832.29
#Sta/Elev= 30
  4687.1  416.80  4795.4  417.39  4816.3  416.82  4845.0  417.26  4888.0  416.89
  4966.2  415.39  4972.7  414.49  4980.4  414.57  4981.7  413.29  4983.4  411.66
  4987.0  408.22  4996.3  403.74  4997.1  402.94  5004.3  402.94  5005.1  403.74
  5015.5  411.58  5061.1  411.74  5107.0  410.70  5157.8  411.22  5178.2  410.71
  5198.5  411.24  5208.7  410.25  5218.9  410.22  5335.7  412.81  5338.1  413.28
  5371.4  416.63  5436.8  418.92  5489.8  421.04  5534.1  422.64  5597.6  426.81
#Mann=6,-1,0
  4687.1    0.05       0  4983.4    0.12       0  4996.3    0.07       0
  5005.1    0.12       0  5436.8    0.16       0  5489.8    0.05       0
Bank Sta=4981.7,5338.1
Exp/Cntr=0.3,0.1

Type RM Length L Ch R = 1,6159,528,528,528
BEGIN DESCRIPTION:
Mapping XS a8a98f8f
END DESCRIPTION:
XS GIS Cut Line= 4
      2849906.11      7053985.07      2849827.99      7053837.51
      2849593.61      7053720.32      2848903.51      7053472.93
#Sta/Elev= 30
  4566.6  415.17  4746.4  415.18  4835.1  412.34  4840.2  412.17  4893.4  410.90
  4925.3  411.34  4929.8  410.88  4970.0  411.14  4982.9  410.50  4992.0  406.79
  4993.6  404.63  4994.4  403.83  5001.6  403.83  5002.4  404.63  5015.4  409.70
  5023.4  411.20  5068.5  410.13  5249.1  409.16  5264.1  409.64  5293.1  412.34
  5302.2  413.24  5320.3  413.11  5325.6  413.98  5351.1  412.50  5405.9  413.09
  5454.7  415.82  5591.8  422.76  5599.6  423.69  5622.5  424.22  5728.7  430.66
#Mann=7,-1,0
  4566.6    0.05       0  4840.2    0.16       0  4929.8    0.12       0
  4993.6    0.07       0  5002.4    0.12       0  5405.9    0.05       0
  5454.7    0.16       0
Bank Sta=4835.1,5293.1
Exp/Cntr=0.3,0.1

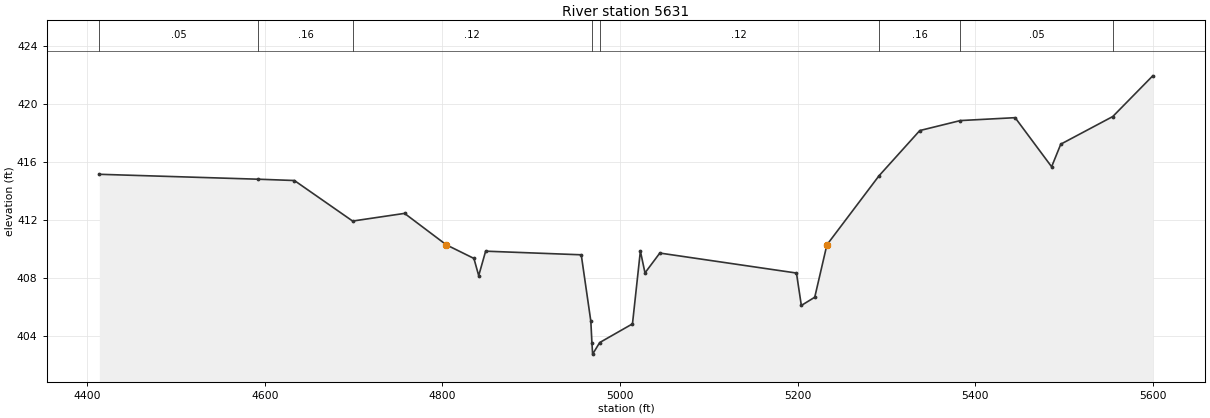
Type RM Length L Ch R = 1,5631,0,0,0
BEGIN DESCRIPTION:
BRUSHY BRANCH 1.0
END DESCRIPTION:
XS GIS Cut Line= 3
      2849927.80      7053959.00      2849710.80      7053416.50
      2849124.01      7053281.09
#Sta/Elev= 30
  4413.5  415.17  4592.4  414.83  4633.2  414.74  4698.8  411.94  4757.3  412.47
  4804.3  410.30  4835.4  409.36  4840.8  408.17  4848.6  409.86  4956.3  409.61
  4967.1  405.02  4968.3  403.55  4969.1  402.75  4977.1  403.55  5014.0  404.84
  5022.9  409.87  5028.1  408.36  5044.8  409.73  5198.7  408.35  5204.2  406.11
  5219.3  406.68  5233.0  410.30  5291.6  415.06  5337.6  418.19  5383.3  418.88
  5445.0  419.08  5486.1  415.69  5496.4  417.25  5555.0  419.16  5600.0  421.97
#Mann=8,-1,0
  4413.5    0.05       0  4592.4    0.16       0  4698.8    0.12       0
  4968.3    0.07       0  4977.1    0.12       0  5291.6    0.16       0
  5383.3    0.05       0  5555.0    0.16       0
Bank Sta=4804.3,5233
Exp/Cntr=0.3,0.1

Chan Stop Cuts=-1