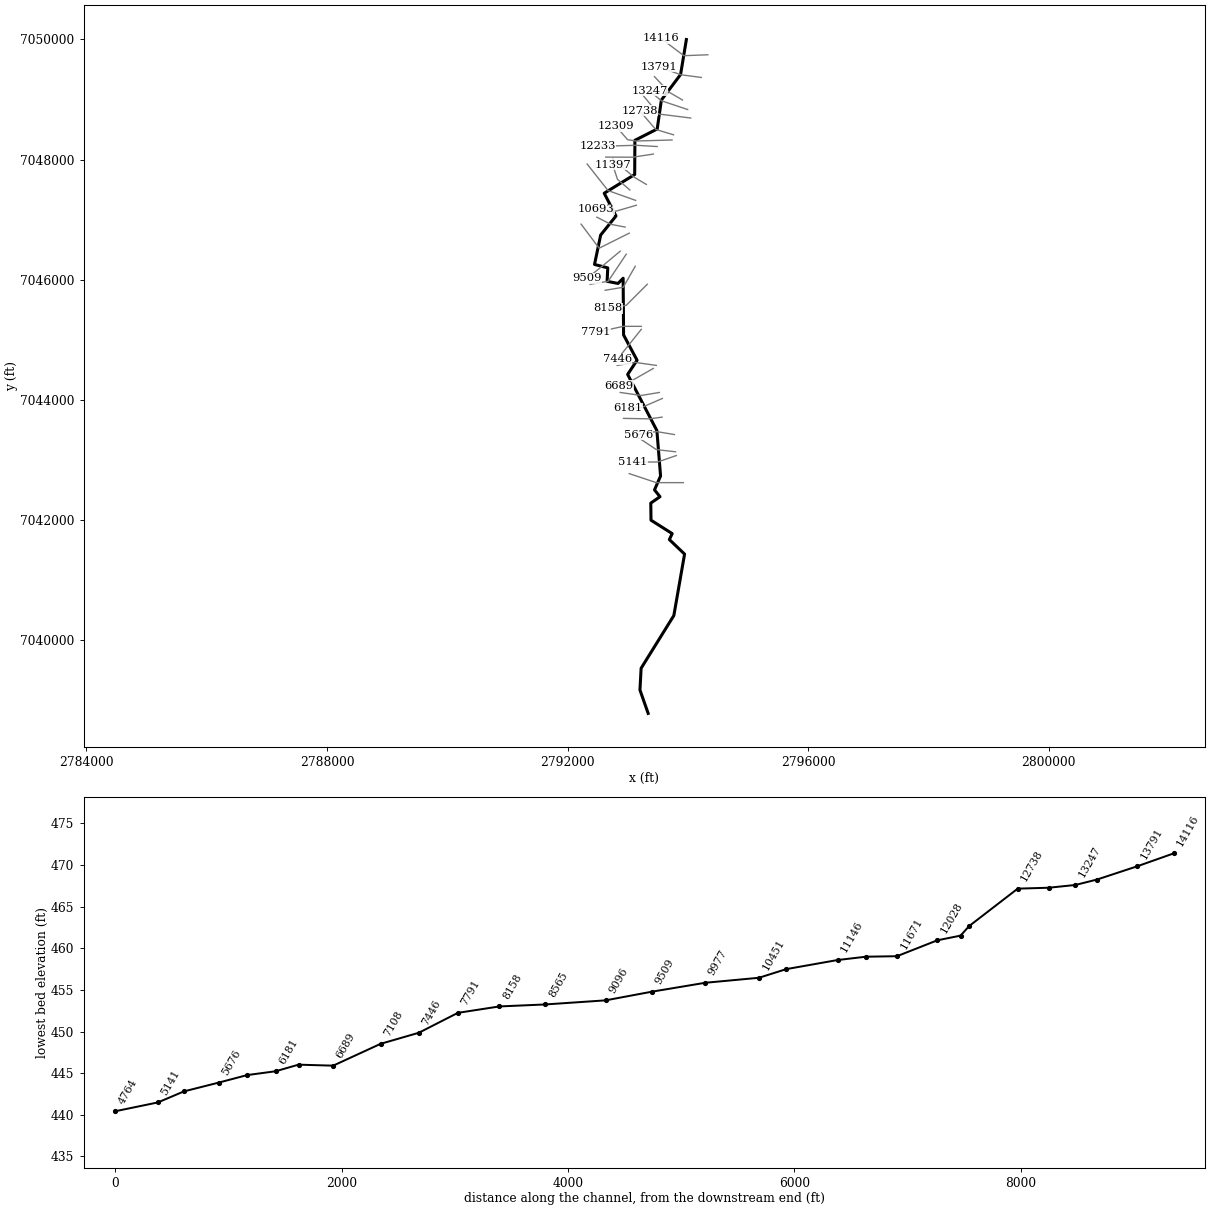
--- BUCKEYE BRANCH.prj (project) ---

Proj Title=BUCKEYE BRANCH Base Level Engineering
Current Plan=p01
Default Exp/Contr=0.3,0.1
English Units
Geom File=g01
Flow File=f01
Plan File=p01
BEGIN DESCRIPTION:
BUCKEYE BRANCH
END DESCRIPTION:

--- BUCKEYE BRANCH.p01 (plan) ---

Plan Title=Multiple Run
Short Identifier=Multiple
Geom File=g01
Flow File=f01
Subcritical Flow
K Sum by GR= 0
Std Step Tol= 0.01
Critical Tol= 0.01
Num of Std Step Trials= 20
Max Error Tol= 0.3
Flow Tol Ratio= 0.001
Split Flow NTrial= 30
Split Flow Tol= 0.02
Split Flow Ratio= 0.02
Log Output Level= 0
Friction Slope Method= 1
Unsteady Friction Slope Method= 2
Unsteady Bridges Friction Slope Method= 1
Parabolic Critical Depth
Global Vel Dist=  1 , 1 , 1
Global Log Level= 0
CheckData=True
Encroach Param= -1, 0, 0, 0
BEGIN DESCRIPTION:
Multiple Run
END DESCRIPTION:

--- BUCKEYE BRANCH.f01 (steady flow) ---

Flow Title=Multiple
Number of Profiles=7
Profile Names=10-year,25-year,50-year,1pct_min,100-year,1pct_plu,500-year
River Rch & RM= BUCKEYE BRANCH,Reach-1,14116
     241     303     349     200     400     797     525
River Rch & RM= BUCKEYE BRANCH,Reach-1,7108
     569     752     899     534    1065    2126    1497
Boundary for River Rch & Prof#=BUCKEYE BRANCH,Reach-1,1
Up Type=0
Dn Type=3
Dn Slope=0.005
Boundary for River Rch & Prof#=BUCKEYE BRANCH,Reach-1,2
Up Type=0
Dn Type=3
Dn Slope=0.005
Boundary for River Rch & Prof#=BUCKEYE BRANCH,Reach-1,3
Up Type=0
Dn Type=3
Dn Slope=0.005
Boundary for River Rch & Prof#=BUCKEYE BRANCH,Reach-1,4
Up Type=0
Dn Type=3
Dn Slope=0.005
Boundary for River Rch & Prof#=BUCKEYE BRANCH,Reach-1,5
Up Type=0
Dn Type=3
Dn Slope=0.005
Boundary for River Rch & Prof#=BUCKEYE BRANCH,Reach-1,6
Up Type=0
Dn Type=3
Dn Slope=0.005
Boundary for River Rch & Prof#=BUCKEYE BRANCH,Reach-1,7
Up Type=0
Dn Type=3
Dn Slope=0.005

--- BUCKEYE BRANCH.g01 (geometry) ---

Geom Title=Existing Conditions

River Reach=BUCKEYE BRANCH,Reach-1
Reach XY= 30
      2793974.80      7049995.92      2793878.43      7049413.75
      2793559.13      7048989.24      2793490.05      7048508.02
      2793119.04      7048319.55      2793115.59      7047750.71
      2792609.02      7047439.26      2792804.71      7047060.57
      2792549.99      7046743.60      2792447.83      7046254.40
      2792668.14      7046197.23      2792656.90      7045973.83
      2792838.62      7045938.45      2792923.56      7046024.76
      2792931.01      7045081.67      2793155.31      7044661.45
      2792998.55      7044425.13      2793484.76      7043490.36
      2793545.70      7042735.66      2793445.11      7042504.24
      2793535.96      7042390.93      2793383.25      7042284.50
      2793386.85      7042000.39      2793739.21      7041777.06
      2793691.67      7041678.34      2793944.78      7041436.36
      2793766.46      7040414.32      2793222.61      7039537.55
      2793203.03      7039175.99      2793339.51      7038786.72

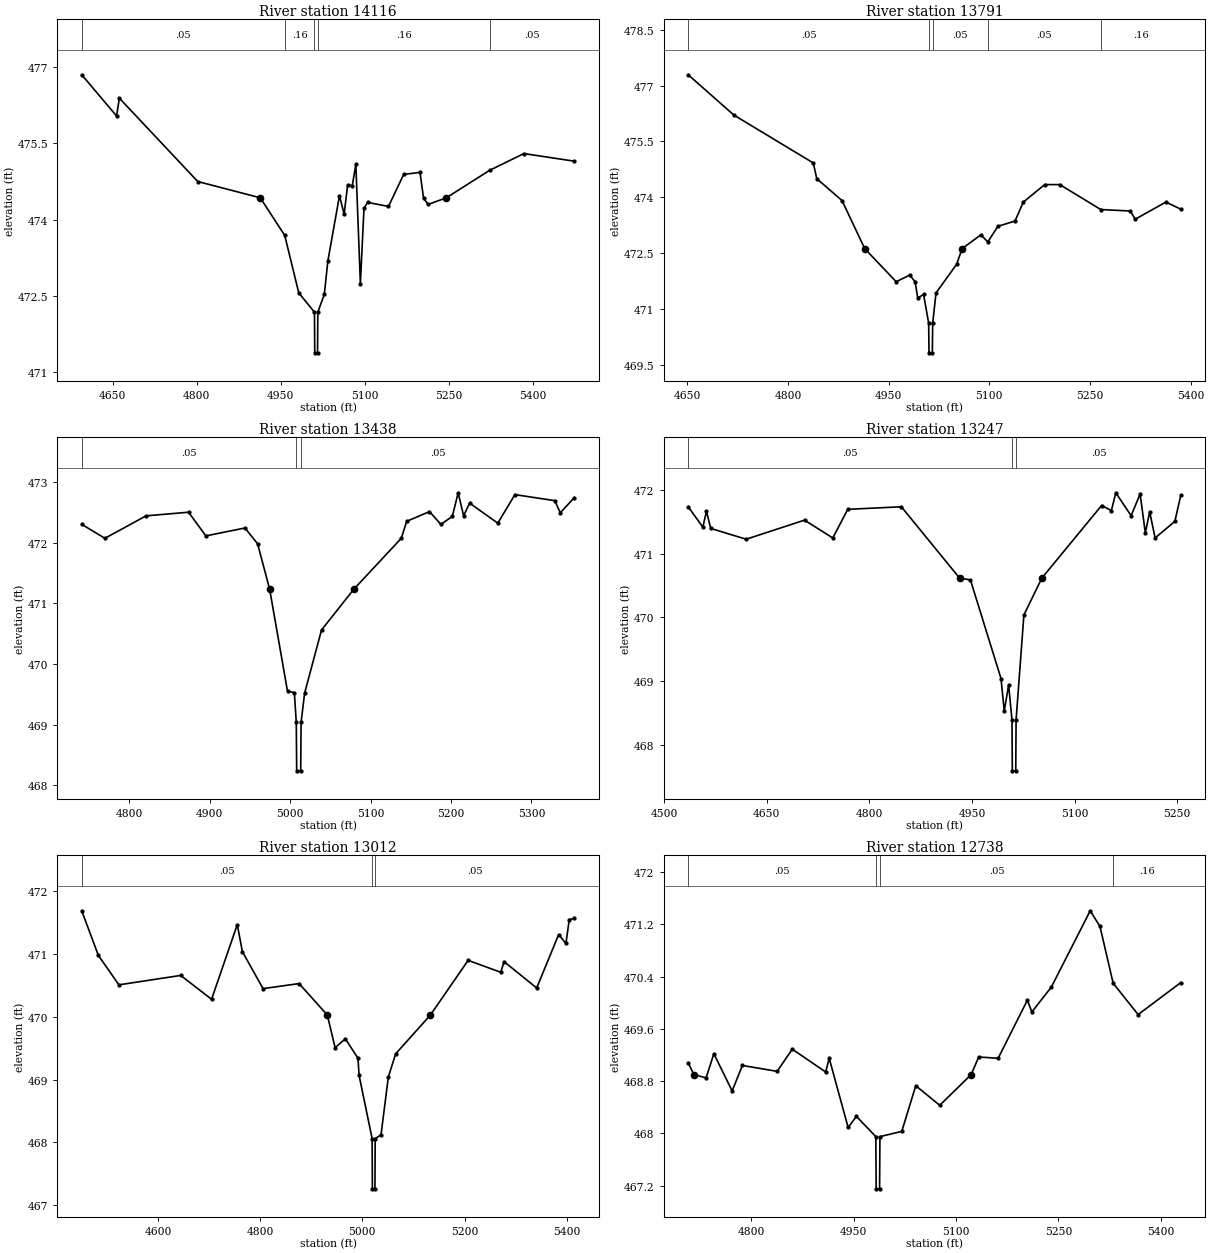
Type RM Length L Ch R = 1,14116,325,325,325
BEGIN DESCRIPTION:
BUCKEYE BRANCH 25.0
END DESCRIPTION:
XS GIS Cut Line= 3
      2794331.74      7049742.45      2793933.35      7049726.83
      2793550.53      7050015.89
#Sta/Elev= 30
  4595.0  476.85  4657.1  476.04  4662.1  476.39  4801.9  474.75  4913.4  474.43
  4957.0  473.69  4982.0  472.56  5010.0  472.18  5010.5  471.38  5015.5  471.38
  5016.0  472.18  5027.6  472.53  5033.8  473.18  5054.6  474.47  5062.9  474.11
  5069.2  474.68  5077.5  474.67  5083.8  475.09  5091.9  472.74  5098.3  474.22
  5104.6  474.34  5142.0  474.26  5169.1  474.89  5198.2  474.93  5204.6  474.42
  5212.8  474.30  5245.2  474.43  5322.3  474.97  5383.5  475.30  5473.4  475.15
#Mann=5,-1,0
  4595.0    0.05       0  4957.0    0.16       0  5010.0    0.07       0
  5016.0    0.16       0  5322.3    0.05       0
Bank Sta=4913.4,5245.2
Exp/Cntr=0.3,0.1

Type RM Length L Ch R = 1,13791,353,353,353
BEGIN DESCRIPTION:
Mapping XS 3d2cccb7
END DESCRIPTION:
XS GIS Cut Line= 3
      2794222.35      7049365.14      2793882.07      7049410.27
      2793514.06      7049542.20
#Sta/Elev= 30
  4651.2  477.29  4719.1  476.21  4837.7  474.92  4842.8  474.50  4880.5  473.91
  4914.3  472.62  4961.2  471.73  4981.4  471.91  4989.4  471.73  4993.4  471.29
  5002.0  471.39  5009.6  470.62  5010.1  469.82  5015.1  469.82  5015.6  470.62
  5020.6  471.43  5051.3  472.20  5059.5  472.62  5087.4  472.99  5097.8  472.80
  5112.8  473.22  5138.3  473.36  5150.7  473.87  5182.6  474.34  5205.1  474.34
  5266.1  473.67  5310.0  473.63  5317.5  473.41  5363.2  473.87  5385.4  473.68
#Mann=5,-1,0
  4651.2    0.05       0  5009.6    0.03       0  5015.6    0.05       0
  5097.8    0.05       0  5266.1    0.16       0
Bank Sta=4914.3,5059.5
Exp/Cntr=0.3,0.1

Type RM Length L Ch R = 1,13438,191,191,191
BEGIN DESCRIPTION:
Mapping XS 3a61e1a4
END DESCRIPTION:
XS GIS Cut Line= 3
      2793909.89      7048990.11      2793684.16      7049122.08
      2793444.57      7049379.03
#Sta/Elev= 30
  4740.6  472.30  4769.4  472.07  4820.6  472.44  4873.5  472.50  4895.0  472.11
  4943.7  472.24  4959.4  471.98  4974.4  471.23  4996.6  469.55  5005.1  469.53
  5007.5  469.04  5008.0  468.24  5013.0  468.24  5013.5  469.04  5017.9  469.52
  5038.9  470.56  5079.0  471.23  5138.1  472.07  5144.9  472.35  5173.2  472.51
  5187.4  472.30  5201.6  472.43  5208.9  472.82  5215.7  472.44  5223.1  472.65
  5258.2  472.32  5279.5  472.79  5329.1  472.69  5335.9  472.49  5353.4  472.74
#Mann=3,-1,0
  4740.6    0.05       0  5007.5    0.03       0  5013.5    0.05       0
Bank Sta=4974.4,5079
Exp/Cntr=0.3,0.1

Type RM Length L Ch R = 1,13247,235,235,235
BEGIN DESCRIPTION:
Mapping XS a31cbaa0
END DESCRIPTION:
XS GIS Cut Line= 3
      2793996.20      7048831.84      2793562.63      7048976.25
      2793358.92      7049141.98
#Sta/Elev= 30
  4535.5  471.74  4556.9  471.42  4562.2  471.67  4568.4  471.40  4620.2  471.23
  4705.4  471.53  4746.7  471.25  4768.6  471.70  4846.9  471.74  4931.9  470.62
  4947.8  470.59  4992.5  469.04  4997.2  468.53  5003.6  468.94  5008.5  468.39
  5009.0  467.59  5014.0  467.59  5014.5  468.39  5025.9  470.04  5052.2  470.62
  5139.4  471.76  5153.7  471.68  5160.2  471.96  5182.5  471.60  5195.7  471.94
  5203.3  471.33  5209.7  471.66  5217.6  471.25  5246.4  471.51  5255.1  471.92
#Mann=3,-1,0
  4535.5    0.05       0  5008.5    0.03       0  5014.5    0.05       0
Bank Sta=4931.9,5052.2
Exp/Cntr=0.3,0.1

Type RM Length L Ch R = 1,13012,274,274,274
BEGIN DESCRIPTION:
Mapping XS ce8f614c
END DESCRIPTION:
XS GIS Cut Line= 3
      2794047.27      7048690.35      2793510.55      7048757.50
      2793240.73      7049084.04
#Sta/Elev= 30
  4450.5  471.69  4483.0  470.98  4523.3  470.51  4644.3  470.66  4704.7  470.28
  4755.1  471.47  4765.0  471.04  4805.5  470.45  4876.1  470.53  4931.3  470.03
  4946.6  469.51  4966.8  469.65  4991.4  469.34  4993.5  469.07  5019.1  468.06
  5019.6  467.26  5024.6  467.26  5025.1  468.06  5036.5  468.12  5050.8  469.04
  5065.1  469.41  5133.3  470.03  5207.1  470.90  5271.0  470.71  5277.4  470.88
  5341.3  470.46  5384.3  471.31  5398.6  471.17  5405.1  471.55  5415.0  471.57
#Mann=3,-1,0
  4450.5    0.05       0  5019.1    0.03       0  5025.1    0.05       0
Bank Sta=4931.3,5133.3
Exp/Cntr=0.3,0.1

Type RM Length L Ch R = 1,12738,429,429,429
BEGIN DESCRIPTION:
Mapping XS 90d492cb
END DESCRIPTION:
XS GIS Cut Line= 3
      2793760.96      7048411.16      2793465.41      7048500.55
      2793195.63      7048813.16
#Sta/Elev= 30
  4707.5  469.08  4715.9  468.90  4733.7  468.85  4745.1  469.22  4771.9  468.65
  4786.9  469.04  4837.8  468.95  4860.0  469.29  4908.9  468.94  4914.1  469.15
  4941.8  468.09  4954.0  468.26  4982.4  467.95  4982.9  467.15  4987.9  467.15
  4988.4  467.95  5020.4  468.03  5040.9  468.73  5076.0  468.43  5122.1  468.90
  5133.1  469.17  5161.6  469.15  5204.4  470.04  5211.0  469.86  5239.5  470.24
  5296.5  471.41  5310.8  471.17  5330.1  470.30  5366.7  469.82  5429.2  470.31
#Mann=4,-1,0
  4707.5    0.05       0  4982.4   0.035       0  4988.4    0.05       0
  5330.1    0.16       0
Bank Sta=4715.9,5122.1
Exp/Cntr=0.3,0.1

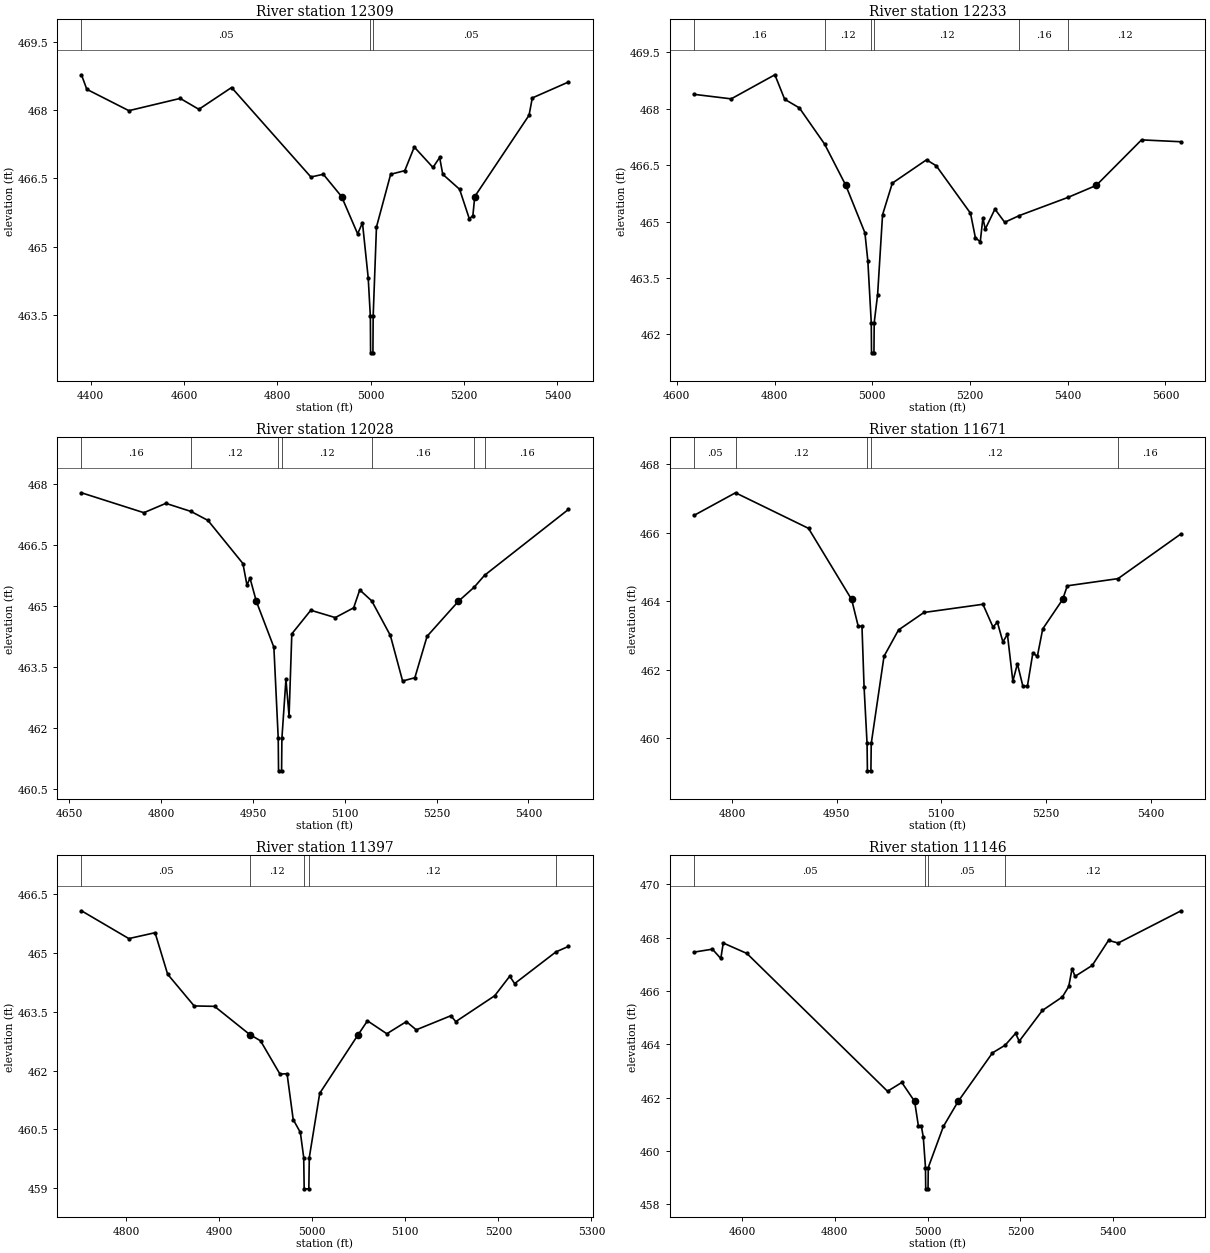
Type RM Length L Ch R = 1,12309,76,76,76
BEGIN DESCRIPTION:
Mapping XS b436020c
END DESCRIPTION:
XS GIS Cut Line= 4
      2793736.53      7048325.11      2793139.33      7048307.74
      2792997.43      7048330.13      2792799.43      7048558.68
#Sta/Elev= 30
  4380.0  468.78  4391.5  468.46  4481.6  467.99  4591.6  468.26  4631.6  468.02
  4701.7  468.50  4871.7  466.53  4898.3  466.59  4937.4  466.10  4971.8  465.28
  4982.2  465.52  4994.5  464.31  4999.1  463.46  4999.6  462.66  5004.6  462.66
  5005.1  463.46  5012.2  465.43  5042.6  466.59  5072.9  466.67  5093.2  467.19
  5133.3  466.74  5147.6  466.96  5154.2  466.59  5190.3  466.26  5211.2  465.61
  5218.8  465.68  5222.8  466.10  5339.2  467.89  5346.1  468.27  5423.5  468.62
#Mann=3,-1,0
  4380.0    0.05       0  4999.1    0.03       0  5005.1    0.05       0
Bank Sta=4937.4,5222.8
Exp/Cntr=0.3,0.1

Type RM Length L Ch R = 1,12233,205,205,205
BEGIN DESCRIPTION:
Mapping XS 1d7a160e
END DESCRIPTION:
XS GIS Cut Line= 3
      2793490.02      7048215.73      2793141.06      7048236.56
      2792494.18      7048219.00
#Sta/Elev= 30
  4635.3  468.38  4711.2  468.26  4800.6  468.90  4820.6  468.25  4850.7  468.02
  4902.3  467.06  4945.8  465.96  4984.9  464.70  4990.9  463.95  4997.9  462.31
  4998.4  461.51  5003.4  461.51  5003.9  462.31  5010.9  463.06  5021.0  465.18
  5041.0  466.02  5111.0  466.64  5131.0  466.48  5201.0  465.22  5211.0  464.57
  5221.0  464.46  5226.3  465.09  5231.3  464.80  5251.0  465.33  5271.0  464.98
  5301.3  465.16  5400.3  465.64  5458.4  465.96  5551.1  467.17  5632.0  467.12
#Mann=6,-1,0
  4635.3    0.16       0  4902.3    0.12       0  4997.9    0.07       0
  5003.9    0.12       0  5301.3    0.16       0  5400.3    0.12       0
Bank Sta=4945.8,5458.4
Exp/Cntr=0.3,0.1

Type RM Length L Ch R = 1,12028,357,357,357
BEGIN DESCRIPTION:
Mapping XS 243e79d6
END DESCRIPTION:
XS GIS Cut Line= 3
      2793425.82      7048090.74      2793082.04      7048038.65
      2792634.15      7048040.38
#Sta/Elev= 30
  4669.8  467.79  4771.8  467.30  4807.7  467.53  4848.9  467.33  4876.5  467.11
  4933.6  466.05  4940.2  465.52  4945.2  465.69  4955.5  465.12  4984.2  463.99
  4991.3  461.75  4991.8  460.95  4996.8  460.95  4997.3  461.75  5003.9  463.20
  5009.0  462.30  5013.5  464.32  5044.5  464.90  5084.5  464.72  5114.5  464.96
  5124.5  465.40  5144.1  465.13  5174.5  464.28  5194.5  463.16  5214.5  463.24
  5234.5  464.26  5285.6  465.12  5311.6  465.47  5328.4  465.76  5465.4  467.38
#Mann=7,-1,0
  4669.8    0.16       0  4848.9    0.12       0  4991.3    0.07       0
  4997.3    0.12       0  5144.1    0.16       0  5311.6    0.12       0
  5328.4    0.16       0
Bank Sta=4955.5,5285.6
Exp/Cntr=0.3,0.1

Type RM Length L Ch R = 1,11671,274,274,274
BEGIN DESCRIPTION:
Mapping XS 25189e72
END DESCRIPTION:
XS GIS Cut Line= 3
      2793309.49      7047585.51      2793104.60      7047707.05
      2792753.91      7048003.93
#Sta/Elev= 30
  4745.8  466.51  4805.1  467.17  4909.7  466.13  4971.5  464.05  4980.9  463.27
  4986.3  463.27  4989.3  461.50  4993.6  459.84  4994.1  459.04  4999.1  459.04
  4999.6  459.84  5017.9  462.39  5038.7  463.16  5075.1  463.67  5159.6  463.91
  5173.9  463.25  5180.4  463.38  5188.2  462.81  5194.7  463.03  5202.5  461.66
  5209.0  462.17  5216.8  461.52  5223.3  461.51  5231.1  462.48  5237.6  462.39
  5245.3  463.19  5273.8  464.05  5280.5  464.45  5353.2  464.66  5443.5  465.97
#Mann=5,-1,0
  4745.8    0.05       0  4805.1    0.12       0  4993.6    0.07       0
  4999.6    0.12       0  5353.2    0.16       0
Bank Sta=4971.5,5273.8
Exp/Cntr=0.3,0.1

Type RM Length L Ch R = 1,11397,251,251,251
BEGIN DESCRIPTION:
Mapping XS 237ee8d5
END DESCRIPTION:
XS GIS Cut Line= 3
      2793034.87      7047493.59      2792829.99      7047670.69
      2792750.18      7047910.13
#Sta/Elev= 30
  4752.1  466.08  4803.0  465.37  4831.2  465.52  4844.7  464.46  4873.2  463.65
  4895.1  463.64  4932.9  462.92  4933.0  462.92  4944.5  462.76  4965.4  461.91
  4973.0  461.92  4979.6  460.75  4987.3  460.42  4990.9  459.78  4991.4  458.98
  4996.4  458.98  4996.9  459.78  5008.1  461.42  5049.5  462.92  5059.4  463.27
  5080.2  462.94  5101.2  463.25  5111.8  463.04  5149.0  463.40  5154.3  463.25
  5196.1  463.91  5212.3  464.41  5217.5  464.22  5261.9  465.03  5275.3  465.17
#Mann=5,-1,0
  4752.1    0.05       0  4933.0    0.12       0  4990.9    0.07       0
  4996.9    0.12       0  5261.9    0.16       0
Bank Sta=4932.9,5049.5
Exp/Cntr=0.3,0.1

Type RM Length L Ch R = 1,11146,453,453,453
BEGIN DESCRIPTION:
BUCKEYE BRANCH 21.0
END DESCRIPTION:
XS GIS Cut Line= 3
      2793132.08      7047319.99      2792673.74      7047483.19
      2792324.99      7047925.01
#Sta/Elev= 30
  4496.9  467.46  4536.3  467.57  4554.4  467.22  4559.7  467.80  4610.6  467.41
  4913.7  462.24  4944.5  462.57  4972.1  461.86  4980.1  460.95  4986.4  460.95
  4990.8  460.52  4995.5  459.38  4996.0  458.58  5001.0  458.58  5001.5  459.38
  5034.1  460.92  5065.9  461.86  5139.9  463.68  5167.3  463.97  5189.6  464.41
  5197.6  464.12  5247.3  465.27  5290.6  465.78  5304.2  466.17  5311.4  466.84
  5317.8  466.55  5354.8  466.96  5390.0  467.90  5410.8  467.80  5546.3  469.01
#Mann=4,-1,0
  4496.9    0.05       0  4995.5    0.03       0  5001.5    0.05       0
  5167.3    0.12       0
Bank Sta=4972.1,5065.9
Exp/Cntr=0.3,0.1

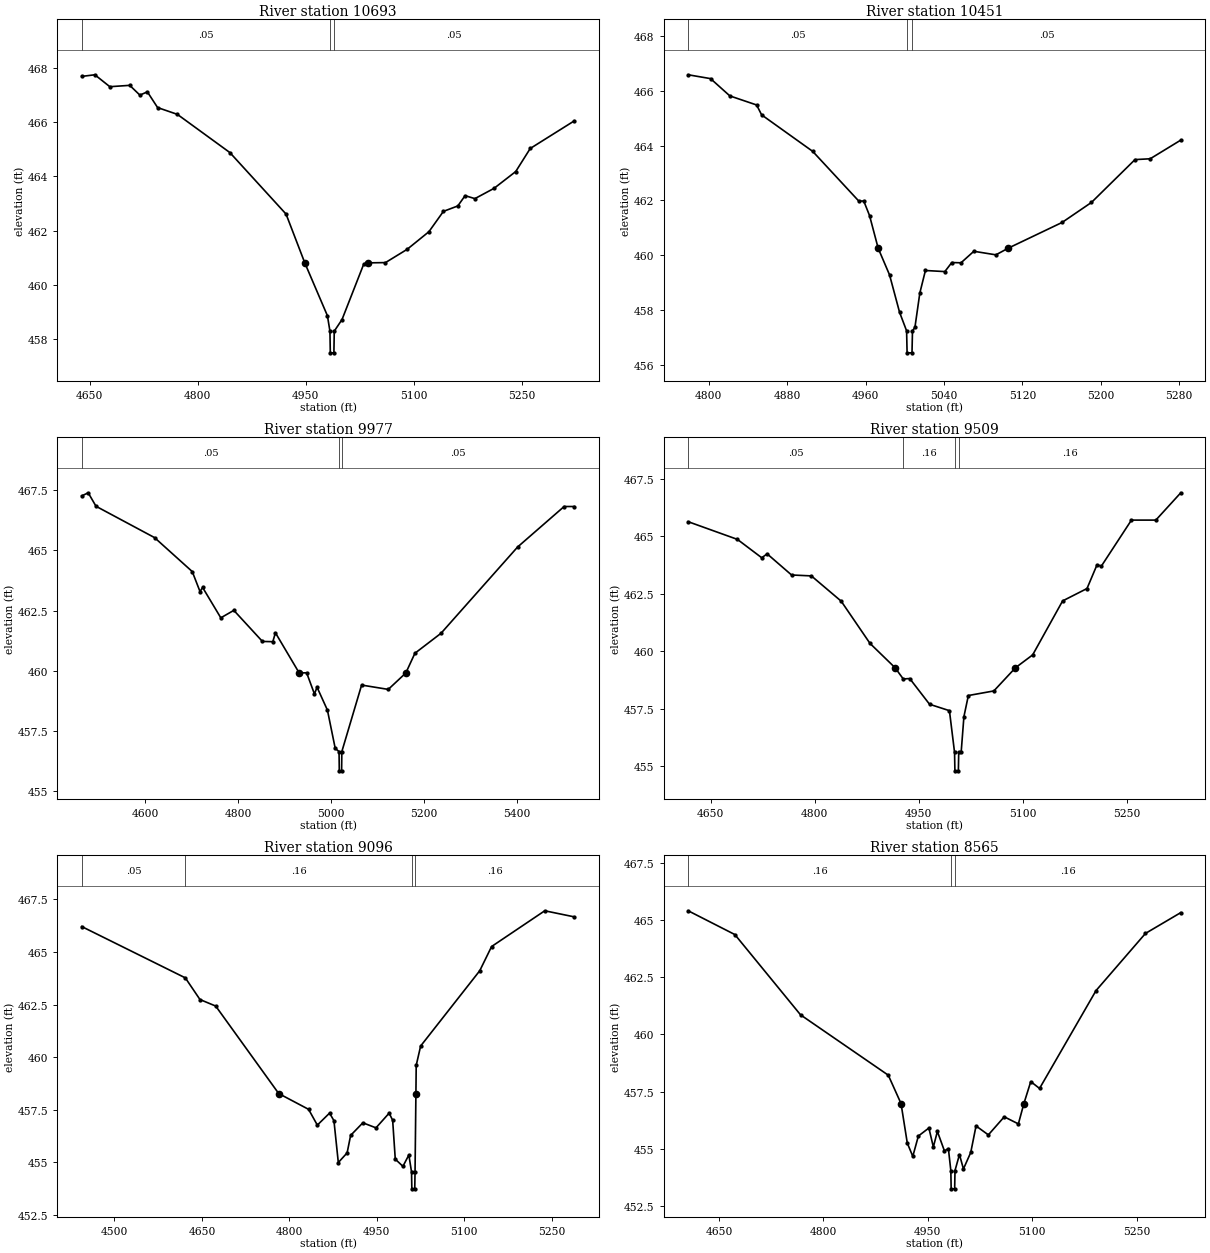
Type RM Length L Ch R = 1,10693,242,242,242
BEGIN DESCRIPTION:
Mapping XS 7c027b05
END DESCRIPTION:
XS GIS Cut Line= 3
      2793142.47      7047238.97      2792807.42      7047141.76
      2792474.05      7047173.01
#Sta/Elev= 30
  4639.2  467.69  4657.4  467.75  4678.2  467.31  4705.8  467.36  4719.9  467.00
  4730.3  467.12  4744.5  466.54  4771.9  466.29  4844.8  464.88  4922.8  462.61
  4948.8  460.81  4980.2  458.86  4983.7  458.29  4984.2  457.49  4989.2  457.49
  4989.7  458.29  5000.5  458.72  5030.7  460.77  5037.2  460.81  5060.8  460.82
  5090.9  461.31  5121.1  461.96  5141.2  462.71  5161.2  462.91  5171.3  463.29
  5184.9  463.18  5211.5  463.56  5241.6  464.18  5261.7  465.03  5322.9  466.05
#Mann=3,-1,0
  4639.2    0.05       0  4983.7    0.03       0  4989.7    0.05       0
Bank Sta=4948.8,5037.2
Exp/Cntr=0.3,0.1

Type RM Length L Ch R = 1,10451,474,474,474
BEGIN DESCRIPTION:
Mapping XS 35c1a660
END DESCRIPTION:
XS GIS Cut Line= 3
      2792956.76      7046876.56      2792718.01      7046922.14
      2792487.27      7047040.74
#Sta/Elev= 30
  4779.1  466.58  4801.9  466.44  4821.6  465.81  4848.9  465.48  4854.0  465.12
  4906.1  463.79  4953.1  461.98  4958.2  461.98  4964.1  461.45  4972.9  460.26
  4984.5  459.29  4994.7  457.93  5001.9  457.25  5002.4  456.45  5007.4  456.45
  5007.9  457.25  5010.4  457.38  5015.4  458.63  5021.1  459.45  5040.9  459.41
  5048.0  459.74  5057.4  459.73  5070.5  460.15  5093.0  460.02  5105.4  460.26
  5160.5  461.20  5190.5  461.93  5234.9  463.49  5250.4  463.52  5281.6  464.20
#Mann=3,-1,0
  4779.1    0.05       0  5001.9    0.03       0  5007.9    0.05       0
Bank Sta=4972.9,5105.4
Exp/Cntr=0.3,0.1

Type RM Length L Ch R = 1,9977,468,468,468
BEGIN DESCRIPTION:
BUCKEYE BRANCH 20.0
END DESCRIPTION:
XS GIS Cut Line= 3
      2793024.97      7046774.99      2792525.00      7046525.00
      2792224.99      7046925.01
#Sta/Elev= 30
  4464.2  467.26  4478.1  467.39  4494.9  466.83  4620.7  465.53  4701.8  464.12
  4718.5  463.29  4724.1  463.46  4763.2  462.20  4791.2  462.51  4852.7  461.22
  4875.0  461.21  4880.6  461.58  4931.8  459.91  4947.7  459.92  4964.5  459.04
  4970.1  459.32  4992.4  458.37  5009.2  456.78  5017.4  456.65  5017.9  455.85
  5022.9  455.85  5023.4  456.65  5065.9  459.41  5123.2  459.23  5160.9  459.91
  5180.5  460.73  5236.7  461.56  5401.3  465.14  5501.3  466.82  5523.2  466.82
#Mann=3,-1,0
  4464.2    0.05       0  5017.4    0.03       0  5023.4    0.05       0
Bank Sta=4931.8,5160.9
Exp/Cntr=0.3,0.1

Type RM Length L Ch R = 1,9509,413,413,413
BEGIN DESCRIPTION:
BUCKEYE BRANCH 19.0
END DESCRIPTION:
XS GIS Cut Line= 3
      2792875.03      7046475.02      2792575.00      7046225.00
      2792325.00      7046025.00
#Sta/Elev= 30
  4617.6  465.64  4688.6  464.87  4723.7  464.07  4731.5  464.24  4766.7  463.32
  4795.3  463.28  4838.3  462.18  4879.9  460.34  4916.1  459.28  4927.9  458.79
  4937.2  458.81  4965.8  457.69  4994.5  457.41  5001.9  455.59  5002.4  454.79
  5007.4  454.79  5007.9  455.59  5011.4  455.59  5015.4  457.15  5021.8  458.07
  5058.6  458.27  5089.8  459.28  5114.6  459.84  5157.8  462.19  5193.0  462.73
  5207.4  463.76  5213.8  463.71  5257.1  465.71  5292.3  465.71  5328.3  466.90
#Mann=4,-1,0
  4617.6    0.05       0  4927.9    0.16       0  5001.9    0.07       0
  5007.9    0.16       0
Bank Sta=4916.1,5089.8
Exp/Cntr=0.3,0.1

Type RM Length L Ch R = 1,9096,531,531,531
BEGIN DESCRIPTION:
BUCKEYE BRANCH 18.0
END DESCRIPTION:
XS GIS Cut Line= 3
      2792974.98      7046424.96      2792675.00      7045975.00
      2792375.03      7045925.00
#Sta/Elev= 30
  4443.9  466.21  4621.6  463.77  4646.7  462.74  4673.7  462.43  4781.8  458.27
  4833.0  457.52  4848.0  456.77  4869.0  457.34  4876.5  456.98  4884.0  454.99
  4899.1  455.45  4905.1  456.28  4926.1  456.88  4948.6  456.64  4971.2  457.34
  4977.2  457.00  4981.7  455.15  4994.8  454.81  5005.0  455.35  5009.6  454.54
  5010.1  453.74  5015.1  453.74  5015.6  454.54  5017.1  458.27  5017.6  459.61
  5025.2  460.53  5126.6  464.11  5146.9  465.26  5238.1  466.96  5288.8  466.67
#Mann=4,-1,0
  4443.9    0.05       0  4621.6    0.16       0  5009.6    0.07       0
  5015.6    0.16       0
Bank Sta=4781.8,5017.1
Exp/Cntr=0.3,0.1

Type RM Length L Ch R = 1,8565,407,407,407
BEGIN DESCRIPTION:
BUCKEYE BRANCH 17.0
END DESCRIPTION:
XS GIS Cut Line= 3
      2793125.02      7046225.04      2792925.00      7045875.00
      2792625.00      7045825.00
#Sta/Elev= 30
  4605.9  465.41  4672.9  464.37  4767.2  460.86  4893.2  458.22  4911.5  456.98
  4920.5  455.25  4928.4  454.67  4936.4  455.56  4951.5  455.91  4957.9  455.08
  4963.7  455.76  4973.8  454.91  4979.5  455.01  4983.0  454.05  4983.5  453.25
  4988.5  453.25  4989.0  454.05  4995.4  454.75  5001.1  454.12  5011.6  454.84
  5019.2  456.00  5036.9  455.61  5059.7  456.40  5080.0  456.09  5087.9  456.98
  5097.8  457.94  5110.4  457.64  5191.5  461.92  5262.5  464.42  5313.2  465.33
#Mann=3,-1,0
  4605.9    0.16       0  4983.0    0.07       0  4989.0    0.16       0
Bank Sta=4911.5,5087.9
Exp/Cntr=0.3,0.1

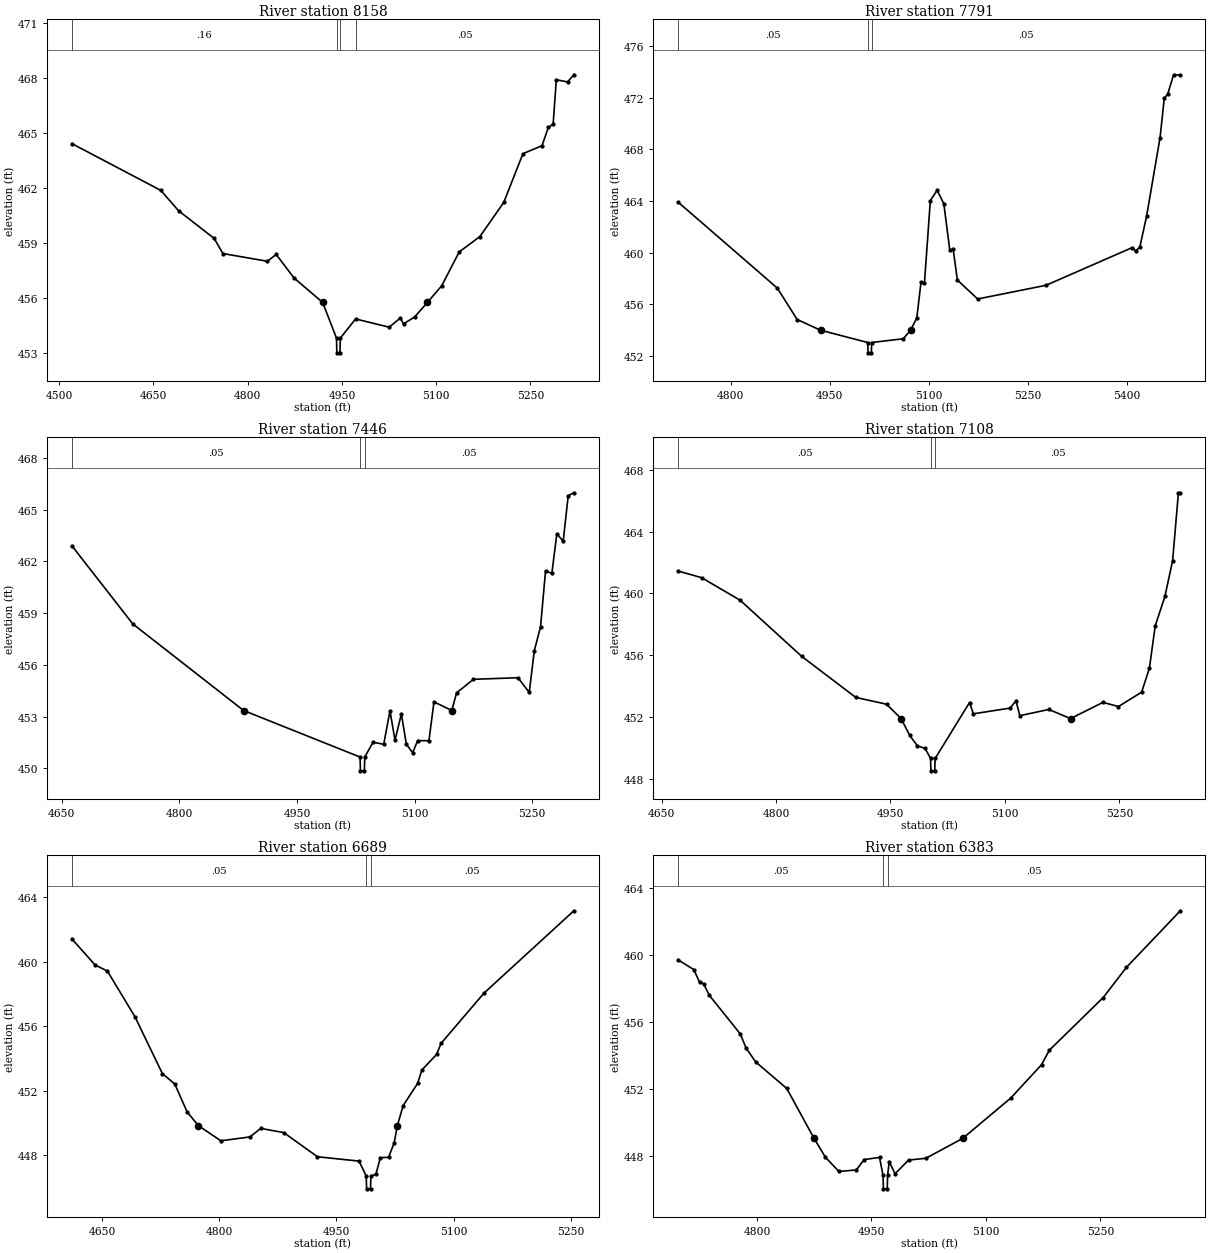
Type RM Length L Ch R = 1,8158,367,367,367
BEGIN DESCRIPTION:
BUCKEYE BRANCH 16.0
END DESCRIPTION:
XS GIS Cut Line= 3
      2793324.99      7045924.99      2792975.00      7045575.00
      2792674.99      7045525.00
#Sta/Elev= 30
  4520.2  464.43  4661.6  461.88  4689.9  460.77  4746.5  459.26  4760.6  458.43
  4831.3  458.01  4845.4  458.38  4873.7  457.10  4919.4  455.76  4941.4  453.81
  4941.9  453.01  4946.9  453.01  4947.4  453.81  4971.8  454.86  5025.3  454.41
  5043.0  454.91  5048.1  454.59  5065.8  454.97  5086.1  455.76  5108.9  456.67
  5136.8  458.52  5169.8  459.36  5207.8  461.23  5238.2  463.88  5268.6  464.32
  5278.7  465.32  5286.3  465.49  5291.4  467.92  5309.2  467.80  5319.3  468.19
#Mann=4,-1,0
  4520.2    0.16       0  4941.4    0.03       0  4947.4    0.16       0
  4971.8    0.05       0
Bank Sta=4919.4,5086.1
Exp/Cntr=0.3,0.1

Type RM Length L Ch R = 1,7791,345,345,345
BEGIN DESCRIPTION:
BUCKEYE BRANCH 15.0
END DESCRIPTION:
XS GIS Cut Line= 3
      2793224.97      7045225.00      2792925.00      7045225.00
      2792475.05      7045125.01
#Sta/Elev= 30
  4720.6  463.89  4870.6  457.25  4900.6  454.82  4936.2  453.99  5007.6  453.04
  5008.1  452.24  5013.1  452.24  5013.6  453.04  5061.5  453.33  5072.5  453.99
  5082.0  454.94  5088.4  457.72  5093.6  457.64  5102.5  464.02  5112.8  464.83
  5123.0  463.78  5132.0  460.18  5137.1  460.27  5143.5  457.88  5174.2  456.41
  5277.9  457.47  5408.6  460.39  5413.7  460.12  5420.1  460.43  5430.3  462.80
  5450.8  468.91  5457.2  471.96  5462.3  472.26  5471.3  473.77  5481.5  473.75
#Mann=3,-1,0
  4720.6    0.05       0  5007.6    0.03       0  5013.6    0.05       0
Bank Sta=4936.2,5072.5
Exp/Cntr=0.3,0.1

Type RM Length L Ch R = 1,7446,338,338,338
BEGIN DESCRIPTION:
BUCKEYE BRANCH 14.0
END DESCRIPTION:
XS GIS Cut Line= 3
      2793225.03      7045175.04      2793025.00      7044925.00
      2792824.97      7044674.97
#Sta/Elev= 30
  4662.9  462.90  4740.6  458.37  4881.9  453.35  5030.5  450.65  5031.0  449.85
  5036.0  449.85  5036.5  450.65  5047.1  451.51  5060.7  451.39  5068.7  453.33
  5075.1  451.62  5083.2  453.15  5089.6  451.39  5097.6  450.90  5104.0  451.60
  5118.4  451.60  5124.8  453.85  5147.6  453.35  5153.6  454.37  5175.2  455.16
  5232.0  455.25  5246.4  454.40  5252.8  456.81  5260.8  458.21  5267.2  461.46
  5275.2  461.30  5281.6  463.60  5289.7  463.17  5296.1  465.81  5303.3  465.98
#Mann=3,-1,0
  4662.9    0.05       0  5030.5    0.03       0  5036.5    0.05       0
Bank Sta=4881.9,5147.6
Exp/Cntr=0.3,0.1

Type RM Length L Ch R = 1,7108,419,419,419
BEGIN DESCRIPTION:
BUCKEYE BRANCH 13.0
END DESCRIPTION:
XS GIS Cut Line= 3
      2793475.04      7044574.99      2793125.00      7044625.00
      2792825.03      7044575.00
#Sta/Elev= 30
  4672.1  461.44  4702.4  461.02  4752.9  459.56  4833.8  455.92  4904.5  453.27
  4944.9  452.83  4963.9  451.90  4975.2  450.81  4985.3  450.14  4995.4  449.97
  5002.5  449.32  5003.0  448.52  5008.0  448.52  5008.5  449.32  5053.6  452.94
  5058.6  452.21  5106.8  452.58  5114.4  453.05  5119.5  452.09  5157.5  452.49
  5185.9  451.90  5228.4  452.95  5248.7  452.68  5279.1  453.61  5289.3  455.16
  5296.9  457.90  5309.6  459.80  5319.7  462.12  5327.3  466.51  5329.8  466.51
#Mann=3,-1,0
  4672.1    0.05       0  5002.5    0.03       0  5008.5    0.05       0
Bank Sta=4963.9,5185.9
Exp/Cntr=0.3,0.1

Type RM Length L Ch R = 1,6689,306,306,306
BEGIN DESCRIPTION:
BUCKEYE BRANCH 12.0
END DESCRIPTION:
XS GIS Cut Line= 3
      2793425.04      7044525.02      2793075.00      7044325.00
      2792850.59      7044239.79
#Sta/Elev= 30
  4611.0  461.40  4640.6  459.79  4656.4  459.41  4691.7  456.58  4726.9  453.05
  4742.8  452.40  4758.6  450.67  4773.1  449.82  4801.8  448.88  4839.2  449.12
  4852.9  449.65  4882.4  449.39  4925.6  447.89  4978.9  447.62  4988.1  446.70
  4988.6  445.90  4993.6  445.90  4994.1  446.70  5000.5  446.80  5006.2  447.83
  5016.8  447.86  5023.9  448.74  5028.0  449.82  5035.5  451.07  5054.0  452.44
  5059.4  453.27  5078.3  454.24  5084.1  454.93  5139.0  458.04  5254.2  463.15
#Mann=3,-1,0
  4611.0    0.05       0  4988.1    0.03       0  4994.1    0.05       0
Bank Sta=4773.1,5028
Exp/Cntr=0.3,0.1

Type RM Length L Ch R = 1,6383,202,202,202
BEGIN DESCRIPTION:
BUCKEYE BRANCH 11.0
END DESCRIPTION:
XS GIS Cut Line= 3
      2793524.96      7044124.99      2793225.00      7044075.00
      2792875.05      7044124.99
#Sta/Elev= 30
  4697.1  459.71  4717.3  459.14  4724.9  458.37  4730.0  458.30  4737.6  457.60
  4778.2  455.29  4785.8  454.44  4798.4  453.61  4839.0  452.03  4874.8  449.04
  4889.7  447.91  4907.4  447.06  4930.2  447.15  4940.4  447.77  4960.6  447.90
  4965.2  446.82  4965.7  446.02  4970.7  446.02  4971.2  446.82  4973.3  447.65
  4980.9  446.92  4998.7  447.74  5021.4  447.85  5069.6  449.04  5132.5  451.45
  5172.9  453.45  5183.0  454.31  5253.7  457.47  5284.0  459.27  5354.7  462.66
#Mann=3,-1,0
  4697.1    0.05       0  4965.2    0.03       0  4971.2    0.05       0
Bank Sta=4874.8,5069.6
Exp/Cntr=0.3,0.1

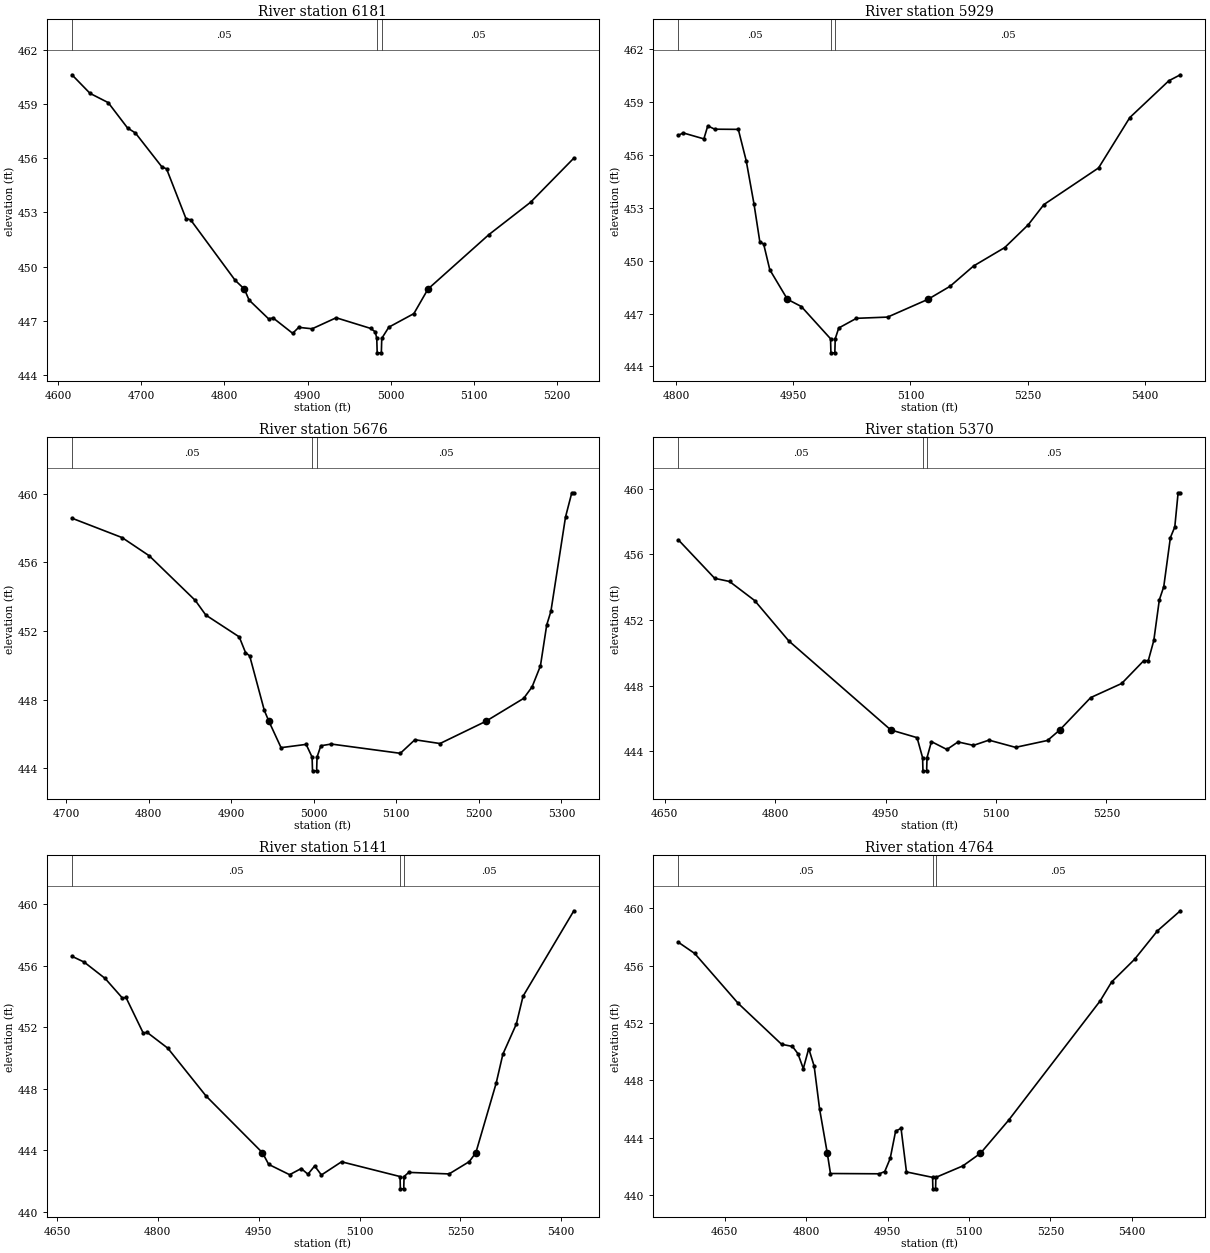
Type RM Length L Ch R = 1,6181,252,252,252
BEGIN DESCRIPTION:
BUCKEYE BRANCH 10.0
END DESCRIPTION:
XS GIS Cut Line= 3
      2793574.98      7044024.99      2793232.33      7043876.13
      2793003.15      7043860.50
#Sta/Elev= 30
  4616.7  460.61  4638.5  459.58  4660.3  459.07  4683.5  457.67  4693.0  457.39
  4724.9  455.51  4730.4  455.41  4753.8  452.65  4759.3  452.59  4812.9  449.24
  4823.9  448.76  4829.6  448.15  4853.1  447.11  4858.5  447.16  4882.0  446.31
  4889.3  446.64  4905.4  446.56  4934.3  447.17  4975.8  446.58  4981.3  446.39
  4983.1  446.03  4983.6  445.23  4988.6  445.23  4989.1  446.03  4997.6  446.65
  5027.7  447.40  5044.7  448.76  5117.9  451.77  5168.0  453.56  5220.0  456.00
#Mann=3,-1,0
  4616.7    0.05       0  4983.1    0.03       0  4989.1    0.05       0
Bank Sta=4823.9,5044.7
Exp/Cntr=0.3,0.1

Type RM Length L Ch R = 1,5929,253,253,253
BEGIN DESCRIPTION:
Mapping XS c32e1a02
END DESCRIPTION:
XS GIS Cut Line= 3
      2793570.92      7043714.68      2793365.15      7043686.03
      2792930.28      7043693.84
#Sta/Elev= 30
  4802.9  457.12  4808.9  457.26  4835.5  456.92  4840.5  457.66  4849.3  457.47
  4879.6  457.46  4889.7  455.68  4899.7  453.22  4907.1  451.09  4912.1  450.94
  4919.9  449.49  4942.5  447.81  4960.3  447.40  4997.7  445.57  4998.2  444.77
  5003.2  444.77  5003.7  445.57  5008.2  446.18  5030.8  446.73  5070.8  446.80
  5122.5  447.81  5150.8  448.55  5180.8  449.70  5220.8  450.75  5250.8  452.04
  5270.9  453.19  5340.9  455.27  5380.9  458.13  5430.9  460.22  5445.6  460.56
#Mann=3,-1,0
  4802.9    0.05       0  4997.7    0.03       0  5003.7    0.05       0
Bank Sta=4942.5,5122.5
Exp/Cntr=0.3,0.1

Type RM Length L Ch R = 1,5676,306,306,306
BEGIN DESCRIPTION:
BUCKEYE BRANCH 9.0
END DESCRIPTION:
XS GIS Cut Line= 3
      2793774.97      7043425.00      2793475.00      7043475.00
      2793175.05      7043425.01
#Sta/Elev= 30
  4706.9  458.57  4767.7  457.44  4800.6  456.38  4856.4  453.78  4869.1  452.93
  4909.6  451.66  4917.2  450.75  4922.3  450.55  4940.0  447.38  4945.6  446.74
  4960.3  445.21  4990.7  445.40  4997.9  444.66  4998.4  443.86  5003.4  443.86
  5003.9  444.66  5008.5  445.32  5021.1  445.42  5104.8  444.88  5122.5  445.67
  5152.9  445.45  5208.3  446.74  5254.3  448.08  5264.5  448.75  5274.6  449.97
  5282.2  452.35  5287.3  453.15  5305.0  458.64  5312.6  460.05  5315.1  460.05
#Mann=3,-1,0
  4706.9    0.05       0  4997.9    0.03       0  5003.9    0.05       0
Bank Sta=4945.6,5208.3
Exp/Cntr=0.3,0.1

Type RM Length L Ch R = 1,5370,229,229,229
BEGIN DESCRIPTION:
BUCKEYE BRANCH 8.0
END DESCRIPTION:
XS GIS Cut Line= 3
      2793793.96      7043138.28      2793475.00      7043175.00
      2793175.02      7043374.99
#Sta/Elev= 30
  4668.7  456.87  4718.0  454.53  4738.1  454.34  4772.2  453.18  4818.6  450.72
  4957.1  445.30  4992.8  444.83  5000.3  443.61  5000.8  442.81  5005.8  442.81
  5006.3  443.61  5012.3  444.59  5033.3  444.11  5048.4  444.57  5069.4  444.36
  5090.4  444.68  5126.5  444.24  5170.0  444.66  5186.6  445.30  5228.6  447.27
  5270.7  448.13  5300.7  449.52  5306.8  449.52  5314.3  450.75  5321.8  453.22
  5327.8  454.02  5336.8  457.01  5342.8  457.66  5347.3  459.74  5350.3  459.74
#Mann=3,-1,0
  4668.7    0.05       0  5000.3    0.03       0  5006.3    0.05       0
Bank Sta=4957.1,5186.6
Exp/Cntr=0.3,0.1

Type RM Length L Ch R = 1,5141,377,377,377
BEGIN DESCRIPTION:
Mapping XS 332a0fe7
END DESCRIPTION:
XS GIS Cut Line= 3
      2793807.85      7043075.78      2793498.83      7042968.14
      2793079.36      7042968.14
#Sta/Elev= 30
  4672.2  456.62  4690.4  456.24  4721.5  455.18  4747.3  453.90  4752.6  453.94
  4778.4  451.61  4783.7  451.68  4814.8  450.64  4871.7  447.53  4955.6  443.84
  4964.9  443.08  4996.0  442.41  5013.3  442.81  5023.3  442.44  5033.3  442.98
  5043.3  442.39  5073.3  443.25  5160.3  442.29  5160.8  441.49  5165.8  441.49
  5166.3  442.29  5173.3  442.56  5233.3  442.46  5263.3  443.26  5273.1  443.84
  5303.3  448.36  5313.3  450.25  5333.3  452.21  5343.3  454.02  5418.9  459.58
#Mann=3,-1,0
  4672.2    0.05       0  5160.3    0.03       0  5166.3    0.05       0
Bank Sta=4955.6,5273.1
Exp/Cntr=0.3,0.1

Type RM Length L Ch R = 1,4764,664,664,664
BEGIN DESCRIPTION:
BUCKEYE BRANCH 7.0
END DESCRIPTION:
XS GIS Cut Line= 3
      2793924.98      7042625.00      2793475.00      7042625.00
      2793025.02      7042774.99
#Sta/Elev= 30
  4564.8  457.64  4594.8  456.86  4674.8  453.38  4754.8  450.52  4774.8  450.37
  4784.8  449.87  4794.8  448.82  4804.8  450.22  4814.8  448.99  4824.8  446.00
  4839.0  442.91  4844.8  441.50  4934.8  441.48  4944.8  441.64  4954.8  442.55
  4964.8  444.46  4974.8  444.65  4984.8  441.61  5032.9  441.23  5033.4  440.43
  5038.4  440.43  5038.9  441.23  5088.6  442.03  5121.0  442.91  5172.9  445.22
  5341.5  453.55  5362.6  454.87  5404.8  456.45  5447.0  458.44  5489.1  459.84
#Mann=3,-1,0
  4564.8    0.05       0  5032.9    0.03       0  5038.9    0.05       0
Bank Sta=4839,5121
Exp/Cntr=0.3,0.1