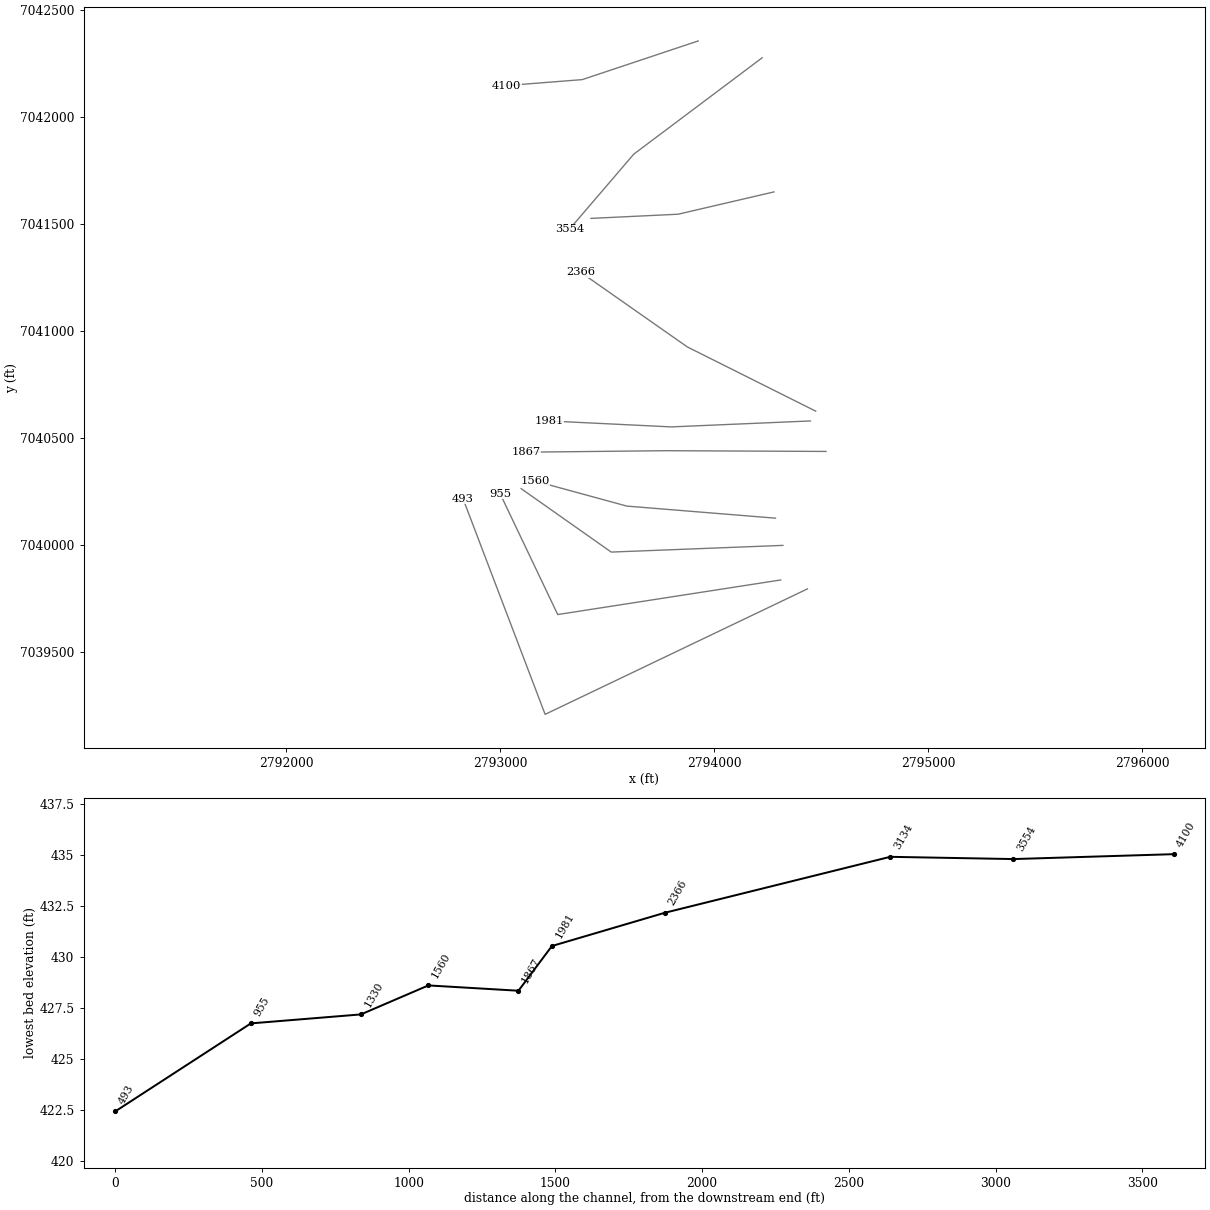
HEC-RAS study BUCKEYE BRANCH.prj: BUCKEYE BRANCH Base Level Engineering

--- BUCKEYE BRANCH.g01 (geometry) --- (continued)

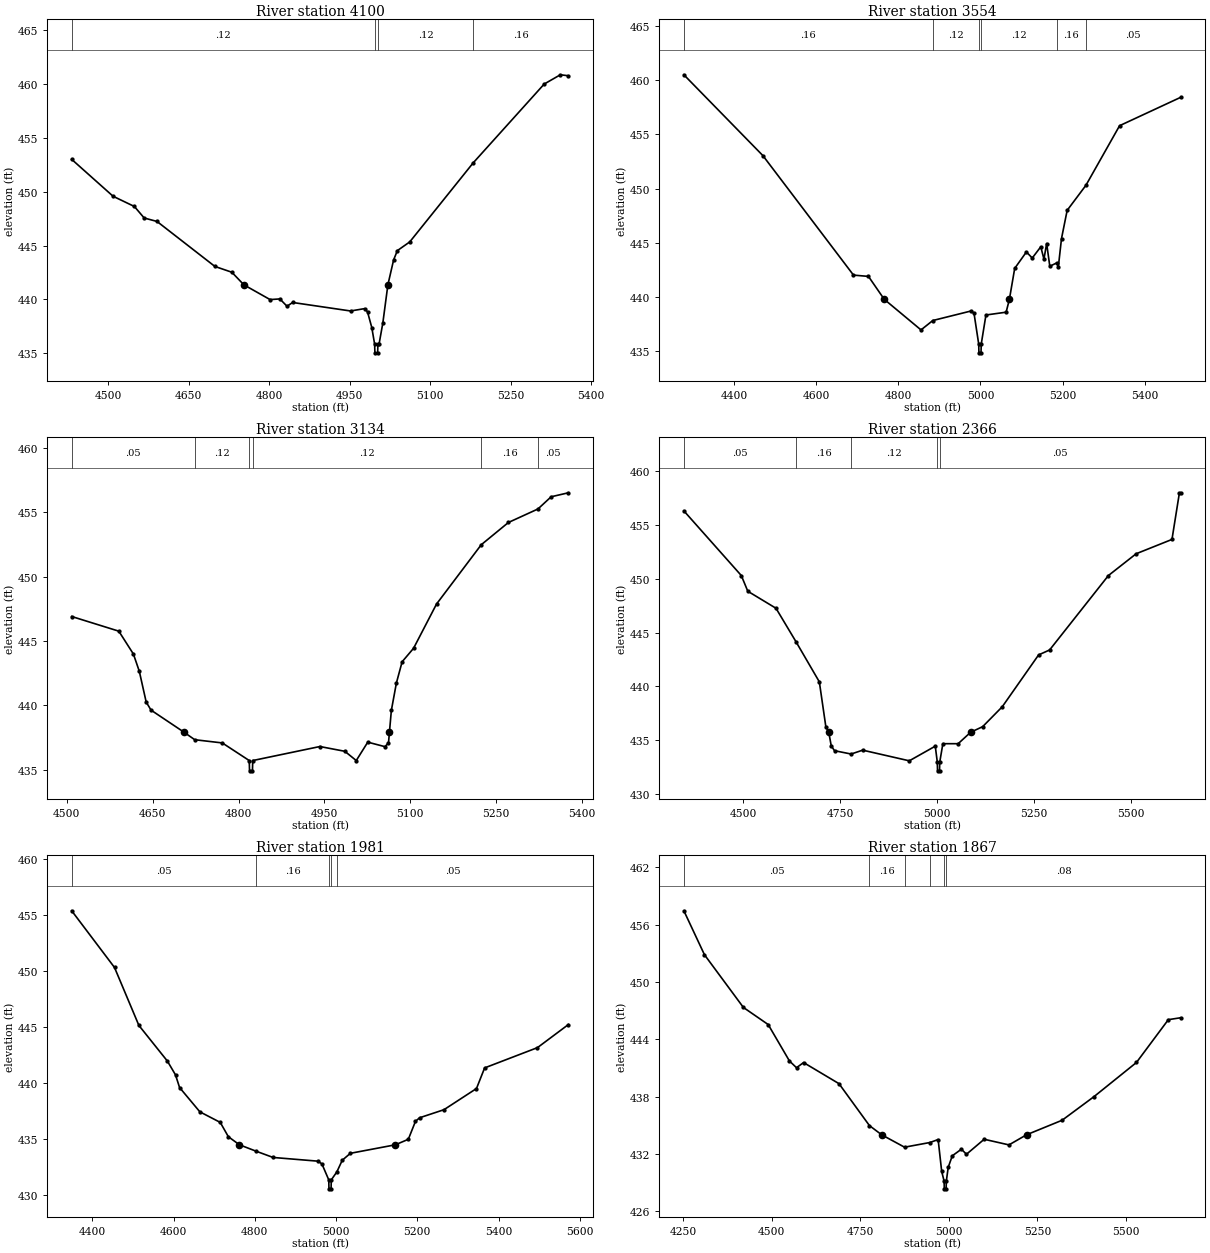
Type RM Length L Ch R = 1,4100,546,546,546
BEGIN DESCRIPTION:
BUCKEYE BRANCH 6.0
END DESCRIPTION:
XS GIS Cut Line= 3
      2793925.90      7042353.56      2793384.24      7042173.01
      2793030.08      7042145.23
#Sta/Elev= 30
  4431.7  453.02  4508.9  449.59  4548.6  448.64  4566.9  447.57  4590.8  447.25
  4698.7  443.07  4730.3  442.53  4752.8  441.36  4801.6  439.99  4819.9  440.05
  4833.2  439.37  4843.7  439.72  4951.7  438.93  4978.0  439.15  4983.3  438.85
  4991.3  437.39  4996.6  435.84  4997.1  435.04  5002.2  435.04  5002.7  435.84
  5004.8  435.84  5011.9  437.82  5021.3  441.36  5032.0  443.68  5039.0  444.54
  5062.1  445.35  5180.3  452.69  5312.8  460.02  5342.9  460.88  5357.9  460.79
#Mann=4,-1,0
  4431.7    0.12       0  4996.6    0.07       0  5002.7    0.12       0
  5180.3    0.16       0
Bank Sta=4752.8,5021.3
Exp/Cntr=0.3,0.1

Type RM Length L Ch R = 1,3554,420,420,420
BEGIN DESCRIPTION:
BUCKEYE BRANCH 5.0
END DESCRIPTION:
XS GIS Cut Line= 3
      2794224.97      7042274.98      2793625.00      7041825.00
      2793325.03      7041475.03
#Sta/Elev= 30
  4276.9  460.52  4469.6  453.04  4690.4  441.99  4726.9  441.87  4765.4  439.75
  4855.0  436.92  4883.8  437.79  4976.9  438.67  4984.2  438.47  4995.7  435.60
  4996.2  434.80  5001.3  434.80  5001.8  435.60  5013.3  438.30  5062.5  438.56
  5070.5  439.75  5083.4  442.61  5111.9  444.13  5126.2  443.57  5147.0  444.61
  5154.7  443.47  5161.3  444.91  5169.0  442.81  5185.4  443.11  5189.9  442.78
  5197.5  445.37  5211.3  447.98  5257.1  450.30  5339.1  455.81  5487.8  458.43
#Mann=6,-1,0
  4276.9    0.16       0  4883.8    0.12       0  4995.7    0.07       0
  5001.8    0.12       0  5185.4    0.16       0  5257.1    0.05       0
Bank Sta=4765.4,5070.5
Exp/Cntr=0.3,0.1

Type RM Length L Ch R = 1,3134,768,768,768
BEGIN DESCRIPTION:
BUCKEYE BRANCH 4.0
END DESCRIPTION:
XS GIS Cut Line= 3
      2794280.04      7041648.69      2793832.16      7041544.53
      2793424.96      7041525.00
#Sta/Elev= 30
  4508.5  446.91  4590.8  445.77  4616.3  443.99  4626.6  442.65  4638.6  440.26
  4647.1  439.63  4703.8  437.94  4723.4  437.33  4771.5  437.08  4818.6  435.71
  4819.1  434.91  4824.2  434.91  4824.7  435.71  4942.0  436.80  4985.5  436.43
  5005.5  435.71  5025.6  437.14  5055.6  436.79  5061.8  437.08  5063.5  437.94
  5066.8  439.61  5075.6  441.74  5085.6  443.39  5105.6  444.44  5145.7  447.88
  5223.8  452.49  5271.2  454.22  5322.8  455.27  5345.9  456.22  5376.0  456.53
#Mann=6,-1,0
  4508.5    0.05       0  4723.4    0.12       0  4818.6    0.07       0
  4824.7    0.12       0  5223.8    0.16       0  5322.8    0.05       0
Bank Sta=4703.8,5063.5
Exp/Cntr=0.3,0.1

Type RM Length L Ch R = 1,2366,385,385,385
BEGIN DESCRIPTION:
BUCKEYE BRANCH 3.0
END DESCRIPTION:
XS GIS Cut Line= 3
      2794474.99      7040625.00      2793875.00      7040925.00
      2793375.03      7041274.98
#Sta/Elev= 30
  4346.3  456.30  4494.4  450.30  4511.2  448.84  4583.9  447.26  4635.4  444.16
  4695.7  440.43  4712.4  436.28  4720.0  435.75  4726.4  434.49  4734.8  434.04
  4777.7  433.73  4807.5  434.09  4927.7  433.10  4994.7  434.46  5000.0  432.97
  5000.5  432.17  5005.7  432.17  5006.2  432.97  5014.3  434.69  5053.7  434.69
  5085.9  435.75  5116.9  436.27  5167.5  438.12  5261.2  442.93  5289.6  443.39
  5441.3  450.30  5512.8  452.32  5605.2  453.65  5624.4  457.98  5627.4  457.98
#Mann=5,-1,0
  4346.3    0.05       0  4635.4    0.16       0  4777.7    0.12       0
  5000.0    0.07       0  5006.2    0.05       0
Bank Sta=4720,5085.9
Exp/Cntr=0.3,0.1

Type RM Length L Ch R = 1,1981,114,114,114
BEGIN DESCRIPTION:
BUCKEYE BRANCH 2.0
END DESCRIPTION:
XS GIS Cut Line= 3
      2794450.26      7040579.26      2793800.91      7040551.48
      2793229.02      7040579.21
#Sta/Elev= 30
  4349.4  455.35  4454.8  450.29  4514.8  445.12  4584.9  441.94  4604.9  440.71
  4614.9  439.58  4664.9  437.41  4715.0  436.47  4735.0  435.19  4762.3  434.47
  4803.9  433.89  4845.1  433.34  4955.2  433.01  4965.2  432.77  4982.1  431.34
  4982.6  430.54  4987.8  430.54  4988.3  431.34  5002.0  432.05  5015.3  433.09
  5035.3  433.71  5146.1  434.47  5177.9  434.96  5195.5  436.56  5205.5  436.88
  5265.6  437.60  5345.7  439.49  5365.7  441.33  5495.8  443.14  5571.9  445.20
#Mann=5,-1,0
  4349.4    0.05       0  4803.9    0.16       0  4982.1    0.07       0
  4988.3    0.16       0  5002.0    0.05       0
Bank Sta=4762.3,5146.1
Exp/Cntr=0.3,0.1

Type RM Length L Ch R = 1,1867,307,307,307
BEGIN DESCRIPTION:
Mapping XS ecdf8476
END DESCRIPTION:
XS GIS Cut Line= 3
      2794523.13      7040436.89      2793773.13      7040440.37
      2793120.37      7040433.42
#Sta/Elev= 30
  4251.8  457.46  4309.9  452.86  4419.9  447.34  4489.9  445.55  4549.9  441.74
  4569.9  441.03  4589.9  441.57  4689.9  439.36  4775.9  434.97  4810.4  434.01
  4875.0  432.71  4946.6  433.20  4969.9  433.51  4979.9  430.18  4986.8  429.15
  4987.3  428.35  4992.5  428.35  4993.0  429.15  4998.4  430.61  5009.9  431.81
  5035.6  432.50  5049.9  431.97  5099.9  433.54  5169.9  432.95  5219.6  434.01
  5320.0  435.53  5410.0  438.00  5530.0  441.58  5620.0  446.06  5654.6  446.26
#Mann=6,-1,0
  4251.8    0.05       0  4775.9    0.16       0  4875.0    0.12       0
  4946.6    0.08       0  4986.8    0.07       0  4993.0    0.08       0
Bank Sta=4810.4,5219.6
Exp/Cntr=0.3,0.1

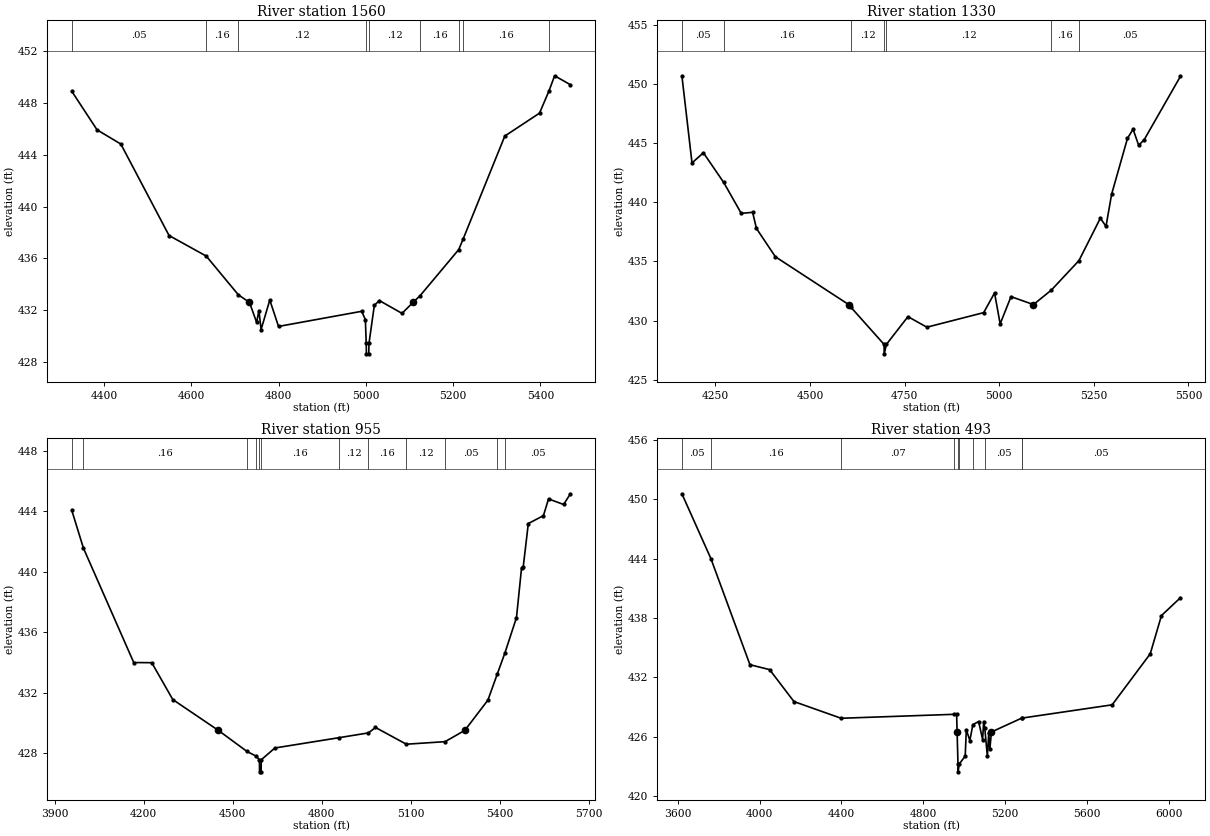
Type RM Length L Ch R = 1,1560,230,230,230
BEGIN DESCRIPTION:
Mapping XS 8b4c75bd
END DESCRIPTION:
XS GIS Cut Line= 3
      2794287.06      7040125.26      2793592.58      7040181.69
      2793162.85      7040298.89
#Sta/Elev= 30
  4326.4  448.91  4384.3  445.93  4438.8  444.83  4549.2  437.76  4634.4  436.17
  4708.1  433.17  4733.4  432.59  4749.9  431.04  4755.1  431.96  4760.1  430.49
  4780.0  432.77  4800.0  430.73  4990.6  431.90  4999.0  431.25  5000.9  429.41
  5001.4  428.61  5006.7  428.61  5007.2  429.41  5019.5  432.36  5031.0  432.73
  5082.9  431.74  5108.3  432.59  5124.7  433.12  5212.8  436.67  5223.2  437.51
  5318.4  445.45  5397.9  447.22  5419.5  448.93  5432.5  450.11  5468.6  449.42
#Mann=9,-1,0
  4326.4    0.05       0  4634.4    0.16       0  4708.1    0.12       0
  5000.9    0.07       0  5007.2    0.12       0  5124.7    0.16       0
  5212.8    0.05       0  5223.2    0.16       0  5419.5    0.05       0
Bank Sta=4733.4,5108.3
Exp/Cntr=0.3,0.1

Type RM Length L Ch R = 1,1330,375,375,375
BEGIN DESCRIPTION:
Mapping XS 87ddf625
END DESCRIPTION:
XS GIS Cut Line= 3
      2794321.72      7039998.23      2793519.67      7039966.98
      2793098.87      7040263.09
#Sta/Elev= 30
  4161.7  450.67  4188.4  443.31  4218.5  444.17  4272.2  441.66  4318.5  439.05
  4348.6  439.14  4358.6  437.78  4408.6  435.39  4602.3  431.35  4608.4  431.12
  4695.7  427.99  4696.2  427.19  4702.0  427.99  4758.9  430.33  4808.9  429.44
  4959.0  430.67  4987.7  432.33  5002.5  429.72  5031.2  432.02  5090.5  431.35
  5137.6  432.57  5210.6  435.06  5267.3  438.65  5282.1  437.95  5296.9  440.66
  5338.8  445.38  5353.6  446.16  5368.4  444.80  5383.2  445.28  5478.9  450.63
#Mann=7,-1,0
  4161.7    0.05       0  4272.2    0.16       0  4608.4    0.12       0
  4695.7    0.07       0  4702.0    0.12       0  5137.6    0.16       0
  5210.6    0.05       0
Bank Sta=4602.3,5090.5
Exp/Cntr=0.3,0.1

Type RM Length L Ch R = 1,955,462,462,462
BEGIN DESCRIPTION:
Mapping XS 3a5f877d
END DESCRIPTION:
XS GIS Cut Line= 3
      2794311.33      7039836.77      2793269.67      7039675.31
      2793000.13      7040240.31
#Sta/Elev= 30
  3957.7  444.07  3997.1  441.56  4166.5  433.99  4227.2  433.98  4298.0  431.54
  4451.3  429.50  4548.1  428.10  4579.9  427.78  4589.9  427.55  4590.4  426.75
  4595.7  426.75  4596.2  427.55  4642.1  428.33  4857.5  429.01  4957.4  429.33
  4981.1  429.69  5085.0  428.58  5215.7  428.75  5282.3  429.50  5359.9  431.50
  5391.5  433.23  5417.5  434.64  5456.2  436.97  5473.4  440.28  5478.9  440.32
  5496.1  443.20  5547.0  443.72  5564.2  444.83  5615.1  444.46  5637.8  445.17
#Mann=12,-1,0
  3957.7    0.05       0  3997.1    0.16       0  4548.1    0.12       0
  4579.9    0.16       0  4589.9    0.07       0  4596.2    0.16       0
  4857.5    0.12       0  4957.4    0.16       0  5085.0    0.12       0
  5215.7    0.05       0  5391.5    0.16       0  5417.5    0.05       0
Bank Sta=4451.3,5282.3
Exp/Cntr=0.3,0.1

Type RM Length L Ch R = 1,493,0,0,0
BEGIN DESCRIPTION:
BUCKEYE BRANCH 1.0
END DESCRIPTION:
XS GIS Cut Line= 3
      2794436.35      7039795.11      2793210.84      7039209.28
      2792826.95      7040217.00
#Sta/Elev= 30
  3620.0  450.57  3761.6  444.02  3952.5  433.28  4048.7  432.78  4167.6  429.55
  4398.0  427.86  4951.2  428.26  4962.6  428.29  4965.0  426.47  4969.3  423.24
  4969.8  422.44  4975.6  423.24  5004.6  424.03  5010.0  426.70  5027.3  425.61
  5042.0  427.22  5070.2  427.53  5089.6  425.71  5094.9  427.53  5100.1  426.90
  5112.9  424.01  5119.7  426.36  5125.0  424.70  5132.6  426.47  5282.3  427.89
  5282.7  427.88  5722.8  429.22  5908.9  434.38  5963.7  438.25  6056.7  440.06
#Mann=10,-1,0
  3620.0    0.05       0  3761.6    0.16       0  4398.0    0.07       0
  4951.2    0.05       0  4969.3    0.03       0  4975.6    0.05       0
  5042.0    0.12       0  5100.1    0.05       0  5282.3    0.12       0
  5282.7    0.05       0
Bank Sta=4965,5132.6
Exp/Cntr=0.3,0.1

Chan Stop Cuts=-1