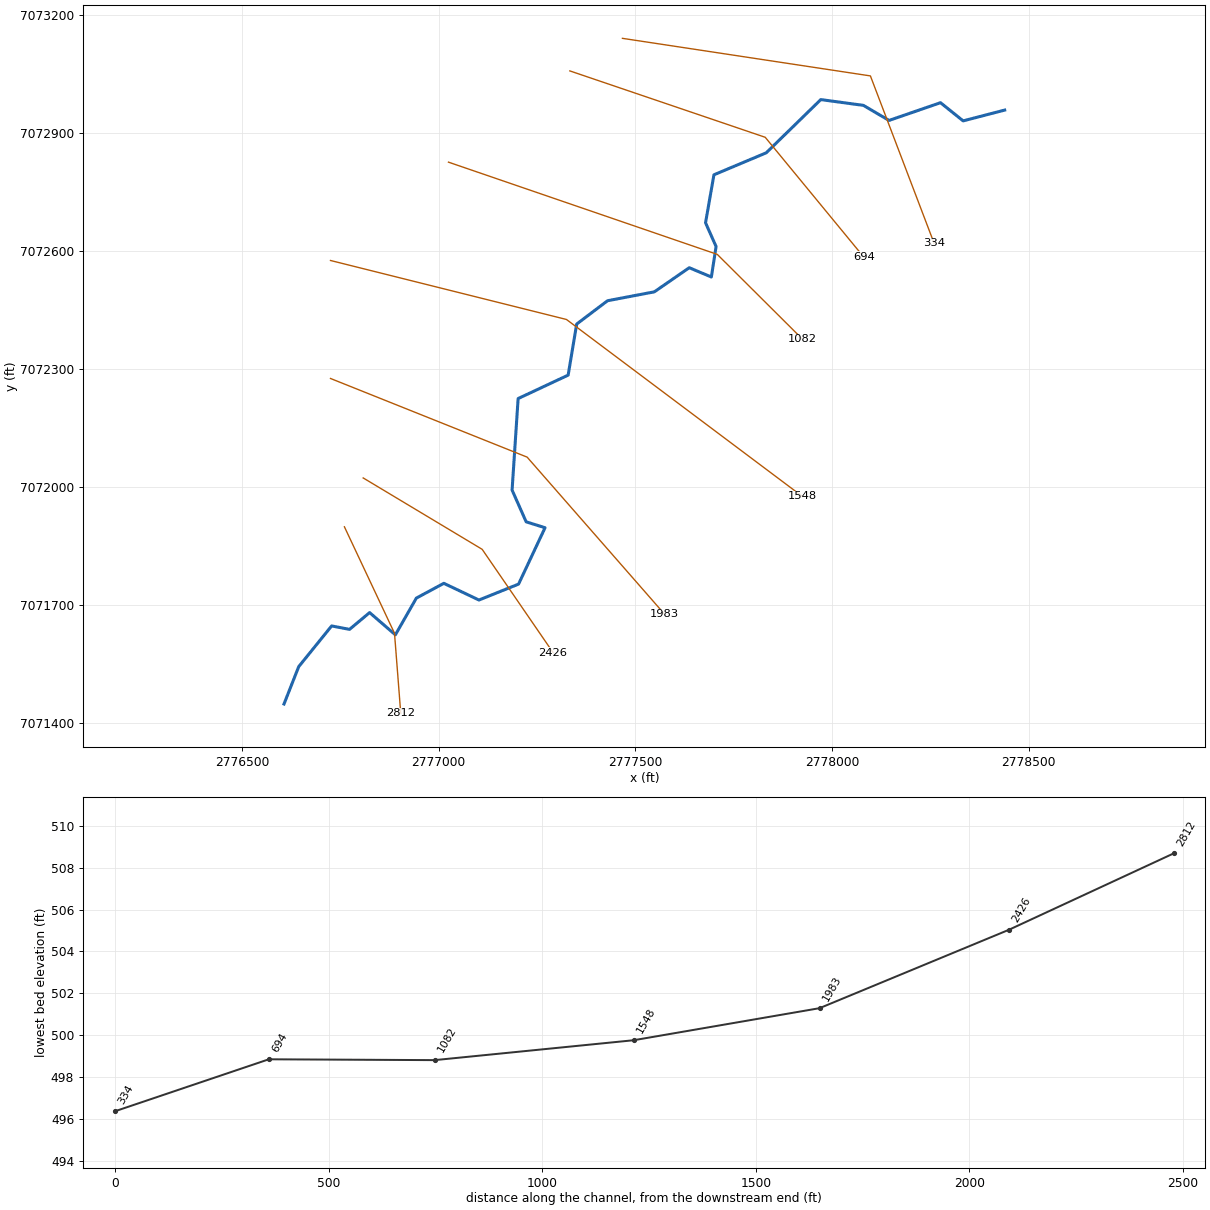
--- BURK BRANCH.prj (project) ---

Proj Title=BURK BRANCH Base Level Engineering
Current Plan=p01
Default Exp/Contr=0.3,0.1
English Units
Geom File=g01
Flow File=f01
Plan File=p01
BEGIN DESCRIPTION:
BURK BRANCH
END DESCRIPTION:

--- BURK BRANCH.p01 (plan) ---

Plan Title=Multiple Run
Short Identifier=Multiple
Geom File=g01
Flow File=f01
Subcritical Flow
K Sum by GR= 0
Std Step Tol= 0.01
Critical Tol= 0.01
Num of Std Step Trials= 20
Max Error Tol= 0.3
Flow Tol Ratio= 0.001
Split Flow NTrial= 30
Split Flow Tol= 0.02
Split Flow Ratio= 0.02
Log Output Level= 0
Friction Slope Method= 1
Unsteady Friction Slope Method= 2
Unsteady Bridges Friction Slope Method= 1
Parabolic Critical Depth
Global Vel Dist=  1 , 1 , 1
Global Log Level= 0
CheckData=True
Encroach Param= -1, 0, 0, 0
BEGIN DESCRIPTION:
Multiple Run
END DESCRIPTION:

--- BURK BRANCH.f01 (steady flow) ---

Flow Title=Multiple
Number of Profiles=7
Profile Names=10-year,25-year,50-year,1pct_min,100-year,1pct_plu,500-year
River Rch & RM= BURK BRANCH,Reach-1,2812
     521     687     819     485     967    1930    1346
Boundary for River Rch & Prof#=BURK BRANCH,Reach-1,1
Up Type=0
Dn Type=3
Dn Slope=0.005
Boundary for River Rch & Prof#=BURK BRANCH,Reach-1,2
Up Type=0
Dn Type=3
Dn Slope=0.005
Boundary for River Rch & Prof#=BURK BRANCH,Reach-1,3
Up Type=0
Dn Type=3
Dn Slope=0.005
Boundary for River Rch & Prof#=BURK BRANCH,Reach-1,4
Up Type=0
Dn Type=3
Dn Slope=0.005
Boundary for River Rch & Prof#=BURK BRANCH,Reach-1,5
Up Type=0
Dn Type=3
Dn Slope=0.005
Boundary for River Rch & Prof#=BURK BRANCH,Reach-1,6
Up Type=0
Dn Type=3
Dn Slope=0.005
Boundary for River Rch & Prof#=BURK BRANCH,Reach-1,7
Up Type=0
Dn Type=3
Dn Slope=0.005

--- BURK BRANCH.g01 (geometry) ---

Geom Title=Existing Conditions

River Reach=BURK BRANCH,Reach-1
Reach XY= 30
      2776606.83      7071447.30      2776644.26      7071542.30
      2776727.98      7071645.79      2776773.44      7071637.02
      2776824.49      7071679.73      2776890.03      7071623.10
      2776943.31      7071716.52      2777013.19      7071754.14
      2777102.51      7071711.70      2777203.18      7071752.09
      2777270.60      7071895.49      2777222.56      7071910.45
      2777186.75      7071991.23      2777202.10      7072223.86
      2777329.27      7072283.46      2777351.02      7072413.32
      2777429.46      7072472.63      2777548.44      7072495.24
      2777637.23      7072556.58      2777693.41      7072532.98
      2777705.45      7072610.37      2777678.63      7072670.76
      2777699.97      7072792.83      2777833.01      7072848.76
      2777971.68      7072984.05      2778079.91      7072969.40
      2778145.30      7072931.06      2778276.08      7072976.16
      2778333.57      7072929.94      2778439.28      7072957.40

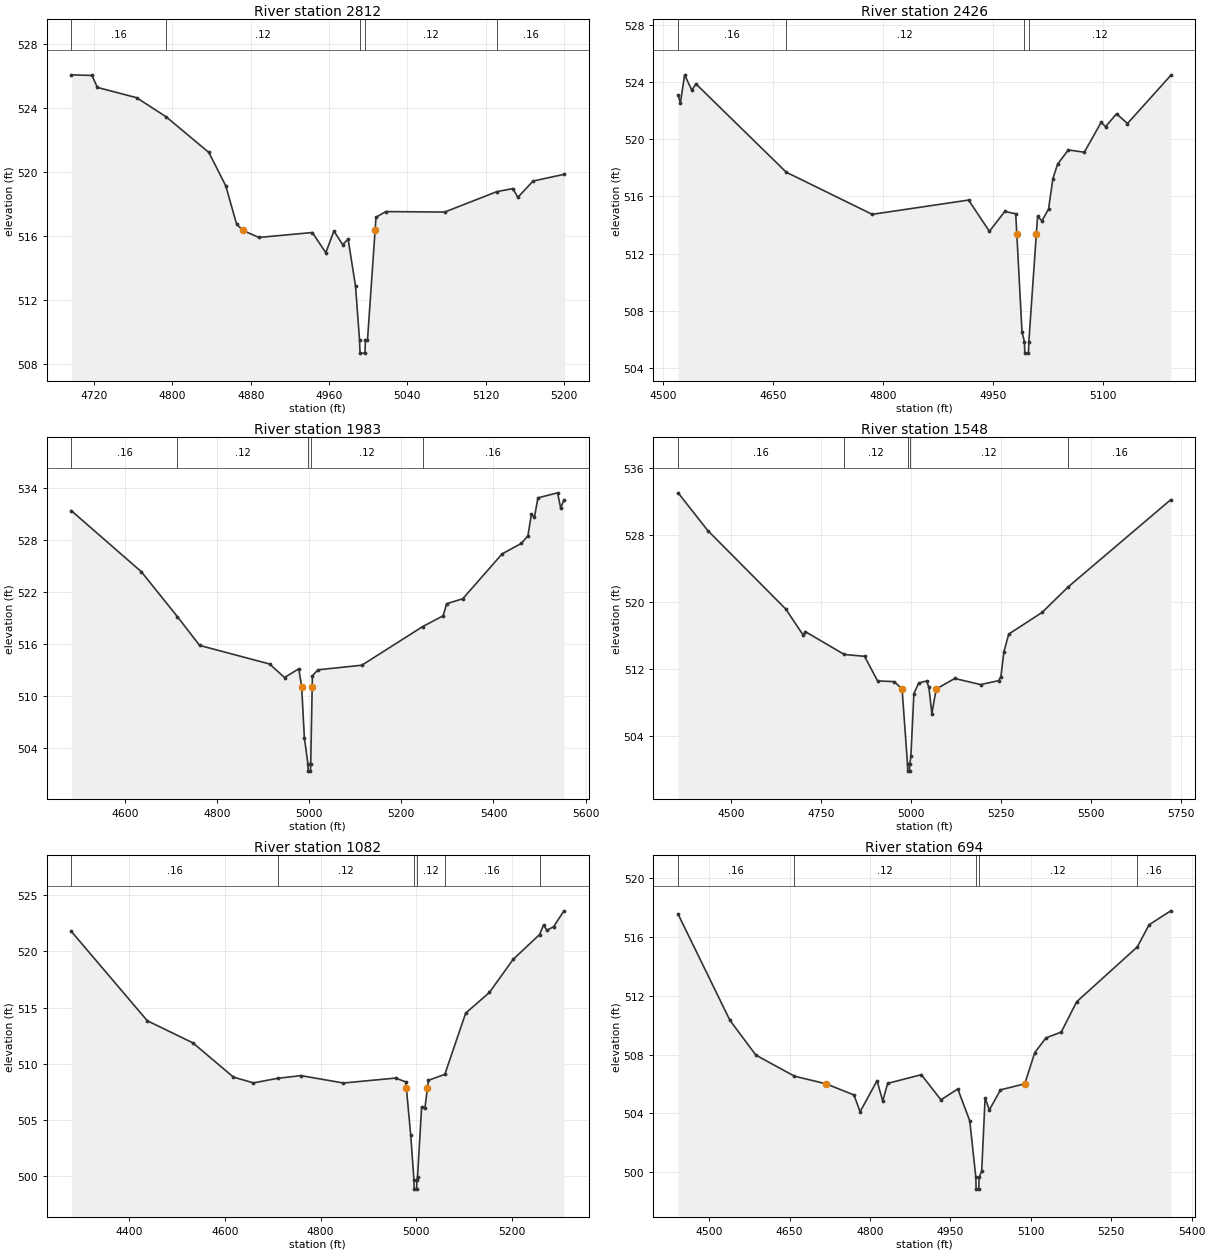
Type RM Length L Ch R = 1,2812,386,386,386
BEGIN DESCRIPTION:
BURK BRANCH 5.0
END DESCRIPTION:
XS GIS Cut Line= 3
      2776760.42      7071897.87      2776887.78      7071627.23
      2776903.70      7071423.46
#Sta/Elev= 30
  4696.6  526.10  4717.7  526.06  4723.3  525.31  4763.3  524.67  4793.6  523.47
  4837.2  521.24  4854.5  519.15  4865.5  516.76  4871.7  516.37  4888.3  515.92
  4942.9  516.23  4956.7  514.97  4965.0  516.32  4974.0  515.47  4979.5  515.82
  4987.1  512.87  4991.2  509.48  4991.7  508.68  4996.7  508.68  4997.2  509.48
  4999.3  509.48  5007.1  516.37  5008.0  517.18  5018.0  517.54  5078.2  517.51
  5131.6  518.79  5148.0  518.98  5153.0  518.43  5168.5  519.45  5200.1  519.87
#Mann=5,-1,0
  4696.6    0.16       0  4793.6    0.12       0  4991.2    0.07       0
  4997.2    0.12       0  5131.6    0.16       0
Bank Sta=4871.7,5007.1
Exp/Cntr=0.3,0.1

Type RM Length L Ch R = 1,2426,443,443,443
BEGIN DESCRIPTION:
Mapping XS 03b0e01a
END DESCRIPTION:
XS GIS Cut Line= 3
      2776808.21      7072022.07      2777110.68      7071840.58
      2777291.07      7071577.91
#Sta/Elev= 30
  4520.7  523.12  4523.8  522.54  4529.6  524.52  4539.3  523.45  4545.1  523.88
  4668.1  517.70  4785.2  514.75  4916.6  515.75  4944.9  513.56  4965.9  514.95
  4980.8  514.79  4982.3  513.38  4989.4  506.50  4992.7  505.83  4993.2  505.03
  4998.2  505.03  4998.7  505.83  5008.9  513.38  5010.6  514.60  5016.6  514.30
  5025.5  515.11  5031.5  517.25  5037.9  518.27  5052.5  519.26  5074.3  519.10
  5097.2  521.19  5103.3  520.89  5118.2  521.79  5133.1  521.11  5192.1  524.48
#Mann=4,-1,0
  4520.7    0.16       0  4668.1    0.12       0  4992.7    0.07       0
  4998.7    0.12       0
Bank Sta=4982.3,5008.9
Exp/Cntr=0.3,0.1

Type RM Length L Ch R = 1,1983,435,435,435
BEGIN DESCRIPTION:
BURK BRANCH 4.0
END DESCRIPTION:
XS GIS Cut Line= 3
      2776725.02      7072274.99      2777225.00      7072075.00
      2777575.00      7071675.00
#Sta/Elev= 30
  4483.1  531.37  4635.2  524.32  4713.7  519.12  4761.8  515.81  4913.9  513.66
  4946.2  512.10  4977.2  513.11  4983.4  511.06  4989.3  505.16  4997.1  502.09
  4997.6  501.29  5002.6  501.29  5003.1  502.09  5006.3  511.06  5006.8  512.31
  5018.9  512.99  5114.1  513.52  5246.5  517.99  5290.7  519.23  5298.3  520.62
  5333.4  521.20  5418.8  526.38  5460.6  527.59  5474.8  528.46  5482.4  530.96
  5489.0  530.62  5496.6  532.85  5539.3  533.43  5546.0  531.67  5553.1  532.63
#Mann=5,-1,0
  4483.1    0.16       0  4713.7    0.12       0  4997.1    0.07       0
  5003.1    0.12       0  5246.5    0.16       0
Bank Sta=4983.4,5006.3
Exp/Cntr=0.3,0.1

Type RM Length L Ch R = 1,1548,466,466,466
BEGIN DESCRIPTION:
BURK BRANCH 3.0
END DESCRIPTION:
XS GIS Cut Line= 3
      2776725.04      7072574.99      2777325.00      7072425.00
      2777924.98      7071975.02
#Sta/Elev= 30
  4352.3  533.04  4434.7  528.53  4651.2  519.15  4700.1  516.00  4705.3  516.45
  4814.0  513.71  4870.2  513.49  4906.3  510.55  4952.7  510.46  4974.4  509.58
  4989.6  500.56  4990.1  499.76  4995.1  499.76  4995.6  500.56  4998.9  501.54
  5007.2  509.04  5020.7  510.30  5042.6  510.54  5048.9  509.77  5057.2  506.63
  5069.1  509.58  5120.7  510.84  5192.6  510.11  5242.6  510.58  5248.9  511.06
  5257.2  514.02  5270.7  516.15  5363.4  518.74  5436.0  521.80  5720.7  532.22
#Mann=5,-1,0
  4352.3    0.16       0  4814.0    0.12       0  4989.6    0.07       0
  4995.6    0.12       0  5436.0    0.16       0
Bank Sta=4974.4,5069.1
Exp/Cntr=0.3,0.1

Type RM Length L Ch R = 1,1082,388,388,388
BEGIN DESCRIPTION:
BURK BRANCH 2.0
END DESCRIPTION:
XS GIS Cut Line= 3
      2777025.01      7072825.00      2777708.51      7072590.45
      2777925.03      7072374.97
#Sta/Elev= 30
  4279.8  521.79  4438.4  513.82  4533.5  511.85  4618.1  508.80  4660.0  508.28
  4710.5  508.69  4759.1  508.93  4847.6  508.27  4956.4  508.71  4977.9  508.37
  4979.1  507.81  4988.1  503.65  4994.9  499.61  4995.4  498.81  5000.4  498.81
  5000.9  499.61  5002.4  499.93  5010.9  506.16  5017.9  506.07  5023.0  507.81
  5025.0  508.51  5059.3  509.04  5102.8  514.50  5152.3  516.34  5201.8  519.29
  5256.9  521.50  5265.4  522.35  5272.5  521.88  5286.6  522.22  5307.9  523.62
#Mann=6,-1,0
  4279.8    0.16       0  4710.5    0.12       0  4994.9    0.07       0
  5000.9    0.12       0  5059.3    0.16       0  5256.9    0.12       0
Bank Sta=4979.1,5023
Exp/Cntr=0.3,0.1

Type RM Length L Ch R = 1,694,360,360,360
BEGIN DESCRIPTION:
Mapping XS 79fba4b8
END DESCRIPTION:
XS GIS Cut Line= 3
      2777333.58      7073057.01      2777830.35      7072888.24
      2778080.93      7072583.74
#Sta/Elev= 30
  4442.0  517.54  4538.6  510.33  4587.1  507.96  4659.0  506.53  4718.0  506.01
  4770.1  505.25  4781.5  504.11  4813.1  506.22  4823.7  504.84  4832.9  506.04
  4895.7  506.63  4932.3  504.92  4963.7  505.66  4986.1  503.49  4997.4  499.65
  4997.9  498.85  5002.9  498.85  5003.4  499.65  5008.3  500.07  5014.7  505.06
  5022.6  504.23  5043.4  505.60  5088.7  506.01  5107.3  508.13  5128.1  509.13
  5156.8  509.53  5185.5  511.59  5298.7  515.32  5320.5  516.82  5361.0  517.77
#Mann=5,-1,0
  4442.0    0.16       0  4659.0    0.12       0  4997.4    0.07       0
  5003.4    0.12       0  5298.7    0.16       0
Bank Sta=4718,5088.7
Exp/Cntr=0.3,0.1

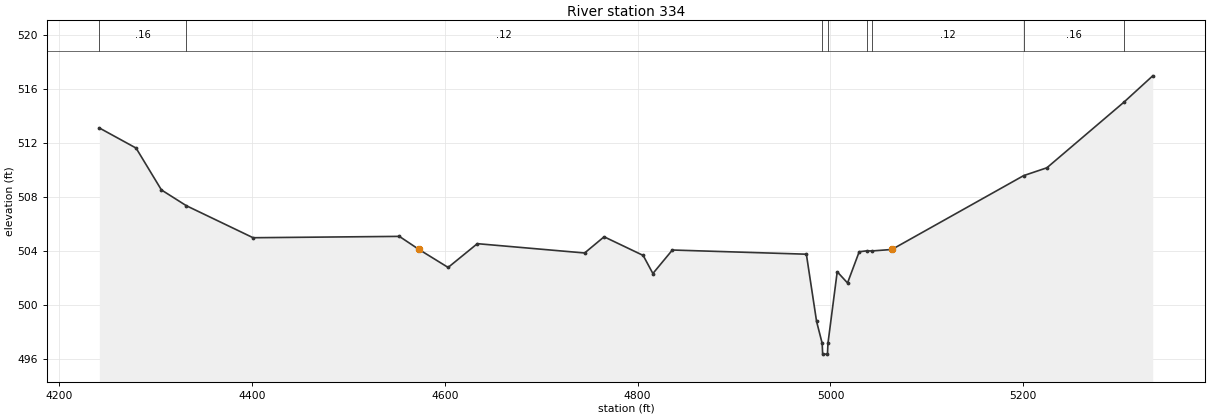
Type RM Length L Ch R = 1,334,0,0,0
BEGIN DESCRIPTION:
BURK BRANCH 1.0
END DESCRIPTION:
XS GIS Cut Line= 3
      2777467.29      7073139.81      2778097.83      7073044.27
      2778259.66      7072619.06
#Sta/Elev= 30
  4241.6  513.12  4279.7  511.63  4306.0  508.53  4331.9  507.36  4401.1  504.99
  4552.8  505.09  4573.2  504.12  4603.4  502.79  4633.7  504.55  4745.0  503.86
  4765.2  505.06  4805.7  503.68  4815.8  502.34  4836.0  504.08  4975.0  503.77
  4985.6  498.79  4991.4  497.17  4991.9  496.37  4996.9  496.37  4997.4  497.17
  5007.0  502.47  5017.7  501.64  5029.8  503.95  5037.6  504.02  5042.9  504.01
  5063.7  504.12  5200.4  509.59  5224.5  510.17  5304.1  515.01  5334.3  516.98
#Mann=8,-1,0
  4241.6    0.16       0  4331.9    0.12       0  4991.4    0.07       0
  4997.4    0.12       0  5037.6    0.07       0  5042.9    0.12       0
  5200.4    0.16       0  5304.1    0.12       0
Bank Sta=4573.2,5063.7
Exp/Cntr=0.3,0.1

Chan Stop Cuts=-1