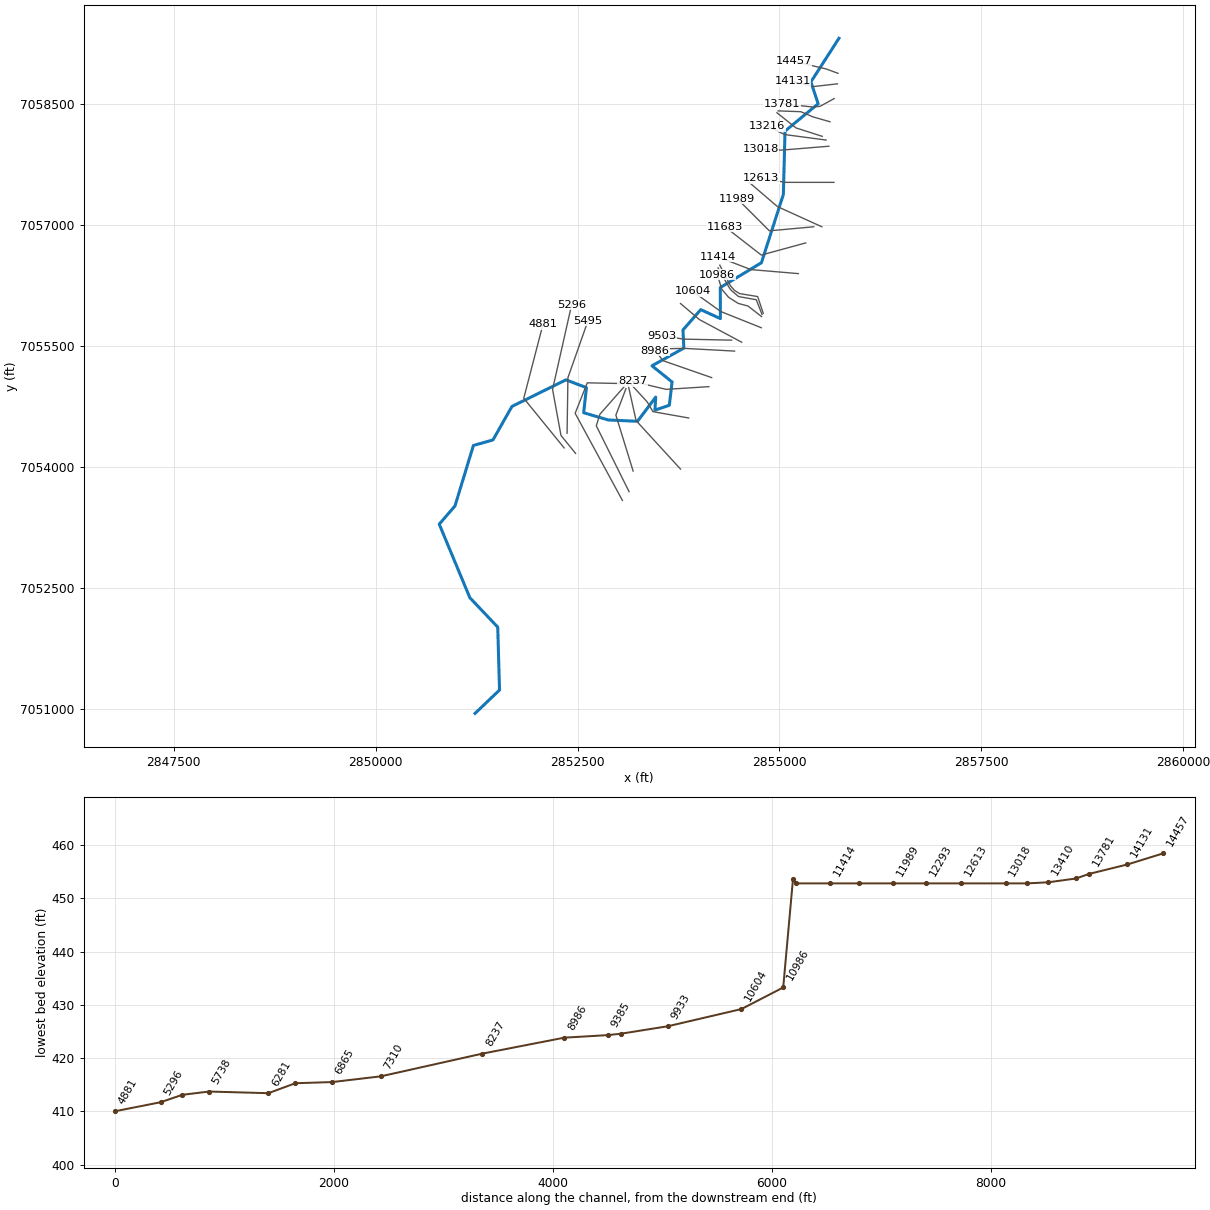
--- CANE BRANCH.prj (project) ---

Proj Title=CANE BRANCH Base Level Engineering
Current Plan=p01
Default Exp/Contr=0.3,0.1
English Units
Geom File=g01
Flow File=f01
Plan File=p01
BEGIN DESCRIPTION:
CANE BRANCH
END DESCRIPTION:

--- CANE BRANCH.p01 (plan) ---

Plan Title=Multiple Run
Short Identifier=Multiple
Geom File=g01
Flow File=f01
Subcritical Flow
K Sum by GR= 0
Std Step Tol= 0.01
Critical Tol= 0.01
Num of Std Step Trials= 20
Max Error Tol= 0.3
Flow Tol Ratio= 0.001
Split Flow NTrial= 30
Split Flow Tol= 0.02
Split Flow Ratio= 0.02
Log Output Level= 0
Friction Slope Method= 1
Unsteady Friction Slope Method= 2
Unsteady Bridges Friction Slope Method= 1
Parabolic Critical Depth
Global Vel Dist=  1 , 1 , 1
Global Log Level= 0
CheckData=True
Encroach Param= -1, 0, 0, 0
BEGIN DESCRIPTION:
Multiple Run
END DESCRIPTION:

--- CANE BRANCH.f01 (steady flow) ---

Flow Title=Multiple
Number of Profiles=7
Profile Names=10-year,25-year,50-year,1pct_min,100-year,1pct_plu,500-year
River Rch & RM= CANE BRANCH,Reach-1,14457
     457     596     706     415     829    1654    1140
River Rch & RM= CANE BRANCH,Reach-1,11105
     753    1016    1231     740    1477    2946    2128
Boundary for River Rch & Prof#=CANE BRANCH,Reach-1,1
Up Type=0
Dn Type=3
Dn Slope=0.005
Boundary for River Rch & Prof#=CANE BRANCH,Reach-1,2
Up Type=0
Dn Type=3
Dn Slope=0.005
Boundary for River Rch & Prof#=CANE BRANCH,Reach-1,3
Up Type=0
Dn Type=3
Dn Slope=0.005
Boundary for River Rch & Prof#=CANE BRANCH,Reach-1,4
Up Type=0
Dn Type=3
Dn Slope=0.005
Boundary for River Rch & Prof#=CANE BRANCH,Reach-1,5
Up Type=0
Dn Type=3
Dn Slope=0.005
Boundary for River Rch & Prof#=CANE BRANCH,Reach-1,6
Up Type=0
Dn Type=3
Dn Slope=0.005
Boundary for River Rch & Prof#=CANE BRANCH,Reach-1,7
Up Type=0
Dn Type=3
Dn Slope=0.005

--- CANE BRANCH.g01 (geometry) ---

Geom Title=Existing Conditions

River Reach=CANE BRANCH,Reach-1
Reach XY= 30
      2855736.48      7059308.27      2855389.61      7058769.27
      2855479.60      7058498.09      2855069.00      7058159.63
      2855048.47      7057375.81      2854776.99      7056529.91
      2854267.38      7056222.84      2854268.79      7055837.97
      2854025.45      7055948.88      2853805.29      7055697.26
      2853816.23      7055472.64      2853421.56      7055253.68
      2853670.63      7055053.36      2853636.54      7054765.55
      2853458.31      7054704.10      2853468.04      7054865.87
      2853242.49      7054566.52      2852880.96      7054582.98
      2852575.75      7054672.56      2852610.46      7054983.47
      2852355.73      7055079.34      2851687.85      7054750.18
      2851452.71      7054335.70      2851210.74      7054267.38
      2850982.43      7053518.12      2850787.72      7053292.67
      2851166.90      7052381.72      2851511.92      7052017.91
      2851534.16      7051238.98      2851231.19      7050950.06

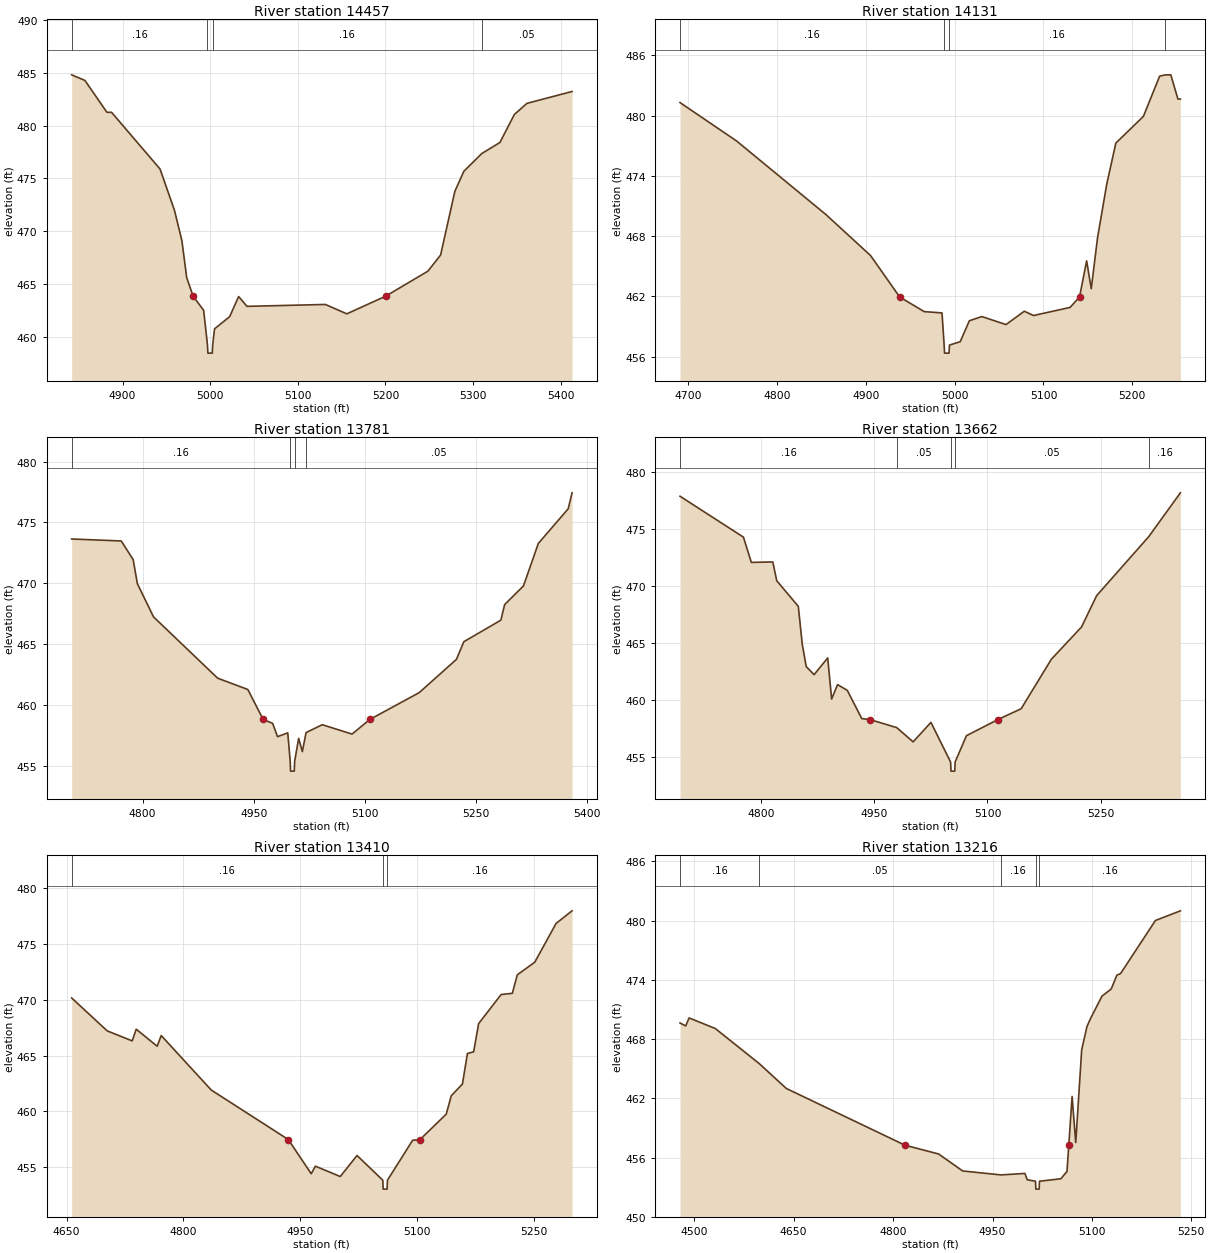
Type RM Length L Ch R = 1,14457,326,326,326
BEGIN DESCRIPTION:
CANE BRANCH 18.0
END DESCRIPTION:
XS GIS Cut Line= 3
      2855724.97      7058875.01      2855583.82      7058927.52
      2855174.98      7059025.00
#Sta/Elev= 30
  4842.0  484.80  4857.1  484.27  4882.2  481.25  4887.5  481.25  4942.8  475.88
  4959.3  471.96  4967.8  469.07  4973.2  465.60  4980.5  463.84  4992.6  462.49
  4996.9  459.24  4997.4  458.44  5002.4  458.44  5002.9  459.24  5005.0  460.74
  5022.2  461.89  5032.5  463.80  5042.0  462.87  5131.4  463.05  5155.9  462.16
  5200.4  463.84  5248.4  466.20  5262.9  467.73  5279.2  473.77  5289.5  475.67
  5310.0  477.35  5330.6  478.39  5347.1  481.05  5361.5  482.10  5412.9  483.22
#Mann=4,-1,0
  4842.0    0.16       0  4996.9    0.07       0  5002.9    0.16       0
  5310.0    0.05       0
Bank Sta=4980.5,5200.4
Exp/Cntr=0.3,0.1

Type RM Length L Ch R = 1,14131,350,350,350
BEGIN DESCRIPTION:
Mapping XS b8eb52e7
END DESCRIPTION:
XS GIS Cut Line= 3
      2855718.24      7058744.95      2855419.30      7058710.84
      2855164.54      7058775.03
#Sta/Elev= 30
  4690.6  481.29  4754.3  477.47  4854.9  470.15  4905.2  466.07  4938.0  461.95
  4965.6  460.49  4985.7  460.36  4988.1  457.16  4988.6  456.36  4993.6  456.36
  4994.1  457.16  5006.2  457.50  5016.5  459.58  5030.5  460.00  5057.8  459.20
  5078.4  460.53  5088.7  460.10  5130.0  460.91  5140.6  461.95  5148.6  465.54
  5153.8  462.77  5160.9  467.85  5171.2  473.15  5181.5  477.26  5212.5  479.91
  5230.8  483.91  5236.8  484.04  5243.4  484.05  5251.4  481.64  5254.2  481.64
#Mann=4,-1,0
  4690.6    0.16       0  4988.1    0.07       0  4994.1    0.16       0
  5236.8    0.12       0
Bank Sta=4938,5140.6
Exp/Cntr=0.3,0.1

Type RM Length L Ch R = 1,13781,119,119,119
BEGIN DESCRIPTION:
Mapping XS 516e4ec0
END DESCRIPTION:
XS GIS Cut Line= 4
      2855678.09      7058562.36      2855501.56      7058466.07
      2855411.28      7058458.04      2855029.80      7058499.98
#Sta/Elev= 30
  4704.3  473.64  4771.2  473.48  4787.3  471.95  4793.0  469.97  4814.8  467.25
  4901.3  462.22  4942.1  461.29  4962.8  458.83  4975.6  458.51  4982.2  457.42
  4996.0  457.73  4999.3  455.39  4999.8  454.59  5004.8  454.59  5005.3  455.39
  5010.7  457.28  5015.7  456.19  5020.7  457.75  5042.6  458.40  5082.8  457.63
  5106.8  458.83  5173.4  461.03  5223.7  463.76  5233.7  465.21  5283.7  466.98
  5288.8  468.26  5314.2  469.79  5334.3  473.28  5374.6  476.12  5379.8  477.43
#Mann=4,-1,0
  4704.3    0.16       0  4999.3    0.07       0  5005.3    0.16       0
  5020.7    0.05       0
Bank Sta=4962.8,5106.8
Exp/Cntr=0.3,0.1

Type RM Length L Ch R = 1,13662,252,252,252
BEGIN DESCRIPTION:
Mapping XS 07888d4b
END DESCRIPTION:
XS GIS Cut Line= 4
      2855625.93      7058275.47      2855415.29      7058335.65
      2855264.81      7058399.86      2854983.97      7058409.89
#Sta/Elev= 30
  4692.2  477.87  4776.3  474.28  4786.8  472.06  4815.3  472.10  4820.5  470.45
  4849.1  468.20  4854.3  464.89  4859.6  462.91  4870.0  462.20  4888.1  463.67
  4893.3  460.06  4901.2  461.33  4914.1  460.82  4933.3  458.34  4944.1  458.26
  4979.7  457.55  5001.4  456.30  5025.0  458.01  5051.1  454.53  5051.6  453.73
  5056.6  453.73  5057.1  454.53  5072.1  456.84  5113.9  458.26  5144.7  459.21
  5184.8  463.56  5224.8  466.39  5244.8  469.14  5313.9  474.32  5355.9  478.17
#Mann=5,-1,0
  4692.2    0.16       0  4979.7    0.05       0  5051.1    0.04       0
  5057.1    0.05       0  5313.9    0.16       0
Bank Sta=4944.1,5113.9
Exp/Cntr=0.3,0.1

Type RM Length L Ch R = 1,13410,194,194,194
BEGIN DESCRIPTION:
Mapping XS dea2b8e7
END DESCRIPTION:
XS GIS Cut Line= 3
      2855529.67      7058094.88      2855204.62      7058199.22
      2854968.95      7058386.96
#Sta/Elev= 30
  4656.6  470.17  4702.2  467.22  4734.3  466.32  4739.5  467.37  4766.4  465.84
  4771.6  466.80  4835.9  461.91  4934.8  457.47  4964.3  454.40  4969.6  455.08
  5001.6  454.15  5023.1  456.04  5056.2  453.82  5056.7  453.02  5061.7  453.02
  5062.2  453.82  5094.5  457.40  5104.1  457.47  5137.7  459.75  5144.1  461.39
  5158.5  462.45  5164.9  465.19  5172.9  465.34  5179.3  467.87  5208.2  470.48
  5222.6  470.59  5229.0  472.25  5251.4  473.38  5278.8  476.86  5299.3  477.99
#Mann=3,-1,0
  4656.6    0.16       0  5056.2    0.07       0  5062.2    0.16       0
Bank Sta=4934.8,5104.1
Exp/Cntr=0.3,0.1

Type RM Length L Ch R = 1,13216,198,198,198
BEGIN DESCRIPTION:
CANE BRANCH 15.0
END DESCRIPTION:
XS GIS Cut Line= 3
      2855577.76      7058048.75      2855064.18      7058116.96
      2854851.10      7058220.52
#Sta/Elev= 30
  4478.5  469.64  4487.1  469.34  4492.2  470.15  4531.7  469.08  4598.3  465.51
  4638.8  463.01  4817.9  457.26  4868.7  456.37  4905.0  454.65  4962.8  454.25
  4998.9  454.40  5002.4  453.76  5014.9  453.61  5015.4  452.81  5020.4  452.81
  5020.9  453.61  5053.1  453.86  5062.4  454.60  5065.1  457.26  5070.1  462.20
  5075.6  457.53  5084.6  466.94  5092.6  469.30  5098.2  470.13  5115.2  472.36
  5129.1  473.08  5137.7  474.48  5143.3  474.65  5195.8  480.02  5233.5  481.00
#Mann=5,-1,0
  4478.5    0.16       0  4598.3    0.05       0  4962.8    0.16       0
  5014.9    0.07       0  5020.9    0.16       0
Bank Sta=4817.9,5065.1
Exp/Cntr=0.3,0.1

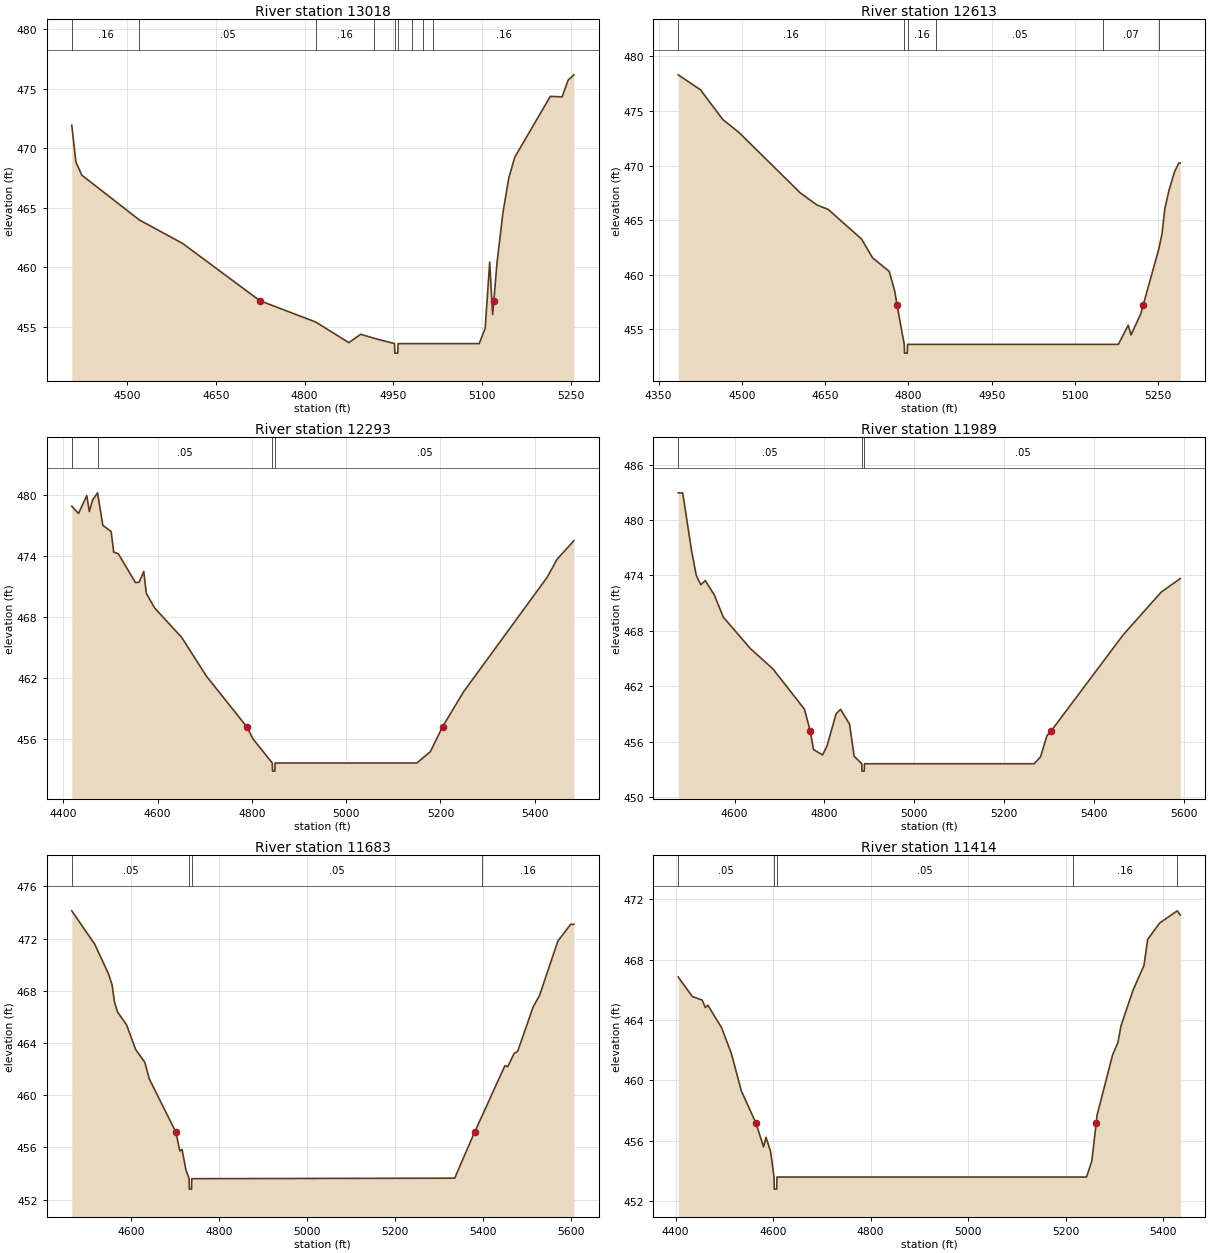
Type RM Length L Ch R = 1,13018,405,405,405
BEGIN DESCRIPTION:
Mapping XS 24c9462e
END DESCRIPTION:
XS GIS Cut Line= 3
      2855611.96      7057972.51      2855028.07      7057924.35
      2854765.22      7057936.39
#Sta/Elev= 30
  4406.2  471.93  4413.2  468.85  4423.2  467.74  4520.6  463.98  4593.8  462.01
  4724.2  457.21  4818.7  455.42  4874.7  453.69  4894.8  454.39  4917.9  454.05
  4952.0  453.61  4952.5  452.81  4957.5  452.81  4958.0  453.61  4982.0  453.61
  5000.6  453.61  5017.2  453.61  5095.2  453.61  5105.3  454.90  5112.9  460.45
  5117.9  456.05  5119.9  457.21  5125.3  460.39  5135.3  464.60  5145.3  467.52
  5155.3  469.25  5215.4  474.35  5235.4  474.31  5245.4  475.70  5255.2  476.16
#Mann=9,-1,0
  4406.2    0.16       0  4520.6    0.05       0  4818.7    0.16       0
  4917.9    0.05       0  4952.0    0.07       0  4958.0    0.05       0
  4982.0    0.16       0  5000.6    0.05       0  5017.2    0.16       0
Bank Sta=4724.2,5119.9
Exp/Cntr=0.3,0.1

Type RM Length L Ch R = 1,12613,320,320,320
BEGIN DESCRIPTION:
CANE BRANCH 14.0
END DESCRIPTION:
XS GIS Cut Line= 3
      2855675.02      7057525.00      2855075.00      7057525.00
      2854774.96      7057575.01
#Sta/Elev= 30
  4385.5  478.31  4425.5  476.94  4465.5  474.23  4495.5  473.00  4605.5  467.48
  4635.5  466.38  4655.5  465.98  4715.5  463.27  4735.5  461.54  4765.5  460.30
  4775.5  458.46  4779.6  457.19  4792.5  453.61  4793.0  452.81  4798.0  452.81
  4798.5  453.61  4850.0  453.61  5150.1  453.61  5178.1  453.61  5195.9  455.37
  5201.0  454.48  5218.7  456.44  5222.7  457.19  5250.9  462.34  5256.7  463.73
  5261.8  466.04  5269.4  467.74  5279.5  469.46  5287.1  470.22  5289.7  470.22
#Mann=6,-1,0
  4385.5    0.16       0  4792.5   0.033       0  4798.5    0.16       0
  4850.0    0.05       0  5150.1    0.07       0  5250.9    0.05       0
Bank Sta=4779.6,5222.7
Exp/Cntr=0.3,0.1

Type RM Length L Ch R = 1,12293,304,304,304
BEGIN DESCRIPTION:
CANE BRANCH 13.0
END DESCRIPTION:
XS GIS Cut Line= 3
      2855524.98      7056975.01      2854975.00      7057225.00
      2854625.01      7057524.99
#Sta/Elev= 30
  4418.0  478.93  4432.3  478.21  4449.8  479.98  4455.3  478.41  4461.9  479.51
  4472.7  480.25  4483.9  477.05  4501.5  476.43  4507.0  474.41  4516.8  474.24
  4553.1  471.40  4560.8  471.43  4570.7  472.50  4576.2  470.33  4593.7  468.90
  4650.9  466.01  4703.6  462.18  4789.3  457.18  4802.4  455.99  4843.4  453.61
  4843.9  452.81  4848.9  452.81  4849.4  453.61  5150.0  453.61  5178.5  454.72
  5204.6  457.18  5248.8  460.61  5426.6  471.93  5447.4  473.69  5483.1  475.53
#Mann=4,-1,0
  4418.0    0.16       0  4472.7    0.05       0  4843.4   0.033       0
  4849.4    0.05       0
Bank Sta=4789.3,5204.6
Exp/Cntr=0.3,0.1

Type RM Length L Ch R = 1,11989,306,306,306
BEGIN DESCRIPTION:
CANE BRANCH 12.0
END DESCRIPTION:
XS GIS Cut Line= 3
      2855424.97      7056975.00      2854875.00      7056925.00
      2854475.01      7057324.99
#Sta/Elev= 30
  4474.4  482.94  4484.4  482.92  4504.5  476.56  4514.5  474.02  4524.6  472.98
  4534.6  473.45  4554.7  471.89  4574.8  469.48  4635.0  466.08  4685.2  463.88
  4755.5  459.51  4768.2  457.17  4775.6  455.15  4795.7  454.56  4805.7  455.54
  4825.8  459.01  4835.9  459.50  4855.9  457.89  4866.0  454.43  4883.1  453.61
  4883.6  452.81  4888.6  452.81  4889.1  453.61  5267.0  453.61  5281.2  454.37
  5295.3  456.64  5304.9  457.17  5465.0  467.56  5549.9  472.20  5592.3  473.66
#Mann=3,-1,0
  4474.4    0.05       0  4883.1   0.033       0  4889.1    0.05       0
Bank Sta=4768.2,5304.9
Exp/Cntr=0.3,0.1

Type RM Length L Ch R = 1,11683,269,269,269
BEGIN DESCRIPTION:
CANE BRANCH 11.0
END DESCRIPTION:
XS GIS Cut Line= 3
      2855325.03      7056775.01      2854775.00      7056625.00
      2854325.01      7056975.00
#Sta/Elev= 30
  4465.9  474.12  4517.8  471.58  4548.9  469.33  4557.5  468.44  4562.7  467.18
  4569.6  466.39  4590.3  465.39  4611.0  463.50  4631.8  462.52  4642.1  461.24
  4702.4  457.17  4711.2  455.74  4716.4  455.85  4725.1  454.29  4732.4  453.61
  4732.9  452.81  4737.9  452.81  4738.4  453.61  5335.5  453.65  5380.6  457.17
  5397.7  458.42  5449.6  462.27  5455.9  462.18  5470.4  463.19  5478.5  463.36
  5513.8  466.77  5528.3  467.65  5569.9  471.81  5598.9  473.09  5606.1  473.08
#Mann=4,-1,0
  4465.9    0.05       0  4732.4   0.033       0  4738.4    0.05       0
  5397.7    0.16       0
Bank Sta=4702.4,5380.6
Exp/Cntr=0.3,0.1

Type RM Length L Ch R = 1,11414,309,309,309
BEGIN DESCRIPTION:
Mapping XS 348dd75a
END DESCRIPTION:
XS GIS Cut Line= 3
      2855233.81      7056395.15      2854645.72      7056445.06
      2854235.56      7056603.49
#Sta/Elev= 30
  4405.4  466.84  4434.3  465.55  4454.4  465.32  4461.1  464.82  4466.1  464.98
  4494.5  463.48  4514.6  461.76  4534.7  459.32  4564.9  457.17  4580.4  455.60
  4585.4  456.24  4594.9  455.29  4601.9  453.61  4602.4  452.81  4607.4  452.81
  4607.9  453.61  5214.6  453.61  5242.9  453.61  5253.7  454.66  5262.8  457.17
  5264.4  457.68  5296.5  461.70  5307.3  462.50  5313.6  463.61  5338.2  465.96
  5360.9  467.62  5368.2  469.32  5392.8  470.41  5428.9  471.22  5435.3  470.94
#Mann=5,-1,0
  4405.4    0.05       0  4601.9   0.033       0  4607.9    0.05       0
  5214.6    0.16       0  5428.9    0.05       0
Bank Sta=4564.9,5262.8
Exp/Cntr=0.3,0.1

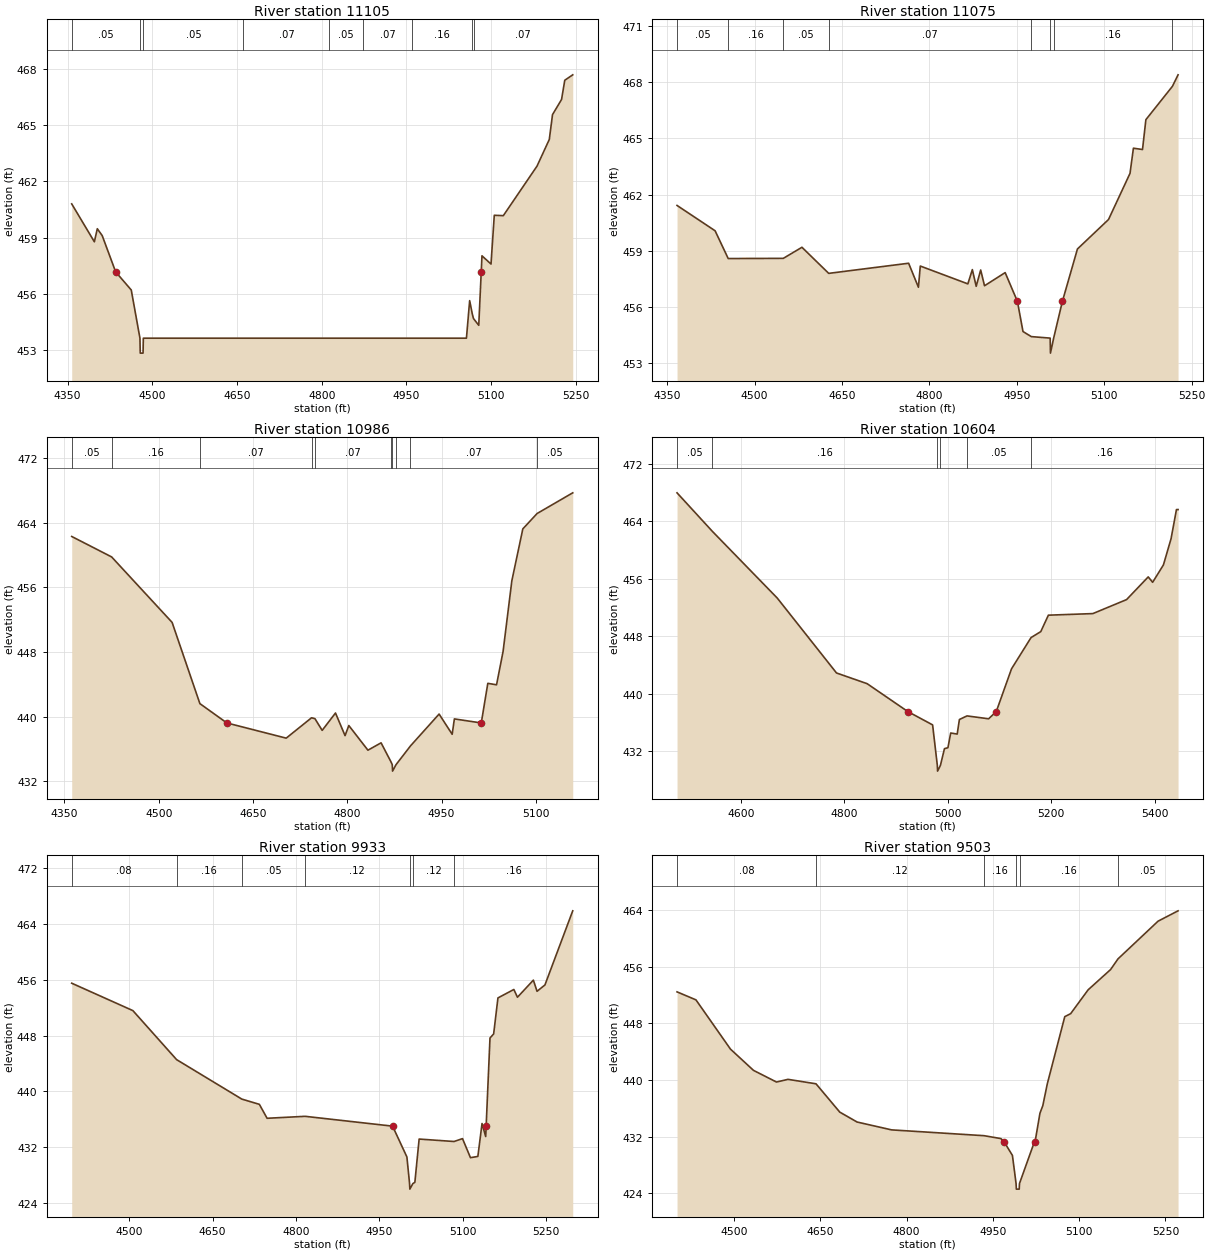
Type RM Length L Ch R = 1,11105,30,30,30
BEGIN DESCRIPTION:
Mapping XS 3d9fda3d
END DESCRIPTION:
XS GIS Cut Line= 6
      2854799.80      7055902.53      2854730.35      7056110.86
      2854506.83      7056147.75      2854446.07      7056184.65
      2854393.98      7056243.24      2854261.58      7056499.36
#Sta/Elev= 30
  4357.4  460.80  4397.5  458.77  4402.7  459.47  4411.4  459.10  4435.2  457.16
  4462.8  456.19  4478.2  453.61  4478.7  452.81  4483.7  452.81  4484.2  453.61
  4661.3  453.61  4813.7  453.61  4873.3  453.61  4959.6  453.61  5056.2  453.61
  5061.9  455.62  5066.7  454.89  5068.7  454.66  5078.0  454.30  5082.4  457.16
  5083.7  458.02  5099.7  457.58  5105.5  460.19  5121.5  460.17  5181.1  462.82
  5202.9  464.25  5208.6  465.58  5224.6  466.39  5230.3  467.42  5244.4  467.71
#Mann=9,-1,0
  4357.4    0.05       0  4478.2    0.07       0  4484.2    0.05       0
  4661.3    0.07       0  4813.7    0.05       0  4873.3    0.07       0
  4959.6    0.16       0  5066.7    0.05       0  5068.7    0.07       0
Bank Sta=4435.2,5082.4
Exp/Cntr=0.3,0.1

Type RM Length L Ch R = 1,11075,89,89,89
BEGIN DESCRIPTION:
Mapping XS 5b9bb55d
END DESCRIPTION:
XS GIS Cut Line= 6
      2854784.62      7055889.49      2854712.99      7056071.80
      2854493.81      7056110.86      2854407.00      7056184.65
      2854380.96      7056217.20      2854239.94      7056464.54
#Sta/Elev= 30
  4367.1  461.42  4432.4  460.07  4454.9  458.59  4549.4  458.60  4581.4  459.19
  4627.3  457.80  4764.4  458.34  4781.2  457.06  4784.4  458.19  4866.0  457.24
  4873.7  458.00  4880.3  457.11  4888.0  457.98  4894.6  457.14  4930.0  457.84
  4951.0  456.31  4960.6  454.70  4974.9  454.43  5007.2  454.35  5007.7  453.55
  5013.2  454.35  5028.2  456.31  5054.0  459.10  5107.3  460.67  5144.2  463.13
  5150.0  464.47  5165.6  464.40  5171.4  465.99  5217.0  467.77  5226.6  468.38
#Mann=8,-1,0
  4367.1    0.05       0  4454.9    0.16       0  4549.4    0.05       0
  4627.3    0.07       0  4974.9    0.16       0  5007.2    0.07       0
  5013.2    0.16       0  5217.0    0.05       0
Bank Sta=4951,5028.2
Exp/Cntr=0.3,0.1

Type RM Length L Ch R = 1,10986,382,382,382
BEGIN DESCRIPTION:
Mapping XS b2d8dee1
END DESCRIPTION:
XS GIS Cut Line= 6
      2854778.10      7055863.46      2854611.00      7055993.67
      2854489.47      7056026.23      2854370.11      7056102.18
      2854285.48      7056202.01      2854231.55      7056381.05
#Sta/Elev= 30
  4361.6  462.29  4425.1  459.76  4521.3  451.66  4565.5  441.61  4608.4  439.22
  4702.8  437.34  4743.1  439.86  4748.5  439.75  4760.0  438.30  4781.2  440.45
  4796.4  437.65  4802.4  438.90  4832.8  435.85  4853.7  436.76  4869.2  434.45
  4871.5  434.06  4872.0  433.26  4877.5  434.06  4900.5  436.38  4946.0  440.32
  4966.8  437.82  4970.3  439.72  5013.1  439.22  5023.5  444.12  5037.4  443.94
  5047.8  448.07  5061.7  456.80  5079.2  463.23  5101.9  465.13  5158.6  467.69
#Mann=10,-1,0
  4361.6    0.05       0  4425.1    0.16       0  4565.5    0.07       0
  4743.1    0.16       0  4748.5    0.07       0  4869.2    0.16       0
  4871.5    0.07       0  4877.5    0.16       0  4900.5    0.07       0
  5101.9    0.05       0
Bank Sta=4608.4,5013.1
Exp/Cntr=0.3,0.1

Type RM Length L Ch R = 1,10604,671,671,671
BEGIN DESCRIPTION:
CANE BRANCH 8.0
END DESCRIPTION:
XS GIS Cut Line= 3
      2854774.98      7055725.01      2854275.00      7055925.00
      2853925.01      7056174.99
#Sta/Elev= 30
  4476.7  467.96  4544.8  462.61  4670.5  453.30  4785.0  442.87  4844.2  441.38
  4922.8  437.50  4970.8  435.64  4979.9  430.00  4980.4  429.20  4985.9  430.00
  4993.7  432.33  5000.4  432.46  5005.8  434.51  5018.3  434.36  5022.6  436.39
  5037.3  436.89  5079.1  436.49  5093.9  437.50  5123.3  443.44  5161.1  447.80
  5179.9  448.63  5194.6  450.92  5280.6  451.14  5345.8  453.09  5387.6  456.25
  5396.2  455.50  5417.0  457.92  5431.8  461.58  5442.2  465.63  5445.3  465.63
#Mann=6,-1,0
  4476.7    0.05       0  4544.8    0.16       0  4979.9    0.07       0
  4985.9    0.16       0  5037.3    0.05       0  5161.1    0.16       0
Bank Sta=4922.8,5093.9
Exp/Cntr=0.3,0.1

Type RM Length L Ch R = 1,9933,430,430,430
BEGIN DESCRIPTION:
CANE BRANCH 7.0
END DESCRIPTION:
XS GIS Cut Line= 3
      2854532.40      7055545.61      2854009.37      7055825.80
      2853775.03      7056024.98
#Sta/Elev= 30
  4396.8  455.51  4506.8  451.58  4585.4  444.55  4702.7  438.89  4734.2  438.14
  4748.1  436.14  4816.5  436.42  4973.8  435.01  4999.5  430.59  5004.3  426.78
  5004.8  425.98  5010.3  426.78  5013.8  426.95  5021.5  433.16  5084.2  432.81
  5099.5  433.22  5113.8  430.49  5127.1  430.67  5134.6  435.39  5141.2  433.52
  5142.0  435.01  5148.9  447.65  5155.5  448.24  5163.2  453.40  5191.8  454.61
  5198.3  453.50  5226.9  455.95  5233.5  454.35  5247.7  455.26  5297.7  465.89
#Mann=7,-1,0
  4396.8    0.08       0  4585.4    0.16       0  4702.7    0.05       0
  4816.5    0.12       0  5004.3    0.07       0  5010.3    0.12       0
  5084.2    0.16       0
Bank Sta=4973.8,5142
Exp/Cntr=0.3,0.1

Type RM Length L Ch R = 1,9503,118,118,118
BEGIN DESCRIPTION:
CANE BRANCH 6.0
END DESCRIPTION:
XS GIS Cut Line= 3
      2854407.88      7055571.08      2853811.52      7055584.10
      2853540.71      7055628.36
#Sta/Elev= 30
  4401.0  452.44  4433.9  451.31  4493.9  444.35  4533.9  441.35  4573.9  439.70
  4593.9  440.08  4642.6  439.45  4683.9  435.45  4714.0  434.05  4774.0  432.94
  4934.7  432.12  4964.0  431.71  4969.3  431.29  4984.0  429.33  4990.3  425.37
  4990.8  424.57  4995.8  424.57  4996.3  425.37  5022.4  431.29  5024.4  431.75
  5031.8  435.28  5036.8  436.36  5044.6  439.44  5075.0  448.94  5085.2  449.36
  5115.6  452.73  5154.6  455.59  5167.5  457.10  5237.2  462.43  5271.9  463.89
#Mann=6,-1,0
  4401.0    0.08       0  4642.6    0.12       0  4934.7    0.16       0
  4990.3    0.07       0  4996.3    0.16       0  5167.5    0.05       0
Bank Sta=4969.3,5022.4
Exp/Cntr=0.3,0.1

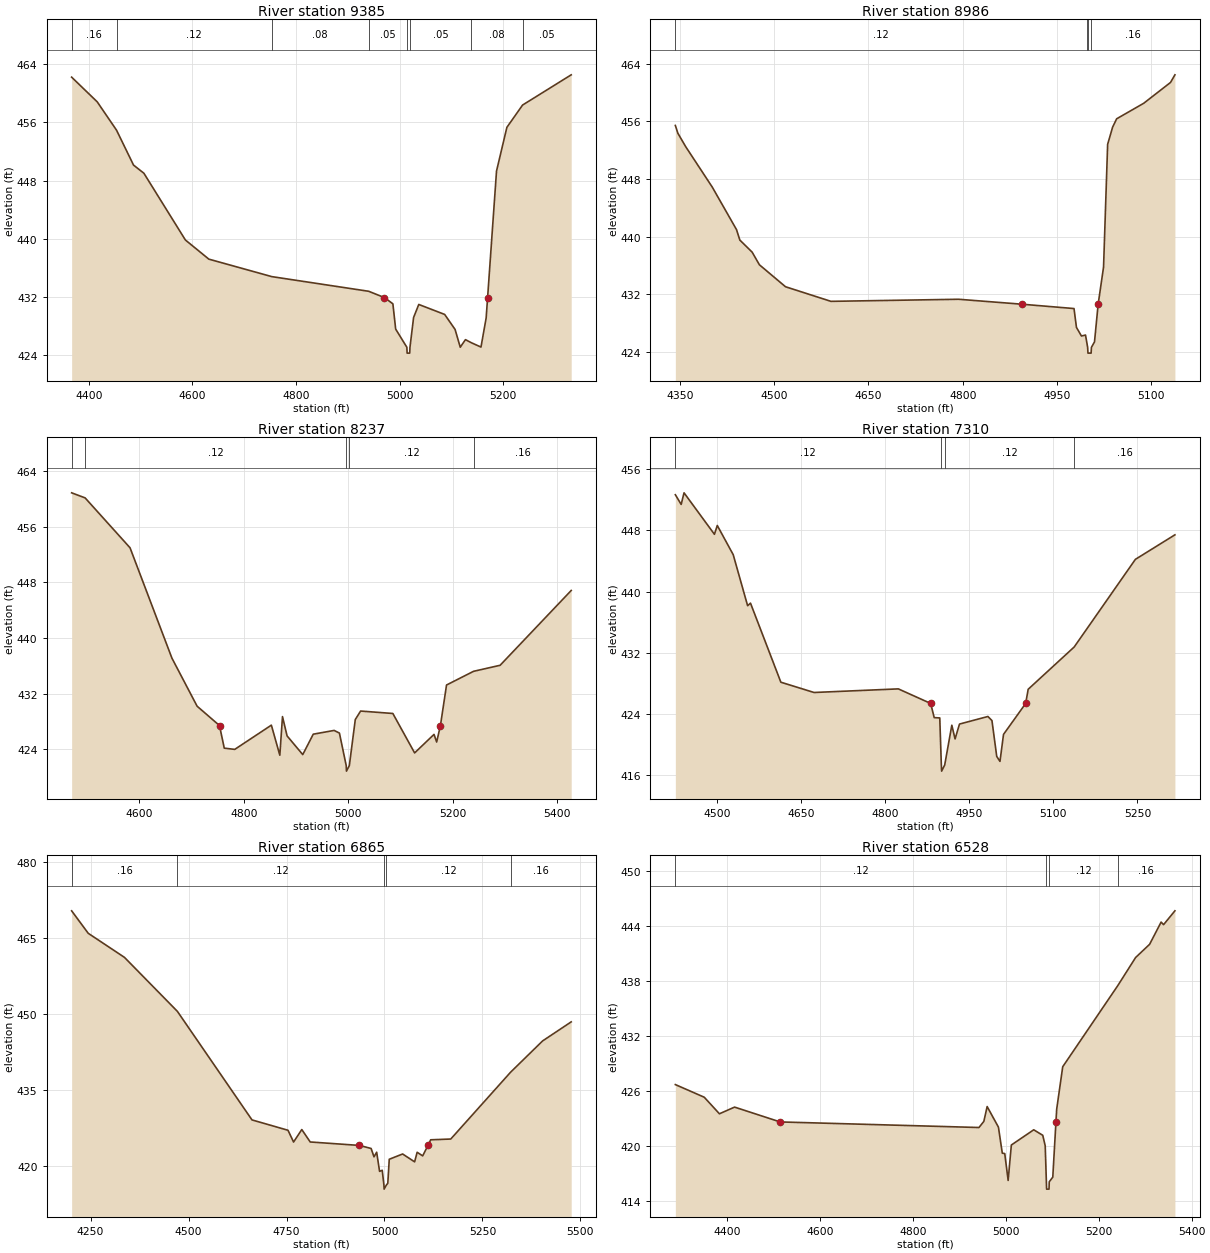
Type RM Length L Ch R = 1,9385,399,399,399
BEGIN DESCRIPTION:
CANE BRANCH 5.0
END DESCRIPTION:
XS GIS Cut Line= 3
      2854444.31      7055435.66      2853819.33      7055469.51
      2853480.81      7055461.70
#Sta/Elev= 30
  4366.9  462.19  4416.3  458.80  4453.6  454.91  4486.4  450.12  4506.4  449.00
  4586.5  439.84  4631.8  437.21  4753.4  434.81  4940.3  432.80  4970.7  431.94
  4987.1  431.08  4992.5  427.61  5014.1  425.11  5014.6  424.31  5019.6  424.31
  5020.1  425.11  5027.1  429.20  5037.1  430.99  5087.1  429.62  5107.2  427.56
  5117.2  425.12  5127.2  426.16  5138.5  425.74  5157.2  425.14  5167.2  429.14
  5170.0  431.94  5187.2  449.30  5207.2  455.30  5237.5  458.36  5331.4  462.51
#Mann=8,-1,0
  4366.9    0.16       0  4453.6    0.12       0  4753.4    0.08       0
  4940.3    0.05       0  5014.1    0.04       0  5020.1    0.05       0
  5138.5    0.08       0  5237.5    0.05       0
Bank Sta=4970.7,5170
Exp/Cntr=0.3,0.1

Type RM Length L Ch R = 1,8986,749,749,749
BEGIN DESCRIPTION:
CANE BRANCH 4.0
END DESCRIPTION:
XS GIS Cut Line= 3
      2854160.46      7055107.54      2853561.52      7055315.87
      2853460.33      7055440.41
#Sta/Elev= 30
  4342.8  455.45  4346.8  454.37  4359.2  452.51  4401.5  446.89  4440.1  440.98
  4445.4  439.53  4465.0  437.85  4476.5  436.10  4518.0  433.05  4590.3  431.02
  4793.3  431.31  4894.6  430.62  4976.9  430.02  4980.8  427.40  4988.7  426.21
  4995.2  426.34  4997.7  425.08  4998.6  424.63  4999.1  423.83  5004.1  423.83
  5004.6  424.63  5009.5  425.39  5015.3  430.62  5023.9  435.78  5030.4  452.83
  5038.3  455.21  5044.7  456.37  5087.8  458.53  5130.4  461.42  5137.4  462.48
#Mann=4,-1,0
  4342.8    0.12       0  4997.7    0.16       0  4998.6    0.07       0
  5004.6    0.16       0
Bank Sta=4894.6,5015.3
Exp/Cntr=0.3,0.1

Type RM Length L Ch R = 1,8237,927,927,927
BEGIN DESCRIPTION:
CANE BRANCH 3.0
END DESCRIPTION:
XS GIS Cut Line= 3
      2854126.61      7054995.55      2853597.98      7054961.70
      2853182.74      7055060.32
#Sta/Elev= 30
  4470.2  460.90  4496.0  460.17  4582.0  452.99  4662.2  437.10  4710.4  430.18
  4753.3  427.39  4762.4  424.14  4782.5  423.96  4852.6  427.45  4868.8  423.12
  4873.9  428.68  4882.7  425.90  4912.7  423.21  4932.8  426.15  4972.8  426.69
  4982.9  426.31  4995.9  421.63  4996.4  420.83  5001.9  421.63  5013.3  428.26
  5023.5  429.48  5085.2  429.13  5126.9  423.45  5164.0  426.12  5169.1  425.02
  5176.3  427.39  5188.0  433.23  5239.7  435.20  5290.6  436.07  5426.7  446.84
#Mann=5,-1,0
  4470.2    0.16       0  4496.0    0.12       0  4995.9    0.07       0
  5001.9    0.12       0  5239.7    0.16       0
Bank Sta=4753.3,5176.3
Exp/Cntr=0.3,0.1

Type RM Length L Ch R = 1,7310,445,445,445
BEGIN DESCRIPTION:
Mapping XS b9cf460b
END DESCRIPTION:
XS GIS Cut Line= 4
      2853876.61      7054607.54      2853433.91      7054685.66
      2853363.60      7054805.45      2853158.92      7055028.27
#Sta/Elev= 30
  4425.8  452.63  4436.2  451.37  4441.3  452.88  4495.5  447.47  4500.6  448.62
  4529.0  444.81  4554.7  438.15  4559.8  438.49  4614.0  428.17  4673.2  426.83
  4823.5  427.30  4881.2  425.40  4887.5  423.55  4897.4  423.51  4900.2  417.37
  4900.7  416.57  4906.2  417.37  4918.9  422.56  4924.7  420.77  4932.6  422.71
  4983.3  423.70  4990.5  423.16  4999.0  418.49  5004.8  417.84  5011.1  421.36
  5050.6  425.40  5055.1  427.25  5137.2  432.77  5246.3  444.20  5316.8  447.40
#Mann=4,-1,0
  4425.8    0.12       0  4900.2    0.07       0  4906.2    0.12       0
  5137.2    0.16       0
Bank Sta=4881.2,5050.6
Exp/Cntr=0.3,0.1

Type RM Length L Ch R = 1,6865,337,337,337
BEGIN DESCRIPTION:
CANE BRANCH 2.0
END DESCRIPTION:
XS GIS Cut Line= 3
      2853775.02      7053974.98      2853225.00      7054575.00
      2853124.99      7055025.05
#Sta/Elev= 30
  4201.6  470.38  4243.9  465.95  4336.4  461.20  4471.5  450.55  4661.9  429.14
  4753.8  427.10  4768.0  424.78  4789.0  427.24  4810.5  424.79  4936.1  424.11
  4965.9  423.51  4973.3  421.86  4980.1  422.77  4987.5  418.99  4994.3  419.21
  4998.6  416.29  4999.1  415.49  5004.8  416.29  5008.5  416.64  5012.2  421.38
  5046.3  422.42  5077.0  420.87  5083.4  422.76  5097.5  422.05  5111.1  424.11
  5118.0  425.22  5169.2  425.37  5322.0  438.56  5403.6  444.72  5476.6  448.48
#Mann=5,-1,0
  4201.6    0.16       0  4471.5    0.12       0  4998.6    0.07       0
  5004.8    0.12       0  5322.0    0.16       0
Bank Sta=4936.1,5111.1
Exp/Cntr=0.3,0.1

Type RM Length L Ch R = 1,6528,247,247,247
BEGIN DESCRIPTION:
Mapping XS fc28ac13
END DESCRIPTION:
XS GIS Cut Line= 3
      2853188.26      7053950.39      2852974.71      7054643.12
      2853099.49      7054970.66
#Sta/Elev= 30
  4288.6  426.69  4350.8  425.31  4383.5  423.50  4416.1  424.23  4514.2  422.61
  4942.2  422.00  4952.7  422.67  4959.8  424.29  4984.1  422.04  4992.4  419.20
  4997.7  419.15  5005.0  416.22  5011.9  420.09  5060.1  421.75  5079.5  421.15
  5084.8  420.00  5087.3  416.07  5087.8  415.27  5093.0  415.27  5093.5  416.07
  5101.1  416.58  5107.9  422.61  5109.5  424.00  5122.5  428.64  5240.9  437.49
  5279.4  440.57  5309.5  442.01  5334.3  444.44  5339.6  444.16  5364.0  445.67
#Mann=4,-1,0
  4288.6    0.12       0  5087.3    0.07       0  5093.5    0.12       0
  5240.9    0.16       0
Bank Sta=4514.2,5107.9
Exp/Cntr=0.3,0.1

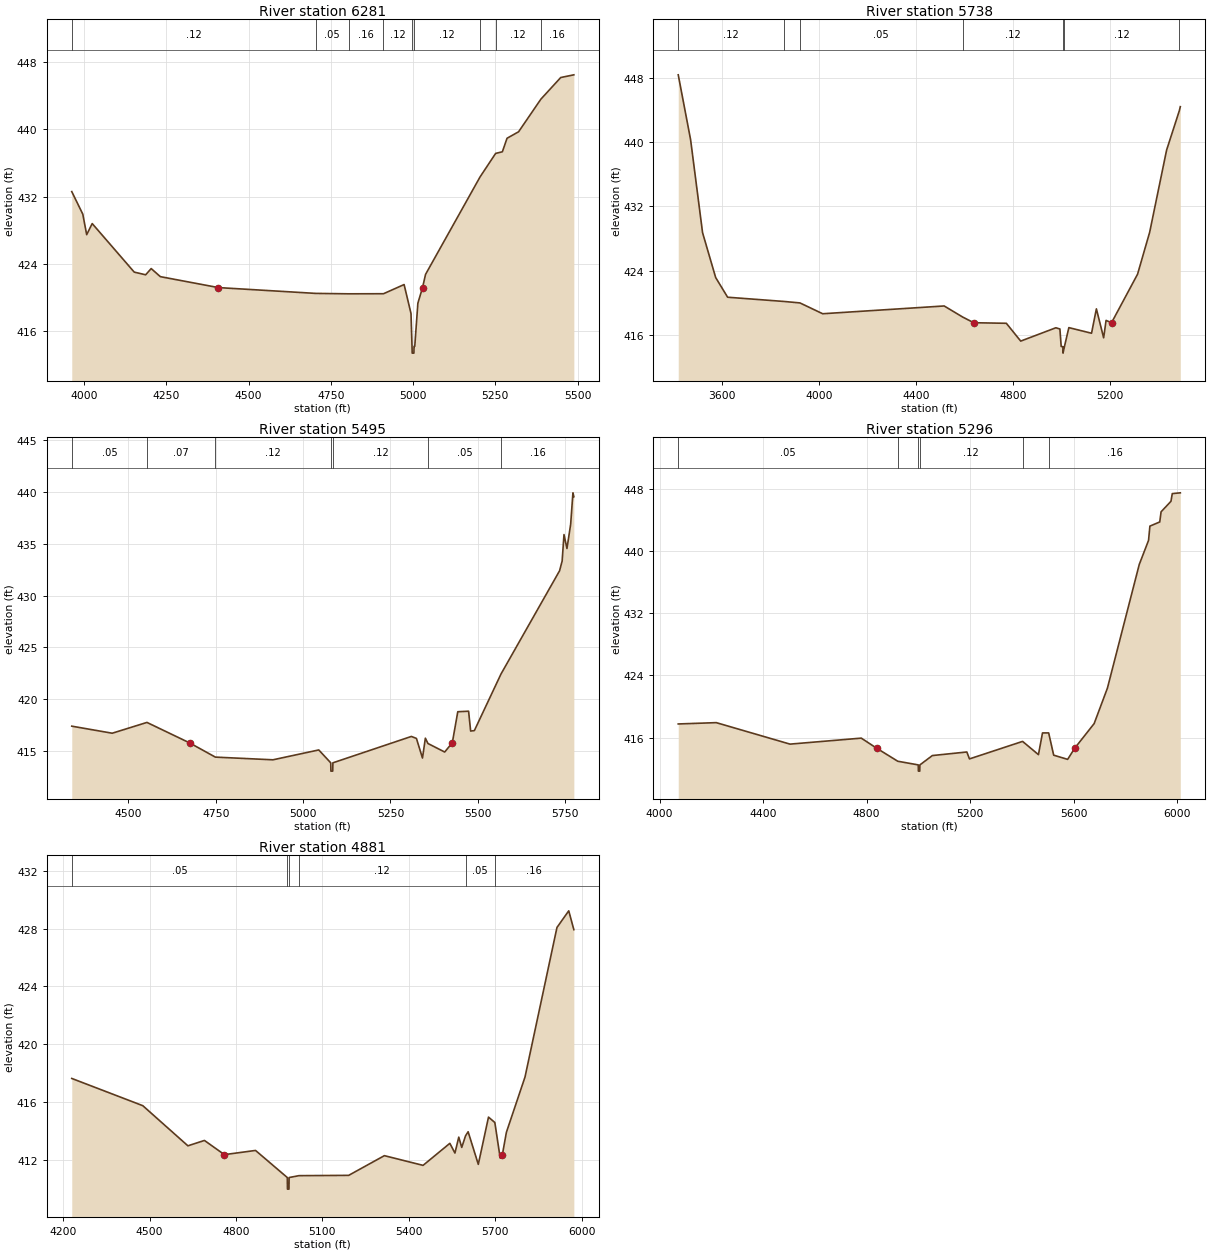
Type RM Length L Ch R = 1,6281,543,543,543
BEGIN DESCRIPTION:
Mapping XS 93d1a8de
END DESCRIPTION:
XS GIS Cut Line= 4
      2853137.97      7053695.04      2852732.15      7054511.01
      2852776.80      7054653.54      2853084.06      7055002.46
#Sta/Elev= 30
  3962.9  432.60  3996.4  429.92  4008.2  427.48  4025.0  428.80  4152.7  423.03
  4187.4  422.71  4204.2  423.45  4232.1  422.49  4408.4  421.19  4703.8  420.50
  4803.8  420.45  4910.1  420.46  4972.7  421.55  4993.7  418.11  4996.8  414.20
  4997.3  413.40  5002.5  413.40  5003.0  414.20  5005.1  414.21  5014.6  419.34
  5028.8  421.19  5037.9  422.76  5203.6  434.35  5250.9  437.14  5271.3  437.33
  5285.5  438.94  5320.6  439.71  5388.4  443.59  5448.7  446.16  5488.5  446.48
#Mann=9,-1,0
  3962.9    0.12       0  4703.8    0.05       0  4803.8    0.16       0
  4910.1    0.12       0  4996.8    0.07       0  5003.0    0.12       0
  5203.6    0.16       0  5250.9    0.12       0  5388.4    0.16       0
Bank Sta=4408.4,5028.8
Exp/Cntr=0.3,0.1

Type RM Length L Ch R = 1,5738,243,243,243
BEGIN DESCRIPTION:
Mapping XS 9aefbdd2
END DESCRIPTION:
XS GIS Cut Line= 4
      2853055.50      7053587.18      2852470.45      7054665.39
      2852620.60      7055042.92      2853061.60      7055033.78
#Sta/Elev= 30
  3418.2  448.41  3469.3  440.32  3518.7  428.73  3572.9  423.13  3622.3  420.68
  3856.2  420.15  3921.0  419.97  4014.9  418.62  4516.8  419.59  4592.6  418.22
  4639.0  417.50  4773.6  417.43  4833.0  415.21  4978.1  416.87  4994.9  416.72
  5000.2  414.54  5007.3  414.51  5007.8  413.71  5013.5  414.51  5031.9  416.89
  5125.6  416.19  5145.6  419.23  5175.6  415.62  5185.6  417.79  5208.2  417.50
  5315.7  423.55  5365.7  428.78  5435.7  439.03  5488.4  443.95  5492.3  444.44
#Mann=7,-1,0
  3418.2    0.12       0  3856.2    0.16       0  3921.0    0.05       0
  4592.6    0.12       0  5007.3    0.07       0  5013.5    0.12       0
  5488.4    0.16       0
Bank Sta=4639,5208.2
Exp/Cntr=0.3,0.1

Type RM Length L Ch R = 1,5495,199,199,199
BEGIN DESCRIPTION:
Mapping XS c0095c05
END DESCRIPTION:
XS GIS Cut Line= 3
      2852370.55      7054419.21      2852380.96      7055106.67
      2852630.47      7055813.59
#Sta/Elev= 30
  4337.9  417.42  4453.7  416.74  4553.1  417.78  4675.2  415.81  4748.9  414.44
  4913.8  414.18  5044.9  415.13  5079.2  413.89  5079.7  413.09  5084.9  413.09
  5085.4  413.89  5310.0  416.43  5324.5  416.24  5341.8  414.35  5350.1  416.26
  5357.5  415.75  5405.4  414.93  5427.2  415.82  5442.9  418.81  5473.8  418.86
  5479.7  416.95  5490.3  416.99  5566.7  422.45  5734.2  432.38  5741.6  433.32
  5746.9  435.87  5755.4  434.53  5766.0  436.86  5772.5  439.89  5775.1  439.52
#Mann=7,-1,0
  4337.9    0.05       0  4553.1    0.07       0  4748.9    0.12       0
  5079.2    0.07       0  5085.4    0.12       0  5357.5    0.05       0
  5566.7    0.16       0
Bank Sta=4675.2,5427.2
Exp/Cntr=0.3,0.1

Type RM Length L Ch R = 1,5296,415,415,415
BEGIN DESCRIPTION:
Mapping XS 61e71c10
END DESCRIPTION:
XS GIS Cut Line= 4
      2852475.53      7054169.47      2852294.98      7054391.69
      2852190.81      7054961.13      2852426.93      7056009.77
#Sta/Elev= 30
  4071.9  417.76  4218.8  417.93  4503.9  415.17  4779.2  415.94  4838.4  414.65
  4920.2  412.97  4999.4  412.50  4999.9  411.70  5005.2  411.70  5005.7  412.50
  5053.8  413.70  5187.1  414.16  5197.3  413.27  5402.5  415.52  5463.8  413.82
  5479.5  416.61  5503.3  416.61  5522.7  413.75  5576.6  413.21  5604.1  414.65
  5679.1  417.81  5730.4  422.37  5853.4  438.26  5889.3  441.35  5894.5  443.18
  5932.6  443.72  5937.7  445.02  5975.9  446.37  5981.0  447.36  6012.0  447.46
#Mann=6,-1,0
  4071.9    0.05       0  4920.2    0.12       0  4999.4    0.07       0
  5005.7    0.12       0  5402.5    0.05       0  5503.3    0.16       0
Bank Sta=4838.4,5604.1
Exp/Cntr=0.3,0.1

Type RM Length L Ch R = 1,4881,0,0,0
BEGIN DESCRIPTION:
CANE BRANCH 1.0
END DESCRIPTION:
XS GIS Cut Line= 3
      2852334.10      7054236.86      2851834.09      7054851.46
      2852073.24      7055771.69
#Sta/Elev= 30
  4230.0  417.65  4476.6  415.77  4633.2  413.00  4690.6  413.37  4760.0  412.39
  4868.0  412.68  4978.3  410.81  4978.8  410.01  4984.1  410.01  4984.6  410.81
  5018.9  410.94  5191.3  410.96  5315.3  412.32  5449.6  411.65  5542.6  413.17
  5560.3  412.50  5573.6  413.60  5583.9  412.89  5597.1  413.69  5606.1  413.97
  5641.4  411.72  5676.8  414.98  5698.8  414.61  5717.4  412.16  5725.0  412.39
  5738.9  413.93  5803.6  417.75  5914.5  428.07  5955.4  429.22  5973.1  427.92
#Mann=6,-1,0
  4230.0    0.05       0  4978.3    0.03       0  4984.6    0.05       0
  5018.9    0.12       0  5597.1    0.05       0  5698.8    0.16       0
Bank Sta=4760,5725
Exp/Cntr=0.3,0.1

Chan Stop Cuts=-1