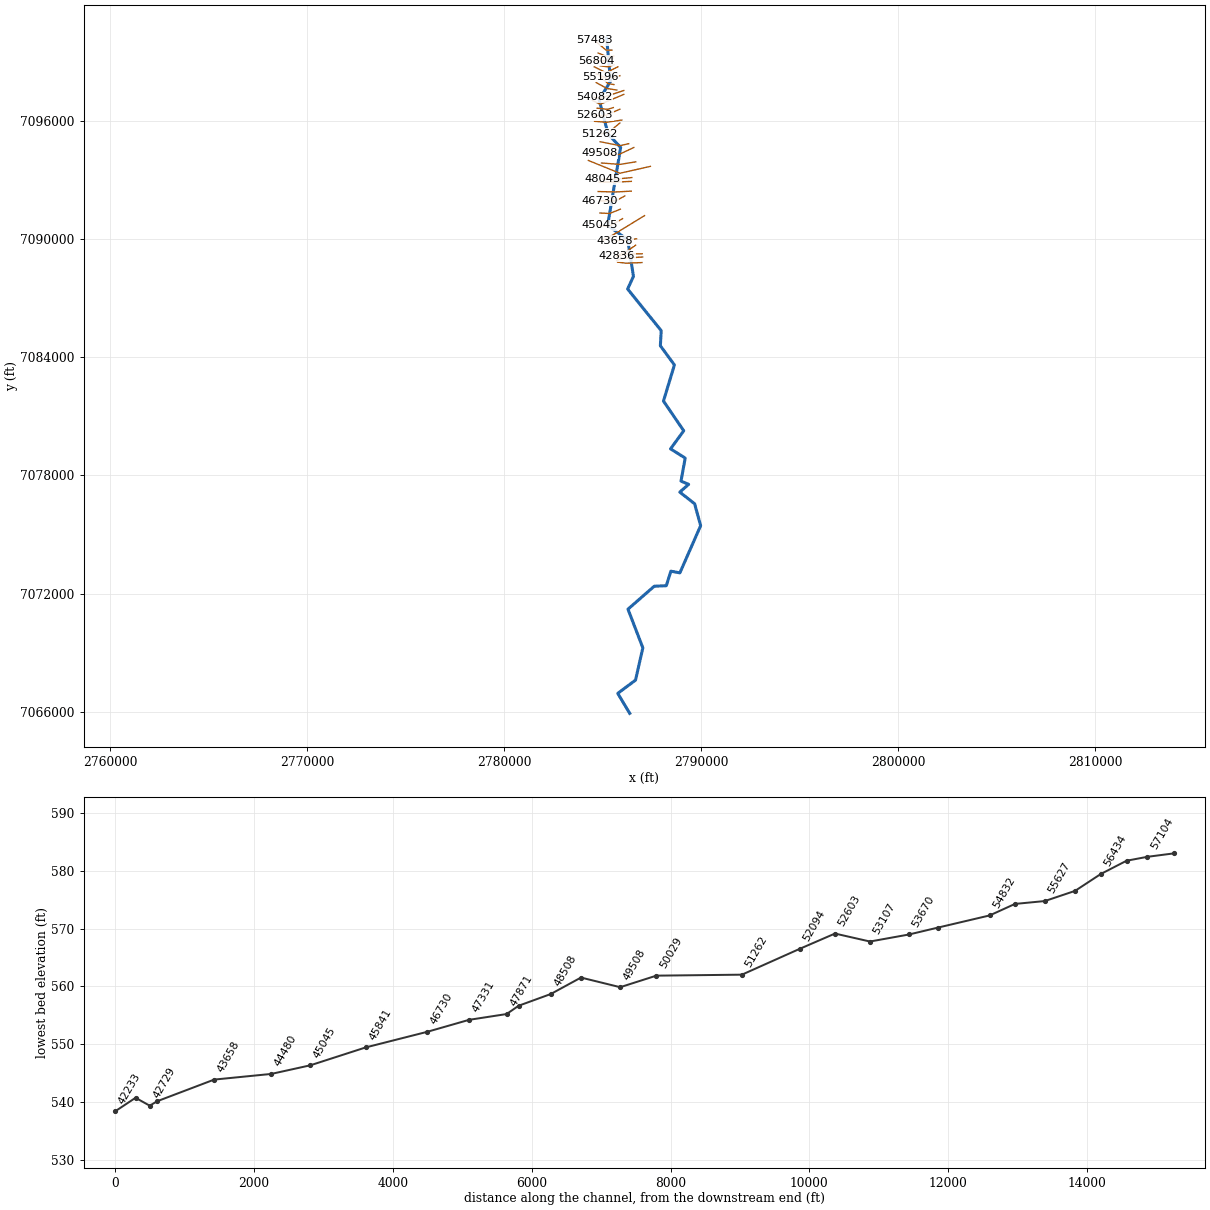
--- CEDAR CREEK.prj (project) ---

Proj Title=CEDAR CREEK Base Level Engineering
Current Plan=p01
Default Exp/Contr=0.3,0.1
English Units
Geom File=g01
Flow File=f01
Plan File=p01
BEGIN DESCRIPTION:
CEDAR CREEK
END DESCRIPTION:

--- CEDAR CREEK.p01 (plan) ---

Plan Title=Multiple Run
Short Identifier=Multiple
Geom File=g01
Flow File=f01
Subcritical Flow
K Sum by GR= 0
Std Step Tol= 0.01
Critical Tol= 0.01
Num of Std Step Trials= 20
Max Error Tol= 0.3
Flow Tol Ratio= 0.001
Split Flow NTrial= 30
Split Flow Tol= 0.02
Split Flow Ratio= 0.02
Log Output Level= 0
Friction Slope Method= 1
Unsteady Friction Slope Method= 2
Unsteady Bridges Friction Slope Method= 1
Parabolic Critical Depth
Global Vel Dist=  1 , 1 , 1
Global Log Level= 0
CheckData=True
Encroach Param= -1, 0, 0, 0
BEGIN DESCRIPTION:
Multiple Run
END DESCRIPTION:

--- CEDAR CREEK.f01 (steady flow) ---

Flow Title=Multiple
Number of Profiles=7
Profile Names=10-year,25-year,50-year,1pct_min,100-year,1pct_plu,500-year
River Rch & RM= CEDAR CREEK,Reach-1,57483
     459     597     704     412     823    1642    1121
River Rch & RM= CEDAR CREEK,Reach-1,56804
     860    1155    1394     833    1662    3316    2358
River Rch & RM= CEDAR CREEK,Reach-1,48045
    1398    1926    2362    1432    2858    5702    4178
River Rch & RM= CEDAR CREEK,Reach-1,37587
    1666    2308    2841    1728    3447    6877    5068
River Rch & RM= CEDAR CREEK,Reach-1,28821
    1704    2358    2902    1764    3519    7021    5168
River Rch & RM= CEDAR CREEK,Reach-1,25505
    1933    2692    3327    2029    4048    8077    5989
River Rch & RM= CEDAR CREEK,Reach-1,16642
    2008    2797    3456    2108    4205    8390    6220
River Rch & RM= CEDAR CREEK,Reach-1,11716
    2444    3435    4270    2617    5222   10420    7808
River Rch & RM= CEDAR CREEK,Reach-1,10003
    2638    3719    4632    2845    5676   11325    8517
Boundary for River Rch & Prof#=CEDAR CREEK,Reach-1,1
Up Type=0
Dn Type=3
Dn Slope=0.005
Boundary for River Rch & Prof#=CEDAR CREEK,Reach-1,2
Up Type=0
Dn Type=3
Dn Slope=0.005
Boundary for River Rch & Prof#=CEDAR CREEK,Reach-1,3
Up Type=0
Dn Type=3
Dn Slope=0.005
Boundary for River Rch & Prof#=CEDAR CREEK,Reach-1,4
Up Type=0
Dn Type=3
Dn Slope=0.005
Boundary for River Rch & Prof#=CEDAR CREEK,Reach-1,5
Up Type=0
Dn Type=3
Dn Slope=0.005
Boundary for River Rch & Prof#=CEDAR CREEK,Reach-1,6
Up Type=0
Dn Type=3
Dn Slope=0.005
Boundary for River Rch & Prof#=CEDAR CREEK,Reach-1,7
Up Type=0
Dn Type=3
Dn Slope=0.005

--- CEDAR CREEK.g01 (geometry) ---

Geom Title=Existing Conditions

River Reach=CEDAR CREEK,Reach-1
Reach XY= 30
      2785205.59      7100170.71      2785404.27      7097996.89
      2784822.01      7097060.74      2785279.50      7095313.05
      2785915.56      7094635.71      2785257.96      7090686.45
      2786270.37      7089943.33      2786565.04      7088095.51
      2786268.82      7087451.87      2787972.96      7085339.62
      2787930.24      7084572.39      2788643.17      7083599.35
      2788087.77      7081766.69      2789115.74      7080258.70
      2788446.34      7079341.58      2789189.40      7078875.31
      2788978.10      7077705.18      2789365.46      7077541.29
      2788915.71      7077148.34      2789669.96      7076553.33
      2789973.51      7075443.38      2788921.30      7073050.29
      2788463.17      7073135.03      2788231.31      7072397.54
      2787621.40      7072372.40      2786287.04      7071207.52
      2787041.40      7069245.81      2786669.69      7067608.36
      2785768.31      7066934.87      2786375.59      7065920.71

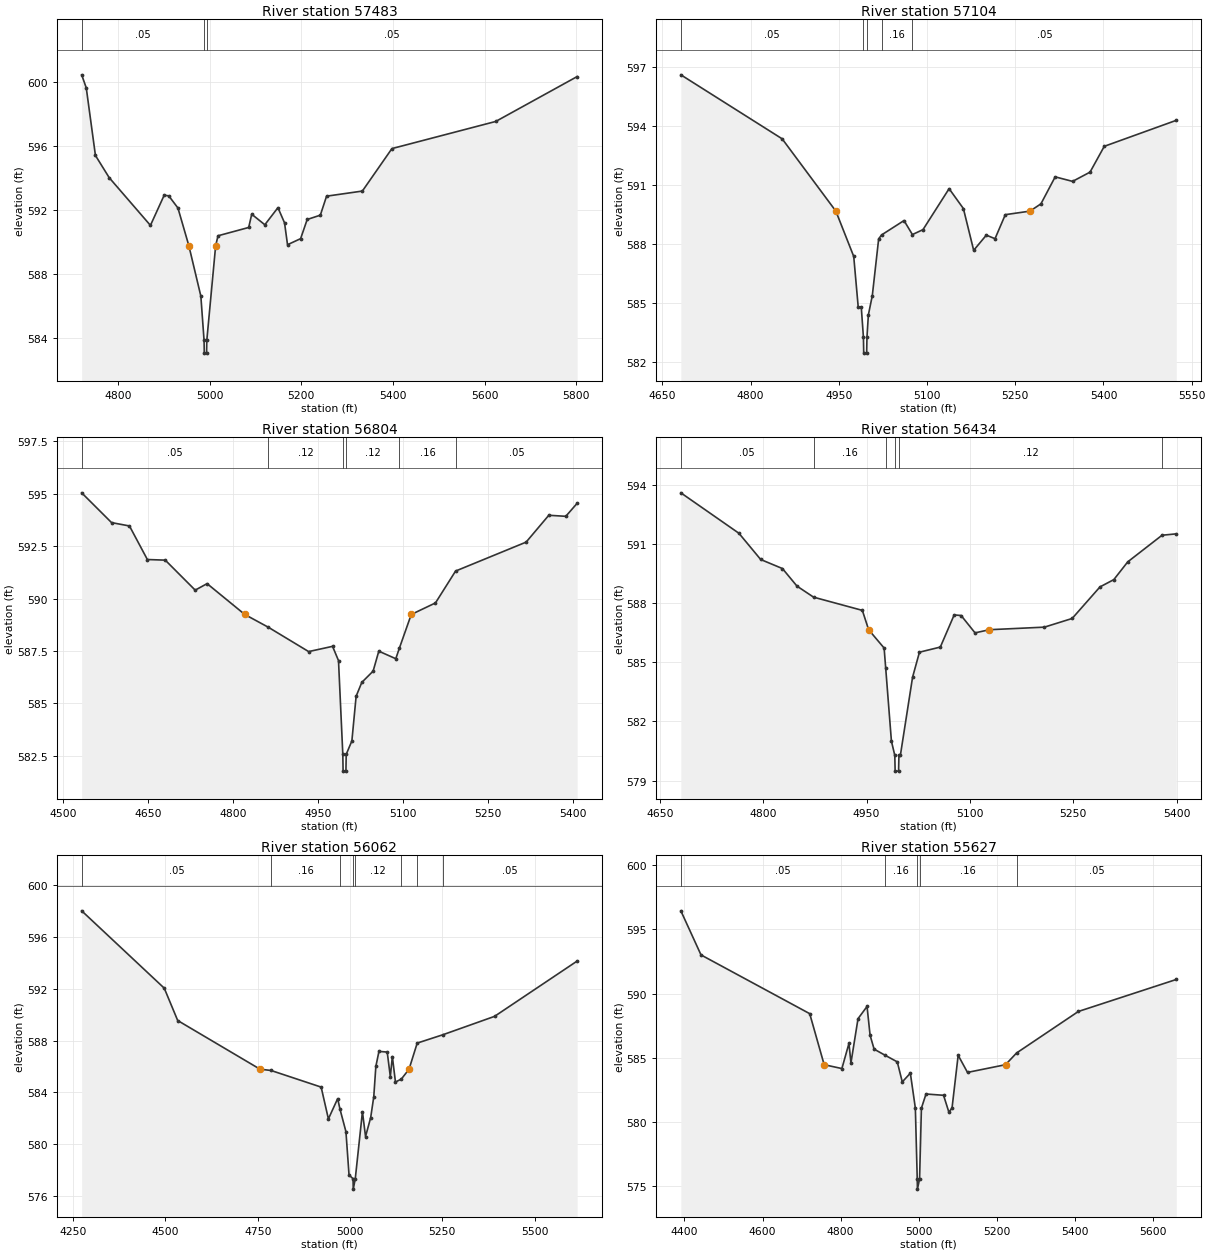
Type RM Length L Ch R = 1,57483,379,379,379
BEGIN DESCRIPTION:
CEDAR CREEK 71.0
END DESCRIPTION:
XS GIS Cut Line= 3
      2785475.01      7099575.00      2785175.00      7099575.00
      2784575.03      7100074.98
#Sta/Elev= 30
  4721.0  600.47  4731.0  599.65  4751.0  595.42  4781.0  594.03  4871.0  591.04
  4901.0  592.93  4911.0  592.89  4931.0  592.13  4954.8  589.77  4981.0  586.61
  4988.0  583.84  4988.5  583.04  4993.5  583.04  4994.0  583.84  5013.3  589.77
  5018.5  590.39  5085.4  590.91  5092.0  591.74  5120.6  591.08  5149.2  592.15
  5163.6  591.20  5170.1  589.83  5198.7  590.21  5213.0  591.41  5241.7  591.68
  5255.3  592.87  5333.4  593.19  5397.9  595.85  5624.4  597.55  5802.0  600.36
#Mann=3,-1,0
  4721.0    0.05       0  4988.0    0.03       0  4994.0    0.05       0
Bank Sta=4954.8,5013.3
Exp/Cntr=0.3,0.1

Type RM Length L Ch R = 1,57104,300,300,300
BEGIN DESCRIPTION:
CEDAR CREEK 70.0
END DESCRIPTION:
XS GIS Cut Line= 3
      2785574.96      7099274.99      2785275.00      7099225.00
      2784775.01      7099425.00
#Sta/Elev= 30
  4681.3  596.58  4853.6  593.33  4944.9  589.66  4975.3  587.36  4982.9  584.80
  4988.1  584.80  4991.8  583.25  4992.3  582.45  4997.3  582.45  4997.8  583.25
  5000.2  584.39  5006.9  585.37  5017.7  588.25  5022.6  588.45  5060.8  589.18
  5075.1  588.47  5093.1  588.72  5137.5  590.80  5161.8  589.79  5179.3  587.67
  5200.8  588.44  5215.6  588.26  5233.1  589.48  5275.1  589.66  5293.7  590.03
  5317.9  591.40  5347.5  591.17  5377.2  591.64  5401.4  592.95  5523.9  594.27
#Mann=5,-1,0
  4681.3    0.05       0  4991.8    0.03       0  4997.8    0.05       0
  5022.6    0.16       0  5075.1    0.05       0
Bank Sta=4944.9,5275.1
Exp/Cntr=0.3,0.1

Type RM Length L Ch R = 1,56804,370,370,370
BEGIN DESCRIPTION:
CEDAR CREEK 69.0
END DESCRIPTION:
XS GIS Cut Line= 3
      2785524.98      7099174.99      2785075.00      7099025.00
      2784675.02      7099025.00
#Sta/Elev= 30
  4533.1  595.04  4585.8  593.62  4617.4  593.46  4649.0  591.86  4680.6  591.83
  4733.4  590.40  4754.4  590.71  4820.9  589.24  4862.5  588.63  4933.6  587.47
  4975.8  587.72  4986.3  587.04  4993.9  582.57  4994.4  581.77  4999.4  581.77
  4999.9  582.57  5009.9  583.21  5017.4  585.34  5027.4  586.00  5047.4  586.54
  5057.4  587.49  5087.4  587.13  5093.8  587.64  5114.7  589.24  5157.4  589.79
  5192.9  591.31  5317.4  592.69  5357.4  593.97  5387.4  593.92  5407.4  594.54
#Mann=6,-1,0
  4533.1    0.05       0  4862.5    0.12       0  4993.9    0.07       0
  4999.9    0.12       0  5093.8    0.16       0  5192.9    0.05       0
Bank Sta=4820.9,5114.7
Exp/Cntr=0.3,0.1

Type RM Length L Ch R = 1,56434,372,372,372
BEGIN DESCRIPTION:
CEDAR CREEK 68.0
END DESCRIPTION:
XS GIS Cut Line= 3
      2785574.97      7098824.99      2785275.00      7098725.00
      2784875.01      7098775.00
#Sta/Elev= 30
  4680.3  593.59  4764.6  591.54  4796.2  590.21  4827.8  589.75  4848.9  588.86
  4873.0  588.30  4943.8  587.63  4952.9  586.65  4975.4  585.72  4977.7  584.70
  4986.0  581.00  4990.9  580.28  4991.4  579.48  4996.4  579.48  4996.9  580.28
  4999.0  580.28  5016.7  584.24  5026.7  585.51  5057.0  585.77  5077.1  587.40
  5087.2  587.37  5107.4  586.49  5128.3  586.65  5208.1  586.78  5248.4  587.22
  5288.8  588.82  5308.9  589.19  5329.1  590.09  5378.9  591.44  5399.6  591.51
#Mann=6,-1,0
  4680.3    0.05       0  4873.0    0.16       0  4977.7    0.12       0
  4990.9    0.07       0  4996.9    0.12       0  5378.9    0.05       0
Bank Sta=4952.9,5128.3
Exp/Cntr=0.3,0.1

Type RM Length L Ch R = 1,56062,435,435,435
BEGIN DESCRIPTION:
CEDAR CREEK 67.0
END DESCRIPTION:
XS GIS Cut Line= 3
      2785775.02      7098725.01      2785175.00      7098425.00
      2784574.97      7098725.02
#Sta/Elev= 30
  4273.3  597.99  4496.9  592.03  4533.3  589.54  4756.2  585.79  4786.2  585.69
  4921.8  584.41  4941.4  581.96  4966.5  583.52  4973.0  582.69  4988.9  580.98
  4997.3  577.64  5008.2  577.35  5008.7  576.55  5014.2  577.35  5033.6  582.51
  5042.0  580.60  5055.9  582.06  5064.3  583.67  5069.9  586.00  5078.3  587.16
  5100.7  587.11  5109.1  585.22  5114.6  586.76  5123.0  584.80  5139.0  585.03
  5159.8  585.79  5181.9  587.80  5251.1  588.44  5391.4  589.86  5615.0  594.12
#Mann=8,-1,0
  4273.3    0.05       0  4786.2    0.16       0  4973.0    0.12       0
  5008.2    0.07       0  5014.2    0.12       0  5139.0    0.16       0
  5181.9    0.12       0  5251.1    0.05       0
Bank Sta=4756.2,5159.8
Exp/Cntr=0.3,0.1

Type RM Length L Ch R = 1,55627,431,431,431
BEGIN DESCRIPTION:
CEDAR CREEK 66.0
END DESCRIPTION:
XS GIS Cut Line= 3
      2785875.01      7098275.00      2785275.00      7098125.00
      2784674.98      7098375.01
#Sta/Elev= 30
  4390.8  596.44  4442.4  593.01  4720.7  588.44  4757.7  584.47  4803.1  584.17
  4821.2  586.13  4826.3  584.61  4844.4  588.05  4867.5  589.00  4875.3  586.76
  4885.6  585.68  4912.8  585.22  4944.9  584.69  4957.7  583.13  4978.4  583.81
  4991.2  581.09  4996.0  575.59  4996.5  574.79  5002.0  575.59  5006.7  581.09
  5018.5  582.19  5063.4  582.09  5077.0  580.78  5085.1  581.10  5100.8  585.20
  5124.7  583.87  5222.1  584.47  5250.3  585.38  5408.5  588.61  5659.3  591.10
#Mann=5,-1,0
  4390.8    0.05       0  4912.8    0.16       0  4996.0    0.07       0
  5002.0    0.16       0  5250.3    0.05       0
Bank Sta=4757.7,5222.1
Exp/Cntr=0.3,0.1

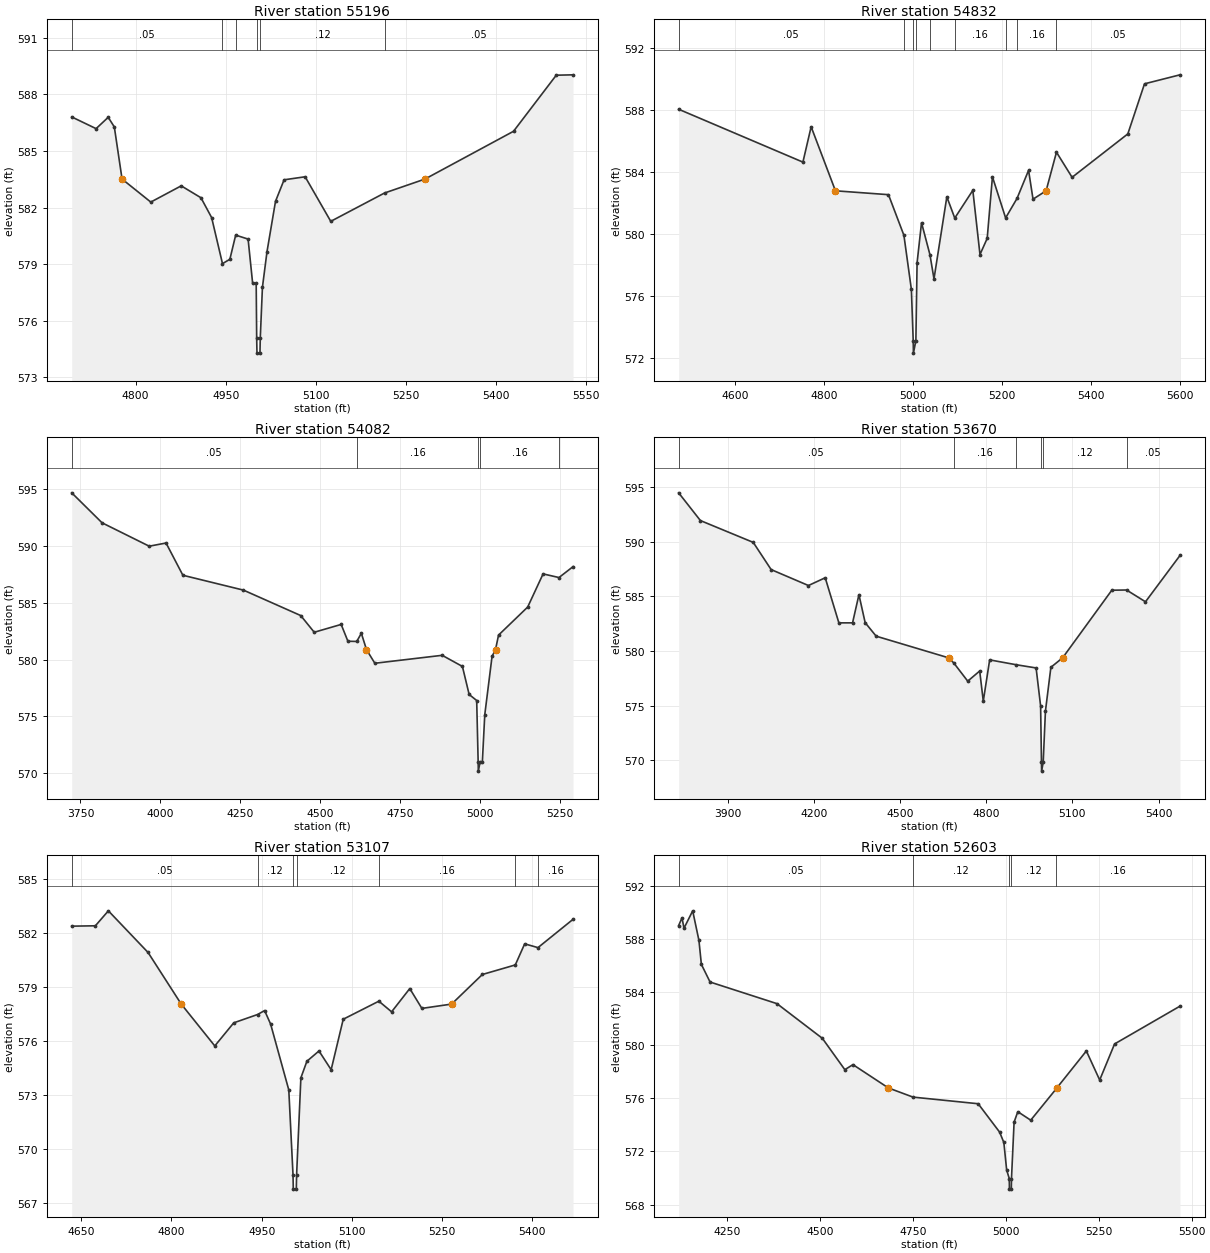
Type RM Length L Ch R = 1,55196,364,364,364
BEGIN DESCRIPTION:
CEDAR CREEK 65.0
END DESCRIPTION:
XS GIS Cut Line= 3
      2785575.02      7097825.00      2785275.00      7097875.00
      2784874.97      7098225.02
#Sta/Elev= 30
  4693.4  586.80  4734.0  586.18  4754.2  586.78  4764.4  586.27  4777.3  583.51
  4825.2  582.29  4875.9  583.15  4908.8  582.52  4926.6  581.47  4944.7  579.03
  4957.0  579.26  4966.7  580.54  4987.4  580.33  4995.0  577.98  5000.9  577.98
  5001.7  575.09  5002.2  574.29  5007.2  574.29  5007.7  575.09  5011.3  577.78
  5018.9  579.66  5033.1  582.33  5047.4  583.47  5082.5  583.63  5125.2  581.27
  5214.8  582.77  5282.3  583.51  5429.9  586.04  5501.1  589.01  5529.1  589.03
#Mann=6,-1,0
  4693.4    0.05       0  4944.7    0.16       0  4966.7    0.12       0
  5001.7    0.07       0  5007.7    0.12       0  5214.8    0.05       0
Bank Sta=4777.3,5282.3
Exp/Cntr=0.3,0.1

Type RM Length L Ch R = 1,54832,750,750,750
BEGIN DESCRIPTION:
CEDAR CREEK 64.0
END DESCRIPTION:
XS GIS Cut Line= 3
      2785719.17      7097546.93      2785225.00      7097625.00
      2784674.99      7097925.00
#Sta/Elev= 30
  4473.9  588.03  4753.2  584.62  4771.7  586.90  4826.3  582.77  4945.5  582.52
  4980.2  579.90  4997.0  576.41  5001.1  573.10  5001.6  572.30  5007.1  573.10
  5009.8  578.12  5019.8  580.71  5038.7  578.65  5047.8  577.09  5076.7  582.38
  5094.5  581.01  5135.1  582.80  5151.2  578.66  5167.4  579.70  5179.2  583.67
  5208.8  581.02  5234.5  582.28  5260.4  584.09  5270.4  582.23  5299.8  582.77
  5323.1  585.26  5358.2  583.64  5483.5  586.44  5521.0  589.67  5600.7  590.25
#Mann=9,-1,0
  4473.9    0.05       0  4980.2    0.16       0  5001.1    0.07       0
  5007.1    0.16       0  5038.7    0.12       0  5094.5    0.16       0
  5208.8    0.12       0  5234.5    0.16       0  5323.1    0.05       0
Bank Sta=4826.3,5299.8
Exp/Cntr=0.3,0.1

Type RM Length L Ch R = 1,54082,412,412,412
BEGIN DESCRIPTION:
CEDAR CREEK 63.0
END DESCRIPTION:
XS GIS Cut Line= 3
      2786075.03      7097525.01      2784875.00      7097125.00
      2784574.98      7097175.00
#Sta/Elev= 30
  3722.7  594.69  3817.6  592.05  3965.2  589.99  4017.9  590.27  4070.6  587.43
  4260.3  586.12  4439.5  583.88  4481.7  582.41  4566.0  583.10  4587.1  581.62
  4614.7  581.60  4629.2  582.32  4645.3  580.88  4671.4  579.68  4882.2  580.38
  4945.5  579.40  4966.6  576.93  4990.2  576.40  4994.8  570.98  4995.3  570.18
  5000.8  570.98  5007.9  570.99  5015.5  575.15  5038.3  580.29  5049.1  580.88
  5058.6  582.16  5149.8  584.63  5198.0  587.55  5247.8  587.23  5291.8  588.19
#Mann=5,-1,0
  3722.7    0.05       0  4614.7    0.16       0  4994.8    0.07       0
  5000.8    0.16       0  5247.8    0.05       0
Bank Sta=4645.3,5049.1
Exp/Cntr=0.3,0.1

Type RM Length L Ch R = 1,53670,563,563,563
BEGIN DESCRIPTION:
CEDAR CREEK 62.0
END DESCRIPTION:
XS GIS Cut Line= 3
      2786074.99      7097325.00      2784875.00      7096825.00
      2784475.00      7097025.00
#Sta/Elev= 30
  3727.6  594.49  3803.4  591.95  3987.6  589.95  4049.9  587.46  4179.9  586.00
  4238.4  586.71  4286.0  582.58  4333.7  582.58  4355.9  585.16  4377.6  582.60
  4416.0  581.36  4668.2  579.38  4686.4  578.91  4735.1  577.24  4776.8  578.17
  4789.3  575.41  4811.5  579.19  4905.0  578.74  4973.4  578.45  4989.1  574.97
  4992.1  569.80  4992.6  569.00  4998.1  569.80  5005.9  574.49  5024.9  578.51
  5065.9  579.38  5237.2  585.57  5288.6  585.59  5354.6  584.51  5474.8  588.75
#Mann=6,-1,0
  3727.6    0.05       0  4686.4    0.16       0  4905.0    0.12       0
  4992.1    0.07       0  4998.1    0.12       0  5288.6    0.05       0
Bank Sta=4668.2,5065.9
Exp/Cntr=0.3,0.1

Type RM Length L Ch R = 1,53107,504,504,504
BEGIN DESCRIPTION:
CEDAR CREEK 61.0
END DESCRIPTION:
XS GIS Cut Line= 3
      2785542.66      7096656.24      2785254.80      7096569.49
      2784725.05      7096625.00
#Sta/Elev= 30
  4634.3  582.36  4673.6  582.38  4695.2  583.21  4761.2  580.90  4816.3  578.04
  4872.1  575.72  4903.6  577.00  4943.1  577.46  4954.9  577.68  4964.9  576.93
  4995.1  573.28  5002.1  568.58  5002.6  567.78  5007.6  567.78  5008.1  568.58
  5015.2  573.95  5025.2  574.87  5045.3  575.44  5065.5  574.40  5085.6  577.20
  5144.8  578.20  5166.0  577.61  5196.2  578.90  5216.3  577.80  5265.8  578.04
  5316.8  579.68  5371.6  580.21  5387.2  581.38  5409.3  581.17  5467.6  582.74
#Mann=7,-1,0
  4634.3    0.05       0  4943.1    0.12       0  5002.1    0.07       0
  5008.1    0.12       0  5144.8    0.16       0  5371.6    0.12       0
  5409.3    0.16       0
Bank Sta=4816.3,5265.8
Exp/Cntr=0.3,0.1

Type RM Length L Ch R = 1,52603,509,509,509
BEGIN DESCRIPTION:
CEDAR CREEK 60.0
END DESCRIPTION:
XS GIS Cut Line= 3
      2785875.02      7096575.01      2785075.00      7096225.00
      2784599.30      7096256.94
#Sta/Elev= 30
  4118.7  589.04  4127.7  589.62  4133.1  588.84  4156.5  590.15  4173.3  587.92
  4179.9  586.11  4203.3  584.78  4383.4  583.15  4505.8  580.53  4566.2  578.17
  4588.1  578.55  4683.6  576.79  4749.9  576.10  4925.3  575.60  4983.0  573.46
  4994.4  572.68  5002.0  570.60  5009.0  569.96  5009.5  569.16  5014.5  569.16
  5015.0  569.96  5022.0  574.21  5032.0  575.00  5066.8  574.36  5135.0  576.71
  5136.8  576.78  5216.6  579.58  5252.5  577.39  5292.6  580.11  5468.7  582.96
#Mann=5,-1,0
  4118.7    0.05       0  4749.9    0.12       0  5009.0    0.07       0
  5015.0    0.12       0  5135.0    0.16       0
Bank Sta=4683.6,5136.8
Exp/Cntr=0.3,0.1

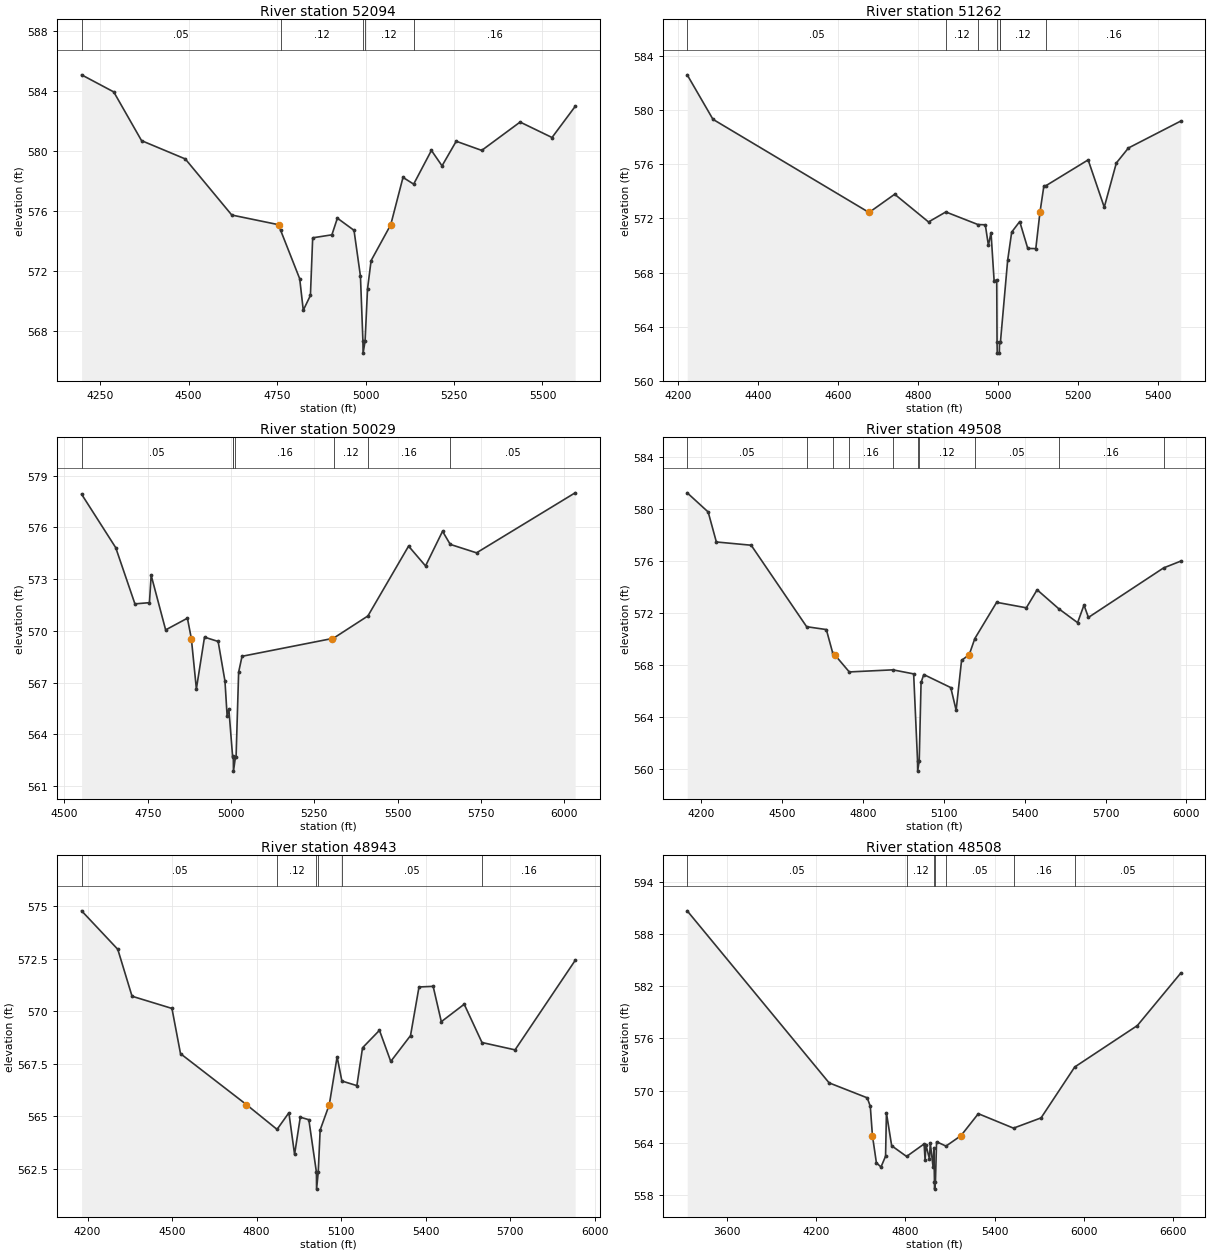
Type RM Length L Ch R = 1,52094,832,832,832
BEGIN DESCRIPTION:
CEDAR CREEK 59.0
END DESCRIPTION:
XS GIS Cut Line= 3
      2785974.99      7096025.00      2785213.14      7095913.24
      2784589.89      7095959.99
#Sta/Elev= 30
  4197.4  585.07  4288.3  583.93  4366.9  580.68  4490.5  579.46  4621.9  575.72
  4755.2  575.07  4760.0  574.70  4813.9  571.47  4824.0  569.37  4844.2  570.36
  4850.6  574.20  4904.9  574.40  4920.4  575.51  4967.4  574.70  4985.6  571.64
  4992.6  567.31  4993.1  566.51  4998.7  567.31  5005.6  570.79  5015.7  572.68
  5071.2  575.07  5105.9  578.23  5136.0  577.78  5186.2  580.03  5216.2  579.00
  5256.3  580.64  5328.4  580.03  5436.9  581.92  5527.1  580.89  5592.4  582.96
#Mann=5,-1,0
  4197.4    0.05       0  4760.0    0.12       0  4992.6    0.07       0
  4998.7    0.12       0  5136.0    0.16       0
Bank Sta=4755.2,5071.2
Exp/Cntr=0.3,0.1

Type RM Length L Ch R = 1,51262,1233,1233,1233
BEGIN DESCRIPTION:
CEDAR CREEK 58.0
END DESCRIPTION:
XS GIS Cut Line= 3
      2785874.97      7095874.97      2785275.00      7095375.00
      2784824.95      7095324.99
#Sta/Elev= 30
  4222.3  582.62  4286.7  579.33  4676.9  572.44  4741.0  573.79  4825.6  571.74
  4868.8  572.48  4949.0  571.55  4967.5  571.53  4975.3  570.01  4981.8  570.95
  4989.6  567.37  4996.1  567.47  4996.9  562.84  4997.4  562.04  5002.6  562.04
  5003.1  562.84  5005.3  562.84  5023.4  568.90  5033.5  570.99  5053.6  571.77
  5073.7  569.78  5093.8  569.77  5104.1  572.44  5114.0  574.41  5119.6  574.43
  5224.6  576.33  5264.9  572.83  5295.1  576.10  5325.3  577.21  5456.1  579.20
#Mann=7,-1,0
  4222.3    0.05       0  4868.8    0.12       0  4949.0    0.16       0
  4996.9    0.07       0  5003.1    0.16       0  5005.3    0.12       0
  5119.6    0.16       0
Bank Sta=4676.9,5104.1
Exp/Cntr=0.3,0.1

Type RM Length L Ch R = 1,50029,521,521,521
BEGIN DESCRIPTION:
CEDAR CREEK 57.0
END DESCRIPTION:
XS GIS Cut Line= 3
      2786324.98      7094825.00      2785875.00      7094725.00
      2784874.96      7094925.01
#Sta/Elev= 30
  4551.6  577.93  4654.0  574.83  4711.6  571.57  4755.2  571.64  4760.3  573.23
  4803.8  570.06  4869.1  570.74  4880.9  569.56  4896.0  566.64  4920.4  569.64
  4961.3  569.39  4981.8  567.09  4988.2  565.08  4993.4  565.48  5004.7  562.72
  5006.8  562.67  5007.3  561.87  5013.1  562.67  5015.1  562.67  5022.8  567.61
  5033.0  568.53  5303.4  569.56  5309.2  569.60  5410.7  570.87  5532.7  574.92
  5583.6  573.77  5634.6  575.78  5657.7  575.02  5736.6  574.53  6032.4  578.01
#Mann=7,-1,0
  4551.6    0.05       0  5004.7    0.16       0  5006.8    0.03       0
  5013.1    0.16       0  5309.2    0.12       0  5410.7    0.16       0
  5657.7    0.05       0
Bank Sta=4880.9,5303.4
Exp/Cntr=0.3,0.1

Type RM Length L Ch R = 1,49508,565,565,565
BEGIN DESCRIPTION:
CEDAR CREEK 56.0
END DESCRIPTION:
XS GIS Cut Line= 3
      2786582.93      7094631.99      2785825.00      7094275.00
      2784832.91      7094329.91
#Sta/Elev= 30
  4147.7  581.22  4225.5  579.75  4255.9  577.45  4385.1  577.20  4590.9  570.95
  4664.0  570.73  4687.2  568.97  4695.0  568.80  4749.1  567.48  4910.8  567.64
  4988.0  567.33  5002.4  560.67  5002.9  559.87  5008.7  560.67  5015.5  566.67
  5025.6  567.28  5125.7  566.28  5145.7  564.54  5165.8  568.37  5194.1  568.80
  5215.0  570.04  5296.0  572.82  5406.1  572.40  5446.2  573.78  5526.9  572.32
  5596.4  571.26  5620.1  572.61  5636.5  571.66  5915.5  575.46  5979.1  575.98
#Mann=10,-1,0
  4147.7    0.05       0  4590.9    0.16       0  4687.2    0.05       0
  4749.1    0.16       0  4910.8    0.12       0  5002.4    0.07       0
  5008.7    0.12       0  5215.0    0.05       0  5526.9    0.16       0
  5915.5    0.05       0
Bank Sta=4695,5194.1
Exp/Cntr=0.3,0.1

Type RM Length L Ch R = 1,48943,435,435,435
BEGIN DESCRIPTION:
CEDAR CREEK 55.0
END DESCRIPTION:
XS GIS Cut Line= 3
      2786681.89      7093902.83      2785875.00      7093775.00
      2784942.31      7093845.54
#Sta/Elev= 30
  4178.6  574.77  4307.1  572.94  4357.7  570.71  4499.4  570.13  4529.8  567.98
  4763.7  565.56  4872.6  564.38  4914.6  565.17  4934.8  563.19  4955.1  564.96
  4985.4  564.84  5012.4  562.34  5012.9  561.54  5018.8  562.34  5025.6  564.35
  5058.1  565.56  5085.8  567.83  5102.8  566.68  5156.0  566.46  5176.1  568.26
  5236.2  569.09  5276.3  567.61  5346.5  568.84  5376.6  571.15  5426.8  571.18
  5455.8  569.50  5537.1  570.33  5600.2  568.51  5717.6  568.16  5930.9  572.41
#Mann=6,-1,0
  4178.6    0.05       0  4872.6    0.12       0  5012.4    0.07       0
  5018.8    0.12       0  5102.8    0.05       0  5600.2    0.16       0
Bank Sta=4763.7,5058.1
Exp/Cntr=0.3,0.1

Type RM Length L Ch R = 1,48508,463,463,463
BEGIN DESCRIPTION:
CEDAR CREEK 54.0
END DESCRIPTION:
XS GIS Cut Line= 3
      2787425.03      7093675.01      2785875.00      7093325.00
      2784275.04      7093974.98
#Sta/Elev= 30
  3334.3  590.64  4287.7  570.89  4544.0  569.17  4564.5  568.19  4578.8  564.83
  4605.5  561.71  4636.3  561.23  4667.1  562.47  4672.9  567.44  4708.1  563.67
  4808.3  562.44  4926.1  563.88  4932.7  562.01  4938.1  563.78  4962.2  562.15
  4967.6  563.99  4986.2  561.24  4991.6  563.45  4995.7  559.49  4996.2  558.69
  5002.1  559.49  5009.7  564.13  5073.2  563.63  5173.8  564.83  5290.3  567.35
  5526.7  565.69  5711.9  566.87  5937.9  572.71  6358.9  577.47  6650.3  583.49
#Mann=7,-1,0
  3334.3    0.05       0  4808.3    0.12       0  4995.7    0.07       0
  5002.1    0.12       0  5073.2    0.05       0  5526.7    0.16       0
  5937.9    0.05       0
Bank Sta=4578.8,5173.8
Exp/Cntr=0.3,0.1

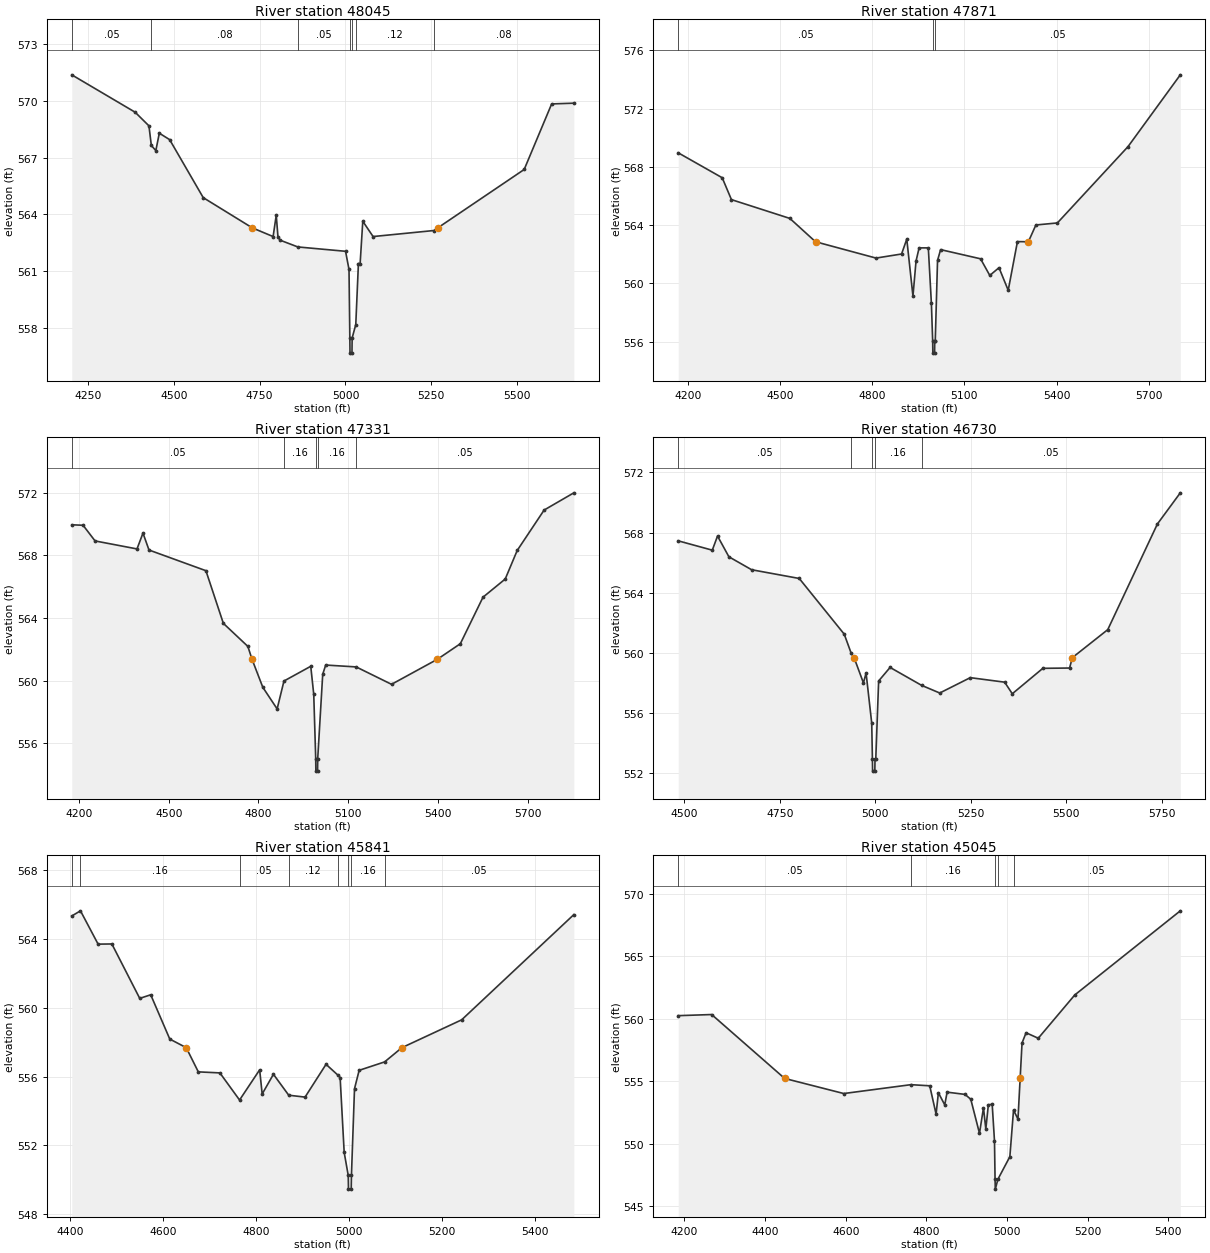
Type RM Length L Ch R = 1,48045,174,174,174
BEGIN DESCRIPTION:
Mapping XS 360afa89
END DESCRIPTION:
XS GIS Cut Line= 3
      2786478.76      7093105.95      2785645.43      7093027.83
      2785020.41      7093027.83
#Sta/Elev= 30
  4203.1  571.39  4387.7  569.41  4427.8  568.69  4434.8  567.65  4447.9  567.38
  4458.0  568.30  4488.1  567.96  4585.9  564.89  4728.8  563.29  4789.4  562.83
  4798.5  563.96  4803.5  562.82  4809.5  562.64  4861.4  562.28  5000.3  562.05
  5010.4  561.09  5012.8  557.46  5013.3  556.66  5019.0  556.66  5019.5  557.46
  5030.1  558.17  5037.8  561.40  5042.8  561.40  5050.5  563.64  5080.5  562.83
  5258.1  563.15  5269.0  563.29  5520.5  566.38  5600.5  569.85  5665.1  569.89
#Mann=7,-1,0
  4203.1    0.05       0  4434.8    0.08       0  4861.4    0.05       0
  5012.8    0.04       0  5019.5    0.05       0  5030.1    0.12       0
  5258.1    0.08       0
Bank Sta=4728.8,5269
Exp/Cntr=0.3,0.1

Type RM Length L Ch R = 1,47871,540,540,540
BEGIN DESCRIPTION:
CEDAR CREEK 53.0
END DESCRIPTION:
XS GIS Cut Line= 3
      2786457.96      7092913.25      2785625.00      7092875.00
      2784825.04      7092875.00
#Sta/Elev= 30
  4169.0  568.96  4312.1  567.25  4342.1  565.75  4532.3  564.46  4615.7  562.86
  4812.6  561.74  4895.8  562.02  4912.7  563.04  4932.8  559.13  4942.8  561.53
  4952.8  562.44  4982.8  562.44  4992.8  558.63  4997.0  556.02  4997.5  555.22
  5003.2  555.22  5003.7  556.02  5005.3  556.02  5012.8  561.58  5022.8  562.32
  5152.8  561.69  5182.8  560.55  5212.8  561.08  5242.8  559.53  5272.8  562.87
  5308.4  562.86  5332.8  564.01  5402.8  564.15  5632.8  569.39  5802.8  574.31
#Mann=3,-1,0
  4169.0    0.05       0  4997.0    0.04       0  5003.7    0.05       0
Bank Sta=4615.7,5308.4
Exp/Cntr=0.3,0.1

Type RM Length L Ch R = 1,47331,601,601,601
BEGIN DESCRIPTION:
CEDAR CREEK 52.0
END DESCRIPTION:
XS GIS Cut Line= 3
      2786452.75      7092418.45      2785675.00      7092375.00
      2784775.65      7092397.62
#Sta/Elev= 30
  4175.9  569.94  4213.7  569.91  4253.8  568.91  4394.0  568.40  4414.0  569.41
  4434.1  568.33  4624.4  567.01  4682.7  563.65  4764.6  562.18  4778.5  561.36
  4814.6  559.57  4862.5  558.19  4885.3  559.97  4974.9  560.91  4984.9  559.12
  4991.5  555.02  4992.0  554.22  4997.7  554.22  4998.2  555.02  5014.9  560.40
  5024.9  560.99  5126.8  560.87  5245.0  559.76  5398.5  561.36  5475.0  562.35
  5550.8  565.32  5625.1  566.48  5665.1  568.30  5755.1  570.88  5854.5  571.98
#Mann=5,-1,0
  4175.9    0.05       0  4885.3    0.16       0  4991.5    0.07       0
  4998.2    0.16       0  5126.8    0.05       0
Bank Sta=4778.5,5398.5
Exp/Cntr=0.3,0.1

Type RM Length L Ch R = 1,46730,889,889,889
BEGIN DESCRIPTION:
CEDAR CREEK 51.0
END DESCRIPTION:
XS GIS Cut Line= 3
      2786124.98      7092174.99      2785675.00      7091925.00
      2784874.96      7091925.00
#Sta/Elev= 30
  4483.7  567.45  4572.9  566.83  4586.6  567.77  4616.4  566.39  4675.9  565.53
  4800.6  564.95  4918.4  561.25  4936.8  559.97  4944.2  559.69  4968.7  558.01
  4975.6  558.67  4990.4  555.34  4992.2  552.95  4992.7  552.15  4998.5  552.15
  4999.0  552.95  5001.0  552.95  5008.5  558.14  5038.5  559.04  5120.9  557.85
  5168.5  557.34  5248.5  558.36  5338.5  558.06  5358.5  557.29  5438.5  558.98
  5508.5  559.00  5515.8  559.69  5608.5  561.55  5738.5  568.57  5798.5  570.64
#Mann=5,-1,0
  4483.7    0.05       0  4936.8    0.16       0  4992.2    0.07       0
  4999.0    0.16       0  5120.9    0.05       0
Bank Sta=4944.2,5515.8
Exp/Cntr=0.3,0.1

Type RM Length L Ch R = 1,45841,796,796,796
BEGIN DESCRIPTION:
CEDAR CREEK 50.0
END DESCRIPTION:
XS GIS Cut Line= 3
      2785900.62      7091501.78      2785353.76      7091283.04
      2784864.13      7091309.08
#Sta/Elev= 30
  4404.3  565.35  4423.0  565.65  4460.9  563.71  4490.5  563.72  4550.4  560.55
  4574.0  560.76  4615.0  558.18  4650.4  557.68  4676.3  556.27  4722.7  556.21
  4765.0  554.63  4808.2  556.39  4813.6  554.98  4837.8  556.13  4870.7  554.91
  4905.8  554.80  4950.9  556.71  4976.4  556.08  4981.2  555.94  4989.9  551.58
  4998.6  550.24  4999.1  549.44  5005.0  549.44  5005.5  550.24  5012.1  555.29
  5022.1  556.36  5076.8  556.85  5114.0  557.68  5242.4  559.30  5483.6  565.43
#Mann=8,-1,0
  4404.3    0.05       0  4423.0    0.16       0  4765.0    0.05       0
  4870.7    0.12       0  4976.4    0.16       0  4998.6    0.07       0
  5005.5    0.16       0  5076.8    0.05       0
Bank Sta=4650.4,5114
Exp/Cntr=0.3,0.1

Type RM Length L Ch R = 1,45045,565,565,565
BEGIN DESCRIPTION:
CEDAR CREEK 49.0
END DESCRIPTION:
XS GIS Cut Line= 3
      2786009.97      7091022.60      2785325.00      7090625.00
      2784874.97      7090675.00
#Sta/Elev= 30
  4184.7  560.25  4267.6  560.34  4448.5  555.22  4595.1  554.01  4761.6  554.72
  4808.2  554.63  4824.0  552.36  4829.7  554.07  4845.5  553.10  4851.3  554.12
  4895.8  553.94  4910.0  553.55  4931.6  550.82  4941.5  552.87  4947.3  551.16
  4953.6  553.11  4963.1  553.14  4968.8  550.21  4970.2  547.15  4970.8  546.35
  4977.4  547.15  5006.9  548.95  5016.0  552.69  5027.0  551.96  5032.4  555.22
  5037.1  558.06  5047.1  558.88  5077.3  558.44  5167.9  561.91  5429.5  568.65
#Mann=5,-1,0
  4184.7    0.05       0  4761.6    0.16       0  4970.2    0.07       0
  4977.4    0.16       0  5016.0    0.05       0
Bank Sta=4448.5,5032.4
Exp/Cntr=0.3,0.1

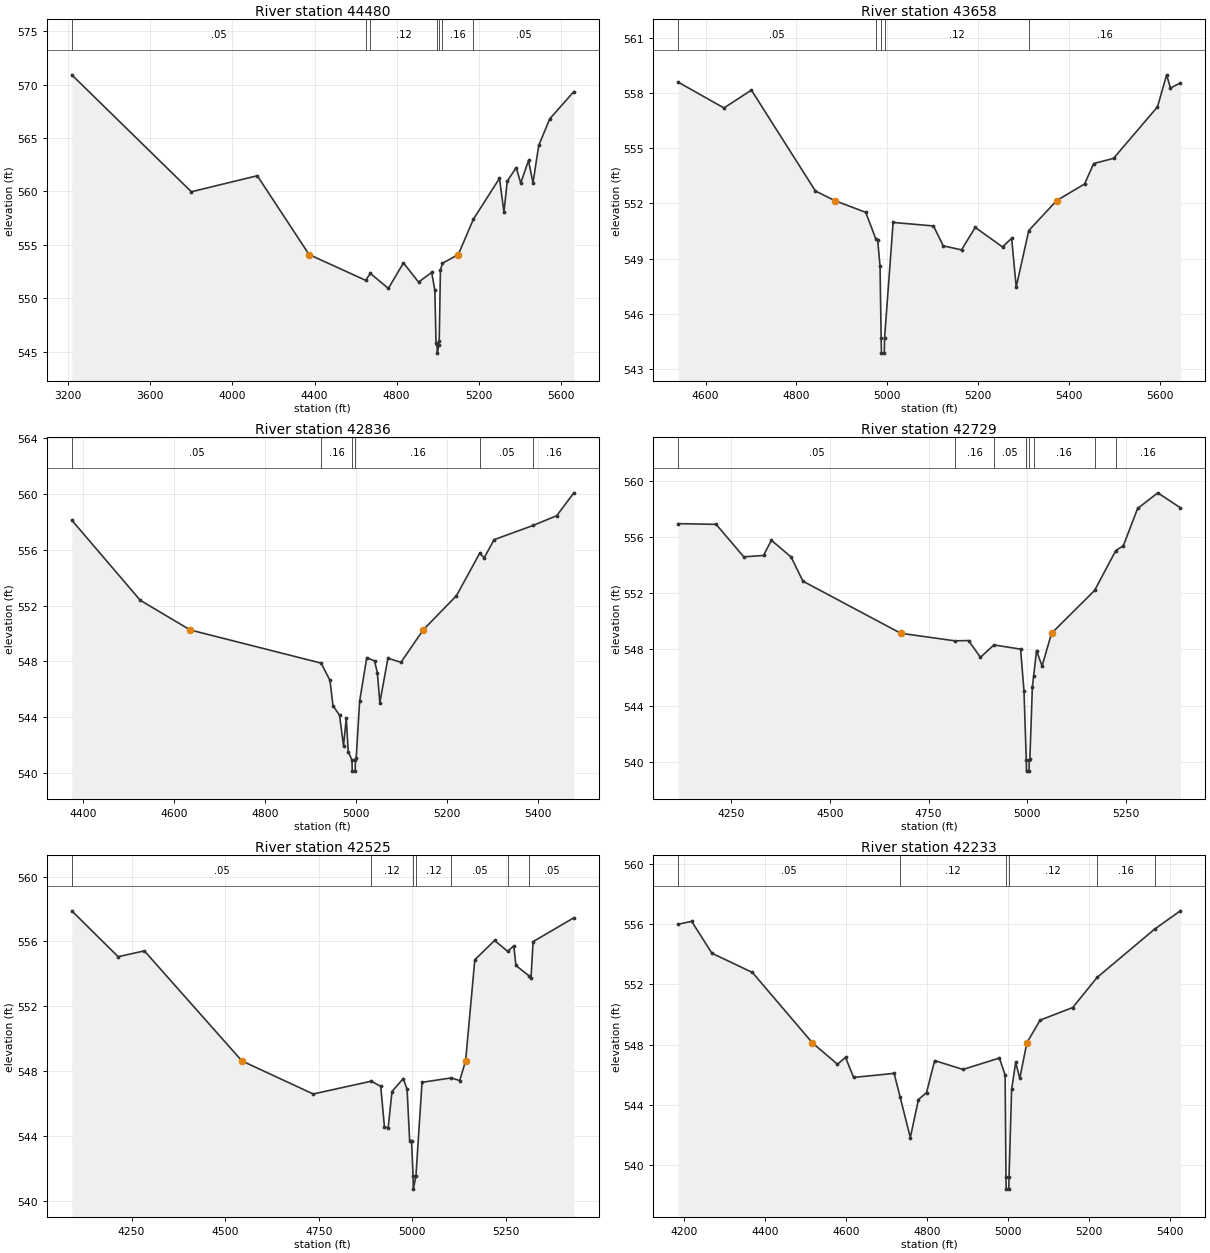
Type RM Length L Ch R = 1,44480,822,822,822
BEGIN DESCRIPTION:
CEDAR CREEK 48.0
END DESCRIPTION:
XS GIS Cut Line= 3
      2787125.03      7091175.02      2785575.00      7090225.00
      2785025.00      7089925.00
#Sta/Elev= 30
  3218.2  570.91  3800.4  559.96  4121.4  561.46  4373.7  554.08  4648.7  551.67
  4672.1  552.31  4759.7  550.91  4833.1  553.30  4906.6  551.50  4970.5  552.41
  4985.9  550.74  4991.8  545.76  4997.4  545.65  4997.9  544.85  5004.7  545.65
  5007.2  545.96  5013.1  552.59  5022.6  553.26  5100.1  554.08  5173.3  557.38
  5300.6  561.22  5322.4  558.06  5338.5  560.95  5382.2  562.23  5404.0  560.77
  5442.0  562.89  5463.8  560.78  5491.8  564.31  5545.5  566.79  5662.7  569.34
#Mann=7,-1,0
  3218.2    0.05       0  4648.7    0.16       0  4672.1    0.12       0
  4997.4    0.07       0  5004.7    0.12       0  5022.6    0.16       0
  5173.3    0.05       0
Bank Sta=4373.7,5100.1
Exp/Cntr=0.3,0.1

Type RM Length L Ch R = 1,43658,822,822,822
BEGIN DESCRIPTION:
CEDAR CREEK 47.0
END DESCRIPTION:
XS GIS Cut Line= 3
      2786724.99      7089998.61      2786275.00      7089948.61
      2785624.98      7089898.61
#Sta/Elev= 30
  4539.9  558.59  4640.5  557.19  4700.9  558.16  4841.7  552.68  4883.9  552.16
  4952.4  551.52  4974.9  550.06  4978.8  549.99  4983.9  548.60  4986.4  544.67
  4987.0  543.87  4993.3  543.87  4993.8  544.67  5012.7  550.97  5101.5  550.78
  5123.0  549.70  5163.2  549.48  5193.3  550.70  5253.4  549.64  5273.5  550.11
  5283.5  547.46  5311.2  550.53  5372.6  552.16  5434.0  553.06  5454.0  554.17
  5497.6  554.45  5594.4  557.25  5614.5  558.99  5623.0  558.27  5644.6  558.55
#Mann=5,-1,0
  4539.9    0.05       0  4974.9    0.12       0  4986.4    0.07       0
  4993.8    0.12       0  5311.2    0.16       0
Bank Sta=4883.9,5372.6
Exp/Cntr=0.3,0.1

Type RM Length L Ch R = 1,42836,107,107,107
BEGIN DESCRIPTION:
CEDAR CREEK 46.0
END DESCRIPTION:
XS GIS Cut Line= 3
      2786674.97      7089674.98      2786175.00      7089325.00
      2785725.04      7089125.02
#Sta/Elev= 30
  4375.3  558.13  4525.7  552.38  4635.4  550.25  4923.0  547.87  4942.4  546.63
  4949.0  544.82  4963.4  544.13  4972.1  541.94  4978.2  543.91  4982.5  541.52
  4990.7  540.92  4991.3  540.12  4997.7  540.12  4998.3  540.92  5000.0  541.05
  5007.5  545.14  5023.2  548.27  5040.3  548.02  5046.5  547.18  5051.9  545.04
  5069.7  548.22  5098.4  547.93  5147.0  550.25  5220.2  552.71  5271.3  555.76
  5281.1  555.43  5302.9  556.73  5388.4  557.75  5440.4  558.45  5478.0  560.09
#Mann=6,-1,0
  4375.3    0.05       0  4923.0    0.16       0  4990.7    0.07       0
  4998.3    0.16       0  5271.3    0.05       0  5388.4    0.16       0
Bank Sta=4635.4,5147
Exp/Cntr=0.3,0.1

Type RM Length L Ch R = 1,42729,204,204,204
BEGIN DESCRIPTION:
Mapping XS ae664961
END DESCRIPTION:
XS GIS Cut Line= 3
      2787011.13      7089240.50      2786143.12      7089227.48
      2785761.14      7089092.92
#Sta/Elev= 30
  4115.1  556.94  4211.2  556.89  4281.3  554.58  4331.3  554.68  4351.3  555.76
  4401.3  554.57  4431.3  552.85  4679.1  549.15  4816.6  548.61  4851.3  548.63
  4881.3  547.44  4915.7  548.32  4983.2  548.02  4991.8  545.06  4997.6  540.15
  4998.2  539.35  5004.6  539.35  5005.2  540.15  5006.7  540.18  5013.0  545.30
  5016.4  546.14  5023.6  547.91  5037.7  546.82  5061.7  549.15  5170.8  552.19
  5224.7  555.03  5243.7  555.37  5280.0  558.02  5331.1  559.13  5388.2  558.07
#Mann=8,-1,0
  4115.1    0.05       0  4816.6    0.16       0  4915.7    0.05       0
  4997.6    0.03       0  5005.2    0.05       0  5016.4    0.16       0
  5170.8    0.08       0  5224.7    0.16       0
Bank Sta=4679.1,5061.7
Exp/Cntr=0.3,0.1

Type RM Length L Ch R = 1,42525,292,292,292
BEGIN DESCRIPTION:
Mapping XS d8f68ab7
END DESCRIPTION:
XS GIS Cut Line= 4
      2787028.55      7089075.57      2786125.75      7089019.15
      2785939.12      7088997.45      2785713.45      7088893.29
#Sta/Elev= 30
  4090.4  557.89  4214.2  555.06  4284.3  555.42  4544.8  548.63  4735.2  546.59
  4890.5  547.38  4915.6  547.06  4925.6  544.54  4935.6  544.52  4945.6  546.74
  4975.7  547.54  4986.0  546.89  4992.8  543.72  4997.9  543.72  5002.0  541.52
  5002.6  540.72  5009.6  541.52  5025.9  547.31  5103.7  547.58  5126.6  547.42
  5142.3  548.63  5166.9  554.87  5219.7  556.06  5254.7  555.39  5271.1  555.73
  5276.6  554.52  5312.8  553.86  5317.0  553.73  5322.5  555.99  5431.4  557.46
#Mann=7,-1,0
  4090.4    0.05       0  4890.5    0.12       0  5002.0    0.07       0
  5009.6    0.12       0  5103.7    0.05       0  5254.7    0.16       0
  5312.8    0.05       0
Bank Sta=4544.8,5142.3
Exp/Cntr=0.3,0.1

Type RM Length L Ch R = 1,42233,532,532,532
BEGIN DESCRIPTION:
Mapping XS 21bed44d
END DESCRIPTION:
XS GIS Cut Line= 3
      2786998.13      7088793.45      2786190.86      7088763.07
      2785761.15      7088815.16
#Sta/Elev= 30
  4185.8  556.01  4219.0  556.20  4269.0  554.08  4369.1  552.80  4517.3  548.12
  4579.2  546.70  4599.2  547.15  4619.2  545.82  4719.3  546.09  4734.1  544.52
  4759.3  541.82  4779.4  544.35  4799.4  544.81  4819.4  546.94  4889.4  546.35
  4979.5  547.11  4993.6  545.97  4995.7  539.19  4996.3  538.39  5002.7  538.39
  5003.3  539.19  5009.6  545.02  5019.7  546.82  5029.8  545.76  5047.3  548.12
  5080.1  549.63  5160.7  550.47  5220.9  552.47  5362.9  555.68  5426.5  556.90
#Mann=6,-1,0
  4185.8    0.05       0  4734.1    0.12       0  4995.7    0.07       0
  5003.3    0.12       0  5220.9    0.16       0  5362.9    0.05       0
Bank Sta=4517.3,5047.3
Exp/Cntr=0.3,0.1