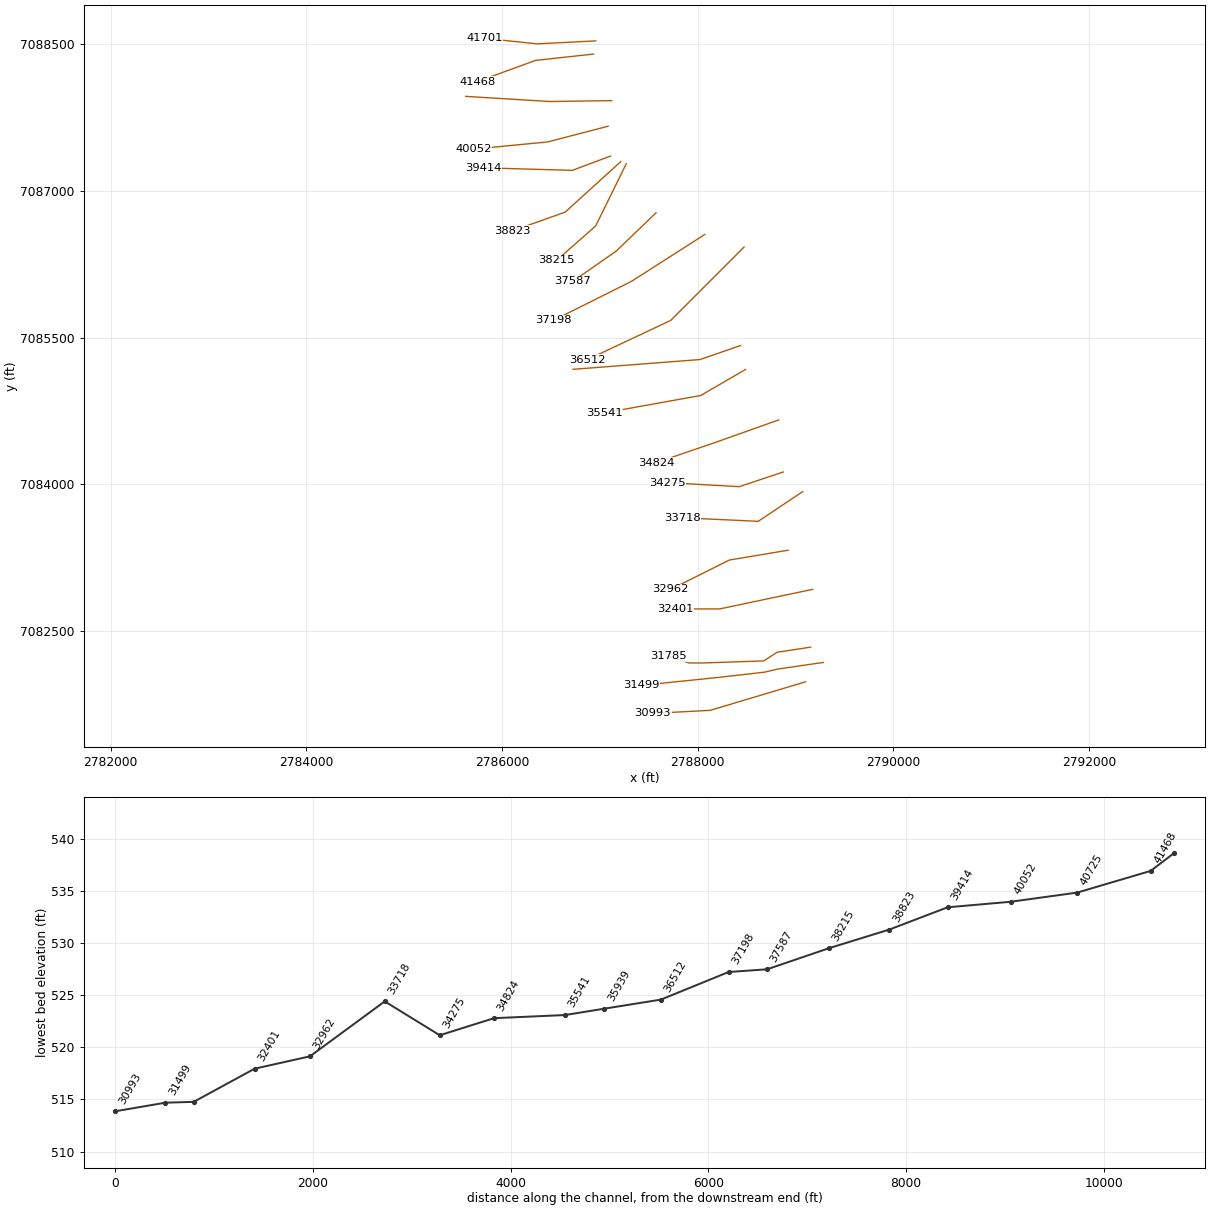
HEC-RAS study CEDAR CREEK.prj: CEDAR CREEK Base Level Engineering

--- CEDAR CREEK.g01 (geometry) --- (continued)

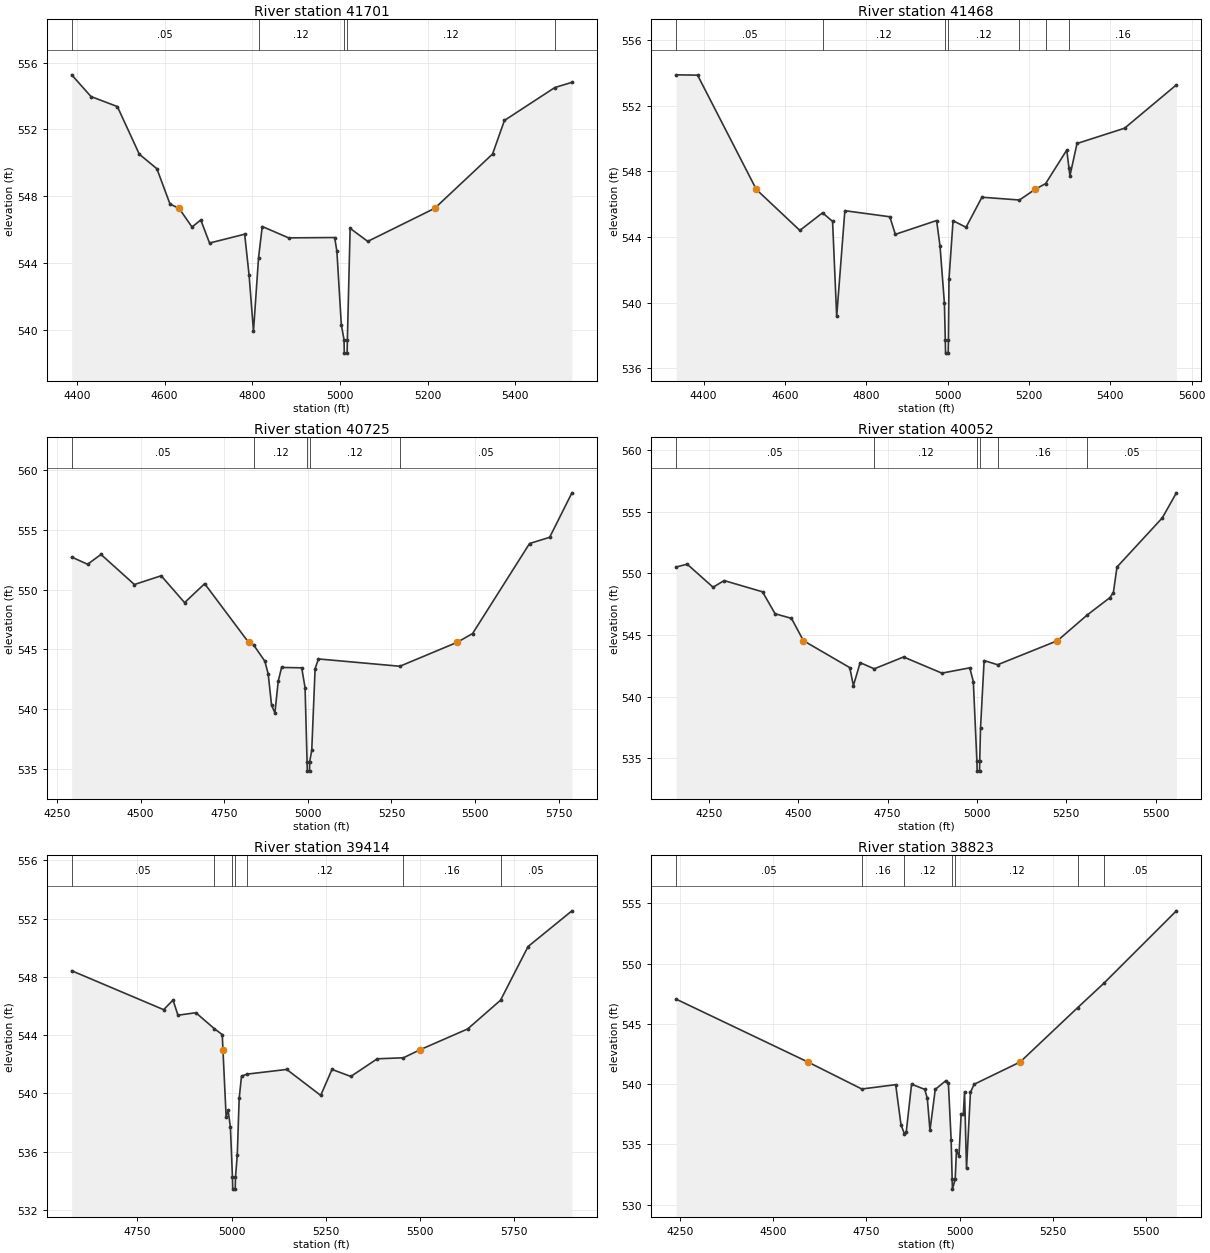
Type RM Length L Ch R = 1,41701,233,233,233
BEGIN DESCRIPTION:
Mapping XS 02f6d5fb
END DESCRIPTION:
XS GIS Cut Line= 3
      2786959.04      7088533.03      2786360.13      7088502.65
      2785821.96      7088559.08
#Sta/Elev= 30
  4388.3  555.27  4432.4  553.97  4492.5  553.37  4542.5  550.52  4582.6  549.65
  4612.6  547.53  4633.1  547.28  4662.7  546.16  4682.7  546.58  4702.7  545.20
  4782.8  545.73  4792.9  543.27  4802.9  539.92  4814.4  544.31  4822.9  546.19
  4883.0  545.51  4988.0  545.53  4993.1  544.71  5003.2  540.31  5009.4  539.41
  5010.0  538.61  5016.4  538.61  5017.0  539.41  5023.3  546.08  5063.5  545.30
  5216.2  547.28  5348.1  550.53  5375.2  552.54  5490.1  554.51  5529.1  554.82
#Mann=5,-1,0
  4388.3    0.05       0  4814.4    0.12       0  5009.4    0.07       0
  5017.0    0.12       0  5490.1    0.16       0
Bank Sta=4633.1,5216.2
Exp/Cntr=0.3,0.1

Type RM Length L Ch R = 1,41468,743,743,743
BEGIN DESCRIPTION:
CEDAR CREEK 43.0
END DESCRIPTION:
XS GIS Cut Line= 3
      2786937.41      7088398.49      2786342.77      7088333.38
      2785749.07      7088116.70
#Sta/Elev= 30
  4332.3  553.87  4385.0  553.85  4529.6  546.89  4636.5  544.40  4692.3  545.47
  4717.0  544.95  4727.1  539.16  4747.2  545.60  4857.8  545.23  4871.3  544.16
  4972.8  545.00  4981.3  543.43  4992.0  539.97  4994.2  537.73  4994.8  536.93
  5001.3  536.93  5001.9  537.73  5003.3  541.45  5013.3  544.99  5045.2  544.59
  5084.3  546.42  5176.6  546.25  5214.4  546.89  5240.9  547.25  5292.9  549.29
  5298.4  548.18  5300.7  547.72  5318.1  549.69  5435.0  550.62  5562.5  553.26
#Mann=7,-1,0
  4332.3    0.05       0  4692.3    0.12       0  4994.2    0.07       0
  5001.9    0.12       0  5176.6    0.16       0  5240.9    0.12       0
  5298.4    0.16       0
Bank Sta=4529.6,5214.4
Exp/Cntr=0.3,0.1

Type RM Length L Ch R = 1,40725,673,673,673
BEGIN DESCRIPTION:
CEDAR CREEK 42.0
END DESCRIPTION:
XS GIS Cut Line= 3
      2787122.58      7087922.19      2786487.69      7087913.08
      2785628.55      7087965.71
#Sta/Elev= 30
  4293.8  552.71  4341.4  552.11  4381.4  552.93  4481.4  550.42  4561.4  551.15
  4631.4  548.91  4691.4  550.49  4822.6  545.60  4838.0  545.37  4871.4  544.02
  4881.4  542.95  4891.4  540.35  4901.4  539.71  4911.4  542.36  4921.4  543.50
  4981.5  543.47  4991.6  541.82  4997.6  535.65  4998.3  534.85  5004.9  534.85
  5005.5  535.65  5011.6  536.60  5021.6  543.40  5031.6  544.21  5275.0  543.60
  5446.6  545.60  5492.5  546.33  5662.8  553.84  5722.9  554.36  5789.5  558.07
#Mann=5,-1,0
  4293.8    0.05       0  4838.0    0.12       0  4997.6    0.07       0
  5005.5    0.12       0  5275.0    0.05       0
Bank Sta=4822.6,5446.6
Exp/Cntr=0.3,0.1

Type RM Length L Ch R = 1,40052,638,638,638
BEGIN DESCRIPTION:
CEDAR CREEK 41.0
END DESCRIPTION:
XS GIS Cut Line= 3
      2787084.92      7087660.63      2786468.64      7087500.05
      2785709.57      7087426.31
#Sta/Elev= 30
  4158.4  550.51  4189.3  550.74  4261.7  548.87  4292.7  549.41  4400.0  548.50
  4435.3  546.72  4481.0  546.35  4514.5  544.54  4644.0  542.36  4654.3  540.90
  4673.2  542.76  4712.6  542.26  4794.6  543.22  4901.8  541.91  4979.8  542.34
  4989.8  541.23  4999.8  534.77  5000.5  533.97  5007.1  533.97  5007.7  534.77
  5009.9  537.45  5020.0  542.93  5057.8  542.59  5225.2  544.54  5308.7  546.63
  5371.6  548.02  5381.6  548.44  5391.7  550.51  5518.5  554.49  5557.9  556.52
#Mann=6,-1,0
  4158.4    0.05       0  4712.6    0.12       0  4999.8    0.07       0
  5007.7    0.12       0  5057.8    0.16       0  5308.7    0.05       0
Bank Sta=4514.5,5225.2
Exp/Cntr=0.3,0.1

Type RM Length L Ch R = 1,39414,591,591,591
BEGIN DESCRIPTION:
CEDAR CREEK 40.0
END DESCRIPTION:
XS GIS Cut Line= 3
      2787109.23      7087355.07      2786718.64      7087209.25
      2785808.63      7087235.25
#Sta/Elev= 30
  4575.5  548.42  4819.5  545.75  4844.4  546.41  4857.5  545.37  4905.0  545.54
  4954.3  544.44  4975.0  544.04  4976.9  542.99  4985.3  538.40  4990.6  538.84
  4996.7  537.67  5002.1  534.24  5002.8  533.44  5009.4  533.44  5010.1  534.24
  5014.9  535.79  5019.9  539.66  5026.1  541.19  5041.2  541.33  5146.1  541.65
  5236.2  539.87  5266.2  541.65  5316.2  541.17  5386.2  542.38  5455.8  542.45
  5498.8  542.99  5626.3  544.43  5713.4  546.40  5786.4  550.08  5902.8  552.53
#Mann=7,-1,0
  4575.5    0.05       0  4954.3    0.16       0  5002.1    0.07       0
  5010.1    0.16       0  5041.2    0.12       0  5455.8    0.16       0
  5713.4    0.05       0
Bank Sta=4976.9,5498.8
Exp/Cntr=0.3,0.1

Type RM Length L Ch R = 1,38823,608,608,608
BEGIN DESCRIPTION:
CEDAR CREEK 39.0
END DESCRIPTION:
XS GIS Cut Line= 3
      2787213.39      7087297.76      2786645.72      7086782.17
      2786104.80      7086589.73
#Sta/Elev= 30
  4240.2  547.05  4593.3  541.84  4737.9  539.60  4828.7  539.96  4842.9  536.64
  4852.1  535.89  4857.1  536.05  4871.3  540.00  4906.5  539.57  4913.5  538.83
  4920.6  536.17  4934.8  539.57  4963.2  540.29  4970.0  540.08  4977.4  535.36
  4980.1  532.10  4980.8  531.30  4988.2  532.10  4991.6  534.51  4998.4  534.05
  5004.2  537.52  5010.1  537.52  5013.3  539.36  5018.6  533.02  5029.1  539.32
  5038.9  539.99  5162.4  541.84  5316.7  546.35  5386.9  548.37  5581.2  554.37
#Mann=7,-1,0
  4240.2    0.05       0  4737.9    0.16       0  4852.1    0.12       0
  4980.1    0.07       0  4988.2    0.12       0  5316.7    0.16       0
  5386.9    0.05       0
Bank Sta=4593.3,5162.4
Exp/Cntr=0.3,0.1

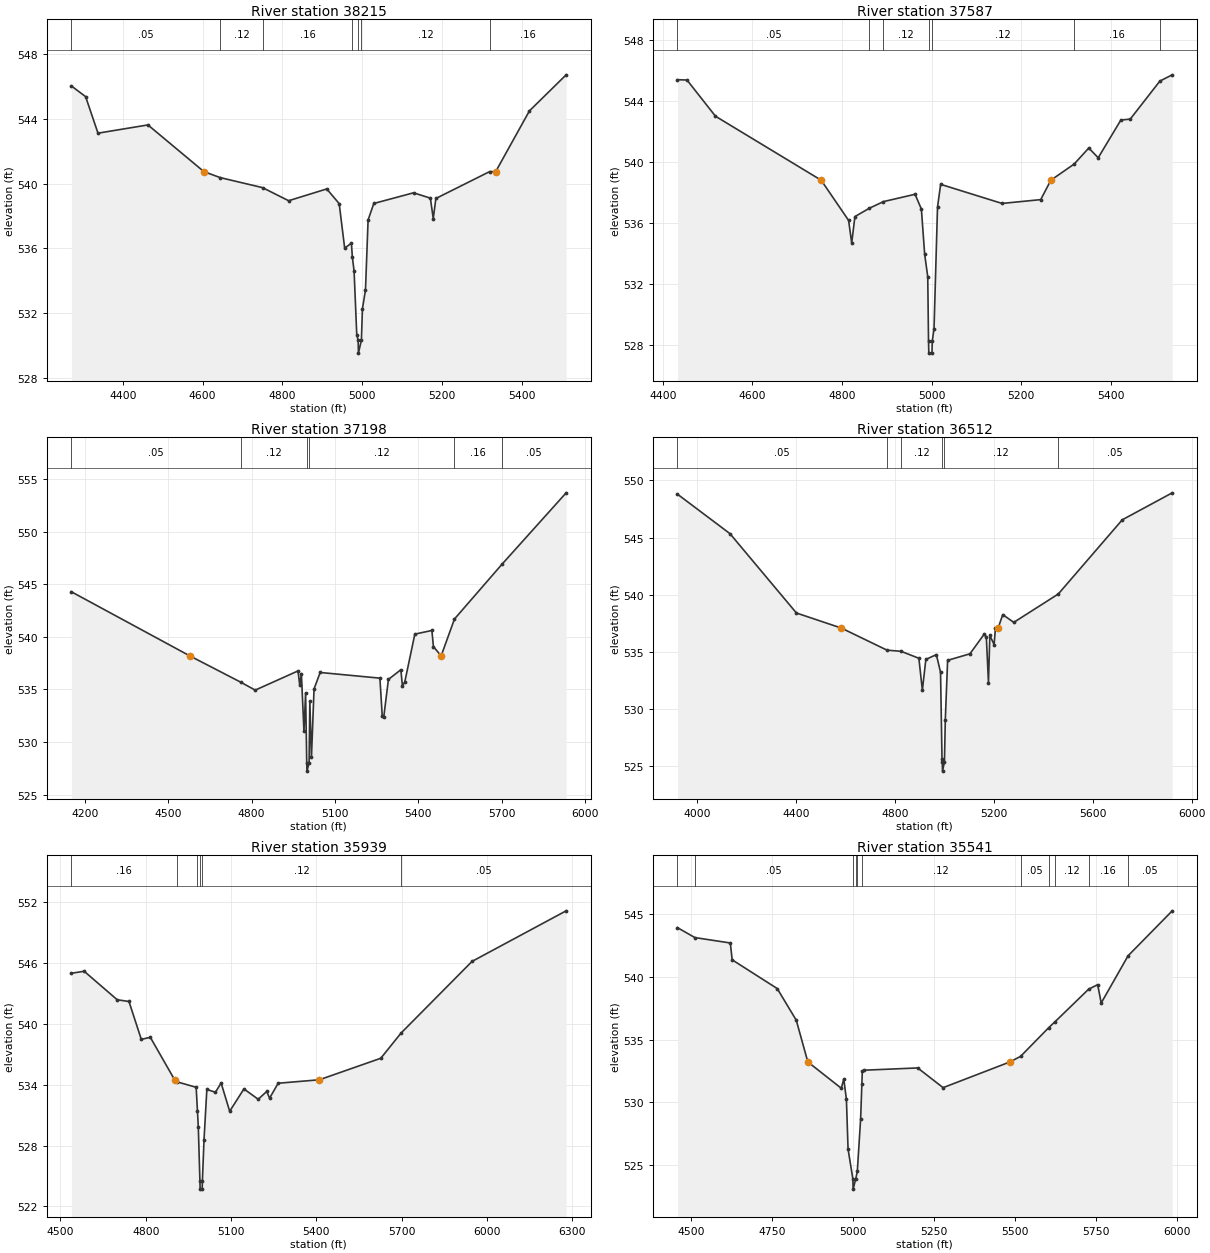
Type RM Length L Ch R = 1,38215,628,628,628
BEGIN DESCRIPTION:
Mapping XS 67cfbca5
END DESCRIPTION:
XS GIS Cut Line= 3
      2787270.73      7087276.99      2786958.22      7086641.54
      2786560.08      7086289.94
#Sta/Elev= 30
  4271.3  546.05  4306.9  545.39  4337.9  543.13  4463.0  543.64  4603.2  540.75
  4644.1  540.38  4750.1  539.76  4815.4  538.95  4910.9  539.68  4942.1  538.77
  4955.8  536.02  4972.7  536.32  4975.0  535.48  4979.4  534.60  4986.1  530.67
  4989.6  530.32  4990.3  529.52  4997.7  530.32  5000.3  532.27  5007.9  533.41
  5014.5  537.76  5028.8  538.78  5128.3  539.44  5170.5  539.11  5177.7  537.85
  5184.3  539.09  5318.8  540.75  5334.1  540.75  5418.6  544.51  5510.6  546.74
#Mann=7,-1,0
  4271.3    0.05       0  4644.1    0.12       0  4750.1    0.16       0
  4975.0    0.12       0  4989.6    0.07       0  4997.7    0.12       0
  5318.8    0.16       0
Bank Sta=4603.2,5334.1
Exp/Cntr=0.3,0.1

Type RM Length L Ch R = 1,37587,389,389,389
BEGIN DESCRIPTION:
double CEDAR CREEK 38.0
END DESCRIPTION:
XS GIS Cut Line= 3
      2787575.02      7086775.01      2787165.57      7086381.88
      2786725.03      7086075.02
#Sta/Elev= 30
  4432.8  545.39  4454.0  545.37  4517.6  543.00  4753.6  538.81  4814.8  536.18
  4821.7  534.70  4828.9  536.43  4860.8  536.97  4892.6  537.41  4963.2  537.89
  4977.3  536.92  4984.6  533.97  4991.5  532.49  4993.2  528.29  4993.9  527.49
  5000.9  527.49  5001.6  528.29  5005.5  529.08  5013.3  537.05  5020.3  538.54
  5157.3  537.29  5243.7  537.54  5266.3  538.81  5318.4  539.87  5351.0  540.92
  5372.0  540.28  5422.6  542.75  5443.5  542.81  5509.7  545.30  5537.3  545.71
#Mann=7,-1,0
  4432.8    0.05       0  4860.8    0.16       0  4892.6    0.12       0
  4993.2    0.07       0  5001.6    0.12       0  5318.4    0.16       0
  5509.7    0.05       0
Bank Sta=4753.6,5266.3
Exp/Cntr=0.3,0.1

Type RM Length L Ch R = 1,37198,686,686,686
BEGIN DESCRIPTION:
double CEDAR CREEK 37.0
END DESCRIPTION:
XS GIS Cut Line= 3
      2788072.76      7086552.97      2787325.00      7086075.00
      2786525.00      7085675.00
#Sta/Elev= 30
  4150.9  544.30  4577.3  538.20  4761.2  535.69  4812.9  534.94  4967.2  536.77
  4973.2  535.42  4979.2  536.51  4988.5  531.01  4994.4  534.68  4998.5  528.03
  4999.3  527.23  5007.0  528.03  5009.6  533.92  5015.5  528.53  5024.8  535.05
  5046.8  536.62  5262.0  536.08  5270.4  532.49  5276.0  532.40  5292.7  535.96
  5337.4  536.88  5343.0  535.38  5351.4  535.69  5387.8  540.27  5449.2  540.62
  5454.8  539.08  5482.6  538.20  5530.6  541.71  5701.0  546.90  5932.8  553.72
#Mann=6,-1,0
  4150.9    0.05       0  4761.2    0.12       0  4998.5    0.07       0
  5007.0    0.12       0  5530.6    0.16       0  5701.0    0.05       0
Bank Sta=4577.3,5482.6
Exp/Cntr=0.3,0.1

Type RM Length L Ch R = 1,36512,573,573,573
BEGIN DESCRIPTION:
CEDAR CREEK 36.0
END DESCRIPTION:
XS GIS Cut Line= 3
      2788474.97      7086424.97      2787725.00      7085675.00
      2786875.03      7085275.01
#Sta/Elev= 30
  3921.5  548.80  4133.6  545.35  4402.3  538.41  4584.1  537.09  4768.5  535.16
  4825.3  535.06  4897.3  534.45  4911.4  531.66  4925.5  534.35  4968.0  534.77
  4984.9  533.22  4990.8  525.62  4992.0  525.38  4992.8  524.58  5000.6  525.38
  5004.2  529.09  5013.5  534.27  5103.7  534.84  5161.4  536.56  5170.0  536.31
  5178.6  532.32  5184.2  536.45  5201.4  535.65  5207.0  537.12  5217.7  537.09
  5236.3  538.27  5280.9  537.59  5460.8  540.07  5719.5  546.56  5921.5  548.92
#Mann=6,-1,0
  3921.5    0.05       0  4768.5    0.16       0  4825.3    0.12       0
  4992.0    0.07       0  5000.6    0.12       0  5460.8    0.05       0
Bank Sta=4584.1,5217.7
Exp/Cntr=0.3,0.1

Type RM Length L Ch R = 1,35939,398,398,398
BEGIN DESCRIPTION:
CEDAR CREEK 35.0
END DESCRIPTION:
XS GIS Cut Line= 3
      2788437.35      7085417.57      2788025.00      7085275.00
      2786725.04      7085175.00
#Sta/Elev= 30
  4538.7  544.97  4583.5  545.17  4699.9  542.36  4741.2  542.19  4784.5  538.46
  4816.3  538.66  4901.7  534.48  4909.7  534.28  4977.5  533.74  4982.0  531.42
  4985.0  529.87  4990.7  524.51  4991.5  523.71  4998.6  523.71  4999.4  524.51
  5005.1  528.56  5015.1  533.53  5045.2  533.25  5065.3  534.16  5095.4  531.38
  5145.5  533.58  5195.7  532.56  5225.7  533.33  5235.8  532.67  5265.9  534.14
  5410.8  534.48  5626.9  536.60  5698.1  539.08  5947.9  546.14  6278.8  551.12
#Mann=6,-1,0
  4538.7    0.16       0  4909.7    0.05       0  4982.0    0.12       0
  4990.7    0.07       0  4999.4    0.12       0  5698.1    0.05       0
Bank Sta=4901.7,5410.8
Exp/Cntr=0.3,0.1

Type RM Length L Ch R = 1,35541,717,717,717
BEGIN DESCRIPTION:
CEDAR CREEK 34.0
END DESCRIPTION:
XS GIS Cut Line= 3
      2788489.48      7085172.80      2788031.14      7084907.17
      2787048.36      7084730.37
#Sta/Elev= 30
  4457.8  543.92  4511.5  543.13  4621.0  542.70  4626.7  541.36  4765.9  539.07
  4824.7  536.55  4860.4  533.23  4963.9  531.13  4971.5  531.87  4979.6  530.25
  4984.7  526.30  4999.6  523.90  5000.3  523.10  5008.3  523.90  5013.3  524.53
  5023.6  528.72  5027.3  531.45  5028.7  532.48  5034.4  532.57  5199.8  532.75
  5278.3  531.18  5484.9  533.23  5517.6  533.67  5603.9  535.94  5623.7  536.42
  5727.8  539.02  5755.8  539.38  5766.7  537.92  5849.7  541.68  5986.1  545.26
#Mann=11,-1,0
  4457.8    0.16       0  4511.5    0.05       0  4999.6    0.03       0
  5008.3    0.05       0  5013.3    0.16       0  5027.3    0.12       0
  5517.6    0.05       0  5603.9    0.16       0  5623.7    0.12       0
  5727.8    0.16       0  5849.7    0.05       0
Bank Sta=4860.4,5484.9
Exp/Cntr=0.3,0.1

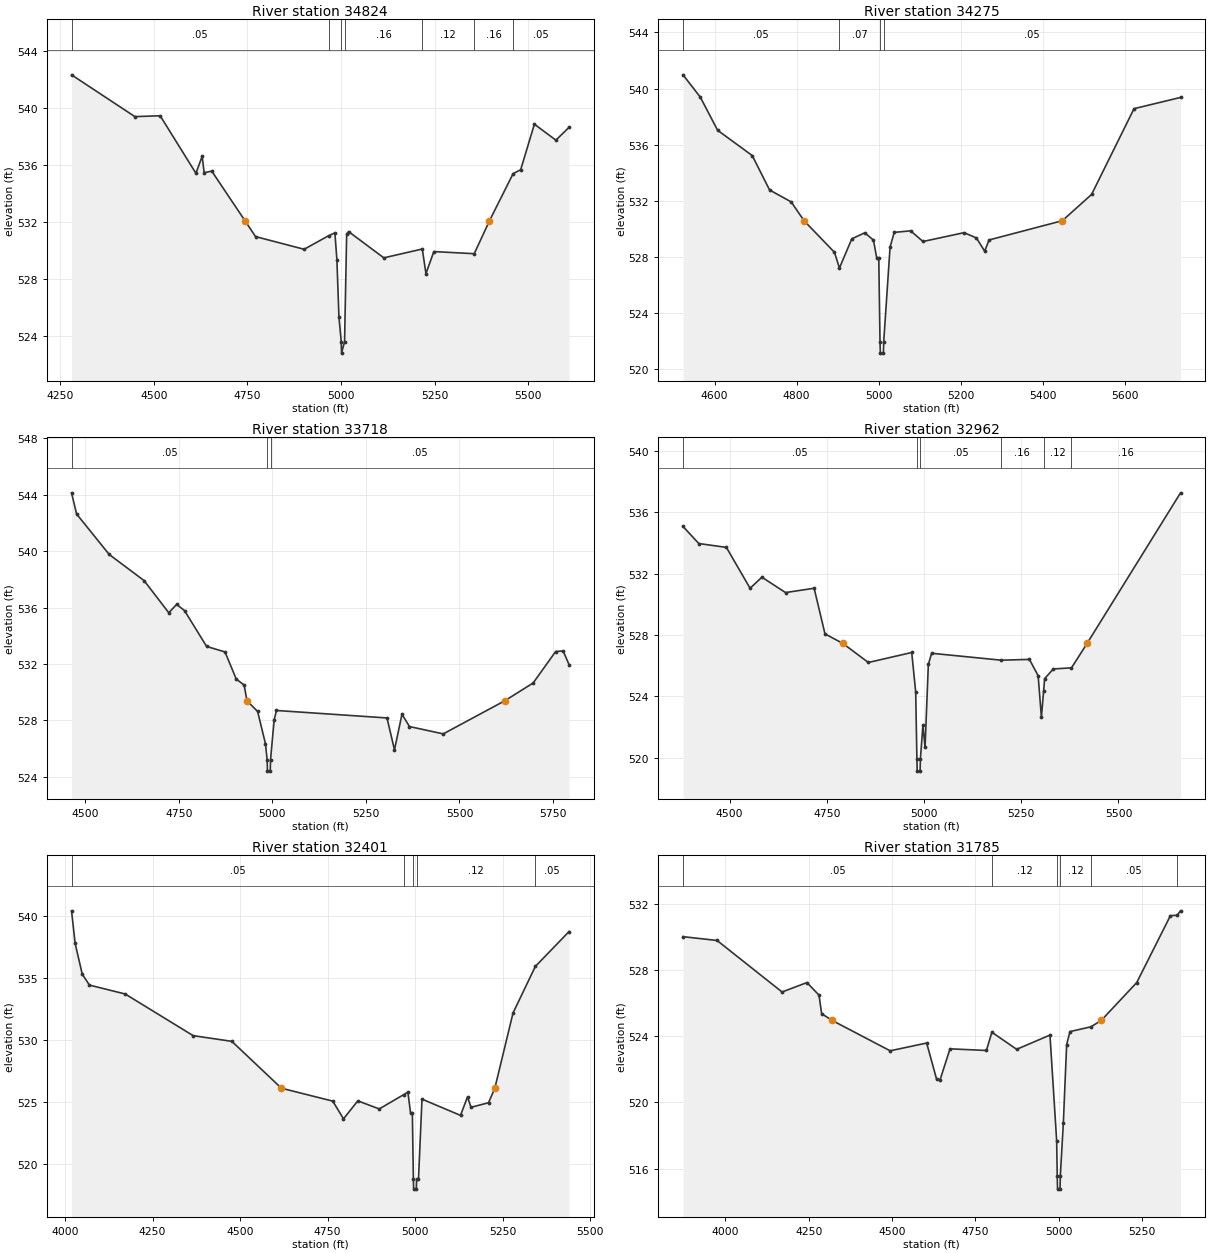
Type RM Length L Ch R = 1,34824,549,549,549
BEGIN DESCRIPTION:
CEDAR CREEK 33.0
END DESCRIPTION:
XS GIS Cut Line= 3
      2788827.99      7084657.16      2788175.00      7084425.00
      2787573.26      7084219.82
#Sta/Elev= 30
  4280.5  542.31  4449.7  539.38  4517.2  539.44  4612.7  535.41  4629.4  536.60
  4634.7  535.45  4655.0  535.56  4743.8  532.08  4771.9  530.97  4901.7  530.08
  4967.0  531.03  4983.9  531.23  4989.2  529.36  4994.7  525.33  5000.8  523.60
  5001.6  522.80  5009.7  523.60  5015.3  531.15  5020.5  531.32  5114.6  529.48
  5217.3  530.10  5227.1  528.38  5248.2  529.92  5356.0  529.77  5396.8  532.08
  5459.8  535.38  5480.1  535.66  5516.7  538.85  5574.1  537.73  5609.3  538.63
#Mann=7,-1,0
  4280.5    0.05       0  4967.0    0.16       0  5000.8    0.07       0
  5009.7    0.16       0  5217.3    0.12       0  5356.0    0.16       0
  5459.8    0.05       0
Bank Sta=4743.8,5396.8
Exp/Cntr=0.3,0.1

Type RM Length L Ch R = 1,34275,557,557,557
BEGIN DESCRIPTION:
CEDAR CREEK 32.0
END DESCRIPTION:
XS GIS Cut Line= 3
      2788874.96      7084124.99      2788425.00      7083975.00
      2787688.66      7084016.47
#Sta/Elev= 30
  4523.2  540.98  4565.3  539.39  4607.5  537.03  4691.8  535.23  4734.0  532.78
  4786.7  531.93  4818.0  530.59  4892.1  528.34  4904.2  527.22  4934.3  529.30
  4965.9  529.73  4987.0  529.21  4994.9  527.96  5000.0  527.96  5003.0  521.96
  5003.9  521.16  5011.2  521.16  5012.0  521.96  5027.5  528.71  5037.6  529.76
  5077.6  529.87  5107.7  529.11  5207.8  529.74  5237.9  529.36  5257.9  528.42
  5268.6  529.22  5447.0  530.59  5518.3  532.46  5621.7  538.57  5735.0  539.37
#Mann=4,-1,0
  4523.2    0.05       0  4904.2    0.07       0  5003.0    0.07       0
  5012.0    0.05       0
Bank Sta=4818,5447
Exp/Cntr=0.3,0.1

Type RM Length L Ch R = 1,33718,756,756,756
BEGIN DESCRIPTION:
CEDAR CREEK 31.0
END DESCRIPTION:
XS GIS Cut Line= 3
      2789074.97      7083924.98      2788619.68      7083620.71
      2787839.23      7083657.13
#Sta/Elev= 30
  4463.8  544.14  4477.3  542.64  4564.4  539.77  4657.5  537.92  4723.5  535.64
  4744.6  536.23  4765.6  535.79  4824.6  533.25  4873.7  532.86  4903.7  530.94
  4924.8  530.51  4932.4  529.40  4960.8  528.64  4981.8  526.35  4986.3  525.21
  4987.2  524.41  4994.5  524.41  4995.3  525.21  5005.0  528.05  5011.2  528.71
  5306.4  528.18  5326.4  525.92  5346.4  528.44  5366.5  527.57  5456.6  527.05
  5621.2  529.40  5696.8  530.66  5756.9  532.89  5776.9  532.93  5792.7  531.96
#Mann=3,-1,0
  4463.8    0.05       0  4986.3    0.03       0  4995.3    0.05       0
Bank Sta=4932.4,5621.2
Exp/Cntr=0.3,0.1

Type RM Length L Ch R = 1,32962,561,561,561
BEGIN DESCRIPTION:
CEDAR CREEK 30.0
END DESCRIPTION:
XS GIS Cut Line= 3
      2788925.03      7083325.01      2788325.00      7083225.00
      2787725.02      7082925.01
#Sta/Elev= 30
  4380.5  535.06  4421.1  533.95  4492.0  533.70  4552.9  531.04  4583.3  531.76
  4644.1  530.76  4717.6  531.04  4745.5  528.07  4791.5  527.45  4857.0  526.21
  4968.5  526.86  4978.7  524.29  4981.8  519.94  4982.6  519.14  4990.0  519.14
  4990.8  519.94  4997.2  522.12  5002.8  520.69  5011.2  526.08  5019.6  526.81
  5198.1  526.36  5271.1  526.41  5293.5  525.35  5301.9  522.65  5307.6  524.37
  5310.2  525.16  5332.6  525.79  5379.2  525.86  5419.3  527.45  5659.6  537.25
#Mann=6,-1,0
  4380.5    0.05       0  4981.8    0.03       0  4990.8    0.05       0
  5198.1    0.16       0  5307.6    0.12       0  5379.2    0.16       0
Bank Sta=4791.5,5419.3
Exp/Cntr=0.3,0.1

Type RM Length L Ch R = 1,32401,616,616,616
BEGIN DESCRIPTION:
CEDAR CREEK 29.0
END DESCRIPTION:
XS GIS Cut Line= 3
      2789174.98      7082925.00      2788225.00      7082725.00
      2787775.00      7082725.00
#Sta/Elev= 30
  4018.8  540.40  4029.0  537.78  4049.4  535.29  4069.9  534.41  4172.1  533.69
  4366.2  530.33  4476.7  529.87  4618.2  526.09  4764.8  525.05  4795.4  523.62
  4836.3  525.07  4897.6  524.42  4967.8  525.58  4979.4  525.78  4987.0  524.08
  4992.1  524.08  4995.0  518.75  4995.9  517.95  5003.4  517.95  5004.3  518.75
  5009.6  518.76  5019.6  525.21  5129.6  523.90  5149.6  525.39  5159.6  524.55
  5209.6  524.92  5227.6  526.09  5279.6  532.16  5343.2  535.91  5439.6  538.73
#Mann=5,-1,0
  4018.8    0.05       0  4967.8    0.12       0  4995.0    0.07       0
  5004.3    0.12       0  5343.2    0.05       0
Bank Sta=4618.2,5227.6
Exp/Cntr=0.3,0.1

Type RM Length L Ch R = 1,31785,286,286,286
BEGIN DESCRIPTION:
Mapping XS b0ed2c10
END DESCRIPTION:
XS GIS Cut Line= 6
      2789156.10      7082334.25      2788812.39      7082282.17
      2788676.97      7082193.63      2788057.18      7082172.79
      2787911.34      7082172.79      2787703.74      7082240.26
#Sta/Elev= 30
  3872.5  530.01  3974.8  529.78  4169.9  526.67  4244.6  527.24  4280.8  526.48
  4288.7  525.36  4320.6  524.95  4494.4  523.12  4604.0  523.59  4634.0  521.39
  4644.1  521.36  4674.1  523.24  4783.3  523.14  4799.8  524.24  4874.2  523.21
  4974.2  524.07  4994.3  517.69  4996.0  515.57  4996.9  514.77  5004.4  514.77
  5005.3  515.57  5014.3  518.75  5024.3  523.50  5034.3  524.28  5097.3  524.57
  5127.9  524.95  5234.7  527.24  5335.8  531.28  5355.7  531.30  5366.2  531.57
#Mann=6,-1,0
  3872.5    0.05       0  4799.8    0.12       0  4996.0    0.07       0
  5005.3    0.12       0  5097.3    0.05       0  5355.7    0.16       0
Bank Sta=4320.6,5127.9
Exp/Cntr=0.3,0.1

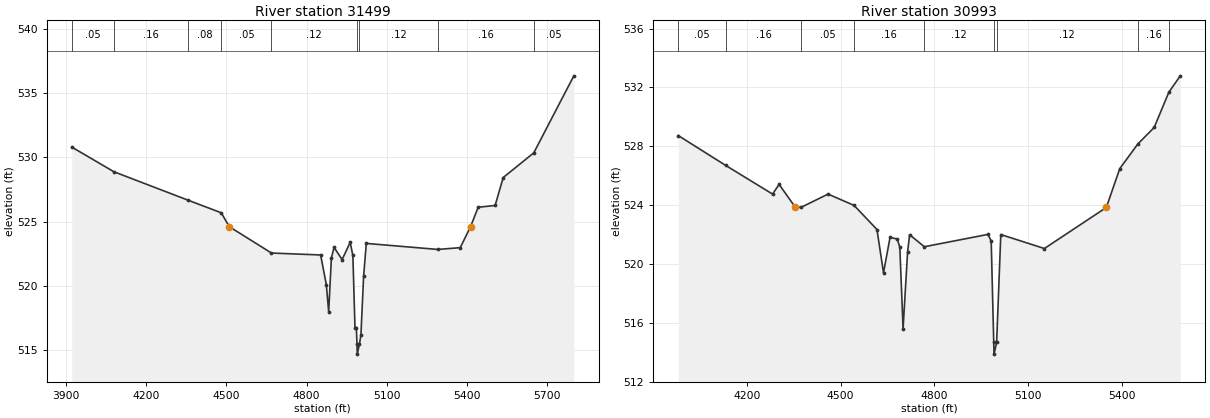
Type RM Length L Ch R = 1,31499,506,506,506
BEGIN DESCRIPTION:
Mapping XS 8b6594df
END DESCRIPTION:
XS GIS Cut Line= 5
      2789286.33      7082178.00      2788817.59      7082110.29
      2788687.39      7082079.04      2788234.26      7082026.96
      2787421.74      7081943.62
#Sta/Elev= 30
  3920.6  530.79  4078.5  528.87  4356.1  526.66  4480.4  525.68  4510.5  524.60
  4668.6  522.55  4852.6  522.40  4873.9  520.10  4882.8  517.99  4892.9  522.15
  4902.9  522.99  4933.1  522.04  4963.3  523.38  4973.4  522.36  4981.3  516.76
  4986.4  516.76  4988.9  515.49  4989.8  514.69  4998.2  515.49  5003.6  516.20
  5013.6  520.74  5023.7  523.30  5291.6  522.83  5375.5  522.97  5414.2  524.60
  5442.7  526.11  5506.2  526.25  5536.4  528.42  5650.9  530.34  5801.0  536.33
#Mann=9,-1,0
  3920.6    0.05       0  4078.5    0.16       0  4356.1    0.08       0
  4480.4    0.05       0  4668.6    0.12       0  4988.9    0.07       0
  4998.2    0.12       0  5291.6    0.16       0  5650.9    0.05       0
Bank Sta=4510.5,5414.2
Exp/Cntr=0.3,0.1

Type RM Length L Ch R = 1,30993,970,970,970
BEGIN DESCRIPTION:
Mapping XS 7882b717
END DESCRIPTION:
XS GIS Cut Line= 3
      2789104.01      7081980.07      2788130.09      7081688.42
      2787541.58      7081657.17
#Sta/Elev= 30
  3980.4  528.73  4132.2  526.70  4282.1  524.75  4303.0  525.41  4355.4  523.84
  4374.4  523.86  4459.6  524.75  4543.0  523.98  4616.1  522.34  4637.0  519.40
  4657.9  521.80  4680.9  521.70  4689.2  521.14  4699.6  515.59  4714.0  520.80
  4720.5  521.99  4767.6  521.17  4971.1  522.01  4981.5  521.56  4989.6  514.67
  4990.5  513.87  4998.9  514.67  5012.2  522.00  5151.6  521.05  5349.8  523.84
  5392.7  526.48  5450.7  528.16  5502.9  529.28  5549.8  531.68  5586.4  532.79
#Mann=9,-1,0
  3980.4    0.05       0  4132.2    0.16       0  4374.4    0.05       0
  4543.0    0.16       0  4767.6    0.12       0  4989.6    0.07       0
  4998.9    0.12       0  5450.7    0.16       0  5549.8    0.05       0
Bank Sta=4355.4,5349.8
Exp/Cntr=0.3,0.1