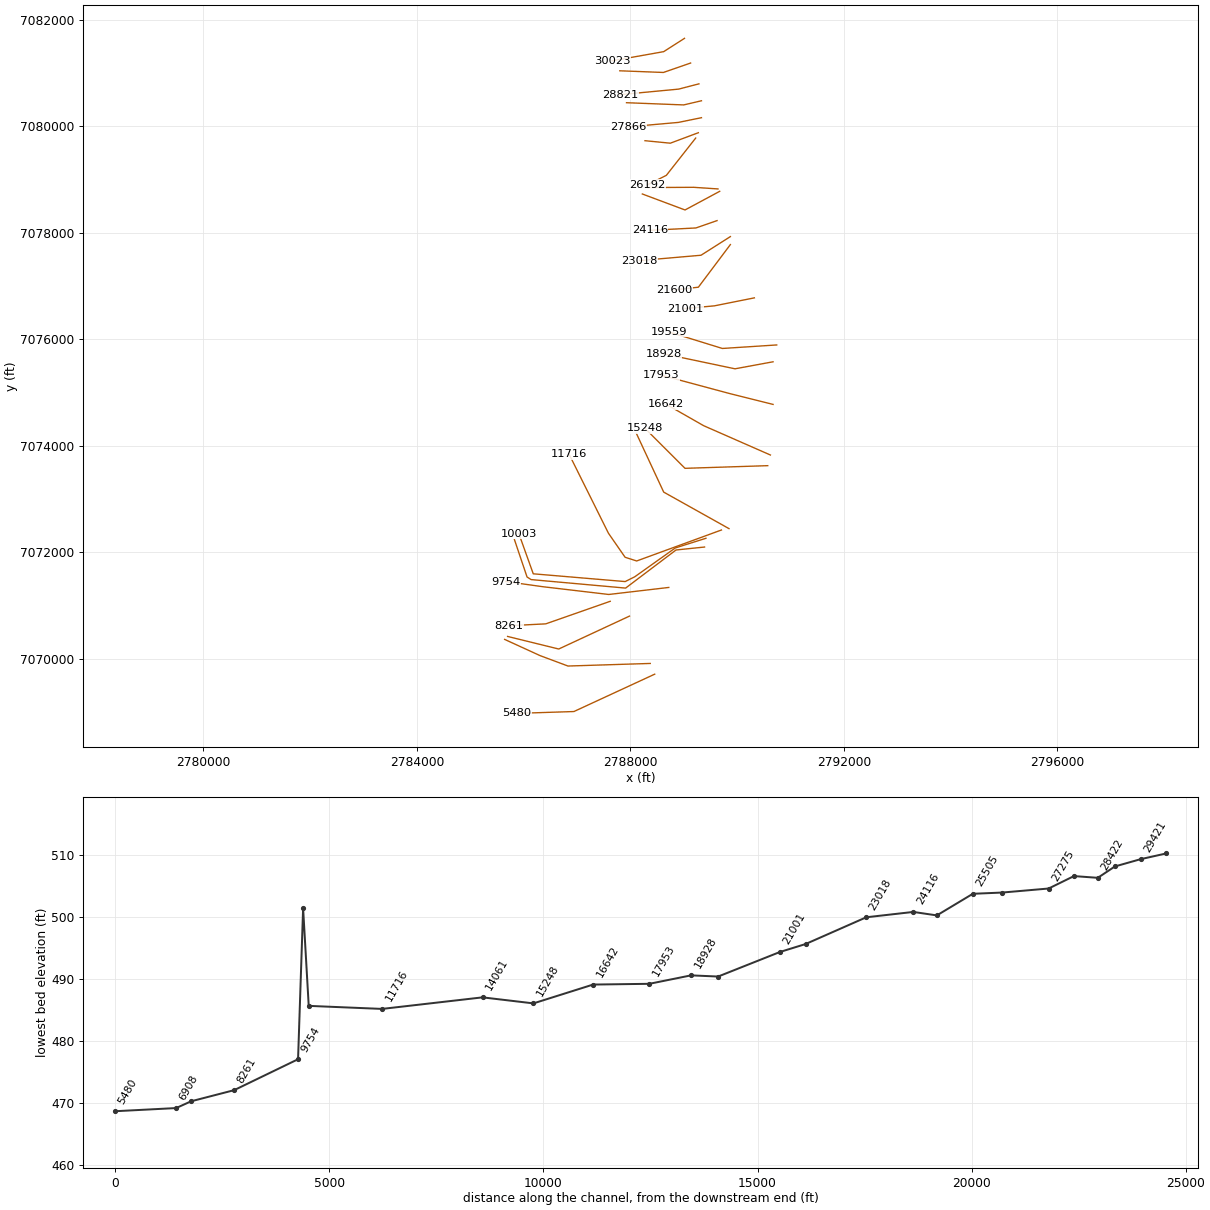
HEC-RAS study CEDAR CREEK.prj: CEDAR CREEK Base Level Engineering

--- CEDAR CREEK.g01 (geometry) --- (continued)

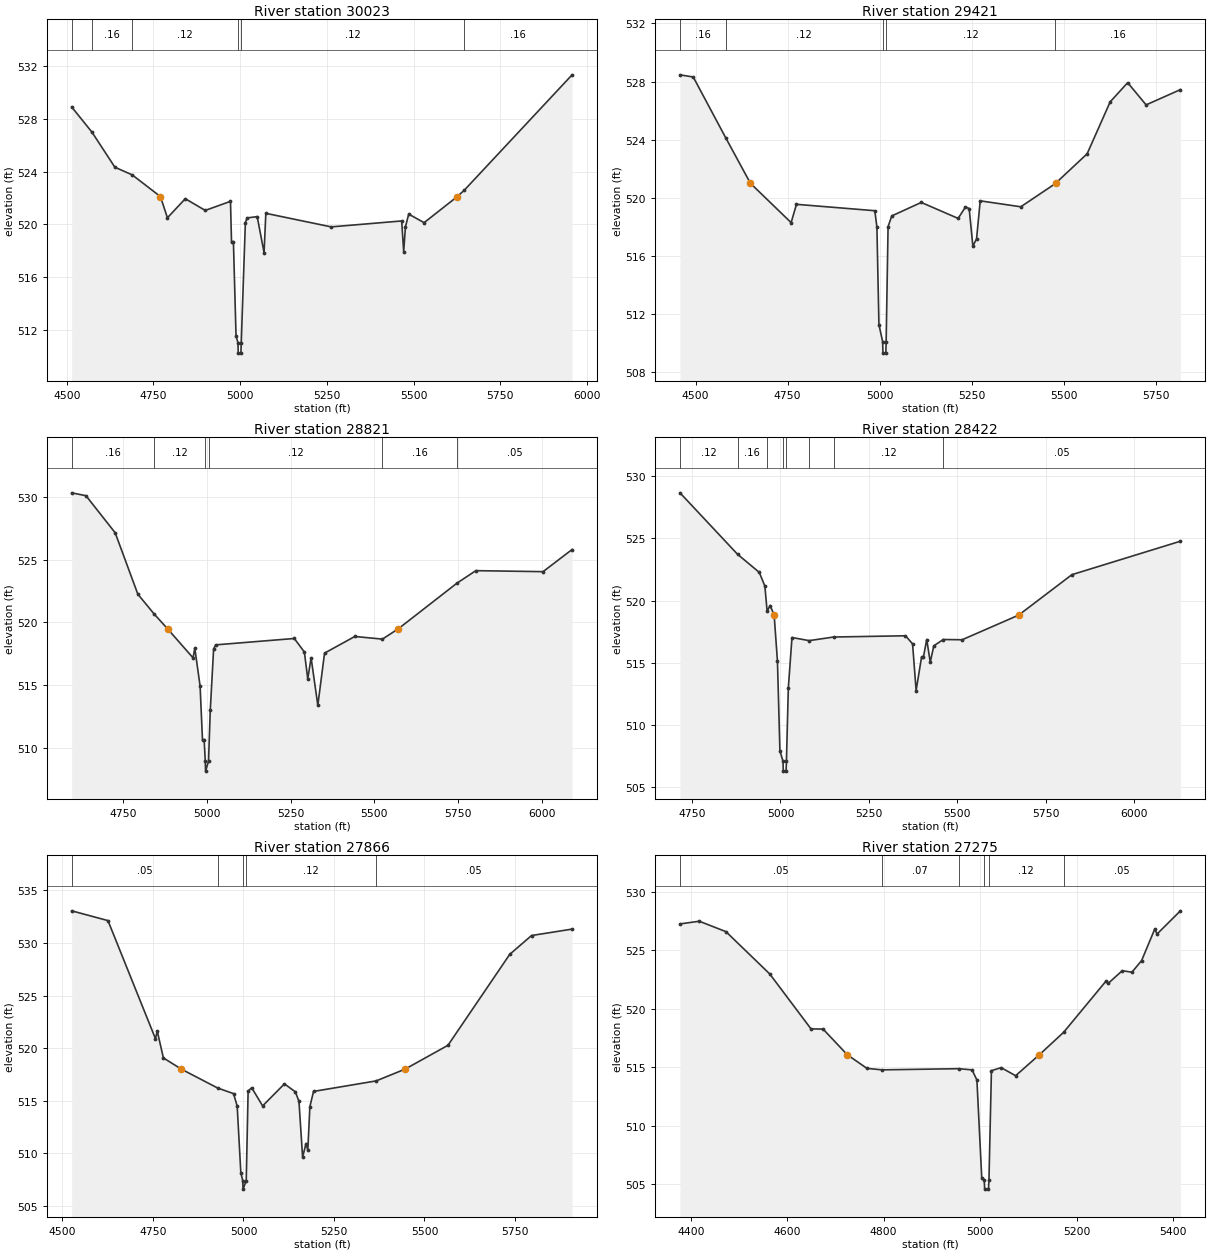
Type RM Length L Ch R = 1,30023,602,602,602
BEGIN DESCRIPTION:
Mapping XS 55a116d8
END DESCRIPTION:
XS GIS Cut Line= 3
      2789015.54      7081646.77      2788624.89      7081396.75
      2787661.30      7081224.87
#Sta/Elev= 30
  4514.4  528.92  4573.0  527.00  4639.0  524.34  4688.9  523.76  4770.3  522.11
  4790.4  520.50  4841.9  521.95  4899.4  521.06  4972.2  521.75  4975.2  518.63
  4980.7  518.63  4988.2  511.52  4993.7  511.02  4994.6  510.22  5002.3  510.22
  5003.2  511.02  5015.1  520.13  5020.2  520.49  5049.2  520.59  5069.0  517.85
  5074.1  520.84  5262.5  519.81  5465.7  520.26  5471.5  517.93  5476.6  519.82
  5486.0  520.78  5530.4  520.13  5625.9  522.11  5646.4  522.60  5957.0  531.36
#Mann=6,-1,0
  4514.4    0.05       0  4573.0    0.16       0  4688.9    0.12       0
  4993.7    0.07       0  5003.2    0.12       0  5646.4    0.16       0
Bank Sta=4770.3,5625.9
Exp/Cntr=0.3,0.1

Type RM Length L Ch R = 1,29421,600,600,600
BEGIN DESCRIPTION:
CEDAR CREEK 25.0
END DESCRIPTION:
XS GIS Cut Line= 3
      2789130.07      7081183.20      2788619.68      7081006.13
      2787802.01      7081037.37
#Sta/Elev= 30
  4457.8  528.46  4493.8  528.31  4581.8  524.13  4649.0  520.99  4759.5  518.28
  4774.0  519.54  4986.7  519.10  4992.4  517.98  4997.9  511.25  5007.9  510.09
  5008.9  509.29  5016.6  509.29  5017.5  510.09  5022.7  518.00  5032.7  518.74
  5112.8  519.67  5212.9  518.57  5232.9  519.36  5242.9  519.25  5252.9  516.66
  5262.9  517.16  5272.9  519.78  5383.0  519.37  5476.4  520.96  5477.5  520.99
  5563.1  523.02  5625.7  526.60  5673.2  527.92  5723.2  526.39  5816.3  527.44
#Mann=5,-1,0
  4457.8    0.16       0  4581.8    0.12       0  5007.9    0.07       0
  5017.5    0.12       0  5476.4    0.16       0
Bank Sta=4649,5477.5
Exp/Cntr=0.3,0.1

Type RM Length L Ch R = 1,28821,399,399,399
BEGIN DESCRIPTION:
Mapping XS a406a519
END DESCRIPTION:
XS GIS Cut Line= 3
      2789286.33      7080792.58      2788906.14      7080693.63
      2787808.62      7080589.60
#Sta/Elev= 30
  4596.1  530.36  4638.8  530.13  4726.0  527.17  4793.8  522.26  4842.1  520.69
  4882.7  519.49  4958.8  517.17  4964.0  517.95  4979.8  514.92  4987.0  510.58
  4992.0  510.58  4995.3  508.92  4996.2  508.12  5005.0  508.92  5010.2  512.98
  5020.2  517.88  5026.3  518.21  5261.3  518.72  5291.4  517.64  5301.5  515.49
  5311.5  517.18  5331.6  513.38  5351.7  517.55  5442.1  518.88  5524.6  518.67
  5571.9  519.49  5747.3  523.14  5803.7  524.14  6004.6  524.06  6091.4  525.83
#Mann=6,-1,0
  4596.1    0.16       0  4842.1    0.12       0  4995.3    0.07       0
  5005.0    0.12       0  5524.6    0.16       0  5747.3    0.05       0
Bank Sta=4882.7,5571.9
Exp/Cntr=0.3,0.1

Type RM Length L Ch R = 1,28422,556,556,556
BEGIN DESCRIPTION:
Mapping XS ba216c7b
END DESCRIPTION:
XS GIS Cut Line= 3
      2789333.22      7080474.88      2788999.89      7080396.75
      2787928.46      7080438.36
#Sta/Elev= 30
  4716.0  528.66  4878.8  523.72  4940.1  522.27  4956.0  521.16  4962.3  519.15
  4970.9  519.60  4982.2  518.83  4991.5  515.14  4998.5  507.92  5007.2  507.09
  5008.1  506.29  5015.9  506.29  5016.9  507.09  5022.3  512.99  5032.6  517.03
  5081.1  516.78  5150.6  517.07  5353.5  517.17  5373.5  516.52  5383.5  512.77
  5399.1  515.49  5404.2  515.46  5413.5  516.87  5423.5  515.05  5433.5  516.36
  5460.3  516.87  5513.6  516.85  5673.4  518.83  5823.8  522.08  6130.6  524.77
#Mann=8,-1,0
  4716.0    0.12       0  4878.8    0.16       0  4962.3    0.12       0
  5007.2    0.07       0  5016.9    0.12       0  5081.1    0.16       0
  5150.6    0.12       0  5460.3    0.05       0
Bank Sta=4982.2,5673.4
Exp/Cntr=0.3,0.1

Type RM Length L Ch R = 1,27866,591,591,591
BEGIN DESCRIPTION:
CEDAR CREEK 24.0
END DESCRIPTION:
XS GIS Cut Line= 3
      2789333.20      7080157.16      2788900.93      7080068.63
      2787963.47      7079985.30
#Sta/Elev= 30
  4525.4  533.06  4625.6  532.13  4756.8  520.89  4761.9  521.60  4778.7  519.06
  4828.4  517.99  4928.3  516.20  4972.6  515.66  4982.6  514.47  4992.7  508.12
  4997.9  507.37  4998.8  506.57  5007.6  507.37  5012.8  515.91  5022.8  516.22
  5052.9  514.49  5113.1  516.59  5143.3  515.83  5153.3  514.92  5163.3  509.61
  5172.7  510.91  5177.7  510.29  5183.4  514.42  5193.5  515.87  5366.3  516.87
  5446.3  517.99  5564.9  520.26  5735.6  528.92  5795.8  530.71  5907.8  531.32
#Mann=5,-1,0
  4525.4    0.05       0  4928.3    0.12       0  4997.9    0.07       0
  5007.6    0.12       0  5366.3    0.05       0
Bank Sta=4828.4,5446.3
Exp/Cntr=0.3,0.1

Type RM Length L Ch R = 1,27275,1083,1083,1083
BEGIN DESCRIPTION:
CEDAR CREEK 23.0
END DESCRIPTION:
XS GIS Cut Line= 3
      2789274.99      7079874.99      2788749.41      7079678.55
      2788274.97      7079725.00
#Sta/Elev= 30
  4377.6  527.25  4417.7  527.48  4472.9  526.59  4563.8  522.97  4649.4  518.27
  4674.3  518.26  4724.4  516.07  4765.2  514.90  4796.5  514.77  4955.4  514.87
  4983.3  514.77  4993.4  513.90  5003.4  505.54  5008.5  505.37  5009.5  504.57
  5017.4  504.57  5018.4  505.37  5023.5  514.70  5043.6  514.96  5073.7  514.27
  5123.1  516.07  5173.2  517.98  5260.5  522.33  5265.5  522.16  5294.8  523.25
  5314.9  523.12  5335.0  524.12  5362.1  526.80  5367.1  526.39  5415.4  528.37
#Mann=6,-1,0
  4377.6    0.05       0  4796.5    0.07       0  4955.4    0.12       0
  5008.5    0.07       0  5018.4    0.12       0  5173.2    0.05       0
Bank Sta=4724.4,5123.1
Exp/Cntr=0.3,0.1

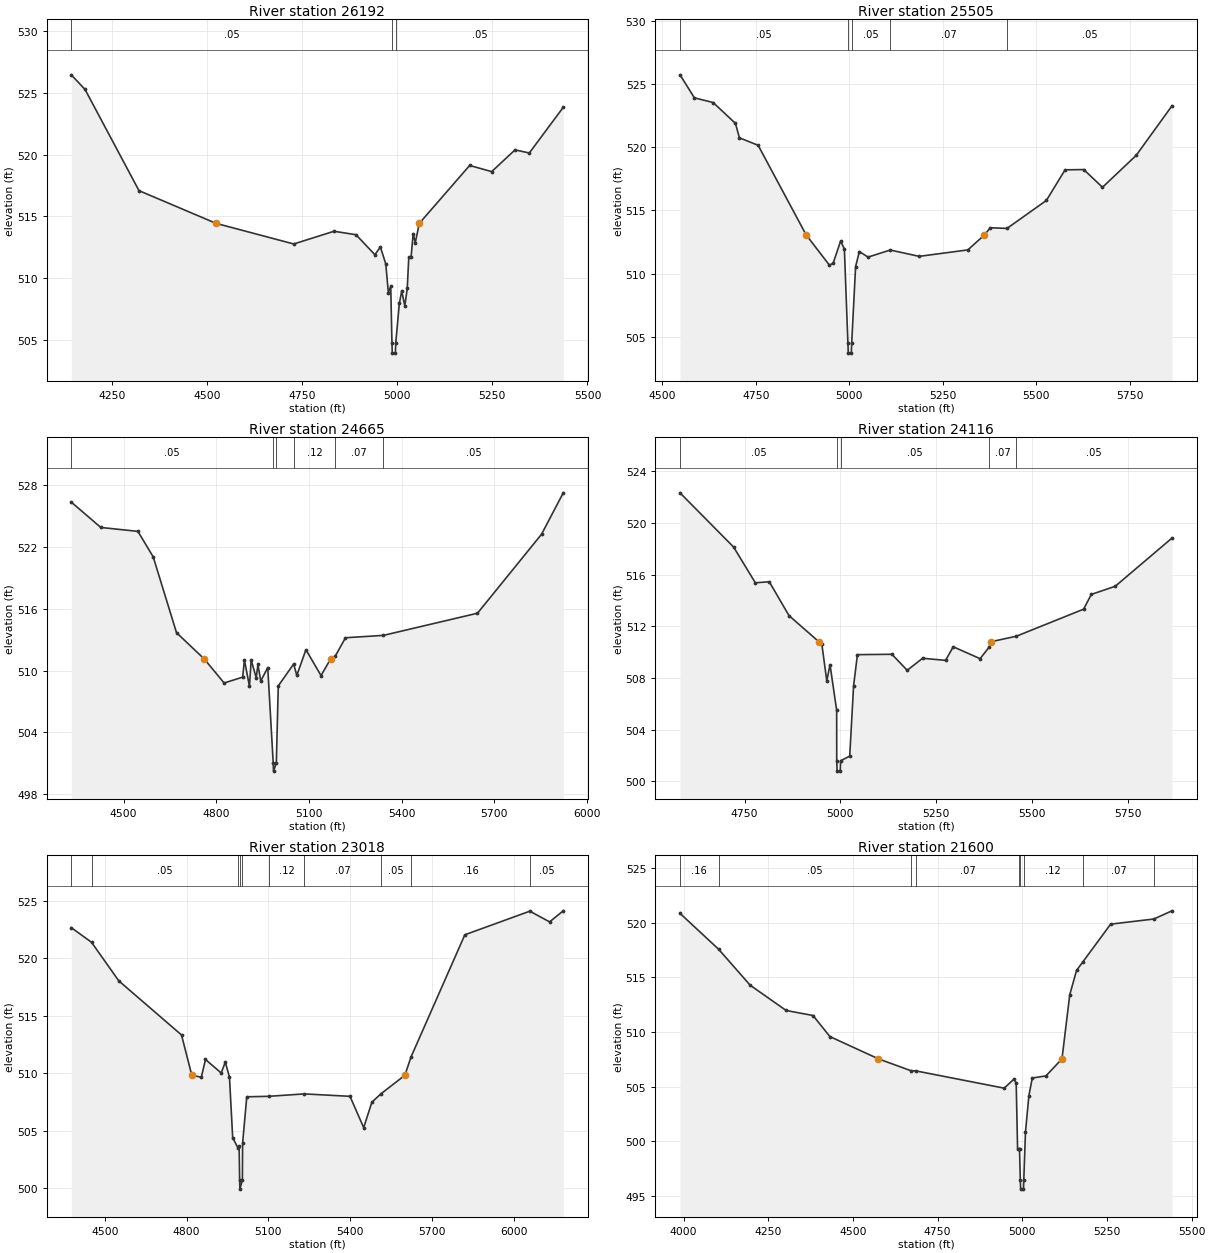
Type RM Length L Ch R = 1,26192,687,687,687
BEGIN DESCRIPTION:
CEDAR CREEK 22.0
END DESCRIPTION:
XS GIS Cut Line= 3
      2789224.98      7079774.98      2788675.00      7079075.00
      2788315.34      7078893.63
#Sta/Elev= 30
  4143.4  526.46  4179.5  525.28  4321.4  517.08  4523.9  514.43  4728.1  512.76
  4833.9  513.79  4891.7  513.51  4941.4  511.89  4955.8  512.52  4970.0  511.14
  4976.7  508.83  4983.0  509.32  4986.2  504.72  4987.1  503.92  4995.1  503.92
  4996.1  504.72  5005.6  507.94  5011.9  508.95  5020.0  507.75  5026.4  509.16
  5030.4  511.67  5036.4  511.67  5041.9  513.59  5047.5  512.87  5058.1  514.43
  5190.4  519.12  5248.3  518.62  5309.6  520.38  5347.2  520.13  5436.4  523.83
#Mann=3,-1,0
  4143.4    0.05       0  4986.2   0.035       0  4996.1    0.05       0
Bank Sta=4523.9,5058.1
Exp/Cntr=0.3,0.1

Type RM Length L Ch R = 1,25505,840,840,840
BEGIN DESCRIPTION:
CEDAR CREEK 21.0
END DESCRIPTION:
XS GIS Cut Line= 3
      2789643.49      7078819.84      2789187.73      7078850.22
      2788329.21      7078845.89
#Sta/Elev= 30
  4547.1  525.72  4585.7  523.90  4635.8  523.53  4695.4  521.88  4705.9  520.74
  4756.0  520.15  4884.5  513.06  4946.5  510.68  4956.5  510.82  4976.5  512.58
  4986.6  511.95  4996.0  504.52  4997.0  503.72  5005.1  503.72  5006.1  504.52
  5016.6  510.56  5026.6  511.75  5049.8  511.31  5109.2  511.87  5186.6  511.37
  5316.6  511.88  5361.0  513.06  5376.6  513.63  5421.4  513.58  5526.6  515.79
  5576.6  518.21  5626.6  518.23  5676.6  516.83  5766.6  519.35  5862.4  523.27
#Mann=5,-1,0
  4547.1    0.05       0  4996.0    0.03       0  5006.1    0.05       0
  5109.2    0.07       0  5421.4    0.05       0
Bank Sta=4884.5,5361
Exp/Cntr=0.3,0.1

Type RM Length L Ch R = 1,24665,549,549,549
BEGIN DESCRIPTION:
CEDAR CREEK 20.0
END DESCRIPTION:
XS GIS Cut Line= 3
      2789674.97      7078774.98      2789025.00      7078425.00
      2788225.01      7078725.00
#Sta/Elev= 30
  4330.9  526.34  4426.6  523.88  4546.7  523.50  4596.1  521.03  4671.6  513.67
  4761.5  511.12  4825.7  508.79  4885.8  509.36  4891.4  511.02  4907.7  508.48
  4913.3  511.02  4929.6  509.29  4935.2  510.59  4944.2  508.98  4966.9  510.29
  4984.6  501.04  4985.6  500.24  4994.7  501.04  5001.0  508.51  5050.7  510.63
  5061.0  509.53  5090.5  512.02  5139.4  509.51  5170.3  511.12  5185.3  511.39
  5218.6  513.18  5341.2  513.41  5645.8  515.56  5853.2  523.22  5923.5  527.24
#Mann=6,-1,0
  4330.9    0.05       0  4984.6    0.03       0  4994.7    0.05       0
  5050.7    0.12       0  5185.3    0.07       0  5341.2    0.05       0
Bank Sta=4761.5,5170.3
Exp/Cntr=0.3,0.1

Type RM Length L Ch R = 1,24116,1098,1098,1098
BEGIN DESCRIPTION:
CEDAR CREEK 19.0
END DESCRIPTION:
XS GIS Cut Line= 3
      2789625.03      7078225.01      2789229.40      7078087.31
      2788364.48      7078042.13
#Sta/Elev= 30
  4581.1  522.33  4721.0  518.14  4777.9  515.37  4814.3  515.45  4865.9  512.83
  4944.2  510.80  4951.7  510.60  4964.5  507.78  4972.9  509.04  4990.3  505.51
  4990.5  501.60  4991.5  500.80  4999.6  500.80  5000.6  501.60  5024.4  501.96
  5034.5  507.40  5044.5  509.81  5134.6  509.84  5174.6  508.60  5214.7  509.53
  5274.8  509.37  5294.8  510.42  5364.9  509.50  5388.5  510.39  5393.4  510.81
  5459.9  511.24  5635.3  513.33  5655.3  514.47  5717.8  515.10  5866.1  518.83
#Mann=5,-1,0
  4581.1    0.05       0  4990.5    0.03       0  5000.6    0.05       0
  5388.5    0.07       0  5459.9    0.05       0
Bank Sta=4944.2,5393.4
Exp/Cntr=0.3,0.1

Type RM Length L Ch R = 1,23018,1418,1418,1418
BEGIN DESCRIPTION:
CEDAR CREEK 18.0
END DESCRIPTION:
XS GIS Cut Line= 3
      2789874.98      7077924.99      2789325.00      7077575.00
      2788175.04      7077475.00
#Sta/Elev= 30
  4376.4  522.65  4450.8  521.38  4550.8  518.03  4781.1  513.33  4818.9  509.83
  4853.9  509.66  4869.1  511.20  4926.7  510.03  4941.9  510.97  4957.2  509.67
  4969.0  504.41  4989.0  503.49  4992.7  503.66  4994.5  500.74  4995.4  499.94
  5004.6  500.74  5005.4  503.91  5020.7  507.96  5100.8  508.00  5232.2  508.21
  5399.7  508.00  5449.9  505.28  5480.0  507.49  5513.3  508.22  5601.3  509.83
  5623.4  511.40  5821.3  522.03  6059.9  524.08  6132.5  523.15  6182.6  524.11
#Mann=10,-1,0
  4376.4    0.16       0  4450.8    0.05       0  4989.0    0.07       0
  4994.5    0.07       0  5004.6    0.07       0  5100.8    0.12       0
  5232.2    0.07       0  5513.3    0.05       0  5623.4    0.16       0
  6059.9    0.05       0
Bank Sta=4818.9,5601.3
Exp/Cntr=0.3,0.1

Type RM Length L Ch R = 1,21600,599,599,599
BEGIN DESCRIPTION:
CEDAR CREEK 17.0
END DESCRIPTION:
XS GIS Cut Line= 3
      2789874.98      7077774.98      2789275.00      7076975.00
      2788825.04      7076925.00
#Sta/Elev= 30
  3989.2  520.87  4103.4  517.58  4196.5  514.29  4302.7  511.98  4381.9  511.52
  4431.9  509.59  4575.3  507.55  4671.0  506.47  4687.4  506.44  4946.5  504.87
  4975.6  505.71  4981.9  505.33  4986.0  499.31  4990.4  499.31  4991.7  499.31
  4994.1  496.43  4995.1  495.63  5003.4  495.63  5004.3  496.43  5009.3  500.86
  5019.4  504.19  5029.4  505.80  5069.7  505.99  5117.1  507.55  5140.1  513.43
  5160.2  515.65  5178.8  516.43  5260.8  519.88  5388.1  520.35  5441.9  521.10
#Mann=9,-1,0
  3989.2    0.16       0  4103.4    0.05       0  4671.0    0.12       0
  4687.4    0.07       0  4990.4    0.12       0  4994.1    0.07       0
  5004.3    0.12       0  5178.8    0.07       0  5388.1    0.05       0
Bank Sta=4575.3,5117.1
Exp/Cntr=0.3,0.1

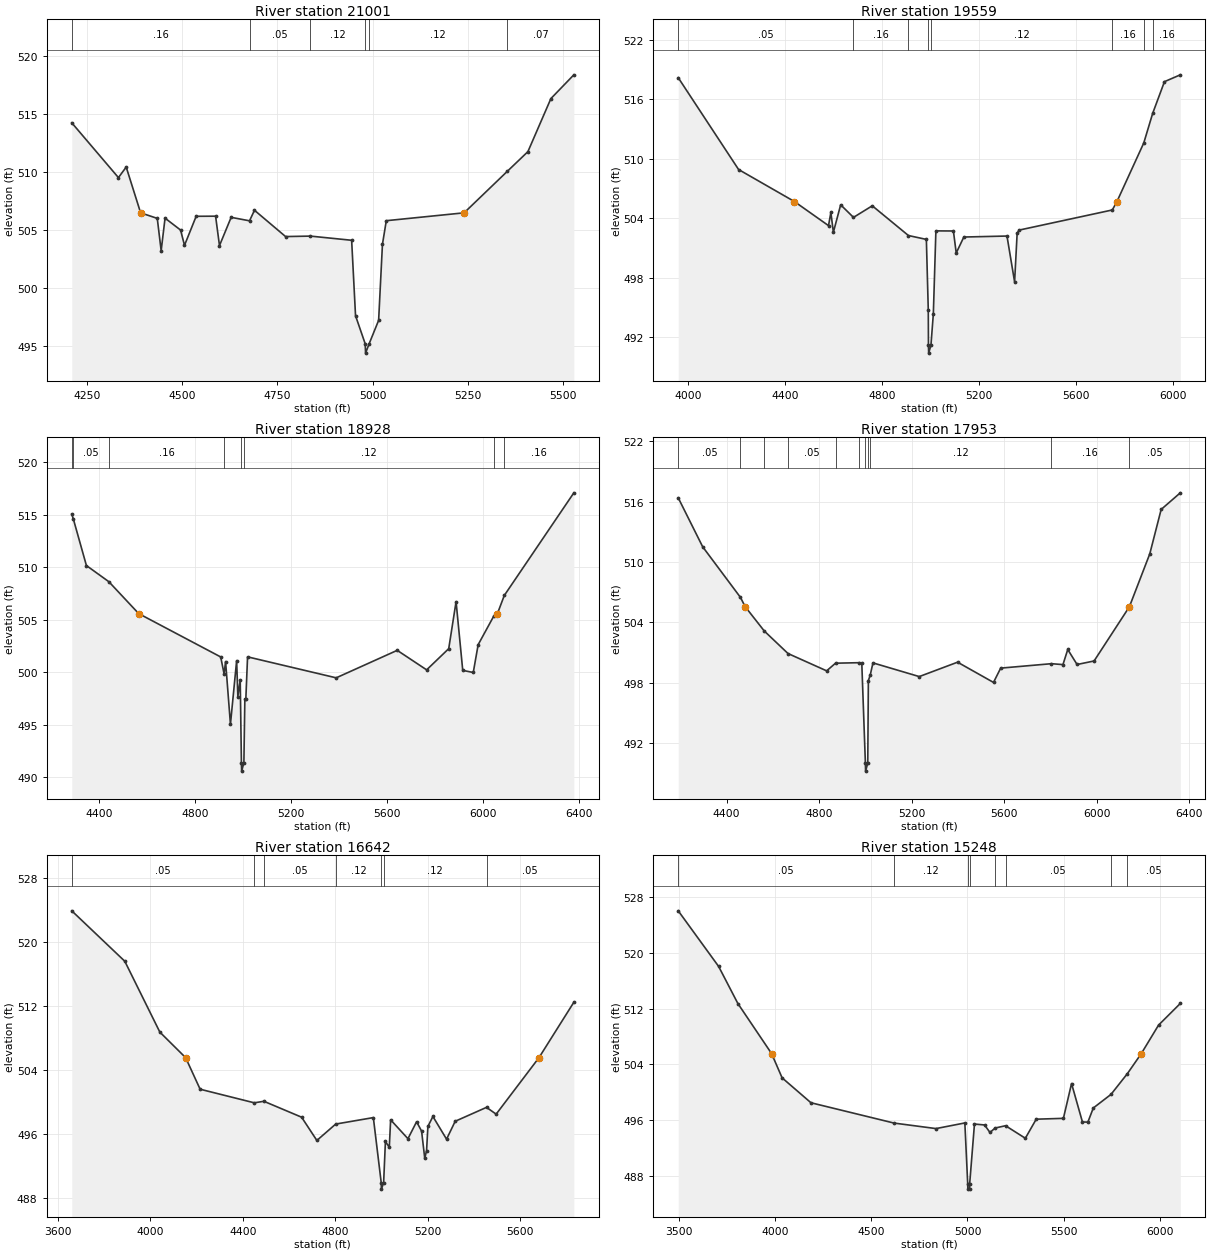
Type RM Length L Ch R = 1,21001,1442,1442,1442
BEGIN DESCRIPTION:
CEDAR CREEK 16.0
END DESCRIPTION:
XS GIS Cut Line= 3
      2790324.98      7076775.00      2789575.00      7076625.00
      2789025.00      7076575.00
#Sta/Elev= 30
  4210.8  514.23  4333.2  509.50  4353.6  510.41  4391.4  506.46  4435.1  505.98
  4445.3  503.19  4455.5  506.00  4496.3  504.97  4506.5  503.65  4537.1  506.16
  4588.1  506.17  4598.3  503.63  4628.9  506.07  4677.1  505.77  4690.1  506.68
  4771.7  504.41  4836.9  504.45  4945.0  504.09  4955.2  497.58  4980.6  495.15
  4981.5  494.35  4990.8  495.15  5015.8  497.18  5025.8  503.74  5035.9  505.78
  5240.1  506.46  5353.0  510.03  5407.4  511.74  5467.7  516.32  5527.9  518.37
#Mann=6,-1,0
  4210.8    0.16       0  4677.1    0.05       0  4836.9    0.12       0
  4980.6    0.07       0  4990.8    0.12       0  5353.0    0.07       0
Bank Sta=4391.4,5240.1
Exp/Cntr=0.3,0.1

Type RM Length L Ch R = 1,19559,631,631,631
BEGIN DESCRIPTION:
CEDAR CREEK 15.0
END DESCRIPTION:
XS GIS Cut Line= 3
      2790743.28      7075891.02      2789725.00      7075825.00
      2788722.49      7076135.80
#Sta/Elev= 30
  3960.4  518.18  4209.2  508.92  4439.4  505.69  4580.0  503.26  4589.7  504.59
  4600.0  502.59  4630.1  505.36  4682.9  504.09  4760.4  505.26  4909.5  502.26
  4983.4  501.87  4991.3  494.75  4992.0  491.20  4992.9  490.40  5002.3  491.20
  5012.2  494.37  5022.7  502.73  5094.9  502.72  5106.5  500.50  5137.9  502.11
  5315.8  502.21  5347.2  497.59  5357.7  502.50  5366.1  502.81  5750.1  504.84
  5769.2  505.69  5879.8  511.60  5916.4  514.58  5965.0  517.78  6030.4  518.47
#Mann=8,-1,0
  3960.4    0.05       0  4682.9    0.16       0  4909.5    0.12       0
  4992.0    0.07       0  5002.3    0.12       0  5750.1    0.16       0
  5879.8    0.12       0  5916.4    0.16       0
Bank Sta=4439.4,5769.2
Exp/Cntr=0.3,0.1

Type RM Length L Ch R = 1,18928,975,975,975
BEGIN DESCRIPTION:
CEDAR CREEK 14.0
END DESCRIPTION:
XS GIS Cut Line= 3
      2790675.01      7075575.00      2789962.04      7075443.11
      2788625.00      7075725.00
#Sta/Elev= 30
  4286.4  515.07  4292.9  514.62  4347.4  510.18  4440.9  508.64  4565.3  505.60
  4906.8  501.47  4921.0  499.85  4927.1  501.03  4947.4  495.06  4973.2  501.12
  4978.3  497.70  4988.1  499.28  4993.1  491.39  4994.1  490.59  5003.4  491.39
  5007.4  497.46  5011.5  497.46  5018.7  501.48  5387.9  499.48  5642.1  502.10
  5764.7  500.24  5856.7  502.26  5887.3  506.74  5915.1  500.19  5958.9  499.99
  5979.3  502.64  6044.0  505.35  6059.6  505.60  6088.2  507.33  6377.9  517.11
#Mann=8,-1,0
  4286.4    0.16       0  4292.9    0.05       0  4440.9    0.16       0
  4921.0    0.12       0  4993.1    0.07       0  5003.4    0.12       0
  6044.0    0.05       0  6088.2    0.16       0
Bank Sta=4565.3,6059.6
Exp/Cntr=0.3,0.1

Type RM Length L Ch R = 1,17953,1311,1311,1311
BEGIN DESCRIPTION:
CEDAR CREEK 13.0
END DESCRIPTION:
XS GIS Cut Line= 3
      2790675.02      7074774.99      2789875.00      7074975.00
      2788575.03      7075324.99
#Sta/Elev= 30
  4191.0  516.37  4296.7  511.51  4460.2  506.48  4480.2  505.57  4562.9  503.15
  4665.6  500.91  4832.7  499.19  4871.1  499.95  4973.8  500.00  4984.7  499.94
  5000.2  490.03  5001.1  489.23  5010.5  490.03  5013.1  498.22  5021.1  498.77
  5033.0  499.98  5233.1  498.62  5398.8  500.05  5554.2  498.04  5585.2  499.46
  5804.6  499.90  5854.5  499.81  5875.2  501.31  5915.5  499.82  5989.1  500.17
  6139.3  505.47  6142.0  505.57  6229.9  510.81  6279.1  515.22  6361.9  516.87
#Mann=11,-1,0
  4191.0    0.05       0  4460.2    0.12       0  4562.9    0.07       0
  4665.6    0.05       0  4871.1    0.07       0  4973.8    0.05       0
  5000.2    0.03       0  5010.5    0.05       0  5021.1    0.12       0
  5804.6    0.16       0  6139.3    0.05       0
Bank Sta=4480.2,6142
Exp/Cntr=0.3,0.1

Type RM Length L Ch R = 1,16642,1394,1394,1394
BEGIN DESCRIPTION:
CEDAR CREEK 11.0
END DESCRIPTION:
XS GIS Cut Line= 3
      2790624.97      7073825.01      2789375.00      7074375.00
      2788675.04      7074774.98
#Sta/Elev= 30
  3659.5  523.93  3888.9  517.62  4040.4  508.76  4152.0  505.56  4214.7  501.61
  4448.9  499.91  4490.6  500.10  4653.7  498.11  4719.7  495.20  4801.2  497.25
  4964.0  498.06  4998.1  489.91  4999.0  489.11  5008.5  489.91  5016.2  495.07
  5033.0  494.35  5038.8  497.78  5113.7  495.42  5151.1  497.54  5172.7  496.37
  5186.4  492.96  5194.3  493.94  5200.0  496.95  5221.6  498.20  5280.7  495.36
  5318.1  497.60  5453.5  499.34  5495.2  498.49  5680.5  505.56  5831.3  512.49
#Mann=7,-1,0
  3659.5    0.05       0  4448.9    0.07       0  4490.6    0.05       0
  4801.2    0.12       0  4998.1    0.07       0  5008.5    0.12       0
  5453.5    0.05       0
Bank Sta=4152,5680.5
Exp/Cntr=0.3,0.1

Type RM Length L Ch R = 1,15248,1187,1187,1187
BEGIN DESCRIPTION:
CEDAR CREEK 9.0
END DESCRIPTION:
XS GIS Cut Line= 3
      2790575.03      7073625.00      2789025.00      7073575.00
      2788275.00      7074325.00
#Sta/Elev= 30
  3495.6  526.07  3705.7  518.08  3805.8  512.75  3981.1  505.56  4035.9  502.07
  4186.0  498.49  4618.5  495.57  4836.3  494.78  4986.4  495.59  5001.2  486.88
  5002.1  486.08  5010.8  486.08  5011.6  486.88  5036.4  495.43  5088.9  495.30
  5117.1  494.22  5143.8  494.86  5198.1  495.19  5301.0  493.39  5357.6  496.13
  5499.0  496.25  5541.4  501.25  5598.0  495.73  5626.3  495.71  5654.6  497.74
  5746.5  499.69  5832.0  502.68  5904.3  505.56  5994.0  509.65  6107.1  512.76
#Mann=8,-1,0
  3495.6    0.05       0  4618.5    0.12       0  5001.2    0.07       0
  5011.6    0.12       0  5143.8    0.07       0  5198.1    0.05       0
  5746.5    0.16       0  5832.0    0.05       0
Bank Sta=3981.1,5904.3
Exp/Cntr=0.3,0.1

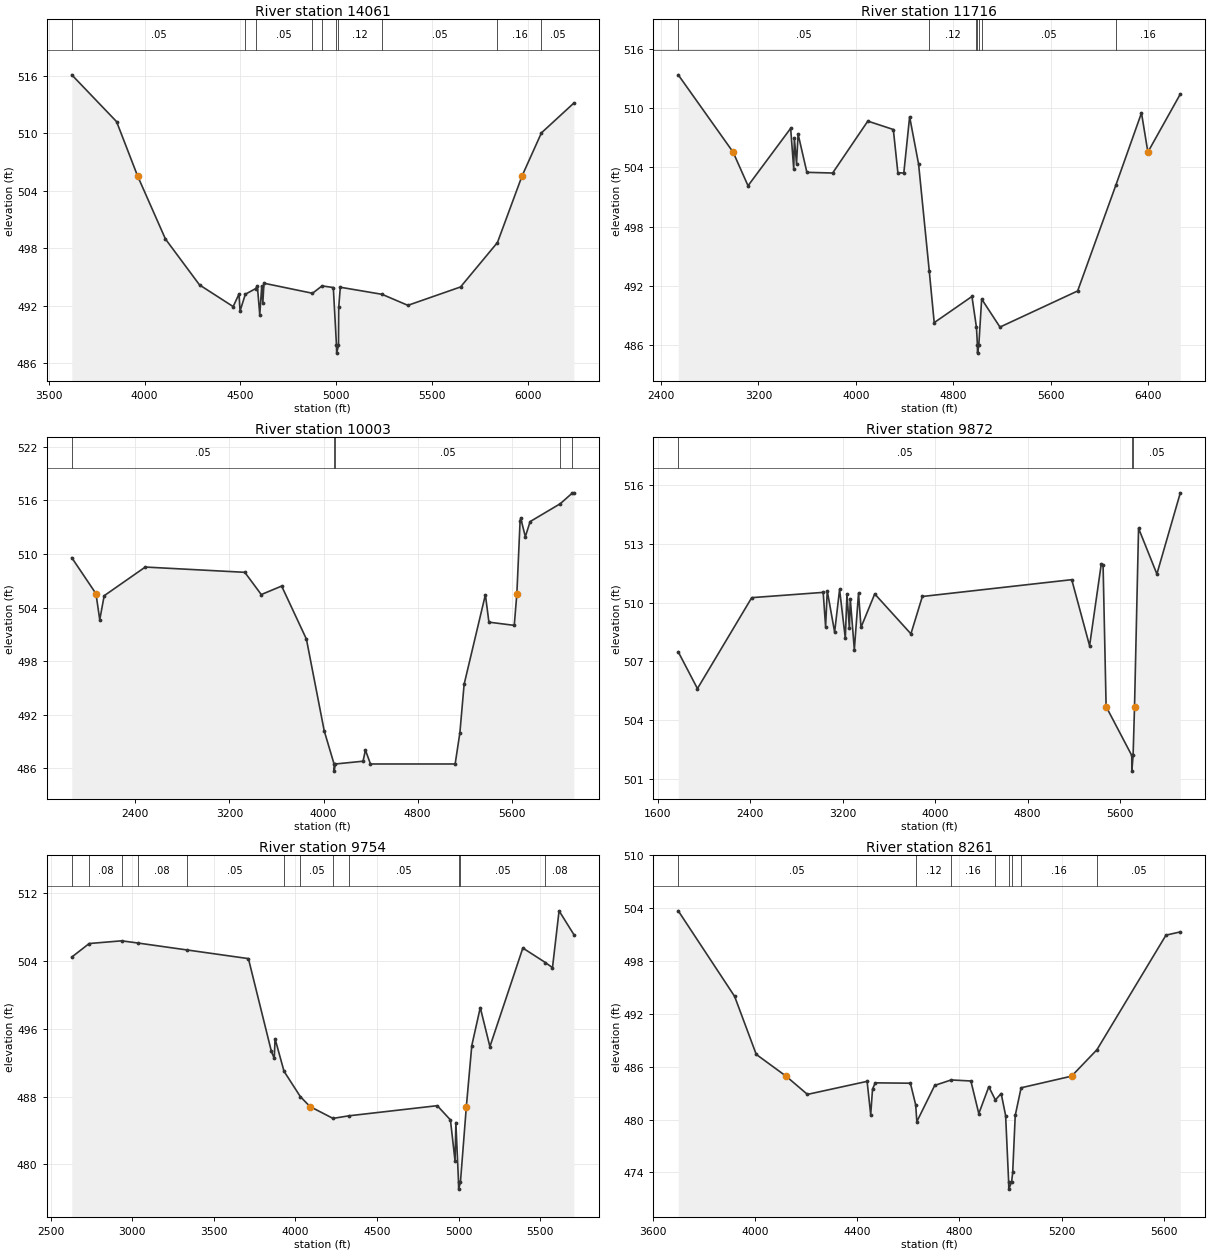
Type RM Length L Ch R = 1,14061,2345,2345,2345
BEGIN DESCRIPTION:
Mapping XS 13e94087
END DESCRIPTION:
XS GIS Cut Line= 3
      2789849.18      7072443.11      2788625.23      7073128.87
      2788113.40      7074230.62
#Sta/Elev= 30
  3620.5  516.11  3854.2  511.22  3963.5  505.56  4108.8  498.97  4286.8  494.17
  4462.1  491.91  4492.3  493.22  4498.0  491.45  4525.5  493.20  4578.5  493.78
  4588.2  494.06  4600.7  491.06  4611.0  494.06  4616.7  492.28  4622.5  494.35
  4875.5  493.30  4925.6  494.07  4984.2  493.90  5000.7  487.85  5001.6  487.05
  5011.2  487.85  5012.3  491.83  5020.7  493.93  5238.4  493.19  5372.9  492.04
  5647.6  493.96  5840.0  498.60  5968.4  505.56  6069.3  510.05  6238.3  513.16
#Mann=10,-1,0
  3620.5    0.05       0  4525.5    0.07       0  4578.5    0.05       0
  4875.5    0.07       0  4925.6    0.12       0  5000.7    0.07       0
  5011.2    0.12       0  5238.4    0.05       0  5840.0    0.16       0
  6069.3    0.05       0
Bank Sta=3963.5,5968.4
Exp/Cntr=0.3,0.1

Type RM Length L Ch R = 1,11716,1713,1713,1713
BEGIN DESCRIPTION:
Mapping XS e589b0b9
END DESCRIPTION:
XS GIS Cut Line= 5
      2789707.72      7072417.48      2788119.23      7071835.94
      2787902.22      7071905.39      2787589.72      7072356.78
      2786852.14      7073840.61
#Sta/Elev= 30
  2540.9  513.39  2991.6  505.56  3114.4  502.15  3464.7  507.97  3489.9  503.84
  3495.2  506.94  3512.9  504.40  3525.7  507.39  3598.1  503.51  3809.6  503.44
  4098.6  508.70  4308.3  507.85  4345.7  503.47  4394.4  503.44  4442.2  509.14
  4515.8  504.35  4603.3  493.54  4644.2  488.28  4954.3  490.93  4991.4  487.79
  4999.3  485.99  5000.0  485.19  5010.6  485.99  5034.1  490.67  5184.5  487.83
  5822.8  491.49  6136.2  502.19  6347.4  509.53  6399.9  505.56  6666.4  511.44
#Mann=7,-1,0
  2540.9    0.05       0  4603.3    0.12       0  4991.4    0.16       0
  4999.3    0.07       0  5010.6    0.16       0  5034.1    0.05       0
  6136.2    0.16       0
Bank Sta=2991.6,6399.9
Exp/Cntr=0.3,0.1

Type RM Length L Ch R = 1,10003,131,131,131
BEGIN DESCRIPTION:
Mapping XS f368a3ee
END DESCRIPTION:
XS GIS Cut Line= 6
      2789416.86      7072261.67      2788843.19      7072080.45
      2788083.57      7071539.46      2787903.01      7071449.18
      2786180.79      7071595.02      2785910.33      7072350.96
#Sta/Elev= 30
  1859.7  509.58  2065.4  505.55  2097.6  502.63  2135.2  505.32  2484.6  508.53
  3330.7  507.94  3470.6  505.45  3643.9  506.40  3854.5  500.46  4005.8  490.19
  4089.5  486.48  4090.1  485.68  4101.0  486.48  4335.9  486.79  4356.0  488.04
  4399.0  486.48  5118.8  486.48  5159.0  489.96  5195.1  495.40  5375.9  505.43
  5405.9  502.36  5621.3  502.00  5643.5  505.55  5671.0  513.71  5676.4  513.98
  5715.5  511.93  5756.3  513.62  6012.2  515.62  6111.8  516.78  6127.9  516.84
#Mann=5,-1,0
  1859.7    0.05       0  4089.5    0.03       0  4101.0    0.05       0
  6012.2    0.08       0  6111.8    0.05       0
Bank Sta=2065.4,5643.5
Exp/Cntr=0.3,0.1

Type RM Length L Ch R = 1,9872,118,118,118
BEGIN DESCRIPTION:
Mapping XS 8656150c
END DESCRIPTION:
XS GIS Cut Line= 6
      2789390.88      7072097.62      2788856.14      7072042.06
      2787911.69      7071326.79      2786140.86      7071486.51
      2786064.47      7071535.12      2785828.35      7072236.54
#Sta/Elev= 30
  1777.6  507.49  1943.7  505.61  2413.2  510.26  3031.3  510.53  3052.2  508.77
  3066.5  510.61  3130.2  508.50  3173.2  510.68  3222.6  508.18  3236.9  510.44
  3257.8  508.70  3265.6  510.20  3300.7  507.60  3337.0  510.49  3358.4  508.74
  3477.1  510.45  3790.1  508.41  3889.0  510.32  5181.1  511.18  5335.4  507.80
  5436.7  511.99  5452.2  511.91  5478.4  504.69  5700.3  502.19  5700.9  501.39
  5711.8  502.19  5724.1  504.69  5758.9  513.81  5917.5  511.47  6120.1  515.62
#Mann=3,-1,0
  1777.6    0.05       0  5700.3    0.03       0  5711.8    0.05       0
Bank Sta=5478.4,5724.1
Exp/Cntr=0.3,0.1

Type RM Length L Ch R = 1,9754,1493,1493,1493
BEGIN DESCRIPTION:
Mapping XS 438fb8e5
END DESCRIPTION:
XS GIS Cut Line= 4
      2788720.75      7071338.94      2787595.72      7071206.99
      2786359.61      7071352.83      2785665.31      7071450.03
#Sta/Elev= 30
  2628.6  504.48  2735.5  506.08  2934.5  506.40  3033.9  506.14  3332.3  505.33
  3711.7  504.30  3852.7  493.34  3870.1  492.52  3875.1  494.84  3930.1  491.00
  4030.1  488.01  4089.1  486.84  4230.2  485.44  4330.2  485.75  4869.7  486.94
  4950.3  485.26  4978.7  480.42  4983.7  484.95  5000.1  477.89  5000.7  477.09
  5011.6  477.89  5048.0  486.84  5081.4  494.04  5133.4  498.52  5192.4  493.91
  5394.4  505.55  5532.3  503.84  5576.1  503.23  5616.5  509.94  5707.1  507.14
#Mann=12,-1,0
  2628.6    0.05       0  2735.5    0.08       0  2934.5    0.05       0
  3033.9    0.08       0  3332.3    0.05       0  3930.1    0.08       0
  4030.1    0.05       0  4230.2    0.08       0  4330.2    0.05       0
  5000.1    0.03       0  5011.6    0.05       0  5532.3    0.08       0
Bank Sta=4089.1,5048
Exp/Cntr=0.3,0.1

Type RM Length L Ch R = 1,8261,1004,1004,1004
BEGIN DESCRIPTION:
Mapping XS d41989f2
END DESCRIPTION:
XS GIS Cut Line= 3
      2787623.52      7071078.98      2786415.24      7070655.39
      2785728.90      7070620.72
#Sta/Elev= 30
  3697.9  503.69  3918.9  493.98  4003.6  487.40  4120.4  484.93  4204.2  482.86
  4438.1  484.34  4452.2  480.55  4459.3  483.46  4469.9  484.17  4607.7  484.13
  4628.4  481.68  4633.0  479.77  4703.0  483.88  4767.6  484.50  4844.8  484.38
  4875.8  480.68  4915.0  483.73  4940.7  482.23  4963.5  482.96  4980.9  480.46
  4992.8  472.91  4993.4  472.11  5004.3  472.91  5008.6  474.00  5018.6  480.48
  5041.6  483.61  5239.4  484.93  5338.8  487.93  5609.3  500.93  5665.5  501.30
#Mann=8,-1,0
  3697.9    0.05       0  4628.4    0.12       0  4767.6    0.16       0
  4940.7    0.12       0  4992.8    0.07       0  5004.3    0.12       0
  5041.6    0.16       0  5338.8    0.05       0
Bank Sta=4120.4,5239.4
Exp/Cntr=0.3,0.1

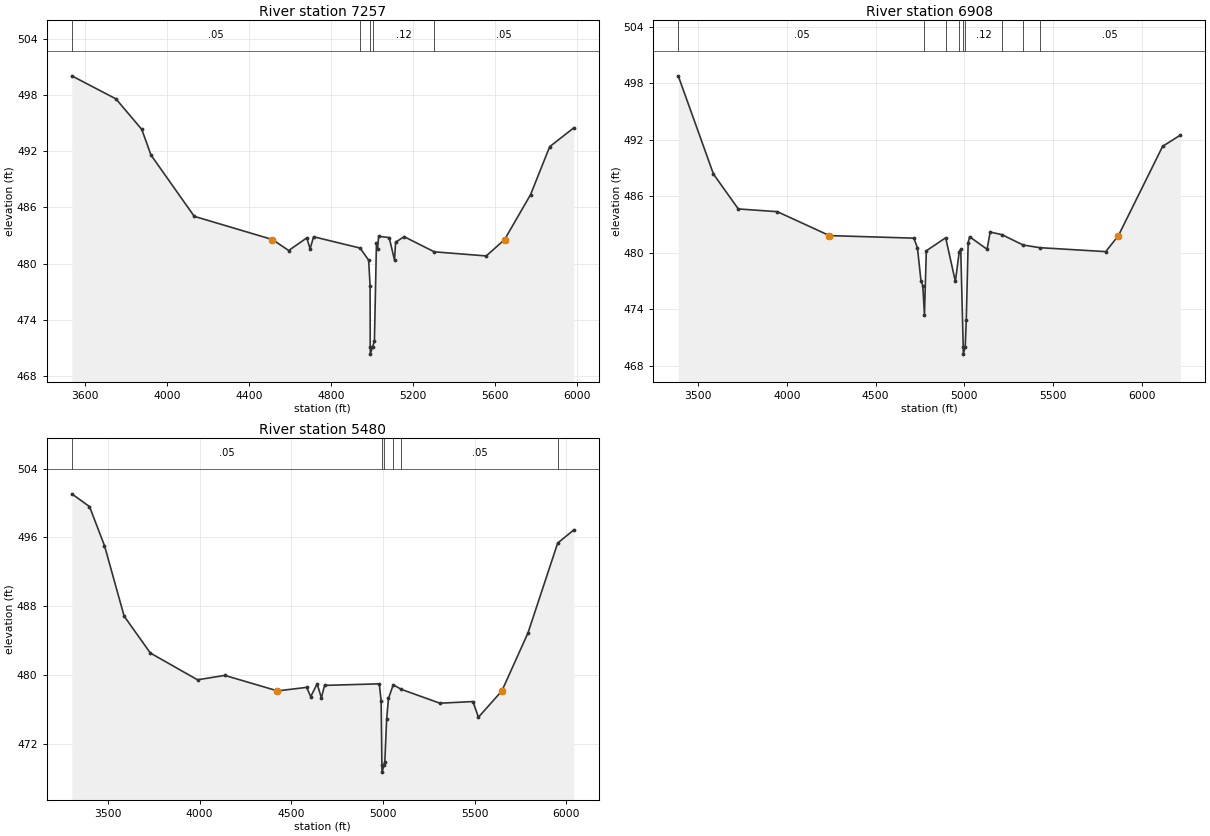
Type RM Length L Ch R = 1,7257,349,349,349
BEGIN DESCRIPTION:
Mapping XS c7d725f7
END DESCRIPTION:
XS GIS Cut Line= 3
      2787984.67      7070801.22      2786658.29      7070183.17
      2785699.96      7070419.28
#Sta/Elev= 30
  3534.5  500.05  3749.9  497.59  3876.1  494.33  3921.0  491.59  4132.3  485.04
  4513.8  482.56  4593.2  481.39  4681.5  482.74  4697.8  481.57  4714.6  482.86
  4941.6  481.65  4983.3  480.36  4990.4  477.64  4991.1  471.12  4991.8  470.32
  5002.6  471.12  5011.5  471.70  5021.5  482.20  5026.7  481.51  5032.1  482.91
  5083.6  482.77  5109.7  480.36  5114.8  482.27  5156.3  482.87  5303.6  481.25
  5557.3  480.81  5646.8  482.56  5773.6  487.36  5866.9  492.48  5984.8  494.50
#Mann=5,-1,0
  3534.5    0.05       0  4941.6    0.12       0  4991.1    0.07       0
  5002.6    0.12       0  5303.6    0.05       0
Bank Sta=4513.8,5646.8
Exp/Cntr=0.3,0.1

Type RM Length L Ch R = 1,6908,1428,1428,1428
BEGIN DESCRIPTION:
Mapping XS f1e6523c
END DESCRIPTION:
XS GIS Cut Line= 4
      2788373.60      7069912.33      2786831.90      7069863.72
      2786311.07      7070058.17      2785644.37      7070363.74
#Sta/Elev= 30
  3386.6  498.77  3585.3  488.34  3725.4  484.64  3945.5  484.35  4239.5  481.81
  4715.9  481.54  4735.9  480.49  4755.9  476.98  4765.9  476.50  4775.3  473.40
  4785.9  480.20  4895.0  481.58  4949.7  476.94  4971.5  480.10  4980.0  480.34
  4993.9  470.03  4994.6  469.23  5005.4  470.03  5011.2  472.85  5021.8  481.04
  5030.0  481.69  5128.6  480.36  5145.9  482.19  5212.5  481.91  5332.1  480.81
  5425.8  480.53  5797.8  480.11  5869.3  481.81  6118.8  491.29  6218.4  492.47
#Mann=9,-1,0
  3386.6    0.05       0  4775.3    0.12       0  4895.0    0.16       0
  4971.5    0.12       0  4993.9    0.07       0  5005.4    0.12       0
  5212.5    0.05       0  5332.1    0.07       0  5425.8    0.05       0
Bank Sta=4239.5,5869.3
Exp/Cntr=0.3,0.1

Type RM Length L Ch R = 1,5480,0,0,0
BEGIN DESCRIPTION:
CEDAR CREEK 1.0
END DESCRIPTION:
XS GIS Cut Line= 3
      2788456.90      7069710.94      2786943.01      7069009.56
      2785875.04      7068975.00
#Sta/Elev= 30
  3303.7  501.06  3400.3  499.58  3482.1  495.04  3589.1  486.85  3732.1  482.56
  3989.1  479.45  4138.2  479.96  4425.2  478.16  4584.2  478.57  4606.3  477.49
  4641.5  478.98  4664.4  477.35  4681.8  478.80  4980.2  478.98  4990.2  476.96
  4994.4  469.52  4994.9  468.72  5006.0  469.52  5010.2  469.90  5020.2  474.89
  5030.2  477.28  5056.2  478.87  5101.1  478.33  5310.4  476.73  5490.5  476.92
  5520.5  475.10  5648.3  478.16  5790.6  484.89  5952.6  495.34  6040.7  496.87
#Mann=6,-1,0
  3303.7    0.05       0  4994.4    0.03       0  5006.0    0.05       0
  5056.2    0.07       0  5101.1    0.05       0  5952.6     0.1       0
Bank Sta=4425.2,5648.3
Exp/Cntr=0.3,0.1

Chan Stop Cuts=-1