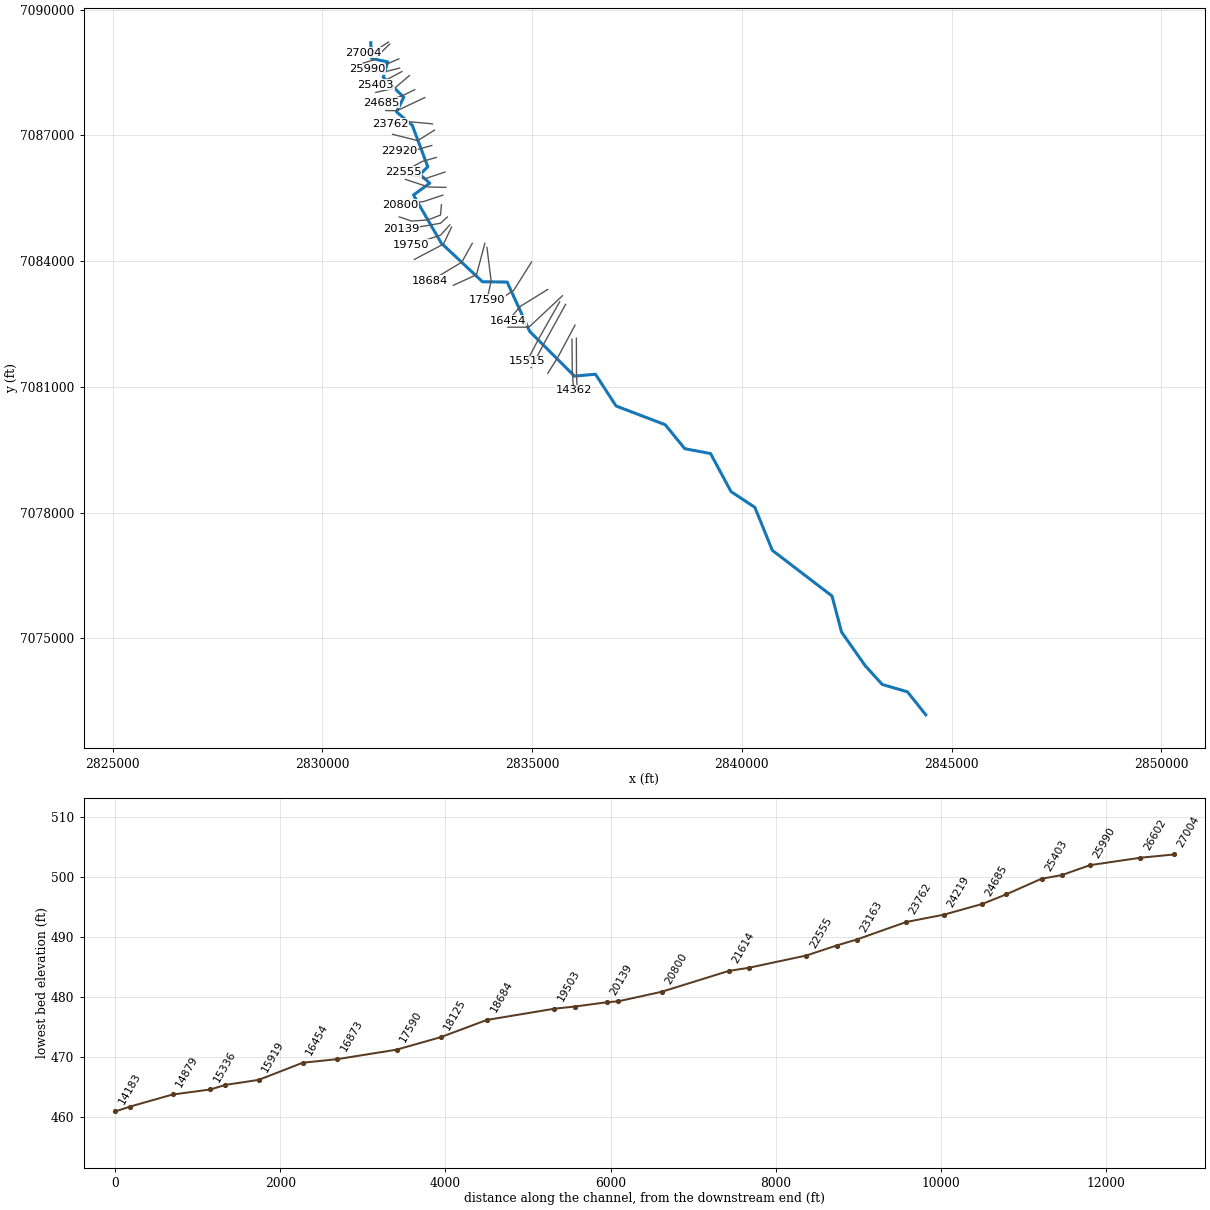
--- CHAFFIN CREEK.prj (project) ---

Proj Title=CHAFFIN CREEK Base Level Engineering
Current Plan=p01
Default Exp/Contr=0.3,0.1
English Units
Geom File=g01
Flow File=f01
Plan File=p01
BEGIN DESCRIPTION:
CHAFFIN CREEK
END DESCRIPTION:

--- CHAFFIN CREEK.p01 (plan) ---

Plan Title=Multiple Run
Short Identifier=Multiple
Geom File=g01
Flow File=f01
Subcritical Flow
K Sum by GR= 0
Std Step Tol= 0.01
Critical Tol= 0.01
Num of Std Step Trials= 20
Max Error Tol= 0.3
Flow Tol Ratio= 0.001
Split Flow NTrial= 30
Split Flow Tol= 0.02
Split Flow Ratio= 0.02
Log Output Level= 0
Friction Slope Method= 1
Unsteady Friction Slope Method= 2
Unsteady Bridges Friction Slope Method= 1
Parabolic Critical Depth
Global Vel Dist=  1 , 1 , 1
Global Log Level= 0
CheckData=True
Encroach Param= -1, 0, 0, 0
BEGIN DESCRIPTION:
Multiple Run
END DESCRIPTION:

--- CHAFFIN CREEK.f01 (steady flow) ---

Flow Title=Multiple
Program Version=5.07
Number of Profiles= 7
Profile Names=10-year,25-year,50-year,1pct_min,100-year,1pct_plu,500-year
River Rch & RM=CHAFFIN CREEK,Reach-1         ,27004
     790    1054    1265     753    1502    2997    2112
River Rch & RM=CHAFFIN CREEK,Reach-1         ,23762
     917    1236    1494     895    1786    3563    2545
River Rch & RM=CHAFFIN CREEK,Reach-1         ,22555
    1070    1450    1760    1057    2109    4207    3022
River Rch & RM=CHAFFIN CREEK,Reach-1         ,18684
    1131    1537    1869    1125    2244    4478    3228
River Rch & RM=CHAFFIN CREEK,Reach-1         ,17590
    1314    1804    2210    1339    2671    5329    3895
River Rch & RM=CHAFFIN CREEK,Reach-1         ,16873
    1488    2051    2518    1528    3049    6083    4462
River Rch & RM=CHAFFIN CREEK,Reach-1         ,14183
    1668    2311    2848    1734    3460    6903    5098
River Rch & RM=CHAFFIN CREEK,Reach-1         ,12457
    1706    2366    2918    1778    3547    7077    5233
River Rch & RM=CHAFFIN CREEK,Reach-1         ,11358
    1734    2407    2968    1808    3606    7196    5320
River Rch & RM=CHAFFIN CREEK,Reach-1         ,9017
    2645    3745    4682    2888    5762   11496    8717
River Rch & RM=CHAFFIN CREEK,Reach-1         ,6375
    2821    4007    5019    3102    6189   12348    9398
River Rch & RM=CHAFFIN CREEK,Reach-1         ,4155
    2883    4088    5114    3155    6296   12561    9531
Boundary for River Rch & Prof#=CHAFFIN CREEK,Reach-1         , 1
Up Type= 0
Dn Type= 3
Dn Slope=0.005
Boundary for River Rch & Prof#=CHAFFIN CREEK,Reach-1         , 2
Up Type= 0
Dn Type= 3
Dn Slope=0.005
Boundary for River Rch & Prof#=CHAFFIN CREEK,Reach-1         , 3
Up Type= 0
Dn Type= 3
Dn Slope=0.005
Boundary for River Rch & Prof#=CHAFFIN CREEK,Reach-1         , 4
Up Type= 0
Dn Type= 3
Dn Slope=0.005
Boundary for River Rch & Prof#=CHAFFIN CREEK,Reach-1         , 5
Up Type= 0
Dn Type= 3
Dn Slope=0.005
Boundary for River Rch & Prof#=CHAFFIN CREEK,Reach-1         , 6
Up Type= 0
Dn Type= 3
Dn Slope=0.005
Boundary for River Rch & Prof#=CHAFFIN CREEK,Reach-1         , 7
Up Type= 0
Dn Type= 3
Dn Slope=0.005
DSS Import GetInterval= 0
DSS Import GetPeak= 0
DSS Import FillOption= 0

--- CHAFFIN CREEK.g01 (geometry) ---

Geom Title=Existing Conditions

River Reach=CHAFFIN CREEK,Reach-1
Reach XY= 30
      2831155.59      7089210.71      2831173.72      7088834.41
      2831559.39      7088752.29      2831451.53      7088387.90
      2831942.12      7087909.10      2831767.87      7087561.67
      2832144.61      7087239.74      2832514.56      7086250.46
      2832327.20      7086067.12      2832561.92      7085860.07
      2832172.59      7085577.64      2832835.62      7084430.45
      2833817.93      7083508.58      2834405.82      7083501.23
      2834943.69      7082324.36      2836008.79      7081258.20
      2836511.73      7081303.13      2837002.79      7080545.77
      2838174.63      7080098.43      2838642.76      7079526.36
      2839255.80      7079411.15      2839743.42      7078503.88
      2840311.55      7078128.22      2840728.33      7077102.58
      2842150.88      7076013.44      2842379.15      7075152.26
      2842944.79      7074347.37      2843348.27      7073903.38
      2843947.22      7073729.27      2844385.55      7073180.67

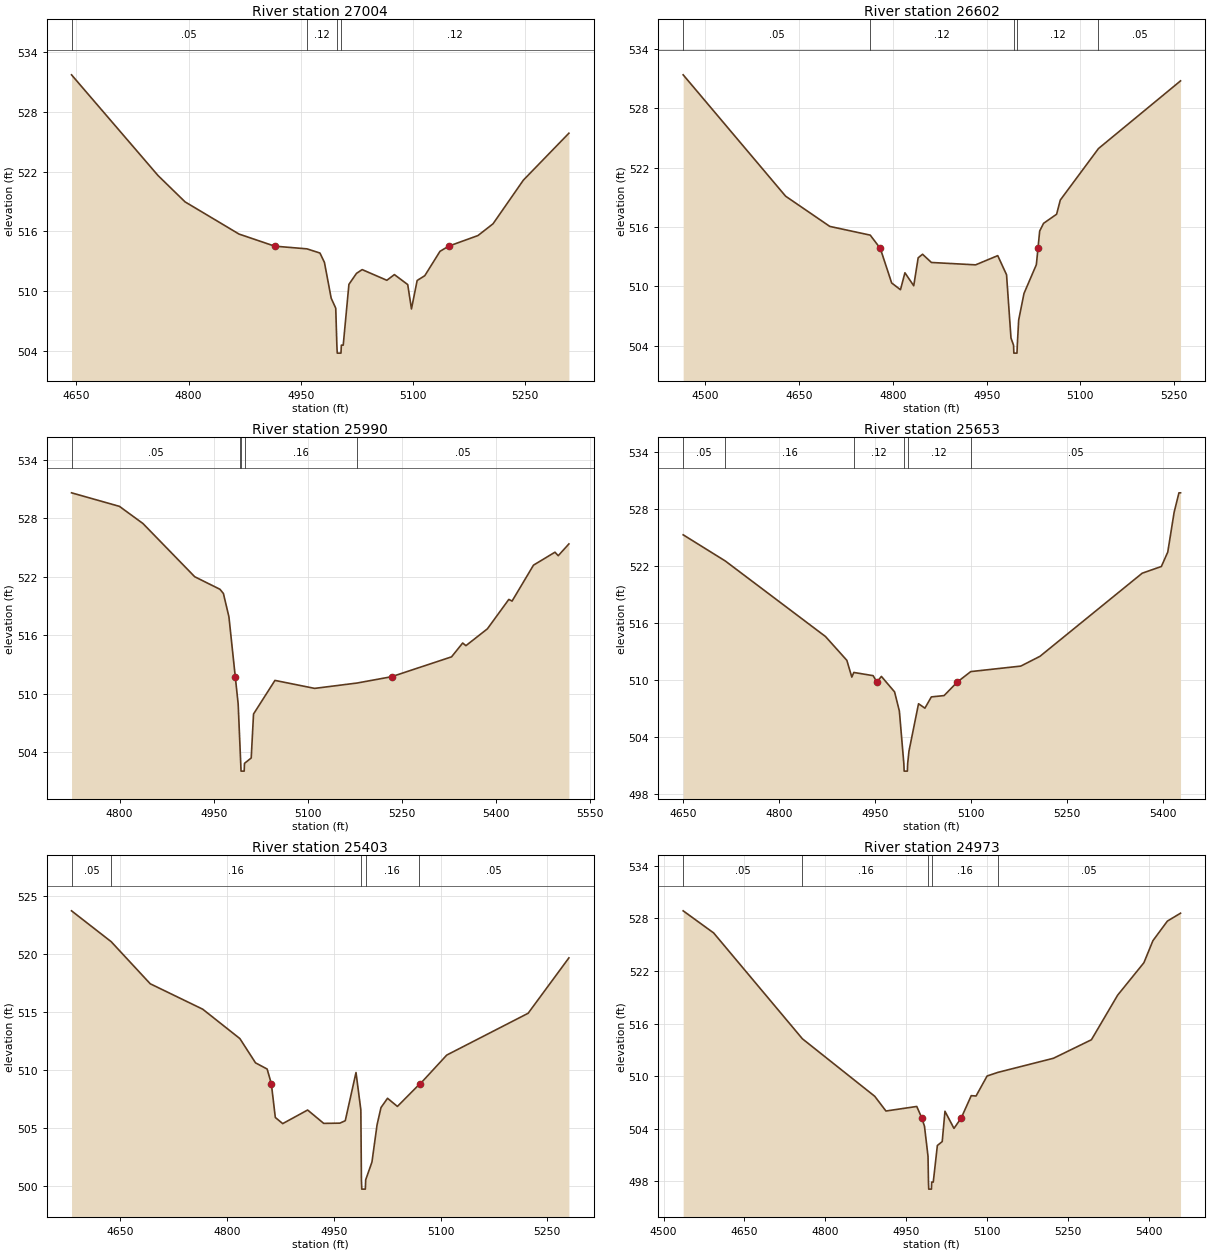
Type RM Length L Ch R = 1,27004,402,402,402
BEGIN DESCRIPTION:
CHAFFIN CREEK 44.0
END DESCRIPTION:
XS GIS Cut Line= 3
      2831575.01      7089225.01      2831275.00      7089025.00
      2830975.01      7088975.00
#Sta/Elev= 30
  4643.5  531.70  4759.2  521.60  4795.2  518.97  4867.4  515.74  4915.0  514.53
  4958.1  514.26  4975.5  513.84  4981.5  512.90  4990.5  509.32  4996.6  508.31
  4998.1  504.61  4998.6  503.81  5003.6  503.81  5004.1  504.61  5006.6  504.61
  5014.2  510.70  5024.3  511.80  5031.9  512.18  5064.9  511.11  5075.0  511.68
  5092.8  510.68  5097.8  508.24  5105.4  511.09  5115.6  511.57  5135.9  514.01
  5147.5  514.53  5186.6  515.59  5206.8  516.77  5247.4  521.15  5308.2  525.85
#Mann=4,-1,0
  4643.5    0.05       0  4958.1    0.12       0  4998.1    0.07       0
  5004.1    0.12       0
Bank Sta=4915,5147.5
Exp/Cntr=0.3,0.1

Type RM Length L Ch R = 1,26602,612,612,612
BEGIN DESCRIPTION:
CHAFFIN CREEK 43.0
END DESCRIPTION:
XS GIS Cut Line= 3
      2831604.81      7089176.91      2831222.60      7088799.16
      2830975.04      7088725.01
#Sta/Elev= 30
  4464.4  531.36  4628.3  519.11  4699.0  516.06  4763.7  515.18  4779.8  513.84
  4798.0  510.35  4812.1  509.67  4819.2  511.38  4833.3  510.07  4840.4  512.89
  4847.4  513.25  4861.6  512.42  4932.3  512.18  4967.7  513.11  4981.8  511.18
  4988.9  504.80  4993.0  504.07  4993.5  503.27  4998.5  503.27  4999.0  504.07
  5001.2  506.61  5009.7  509.29  5029.5  512.20  5032.1  513.84  5034.8  515.59
  5041.0  516.37  5061.9  517.29  5067.8  518.72  5128.9  523.92  5260.2  530.75
#Mann=5,-1,0
  4464.4    0.05       0  4763.7    0.12       0  4993.0    0.07       0
  4999.0    0.12       0  5128.9    0.05       0
Bank Sta=4779.8,5032.1
Exp/Cntr=0.3,0.1

Type RM Length L Ch R = 1,25990,337,337,337
BEGIN DESCRIPTION:
CHAFFIN CREEK 42.0
END DESCRIPTION:
XS GIS Cut Line= 3
      2831824.96      7088824.98      2831564.60      7088711.99
      2831075.02      7088575.01
#Sta/Elev= 30
  4723.6  530.62  4799.9  529.23  4837.3  527.47  4919.8  522.00  4960.0  520.71
  4965.5  520.28  4974.3  517.88  4984.4  511.73  4989.0  508.94  4991.4  505.36
  4993.1  502.83  4993.6  502.03  4998.6  502.03  4999.1  502.83  5009.8  503.38
  5013.5  507.90  5047.6  511.35  5110.8  510.53  5178.4  511.08  5233.4  511.73
  5328.9  513.77  5346.6  515.19  5351.8  514.92  5386.0  516.65  5420.1  519.67
  5425.3  519.50  5459.4  523.19  5493.6  524.52  5498.8  524.16  5515.8  525.37
#Mann=5,-1,0
  4723.6    0.05       0  4991.4    0.16       0  4993.1    0.07       0
  4999.1    0.16       0  5178.4    0.05       0
Bank Sta=4984.4,5233.4
Exp/Cntr=0.3,0.1

Type RM Length L Ch R = 1,25653,250,250,250
BEGIN DESCRIPTION:
CHAFFIN CREEK 41.0
END DESCRIPTION:
XS GIS Cut Line= 3
      2831843.42      7088604.77      2831525.00      7088525.00
      2831074.96      7088525.00
#Sta/Elev= 30
  4649.5  525.31  4715.4  522.55  4872.2  514.58  4905.6  512.07  4913.4  510.30
  4916.5  510.79  4946.8  510.45  4952.5  509.78  4959.7  510.37  4980.3  508.74
  4987.8  506.72  4994.8  501.18  4995.3  500.38  5000.3  500.38  5000.8  501.18
  5002.8  502.48  5017.8  507.49  5027.8  507.02  5037.8  508.21  5057.8  508.35
  5078.5  509.78  5099.5  510.88  5177.8  511.46  5207.8  512.49  5367.8  521.26
  5397.8  521.97  5407.8  523.49  5417.8  527.70  5425.3  529.74  5427.8  529.74
#Mann=6,-1,0
  4649.5    0.05       0  4715.4    0.16       0  4916.5    0.12       0
  4994.8    0.07       0  5000.8    0.12       0  5099.5    0.05       0
Bank Sta=4952.5,5078.5
Exp/Cntr=0.3,0.1

Type RM Length L Ch R = 1,25403,430,430,430
BEGIN DESCRIPTION:
Mapping XS d32e3329
END DESCRIPTION:
XS GIS Cut Line= 3
      2831897.69      7088522.00      2831533.31      7088327.51
      2831272.83      7088209.52
#Sta/Elev= 30
  4581.4  523.72  4637.2  521.06  4692.0  517.44  4765.8  515.25  4818.0  512.72
  4840.0  510.63  4856.3  510.10  4862.2  508.84  4867.8  505.93  4878.2  505.40
  4913.2  506.57  4935.8  505.42  4958.5  505.44  4966.1  505.65  4981.2  509.80
  4988.0  506.58  4988.8  500.56  4989.3  499.76  4994.3  499.76  4994.8  500.56
  5003.6  502.09  5010.8  505.30  5016.3  506.78  5025.5  507.58  5039.4  506.88
  5069.5  508.74  5071.8  508.85  5108.7  511.30  5223.1  514.90  5280.4  519.67
#Mann=5,-1,0
  4581.4    0.05       0  4637.2    0.16       0  4988.8    0.07       0
  4994.8    0.16       0  5069.5    0.05       0
Bank Sta=4862.2,5071.8
Exp/Cntr=0.3,0.1

Type RM Length L Ch R = 1,24973,288,288,288
BEGIN DESCRIPTION:
CHAFFIN CREEK 40.0
END DESCRIPTION:
XS GIS Cut Line= 3
      2832075.01      7088425.01      2831725.00      7088125.00
      2831274.97      7088024.99
#Sta/Elev= 30
  4536.4  528.84  4592.9  526.32  4757.4  514.26  4891.5  507.71  4912.3  506.03
  4969.4  506.55  4978.8  505.23  4983.7  504.30  4990.3  500.86  4991.1  497.93
  4991.6  497.13  4996.6  497.13  4997.1  497.93  5000.0  497.93  5007.6  502.10
  5016.6  502.55  5021.7  506.00  5038.4  504.05  5051.8  505.23  5070.4  507.78
  5079.3  507.74  5099.8  510.02  5119.7  510.43  5222.8  512.04  5293.2  514.15
  5341.8  519.23  5390.5  522.93  5407.2  525.44  5434.0  527.67  5458.4  528.57
#Mann=5,-1,0
  4536.4    0.05       0  4757.4    0.16       0  4991.1    0.07       0
  4997.1    0.16       0  5119.7    0.05       0
Bank Sta=4978.8,5051.8
Exp/Cntr=0.3,0.1

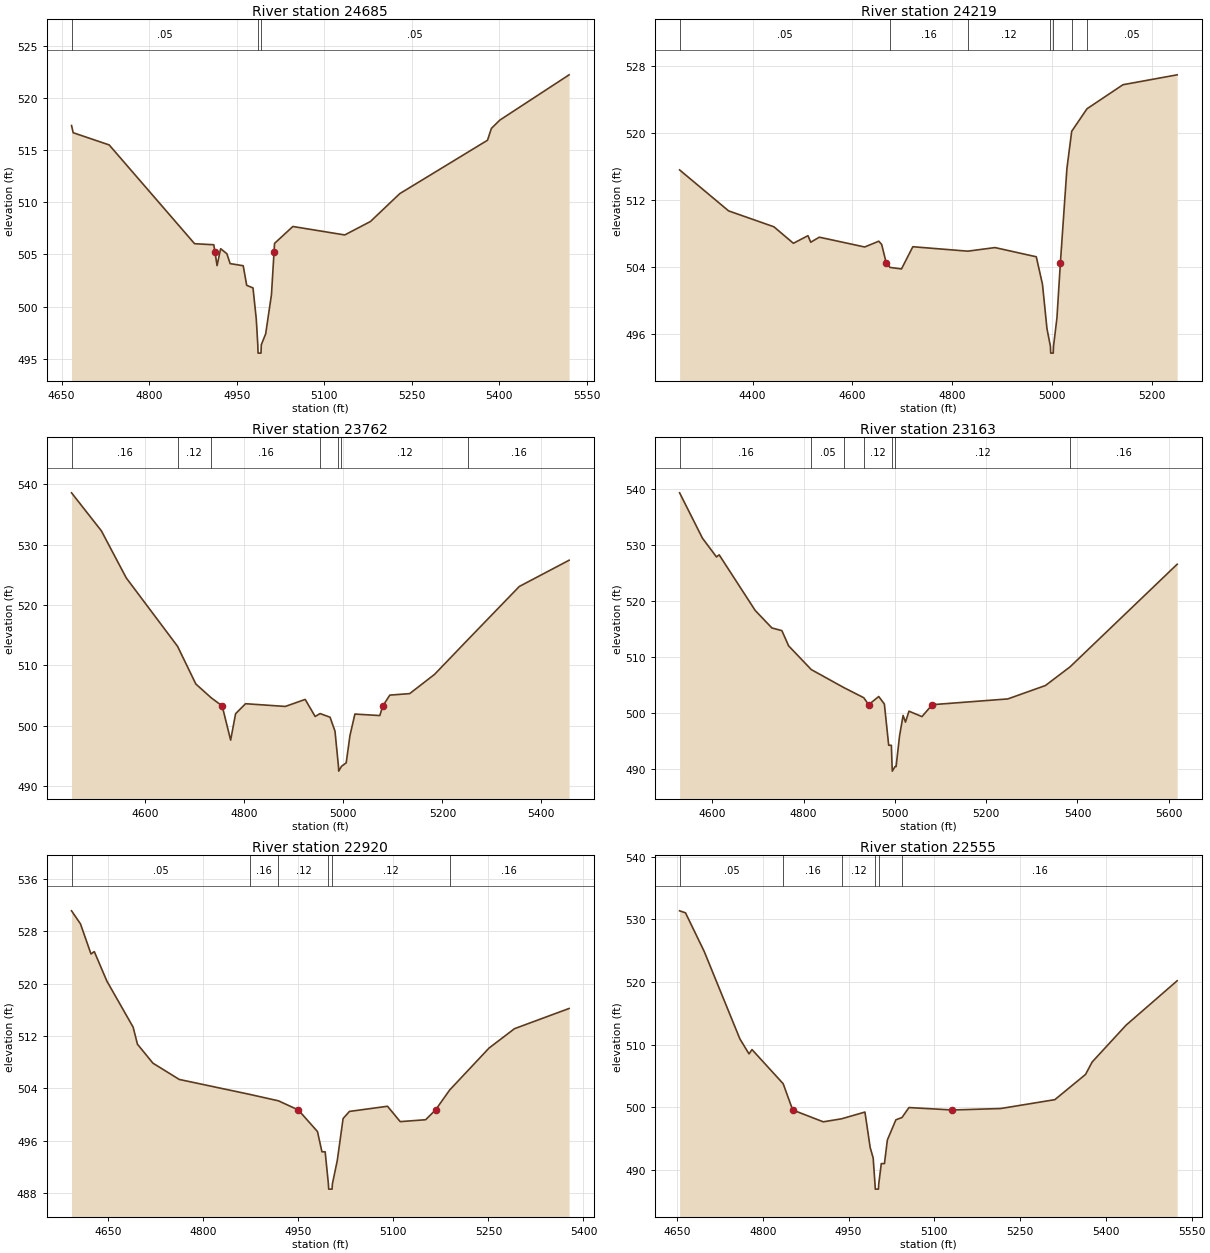
Type RM Length L Ch R = 1,24685,466,466,466
BEGIN DESCRIPTION:
CHAFFIN CREEK 39.0
END DESCRIPTION:
XS GIS Cut Line= 3
      2832203.89      7088090.57      2831920.02      7087949.75
      2831412.59      7087777.63
#Sta/Elev= 30
  4667.0  517.36  4669.8  516.67  4731.5  515.50  4877.9  506.03  4910.8  505.93
  4912.9  505.19  4916.4  503.93  4922.5  505.55  4933.2  505.07  4938.8  504.12
  4961.2  503.92  4967.2  502.04  4978.0  501.79  4983.6  498.81  4986.2  496.34
  4986.7  495.54  4991.7  495.54  4992.2  496.34  4999.7  497.39  5009.6  501.14
  5014.0  505.19  5014.9  506.06  5046.3  507.68  5135.2  506.87  5179.3  508.16
  5229.5  510.83  5379.9  515.95  5386.5  517.08  5401.0  517.88  5519.7  522.22
#Mann=3,-1,0
  4667.0    0.05       0  4986.2    0.03       0  4992.2    0.05       0
Bank Sta=4912.9,5014
Exp/Cntr=0.3,0.1

Type RM Length L Ch R = 1,24219,457,457,457
BEGIN DESCRIPTION:
Mapping XS 3ad40651
END DESCRIPTION:
XS GIS Cut Line= 3
      2832441.05      7087900.97      2831782.20      7087588.48
      2831514.02      7087591.08
#Sta/Elev= 30
  4253.7  515.62  4351.9  510.73  4442.8  508.83  4481.8  506.86  4511.0  507.77
  4516.6  506.99  4533.8  507.59  4624.7  506.42  4653.0  507.11  4658.8  506.72
  4667.9  504.52  4675.5  503.98  4698.5  503.80  4721.2  506.45  4831.4  505.92
  4885.9  506.35  4968.7  505.25  4981.1  501.97  4990.1  496.68  4997.1  494.55
  4997.6  493.75  5002.7  493.75  5003.2  494.55  5010.1  497.95  5017.0  504.52
  5030.1  515.79  5039.7  520.23  5070.4  522.92  5142.5  525.79  5251.1  526.97
#Mann=7,-1,0
  4253.7    0.05       0  4675.5    0.16       0  4831.4    0.12       0
  4997.1    0.07       0  5003.2    0.12       0  5039.7    0.16       0
  5070.4    0.05       0
Bank Sta=4667.9,5017
Exp/Cntr=0.3,0.1

Type RM Length L Ch R = 1,23762,599,599,599
BEGIN DESCRIPTION:
double CHAFFIN CREEK 38.0
END DESCRIPTION:
XS GIS Cut Line= 3
      2832625.05      7087275.00      2832075.00      7087325.00
      2831624.98      7087275.00
#Sta/Elev= 30
  4450.8  538.55  4511.1  532.26  4561.3  524.48  4665.0  513.16  4701.9  506.93
  4732.5  504.68  4755.1  503.30  4772.2  497.65  4782.2  502.02  4802.3  503.67
  4882.6  503.22  4922.8  504.38  4942.9  501.56  4952.9  502.04  4973.0  501.44
  4983.0  499.13  4990.0  493.32  4990.5  492.52  4996.1  493.32  5005.6  493.88
  5013.2  498.39  5023.2  501.96  5073.5  501.71  5079.6  503.30  5093.7  505.09
  5133.9  505.34  5184.2  508.53  5251.3  514.25  5355.3  523.06  5455.9  527.40
#Mann=7,-1,0
  4450.8    0.16       0  4665.0    0.12       0  4732.5    0.16       0
  4952.9    0.12       0  4990.0    0.07       0  4996.1    0.12       0
  5251.3    0.16       0
Bank Sta=4755.1,5079.6
Exp/Cntr=0.3,0.1

Type RM Length L Ch R = 1,23163,243,243,243
BEGIN DESCRIPTION:
CHAFFIN CREEK 37.0
END DESCRIPTION:
XS GIS Cut Line= 3
      2832675.00      7087125.00      2832275.00      7086875.00
      2831674.96      7087025.01
#Sta/Elev= 30
  4528.3  539.31  4578.4  531.20  4609.1  527.86  4615.0  528.23  4694.0  518.29
  4730.5  515.17  4752.4  514.69  4767.1  511.98  4816.8  507.73  4888.5  504.50
  4931.9  502.70  4942.5  501.46  4964.6  502.92  4977.0  501.57  4986.4  494.22
  4992.3  494.20  4993.9  490.39  4994.4  489.59  5000.2  490.39  5002.6  490.39
  5010.3  495.93  5018.0  499.54  5023.2  498.35  5030.9  500.30  5059.3  499.33
  5081.8  501.46  5247.4  502.49  5329.8  504.88  5383.7  508.21  5618.5  526.55
#Mann=7,-1,0
  4528.3    0.16       0  4816.8    0.05       0  4888.5    0.16       0
  4931.9    0.12       0  4993.9    0.07       0  5000.2    0.12       0
  5383.7    0.16       0
Bank Sta=4942.5,5081.8
Exp/Cntr=0.3,0.1

Type RM Length L Ch R = 1,22920,365,365,365
BEGIN DESCRIPTION:
Mapping XS ccdb3b85
END DESCRIPTION:
XS GIS Cut Line= 3
      2832608.59      7086758.62      2832226.65      7086650.98
      2831838.93      7086630.21
#Sta/Elev= 30
  4592.2  531.15  4606.3  529.16  4622.9  524.55  4628.1  524.92  4647.9  520.42
  4689.4  513.36  4696.2  510.76  4720.6  507.86  4762.2  505.37  4873.2  503.09
  4918.7  502.10  4950.0  500.71  4980.3  497.40  4987.3  494.31  4992.4  494.31
  4997.5  489.40  4998.0  488.60  5003.3  488.60  5003.8  489.40  5011.5  492.97
  5020.7  499.39  5030.7  500.48  5090.8  501.27  5110.8  498.92  5150.9  499.21
  5166.6  500.71  5188.8  503.75  5251.0  510.17  5291.1  513.13  5377.3  516.22
#Mann=6,-1,0
  4592.2    0.05       0  4873.2    0.16       0  4918.7    0.12       0
  4997.5    0.07       0  5003.8    0.12       0  5188.8    0.16       0
Bank Sta=4950,5166.6
Exp/Cntr=0.3,0.1

Type RM Length L Ch R = 1,22555,701,701,701
BEGIN DESCRIPTION:
CHAFFIN CREEK 36.0
END DESCRIPTION:
XS GIS Cut Line= 3
      2832716.27      7086473.91      2832375.00      7086375.00
      2831925.00      7086125.00
#Sta/Elev= 30
  4654.6  531.38  4664.9  531.06  4697.6  524.90  4760.0  510.93  4776.0  508.53
  4781.2  509.22  4835.7  503.77  4852.4  499.57  4905.8  497.68  4938.2  498.17
  4978.7  499.24  4987.9  493.56  4993.1  491.91  4996.3  487.73  4996.8  486.93
  5002.3  486.93  5002.8  487.73  5007.3  491.01  5012.8  491.01  5017.9  494.77
  5032.8  498.00  5043.5  498.37  5055.7  499.96  5131.7  499.57  5215.8  499.80
  5310.8  501.22  5364.5  505.25  5376.0  507.23  5435.5  513.13  5524.7  520.21
#Mann=6,-1,0
  4654.6    0.05       0  4835.7    0.16       0  4938.2    0.12       0
  4996.3    0.07       0  5002.8    0.12       0  5043.5    0.16       0
Bank Sta=4852.4,5131.7
Exp/Cntr=0.3,0.1

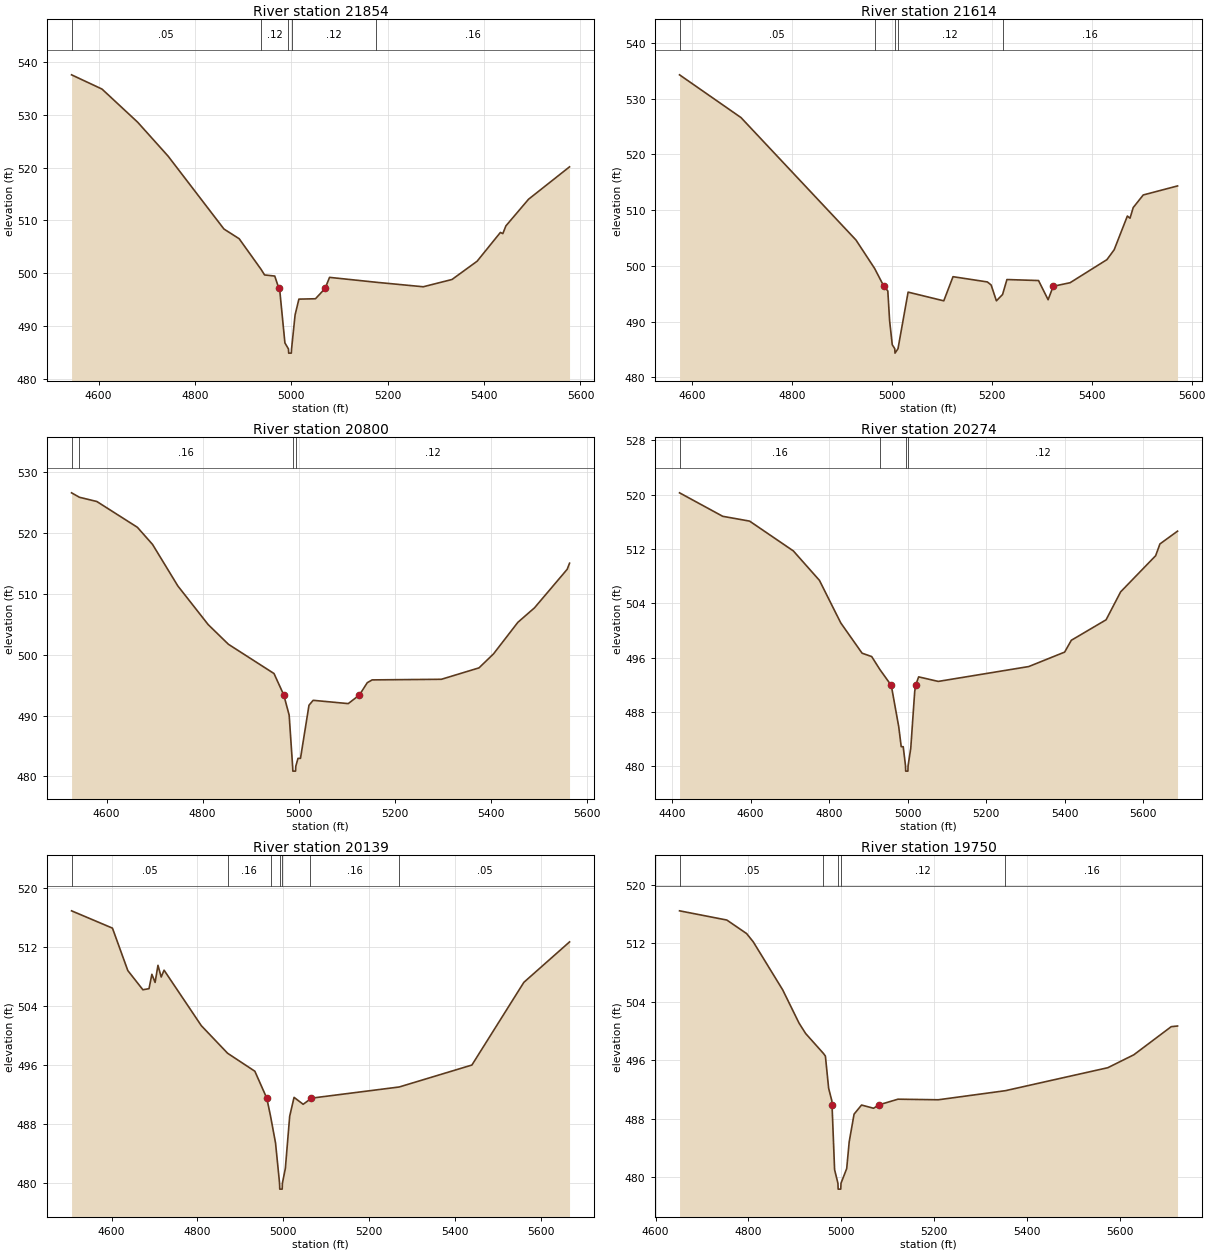
Type RM Length L Ch R = 1,21854,240,240,240
BEGIN DESCRIPTION:
CHAFFIN CREEK 35.0
END DESCRIPTION:
XS GIS Cut Line= 3
      2832924.99      7086125.00      2832475.00      7085975.00
      2831925.05      7086074.99
#Sta/Elev= 30
  4544.0  537.59  4607.2  534.89  4681.0  528.63  4744.3  522.19  4860.2  508.38
  4891.8  506.54  4937.0  500.77  4944.5  499.68  4965.6  499.47  4974.2  497.12
  4976.2  496.57  4986.7  486.80  4994.0  485.67  4994.5  484.87  5000.0  484.87
  5000.5  485.67  5007.8  492.11  5015.7  495.10  5050.1  495.17  5070.0  497.12
  5079.3  499.22  5176.4  498.29  5273.7  497.44  5333.4  498.82  5385.5  502.28
  5433.8  507.73  5438.9  507.51  5445.2  508.97  5492.2  514.02  5577.3  520.16
#Mann=5,-1,0
  4544.0    0.05       0  4937.0    0.12       0  4994.0    0.07       0
  5000.5    0.12       0  5176.4    0.16       0
Bank Sta=4974.2,5070
Exp/Cntr=0.3,0.1

Type RM Length L Ch R = 1,21614,814,814,814
BEGIN DESCRIPTION:
Mapping XS 18d68781
END DESCRIPTION:
XS GIS Cut Line= 3
      2832948.01      7085759.48      2832531.33      7085768.16
      2831980.83      7085950.22
#Sta/Elev= 30
  4575.2  534.27  4698.2  526.60  4928.3  504.64  4965.6  499.54  4984.1  496.34
  4992.0  495.51  4995.6  490.16  5000.9  485.85  5005.9  485.15  5006.4  484.35
  5012.4  485.15  5032.6  495.29  5104.0  493.73  5122.5  498.06  5191.2  497.12
  5198.8  496.57  5209.3  493.73  5221.6  494.86  5230.4  497.55  5293.6  497.37
  5312.8  493.93  5323.0  496.34  5356.8  496.98  5430.5  501.12  5445.0  502.89
  5471.4  508.94  5476.7  508.55  5483.1  510.46  5503.2  512.72  5571.8  514.34
#Mann=5,-1,0
  4575.2    0.05       0  4965.6    0.12       0  5005.9    0.07       0
  5012.4    0.12       0  5221.6    0.16       0
Bank Sta=4984.1,5323
Exp/Cntr=0.3,0.1

Type RM Length L Ch R = 1,20800,526,526,526
BEGIN DESCRIPTION:
CHAFFIN CREEK 34.0
END DESCRIPTION:
XS GIS Cut Line= 3
      2832875.02      7085575.01      2832425.00      7085425.00
      2831868.62      7085338.69
#Sta/Elev= 30
  4526.9  526.65  4543.3  525.92  4579.6  525.22  4664.0  520.98  4695.6  518.16
  4748.3  511.33  4811.5  504.97  4853.7  501.73  4948.6  496.92  4969.0  493.39
  4980.2  490.07  4987.4  481.66  4987.9  480.86  4993.5  480.86  4994.0  481.66
  4998.6  482.96  5003.8  482.96  5021.5  491.70  5030.2  492.51  5103.3  491.97
  5126.6  493.39  5142.9  495.41  5153.1  495.87  5297.3  495.97  5375.7  497.85
  5406.0  500.16  5456.6  505.34  5491.3  507.73  5559.3  514.06  5564.3  515.07
#Mann=4,-1,0
  4526.9    0.08       0  4543.3    0.16       0  4987.4    0.07       0
  4994.0    0.12       0
Bank Sta=4969,5126.6
Exp/Cntr=0.3,0.1

Type RM Length L Ch R = 1,20274,135,135,135
BEGIN DESCRIPTION:
Mapping XS 93c0d4b8
END DESCRIPTION:
XS GIS Cut Line= 5
      2832839.49      7085342.79      2832817.79      7085099.76
      2832518.31      7084982.57      2832127.69      7084956.53
      2831832.59      7085056.35
#Sta/Elev= 30
  4419.0  520.28  4529.0  516.82  4597.5  516.11  4708.9  511.72  4775.4  507.38
  4829.7  501.11  4884.0  496.65  4908.5  496.15  4929.4  494.24  4958.4  491.90
  4977.4  485.80  4983.7  482.87  4988.8  482.87  4994.6  480.07  4995.1  479.27
  5000.7  479.27  5001.2  480.07  5008.0  482.64  5018.0  490.95  5020.3  491.90
  5028.1  493.16  5078.1  492.49  5308.6  494.68  5400.0  496.81  5417.0  498.55
  5505.6  501.57  5542.7  505.69  5631.8  511.01  5642.8  512.75  5687.6  514.63
#Mann=4,-1,0
  4419.0    0.16       0  4929.4    0.12       0  4994.6    0.07       0
  5001.2    0.12       0
Bank Sta=4958.4,5020.3
Exp/Cntr=0.3,0.1

Type RM Length L Ch R = 1,20139,389,389,389
BEGIN DESCRIPTION:
Mapping XS b431fa07
END DESCRIPTION:
XS GIS Cut Line= 4
      2832982.71      7085052.01      2832817.79      7084904.45
      2832422.83      7084835.00      2831889.51      7084761.29
#Sta/Elev= 30
  4506.9  516.91  4602.2  514.56  4638.0  508.80  4673.2  506.19  4687.4  506.34
  4694.1  508.29  4701.6  507.19  4708.3  509.51  4715.8  507.92  4722.5  508.85
  4809.4  501.31  4870.6  497.57  4934.1  495.13  4962.0  491.46  4970.8  489.00
  4982.3  485.39  4991.7  479.92  4992.2  479.12  4997.8  479.12  4998.3  479.92
  5005.2  481.93  5015.3  489.02  5025.5  491.58  5046.7  490.64  5061.9  491.29
  5064.2  491.46  5270.6  492.99  5440.0  495.97  5561.1  507.20  5667.6  512.69
#Mann=7,-1,0
  4506.9    0.05       0  4870.6    0.16       0  4970.8    0.12       0
  4991.7    0.07       0  4998.3    0.12       0  5061.9    0.16       0
  5270.6    0.05       0
Bank Sta=4962,5064.2
Exp/Cntr=0.3,0.1

Type RM Length L Ch R = 1,19750,247,247,247
BEGIN DESCRIPTION:
Mapping XS 0ed86a9f
END DESCRIPTION:
XS GIS Cut Line= 3
      2833039.15      7084864.52      2832820.40      7084619.73
      2832112.04      7084390.55
#Sta/Elev= 30
  4651.6  516.43  4753.5  515.17  4796.1  513.32  4810.3  512.20  4873.8  505.63
  4909.0  501.09  4923.2  499.67  4961.6  496.94  4965.8  496.58  4972.8  492.18
  4979.7  490.47  4980.1  489.90  4985.6  481.06  4992.8  479.20  4993.3  478.40
  4998.9  478.40  4999.4  479.20  5011.7  481.21  5017.1  484.88  5027.6  488.65
  5043.7  489.89  5069.6  489.45  5080.3  489.90  5122.2  490.69  5209.0  490.61
  5353.4  491.85  5574.1  494.99  5630.3  496.76  5710.8  500.60  5724.4  500.69
#Mann=5,-1,0
  4651.6    0.05       0  4961.6    0.12       0  4992.8    0.07       0
  4999.4    0.12       0  5353.4    0.16       0
Bank Sta=4980.1,5080.3
Exp/Cntr=0.3,0.1

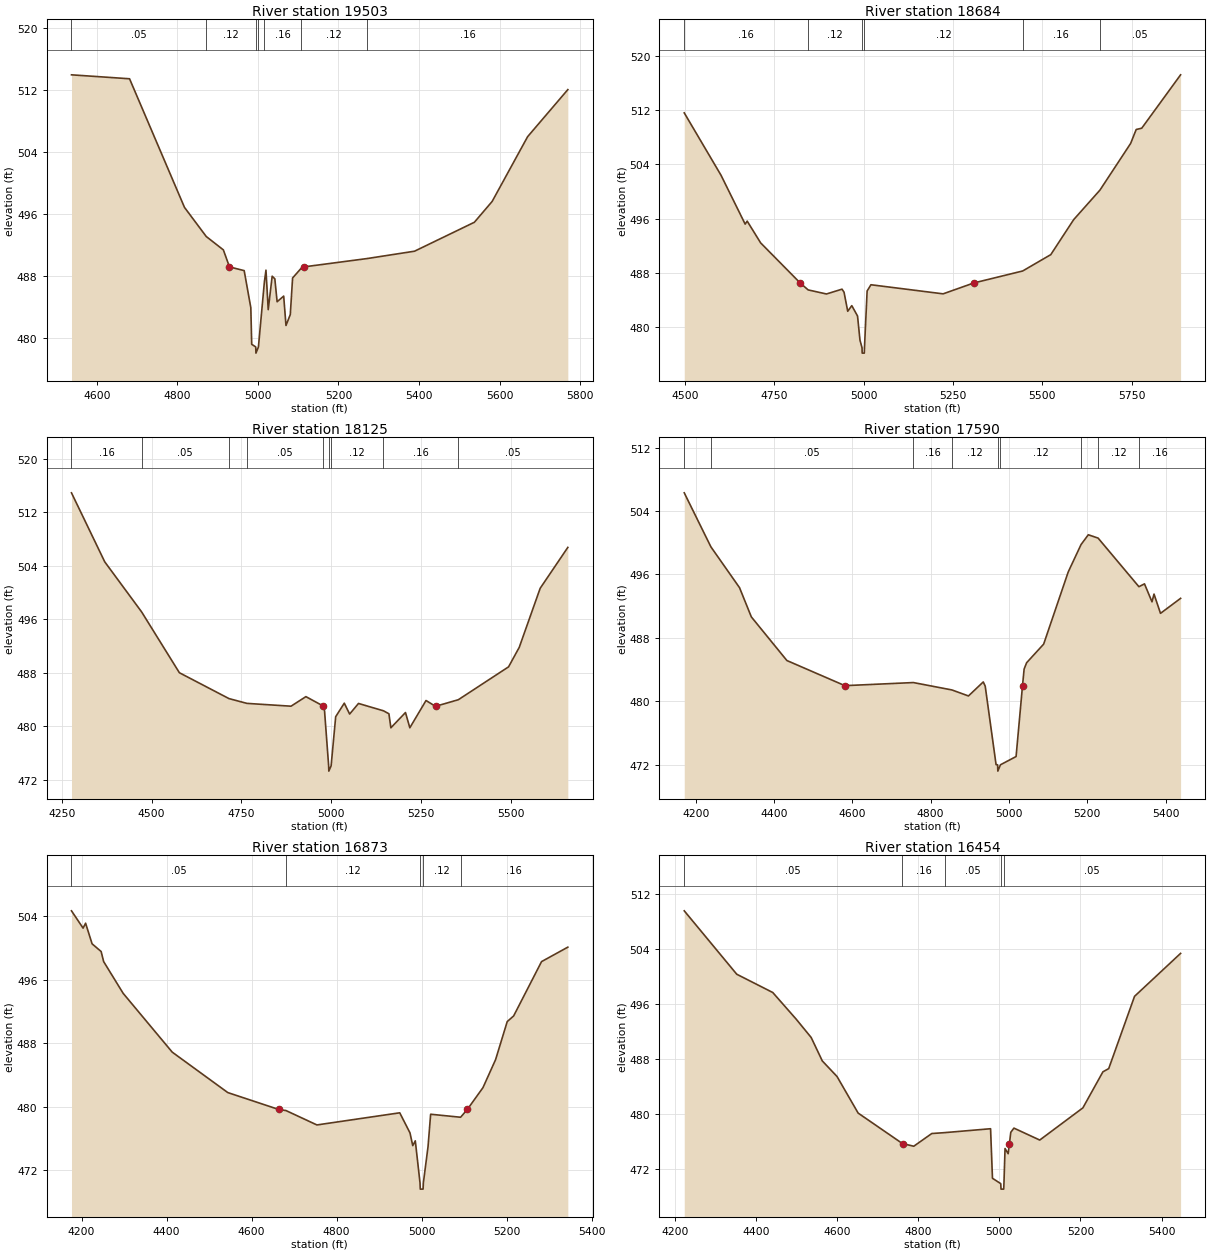
Type RM Length L Ch R = 1,19503,819,819,819
BEGIN DESCRIPTION:
Mapping XS 01428445
END DESCRIPTION:
XS GIS Cut Line= 3
      2833080.80      7084812.41      2832888.10      7084406.19
      2832195.40      7084041.60
#Sta/Elev= 30
  4537.1  514.00  4681.3  513.49  4817.7  496.87  4871.7  493.11  4914.2  491.38
  4929.4  489.18  4965.9  488.70  4982.4  483.90  4984.6  479.18  4994.6  478.84
  4995.1  478.04  5001.3  478.84  5016.1  487.26  5020.0  488.76  5025.6  483.66
  5035.4  487.98  5042.0  487.64  5047.7  484.68  5064.0  485.41  5069.7  481.61
  5080.4  483.02  5086.1  487.75  5107.7  489.02  5113.7  489.18  5271.2  490.26
  5388.9  491.21  5537.5  494.95  5581.6  497.64  5669.7  506.01  5769.5  512.09
#Mann=7,-1,0
  4537.1    0.05       0  4871.7    0.12       0  4994.6    0.07       0
  5001.3    0.12       0  5016.1    0.16       0  5107.7    0.12       0
  5271.2    0.16       0
Bank Sta=4929.4,5113.7
Exp/Cntr=0.3,0.1

Type RM Length L Ch R = 1,18684,559,559,559
BEGIN DESCRIPTION:
CHAFFIN CREEK 30.0
END DESCRIPTION:
XS GIS Cut Line= 3
      2833575.01      7084425.02      2833325.00      7083975.00
      2832575.04      7083525.02
#Sta/Elev= 30
  4497.7  511.58  4600.7  502.38  4668.2  495.18  4673.9  495.62  4711.6  492.41
  4822.3  486.50  4844.5  485.48  4895.8  484.88  4939.3  485.59  4945.0  485.14
  4955.3  482.33  4966.7  483.16  4982.8  481.63  4989.6  478.07  4995.3  476.96
  4995.8  476.16  5001.7  476.16  5002.2  476.96  5009.6  485.32  5020.3  486.24
  5222.4  484.90  5307.9  486.50  5445.0  488.27  5523.7  490.68  5587.8  495.84
  5661.3  500.19  5747.2  507.07  5762.8  509.13  5778.3  509.32  5887.1  517.19
#Mann=6,-1,0
  4497.7    0.16       0  4844.5    0.12       0  4995.3    0.07       0
  5002.2    0.12       0  5445.0    0.16       0  5661.3    0.05       0
Bank Sta=4822.3,5307.9
Exp/Cntr=0.3,0.1

Type RM Length L Ch R = 1,18125,535,535,535
BEGIN DESCRIPTION:
CHAFFIN CREEK 29.0
END DESCRIPTION:
XS GIS Cut Line= 3
      2833875.00      7084425.01      2833675.00      7083675.00
      2833124.97      7083424.99
#Sta/Elev= 30
  4277.4  514.94  4369.9  504.61  4472.4  497.12  4577.5  488.01  4715.3  484.14
  4765.4  483.42  4888.0  483.00  4929.4  484.43  4977.1  483.04  4977.4  482.98
  4981.2  482.29  4992.6  474.08  4993.1  473.28  4999.5  474.08  5012.2  481.43
  5036.1  483.45  5051.0  481.82  5075.6  483.41  5145.1  482.31  5160.2  481.87
  5165.7  479.77  5206.3  482.05  5218.4  479.77  5263.4  483.85  5289.9  482.98
  5353.3  483.97  5493.0  488.89  5522.7  491.81  5580.9  500.65  5657.8  506.77
#Mann=9,-1,0
  4277.4    0.16       0  4472.4    0.05       0  4715.3    0.07       0
  4765.4    0.05       0  4977.1    0.12       0  4992.6    0.07       0
  4999.5    0.12       0  5145.1    0.16       0  5353.3    0.05       0
Bank Sta=4977.4,5289.9
Exp/Cntr=0.3,0.1

Type RM Length L Ch R = 1,17590,717,717,717
BEGIN DESCRIPTION:
CHAFFIN CREEK 28.0
END DESCRIPTION:
XS GIS Cut Line= 3
      2833925.00      7084324.96      2834025.00      7083525.00
      2833924.99      7083074.97
#Sta/Elev= 30
  4170.9  506.29  4238.9  499.48  4312.0  494.33  4342.2  490.64  4432.9  485.14
  4581.0  481.97  4755.9  482.36  4854.2  481.43  4896.5  480.67  4934.3  482.44
  4939.3  481.90  4967.0  472.01  4970.9  471.99  4971.5  471.19  4978.2  471.99
  5018.1  473.03  5034.5  481.97  5038.6  484.06  5045.0  484.86  5088.5  487.21
  5151.2  496.31  5184.0  499.77  5202.5  501.00  5227.5  500.58  5331.7  494.45
  5345.9  494.81  5365.1  492.54  5370.2  493.52  5386.8  491.09  5438.1  492.98
#Mann=9,-1,0
  4170.9    0.16       0  4238.9    0.05       0  4755.9    0.16       0
  4854.2    0.12       0  4970.9    0.07       0  4978.2    0.12       0
  5184.0    0.16       0  5227.5    0.12       0  5331.7    0.16       0
Bank Sta=4581,5034.5
Exp/Cntr=0.3,0.1

Type RM Length L Ch R = 1,16873,419,419,419
BEGIN DESCRIPTION:
CHAFFIN CREEK 27.0
END DESCRIPTION:
XS GIS Cut Line= 3
      2834987.07      7083979.11      2834565.19      7083307.23
      2834253.55      7083099.47
#Sta/Elev= 30
  4176.4  504.69  4203.7  502.51  4209.6  503.13  4224.9  500.53  4246.2  499.56
  4252.1  498.29  4298.0  494.29  4413.4  486.88  4544.2  481.78  4663.6  479.66
  4681.3  479.51  4753.9  477.70  4948.8  479.23  4972.9  476.70  4979.4  475.09
  4985.4  475.70  4996.5  470.41  4997.1  469.61  5003.7  469.61  5004.4  470.41
  5015.4  474.98  5021.5  479.05  5092.0  478.67  5107.9  479.66  5144.6  482.40
  5174.3  485.93  5201.7  490.73  5216.8  491.44  5282.5  498.29  5344.3  500.11
#Mann=5,-1,0
  4176.4    0.05       0  4681.3    0.12       0  4996.5    0.07       0
  5004.4    0.12       0  5092.0    0.16       0
Bank Sta=4663.6,5107.9
Exp/Cntr=0.3,0.1

Type RM Length L Ch R = 1,16454,535,535,535
BEGIN DESCRIPTION:
CHAFFIN CREEK 26.0
END DESCRIPTION:
XS GIS Cut Line= 3
      2835374.97      7083324.98      2834725.00      7082925.00
      2834424.97      7082574.97
#Sta/Elev= 30
  4222.8  509.56  4352.3  500.32  4441.1  497.66  4499.1  493.76  4535.8  491.11
  4563.3  487.69  4599.6  485.42  4651.7  480.09  4760.7  475.66  4761.4  475.64
  4788.9  475.26  4833.3  477.11  4864.9  477.24  4978.3  477.81  4983.0  470.59
  5003.4  469.81  5004.1  469.01  5010.7  469.01  5011.3  469.81  5014.0  474.93
  5021.7  474.17  5024.8  475.64  5028.2  477.29  5035.9  477.90  5099.6  476.16
  5206.0  480.85  5255.4  486.10  5269.7  486.57  5333.4  497.10  5447.0  503.36
#Mann=5,-1,0
  4222.8    0.05       0  4760.7    0.16       0  4864.9    0.05       0
  5003.4    0.03       0  5011.3    0.05       0
Bank Sta=4761.4,5024.8
Exp/Cntr=0.3,0.1

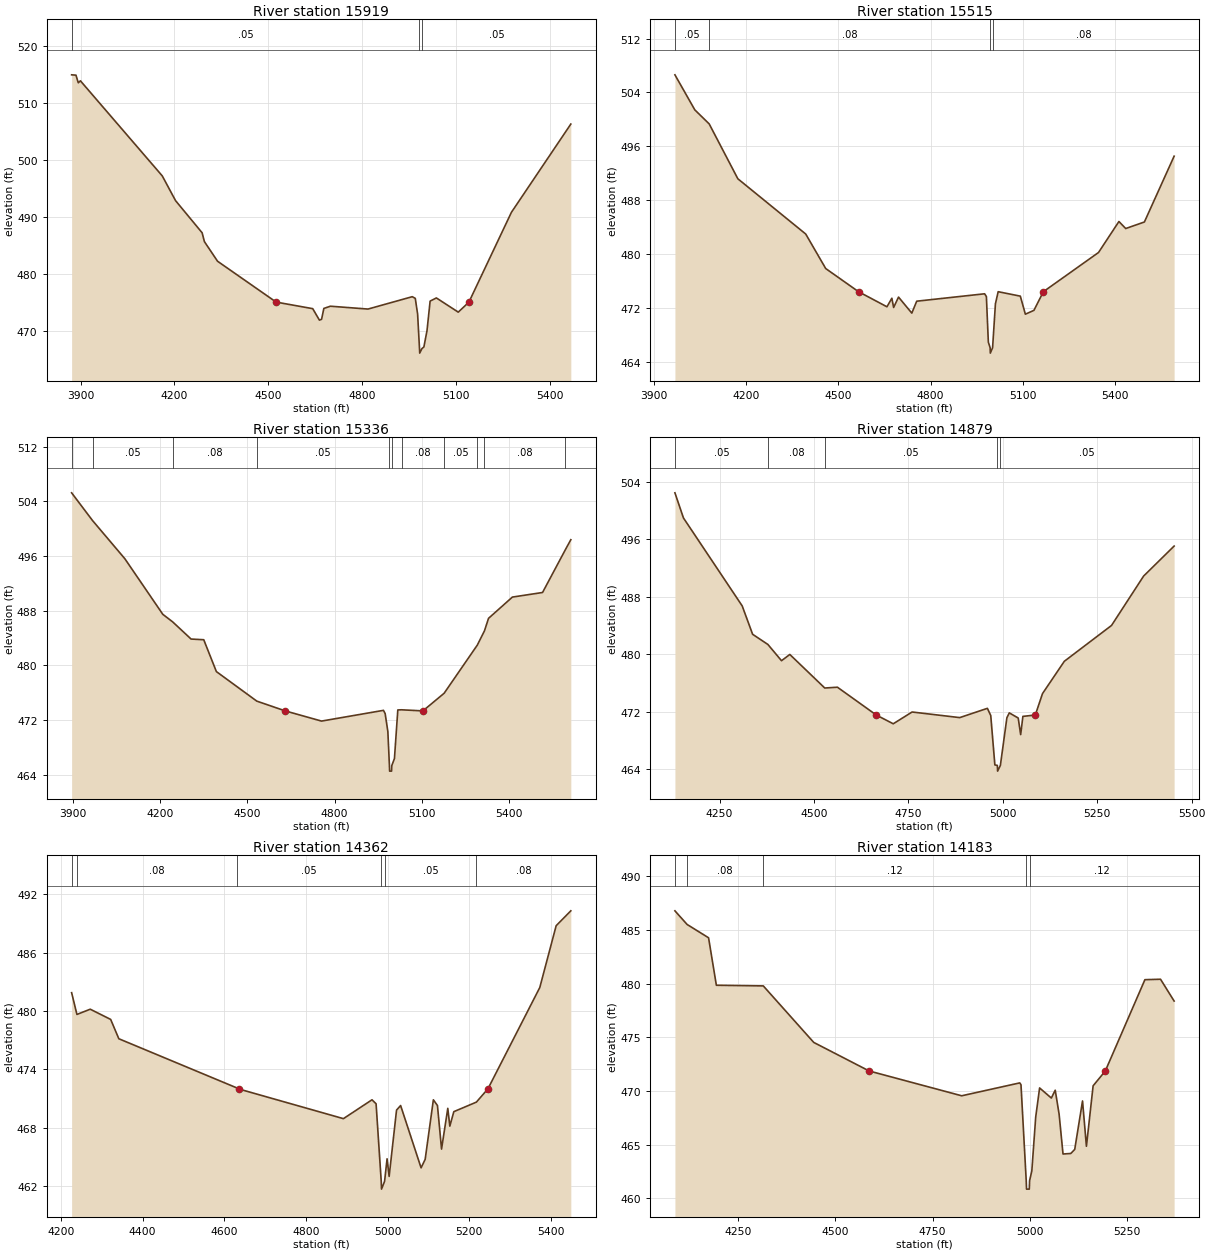
Type RM Length L Ch R = 1,15919,404,404,404
BEGIN DESCRIPTION:
CHAFFIN CREEK 25.0
END DESCRIPTION:
XS GIS Cut Line= 3
      2835725.01      7083175.01      2834925.00      7082425.00
      2834425.00      7082425.00
#Sta/Elev= 30
  3871.5  514.96  3885.4  514.90  3892.8  513.56  3899.6  513.91  4161.4  497.23
  4203.9  492.89  4288.9  487.25  4296.2  485.70  4338.2  482.26  4525.7  475.09
  4642.6  473.94  4664.0  471.93  4670.9  472.07  4678.2  473.98  4699.2  474.37
  4819.4  473.87  4961.0  476.04  4970.6  475.75  4978.1  472.99  4984.1  466.94
  4984.8  466.14  4992.0  466.94  4998.1  467.21  5008.1  470.07  5018.1  475.27
  5038.1  475.82  5108.1  473.33  5142.2  475.09  5278.1  490.84  5468.1  506.32
#Mann=3,-1,0
  3871.5    0.05       0  4984.1    0.03       0  4992.0    0.05       0
Bank Sta=4525.7,5142.2
Exp/Cntr=0.3,0.1

Type RM Length L Ch R = 1,15515,179,179,179
BEGIN DESCRIPTION:
Mapping XS b0f8d691
END DESCRIPTION:
XS GIS Cut Line= 3
      2835658.93      7083031.17      2835153.73      7082140.56
      2834877.88      7081609.67
#Sta/Elev= 30
  3969.2  506.62  4033.8  501.42  4080.6  499.33  4173.6  491.19  4394.3  482.98
  4459.2  477.86  4565.9  474.42  4658.2  472.18  4674.1  473.45  4679.9  472.08
  4695.8  473.62  4739.0  471.24  4754.9  473.01  4975.6  474.11  4981.3  473.70
  4987.7  466.92  4993.5  466.10  4994.1  465.30  5001.5  466.10  5010.7  472.62
  5019.6  474.42  5091.6  473.76  5108.0  471.08  5135.8  471.65  5166.5  474.42
  5345.7  480.24  5412.0  484.84  5434.1  483.80  5494.8  484.77  5591.4  494.54
#Mann=4,-1,0
  3969.2    0.05       0  4080.6    0.08       0  4993.5    0.07       0
  5001.5    0.08       0
Bank Sta=4565.9,5166.5
Exp/Cntr=0.3,0.1

Type RM Length L Ch R = 1,15336,457,457,457
BEGIN DESCRIPTION:
Mapping XS 78fb4895
END DESCRIPTION:
XS GIS Cut Line= 3
      2835799.54      7082968.64      2835268.31      7082005.14
      2834977.09      7081459.09
#Sta/Elev= 30
  3894.4  505.25  3966.3  501.20  4077.7  495.61  4208.4  487.48  4242.4  486.37
  4305.8  483.86  4349.4  483.76  4392.9  479.10  4532.1  474.78  4630.0  473.35
  4755.0  471.86  4968.3  473.43  4974.1  472.96  4983.4  470.34  4988.8  465.34
  4989.5  464.54  4996.2  464.54  4996.9  465.34  5006.1  466.38  5017.7  473.49
  5030.7  473.51  5104.1  473.35  5177.2  475.93  5291.4  482.97  5316.2  485.07
  5330.1  486.89  5412.3  490.00  5516.1  490.67  5595.1  496.96  5613.5  498.39
#Mann=11,-1,0
  3894.4    0.08       0  3966.3    0.05       0  4242.4    0.08       0
  4532.1    0.05       0  4988.8    0.03       0  4996.9    0.05       0
  5030.7    0.08       0  5177.2    0.05       0  5291.4     0.1       0
  5316.2    0.08       0  5595.1    0.05       0
Bank Sta=4630,5104.1
Exp/Cntr=0.3,0.1

Type RM Length L Ch R = 1,14879,517,517,517
BEGIN DESCRIPTION:
CHAFFIN CREEK 23.0
END DESCRIPTION:
XS GIS Cut Line= 3
      2836024.99      7082474.97      2835625.00      7081725.00
      2835374.98      7081324.97
#Sta/Elev= 30
  4131.9  502.44  4154.5  498.94  4310.0  486.70  4337.6  482.75  4378.1  481.33
  4414.1  479.07  4436.1  479.94  4528.6  475.27  4562.2  475.38  4665.0  471.51
  4709.9  470.29  4759.8  471.93  4885.9  471.15  4959.2  472.44  4968.1  471.44
  4979.0  464.56  4985.5  464.50  4986.2  463.70  4993.6  464.50  5010.8  471.13
  5017.2  471.81  5040.8  471.09  5047.3  468.78  5053.2  471.32  5086.1  471.51
  5105.1  474.49  5162.9  478.99  5287.9  483.98  5372.8  490.85  5453.6  495.03
#Mann=5,-1,0
  4131.9    0.05       0  4378.1    0.08       0  4528.6    0.05       0
  4985.5    0.03       0  4993.6    0.05       0
Bank Sta=4665,5086.1
Exp/Cntr=0.3,0.1

Type RM Length L Ch R = 1,14362,179,179,179
BEGIN DESCRIPTION:
Mapping XS e99154f3
END DESCRIPTION:
XS GIS Cut Line= 3
      2835952.34      7082140.58      2835959.29      7081376.67
      2835990.48      7080919.17
#Sta/Elev= 30
  4226.0  481.89  4239.0  479.65  4271.6  480.19  4321.6  479.14  4341.6  477.15
  4630.2  472.10  4634.8  471.99  4891.6  468.93  4961.6  470.87  4971.6  470.46
  4984.2  462.48  4984.9  461.68  4992.4  462.48  4998.5  464.80  5003.6  462.99
  5021.7  469.81  5031.7  470.28  5081.8  463.87  5091.8  464.74  5111.9  470.87
  5121.9  470.28  5131.9  465.80  5147.2  469.99  5152.2  468.16  5162.0  469.65
  5217.2  470.63  5245.4  471.99  5372.5  482.42  5412.6  488.78  5448.5  490.31
#Mann=6,-1,0
  4226.0    0.05       0  4239.0    0.08       0  4630.2    0.05       0
  4984.2    0.04       0  4992.4    0.05       0  5217.2    0.08       0
Bank Sta=4634.8,5245.4
Exp/Cntr=0.3,0.1

Type RM Length L Ch R = 1,14183,462,462,462
BEGIN DESCRIPTION:
Mapping XS ead6376c
END DESCRIPTION:
XS GIS Cut Line= 3
      2836056.51      7082161.36      2836059.98      7081275.98
      2836080.81      7080880.11
#Sta/Elev= 30
  4088.6  486.78  4119.9  485.51  4175.0  484.27  4195.0  479.85  4315.5  479.79
  4445.0  474.53  4587.3  471.87  4825.0  469.56  4974.0  470.76  4977.2  470.59
  4990.6  461.67  4991.4  460.87  4998.5  460.87  4999.3  461.67  5005.0  462.56
  5015.0  467.59  5025.0  470.29  5055.1  469.35  5065.1  470.08  5075.1  467.84
  5085.1  464.14  5105.1  464.19  5115.2  464.57  5135.2  469.08  5145.2  464.86
  5162.4  470.49  5193.7  471.87  5295.4  480.37  5335.5  480.41  5370.4  478.38
#Mann=5,-1,0
  4088.6    0.05       0  4119.9    0.08       0  4315.5    0.12       0
  4990.6    0.07       0  4999.3    0.12       0
Bank Sta=4587.3,5193.7
Exp/Cntr=0.3,0.1