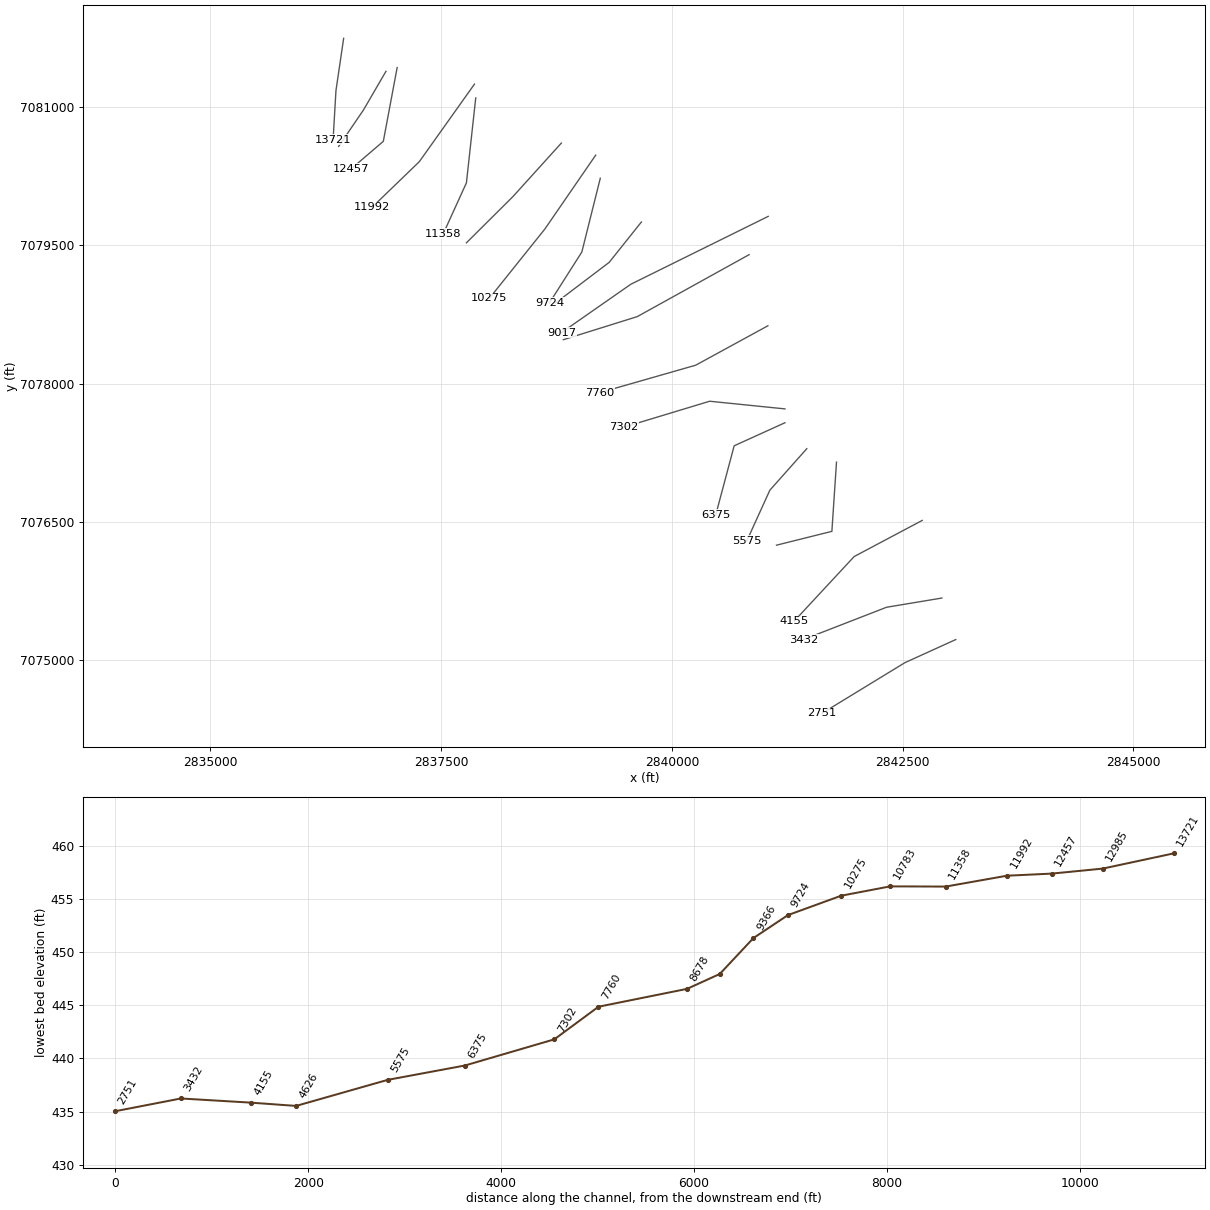
HEC-RAS study CHAFFIN CREEK.prj: CHAFFIN CREEK Base Level Engineering

--- CHAFFIN CREEK.g01 (geometry) --- (continued)

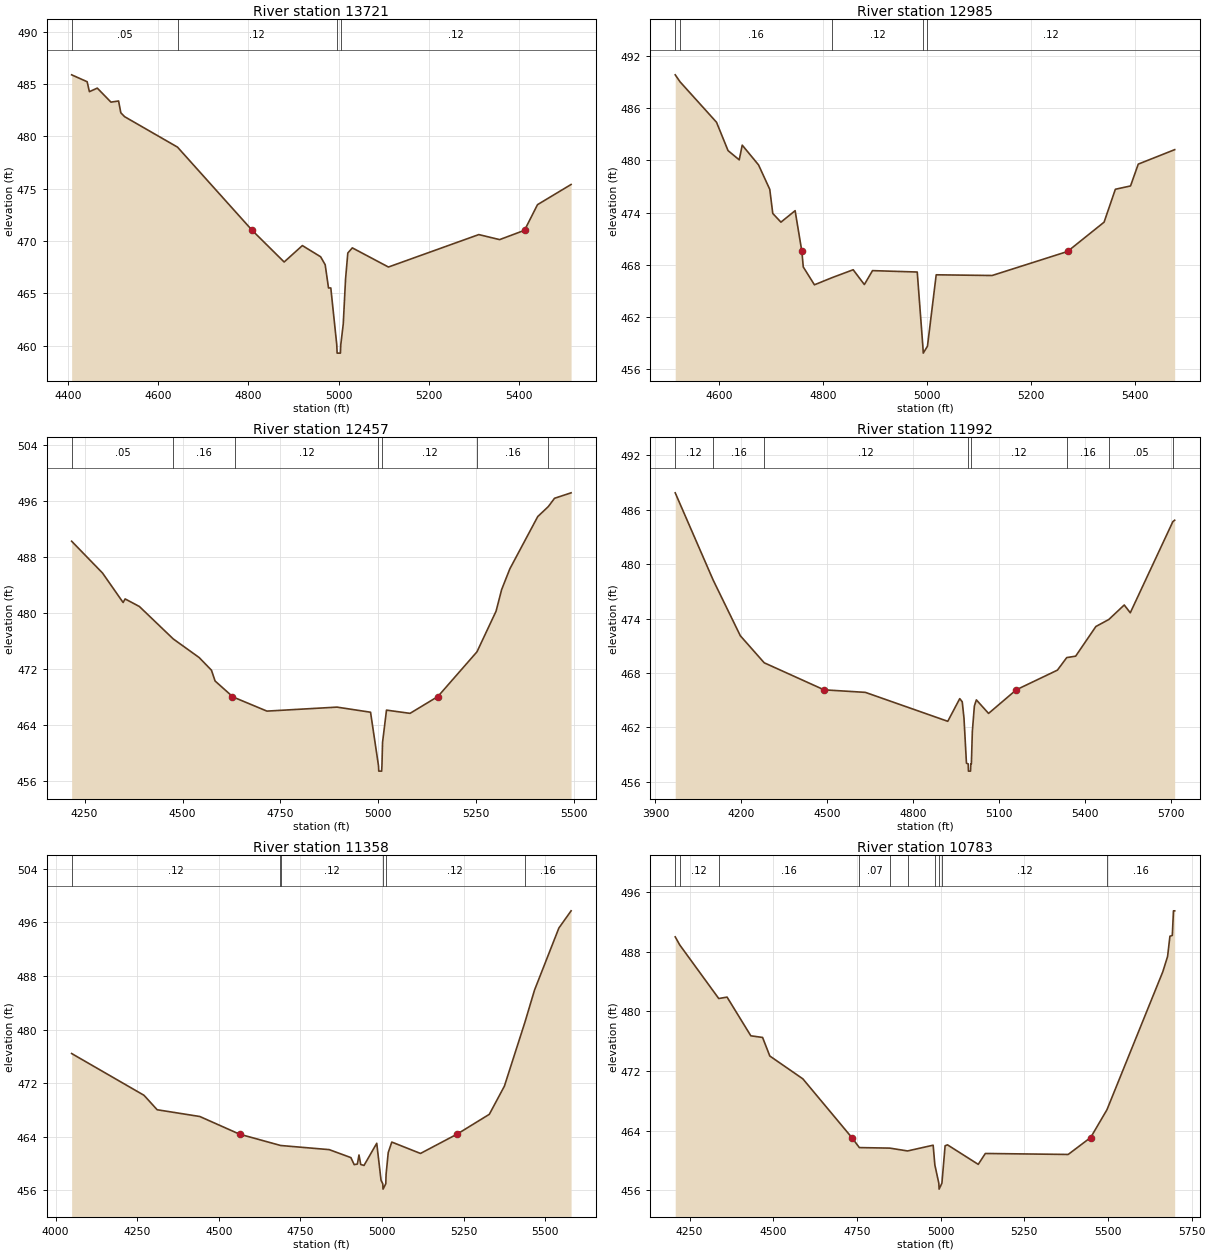
Type RM Length L Ch R = 1,13721,736,736,736
BEGIN DESCRIPTION:
Mapping XS 3f89ab82
END DESCRIPTION:
XS GIS Cut Line= 3
      2836445.40      7081741.29      2836362.06      7081175.28
      2836330.82      7080640.60
#Sta/Elev= 30
  4407.9  485.88  4442.3  485.22  4447.3  484.27  4464.8  484.61  4495.1  483.27
  4512.0  483.38  4517.0  482.25  4525.4  481.88  4642.7  478.97  4808.2  471.02
  4879.2  467.99  4919.6  469.56  4960.1  468.49  4970.2  467.73  4977.6  465.51
  4982.7  465.51  4995.9  460.08  4996.7  459.28  5004.0  459.28  5004.8  460.08
  5010.3  462.07  5015.4  466.36  5020.4  468.85  5030.4  469.34  5110.5  467.51
  5310.9  470.61  5357.1  470.13  5412.3  471.02  5441.1  473.47  5515.6  475.40
#Mann=4,-1,0
  4407.9    0.05       0  4642.7    0.12       0  4995.9    0.07       0
  5004.8    0.12       0
Bank Sta=4808.2,5412.3
Exp/Cntr=0.3,0.1

Type RM Length L Ch R = 1,12985,528,528,528
BEGIN DESCRIPTION:
CHAFFIN CREEK 20.0
END DESCRIPTION:
XS GIS Cut Line= 3
      2836903.55      7081383.69      2836660.49      7080965.42
      2836391.52      7080570.60
#Sta/Elev= 30
  4515.2  489.83  4524.6  489.02  4594.7  484.38  4616.9  481.12  4638.4  480.06
  4644.2  481.75  4675.6  479.48  4697.2  476.67  4703.0  473.90  4718.7  472.90
  4746.0  474.22  4759.0  469.53  4761.7  467.75  4783.2  465.70  4817.4  466.53
  4857.8  467.43  4879.3  465.73  4895.0  467.33  4981.1  467.17  4991.9  458.65
  4992.7  457.85  5000.8  458.65  5017.6  466.85  5125.3  466.77  5270.4  469.53
  5340.8  472.90  5362.5  476.68  5391.7  477.06  5406.6  479.57  5476.7  481.23
#Mann=5,-1,0
  4515.2    0.05       0  4524.6    0.16       0  4817.4    0.12       0
  4991.9    0.07       0  5000.8    0.12       0
Bank Sta=4759,5270.4
Exp/Cntr=0.3,0.1

Type RM Length L Ch R = 1,12457,465,465,465
BEGIN DESCRIPTION:
CHAFFIN CREEK 19.0
END DESCRIPTION:
XS GIS Cut Line= 3
      2837024.99      7081424.96      2836875.00      7080625.00
      2836524.99      7080324.99
#Sta/Elev= 30
  4216.9  490.21  4295.7  485.67  4348.3  481.46  4353.4  481.97  4389.8  480.89
  4476.2  476.26  4542.4  473.60  4573.8  471.79  4583.1  470.25  4627.5  468.03
  4633.1  467.87  4715.4  465.95  4894.3  466.52  4979.9  465.79  5000.1  458.18
  5000.9  457.38  5008.2  457.38  5009.0  458.18  5010.5  461.47  5020.6  466.09
  5080.7  465.63  5151.7  468.03  5251.6  474.42  5300.3  480.22  5314.5  483.30
  5335.4  486.26  5406.7  493.73  5433.7  495.16  5449.5  496.34  5491.8  497.12
#Mann=7,-1,0
  4216.9    0.05       0  4476.2    0.16       0  4633.1    0.12       0
  5000.1    0.07       0  5009.0    0.12       0  5251.6    0.16       0
  5433.7    0.12       0
Bank Sta=4627.5,5151.7
Exp/Cntr=0.3,0.1

Type RM Length L Ch R = 1,11992,634,634,634
BEGIN DESCRIPTION:
CHAFFIN CREEK 18.0
END DESCRIPTION:
XS GIS Cut Line= 3
      2837862.09      7081244.76      2837264.84      7080404.45
      2836752.04      7079908.97
#Sta/Elev= 30
  3969.2  487.85  4101.6  478.24  4196.5  472.10  4279.9  469.12  4488.8  466.14
  4633.1  465.86  4920.9  462.67  4962.7  465.17  4971.4  464.82  4977.5  463.02
  4986.1  458.05  4992.2  457.98  4993.0  457.18  5000.4  457.18  5001.3  457.98
  5003.3  457.98  5006.7  461.56  5013.8  464.36  5020.8  465.03  5063.3  463.54
  5160.0  466.14  5303.8  468.31  5336.2  469.69  5367.4  469.85  5438.1  473.12
  5483.2  473.89  5537.1  475.49  5558.2  474.63  5706.9  484.68  5713.2  484.83
#Mann=8,-1,0
  3969.2    0.12       0  4101.6    0.16       0  4279.9    0.12       0
  4992.2    0.07       0  5001.3    0.12       0  5336.2    0.16       0
  5483.2    0.05       0  5706.9    0.16       0
Bank Sta=4488.8,5160
Exp/Cntr=0.3,0.1

Type RM Length L Ch R = 1,11358,575,575,575
BEGIN DESCRIPTION:
CHAFFIN CREEK 17.0
END DESCRIPTION:
XS GIS Cut Line= 3
      2837875.95      7081095.39      2837775.00      7080175.00
      2837524.99      7079624.97
#Sta/Elev= 30
  4049.0  476.42  4270.7  470.18  4311.0  468.02  4441.7  467.01  4563.5  464.37
  4688.6  462.69  4689.0  462.68  4838.2  462.06  4904.5  460.87  4914.6  459.82
  4924.3  459.90  4929.3  461.26  4934.7  459.84  4944.7  459.70  4983.7  463.01
  4996.9  457.48  5002.2  456.96  5003.0  456.16  5011.4  456.96  5012.3  458.35
  5018.9  461.62  5029.8  463.19  5117.7  461.49  5229.6  464.37  5328.6  467.34
  5374.8  471.55  5437.6  481.09  5467.0  485.89  5541.7  495.17  5579.1  497.74
#Mann=6,-1,0
  4049.0    0.12       0  4688.6    0.05       0  4689.0    0.12       0
  5002.2    0.07       0  5011.4    0.12       0  5437.6    0.16       0
Bank Sta=4563.5,5229.6
Exp/Cntr=0.3,0.1

Type RM Length L Ch R = 1,10783,508,508,508
BEGIN DESCRIPTION:
CHAFFIN CREEK 16.0
END DESCRIPTION:
XS GIS Cut Line= 3
      2838803.02      7080605.82      2838278.73      7080025.98
      2837774.98      7079524.98
#Sta/Elev= 30
  4207.1  490.01  4220.7  488.92  4337.1  481.74  4362.0  481.93  4433.0  476.74
  4468.1  476.52  4489.7  474.03  4588.4  470.97  4734.7  463.10  4757.2  461.75
  4848.1  461.68  4901.2  461.30  4977.7  462.07  4982.8  459.42  4994.6  456.98
  4995.5  456.18  5003.9  456.98  5013.4  461.99  5020.5  462.12  5112.4  459.50
  5133.6  460.96  5381.1  460.83  5448.3  463.10  5497.0  466.83  5663.9  485.34
  5678.1  487.38  5685.1  490.09  5692.2  490.20  5695.7  493.50  5699.3  493.50
#Mann=10,-1,0
  4207.1    0.16       0  4220.7    0.12       0  4337.1    0.16       0
  4757.2    0.07       0  4848.1    0.12       0  4901.2    0.07       0
  4982.8    0.12       0  4994.6    0.07       0  5003.9    0.12       0
  5497.0    0.16       0
Bank Sta=4734.7,5448.3
Exp/Cntr=0.3,0.1

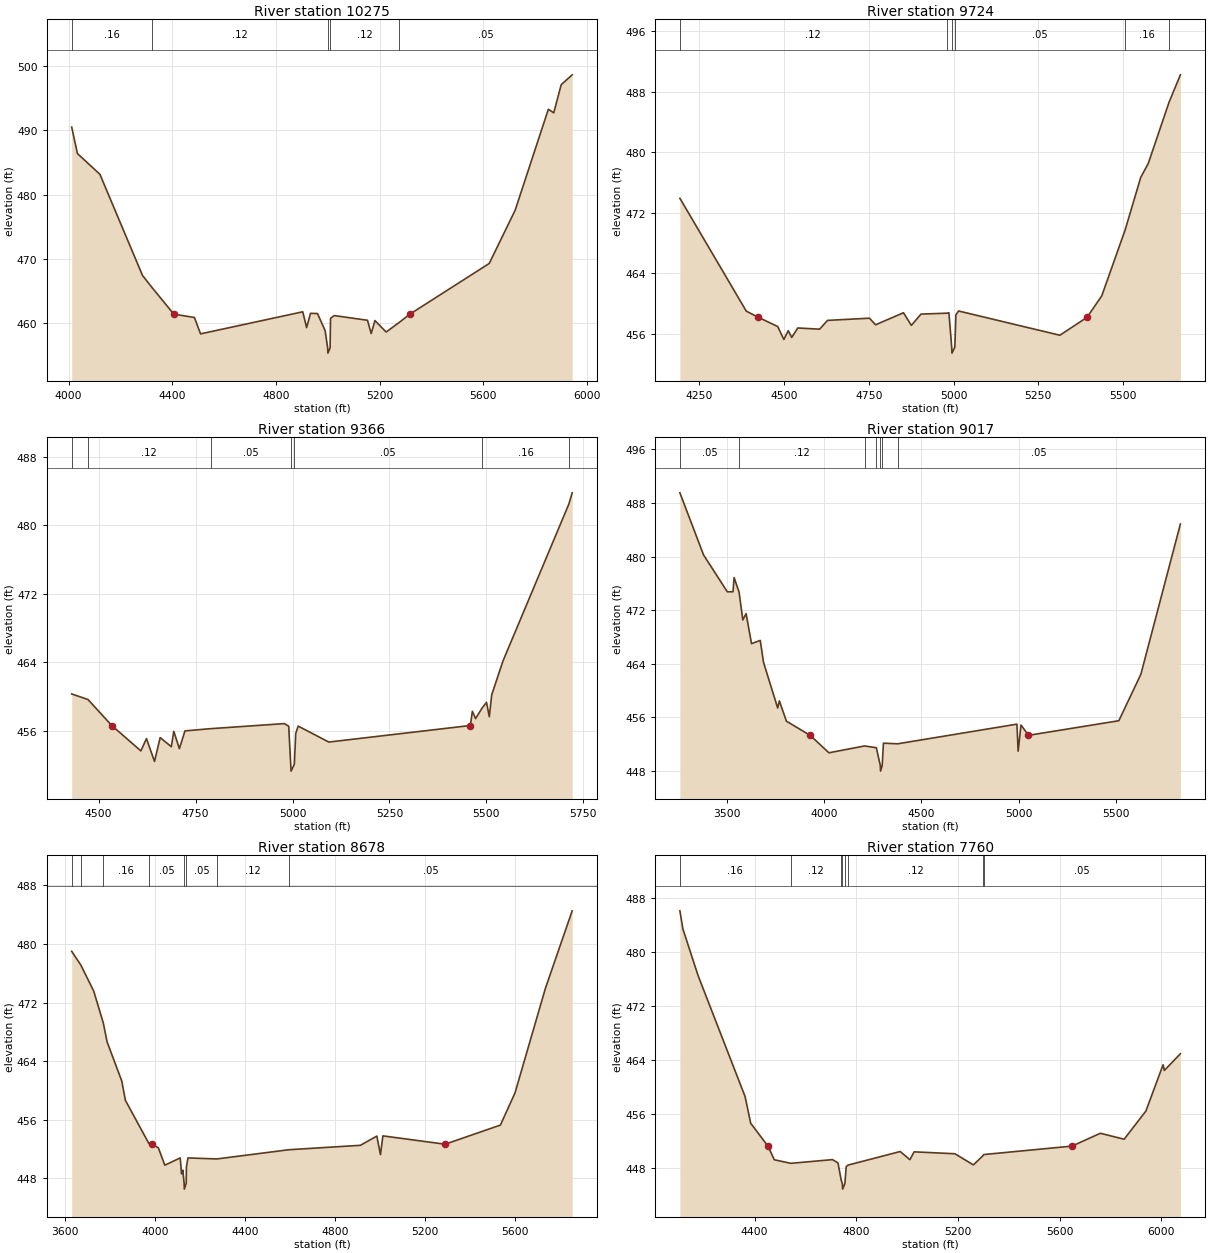
Type RM Length L Ch R = 1,10275,551,551,551
BEGIN DESCRIPTION:
CHAFFIN CREEK 15.0
END DESCRIPTION:
XS GIS Cut Line= 3
      2839174.97      7080474.96      2838625.00      7079675.00
      2838025.03      7078925.04
#Sta/Elev= 30
  4012.0  490.51  4034.3  486.39  4120.9  483.16  4285.3  467.40  4323.0  465.47
  4406.1  461.37  4485.5  460.86  4509.2  458.30  4903.6  461.74  4918.5  459.27
  4933.4  461.50  4960.4  461.47  4990.0  458.80  4999.7  456.10  5000.6  455.30
  5009.0  456.10  5010.8  460.73  5025.2  461.15  5153.3  460.42  5167.7  458.35
  5182.1  460.37  5225.3  458.59  5274.4  460.04  5316.9  461.37  5623.1  469.27
  5723.1  477.56  5851.2  493.29  5872.0  492.74  5900.8  497.12  5943.2  498.66
#Mann=5,-1,0
  4012.0    0.16       0  4323.0    0.12       0  4999.7    0.07       0
  5009.0    0.12       0  5274.4    0.05       0
Bank Sta=4406.1,5316.9
Exp/Cntr=0.3,0.1

Type RM Length L Ch R = 1,9724,358,358,358
BEGIN DESCRIPTION:
CHAFFIN CREEK 14.0
END DESCRIPTION:
XS GIS Cut Line= 3
      2839225.00      7080225.02      2839025.00      7079425.00
      2838674.98      7078874.96
#Sta/Elev= 30
  4192.7  473.91  4388.6  459.02  4424.4  458.20  4481.3  456.99  4499.4  455.28
  4512.3  456.44  4522.6  455.55  4540.6  456.80  4605.0  456.64  4628.2  457.80
  4751.9  458.09  4770.0  457.22  4852.4  458.81  4875.6  457.14  4904.0  458.63
  4980.0  458.75  4986.4  458.80  4994.6  454.28  4995.5  453.48  5003.9  454.28
  5007.0  458.52  5014.8  459.04  5313.7  455.84  5393.8  458.20  5437.3  461.03
  5506.4  469.75  5552.4  476.68  5574.4  478.49  5635.6  486.55  5669.3  490.20
#Mann=6,-1,0
  4192.7    0.12       0  4980.0    0.05       0  4994.6    0.03       0
  5003.9    0.05       0  5506.4    0.16       0  5635.6    0.05       0
Bank Sta=4424.4,5393.8
Exp/Cntr=0.3,0.1

Type RM Length L Ch R = 1,9366,349,349,349
BEGIN DESCRIPTION:
Mapping XS 5564b61e
END DESCRIPTION:
XS GIS Cut Line= 3
      2839670.21      7079750.79      2839321.26      7079313.30
      2838738.97      7078871.38
#Sta/Elev= 30
  4430.6  460.32  4472.7  459.67  4533.9  456.64  4609.0  453.68  4623.4  455.12
  4644.2  452.45  4658.7  455.23  4687.5  454.17  4693.9  455.96  4708.3  453.94
  4722.7  456.01  4788.6  456.27  4978.9  456.86  4990.2  456.56  4995.4  452.12
  4996.3  451.32  5004.7  452.12  5008.3  455.70  5014.6  456.57  5093.6  454.71
  5458.6  456.64  5463.8  458.30  5472.1  457.44  5488.7  458.66  5500.2  459.34
  5507.5  457.67  5513.7  460.22  5542.8  464.17  5712.8  482.48  5721.2  483.77
#Mann=7,-1,0
  4430.6    0.16       0  4472.7    0.12       0  4788.6    0.05       0
  4995.4    0.03       0  5004.7    0.05       0  5488.7    0.16       0
  5712.8    0.05       0
Bank Sta=4533.9,5458.6
Exp/Cntr=0.3,0.1

Type RM Length L Ch R = 1,9017,339,339,339
BEGIN DESCRIPTION:
double CHAFFIN CREEK 13.0
END DESCRIPTION:
XS GIS Cut Line= 3
      2841043.80      7079811.69      2839556.02      7079076.20
      2838805.32      7078552.27
#Sta/Elev= 30
  3257.1  489.52  3378.9  480.24  3501.2  474.73  3530.4  474.74  3536.0  476.86
  3561.8  474.66  3580.8  470.53  3597.7  471.48  3625.7  466.99  3670.6  467.47
  3687.4  464.19  3760.3  457.37  3768.9  458.44  3805.2  455.40  3927.2  453.29
  4024.0  450.68  4207.3  451.70  4267.8  451.44  4288.5  448.74  4289.4  447.94
  4297.8  448.74  4304.4  452.12  4377.1  452.02  4991.2  454.96  4997.4  450.92
  5012.2  454.83  5050.7  453.29  5515.5  455.47  5628.9  462.41  5832.2  484.86
#Mann=7,-1,0
  3257.1    0.05       0  3561.8    0.12       0  4207.3    0.05       0
  4267.8    0.07       0  4288.5    0.03       0  4297.8    0.07       0
  4377.1    0.05       0
Bank Sta=3927.2,5050.7
Exp/Cntr=0.3,0.1

Type RM Length L Ch R = 1,8678,918,918,918
BEGIN DESCRIPTION:
double CHAFFIN CREEK 12.0
END DESCRIPTION:
XS GIS Cut Line= 3
      2840836.87      7079396.62      2839625.00      7078725.00
      2838824.99      7078475.00
#Sta/Elev= 30
  3628.6  479.00  3669.4  477.12  3726.4  473.58  3769.0  469.23  3785.9  466.64
  3851.1  461.30  3867.2  458.66  3971.3  452.78  3986.0  452.67  4013.7  452.18
  4042.3  449.81  4110.9  450.80  4116.7  448.62  4122.4  449.13  4128.1  447.34
  4129.0  446.54  4137.4  447.34  4138.4  449.58  4145.2  450.80  4273.2  450.66
  4594.2  451.92  4911.2  452.52  4984.4  453.78  5000.4  451.25  5011.3  453.81
  5287.6  452.67  5533.3  455.28  5598.2  459.67  5733.4  473.96  5852.3  484.53
#Mann=8,-1,0
  3628.6    0.05       0  3669.4    0.12       0  3769.0    0.16       0
  3971.3    0.05       0  4128.1    0.03       0  4137.4    0.05       0
  4273.2    0.12       0  4594.2    0.05       0
Bank Sta=3986,5287.6
Exp/Cntr=0.3,0.1

Type RM Length L Ch R = 1,7760,458,458,458
BEGIN DESCRIPTION:
double CHAFFIN CREEK 11.0
END DESCRIPTION:
XS GIS Cut Line= 3
      2841040.04      7078625.82      2840258.76      7078198.72
      2839222.33      7077901.85
#Sta/Elev= 30
  4106.3  486.07  4118.1  483.39  4177.8  476.49  4362.8  458.56  4384.7  454.62
  4452.7  451.23  4477.6  449.21  4542.4  448.68  4706.3  449.23  4728.1  448.75
  4740.8  446.17  4745.3  445.66  4746.3  444.86  4755.2  445.66  4760.3  448.18
  4767.8  448.42  4972.8  450.43  5011.0  449.22  5027.5  450.38  5187.8  450.10
  5260.7  448.45  5298.3  449.81  5301.4  449.98  5648.6  451.23  5760.0  453.13
  5853.6  452.25  5939.1  456.42  6006.7  463.27  6011.9  462.44  6074.8  464.91
#Mann=8,-1,0
  4106.3    0.16       0  4542.4    0.12       0  4740.8    0.05       0
  4745.3    0.07       0  4755.2    0.05       0  4767.8    0.12       0
  5298.3    0.07       0  5301.4    0.05       0
Bank Sta=4452.7,5648.6
Exp/Cntr=0.3,0.1

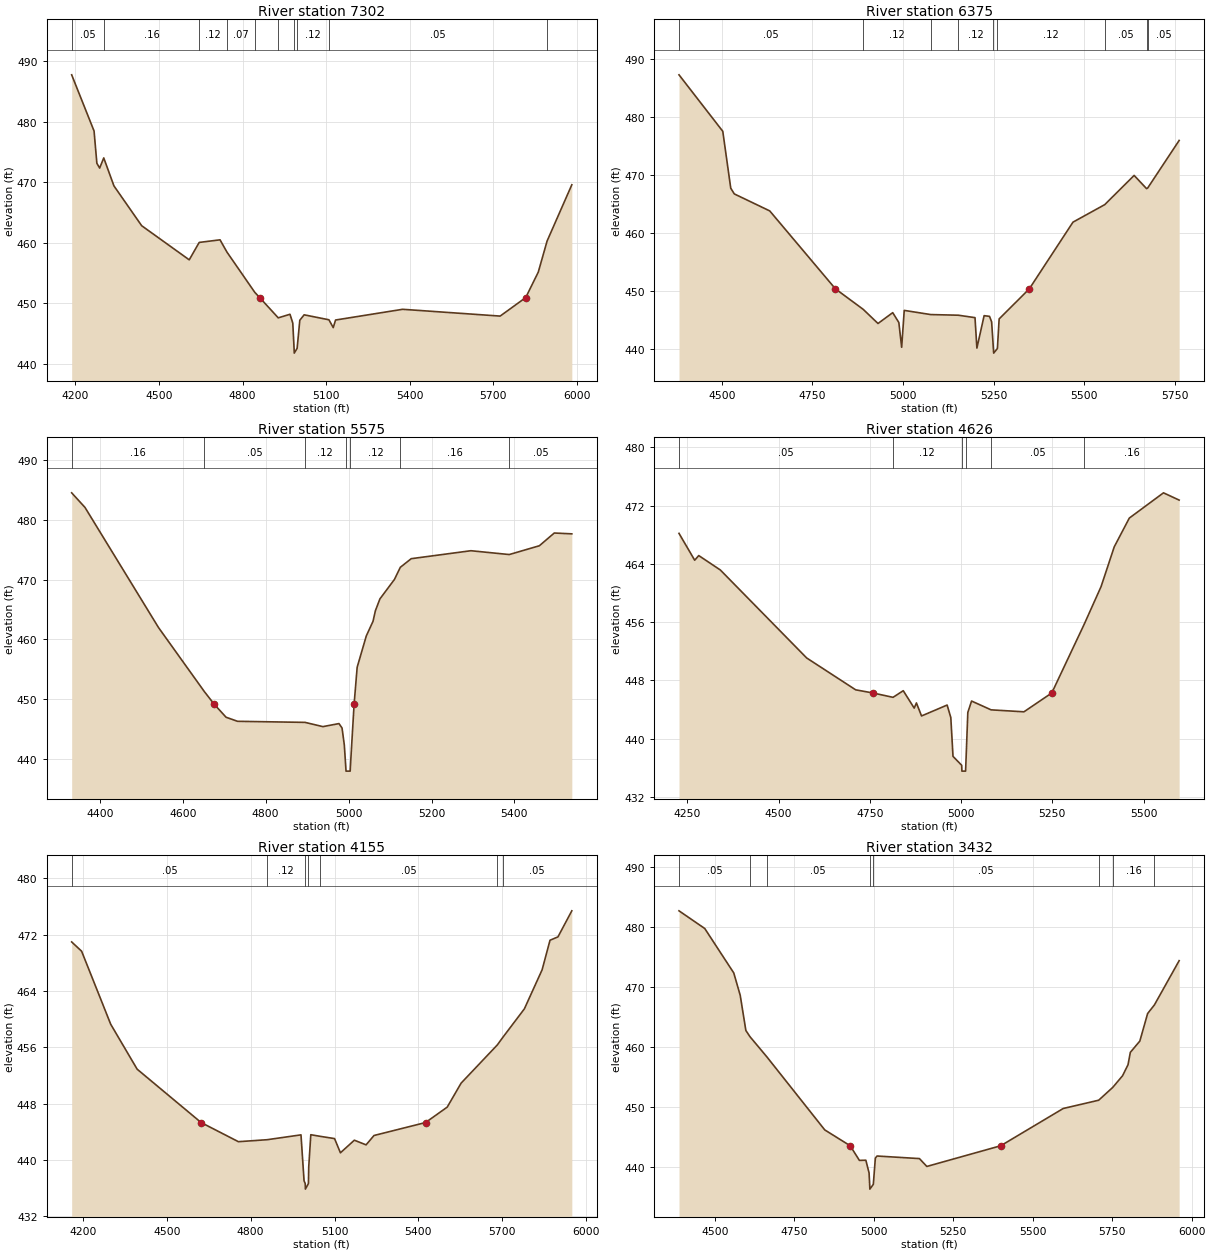
Type RM Length L Ch R = 1,7302,927,927,927
BEGIN DESCRIPTION:
CHAFFIN CREEK 10.0
END DESCRIPTION:
XS GIS Cut Line= 3
      2841225.01      7077725.00      2840409.81      7077808.09
      2839474.96      7077524.99
#Sta/Elev= 30
  4186.3  487.70  4266.7  478.43  4276.8  473.11  4286.8  472.32  4301.5  473.99
  4338.2  469.37  4437.7  462.81  4608.5  457.18  4644.3  460.05  4719.1  460.48
  4744.1  458.45  4843.9  451.82  4861.6  450.95  4928.2  447.61  4970.3  448.20
  4980.4  446.75  4985.0  442.59  4985.7  441.79  4996.0  442.59  5005.6  447.21
  5021.2  448.11  5110.2  447.29  5125.7  446.00  5134.0  447.25  5374.9  449.02
  5725.1  447.90  5816.9  450.95  5862.0  455.15  5893.7  460.28  5982.5  469.56
#Mann=10,-1,0
  4186.3    0.05       0  4301.5    0.16       0  4644.3    0.12       0
  4744.1    0.07       0  4843.9    0.05       0  4928.2    0.12       0
  4985.0    0.07       0  4996.0    0.12       0  5110.2    0.05       0
  5893.7    0.16       0
Bank Sta=4861.6,5816.9
Exp/Cntr=0.3,0.1

Type RM Length L Ch R = 1,6375,800,800,800
BEGIN DESCRIPTION:
double CHAFFIN CREEK 9.0
END DESCRIPTION:
XS GIS Cut Line= 3
      2841224.96      7077574.98      2840675.00      7077325.00
      2840475.01      7076575.02
#Sta/Elev= 30
  4381.9  487.33  4502.7  477.59  4524.7  467.78  4534.5  466.79  4632.3  463.86
  4813.7  450.41  4890.1  446.89  4931.1  444.44  4971.7  446.31  4988.6  444.61
  4996.4  440.34  5003.5  446.70  5076.7  445.98  5152.6  445.87  5198.8  445.45
  5204.0  440.20  5224.0  445.79  5238.9  445.67  5244.7  444.72  5249.5  440.13
  5250.3  439.33  5260.6  440.13  5265.4  445.23  5348.6  450.41  5469.2  461.92
  5556.8  464.94  5638.0  469.98  5672.3  467.70  5675.4  467.81  5762.2  476.01
#Mann=9,-1,0
  4381.9    0.05       0  4890.1    0.12       0  5076.7    0.16       0
  5152.6    0.12       0  5249.5    0.07       0  5260.6    0.12       0
  5556.8    0.05       0  5672.3    0.16       0  5675.4    0.05       0
Bank Sta=4813.7,5348.6
Exp/Cntr=0.3,0.1

Type RM Length L Ch R = 1,5575,949,949,949
BEGIN DESCRIPTION:
CHAFFIN CREEK 8.0
END DESCRIPTION:
XS GIS Cut Line= 3
      2841461.48      7077293.78      2841061.46      7076843.75
      2840811.45      7076293.72
#Sta/Elev= 30
  4332.1  484.51  4364.2  482.07  4541.5  461.99  4652.1  451.28  4675.8  449.17
  4704.5  446.99  4732.1  446.31  4894.9  446.13  4938.0  445.42  4976.8  445.93
  4984.2  445.19  4989.7  442.35  4993.1  438.78  4993.8  437.98  5003.8  437.98
  5004.4  438.78  5013.3  449.17  5020.7  455.35  5042.7  460.58  5058.9  463.02
  5064.7  464.81  5075.6  466.78  5110.5  470.02  5124.8  472.06  5151.1  473.50
  5295.0  474.83  5387.5  474.19  5460.1  475.66  5496.1  477.79  5538.4  477.65
#Mann=7,-1,0
  4332.1    0.16       0  4652.1    0.05       0  4894.9    0.12       0
  4993.1    0.07       0  5004.4    0.12       0  5124.8    0.16       0
  5387.5    0.05       0
Bank Sta=4675.8,5013.3
Exp/Cntr=0.3,0.1

Type RM Length L Ch R = 1,4626,471,471,471
BEGIN DESCRIPTION:
CHAFFIN CREEK 7.0
END DESCRIPTION:
XS GIS Cut Line= 3
      2841783.33      7077147.92      2841733.33      7076397.92
      2841133.36      7076247.92
#Sta/Elev= 30
  4227.3  468.20  4270.3  464.51  4281.4  465.15  4340.5  463.17  4577.0  451.08
  4711.3  446.70  4758.4  446.27  4813.6  445.67  4841.6  446.58  4871.6  444.19
  4877.7  444.90  4891.7  443.11  4961.8  444.61  4971.9  442.89  4977.9  437.56
  5001.7  436.33  5002.3  435.53  5012.3  435.53  5013.0  436.33  5018.5  443.60
  5028.8  445.16  5082.2  443.95  5172.2  443.68  5248.5  446.27  5337.0  455.68
  5383.5  460.88  5419.6  466.35  5460.9  470.30  5554.5  473.77  5597.4  472.77
#Mann=6,-1,0
  4227.3    0.05       0  4813.6    0.12       0  5001.7    0.07       0
  5013.0    0.12       0  5082.2    0.05       0  5337.0    0.16       0
Bank Sta=4758.4,5248.5
Exp/Cntr=0.3,0.1

Type RM Length L Ch R = 1,4155,723,723,723
BEGIN DESCRIPTION:
CHAFFIN CREEK 6.0
END DESCRIPTION:
XS GIS Cut Line= 3
      2842711.89      7076516.43      2841975.00      7076125.00
      2841324.97      7075424.97
#Sta/Elev= 30
  4159.5  470.96  4195.1  469.64  4299.3  459.26  4393.8  452.88  4622.8  445.30
  4756.1  442.58  4858.8  442.86  4980.1  443.55  4991.1  437.02  4995.2  436.64
  4995.9  435.84  5006.7  436.64  5007.8  438.99  5015.2  443.57  5047.4  443.35
  5100.2  443.02  5121.2  441.00  5171.0  442.79  5213.0  442.13  5241.4  443.46
  5425.8  445.30  5503.3  447.49  5553.1  450.90  5682.7  456.33  5701.7  457.37
  5779.4  461.45  5842.9  467.00  5871.2  471.20  5899.6  471.68  5949.2  475.38
#Mann=7,-1,0
  4159.5    0.05       0  4858.8    0.12       0  4995.2    0.07       0
  5006.7    0.12       0  5047.4    0.05       0  5682.7    0.16       0
  5701.7    0.05       0
Bank Sta=4622.8,5425.8
Exp/Cntr=0.3,0.1

Type RM Length L Ch R = 1,3432,681,681,681
BEGIN DESCRIPTION:
CHAFFIN CREEK 5.0
END DESCRIPTION:
XS GIS Cut Line= 3
      2842925.00      7075675.00      2842325.00      7075575.00
      2841425.03      7075225.01
#Sta/Elev= 30
  4386.9  482.62  4468.0  479.67  4559.2  472.27  4579.5  468.55  4597.3  462.68
  4610.1  461.65  4663.2  458.29  4845.6  446.10  4925.6  443.46  4954.6  441.02
  4974.9  441.05  4985.0  438.94  4986.9  437.03  4987.5  436.23  4998.4  437.03
  5004.8  441.40  5010.1  441.75  5143.5  441.32  5166.8  440.01  5399.4  443.46
  5596.0  449.67  5707.6  451.05  5751.9  453.19  5782.6  455.12  5799.9  456.96
  5807.2  459.03  5837.1  460.91  5861.6  465.50  5883.0  466.94  5960.8  474.31
#Mann=8,-1,0
  4386.9    0.05       0  4610.1    0.16       0  4663.2    0.05       0
  4986.9    0.03       0  4998.4    0.05       0  5707.6    0.12       0
  5751.9    0.16       0  5883.0    0.05       0
Bank Sta=4925.6,5399.4
Exp/Cntr=0.3,0.1

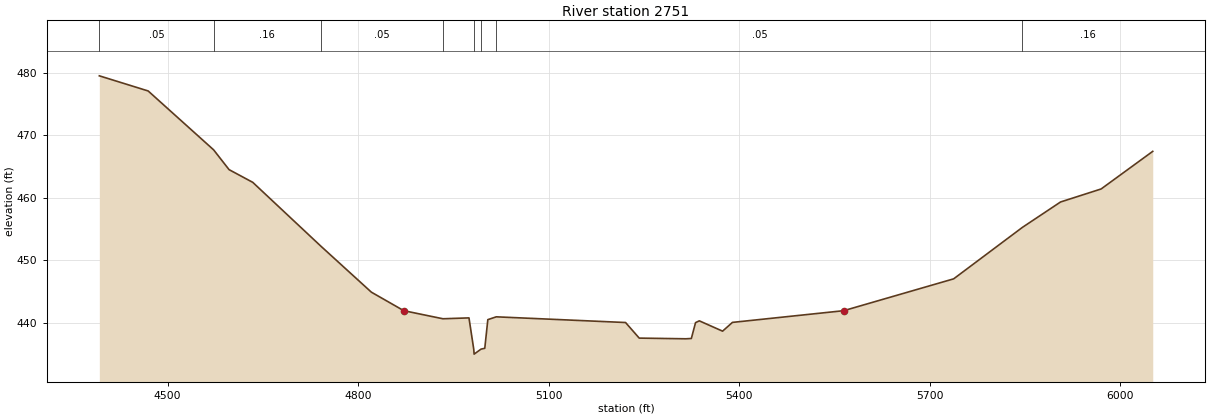
Type RM Length L Ch R = 1,2751,698,698,698
BEGIN DESCRIPTION:
CHAFFIN CREEK 4.0
END DESCRIPTION:
XS GIS Cut Line= 3
      2843074.97      7075224.99      2842525.00      7074975.00
      2841624.97      7074424.98
#Sta/Elev= 30
  4392.6  479.50  4469.5  477.08  4572.6  467.67  4596.9  464.51  4634.2  462.48
  4741.6  452.27  4821.0  444.93  4872.1  441.97  4933.7  440.68  4974.7  440.82
  4982.2  435.83  4982.8  435.03  4993.7  435.83  4999.6  435.96  5004.4  440.54
  5017.7  440.99  5221.3  440.08  5242.8  437.59  5316.1  437.48  5324.9  437.53
  5331.5  440.06  5337.4  440.35  5374.1  438.70  5389.6  440.10  5564.8  441.97
  5738.0  447.06  5846.2  455.28  5906.3  459.34  5970.2  461.42  6051.5  467.43
#Mann=8,-1,0
  4392.6    0.05       0  4572.6    0.16       0  4741.6    0.05       0
  4933.7    0.16       0  4982.2    0.07       0  4993.7    0.16       0
  5017.7    0.05       0  5846.2    0.16       0
Bank Sta=4872.1,5564.8
Exp/Cntr=0.3,0.1