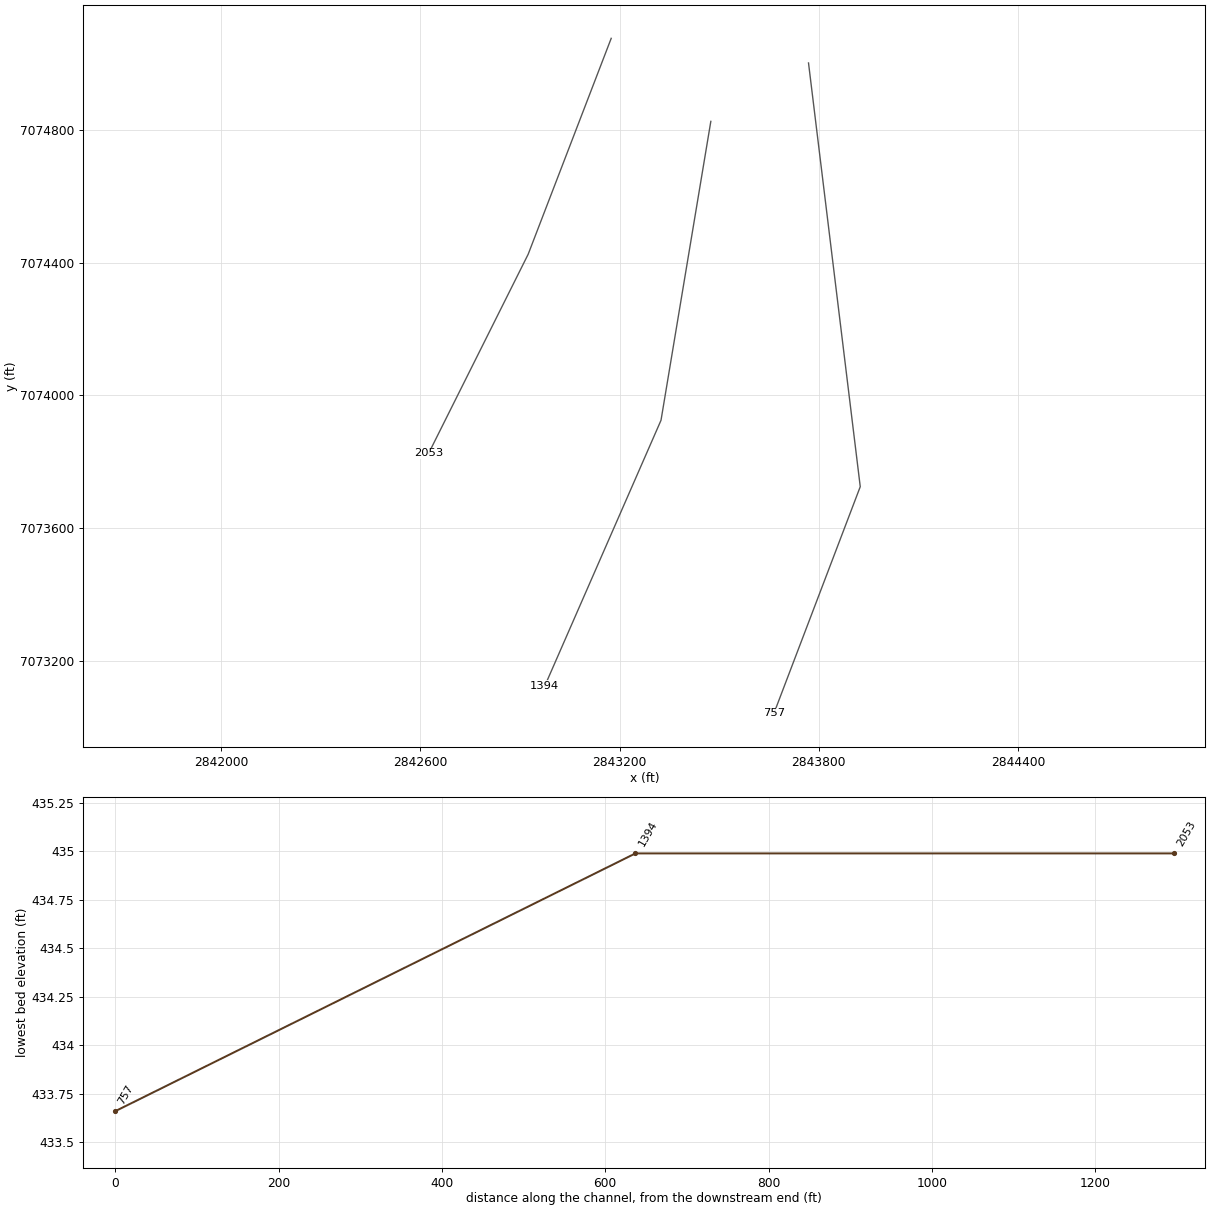
HEC-RAS study CHAFFIN CREEK.prj: CHAFFIN CREEK Base Level Engineering

--- CHAFFIN CREEK.g01 (geometry) --- (continued)

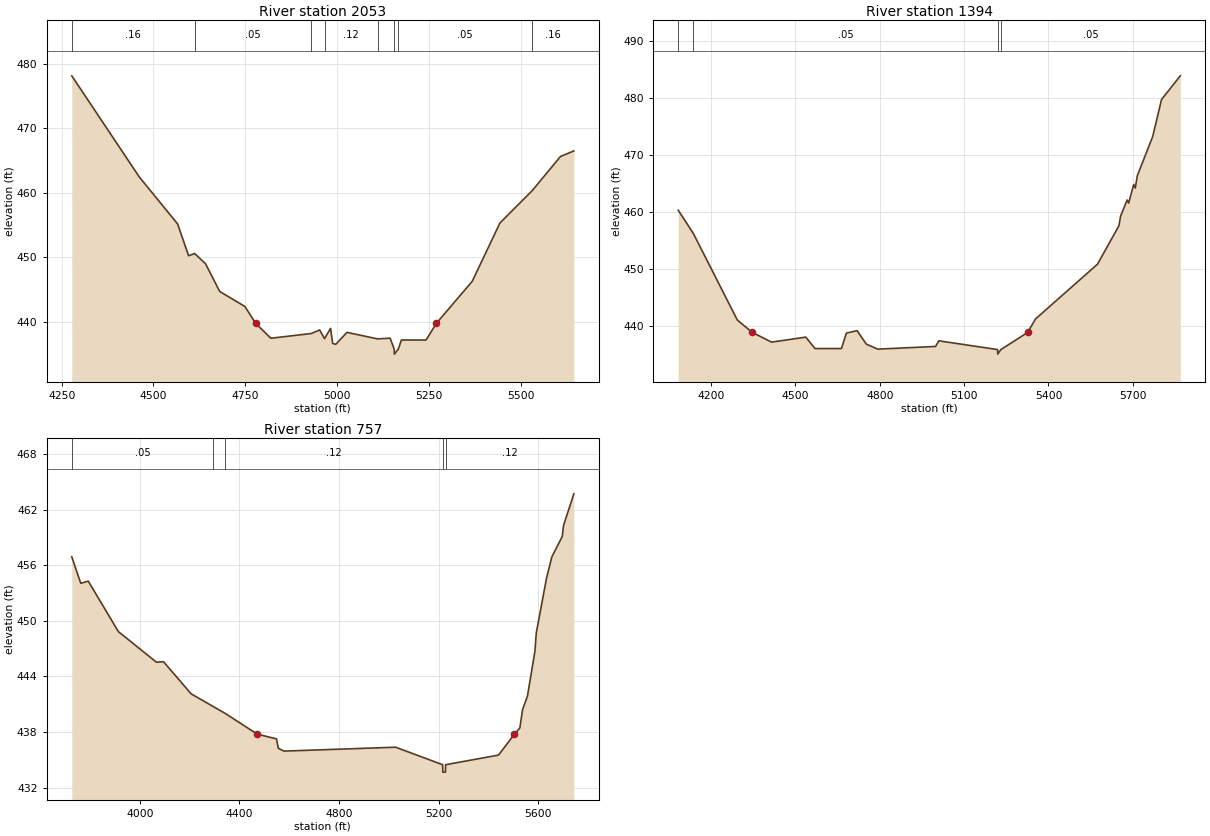
Type RM Length L Ch R = 1,2053,659,659,659
BEGIN DESCRIPTION:
CHAFFIN CREEK 3.0
END DESCRIPTION:
XS GIS Cut Line= 3
      2843174.99      7075074.97      2842925.00      7074425.00
      2842625.00      7073825.01
#Sta/Elev= 30
  4277.6  478.10  4461.9  462.40  4565.8  455.16  4595.8  450.23  4612.3  450.57
  4641.9  448.99  4680.4  444.70  4749.0  442.37  4778.4  439.76  4819.7  437.45
  4929.5  438.18  4952.6  438.73  4965.9  437.39  4982.4  438.98  4988.0  436.66
  4996.3  436.50  5027.1  438.36  5110.4  437.35  5144.5  437.46  5155.5  435.79
  5156.1  434.99  5167.0  435.79  5175.2  437.18  5242.3  437.17  5270.5  439.76
  5368.1  446.27  5443.6  455.31  5531.5  460.32  5608.5  465.61  5644.8  466.46
#Mann=8,-1,0
  4277.6    0.16       0  4612.3    0.05       0  4929.5    0.07       0
  4965.9    0.12       0  5110.4    0.05       0  5155.5    0.07       0
  5167.0    0.05       0  5531.5    0.16       0
Bank Sta=4778.4,5270.5
Exp/Cntr=0.3,0.1

Type RM Length L Ch R = 1,1394,637,637,637
BEGIN DESCRIPTION:
CHAFFIN CREEK 2.0
END DESCRIPTION:
XS GIS Cut Line= 3
      2843475.00      7074824.97      2843325.00      7073925.00
      2842975.00      7073125.00
#Sta/Elev= 30
  4083.3  460.30  4136.7  456.24  4293.6  440.98  4346.9  438.80  4415.3  437.10
  4536.9  437.98  4569.9  435.97  4663.7  435.97  4681.4  438.69  4719.4  439.12
  4752.4  436.74  4792.9  435.87  4998.4  436.34  5010.1  437.33  5219.1  435.79
  5219.7  434.99  5230.7  435.79  5325.9  438.80  5353.9  441.17  5574.2  450.80
  5650.6  457.57  5656.4  459.25  5679.8  462.10  5685.3  461.56  5703.2  464.82
  5708.7  464.21  5716.1  466.38  5770.7  473.26  5802.2  479.78  5868.9  483.94
#Mann=4,-1,0
  4083.3    0.16       0  4136.7    0.05       0  5219.1    0.03       0
  5230.7    0.05       0
Bank Sta=4346.9,5325.9
Exp/Cntr=0.3,0.1

Type RM Length L Ch R = 1,757,0,0,0
BEGIN DESCRIPTION:
CHAFFIN CREEK 1.0
END DESCRIPTION:
XS GIS Cut Line= 3
      2843769.18      7075000.82      2843925.00      7073725.00
      2843665.00      7073042.44
#Sta/Elev= 30
  3726.8  456.91  3762.9  454.05  3793.1  454.28  3914.0  448.83  4066.8  445.53
  4095.3  445.58  4206.2  442.11  4294.8  440.74  4342.3  440.01  4471.5  437.76
  4548.7  437.25  4556.1  436.23  4578.9  435.93  5027.1  436.35  5215.9  434.46
  5216.5  433.66  5227.0  433.66  5227.6  434.46  5440.1  435.50  5504.2  437.76
  5525.7  438.43  5536.8  440.42  5556.2  441.86  5586.3  446.72  5591.7  448.69
  5632.8  454.60  5654.2  456.90  5696.0  459.11  5701.3  460.31  5742.5  463.71
#Mann=5,-1,0
  3726.8    0.05       0  4294.8    0.16       0  4342.3    0.12       0
  5215.9    0.07       0  5227.6    0.12       0
Bank Sta=4471.5,5504.2
Exp/Cntr=0.3,0.1

Chan Stop Cuts=-1