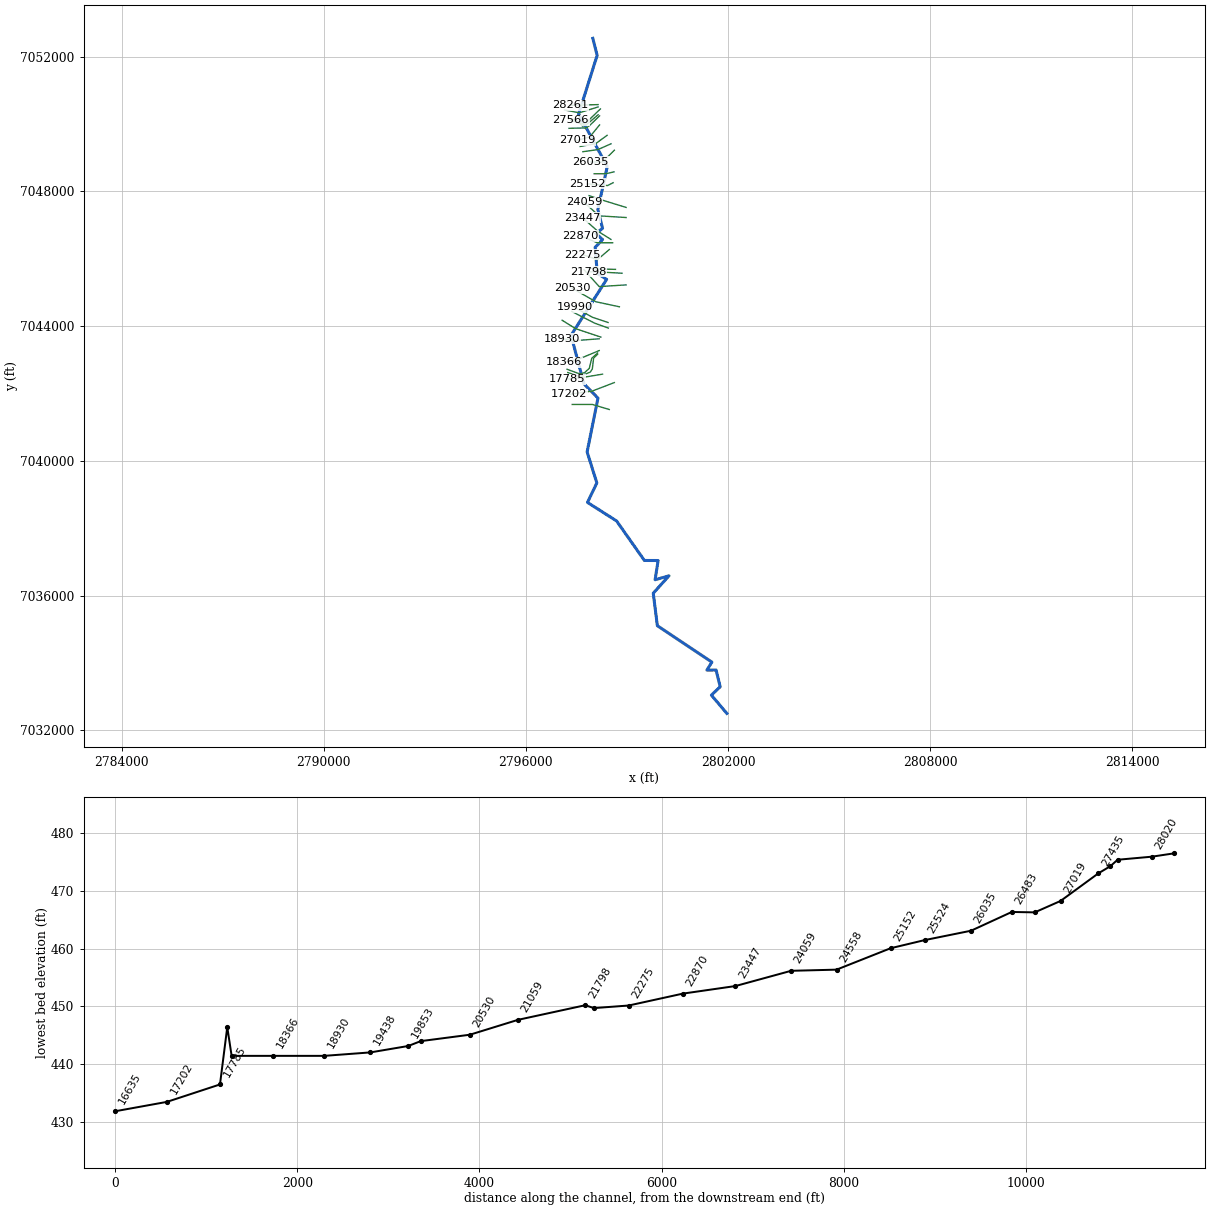
--- DEMENT BRANCH.prj (project) ---

Proj Title=DEMENT BRANCH Base Level Engineering
Current Plan=p01
Default Exp/Contr=0.3,0.1
English Units
Geom File=g01
Flow File=f01
Plan File=p01
BEGIN DESCRIPTION:
DEMENT BRANCH
END DESCRIPTION:

--- DEMENT BRANCH.p01 (plan) ---

Plan Title=Multiple Run
Short Identifier=Multiple
Geom File=g01
Flow File=f01
Subcritical Flow
K Sum by GR= 0
Std Step Tol= 0.01
Critical Tol= 0.01
Num of Std Step Trials= 20
Max Error Tol= 0.3
Flow Tol Ratio= 0.001
Split Flow NTrial= 30
Split Flow Tol= 0.02
Split Flow Ratio= 0.02
Log Output Level= 0
Friction Slope Method= 1
Unsteady Friction Slope Method= 2
Unsteady Bridges Friction Slope Method= 1
Parabolic Critical Depth
Global Vel Dist=  1 , 1 , 1
Global Log Level= 0
CheckData=True
Encroach Param= -1, 0, 0, 0
BEGIN DESCRIPTION:
Multiple Run
END DESCRIPTION:

--- DEMENT BRANCH.f01 (steady flow) ---

Flow Title=Multiple
Number of Profiles=7
Profile Names=10-year,25-year,50-year,1pct_min,100-year,1pct_plu,500-year
River Rch & RM= DEMENT BRANCH,Reach-1,28261
     273     346     402     233     465     929     622
River Rch & RM= DEMENT BRANCH,Reach-1,24558
     639     853    1026     612    1222    2438    1737
River Rch & RM= DEMENT BRANCH,Reach-1,19990
     743     997    1203     720    1437    2867    2055
River Rch & RM= DEMENT BRANCH,Reach-1,12836
     879    1191    1445     870    1735    3462    2508
River Rch & RM= DEMENT BRANCH,Reach-1,11910
     932    1264    1535     925    1846    3683    2673
River Rch & RM= DEMENT BRANCH,Reach-1,7279
    1604    2229    2753    1683    3357    6699    5007
Boundary for River Rch & Prof#=DEMENT BRANCH,Reach-1,1
Up Type=0
Dn Type=3
Dn Slope=0.005
Boundary for River Rch & Prof#=DEMENT BRANCH,Reach-1,2
Up Type=0
Dn Type=3
Dn Slope=0.005
Boundary for River Rch & Prof#=DEMENT BRANCH,Reach-1,3
Up Type=0
Dn Type=3
Dn Slope=0.005
Boundary for River Rch & Prof#=DEMENT BRANCH,Reach-1,4
Up Type=0
Dn Type=3
Dn Slope=0.005
Boundary for River Rch & Prof#=DEMENT BRANCH,Reach-1,5
Up Type=0
Dn Type=3
Dn Slope=0.005
Boundary for River Rch & Prof#=DEMENT BRANCH,Reach-1,6
Up Type=0
Dn Type=3
Dn Slope=0.005
Boundary for River Rch & Prof#=DEMENT BRANCH,Reach-1,7
Up Type=0
Dn Type=3
Dn Slope=0.005

--- DEMENT BRANCH.g01 (geometry) ---

Geom Title=Existing Conditions

River Reach=DEMENT BRANCH,Reach-1
Reach XY= 30
      2797985.59      7052545.71      2798114.41      7052040.80
      2797565.42      7050300.74      2798414.79      7048739.97
      2798135.44      7047462.08      2798275.34      7046904.81
      2798077.58      7046750.59      2798275.06      7046571.10
      2798055.36      7046340.63      2798116.95      7045566.08
      2798396.22      7045390.53      2797339.58      7043727.77
      2797721.84      7042287.82      2798138.79      7041864.42
      2797816.76      7040265.69      2798105.38      7039344.99
      2797827.40      7038766.49      2798691.60      7038215.92
      2799517.23      7037043.06      2799924.84      7037041.30
      2799835.05      7036471.29      2800246.83      7036586.99
      2799780.40      7036070.68      2799901.81      7035105.40
      2801521.87      7034024.74      2801371.59      7033787.77
      2801646.11      7033790.14      2801767.98      7033291.99
      2801505.30      7033044.68      2801964.45      7032502.98

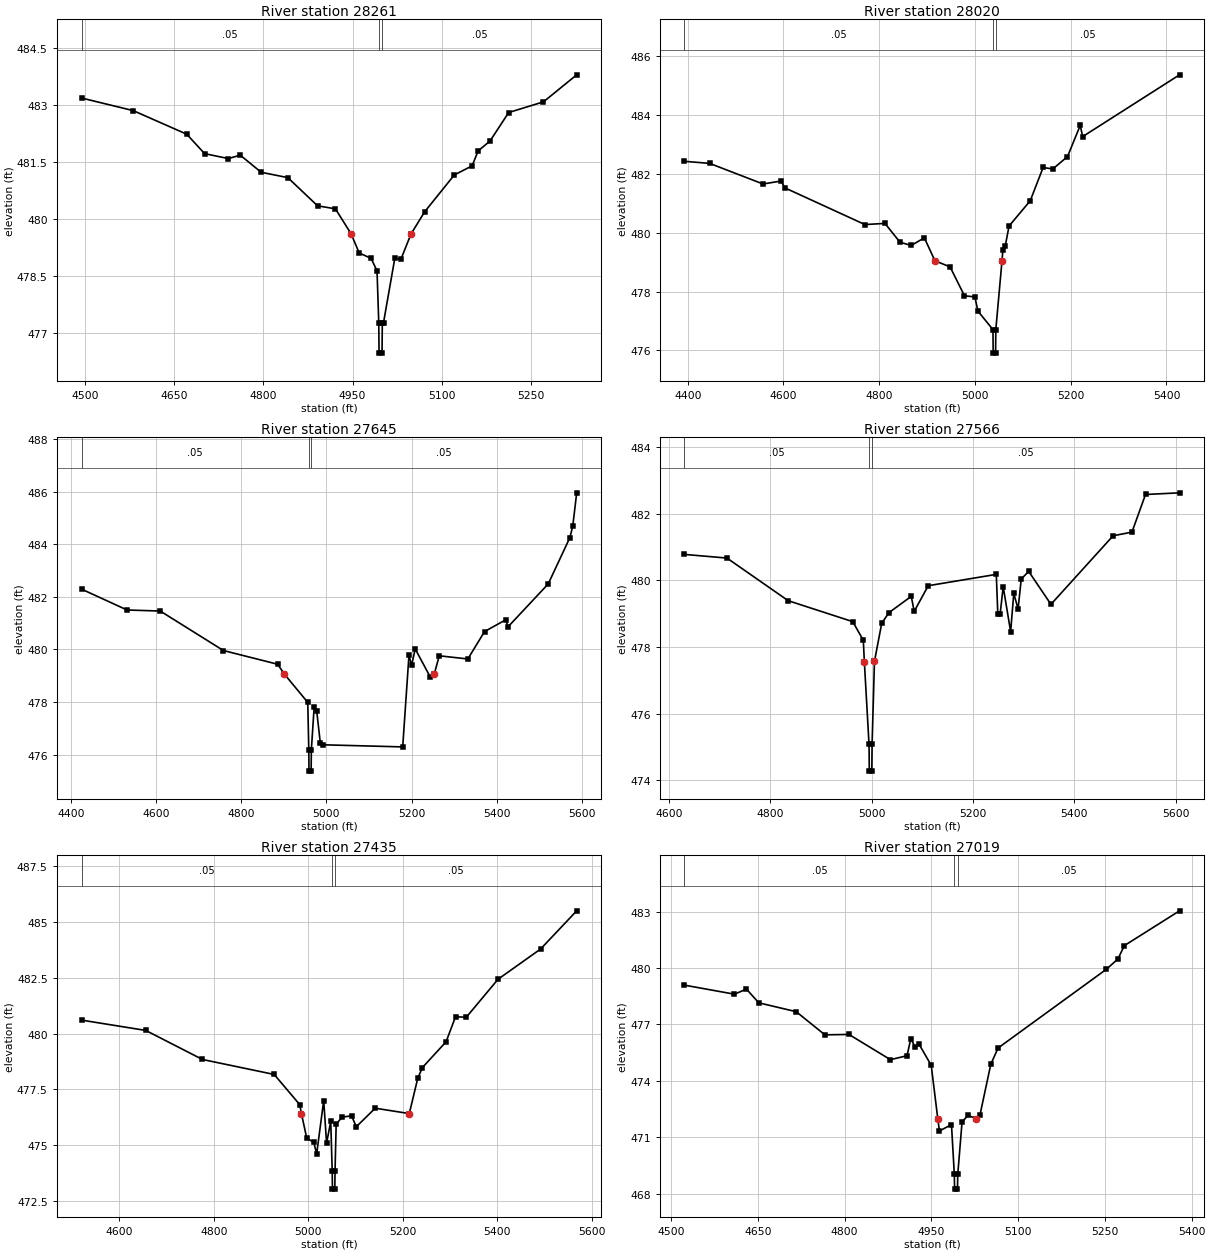
Type RM Length L Ch R = 1,28261,241,241,241
BEGIN DESCRIPTION:
DEMENT BRANCH 40.0
END DESCRIPTION:
XS GIS Cut Line= 3
      2798141.69      7050578.33      2797638.17      7050564.44
      2797309.16      7050557.52
#Sta/Elev= 30
  4494.3  483.18  4581.0  482.85  4671.1  482.23  4701.1  481.72  4741.1  481.59
  4761.1  481.68  4796.3  481.23  4841.1  481.09  4891.1  480.35  4921.2  480.27
  4947.7  479.61  4961.2  479.11  4981.2  478.97  4991.2  478.64  4994.1  477.28
  4994.6  476.48  4999.6  476.48  5000.1  477.28  5002.1  477.28  5021.2  478.98
  5031.2  478.94  5048.4  479.61  5071.2  480.19  5121.2  481.16  5151.2  481.40
  5161.2  481.79  5181.2  482.05  5212.7  482.80  5271.2  483.08  5327.1  483.79
#Mann=3,-1,0
  4494.3    0.05       0  4994.1    0.03       0  5000.1    0.05       0
Bank Sta=4947.7,5048.4
Exp/Cntr=0.3,0.1

Type RM Length L Ch R = 1,28020,375,375,375
BEGIN DESCRIPTION:
Mapping XS 7b41d117
END DESCRIPTION:
XS GIS Cut Line= 3
      2798145.11      7050508.89      2797582.62      7050335.28
      2797145.16      7050418.60
#Sta/Elev= 30
  4393.3  482.43  4445.7  482.36  4557.3  481.66  4595.2  481.76  4602.7  481.53
  4770.2  480.28  4812.0  480.32  4843.4  479.68  4866.9  479.57  4894.3  479.83
  4916.4  479.05  4948.1  478.84  4978.1  477.86  4999.9  477.82  5006.1  477.34
  5037.6  476.71  5038.1  475.91  5043.1  475.91  5043.6  476.71  5056.5  479.05
  5058.3  479.41  5063.4  479.56  5071.2  480.23  5115.5  481.09  5142.4  482.22
  5162.6  482.17  5193.3  482.59  5219.9  483.65  5225.0  483.27  5427.3  485.37
#Mann=3,-1,0
  4393.3    0.05       0  5037.6    0.03       0  5043.6    0.05       0
Bank Sta=4916.4,5056.5
Exp/Cntr=0.3,0.1

Type RM Length L Ch R = 1,27645,79,79,79
BEGIN DESCRIPTION:
Mapping XS 3f3eebff
END DESCRIPTION:
XS GIS Cut Line= 6
      2798211.06      7050449.83      2797822.20      7050074.86
      2797728.45      7050015.83      2797652.06      7050005.42
      2797537.48      7050088.75      2797259.83      7050182.46
#Sta/Elev= 30
  4425.1  482.29  4531.7  481.50  4609.7  481.46  4758.1  479.96  4885.4  479.44
  4901.5  479.06  4956.2  477.99  4958.6  476.18  4959.1  475.38  4964.1  475.38
  4964.6  476.18  4971.2  477.82  4977.1  477.68  4985.6  476.46  4992.4  476.38
  5179.2  476.30  5193.9  479.78  5200.1  479.40  5208.6  480.02  5244.1  478.95
  5253.2  479.06  5265.0  479.76  5332.2  479.64  5371.4  480.68  5421.4  481.13
  5426.6  480.86  5521.0  482.49  5571.9  484.25  5578.7  484.69  5587.9  485.95
#Mann=3,-1,0
  4425.1    0.05       0  4958.6    0.03       0  4964.6    0.05       0
Bank Sta=4901.5,5253.2
Exp/Cntr=0.3,0.1

Type RM Length L Ch R = 1,27566,131,131,131
BEGIN DESCRIPTION:
Mapping XS bc62e36b
END DESCRIPTION:
XS GIS Cut Line= 6
      2798141.61      7050276.22      2797829.15      7050008.89
      2797724.98      7049949.86      2797676.37      7049939.44
      2797599.98      7050022.78      2797332.64      7050109.58
#Sta/Elev= 30
  4631.0  480.78  4714.8  480.67  4835.5  479.39  4962.9  478.76  4983.7  478.20
  4985.8  477.54  4995.0  475.07  4995.5  474.27  5000.5  474.27  5001.0  475.07
  5005.7  477.57  5020.0  478.71  5034.2  479.03  5078.3  479.52  5084.1  479.07
  5111.8  479.84  5246.0  480.18  5249.0  478.99  5253.6  478.99  5259.6  479.81
  5274.3  478.46  5280.5  479.61  5289.0  479.14  5295.2  480.04  5309.9  480.27
  5353.8  479.28  5476.4  481.34  5513.6  481.45  5540.3  482.58  5607.4  482.63
#Mann=3,-1,0
  4631.0    0.05       0  4995.0    0.03       0  5001.0    0.05       0
Bank Sta=4985.8,5005.7
Exp/Cntr=0.3,0.1

Type RM Length L Ch R = 1,27435,416,416,416
BEGIN DESCRIPTION:
Mapping XS 6908eb88
END DESCRIPTION:
XS GIS Cut Line= 5
      2798186.76      7050244.98      2797895.12      7049960.28
      2797784.01      7049883.89      2797655.54      7049883.89
      2797278.55      7049873.51
#Sta/Elev= 30
  4520.1  480.60  4655.7  480.14  4775.8  478.84  4927.7  478.17  4981.8  476.82
  4985.3  476.42  4996.7  475.31  5011.5  475.14  5017.6  474.61  5032.5  477.00
  5038.6  475.10  5047.4  476.07  5050.5  473.84  5051.0  473.04  5056.0  473.04
  5056.5  473.84  5058.9  475.95  5071.5  476.26  5091.5  476.32  5101.5  475.83
  5141.5  476.66  5213.7  476.42  5231.5  477.99  5241.5  478.48  5291.5  479.63
  5311.6  480.75  5334.4  480.73  5401.6  482.43  5491.6  483.78  5568.1  485.49
#Mann=3,-1,0
  4520.1    0.05       0  5050.5    0.03       0  5056.5    0.05       0
Bank Sta=4985.3,5213.7
Exp/Cntr=0.3,0.1

Type RM Length L Ch R = 1,27019,284,284,284
BEGIN DESCRIPTION:
Mapping XS 38958188
END DESCRIPTION:
XS GIS Cut Line= 3
      2798186.82      7049974.20      2797895.12      7049620.00
      2797513.15      7049512.35
#Sta/Elev= 30
  4523.4  479.09  4609.7  478.61  4630.5  478.88  4651.9  478.15  4716.5  477.68
  4766.1  476.45  4807.7  476.47  4879.4  475.13  4908.1  475.34  4914.6  476.25
  4922.4  475.78  4928.9  475.95  4949.9  474.83  4961.2  472.00  4964.1  471.34
  4984.9  471.68  4989.8  469.05  4990.3  468.25  4995.3  468.25  4995.8  469.05
  5003.2  471.82  5013.5  472.17  5027.2  472.00  5034.3  472.21  5052.9  474.89
  5065.5  475.75  5252.5  479.93  5272.6  480.48  5283.7  481.19  5379.1  483.04
#Mann=3,-1,0
  4523.4    0.05       0  4989.8    0.03       0  4995.8    0.05       0
Bank Sta=4961.2,5027.2
Exp/Cntr=0.3,0.1

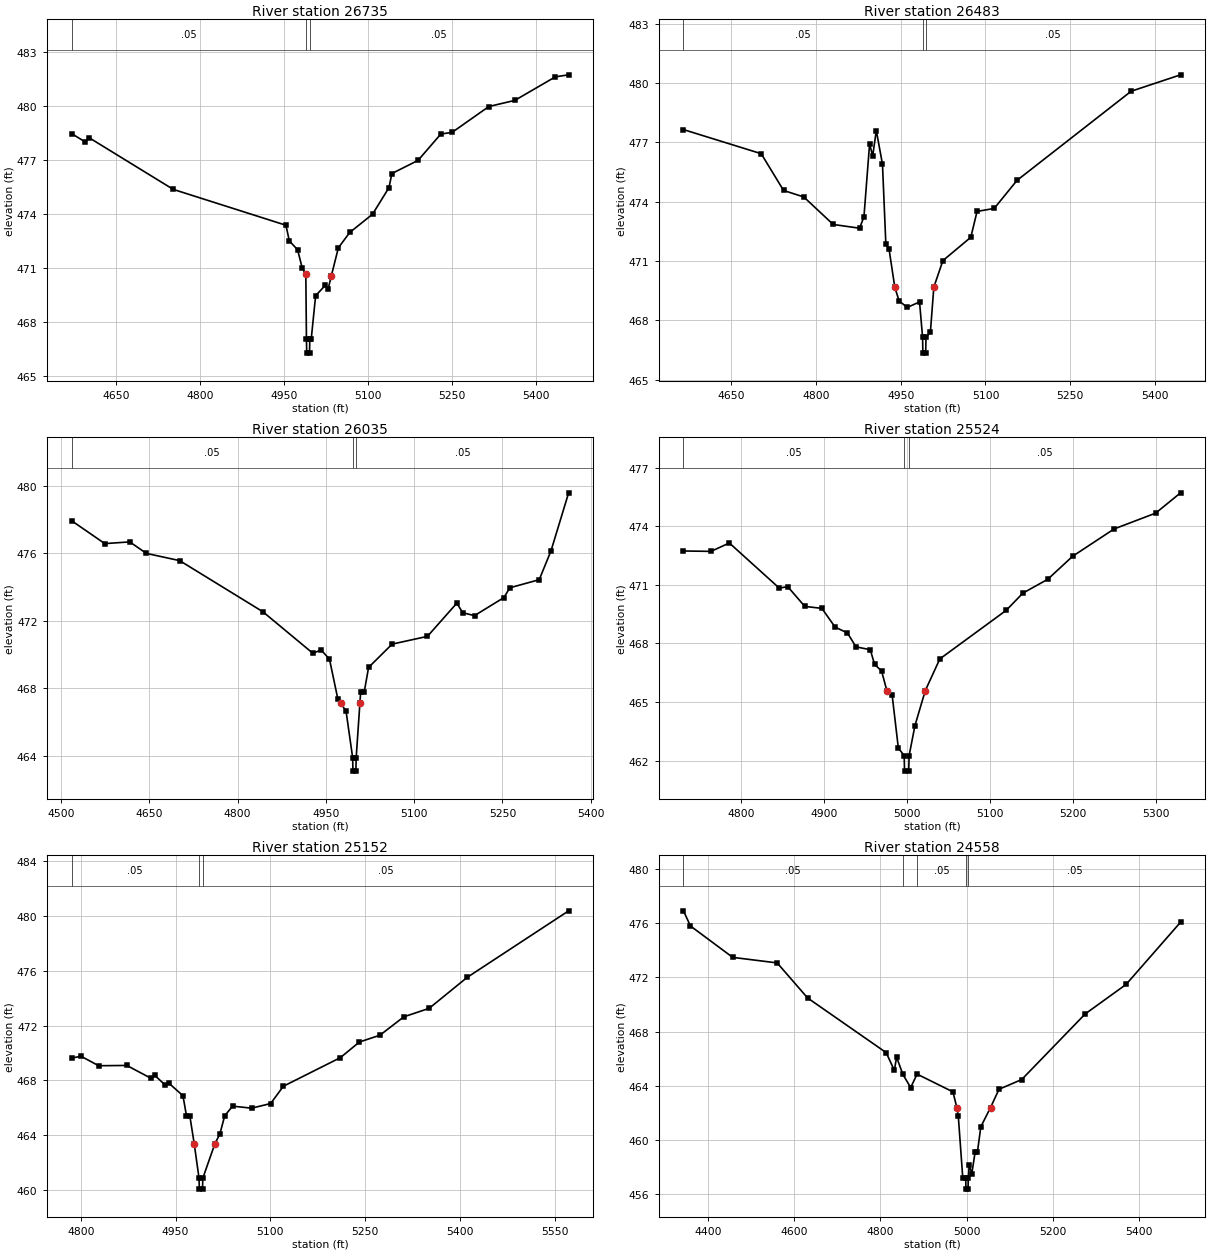
Type RM Length L Ch R = 1,26735,252,252,252
BEGIN DESCRIPTION:
Mapping XS 741aec4f
END DESCRIPTION:
XS GIS Cut Line= 3
      2798409.03      7049665.15      2798065.26      7049415.14
      2797610.38      7049335.28
#Sta/Elev= 30
  4570.9  478.46  4595.5  477.99  4601.7  478.24  4752.4  475.36  4953.4  473.37
  4959.5  472.50  4974.2  472.01  4982.7  470.97  4988.9  470.68  4990.0  467.07
  4990.5  466.27  4995.5  466.27  4996.0  467.07  4998.6  467.07  5006.4  469.46
  5023.6  470.03  5028.7  469.83  5034.4  470.56  5047.0  472.12  5067.3  472.97
  5107.9  473.98  5137.3  475.46  5142.4  476.24  5189.1  476.97  5229.7  478.43
  5250.1  478.53  5315.4  479.96  5361.7  480.30  5434.2  481.61  5457.8  481.72
#Mann=3,-1,0
  4570.9    0.05       0  4990.0    0.03       0  4996.0    0.05       0
Bank Sta=4988.9,5034.4
Exp/Cntr=0.3,0.1

Type RM Length L Ch R = 1,26483,448,448,448
BEGIN DESCRIPTION:
Mapping XS 56e7f191
END DESCRIPTION:
XS GIS Cut Line= 3
      2798527.08      7049415.15      2798134.70      7049241.53
      2797688.40      7049179.25
#Sta/Elev= 30
  4565.5  477.65  4703.1  476.43  4742.7  474.57  4778.5  474.24  4830.5  472.85
  4877.1  472.66  4884.9  473.23  4894.9  476.92  4900.4  476.32  4906.8  477.60
  4917.7  475.90  4923.7  471.84  4929.2  471.63  4939.5  469.68  4947.0  468.99
  4961.4  468.65  4983.3  468.93  4988.7  467.14  4989.2  466.34  4994.2  466.34
  4994.7  467.14  5002.5  467.40  5008.6  469.68  5024.6  471.02  5074.0  472.20
  5085.1  473.51  5115.4  473.66  5155.8  475.08  5357.8  479.59  5445.2  480.42
#Mann=3,-1,0
  4565.5    0.05       0  4988.7    0.03       0  4994.7    0.05       0
Bank Sta=4939.5,5008.6
Exp/Cntr=0.3,0.1

Type RM Length L Ch R = 1,26035,511,511,511
BEGIN DESCRIPTION:
DEMENT BRANCH 38.0
END DESCRIPTION:
XS GIS Cut Line= 3
      2798624.97      7049224.97      2798275.00      7048875.00
      2797925.03      7048875.00
#Sta/Elev= 30
  4517.7  477.94  4574.2  476.58  4616.7  476.68  4644.9  476.00  4701.5  475.57
  4842.9  472.54  4927.8  470.08  4941.9  470.27  4956.1  469.73  4970.2  467.39
  4975.5  467.11  4984.3  466.64  4995.5  463.89  4996.0  463.09  5001.0  463.09
  5001.5  463.89  5007.8  467.11  5009.1  467.77  5015.1  467.77  5022.6  469.24
  5062.6  470.62  5122.6  471.08  5172.6  473.05  5182.6  472.48  5202.6  472.31
  5252.6  473.38  5262.6  473.96  5312.6  474.44  5332.6  476.15  5362.6  479.59
#Mann=3,-1,0
  4517.7    0.05       0  4995.5    0.03       0  5001.5    0.05       0
Bank Sta=4975.5,5007.8
Exp/Cntr=0.3,0.1

Type RM Length L Ch R = 1,25524,372,372,372
BEGIN DESCRIPTION:
DEMENT BRANCH 37.0
END DESCRIPTION:
XS GIS Cut Line= 3
      2798617.36      7048581.81      2798375.00      7048525.00
      2798025.03      7048525.00
#Sta/Elev= 30
  4730.6  472.74  4763.8  472.72  4785.9  473.15  4846.0  470.84  4856.3  470.91
  4876.8  469.90  4897.4  469.80  4913.3  468.84  4928.2  468.54  4938.4  467.83
  4955.7  467.68  4960.9  466.93  4969.3  466.59  4975.7  465.58  4982.0  465.37
  4989.5  462.64  4996.5  462.26  4997.0  461.46  5002.0  461.46  5002.5  462.26
  5009.5  463.79  5021.9  465.58  5039.5  467.21  5119.5  469.70  5139.5  470.58
  5169.5  471.29  5199.5  472.47  5249.5  473.87  5299.5  474.68  5329.5  475.72
#Mann=3,-1,0
  4730.6    0.05       0  4996.5    0.03       0  5002.5    0.05       0
Bank Sta=4975.7,5021.9
Exp/Cntr=0.3,0.1

Type RM Length L Ch R = 1,25152,594,594,594
BEGIN DESCRIPTION:
DEMENT BRANCH 36.0
END DESCRIPTION:
XS GIS Cut Line= 3
      2798589.55      7048258.88      2798425.00      7048175.00
      2797824.98      7048225.00
#Sta/Elev= 30
  4785.4  469.63  4800.5  469.76  4828.4  469.07  4872.9  469.09  4911.7  468.14
  4917.3  468.36  4933.9  467.65  4939.6  467.79  4961.8  466.88  4967.3  465.42
  4972.6  465.42  4979.6  463.37  4987.2  460.86  4987.7  460.06  4992.7  460.06
  4993.2  460.86  5012.3  463.37  5020.3  464.10  5027.8  465.41  5040.3  466.12
  5070.4  465.97  5100.6  466.31  5120.6  467.57  5210.9  469.66  5241.0  470.80
  5273.6  471.30  5311.3  472.64  5351.4  473.26  5411.6  475.52  5572.2  480.38
#Mann=3,-1,0
  4785.4    0.05       0  4987.2    0.03       0  4993.2    0.05       0
Bank Sta=4979.6,5012.3
Exp/Cntr=0.3,0.1

Type RM Length L Ch R = 1,24558,499,499,499
BEGIN DESCRIPTION:
DEMENT BRANCH 35.0
END DESCRIPTION:
XS GIS Cut Line= 3
      2798974.97      7047525.01      2798325.00      7047725.00
      2797874.99      7047875.00
#Sta/Elev= 30
  4342.6  476.92  4358.9  475.80  4457.0  473.48  4560.3  473.07  4630.9  470.48
  4813.4  466.44  4832.4  465.12  4837.6  466.11  4852.1  464.83  4870.3  463.86
  4885.2  464.85  4968.4  463.54  4977.5  462.38  4980.8  461.77  4991.3  457.16
  4998.1  457.15  4998.6  456.35  5003.6  456.35  5004.1  457.15  5006.3  458.14
  5012.2  457.49  5020.0  459.10  5025.3  459.10  5033.2  460.96  5055.7  462.38
  5075.4  463.73  5128.1  464.45  5275.6  469.30  5370.5  471.48  5497.0  476.08
#Mann=5,-1,0
  4342.6    0.05       0  4852.1    0.16       0  4885.2    0.05       0
  4998.1    0.03       0  5004.1    0.05       0
Bank Sta=4977.5,5055.7
Exp/Cntr=0.3,0.1

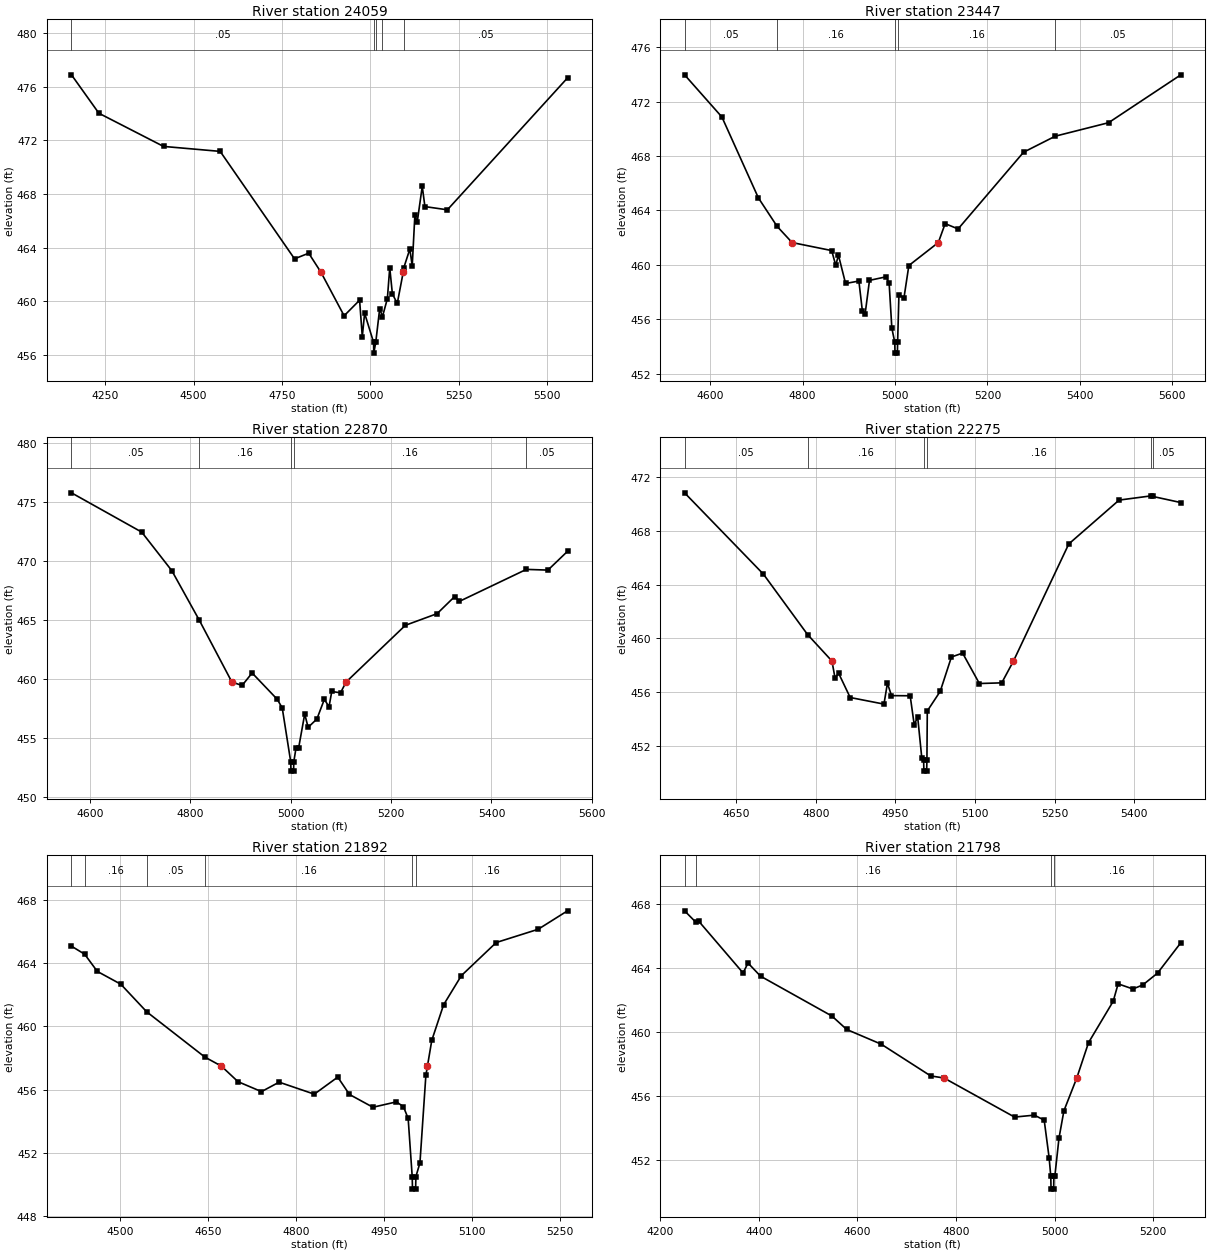
Type RM Length L Ch R = 1,24059,612,612,612
BEGIN DESCRIPTION:
DEMENT BRANCH 34.0
END DESCRIPTION:
XS GIS Cut Line= 3
      2798974.97      7047225.00      2798175.00      7047275.00
      2797725.01      7047674.99
#Sta/Elev= 30
  4154.3  476.87  4231.9  474.01  4414.8  471.54  4575.1  471.17  4785.5  463.17
  4825.6  463.59  4860.3  462.17  4925.8  458.93  4969.6  460.09  4977.2  457.38
  4983.8  459.12  5009.2  456.95  5009.7  456.15  5015.3  456.95  5026.5  459.47
  5034.3  458.86  5048.2  460.21  5054.9  462.51  5062.4  460.56  5076.2  459.85
  5093.0  462.17  5094.7  462.51  5111.8  463.90  5118.5  462.64  5126.0  466.42
  5132.7  465.91  5146.9  468.57  5154.4  467.06  5218.0  466.82  5557.9  476.64
#Mann=5,-1,0
  4154.3    0.05       0  5009.2    0.03       0  5015.3    0.05       0
  5034.3    0.16       0  5094.7    0.05       0
Bank Sta=4860.3,5093
Exp/Cntr=0.3,0.1

Type RM Length L Ch R = 1,23447,577,577,577
BEGIN DESCRIPTION:
DEMENT BRANCH 33.0
END DESCRIPTION:
XS GIS Cut Line= 3
      2798524.99      7046575.01      2798125.00      7046825.00
      2797674.97      7047225.03
#Sta/Elev= 30
  4544.5  473.97  4625.3  470.87  4704.3  464.92  4744.8  462.83  4777.2  461.64
  4862.9  461.05  4871.7  459.97  4877.6  460.71  4893.0  458.63  4921.8  458.81
  4929.5  456.58  4935.4  456.41  4944.8  458.86  4980.8  459.12  4987.3  458.66
  4993.2  455.34  4999.5  454.31  5000.0  453.51  5005.2  453.51  5005.7  454.31
  5008.5  457.78  5019.5  457.59  5030.0  459.95  5093.8  461.64  5108.6  463.03
  5136.6  462.64  5278.3  468.28  5347.0  469.46  5462.3  470.45  5618.3  473.96
#Mann=5,-1,0
  4544.5    0.05       0  4744.8    0.16       0  4999.5    0.07       0
  5005.7    0.16       0  5347.0    0.05       0
Bank Sta=4777.2,5093.8
Exp/Cntr=0.3,0.1

Type RM Length L Ch R = 1,22870,595,595,595
BEGIN DESCRIPTION:
DEMENT BRANCH 32.0
END DESCRIPTION:
XS GIS Cut Line= 3
      2798575.03      7046475.00      2798125.00      7046475.00
      2797625.05      7046674.98
#Sta/Elev= 30
  4563.0  475.79  4703.0  472.46  4763.0  469.19  4817.9  464.98  4882.7  459.75
  4903.0  459.46  4923.0  460.52  4973.0  458.29  4983.0  457.56  4999.9  453.00
  5000.4  452.20  5005.6  452.20  5006.1  453.00  5010.5  454.17  5015.7  454.17
  5027.8  457.04  5034.6  455.91  5052.1  456.62  5066.9  458.28  5076.3  457.66
  5081.7  458.95  5099.2  458.84  5110.2  459.75  5228.4  464.56  5291.7  465.55
  5326.7  467.00  5336.1  466.59  5469.5  469.30  5512.5  469.24  5551.5  470.83
#Mann=5,-1,0
  4563.0    0.05       0  4817.9    0.16       0  4999.9    0.07       0
  5006.1    0.16       0  5469.5    0.05       0
Bank Sta=4882.7,5110.2
Exp/Cntr=0.3,0.1

Type RM Length L Ch R = 1,22275,383,383,383
BEGIN DESCRIPTION:
DEMENT BRANCH 31.0
END DESCRIPTION:
XS GIS Cut Line= 3
      2798475.04      7046275.03      2798125.00      7045975.00
      2797674.97      7046125.01
#Sta/Elev= 30
  4552.4  470.82  4701.2  464.77  4784.3  460.29  4830.3  458.32  4836.2  457.04
  4842.8  457.42  4864.7  455.61  4928.4  455.12  4934.9  456.67  4942.6  455.75
  4977.8  455.74  4985.4  453.60  4992.0  454.15  4999.7  451.13  5003.2  450.94
  5003.7  450.14  5008.9  450.14  5009.4  450.94  5010.1  454.61  5034.5  456.07
  5055.6  458.62  5076.7  458.91  5108.3  456.65  5150.5  456.70  5172.6  458.32
  5276.9  467.02  5371.8  470.28  5431.4  470.59  5435.5  470.55  5487.8  470.10
#Mann=6,-1,0
  4552.4    0.05       0  4784.3    0.16       0  5003.2    0.07       0
  5009.4    0.16       0  5431.4    0.08       0  5435.5    0.05       0
Bank Sta=4830.3,5172.6
Exp/Cntr=0.3,0.1

Type RM Length L Ch R = 1,21892,94,94,94
BEGIN DESCRIPTION:
Mapping XS a89d2af4
END DESCRIPTION:
XS GIS Cut Line= 3
      2798659.05      7045685.97      2798093.04      7045699.86
      2797815.28      7045734.58
#Sta/Elev= 30
  4417.4  465.09  4439.9  464.58  4461.5  463.49  4501.5  462.68  4545.7  460.93
  4644.9  458.06  4673.0  457.49  4701.5  456.50  4741.5  455.87  4771.6  456.47
  4831.6  455.71  4871.6  456.79  4891.6  455.69  4931.6  454.88  4971.6  455.22
  4983.6  454.92  4991.7  454.17  4998.6  450.49  4999.1  449.69  5004.4  449.69
  5004.9  450.49  5011.8  451.35  5021.9  456.90  5024.6  457.49  5032.0  459.12
  5052.1  461.37  5082.4  463.22  5141.9  465.32  5213.4  466.16  5263.5  467.33
#Mann=6,-1,0
  4417.4    0.05       0  4439.9    0.16       0  4545.7    0.05       0
  4644.9    0.16       0  4998.6    0.07       0  5004.9    0.16       0
Bank Sta=4673,5024.6
Exp/Cntr=0.3,0.1

Type RM Length L Ch R = 1,21798,739,739,739
BEGIN DESCRIPTION:
Mapping XS 52c6a53b
END DESCRIPTION:
XS GIS Cut Line= 3
      2798853.48      7045571.39      2798106.92      7045613.06
      2797848.24      7045613.06
#Sta/Elev= 30
  4249.3  467.57  4272.1  466.86  4277.8  466.93  4368.0  463.69  4378.0  464.31
  4403.4  463.49  4548.2  461.00  4578.3  460.16  4648.4  459.24  4748.6  457.26
  4775.7  457.13  4918.8  454.69  4958.9  454.81  4978.9  454.50  4988.9  452.16
  4992.3  450.99  4992.8  450.19  4998.1  450.19  4998.6  450.99  5000.5  450.99
  5008.9  453.37  5018.9  455.08  5045.0  457.13  5068.9  459.34  5118.9  461.92
  5128.9  463.01  5158.9  462.69  5178.9  462.94  5208.9  463.68  5255.7  465.56
#Mann=4,-1,0
  4249.3    0.05       0  4272.1    0.16       0  4992.3    0.07       0
  4998.6    0.16       0
Bank Sta=4775.7,5045
Exp/Cntr=0.3,0.1

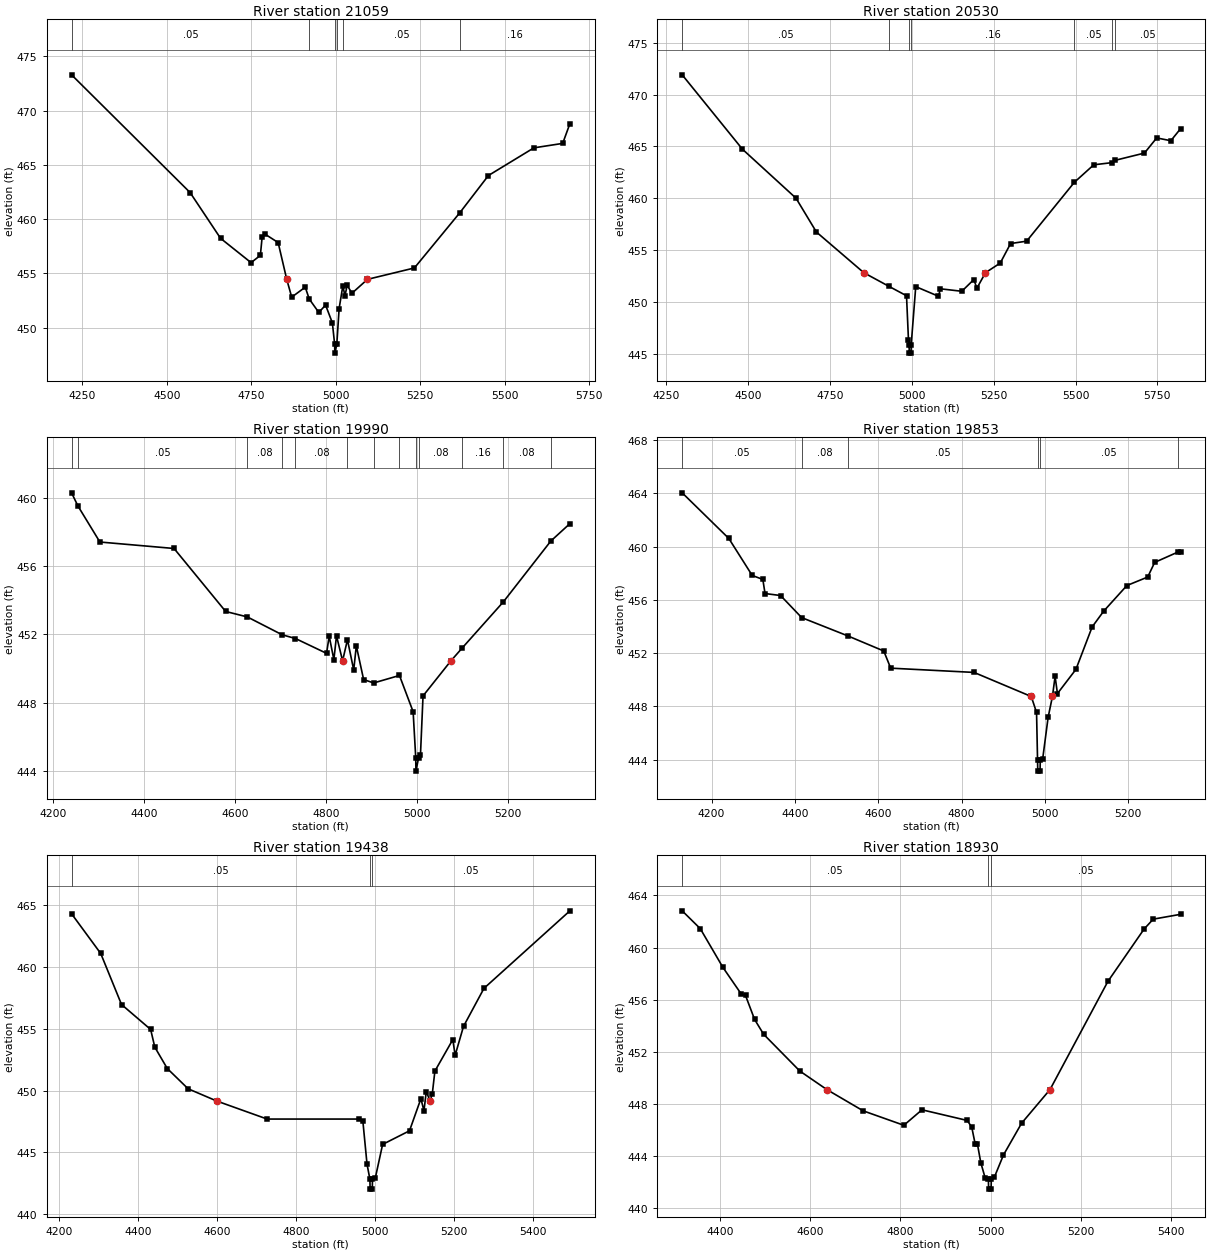
Type RM Length L Ch R = 1,21059,529,529,529
BEGIN DESCRIPTION:
DEMENT BRANCH 30.0
END DESCRIPTION:
XS GIS Cut Line= 3
      2798974.95      7045225.00      2798175.00      7045175.00
      2797725.00      7045675.00
#Sta/Elev= 30
  4218.3  473.31  4568.9  462.46  4659.1  458.24  4749.3  456.00  4776.8  456.67
  4781.9  458.32  4789.4  458.65  4829.4  457.85  4854.8  454.46  4869.5  452.82
  4909.6  453.74  4921.3  452.65  4949.7  451.41  4969.7  452.09  4989.8  450.45
  4996.6  448.46  4997.1  447.66  5002.9  448.46  5009.8  451.77  5020.9  453.89
  5026.9  452.92  5033.6  453.91  5047.8  453.18  5093.6  454.46  5232.5  455.51
  5367.4  460.62  5451.5  464.03  5586.0  466.58  5671.2  466.99  5692.5  468.81
#Mann=6,-1,0
  4218.3    0.05       0  4921.3    0.16       0  4996.6    0.07       0
  5002.9    0.16       0  5020.9    0.05       0  5367.4    0.16       0
Bank Sta=4854.8,5093.6
Exp/Cntr=0.3,0.1

Type RM Length L Ch R = 1,20530,540,540,540
BEGIN DESCRIPTION:
DEMENT BRANCH 29.0
END DESCRIPTION:
XS GIS Cut Line= 3
      2798775.02      7044574.99      2798075.00      7044725.00
      2797375.04      7045124.98
#Sta/Elev= 30
  4298.4  471.90  4482.5  464.73  4646.1  460.01  4708.4  456.75  4853.2  452.83
  4929.7  451.52  4983.6  450.61  4989.6  446.34  4991.5  445.88  4992.0  445.08
  4997.4  445.08  4997.9  445.88  5011.8  451.49  5081.3  450.56  5087.0  451.28
  5152.5  451.04  5189.2  452.17  5198.6  451.34  5224.8  452.83  5269.9  453.76
  5301.5  455.64  5350.5  455.87  5496.5  461.55  5555.6  463.23  5612.1  463.44
  5619.3  463.65  5710.4  464.36  5747.8  465.82  5791.0  465.55  5820.5  466.70
#Mann=7,-1,0
  4298.4    0.05       0  4929.7    0.16       0  4991.5    0.07       0
  4997.9    0.16       0  5496.5    0.05       0  5612.1    0.16       0
  5619.3    0.05       0
Bank Sta=4853.2,5224.8
Exp/Cntr=0.3,0.1

Type RM Length L Ch R = 1,19990,137,137,137
BEGIN DESCRIPTION:
Mapping XS 1353c1a7
END DESCRIPTION:
XS GIS Cut Line= 3
      2798436.83      7044109.57      2797978.45      7044262.36
      2797440.24      7044557.51
#Sta/Elev= 30
  4240.1  460.32  4254.0  459.55  4302.4  457.43  4465.7  457.05  4579.3  453.35
  4626.9  453.03  4703.7  451.98  4733.0  451.76  4801.4  450.89  4807.2  451.90
  4817.5  450.52  4823.3  451.92  4836.7  450.45  4847.4  451.69  4861.2  449.91
  4866.9  451.33  4883.0  449.35  4905.1  449.15  4961.9  449.59  4992.0  447.46
  4997.7  444.77  4998.2  443.97  5004.1  444.77  5008.1  444.89  5013.8  448.39
  5075.2  450.45  5100.2  451.21  5190.8  453.92  5295.2  457.49  5337.1  458.51
#Mann=13,-1,0
  4240.1    0.08       0  4254.0    0.05       0  4626.9    0.08       0
  4703.7    0.05       0  4733.0    0.08       0  4847.4    0.05       0
  4905.1    0.16       0  4961.9    0.08       0  4997.7    0.07       0
  5004.1    0.08       0  5100.2    0.16       0  5190.8    0.08       0
  5295.2    0.16       0
Bank Sta=4836.7,5075.2
Exp/Cntr=0.3,0.1

Type RM Length L Ch R = 1,19853,415,415,415
BEGIN DESCRIPTION:
Mapping XS 33446a00
END DESCRIPTION:
XS GIS Cut Line= 3
      2798447.24      7043942.90      2798040.95      7044088.75
      2797360.39      7044435.98
#Sta/Elev= 30
  4129.4  464.05  4241.3  460.62  4297.4  457.84  4322.9  457.54  4328.2  456.48
  4365.5  456.33  4416.1  454.67  4526.5  453.30  4613.1  452.16  4629.7  450.87
  4829.7  450.55  4967.0  448.74  4979.7  447.54  4982.1  443.93  4982.6  443.13
  4988.1  443.13  4988.6  443.93  4994.4  444.05  5007.5  447.18  5017.8  448.74
  5024.2  450.25  5029.8  448.96  5074.2  450.78  5113.1  453.97  5140.9  455.16
  5196.4  457.08  5246.4  457.72  5263.1  458.82  5319.1  459.60  5325.1  459.63
#Mann=6,-1,0
  4129.4    0.05       0  4416.1    0.08       0  4526.5    0.05       0
  4982.1    0.03       0  4988.6    0.05       0  5319.1    0.08       0
Bank Sta=4967,5017.8
Exp/Cntr=0.3,0.1

Type RM Length L Ch R = 1,19438,508,508,508
BEGIN DESCRIPTION:
DEMENT BRANCH 27.0
END DESCRIPTION:
XS GIS Cut Line= 3
      2798225.01      7043675.00      2797475.00      7043925.00
      2797074.98      7044175.01
#Sta/Elev= 30
  4231.7  464.30  4305.5  461.09  4358.2  456.96  4432.0  454.94  4442.5  453.51
  4474.1  451.78  4526.9  450.14  4599.4  449.15  4727.1  447.69  4959.0  447.69
  4969.6  447.51  4980.1  444.04  4987.4  442.82  4987.9  442.02  4993.4  442.02
  4993.9  442.82  5001.2  442.94  5019.6  445.64  5087.7  446.74  5116.6  449.34
  5124.3  448.36  5130.2  449.92  5139.9  449.15  5145.5  449.75  5152.0  451.57
  5197.4  454.12  5203.3  452.85  5224.5  455.19  5276.4  458.27  5494.0  464.54
#Mann=3,-1,0
  4231.7    0.05       0  4987.4    0.03       0  4993.9    0.05       0
Bank Sta=4599.4,5139.9
Exp/Cntr=0.3,0.1

Type RM Length L Ch R = 1,18930,564,564,564
BEGIN DESCRIPTION:
DEMENT BRANCH 26.0
END DESCRIPTION:
XS GIS Cut Line= 3
      2798174.99      7043625.00      2797525.00      7043575.00
      2797074.98      7043625.00
#Sta/Elev= 30
  4316.1  462.82  4356.2  461.45  4406.4  458.47  4446.5  456.45  4456.5  456.31
  4476.6  454.47  4496.6  453.33  4576.9  450.50  4636.6  449.08  4717.3  447.44
  4807.5  446.33  4847.7  447.52  4948.0  446.70  4958.0  446.19  4965.5  444.91
  4970.5  444.91  4978.1  443.45  4988.1  442.24  4994.9  442.22  4995.4  441.42
  5000.9  441.42  5001.4  442.22  5008.3  442.35  5028.4  444.05  5068.6  446.49
  5131.6  449.08  5259.8  457.39  5340.3  461.43  5360.4  462.18  5420.8  462.55
#Mann=3,-1,0
  4316.1    0.05       0  4994.9    0.03       0  5001.4    0.05       0
Bank Sta=4636.6,5131.6
Exp/Cntr=0.3,0.1

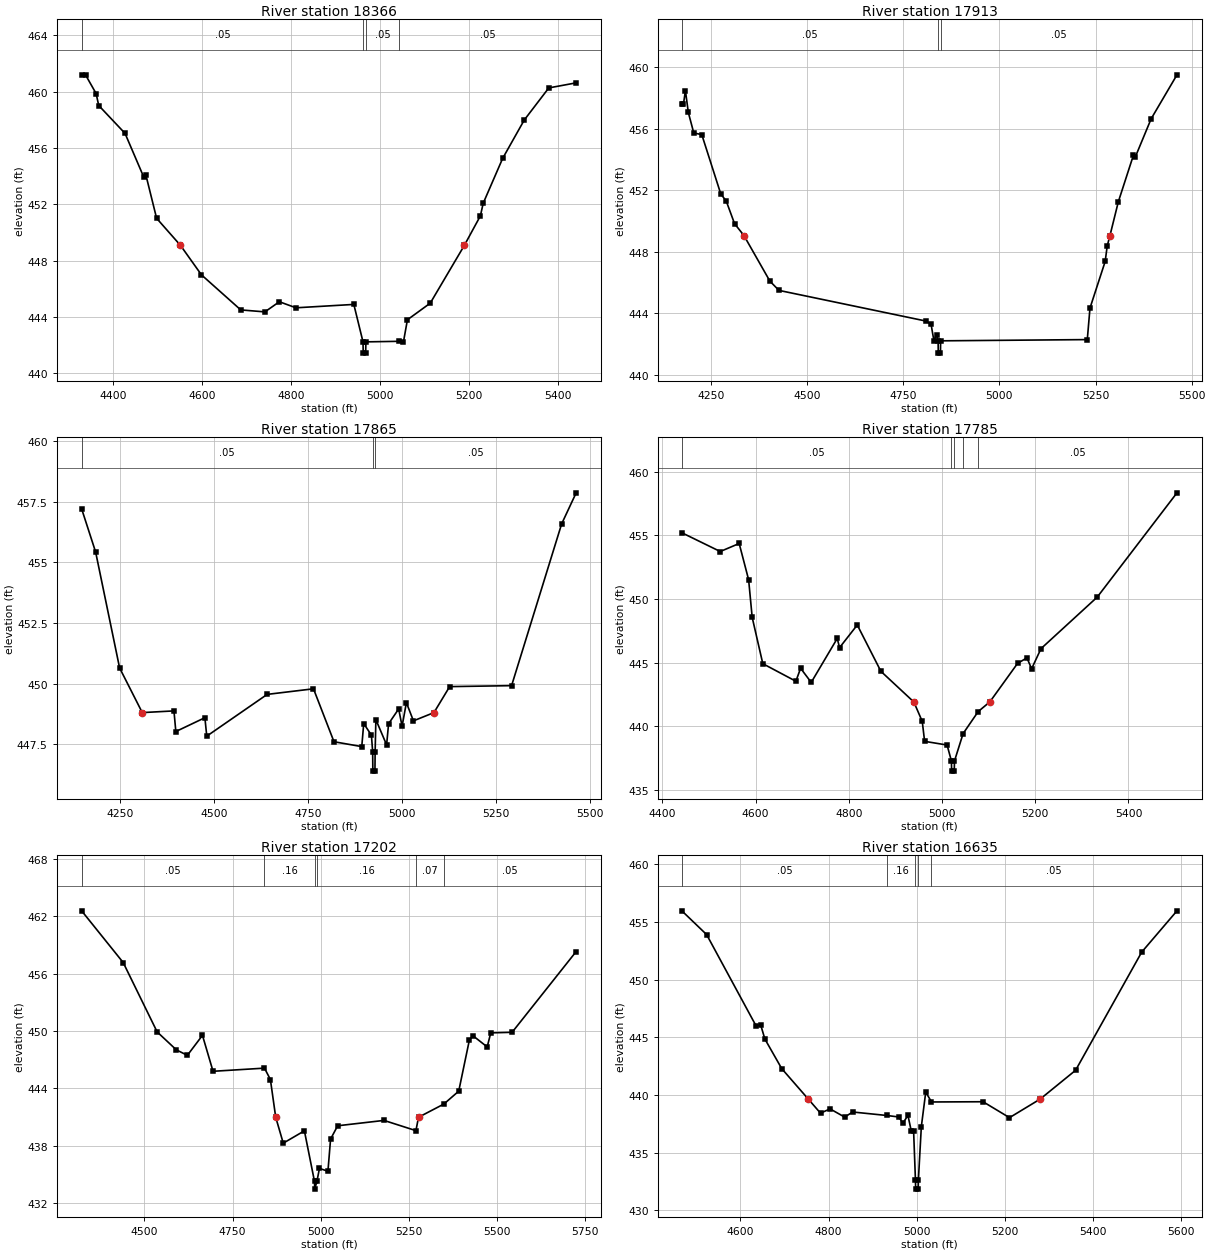
Type RM Length L Ch R = 1,18366,453,453,453
BEGIN DESCRIPTION:
DEMENT BRANCH 25.0
END DESCRIPTION:
XS GIS Cut Line= 3
      2798174.99      7043275.00      2797575.00      7043025.00
      2797124.97      7042924.99
#Sta/Elev= 30
  4330.1  461.19  4339.3  461.16  4362.6  459.86  4368.5  459.01  4427.6  457.03
  4469.3  453.95  4474.7  454.04  4498.5  451.00  4552.0  449.08  4599.3  446.98
  4687.6  444.49  4741.8  444.35  4774.3  445.07  4811.6  444.64  4941.6  444.88
  4962.2  442.22  4962.7  441.42  4968.2  441.42  4968.7  442.22  5044.0  442.26
  5053.1  442.22  5062.0  443.79  5113.3  444.97  5190.0  449.08  5225.9  451.17
  5232.3  452.07  5275.9  455.25  5324.5  457.98  5379.6  460.26  5441.1  460.62
#Mann=4,-1,0
  4330.1    0.05       0  4962.2    0.07       0  4968.7    0.05       0
  5044.0    0.05       0
Bank Sta=4552,5190
Exp/Cntr=0.3,0.1

Type RM Length L Ch R = 1,17913,48,48,48
BEGIN DESCRIPTION:
Mapping XS b7e68f23
END DESCRIPTION:
XS GIS Cut Line= 6
      2798127.78      7043203.35      2797954.15      7043047.08
      2797881.23      7042748.47      2797738.87      7042616.53
      2797589.56      7042585.28      2797220.24      7042720.08
#Sta/Elev= 30
  4175.5  457.60  4178.0  457.60  4183.2  458.49  4190.7  457.08  4204.9  455.74
  4225.8  455.63  4275.2  451.77  4289.4  451.31  4311.0  449.84  4335.4  449.07
  4403.0  446.10  4426.6  445.50  4808.1  443.51  4822.2  443.30  4829.6  442.23
  4836.4  442.63  4840.5  442.22  4841.0  441.42  4846.6  441.42  4847.1  442.22
  5228.6  442.30  5235.6  444.35  5275.1  447.38  5280.5  448.40  5287.6  449.07
  5309.3  451.26  5348.7  454.30  5353.9  454.20  5394.7  456.66  5461.9  459.52
#Mann=3,-1,0
  4175.5    0.05       0  4840.5    0.03       0  4847.1    0.05       0
Bank Sta=4335.4,5287.6
Exp/Cntr=0.3,0.1

Type RM Length L Ch R = 1,17865,80,80,80
BEGIN DESCRIPTION:
Mapping XS 4a0be96e
END DESCRIPTION:
XS GIS Cut Line= 6
      2798127.72      7043165.11      2798009.70      7043050.56
      2797971.51      7042731.11      2797912.48      7042637.36
      2797589.56      7042501.94      2797242.35      7042623.47
#Sta/Elev= 30
  4146.5  457.20  4183.8  455.42  4247.6  450.65  4308.0  448.81  4392.4  448.88
  4397.4  448.03  4474.8  448.60  4479.8  447.84  4640.7  449.56  4764.1  449.79
  4818.7  447.61  4892.7  447.41  4897.9  448.36  4918.4  447.88  4921.7  447.20
  4922.2  446.40  4927.8  446.40  4928.3  447.20  4930.3  448.52  4958.9  447.48
  4964.1  448.35  4991.0  448.96  5000.1  448.25  5011.6  449.22  5030.3  448.47
  5085.0  448.81  5126.8  449.88  5291.8  449.92  5425.1  456.58  5463.8  457.86
#Mann=3,-1,0
  4146.5    0.05       0  4921.7    0.03       0  4928.3    0.05       0
Bank Sta=4308,5085
Exp/Cntr=0.3,0.1

Type RM Length L Ch R = 1,17785,583,583,583
BEGIN DESCRIPTION:
DEMENT BRANCH 24.0
END DESCRIPTION:
XS GIS Cut Line= 3
      2798275.04      7042575.01      2797675.00      7042475.00
      2797224.99      7042425.00
#Sta/Elev= 30
  4443.0  455.17  4524.1  453.72  4564.7  454.35  4585.0  451.50  4592.6  448.55
  4615.4  444.91  4686.4  443.53  4696.5  444.55  4719.3  443.44  4775.1  446.89
  4780.1  446.17  4818.1  447.95  4868.8  444.31  4939.5  441.90  4957.5  440.38
  4962.6  438.81  5010.8  438.52  5020.1  437.27  5020.6  436.47  5026.2  436.47
  5026.7  437.27  5045.2  439.42  5077.6  441.15  5102.6  441.91  5162.0  444.93
  5182.1  445.37  5192.2  444.51  5212.3  446.09  5333.0  450.14  5504.1  458.33
#Mann=5,-1,0
  4443.0    0.05       0  5020.1    0.03       0  5026.7    0.05       0
  5045.2    0.12       0  5077.6    0.05       0
Bank Sta=4939.5,5102.6
Exp/Cntr=0.3,0.1

Type RM Length L Ch R = 1,17202,567,567,567
BEGIN DESCRIPTION:
DEMENT BRANCH 23.0
END DESCRIPTION:
XS GIS Cut Line= 3
      2798625.02      7042325.01      2797975.00      7042075.00
      2797275.05      7041975.01
#Sta/Elev= 30
  4321.8  462.57  4439.7  457.16  4536.1  449.90  4590.7  448.02  4621.8  447.45
  4664.7  449.54  4694.7  445.78  4840.7  446.11  4857.5  444.92  4872.6  440.97
  4894.0  438.26  4954.0  439.55  4982.7  434.25  4983.2  433.45  4989.4  434.25
  4996.8  435.62  5020.8  435.32  5028.3  438.69  5048.5  440.08  5179.9  440.64
  5270.5  439.57  5277.9  440.97  5349.7  442.35  5392.0  443.70  5422.3  449.06
  5432.4  449.50  5472.8  448.33  5482.9  449.80  5543.5  449.86  5725.3  458.31
#Mann=6,-1,0
  4321.8    0.05       0  4840.7    0.16       0  4982.7    0.07       0
  4989.4    0.16       0  5270.5    0.07       0  5349.7    0.05       0
Bank Sta=4872.6,5277.9
Exp/Cntr=0.3,0.1

Type RM Length L Ch R = 1,16635,543,543,543
BEGIN DESCRIPTION:
DEMENT BRANCH 22.0
END DESCRIPTION:
XS GIS Cut Line= 3
      2798474.98      7041525.01      2797975.00      7041675.00
      2797375.00      7041675.00
#Sta/Elev= 30
  4468.5  455.92  4523.3  453.91  4635.5  445.99  4646.0  446.07  4655.5  444.85
  4693.8  442.28  4754.0  439.64  4781.7  438.42  4803.4  438.79  4836.5  438.08
  4854.8  438.52  4931.6  438.22  4959.2  438.09  4968.7  437.56  4980.1  438.22
  4987.9  436.83  4993.0  436.83  4997.1  432.63  4997.6  431.83  5003.3  431.83
  5003.8  432.63  5010.5  437.26  5020.5  440.25  5033.5  439.39  5150.5  439.41
  5210.5  438.03  5280.1  439.64  5360.5  442.14  5510.5  452.39  5590.5  455.97
#Mann=5,-1,0
  4468.5    0.05       0  4931.6    0.16       0  4997.1    0.07       0
  5003.8    0.16       0  5033.5    0.05       0
Bank Sta=4754,5280.1
Exp/Cntr=0.3,0.1