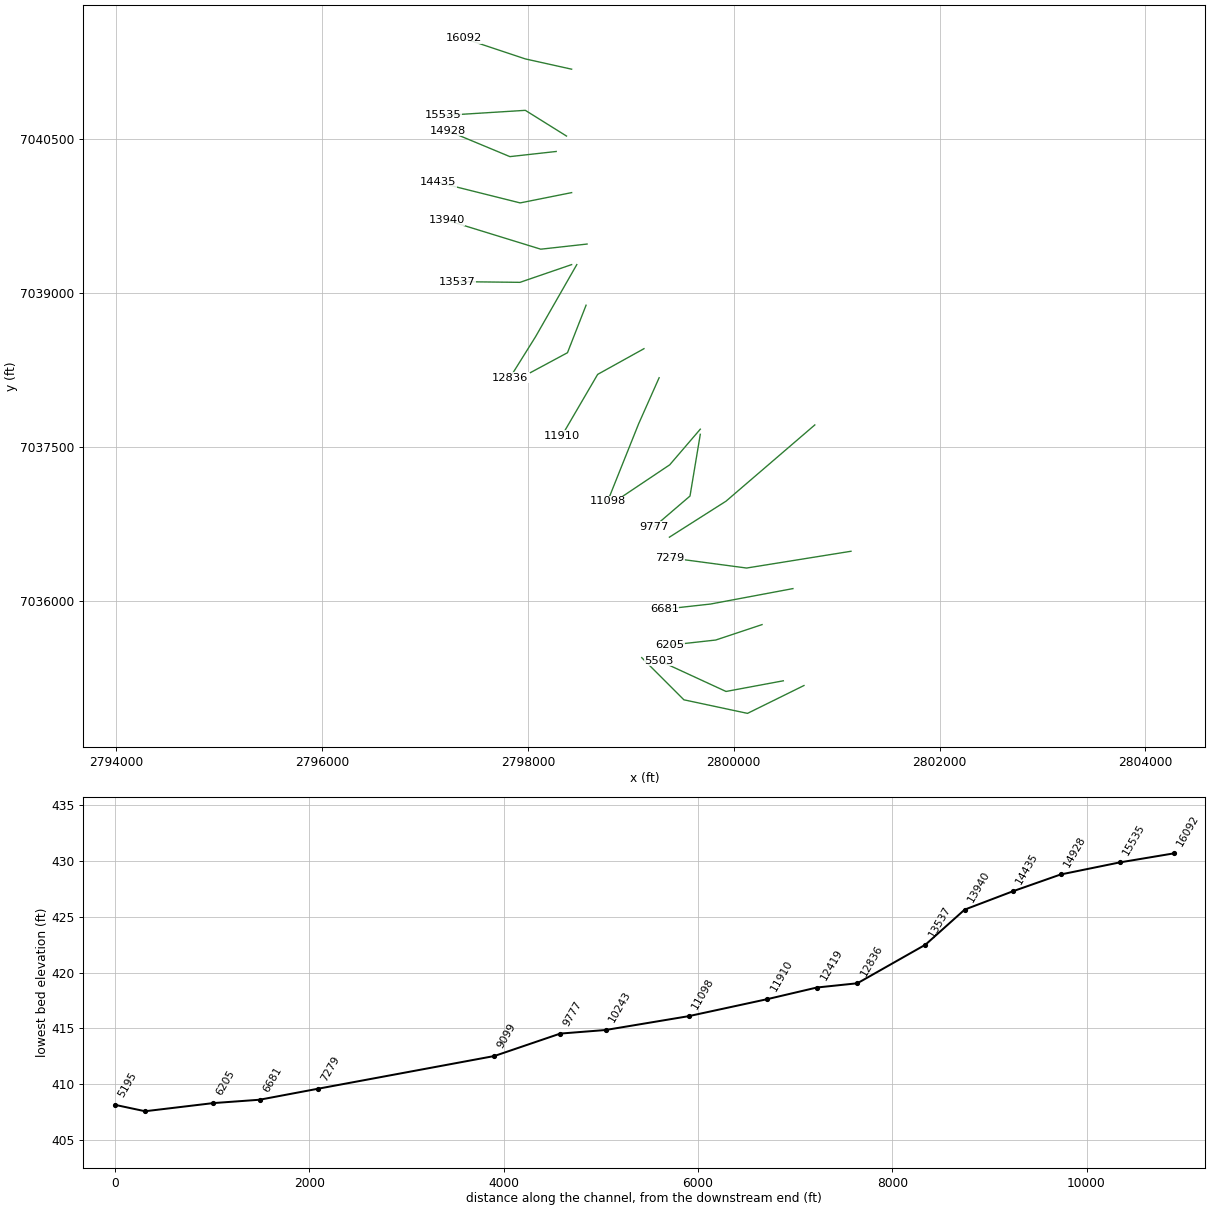
HEC-RAS study DEMENT BRANCH.prj: DEMENT BRANCH Base Level Engineering

--- DEMENT BRANCH.g01 (geometry) --- (continued)

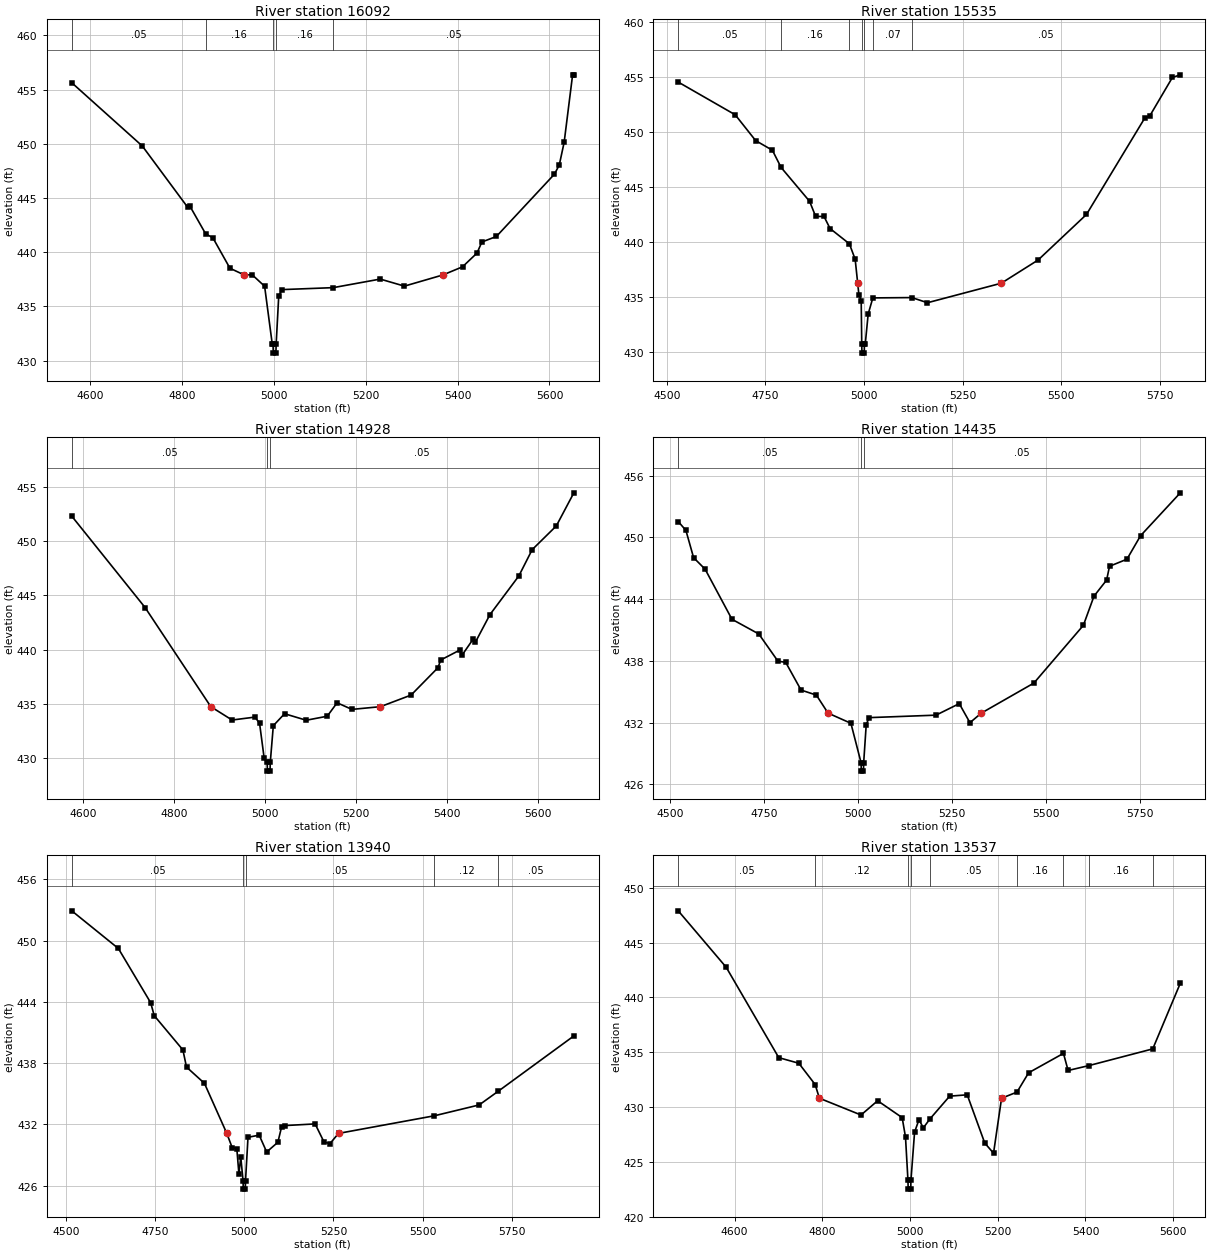
Type RM Length L Ch R = 1,16092,557,557,557
BEGIN DESCRIPTION:
DEMENT BRANCH 21.0
END DESCRIPTION:
XS GIS Cut Line= 3
      2798425.02      7041175.00      2797975.00      7041275.00
      2797374.96      7041475.01
#Sta/Elev= 30
  4559.6  455.63  4713.3  449.79  4811.9  444.15  4817.0  444.24  4851.2  441.69
  4866.9  441.33  4904.1  438.52  4935.3  437.90  4952.7  437.91  4979.6  436.86
  4996.3  431.51  4998.0  431.49  4998.5  430.69  5004.2  430.69  5004.7  431.49
  5010.4  435.99  5018.0  436.55  5129.0  436.73  5231.4  437.52  5284.1  436.87
  5367.8  437.90  5410.6  438.65  5442.2  439.92  5452.8  440.94  5484.4  441.45
  5610.9  447.20  5621.4  448.05  5632.0  450.14  5650.4  456.36  5653.1  456.36
#Mann=5,-1,0
  4559.6    0.05       0  4851.2    0.16       0  4998.0    0.07       0
  5004.7    0.16       0  5129.0    0.05       0
Bank Sta=4935.3,5367.8
Exp/Cntr=0.3,0.1

Type RM Length L Ch R = 1,15535,607,607,607
BEGIN DESCRIPTION:
DEMENT BRANCH 20.0
END DESCRIPTION:
XS GIS Cut Line= 3
      2798375.00      7040525.00      2797975.00      7040775.00
      2797174.96      7040725.00
#Sta/Elev= 30
  4528.9  454.57  4673.4  451.59  4725.2  449.24  4767.7  448.36  4789.6  446.80
  4862.0  443.71  4877.4  442.33  4898.6  442.33  4913.9  441.23  4962.9  439.84
  4977.6  438.43  4984.0  436.25  4987.0  435.22  4992.9  434.67  4994.3  430.68
  4994.8  429.88  5000.6  429.88  5001.1  430.68  5003.1  430.68  5010.6  433.44
  5022.4  434.91  5121.5  434.94  5160.9  434.47  5348.3  436.25  5441.5  438.36
  5564.2  442.51  5712.0  451.29  5724.5  451.47  5782.1  454.99  5802.2  455.23
#Mann=7,-1,0
  4528.9    0.05       0  4789.6    0.16       0  4962.9    0.12       0
  4994.3    0.07       0  5001.1    0.12       0  5022.4    0.07       0
  5121.5    0.05       0
Bank Sta=4984,5348.3
Exp/Cntr=0.3,0.1

Type RM Length L Ch R = 1,14928,493,493,493
BEGIN DESCRIPTION:
DEMENT BRANCH 19.0
END DESCRIPTION:
XS GIS Cut Line= 3
      2798274.98      7040375.00      2797825.00      7040325.00
      2797224.96      7040575.02
#Sta/Elev= 30
  4575.9  452.30  4736.9  443.88  4881.3  434.74  4928.0  433.51  4978.3  433.78
  4988.4  433.21  4998.5  429.99  5005.1  429.60  5005.6  428.80  5011.4  428.80
  5011.9  429.60  5018.6  432.99  5043.3  434.09  5090.9  433.49  5137.0  433.86
  5158.7  435.10  5191.2  434.49  5253.9  434.74  5321.2  435.81  5380.2  438.33
  5386.2  439.04  5427.9  439.95  5433.3  439.50  5457.1  440.94  5462.5  440.69
  5494.5  443.23  5557.9  446.79  5587.1  449.21  5640.2  451.40  5678.7  454.45
#Mann=3,-1,0
  4575.9    0.05       0  5005.1    0.03       0  5011.9    0.05       0
Bank Sta=4881.3,5253.9
Exp/Cntr=0.3,0.1

Type RM Length L Ch R = 1,14435,495,495,495
BEGIN DESCRIPTION:
DEMENT BRANCH 18.0
END DESCRIPTION:
XS GIS Cut Line= 3
      2798425.04      7039975.01      2797925.00      7039875.00
      2797124.96      7040075.01
#Sta/Elev= 30
  4521.7  451.55  4542.1  450.69  4562.5  448.04  4593.1  446.92  4664.5  442.05
  4735.9  440.62  4786.9  437.97  4807.3  437.87  4848.1  435.17  4888.9  434.68
  4919.9  432.93  4980.7  431.94  5007.8  428.09  5008.3  427.29  5014.1  427.29
  5014.6  428.09  5021.4  431.81  5029.1  432.49  5206.9  432.73  5268.7  433.85
  5297.1  432.00  5327.4  432.93  5467.1  435.85  5598.6  441.46  5626.9  444.30
  5660.4  445.86  5668.1  447.20  5714.5  447.89  5750.6  450.17  5856.3  454.34
#Mann=3,-1,0
  4521.7    0.05       0  5007.8    0.03       0  5014.6    0.05       0
Bank Sta=4919.9,5327.4
Exp/Cntr=0.3,0.1

Type RM Length L Ch R = 1,13940,403,403,403
BEGIN DESCRIPTION:
DEMENT BRANCH 17.0
END DESCRIPTION:
XS GIS Cut Line= 3
      2798575.01      7039475.00      2798125.00      7039425.00
      2797211.14      7039706.79
#Sta/Elev= 30
  4515.5  452.92  4646.3  449.23  4736.9  443.92  4746.9  442.65  4827.4  439.29
  4837.5  437.61  4887.8  436.02  4950.6  431.11  4965.8  429.71  4978.7  429.63
  4984.6  427.14  4989.8  428.80  4996.3  426.45  4996.8  425.65  5002.6  425.65
  5003.1  426.45  5010.1  430.73  5041.5  430.94  5062.5  429.29  5093.9  430.24
  5104.3  431.74  5114.8  431.88  5198.5  432.04  5223.7  430.25  5240.4  430.12
  5264.1  431.11  5533.5  432.84  5658.9  433.90  5712.7  435.25  5924.6  440.66
#Mann=5,-1,0
  4515.5    0.05       0  4996.3    0.03       0  5003.1    0.05       0
  5533.5    0.12       0  5712.7    0.05       0
Bank Sta=4950.6,5264.1
Exp/Cntr=0.3,0.1

Type RM Length L Ch R = 1,13537,701,701,701
BEGIN DESCRIPTION:
DEMENT BRANCH 16.0
END DESCRIPTION:
XS GIS Cut Line= 3
      2798425.00      7039275.00      2797922.90      7039102.64
      2797309.19      7039109.57
#Sta/Elev= 30
  4471.6  447.89  4581.0  442.74  4700.8  434.50  4746.5  433.99  4783.7  432.05
  4793.4  430.80  4888.3  429.27  4926.2  430.57  4982.1  429.03  4989.7  427.26
  4995.3  423.31  4995.8  422.51  5001.6  422.51  5002.1  423.31  5010.4  427.71
  5020.4  428.84  5030.4  428.10  5045.6  428.92  5090.4  430.99  5130.4  431.11
  5170.4  426.71  5190.4  425.79  5208.7  430.80  5243.9  431.36  5270.4  433.12
  5349.8  434.89  5360.4  433.33  5408.2  433.78  5553.4  435.30  5616.2  441.29
#Mann=9,-1,0
  4471.6    0.05       0  4783.7    0.12       0  4995.3    0.07       0
  5002.1    0.12       0  5045.6    0.05       0  5243.9    0.16       0
  5349.8    0.12       0  5408.2    0.16       0  5553.4    0.05       0
Bank Sta=4793.4,5208.7
Exp/Cntr=0.3,0.1

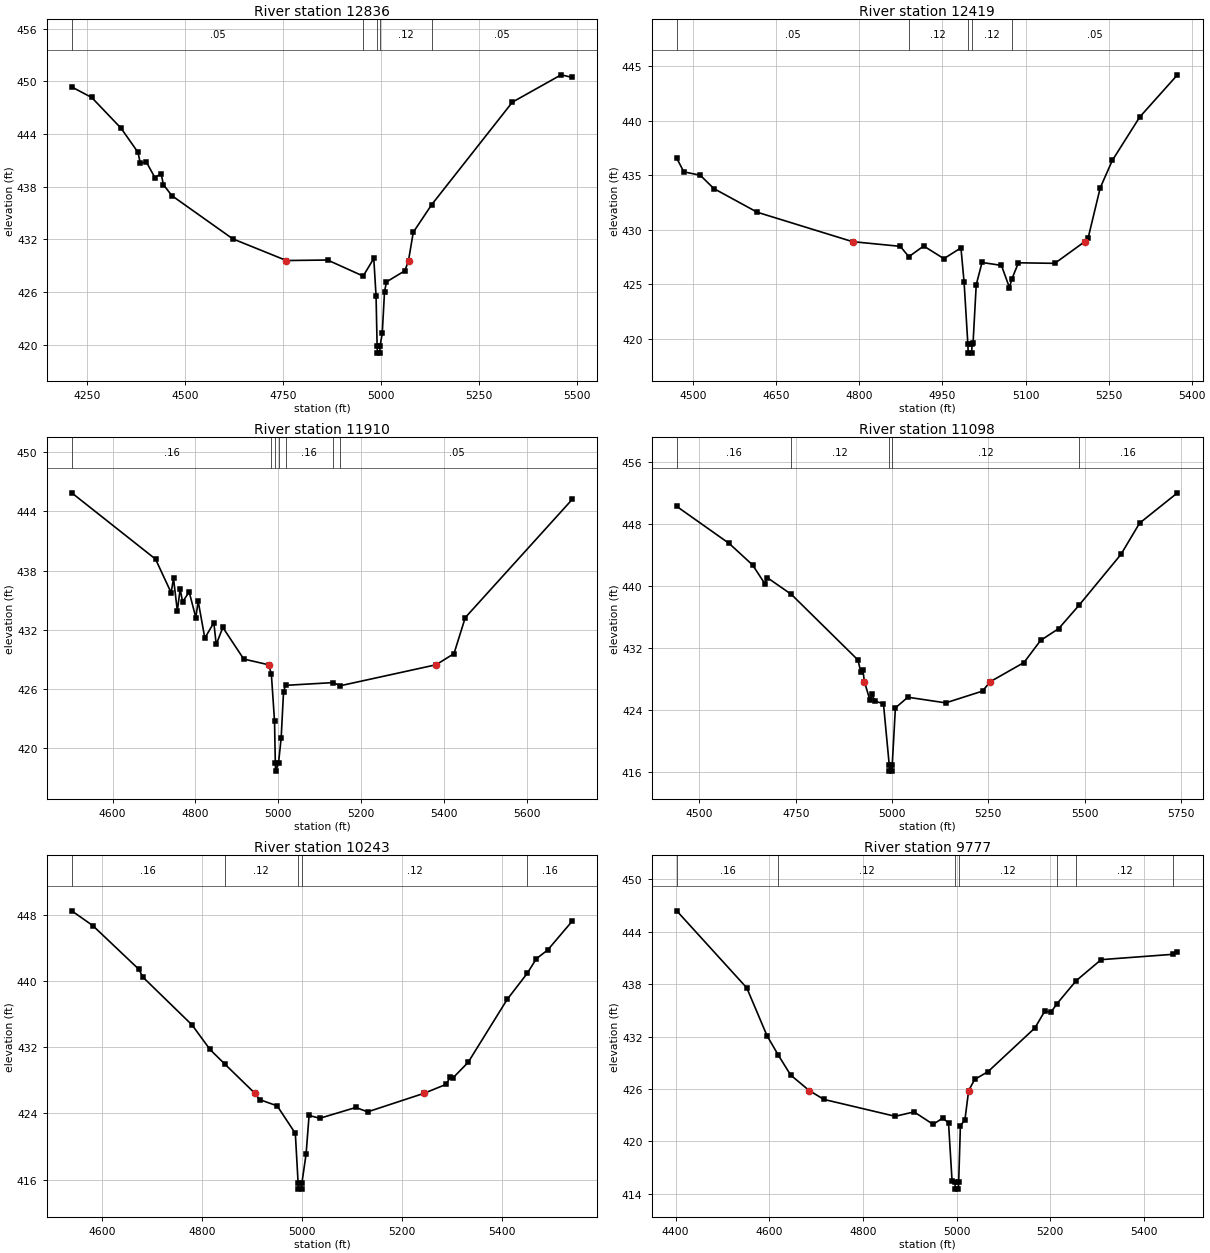
Type RM Length L Ch R = 1,12836,417,417,417
BEGIN DESCRIPTION:
DEMENT BRANCH 15.0
END DESCRIPTION:
XS GIS Cut Line= 3
      2798474.99      7039274.99      2798075.00      7038575.00
      2797825.01      7038175.01
#Sta/Elev= 30
  4210.8  449.35  4261.9  448.15  4336.8  444.65  4379.9  441.91  4385.7  440.70
  4401.5  440.79  4423.1  439.03  4439.0  439.49  4444.7  438.24  4466.3  436.98
  4621.8  432.06  4758.8  429.59  4863.7  429.65  4954.6  427.82  4981.7  429.83
  4987.5  425.55  4990.2  419.85  4990.8  419.05  4997.1  419.05  4997.7  419.85
  5003.3  421.30  5009.1  426.05  5014.1  427.16  5061.2  428.43  5070.3  429.59
  5082.5  432.81  5129.6  435.96  5335.4  447.62  5459.8  450.73  5488.7  450.43
#Mann=5,-1,0
  4210.8    0.05       0  4954.6    0.12       0  4990.2    0.07       0
  4997.7    0.12       0  5129.6    0.05       0
Bank Sta=4758.8,5070.3
Exp/Cntr=0.3,0.1

Type RM Length L Ch R = 1,12419,509,509,509
BEGIN DESCRIPTION:
DEMENT BRANCH 14.0
END DESCRIPTION:
XS GIS Cut Line= 3
      2798565.26      7038880.41      2798384.70      7038418.61
      2798025.04      7038225.02
#Sta/Elev= 30
  4470.1  436.56  4482.9  435.31  4512.7  434.99  4537.2  433.77  4615.5  431.60
  4787.6  428.90  4873.8  428.47  4889.3  427.52  4916.1  428.50  4952.6  427.34
  4983.4  428.33  4989.1  425.16  4995.9  419.47  4996.5  418.67  5002.8  418.67
  5003.4  419.47  5005.3  419.64  5011.0  424.95  5021.5  426.99  5056.5  426.72
  5071.0  424.69  5075.0  425.43  5087.2  426.96  5152.9  426.91  5206.9  428.90
  5213.0  429.22  5234.9  433.84  5256.8  436.36  5306.3  440.34  5374.4  444.21
#Mann=5,-1,0
  4470.1    0.05       0  4889.3    0.12       0  4995.9    0.07       0
  5003.4    0.12       0  5075.0    0.05       0
Bank Sta=4787.6,5206.9
Exp/Cntr=0.3,0.1

Type RM Length L Ch R = 1,11910,812,812,812
BEGIN DESCRIPTION:
DEMENT BRANCH 13.0
END DESCRIPTION:
XS GIS Cut Line= 3
      2799127.74      7038457.62      2798677.78      7038207.64
      2798328.46      7037608.82
#Sta/Elev= 30
  4501.5  445.89  4703.7  439.16  4741.4  435.75  4747.1  437.20  4756.3  433.91
  4763.2  436.13  4768.9  434.81  4784.9  435.83  4800.9  433.22  4806.6  434.89
  4822.6  431.14  4844.4  432.70  4850.1  430.49  4866.1  432.22  4916.5  429.01
  4976.6  428.43  4983.1  427.51  4990.8  422.70  4992.7  418.43  4993.3  417.63
  5000.4  418.43  5006.8  421.00  5012.5  425.68  5017.3  426.34  5132.1  426.62
  5149.3  426.30  5380.5  428.43  5423.7  429.56  5450.9  433.22  5709.5  445.25
#Mann=7,-1,0
  4501.5    0.16       0  4983.1    0.12       0  4992.7    0.07       0
  5000.4    0.12       0  5017.3    0.16       0  5132.1    0.07       0
  5149.3    0.05       0
Bank Sta=4976.6,5380.5
Exp/Cntr=0.3,0.1

Type RM Length L Ch R = 1,11098,855,855,855
BEGIN DESCRIPTION:
DEMENT BRANCH 12.0
END DESCRIPTION:
XS GIS Cut Line= 3
      2799274.99      7038174.98      2799075.00      7037725.00
      2798775.00      7036974.99
#Sta/Elev= 30
  4441.0  450.27  4577.1  445.49  4638.0  442.71  4670.1  440.27  4675.6  441.09
  4738.5  438.92  4911.5  430.45  4919.1  428.87  4924.5  429.09  4928.4  427.63
  4942.8  425.25  4948.2  426.03  4955.0  425.14  4977.8  424.80  4992.8  416.90
  4993.4  416.10  4999.9  416.10  5000.6  416.90  5008.8  424.26  5041.1  425.64
  5139.4  424.91  5235.0  426.43  5254.7  427.63  5342.7  430.12  5385.8  432.97
  5432.9  434.50  5485.3  437.49  5594.4  444.07  5642.9  448.11  5741.2  452.02
#Mann=5,-1,0
  4441.0    0.16       0  4738.5    0.12       0  4992.8    0.07       0
  5000.6    0.12       0  5485.3    0.16       0
Bank Sta=4928.4,5254.7
Exp/Cntr=0.3,0.1

Type RM Length L Ch R = 1,10243,466,466,466
BEGIN DESCRIPTION:
DEMENT BRANCH 11.0
END DESCRIPTION:
XS GIS Cut Line= 3
      2799675.01      7037675.01      2799377.76      7037328.33
      2798925.04      7037025.02
#Sta/Elev= 30
  4539.7  448.46  4582.0  446.67  4674.2  441.39  4681.8  440.47  4780.6  434.67
  4816.3  431.72  4845.4  429.99  4906.1  426.43  4915.6  425.67  4950.7  424.91
  4987.0  421.59  4992.5  415.66  4993.1  414.86  4999.7  414.86  5000.3  415.66
  5008.5  419.09  5014.5  423.76  5035.8  423.41  5108.0  424.72  5131.6  424.19
  5244.5  426.43  5288.6  427.51  5296.7  428.38  5302.7  428.31  5332.7  430.17
  5410.8  437.77  5451.2  440.94  5469.1  442.68  5491.8  443.73  5541.3  447.25
#Mann=5,-1,0
  4539.7    0.16       0  4845.4    0.12       0  4992.5    0.07       0
  5000.3    0.12       0  5451.2    0.16       0
Bank Sta=4906.1,5244.5
Exp/Cntr=0.3,0.1

Type RM Length L Ch R = 1,9777,678,678,678
BEGIN DESCRIPTION:
DEMENT BRANCH 10.0
END DESCRIPTION:
XS GIS Cut Line= 3
      2799675.01      7037625.04      2799575.00      7037025.00
      2799224.99      7036724.99
#Sta/Elev= 30
  4402.2  446.40  4551.8  437.58  4594.9  432.12  4618.8  429.91  4645.5  427.60
  4685.3  425.82  4716.5  424.81  4868.6  422.88  4909.1  423.38  4949.7  421.96
  4970.0  422.66  4982.6  422.14  4990.2  415.46  4996.4  415.34  4997.1  414.54
  5003.7  414.54  5004.3  415.34  5008.0  421.81  5017.6  422.46  5025.6  425.82
  5038.5  427.10  5067.0  427.99  5166.9  432.98  5187.8  434.88  5202.0  434.84
  5213.8  435.74  5255.2  438.40  5308.5  440.81  5461.4  441.42  5471.5  441.68
#Mann=7,-1,0
  4402.2    0.16       0  4618.8    0.12       0  4996.4    0.07       0
  5004.3    0.12       0  5213.8    0.16       0  5255.2    0.12       0
  5461.4    0.16       0
Bank Sta=4685.3,5025.6
Exp/Cntr=0.3,0.1

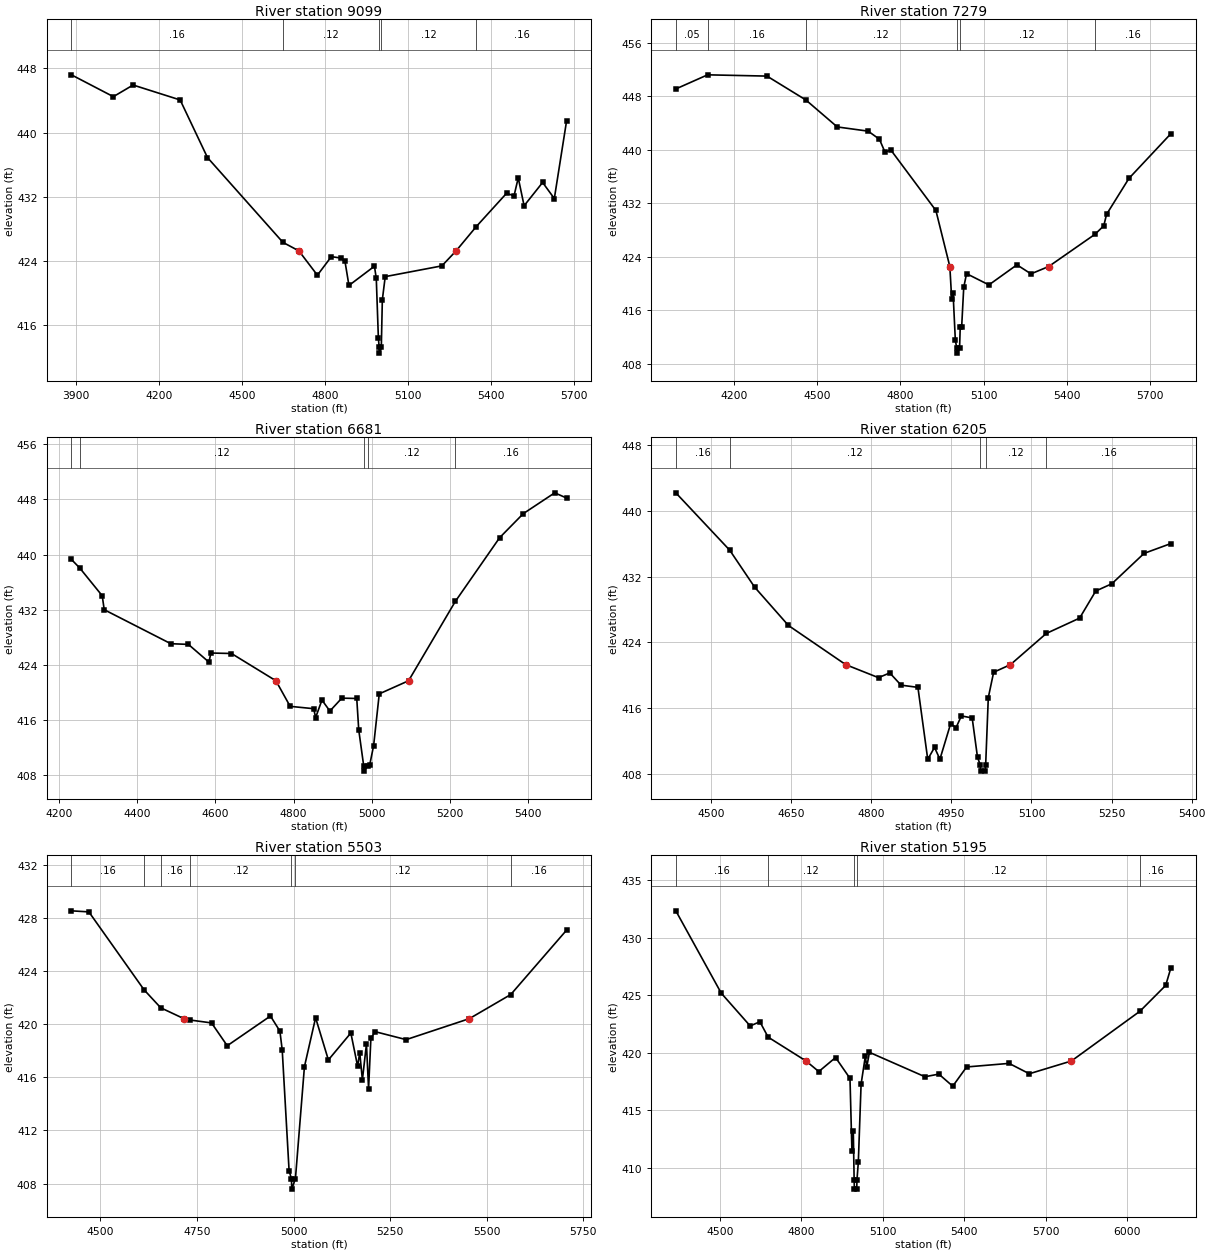
Type RM Length L Ch R = 1,9099,1820,1820,1820
BEGIN DESCRIPTION:
DEMENT BRANCH 9.0
END DESCRIPTION:
XS GIS Cut Line= 3
      2800787.73      7037716.41      2799925.00      7036975.00
      2799374.96      7036624.98
#Sta/Elev= 30
  3883.0  447.20  4034.6  444.48  4105.9  445.93  4276.0  444.07  4374.8  436.89
  4647.4  426.33  4705.1  425.27  4772.0  422.24  4822.5  424.55  4857.6  424.37
  4871.8  423.95  4886.1  420.96  4978.3  423.36  4984.9  421.83  4992.5  414.37
  4995.2  413.33  4995.8  412.53  5003.1  413.33  5006.8  419.18  5017.2  422.06
  5222.0  423.40  5273.4  425.27  5346.2  428.29  5455.7  432.44  5482.8  432.13
  5498.0  434.37  5519.2  430.89  5586.1  433.79  5628.4  431.79  5672.5  441.41
#Mann=5,-1,0
  3883.0    0.16       0  4647.4    0.12       0  4995.2    0.07       0
  5003.1    0.12       0  5346.2    0.16       0
Bank Sta=4705.1,5273.4
Exp/Cntr=0.3,0.1

Type RM Length L Ch R = 1,7279,598,598,598
BEGIN DESCRIPTION:
DEMENT BRANCH 8.0
END DESCRIPTION:
XS GIS Cut Line= 3
      2801139.32      7036488.13      2800125.00      7036325.00
      2799374.99      7036425.00
#Sta/Elev= 30
  3990.9  449.08  4105.4  451.19  4319.4  451.00  4459.5  447.43  4572.6  443.40
  4684.0  442.77  4724.5  441.56  4744.8  439.61  4765.0  439.99  4928.0  430.91
  4978.2  422.53  4984.8  417.74  4989.8  418.65  4998.0  411.55  5002.9  410.39
  5003.8  409.59  5013.3  410.39  5015.7  413.50  5020.8  413.50  5028.3  419.42
  5038.4  421.47  5119.1  419.79  5220.0  422.79  5270.5  421.44  5334.2  422.53
  5501.1  427.35  5532.8  428.62  5542.9  430.33  5623.6  435.71  5774.9  442.40
#Mann=6,-1,0
  3990.9    0.05       0  4105.4    0.16       0  4459.5    0.12       0
  5002.9    0.07       0  5013.3    0.12       0  5501.1    0.16       0
Bank Sta=4978.2,5334.2
Exp/Cntr=0.3,0.1

Type RM Length L Ch R = 1,6681,476,476,476
BEGIN DESCRIPTION:
DEMENT BRANCH 7.0
END DESCRIPTION:
XS GIS Cut Line= 3
      2800574.98      7036125.00      2799775.00      7035975.00
      2799324.99      7035925.00
#Sta/Elev= 30
  4231.8  439.29  4253.0  438.06  4310.6  434.03  4315.7  432.01  4486.1  427.08
  4531.1  426.98  4583.6  424.41  4588.7  425.73  4641.3  425.66  4755.0  421.71
  4791.4  418.00  4851.6  417.66  4856.6  416.38  4872.8  418.91  4893.1  417.32
  4923.6  419.19  4961.8  419.14  4966.9  414.58  4979.5  409.41  4980.4  408.61
  4989.9  409.41  4994.8  409.46  5005.0  412.32  5019.4  419.81  5094.4  421.71
  5214.0  433.21  5327.4  442.45  5387.8  445.93  5468.3  448.95  5498.5  448.20
#Mann=5,-1,0
  4231.8    0.16       0  4253.0    0.12       0  4979.5    0.07       0
  4989.9    0.12       0  5214.0    0.16       0
Bank Sta=4755,5094.4
Exp/Cntr=0.3,0.1

Type RM Length L Ch R = 1,6205,702,702,702
BEGIN DESCRIPTION:
DEMENT BRANCH 6.0
END DESCRIPTION:
XS GIS Cut Line= 3
      2800275.03      7035775.01      2799825.00      7035625.00
      2799375.05      7035575.01
#Sta/Elev= 30
  4434.1  442.23  4535.1  435.23  4581.7  430.73  4645.0  426.06  4752.2  421.29
  4813.6  419.70  4834.7  420.28  4855.8  418.79  4887.4  418.52  4905.8  409.75
  4918.5  411.20  4928.6  409.76  4948.7  414.09  4958.8  413.61  4968.8  415.04
  4989.0  414.79  4999.0  410.00  5003.9  409.11  5004.8  408.31  5013.4  408.31
  5014.3  409.11  5019.2  417.27  5029.2  420.36  5060.7  421.29  5127.8  425.09
  5190.2  426.96  5220.4  430.26  5250.6  431.15  5310.9  434.85  5361.2  436.05
#Mann=5,-1,0
  4434.1    0.16       0  4535.1    0.12       0  5003.9    0.07       0
  5014.3    0.12       0  5127.8    0.16       0
Bank Sta=4752.2,5060.7
Exp/Cntr=0.3,0.1

Type RM Length L Ch R = 1,5503,308,308,308
BEGIN DESCRIPTION:
DEMENT BRANCH 5.0
END DESCRIPTION:
XS GIS Cut Line= 3
      2800481.63      7035228.79      2799925.00      7035125.00
      2799275.02      7035424.99
#Sta/Elev= 30
  4424.9  428.56  4470.1  428.48  4612.9  422.61  4656.2  421.25  4716.2  420.43
  4731.8  420.33  4787.7  420.11  4828.4  418.39  4940.3  420.63  4964.8  419.49
  4970.8  418.06  4988.6  408.95  4994.6  408.38  4995.5  407.58  5005.0  408.38
  5028.3  416.81  5057.2  420.50  5090.3  417.32  5148.5  419.35  5166.0  416.85
  5171.5  417.87  5178.4  415.82  5188.9  418.52  5194.4  415.15  5200.4  418.95
  5211.4  419.45  5291.7  418.85  5455.3  420.43  5562.6  422.25  5707.0  427.10
#Mann=7,-1,0
  4424.9    0.16       0  4612.9    0.12       0  4656.2    0.16       0
  4731.8    0.12       0  4994.6    0.07       0  5005.0    0.12       0
  5562.6    0.16       0
Bank Sta=4716.2,5455.3
Exp/Cntr=0.3,0.1

Type RM Length L Ch R = 1,5195,0,0,0
BEGIN DESCRIPTION:
Mapping XS 2cae0d84
END DESCRIPTION:
XS GIS Cut Line= 4
      2800682.46      7035182.79      2800133.83      7034911.96
      2799515.78      7035043.90      2799106.09      7035453.59
#Sta/Elev= 30
  4338.4  432.32  4505.6  425.17  4612.3  422.32  4647.8  422.69  4678.3  421.35
  4817.9  419.28  4864.8  418.36  4926.6  419.58  4979.7  417.77  4986.8  411.50
  4991.9  413.20  4995.0  408.95  4995.9  408.15  5004.5  408.15  5005.4  408.95
  5010.4  410.48  5020.6  417.27  5036.3  419.70  5041.4  418.75  5051.3  420.03
  5255.8  417.91  5306.9  418.14  5358.1  417.09  5409.2  418.76  5565.6  419.07
  5640.1  418.17  5795.2  419.28  6047.5  423.60  6142.2  425.84  6161.6  427.38
#Mann=5,-1,0
  4338.4    0.16       0  4678.3    0.12       0  4995.0    0.07       0
  5005.4    0.12       0  6047.5    0.16       0
Bank Sta=4817.9,5795.2
Exp/Cntr=0.3,0.1

Chan Stop Cuts=-1