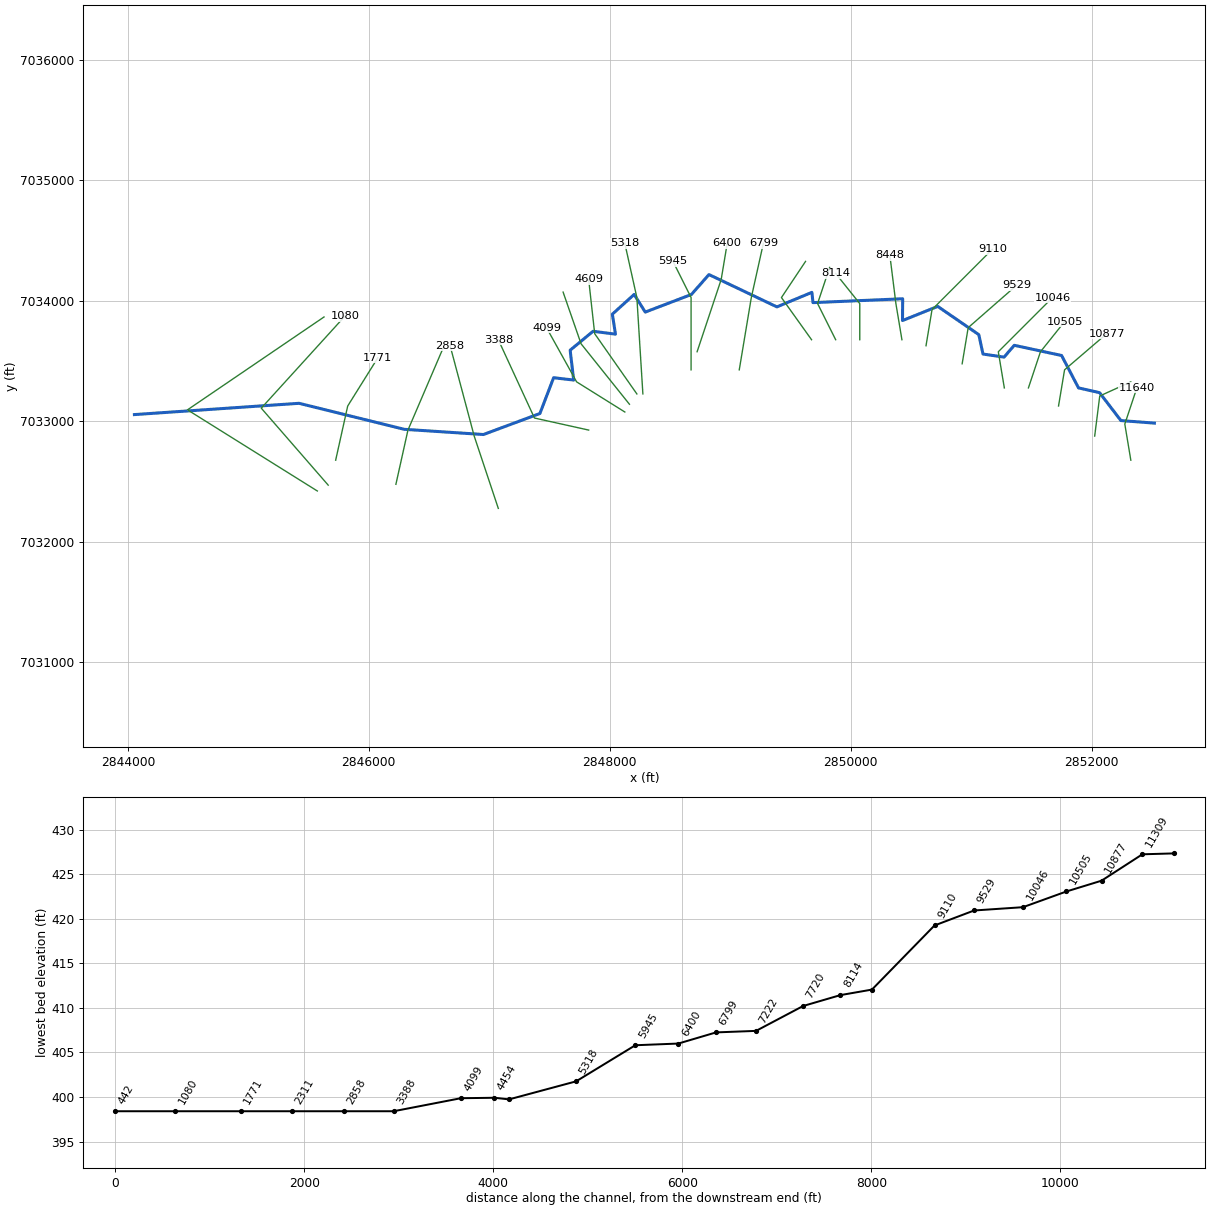
--- DOUBLE BRANCH.prj (project) ---

Proj Title=DOUBLE BRANCH Base Level Engineering
Current Plan=p01
Default Exp/Contr=0.3,0.1
English Units
Geom File=g01
Flow File=f01
Plan File=p01
Y Axis Title=Elevation
X Axis Title(PF)=Main Channel Distance
X Axis Title(XS)=Station
BEGIN DESCRIPTION:
DOUBLE BRANCH
END DESCRIPTION:
DSS Export Rating Curves= 0
DSS Export Rating Curve Sorted= 0
DSS Export Volume Flow Curves= 0
DXF OffsetX= 0
DXF OffsetY= 0
DXF ScaleX= 1
DXF ScaleY= 10

--- DOUBLE BRANCH.p01 (plan) ---

Plan Title=Multiple Run
Short Identifier=Multiple
Geom File=g01
Flow File=f01
Subcritical Flow
K Sum by GR= 0
Std Step Tol= 0.01
Critical Tol= 0.01
Num of Std Step Trials= 20
Max Error Tol= 0.3
Flow Tol Ratio= 0.001
Split Flow NTrial= 30
Split Flow Tol= 0.02
Split Flow Ratio= 0.02
Log Output Level= 0
Friction Slope Method= 1
Unsteady Friction Slope Method= 2
Unsteady Bridges Friction Slope Method= 1
Parabolic Critical Depth
Global Vel Dist=  1 , 1 , 1
Global Log Level= 0
CheckData=True
Encroach Param= -1, 0, 0, 0
BEGIN DESCRIPTION:
Multiple Run
END DESCRIPTION:

--- DOUBLE BRANCH.f01 (steady flow) ---

Flow Title=Multiple
Program Version=5.07
Number of Profiles= 7
Profile Names=10-year,25-year,50-year,1pct_min,100-year,1pct_plu,500-year
River Rch & RM=DOUBLE BRANCH,Reach-1         ,11640
     445     585     696     412     822    1640    1148
River Rch & RM=DOUBLE BRANCH,Reach-1         ,6799
     648     867    1044     624    1245    2485    1776
Boundary for River Rch & Prof#=DOUBLE BRANCH,Reach-1         , 1
Up Type= 0
Dn Type= 3
Dn Slope=0.005
Boundary for River Rch & Prof#=DOUBLE BRANCH,Reach-1         , 2
Up Type= 0
Dn Type= 3
Dn Slope=0.005
Boundary for River Rch & Prof#=DOUBLE BRANCH,Reach-1         , 3
Up Type= 0
Dn Type= 3
Dn Slope=0.005
Boundary for River Rch & Prof#=DOUBLE BRANCH,Reach-1         , 4
Up Type= 0
Dn Type= 3
Dn Slope=0.005
Boundary for River Rch & Prof#=DOUBLE BRANCH,Reach-1         , 5
Up Type= 0
Dn Type= 3
Dn Slope=0.005
Boundary for River Rch & Prof#=DOUBLE BRANCH,Reach-1         , 6
Up Type= 0
Dn Type= 3
Dn Slope=0.005
Boundary for River Rch & Prof#=DOUBLE BRANCH,Reach-1         , 7
Up Type= 0
Dn Type= 3
Dn Slope=0.005
DSS Import GetInterval= 0
DSS Import GetPeak= 0
DSS Import FillOption= 0

--- DOUBLE BRANCH.g01 (geometry) ---

Geom Title=Existing Conditions

River Reach=DOUBLE BRANCH,Reach-1
Reach XY= 30
      2852520.77      7032982.66      2852242.44      7033003.97
      2852065.32      7033235.69      2851890.86      7033274.98
      2851750.36      7033543.98      2851357.50      7033628.55
      2851272.94      7033530.67      2851097.82      7033555.97
      2851063.19      7033717.11      2850722.27      7033951.49
      2850429.95      7033834.30      2850431.29      7034014.75
      2849686.85      7033982.79      2849677.53      7034068.02
      2849387.21      7033947.50      2848823.22      7034215.84
      2848678.07      7034050.71      2848294.53      7033904.22
      2848202.64      7034050.71      2848021.52      7033886.90
      2848047.49      7033721.10      2847861.72      7033745.08
      2847671.28      7033587.93      2847700.58      7033340.23
      2847534.11      7033359.54      2847420.25      7033062.57
      2846951.63      7032888.13      2846294.35      7032931.30
      2845421.18      7033147.20      2844054.63      7033053.53

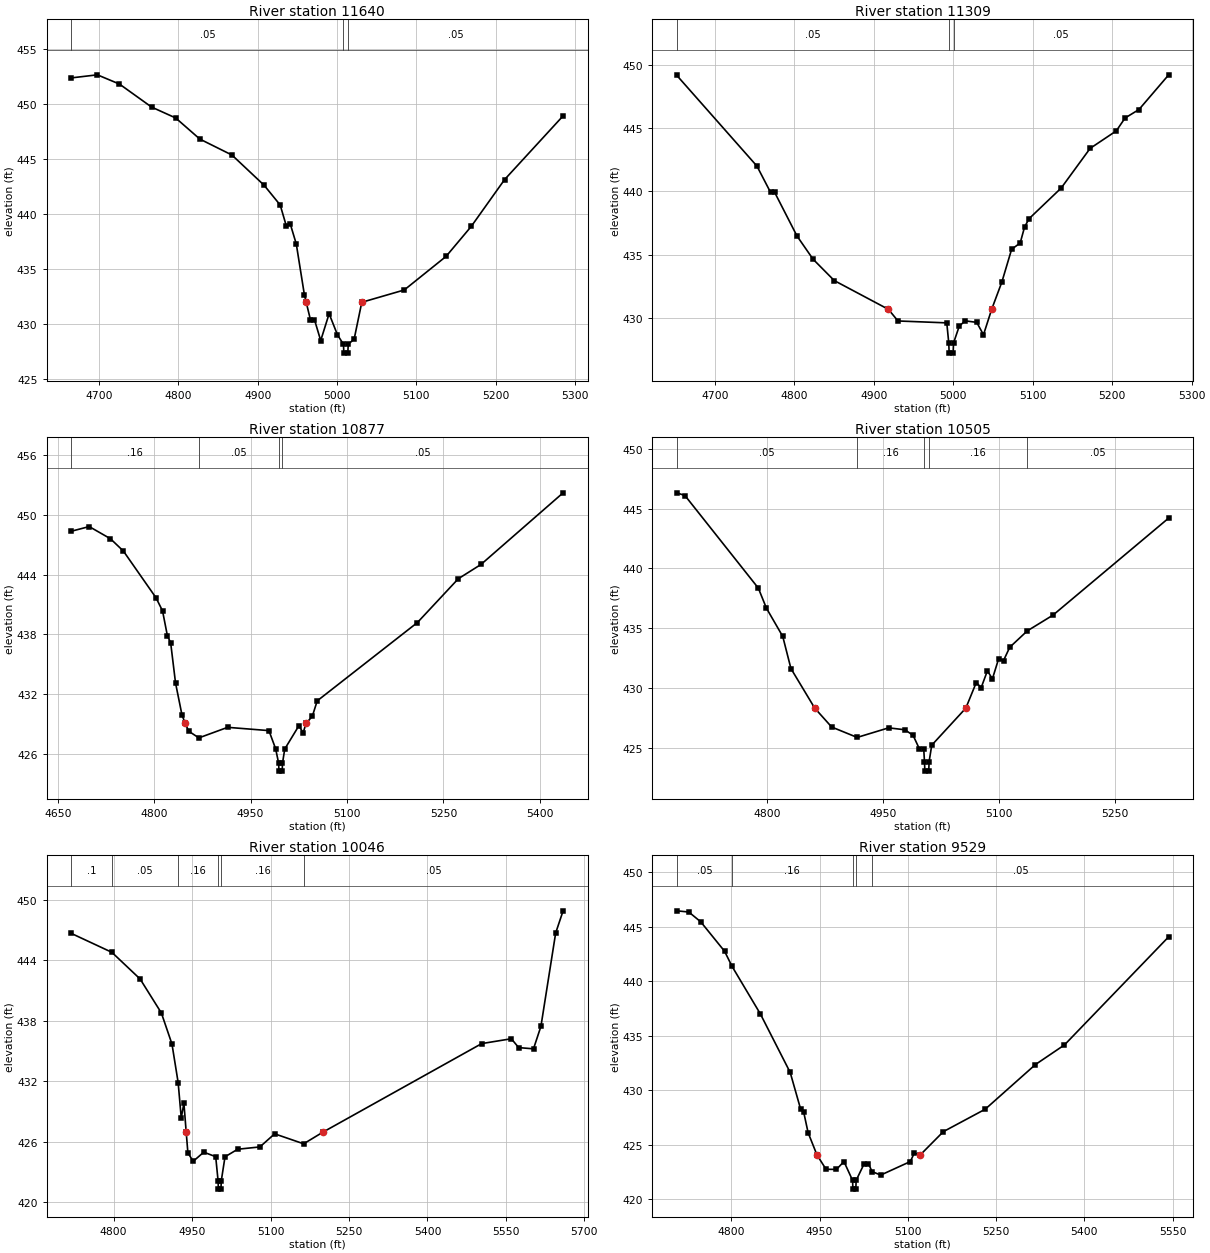
Type RM Length L Ch R = 1,11640,331,331,331
BEGIN DESCRIPTION:
DOUBLE BRANCH 22.0
END DESCRIPTION:
XS GIS Cut Line= 3
      2852324.99      7032675.05      2852275.00      7032975.00
      2852374.99      7033274.98
#Sta/Elev= 30
  4664.8  452.33  4697.7  452.61  4725.6  451.77  4766.1  449.68  4796.5  448.69
  4827.0  446.77  4867.5  445.32  4908.1  442.57  4928.3  440.78  4935.9  438.91
  4941.0  439.06  4948.6  437.24  4958.8  432.63  4961.1  431.94  4966.4  430.37
  4971.5  430.37  4979.4  428.46  4990.0  430.90  5000.5  428.99  5008.1  428.12
  5008.6  427.32  5013.6  427.32  5014.1  428.12  5021.6  428.60  5031.2  431.94
  5084.8  433.06  5137.5  436.11  5169.2  438.83  5211.3  443.09  5285.1  448.88
#Mann=3,-1,0
  4664.8    0.05       0  5008.1    0.03       0  5014.1    0.05       0
Bank Sta=4961.1,5031.2
Exp/Cntr=0.3,0.1

Type RM Length L Ch R = 1,11309,432,432,432
BEGIN DESCRIPTION:
DOUBLE BRANCH 21.0
END DESCRIPTION:
XS GIS Cut Line= 3
      2852024.99      7032874.95      2852067.07      7033208.06
      2852325.04      7033325.02
#Sta/Elev= 30
  4652.1  449.15  4752.9  441.99  4770.0  439.92  4775.0  439.94  4803.3  436.47
  4823.5  434.64  4850.2  432.95  4918.3  430.68  4930.4  429.76  4991.8  429.61
  4994.3  428.02  4994.8  427.22  4999.8  427.22  5000.3  428.02  5007.5  429.35
  5014.9  429.77  5029.5  429.65  5038.0  428.67  5048.3  430.68  5061.1  432.83
  5073.4  435.42  5084.2  435.92  5089.7  437.18  5095.4  437.84  5135.8  440.26
  5172.2  443.39  5205.1  444.77  5216.2  445.79  5233.7  446.46  5271.1  449.20
#Mann=3,-1,0
  4652.1    0.05       0  4994.3    0.03       0  5000.3    0.05       0
Bank Sta=4918.3,5048.3
Exp/Cntr=0.3,0.1

Type RM Length L Ch R = 1,10877,372,372,372
BEGIN DESCRIPTION:
DOUBLE BRANCH 20.0
END DESCRIPTION:
XS GIS Cut Line= 3
      2851725.00      7033124.98      2851775.00      7033425.00
      2852124.97      7033724.98
#Sta/Elev= 30
  4671.1  448.36  4699.0  448.83  4732.0  447.61  4752.2  446.37  4802.9  441.68
  4813.1  440.36  4820.7  437.84  4825.7  437.17  4833.3  433.12  4843.5  429.85
  4848.6  429.06  4853.6  428.28  4869.6  427.60  4914.4  428.66  4978.6  428.33
  4989.0  426.51  4993.7  425.06  4994.2  424.26  4999.2  424.26  4999.7  425.06
  5003.2  426.48  5025.2  428.82  5031.8  428.11  5036.4  429.06  5046.1  429.77
  5053.7  431.32  5209.6  439.19  5273.2  443.59  5308.4  445.02  5436.2  452.22
#Mann=4,-1,0
  4671.1    0.16       0  4869.6    0.05       0  4993.7    0.03       0
  4999.7    0.05       0
Bank Sta=4848.6,5036.4
Exp/Cntr=0.3,0.1

Type RM Length L Ch R = 1,10505,459,459,459
BEGIN DESCRIPTION:
DOUBLE BRANCH 19.0
END DESCRIPTION:
XS GIS Cut Line= 3
      2851475.01      7033275.02      2851575.00      7033575.00
      2851775.02      7033825.03
#Sta/Elev= 30
  4683.6  446.33  4694.1  446.10  4789.0  438.36  4799.5  436.68  4820.6  434.32
  4831.2  431.63  4862.0  428.32  4883.9  426.74  4916.9  425.87  4957.6  426.67
  4978.7  426.51  4989.3  426.04  4997.2  424.94  5003.0  424.94  5004.0  423.85
  5004.5  423.05  5009.5  423.05  5010.0  423.85  5013.4  425.22  5057.5  428.32
  5071.0  430.46  5077.4  430.04  5085.4  431.44  5091.9  430.77  5099.9  432.44
  5106.3  432.30  5114.3  433.41  5137.0  434.78  5170.3  436.10  5320.0  444.22
#Mann=5,-1,0
  4683.6    0.05       0  4916.9    0.16       0  5004.0    0.07       0
  5010.0    0.16       0  5137.0    0.05       0
Bank Sta=4862,5057.5
Exp/Cntr=0.3,0.1

Type RM Length L Ch R = 1,10046,517,517,517
BEGIN DESCRIPTION:
DOUBLE BRANCH 18.0
END DESCRIPTION:
XS GIS Cut Line= 3
      2851274.99      7033275.04      2851225.00      7033575.00
      2851675.01      7034025.01
#Sta/Elev= 30
  4718.9  446.68  4796.6  444.80  4850.6  442.15  4891.2  438.78  4911.5  435.69
  4923.3  431.87  4929.2  428.36  4934.3  429.82  4938.7  426.94  4941.9  424.90
  4952.0  424.05  4972.3  424.96  4995.1  424.51  4999.7  422.09  5000.2  421.29
  5005.2  421.29  5005.7  422.09  5012.9  424.50  5037.1  425.25  5079.6  425.48
  5107.8  426.78  5163.3  425.79  5199.9  426.94  5503.8  435.74  5560.4  436.22
  5574.5  435.34  5602.8  435.22  5617.0  437.45  5645.2  446.72  5659.4  448.92
#Mann=6,-1,0
  4718.9     0.1       0  4796.6    0.05       0  4923.3    0.16       0
  4999.7    0.07       0  5005.7    0.16       0  5163.3    0.05       0
Bank Sta=4938.7,5199.9
Exp/Cntr=0.3,0.1

Type RM Length L Ch R = 1,9529,419,419,419
BEGIN DESCRIPTION:
DOUBLE BRANCH 17.0
END DESCRIPTION:
XS GIS Cut Line= 3
      2850925.00      7033474.99      2850975.00      7033775.00
      2851375.04      7034125.03
#Sta/Elev= 30
  4707.5  446.45  4727.8  446.34  4748.1  445.44  4788.6  442.74  4801.2  441.36
  4849.4  436.99  4900.1  431.62  4917.9  428.24  4922.9  428.01  4930.5  426.10
  4945.6  424.05  4961.0  422.74  4978.7  422.73  4991.4  423.45  5006.1  421.72
  5006.6  420.92  5011.6  420.92  5012.1  421.72  5025.4  423.21  5033.0  423.27
  5039.1  422.53  5053.9  422.21  5104.2  423.45  5110.8  424.22  5120.9  424.05
  5160.2  426.19  5231.4  428.25  5316.8  432.35  5366.1  434.15  5543.2  444.07
#Mann=5,-1,0
  4707.5    0.05       0  4801.2    0.16       0  5006.1    0.07       0
  5012.1    0.16       0  5039.1    0.05       0
Bank Sta=4945.6,5120.9
Exp/Cntr=0.3,0.1

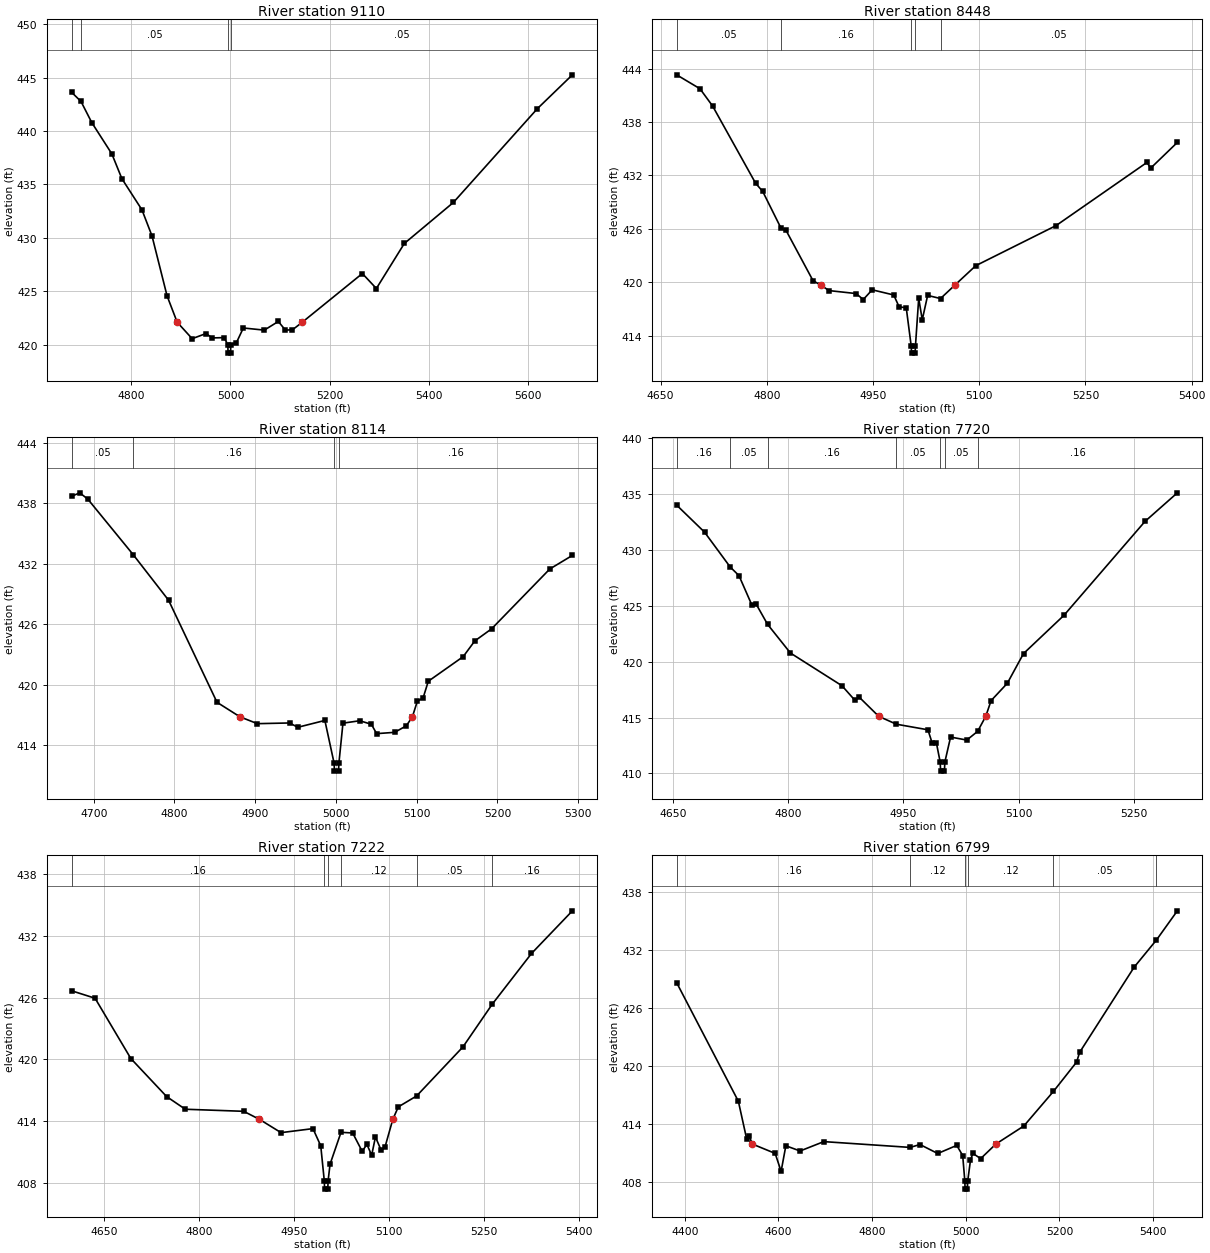
Type RM Length L Ch R = 1,9110,662,662,662
BEGIN DESCRIPTION:
DOUBLE BRANCH 16.0
END DESCRIPTION:
XS GIS Cut Line= 3
      2850625.00      7033625.00      2850675.00      7033925.00
      2851174.97      7034424.97
#Sta/Elev= 30
  4679.3  443.61  4698.1  442.76  4719.8  440.79  4760.4  437.86  4780.7  435.54
  4821.2  432.63  4841.5  430.19  4871.9  424.59  4892.3  422.13  4922.6  420.59
  4950.5  421.07  4963.2  420.66  4987.0  420.69  4994.6  420.04  4995.1  419.24
  5000.1  419.24  5000.6  420.04  5011.7  420.19  5025.9  421.59  5068.3  421.39
  5096.6  422.20  5110.7  421.40  5124.9  421.41  5145.0  422.13  5266.3  426.68
  5294.6  425.28  5351.1  429.49  5450.1  433.32  5619.8  442.09  5690.5  445.25
#Mann=4,-1,0
  4679.3     0.1       0  4698.1    0.05       0  4994.6    0.03       0
  5000.6    0.05       0
Bank Sta=4892.3,5145
Exp/Cntr=0.3,0.1

Type RM Length L Ch R = 1,8448,334,334,334
BEGIN DESCRIPTION:
DOUBLE BRANCH 15.0
END DESCRIPTION:
XS GIS Cut Line= 3
      2850425.00      7033675.02      2850375.00      7033975.00
      2850325.00      7034374.97
#Sta/Elev= 30
  4672.6  443.30  4705.5  441.74  4723.3  439.81  4784.1  431.13  4794.2  430.20
  4820.2  426.05  4827.2  425.82  4865.2  420.19  4876.6  419.66  4888.0  419.07
  4926.0  418.74  4936.2  418.07  4948.8  419.16  4979.2  418.58  4986.8  417.25
  4996.9  417.14  5003.9  412.85  5004.4  412.05  5009.4  412.05  5009.9  412.85
  5014.5  418.21  5019.5  415.79  5027.1  418.53  5045.3  418.18  5065.2  419.66
  5095.1  421.87  5208.5  426.37  5337.0  433.47  5342.0  432.81  5379.8  435.71
#Mann=5,-1,0
  4672.6    0.05       0  4820.2    0.16       0  5003.9    0.07       0
  5009.9    0.16       0  5045.3    0.05       0
Bank Sta=4876.6,5065.2
Exp/Cntr=0.3,0.1

Type RM Length L Ch R = 1,8114,394,394,394
BEGIN DESCRIPTION:
DOUBLE BRANCH 14.0
END DESCRIPTION:
XS GIS Cut Line= 3
      2850075.00      7033674.99      2850075.00      7033975.00
      2849874.98      7034225.02
#Sta/Elev= 30
  4672.7  438.71  4682.7  439.05  4692.7  438.42  4748.9  432.91  4792.7  428.39
  4852.7  418.26  4881.1  416.82  4902.7  416.14  4942.7  416.21  4952.7  415.78
  4986.3  416.46  4997.7  412.23  4998.2  411.43  5003.2  411.43  5003.7  412.23
  5008.7  416.19  5029.5  416.43  5043.9  416.08  5050.4  415.15  5072.8  415.28
  5087.2  415.93  5094.7  416.82  5100.8  418.36  5108.0  418.70  5114.4  420.35
  5157.6  422.79  5172.0  424.35  5192.8  425.55  5264.9  431.49  5292.9  432.84
#Mann=4,-1,0
  4672.7    0.05       0  4748.9    0.16       0  4997.7    0.07       0
  5003.7    0.16       0
Bank Sta=4881.1,5094.7
Exp/Cntr=0.3,0.1

Type RM Length L Ch R = 1,7720,498,498,498
BEGIN DESCRIPTION:
DOUBLE BRANCH 13.0
END DESCRIPTION:
XS GIS Cut Line= 3
      2849875.00      7033674.99      2849725.00      7033975.00
      2849824.99      7034274.96
#Sta/Elev= 30
  4654.8  434.02  4691.1  431.60  4724.5  428.48  4735.9  427.71  4752.6  425.09
  4758.2  425.17  4773.1  423.35  4802.9  420.78  4870.0  417.85  4886.8  416.55
  4892.4  416.83  4917.7  415.12  4940.7  414.41  4981.8  413.91  4987.4  412.71
  4992.9  412.71  4997.8  411.01  4998.3  410.21  5003.3  410.21  5003.8  411.01
  5011.3  413.26  5032.4  412.99  5046.5  413.77  5057.1  415.12  5064.0  416.52
  5085.1  418.07  5106.2  420.73  5158.9  424.16  5264.3  432.56  5306.4  435.12
#Mann=7,-1,0
  4654.8    0.16       0  4724.5    0.05       0  4773.1    0.16       0
  4940.7    0.05       0  4997.8    0.03       0  5003.8    0.05       0
  5046.5    0.16       0
Bank Sta=4917.7,5057.1
Exp/Cntr=0.3,0.1

Type RM Length L Ch R = 1,7222,423,423,423
BEGIN DESCRIPTION:
DOUBLE BRANCH 12.0
END DESCRIPTION:
XS GIS Cut Line= 3
      2849675.01      7033674.99      2849425.00      7034025.00
      2849625.01      7034325.01
#Sta/Elev= 30
  4598.4  426.66  4635.3  425.94  4691.8  420.09  4748.3  416.40  4777.8  415.17
  4870.0  414.97  4894.9  414.19  4929.0  412.90  4979.4  413.29  4991.7  411.62
  4997.3  408.22  4997.8  407.42  5002.8  407.42  5003.3  408.22  5006.4  409.84
  5023.7  412.93  5042.1  412.87  5057.1  411.09  5064.6  411.76  5072.1  410.71
  5078.1  412.48  5087.1  411.19  5093.1  411.49  5105.5  414.19  5114.2  415.40
  5143.1  416.46  5216.3  421.22  5262.5  425.36  5324.5  430.28  5389.1  434.42
#Mann=6,-1,0
  4598.4    0.16       0  4997.3    0.07       0  5003.3    0.16       0
  5023.7    0.12       0  5143.1    0.05       0  5262.5    0.16       0
Bank Sta=4894.9,5105.5
Exp/Cntr=0.3,0.1

Type RM Length L Ch R = 1,6799,399,399,399
BEGIN DESCRIPTION:
DOUBLE BRANCH 11.0
END DESCRIPTION:
XS GIS Cut Line= 3
      2849075.00      7033424.97      2849175.00      7034025.00
      2849275.00      7034475.02
#Sta/Elev= 30
  4382.6  428.63  4514.4  416.35  4532.2  412.43  4537.2  412.79  4544.2  411.92
  4593.0  410.95  4605.7  409.09  4615.8  411.74  4646.2  411.20  4696.9  412.17
  4881.3  411.57  4902.2  411.87  4940.2  410.94  4980.8  411.78  4993.5  410.73
  4998.1  408.05  4998.6  407.25  5003.6  407.25  5004.1  408.05  5010.1  410.24
  5015.2  410.95  5031.9  410.41  5064.4  411.92  5124.1  413.79  5187.3  417.37
  5236.8  420.41  5243.2  421.41  5359.7  430.24  5407.3  433.05  5451.9  436.07
#Mann=6,-1,0
  4382.6    0.16       0  4881.3    0.12       0  4998.1    0.07       0
  5004.1    0.12       0  5187.3    0.05       0  5407.3    0.16       0
Bank Sta=4544.2,5064.4
Exp/Cntr=0.3,0.1

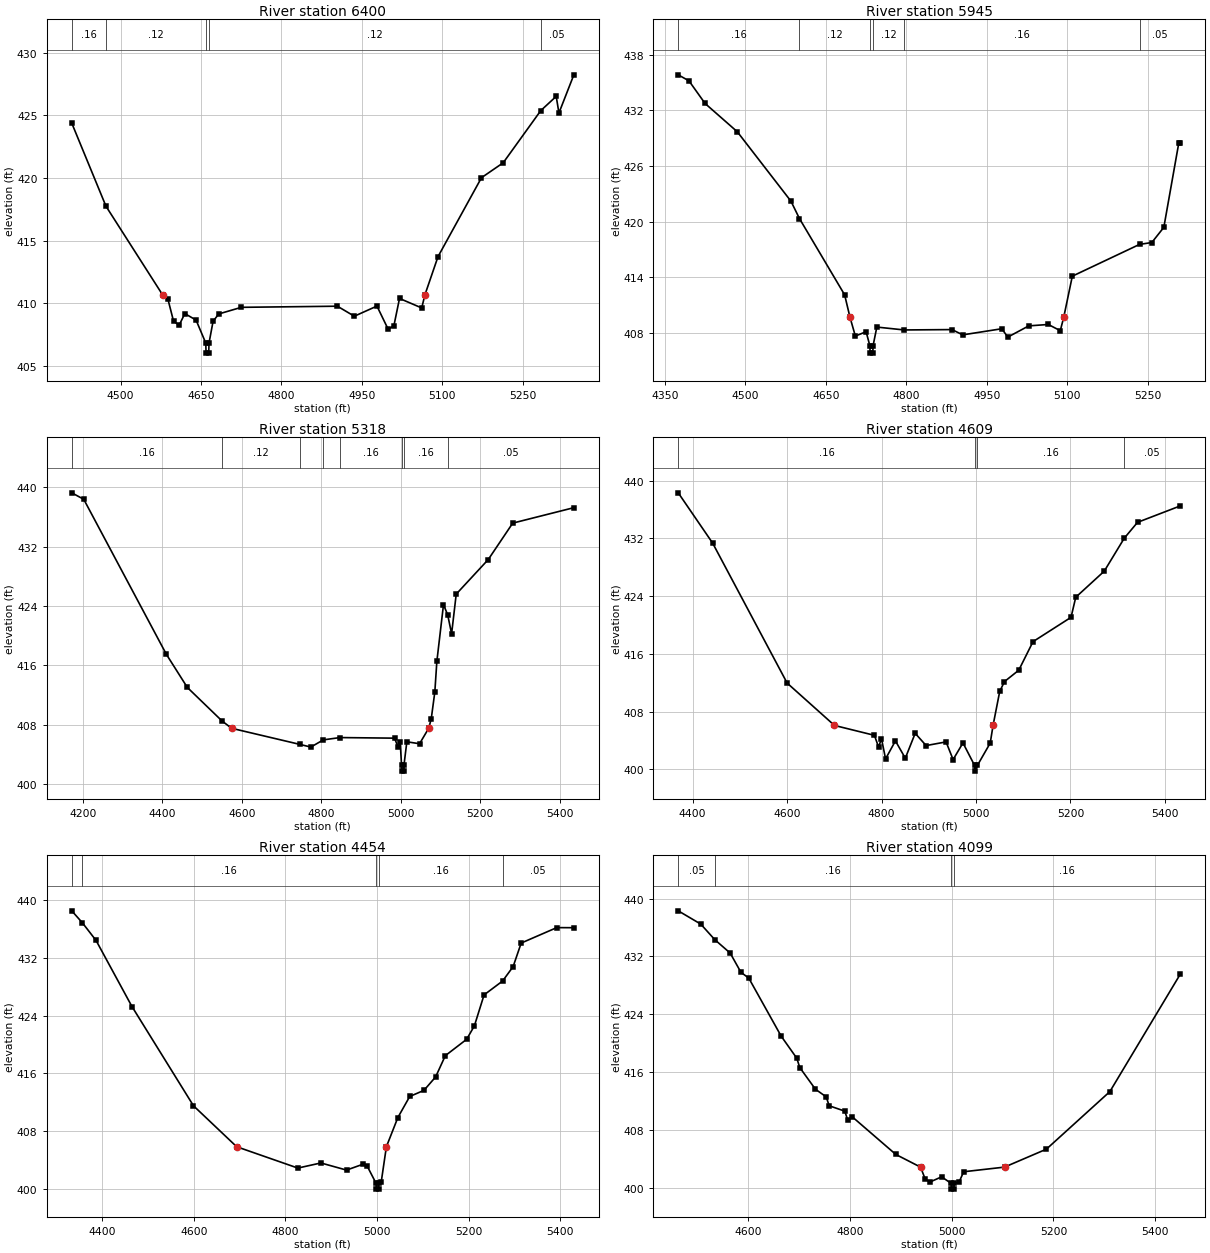
Type RM Length L Ch R = 1,6400,455,455,455
BEGIN DESCRIPTION:
DOUBLE BRANCH 10.0
END DESCRIPTION:
XS GIS Cut Line= 3
      2848724.99      7033574.96      2848925.00      7034175.00
      2848974.99      7034474.96
#Sta/Elev= 30
  4408.9  424.38  4472.7  417.74  4578.3  410.66  4588.1  410.34  4598.7  408.56
  4609.2  408.23  4619.8  409.16  4640.8  408.64  4658.9  406.80  4659.4  406.00
  4664.4  406.00  4664.9  406.80  4672.5  408.54  4683.0  409.13  4725.2  409.66
  4904.4  409.75  4936.0  408.95  4978.2  409.76  4999.2  407.90  5009.8  408.19
  5020.3  410.37  5061.7  409.61  5067.7  410.66  5092.1  413.71  5173.2  420.02
  5213.7  421.21  5283.8  425.38  5312.6  426.52  5317.7  425.19  5345.5  428.24
#Mann=5,-1,0
  4408.9    0.16       0  4472.7    0.12       0  4658.9    0.07       0
  4664.9    0.12       0  5283.8    0.05       0
Bank Sta=4578.3,5067.7
Exp/Cntr=0.3,0.1

Type RM Length L Ch R = 1,5945,627,627,627
BEGIN DESCRIPTION:
DOUBLE BRANCH 9.0
END DESCRIPTION:
XS GIS Cut Line= 3
      2848675.00      7033424.99      2848675.00      7034025.00
      2848525.01      7034324.98
#Sta/Elev= 30
  4375.2  435.83  4395.2  435.18  4425.2  432.74  4485.2  429.69  4585.2  422.20
  4601.0  420.33  4685.2  412.10  4695.2  409.67  4705.2  407.65  4725.2  408.12
  4732.2  406.61  4732.7  405.81  4737.7  405.81  4738.2  406.61  4745.2  408.62
  4796.2  408.31  4885.2  408.35  4905.2  407.78  4978.0  408.44  4989.2  407.54
  5028.3  408.75  5064.7  408.90  5087.0  408.23  5093.4  409.68  5109.4  414.11
  5234.7  417.54  5257.5  417.74  5279.9  419.38  5307.8  428.49  5310.6  428.49
#Mann=6,-1,0
  4375.2    0.16       0  4601.0    0.12       0  4732.2    0.07       0
  4738.2    0.12       0  4796.2    0.16       0  5234.7    0.05       0
Bank Sta=4695.2,5093.4
Exp/Cntr=0.3,0.1

Type RM Length L Ch R = 1,5318,709,709,709
BEGIN DESCRIPTION:
DOUBLE BRANCH 8.0
END DESCRIPTION:
XS GIS Cut Line= 3
      2848275.00      7033224.98      2848225.00      7034025.00
      2848124.99      7034475.04
#Sta/Elev= 30
  4172.7  439.24  4202.8  438.37  4410.7  417.48  4463.3  413.03  4550.5  408.52
  4574.6  407.53  4746.3  405.36  4773.9  405.00  4805.3  405.97  4847.4  406.28
  4984.5  406.20  4993.5  404.95  4998.6  405.70  5002.0  402.56  5002.5  401.76
  5007.6  401.76  5008.1  402.56  5015.3  405.71  5047.3  405.45  5070.3  407.53
  5076.7  408.81  5085.7  412.42  5090.8  416.54  5107.5  424.18  5118.0  422.81
  5127.9  420.26  5139.5  425.60  5220.1  430.26  5281.6  435.16  5435.3  437.24
#Mann=8,-1,0
  4172.7    0.16       0  4550.5    0.12       0  4746.3    0.16       0
  4805.3    0.12       0  4847.4    0.16       0  5002.0    0.07       0
  5008.1    0.16       0  5118.0    0.05       0
Bank Sta=4574.6,5070.3
Exp/Cntr=0.3,0.1

Type RM Length L Ch R = 1,4609,155,155,155
BEGIN DESCRIPTION:
DOUBLE BRANCH 7.0
END DESCRIPTION:
XS GIS Cut Line= 3
      2848224.98      7033225.02      2847875.00      7033725.00
      2847825.00      7034175.03
#Sta/Elev= 30
  4369.5  438.30  4442.3  431.34  4600.1  411.94  4700.3  406.07  4784.9  404.70
  4793.7  403.07  4799.8  404.25  4808.5  401.44  4829.4  403.93  4850.3  401.53
  4871.2  404.98  4894.4  403.28  4936.6  403.79  4951.5  401.34  4972.4  403.65
  4996.9  400.54  4997.4  399.74  5003.0  400.54  5030.1  403.63  5036.1  406.07
  5050.2  410.78  5060.3  412.15  5090.5  413.72  5120.7  417.68  5201.2  421.05
  5211.2  423.83  5271.6  427.45  5313.9  432.01  5342.0  434.21  5432.6  436.49
#Mann=4,-1,0
  4369.5    0.16       0  4996.9    0.07       0  5003.0    0.16       0
  5313.9    0.05       0
Bank Sta=4700.3,5036.1
Exp/Cntr=0.3,0.1

Type RM Length L Ch R = 1,4454,355,355,355
BEGIN DESCRIPTION:
Mapping XS 5ee74917
END DESCRIPTION:
XS GIS Cut Line= 3
      2848163.62      7033139.14      2847761.80      7033641.41
      2847612.75      7034070.33
#Sta/Elev= 30
  4332.9  438.52  4356.2  436.85  4386.0  434.41  4464.4  425.25  4598.9  411.48
  4693.3  405.80  4827.0  402.84  4877.4  403.55  4933.4  402.56  4968.7  403.36
  4978.9  403.07  4998.0  400.72  4998.5  399.92  5003.6  399.92  5004.1  400.72
  5009.2  400.90  5020.5  405.80  5045.6  409.85  5071.5  412.77  5102.6  413.62
  5128.1  415.48  5149.3  418.43  5195.9  420.70  5212.8  422.56  5234.0  426.86
  5274.4  428.78  5297.5  430.78  5315.1  434.05  5392.8  436.19  5430.2  436.18
#Mann=5,-1,0
  4332.9    0.05       0  4356.2    0.16       0  4998.0    0.07       0
  5004.1    0.16       0  5274.4    0.05       0
Bank Sta=4693.3,5020.5
Exp/Cntr=0.3,0.1

Type RM Length L Ch R = 1,4099,711,711,711
BEGIN DESCRIPTION:
DOUBLE BRANCH 6.0
END DESCRIPTION:
XS GIS Cut Line= 3
      2848125.00      7033075.00      2847725.00      7033325.00
      2847474.99      7033775.01
#Sta/Elev= 30
  4462.8  438.30  4507.0  436.47  4534.6  434.32  4564.8  432.47  4586.0  429.81
  4601.4  429.01  4665.0  421.00  4695.7  417.95  4701.6  416.66  4732.3  413.67
  4753.5  412.61  4759.4  411.38  4790.0  410.64  4795.9  409.39  4804.8  409.85
  4890.3  404.66  4938.9  402.91  4948.2  401.23  4957.4  400.85  4980.3  401.57
  4998.9  400.67  4999.4  399.87  5004.5  399.87  5005.0  400.67  5014.6  400.85
  5023.7  402.27  5103.9  402.91  5186.2  405.39  5310.9  413.34  5449.3  429.56
#Mann=4,-1,0
  4462.8    0.05       0  4534.6    0.16       0  4998.9    0.07       0
  5005.0    0.16       0
Bank Sta=4938.9,5103.9
Exp/Cntr=0.3,0.1

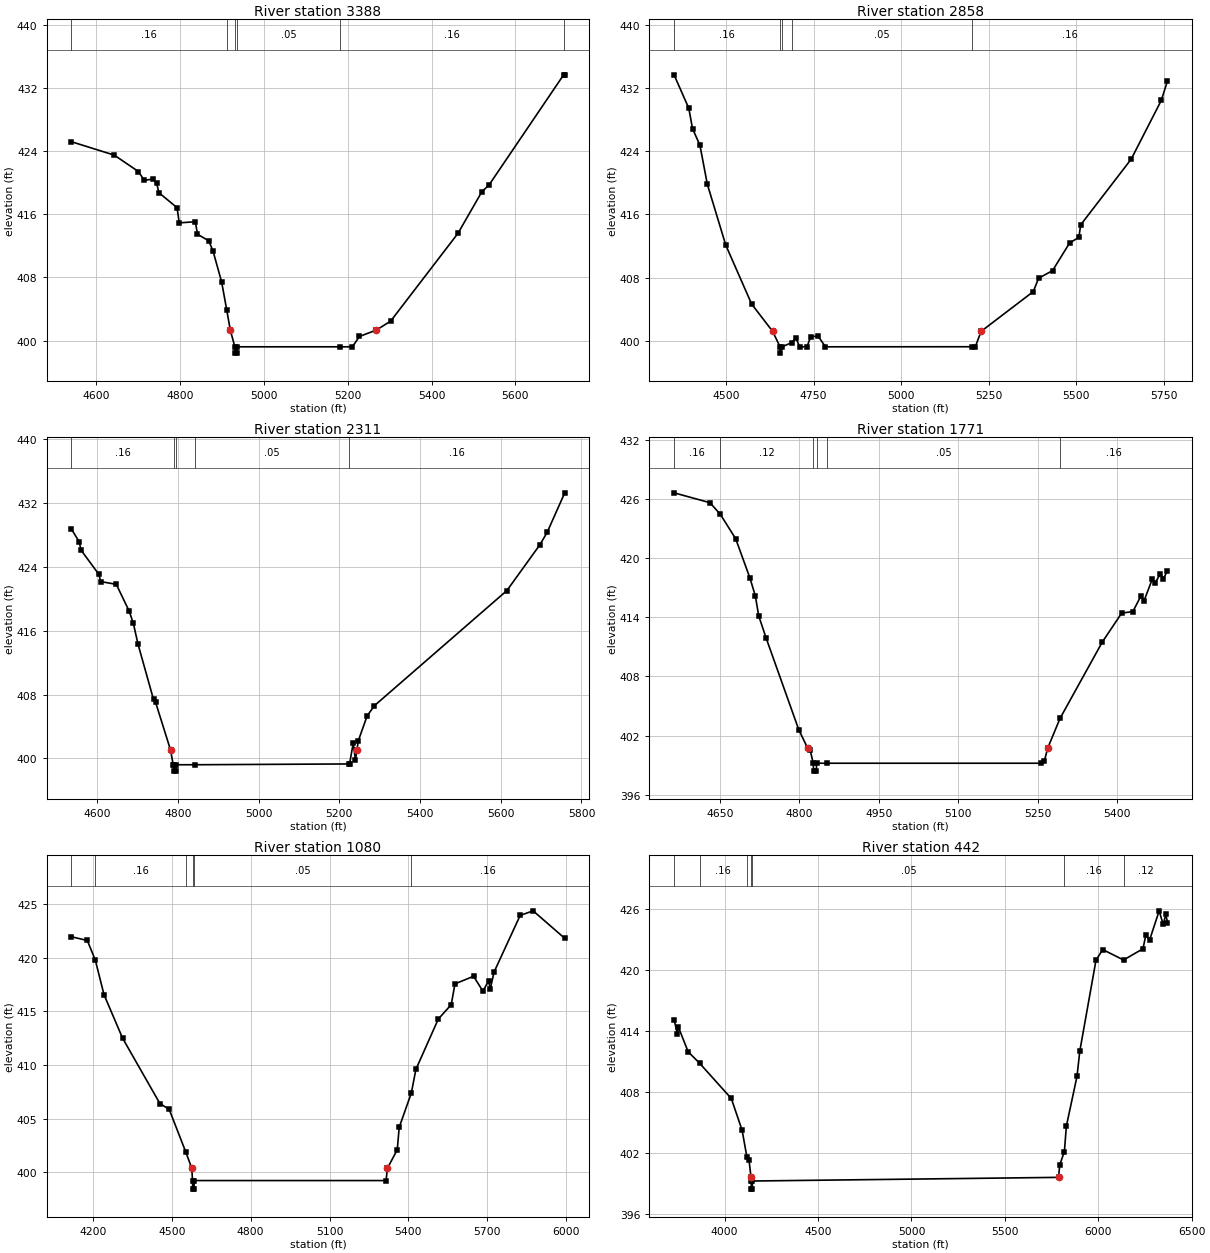
Type RM Length L Ch R = 1,3388,530,530,530
BEGIN DESCRIPTION:
DOUBLE BRANCH 5.0
END DESCRIPTION:
XS GIS Cut Line= 3
      2847824.97      7032925.01      2847375.00      7033025.00
      2847075.02      7033674.97
#Sta/Elev= 30
  4540.9  425.19  4643.3  423.49  4700.9  421.41  4715.0  420.28  4735.5  420.47
  4744.5  419.93  4749.6  418.74  4793.1  416.83  4798.2  414.91  4836.7  415.05
  4841.8  413.47  4868.7  412.63  4878.9  411.33  4899.4  407.42  4911.7  403.83
  4920.0  401.33  4930.9  399.21  4931.4  398.41  4936.5  398.41  4937.0  399.21
  5181.8  399.21  5211.1  399.21  5228.1  400.52  5268.3  401.33  5302.4  402.46
  5463.0  413.58  5519.9  418.84  5537.4  419.73  5714.8  433.64  5717.7  433.66
#Mann=6,-1,0
  4540.9    0.16       0  4911.7    0.05       0  4930.9   0.035       0
  4937.0    0.05       0  5181.8    0.16       0  5714.8    0.12       0
Bank Sta=4920,5268.3
Exp/Cntr=0.3,0.1

Type RM Length L Ch R = 1,2858,547,547,547
BEGIN DESCRIPTION:
DOUBLE BRANCH 4.0
END DESCRIPTION:
XS GIS Cut Line= 3
      2847075.00      7032275.00      2846875.00      7032875.00
      2846674.99      7033625.03
#Sta/Elev= 30
  4351.7  433.71  4393.9  429.45  4404.4  426.88  4425.5  424.79  4446.6  419.84
  4499.3  412.11  4573.1  404.64  4633.1  401.17  4654.3  399.21  4654.8  398.41
  4660.4  399.21  4687.6  399.75  4699.6  400.35  4710.1  399.21  4731.2  399.21
  4741.7  400.50  4762.8  400.57  4783.9  399.21  5201.1  399.22  5211.8  399.22
  5228.3  401.17  5377.4  406.22  5392.3  407.90  5432.4  408.88  5480.9  412.38
  5507.5  413.10  5512.6  414.68  5656.9  423.02  5742.9  430.48  5760.4  432.94
#Mann=5,-1,0
  4351.7    0.16       0  4654.3   0.033       0  4660.4    0.16       0
  4687.6    0.05       0  5201.1    0.16       0
Bank Sta=4633.1,5228.3
Exp/Cntr=0.3,0.1

Type RM Length L Ch R = 1,2311,540,540,540
BEGIN DESCRIPTION:
DOUBLE BRANCH 3.0
END DESCRIPTION:
XS GIS Cut Line= 3
      2846225.00      7032474.99      2846325.00      7032925.00
      2846625.01      7033625.03
#Sta/Elev= 30
  4536.0  428.77  4555.2  427.19  4560.3  426.10  4603.9  423.10  4609.0  422.17
  4647.4  421.83  4679.4  418.46  4689.7  416.93  4701.2  414.33  4739.6  407.40
  4744.7  407.05  4782.1  401.01  4788.3  399.22  4790.2  399.21  4790.7  398.41
  4796.0  398.41  4796.5  399.21  4841.7  399.21  5223.3  399.31  5225.5  399.34
  5234.5  401.92  5240.0  399.84  5243.5  401.01  5247.2  402.23  5269.0  405.34
  5287.1  406.62  5615.3  421.05  5696.9  426.78  5715.0  428.34  5758.6  433.30
#Mann=5,-1,0
  4536.0    0.16       0  4790.2   0.033       0  4796.5    0.16       0
  4841.7    0.05       0  5223.3    0.16       0
Bank Sta=4782.1,5243.5
Exp/Cntr=0.3,0.1

Type RM Length L Ch R = 1,1771,691,691,691
BEGIN DESCRIPTION:
DOUBLE BRANCH 2.0
END DESCRIPTION:
XS GIS Cut Line= 3
      2845725.01      7032675.05      2845825.00      7033125.00
      2846074.99      7033524.98
#Sta/Elev= 30
  4563.0  426.61  4630.8  425.61  4650.6  424.42  4679.5  421.95  4706.4  417.98
  4716.6  416.17  4723.0  414.14  4737.1  411.88  4798.6  402.62  4815.5  400.74
  4820.3  400.52  4826.1  399.21  4826.6  398.41  4831.9  398.41  4832.4  399.21
  4852.1  399.21  5256.8  399.21  5262.7  399.39  5269.2  400.74  5292.5  403.75
  5372.4  411.49  5409.0  414.42  5430.2  414.58  5445.5  416.16  5451.4  415.68
  5466.7  417.84  5472.6  417.49  5482.1  418.42  5488.0  417.90  5495.6  418.73
#Mann=6,-1,0
  4563.0    0.16       0  4650.6    0.12       0  4826.1   0.033       0
  4832.4    0.12       0  4852.1    0.05       0  5292.5    0.16       0
Bank Sta=4815.5,5269.2
Exp/Cntr=0.3,0.1

Type RM Length L Ch R = 1,1080,638,638,638
BEGIN DESCRIPTION:
Mapping XS 2bb6d359
END DESCRIPTION:
XS GIS Cut Line= 3
      2845663.11      7032467.95      2845107.52      7033106.87
      2845800.65      7033869.30
#Sta/Elev= 30
  4117.7  421.98  4178.4  421.63  4208.9  419.80  4242.0  416.57  4312.6  412.51
  4454.7  406.40  4489.8  405.87  4553.5  401.85  4575.9  400.36  4578.8  399.21
  4579.3  398.41  4584.6  398.41  4585.1  399.21  5315.0  399.21  5320.2  400.36
  5357.6  402.08  5365.0  404.18  5411.2  407.39  5428.5  409.59  5513.7  414.29
  5563.0  415.64  5577.2  417.58  5648.1  418.29  5683.3  416.90  5704.9  417.84
  5711.7  417.11  5725.8  418.68  5825.2  423.97  5874.5  424.40  5994.8  421.83
#Mann=6,-1,0
  4117.7    0.12       0  4208.9    0.16       0  4553.5    0.05       0
  4578.8   0.033       0  4585.1    0.05       0  5411.2    0.16       0
Bank Sta=4575.9,5320.2
Exp/Cntr=0.3,0.1

Type RM Length L Ch R = 1,442,0,0,0
BEGIN DESCRIPTION:
DOUBLE BRANCH 1.0
END DESCRIPTION:
XS GIS Cut Line= 3
      2845572.76      7032419.39      2844495.17      7033092.99
      2845628.35      7033863.81
#Sta/Elev= 30
  3729.2  415.14  3746.7  413.76  3752.6  414.38  3804.5  411.96  3865.7  410.83
  4035.6  407.35  4093.4  404.22  4118.7  401.62  4130.0  401.33  4141.2  399.57
  4142.1  399.21  4142.6  398.41  4148.0  398.41  4148.5  399.21  5787.6  399.57
  5793.4  400.78  5818.7  402.12  5829.3  404.63  5886.2  409.53  5901.1  412.02
  5987.9  420.99  6023.8  422.04  6135.4  421.01  6239.4  422.12  6254.3  423.44
  6275.3  423.01  6326.1  425.86  6347.1  424.53  6362.1  425.50  6370.5  424.70
#Mann=7,-1,0
  3729.2    0.12       0  3865.7    0.16       0  4118.7    0.05       0
  4142.1   0.033       0  4148.5    0.05       0  5818.7    0.16       0
  6135.4    0.12       0
Bank Sta=4141.2,5787.6
Exp/Cntr=0.3,0.1

Chan Stop Cuts=-1