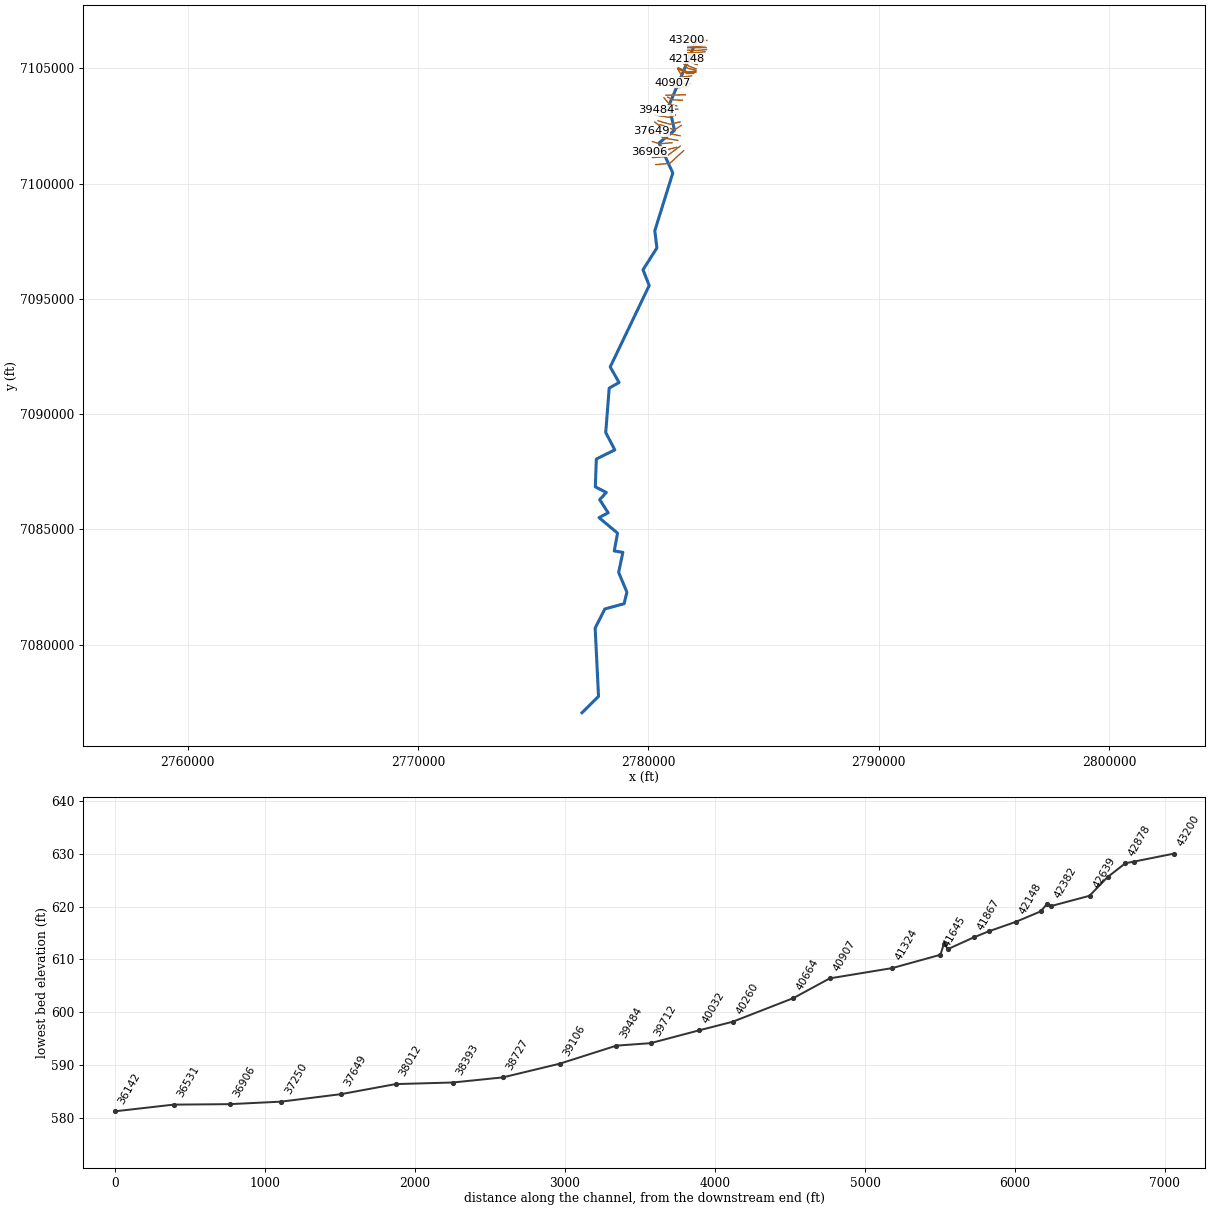
--- EAST FORK TURKEY CREEK.prj (project) ---

Proj Title=EAST FORK TURKEY CREEK Base Level Engineering
Current Plan=p01
Default Exp/Contr=0.3,0.1
English Units
Geom File=g01
Flow File=f01
Plan File=p01
Y Axis Title=Elevation
X Axis Title(PF)=Main Channel Distance
X Axis Title(XS)=Station
BEGIN DESCRIPTION:
EAST FORK TURKEY CREEK
END DESCRIPTION:
DSS Export Rating Curves= 0
DSS Export Rating Curve Sorted= 0
DSS Export Volume Flow Curves= 0
DXF OffsetX= 0
DXF OffsetY= 0
DXF ScaleX= 1
DXF ScaleY= 10

--- EAST FORK TURKEY CREEK.p01 (plan) ---

Plan Title=Multiple Run
Short Identifier=Multiple
Geom File=g01
Flow File=f01
Subcritical Flow
K Sum by GR= 0
Std Step Tol= 0.01
Critical Tol= 0.01
Num of Std Step Trials= 20
Max Error Tol= 0.3
Flow Tol Ratio= 0.001
Split Flow NTrial= 30
Split Flow Tol= 0.02
Split Flow Ratio= 0.02
Log Output Level= 0
Friction Slope Method= 1
Unsteady Friction Slope Method= 2
Unsteady Bridges Friction Slope Method= 1
Parabolic Critical Depth
Global Vel Dist=  1 , 1 , 1
Global Log Level= 0
CheckData=True
Encroach Param= -1, 0, 0, 0
BEGIN DESCRIPTION:
Multiple Run
END DESCRIPTION:

--- EAST FORK TURKEY CREEK.f01 (steady flow) ---

Flow Title=Multiple
Program Version=5.07
Number of Profiles= 7
Profile Names=10-year,25-year,50-year,1pct_min,100-year,1pct_plu,500-year
River Rch & RM=EAST FORK TURKEY,Reach-1         ,43200
     287     364     423     244     488     973     646
River Rch & RM=EAST FORK TURKEY,Reach-1         ,38727
     616     820     984     586    1169    2332    1644
River Rch & RM=EAST FORK TURKEY,Reach-1         ,35083
    1208    1665    2045    1242    2479    4946    3639
River Rch & RM=EAST FORK TURKEY,Reach-1         ,25823
    1400    1937    2384    1450    2894    5774    4260
River Rch & RM=EAST FORK TURKEY,Reach-1         ,20739
    1615    2247    2775    1693    3378    6741    5004
River Rch & RM=EAST FORK TURKEY,Reach-1         ,11863
    1835    2564    3175    1942    3874    7731    5765
River Rch & RM=EAST FORK TURKEY,Reach-1         ,7225
    1926    2695    3342    2045    4081    8143    6084
River Rch & RM=EAST FORK TURKEY,Reach-1         ,3680
    2019    2829    3510    2150    4289    8558    6401
River Rch & RM=EAST FORK TURKEY,Reach-1         ,811
    3730    5325    6690    4140    8260   16481   12586
River Rch & RM=EAST FORK TURKEY,Reach-1         ,3
    5010    7225    9140    5691   11355   22657   17515
Boundary for River Rch & Prof#=EAST FORK TURKEY,Reach-1         , 1
Up Type= 0
Dn Type= 1
Dn Known WS=499.61
Boundary for River Rch & Prof#=EAST FORK TURKEY,Reach-1         , 2
Up Type= 0
Dn Type= 1
Dn Known WS=500.26
Boundary for River Rch & Prof#=EAST FORK TURKEY,Reach-1         , 3
Up Type= 0
Dn Type= 1
Dn Known WS=500.76
Boundary for River Rch & Prof#=EAST FORK TURKEY,Reach-1         , 4
Up Type= 0
Dn Type= 1
Dn Known WS=499.82
Boundary for River Rch & Prof#=EAST FORK TURKEY,Reach-1         , 5
Up Type= 0
Dn Type= 1
Dn Known WS=501.3
Boundary for River Rch & Prof#=EAST FORK TURKEY,Reach-1         , 6
Up Type= 0
Dn Type= 1
Dn Known WS=503.62
Boundary for River Rch & Prof#=EAST FORK TURKEY,Reach-1         , 7
Up Type= 0
Dn Type= 1
Dn Known WS=502.62
DSS Import GetInterval= 0
DSS Import GetPeak= 0
DSS Import FillOption= 0

--- EAST FORK TURKEY CREEK.g01 (geometry) ---

Geom Title=Existing Conditions

River Reach=EAST FORK TURKEY,Reach-1
Reach XY= 30
      2782126.76      7106303.56      2780887.88      7103385.45
      2781132.12      7102311.96      2780460.11      7101759.72
      2781058.01      7100460.28      2780277.49      7097955.32
      2780367.29      7097207.29      2779765.59      7096260.71
      2780033.83      7095576.17      2778342.15      7092044.50
      2778725.99      7091369.14      2778297.97      7091125.12
      2778147.73      7089200.54      2778541.74      7088445.43
      2777739.16      7088049.38      2777696.85      7086840.62
      2778172.66      7086599.04      2777885.78      7086286.22
      2778254.12      7085716.80      2777857.41      7085506.28
      2778661.60      7084833.64      2778516.47      7084060.79
      2778890.52      7084000.29      2778707.94      7083130.83
      2779065.62      7082276.24      2778945.46      7081771.33
      2778108.84      7081543.48      2777689.39      7080713.83
      2777835.09      7077751.04      2777115.59      7077040.71

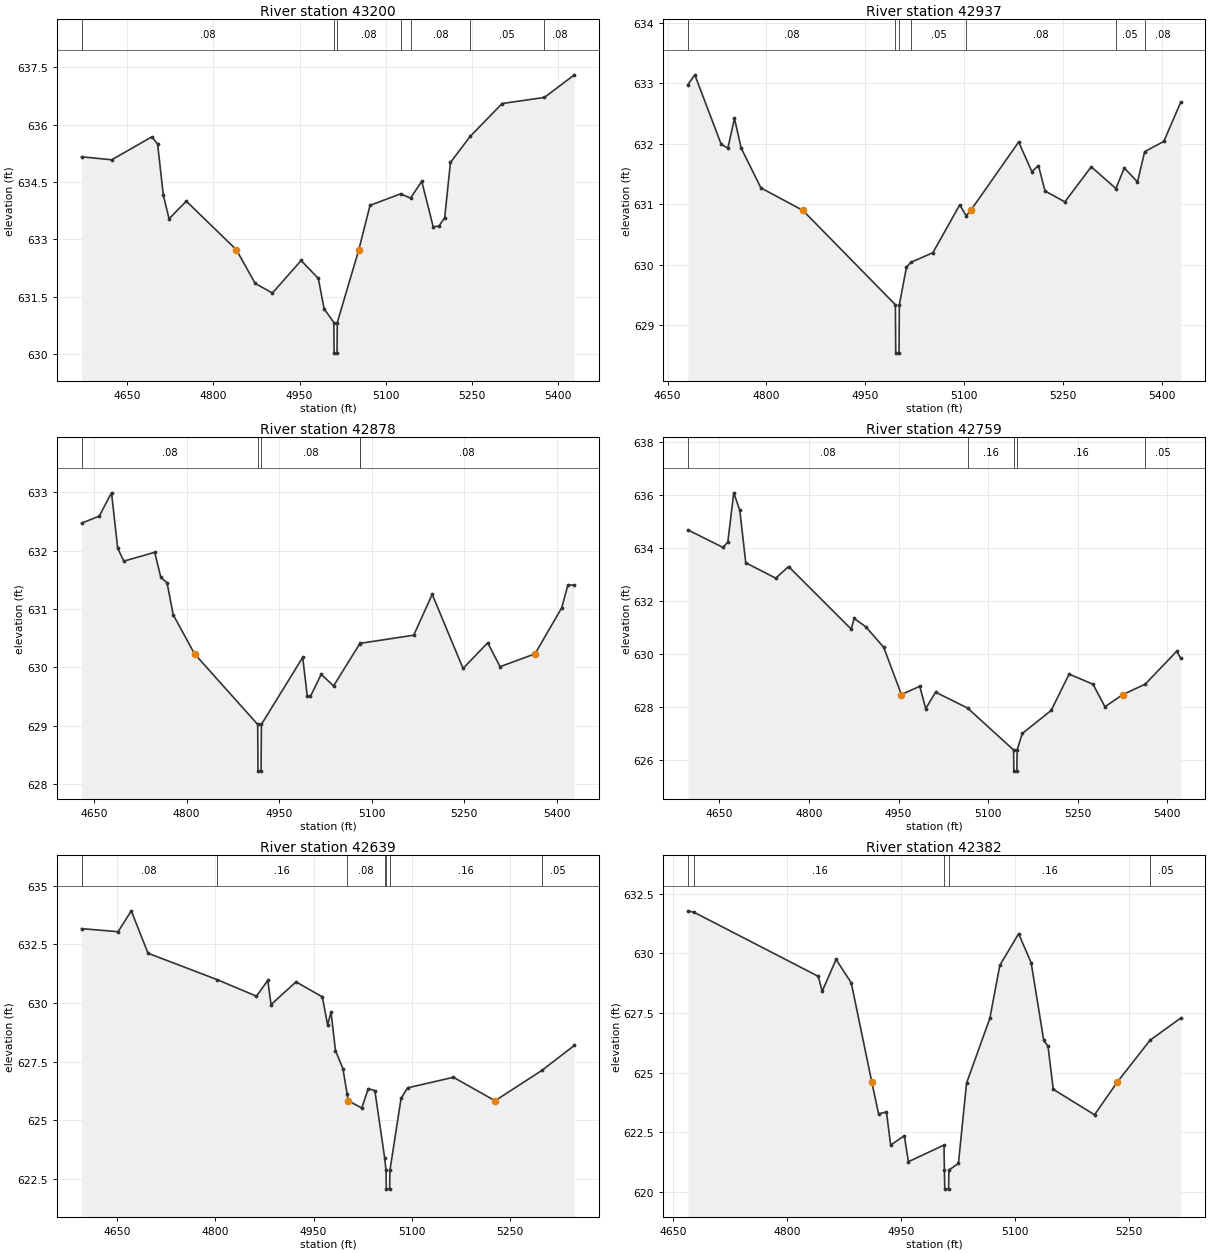
Type RM Length L Ch R = 1,43200,263,263,263
BEGIN DESCRIPTION:
Mapping XS c571e580
END DESCRIPTION:
XS GIS Cut Line= 3
      2782537.51      7106211.05      2782087.54      7106213.59
      2781679.14      7106223.74
#Sta/Elev= 30
  4570.3  635.16  4622.8  635.08  4692.8  635.68  4702.8  635.49  4712.8  634.15
  4722.8  633.54  4752.8  634.00  4840.0  632.73  4872.8  631.85  4902.8  631.60
  4952.8  632.45  4982.8  631.98  4992.8  631.19  5009.8  630.83  5010.3  630.03
  5015.3  630.03  5015.8  630.83  5053.3  632.73  5072.8  633.89  5126.0  634.19
  5143.5  634.08  5162.9  634.52  5182.9  633.33  5192.9  633.35  5202.9  633.57
  5212.9  635.01  5247.2  635.69  5302.9  636.55  5376.7  636.71  5428.8  637.30
#Mann=7,-1,0
  4570.3    0.08       0  5009.8    0.07       0  5015.8    0.08       0
  5126.0    0.05       0  5143.5    0.08       0  5247.2    0.05       0
  5376.7    0.08       0
Bank Sta=4840,5053.3
Exp/Cntr=0.3,0.1

Type RM Length L Ch R = 1,42937,59,59,59
BEGIN DESCRIPTION:
Mapping XS 6df0c0fc
END DESCRIPTION:
XS GIS Cut Line= 3
      2782455.34      7105982.91      2782137.52      7105954.94
      2781709.36      7105979.28
#Sta/Elev= 30
  4680.9  632.98  4691.3  633.14  4731.4  631.99  4741.5  631.93  4751.5  632.42
  4761.6  631.93  4791.7  631.27  4855.2  630.90  4995.7  629.34  4996.2  628.54
  5001.2  628.54  5001.7  629.34  5012.5  629.96  5019.1  630.04  5052.6  630.20
  5093.3  630.99  5103.2  630.81  5110.1  630.90  5182.8  632.03  5202.8  631.54
  5212.8  631.64  5222.8  631.22  5252.9  631.04  5292.9  631.62  5330.4  631.26
  5343.0  631.60  5363.1  631.37  5374.0  631.87  5403.1  632.04  5428.8  632.69
#Mann=7,-1,0
  4680.9    0.08       0  4995.7    0.07       0  5001.7    0.08       0
  5019.1    0.05       0  5103.2    0.08       0  5330.4    0.05       0
  5374.0    0.08       0
Bank Sta=4855.2,5110.1
Exp/Cntr=0.3,0.1

Type RM Length L Ch R = 1,42878,119,119,119
BEGIN DESCRIPTION:
Mapping XS c5af149a
END DESCRIPTION:
XS GIS Cut Line= 3
      2782503.60      7105899.01      2782134.98      7105896.47
      2781704.51      7105895.20
#Sta/Elev= 30
  4629.8  632.47  4658.4  632.59  4678.4  632.99  4688.4  632.04  4698.4  631.82
  4748.4  631.97  4758.4  631.54  4768.4  631.45  4778.4  630.90  4813.0  630.23
  4915.4  629.02  4915.9  628.22  4920.9  628.22  4921.4  629.02  4988.4  630.17
  4995.9  629.50  5000.9  629.50  5018.4  629.88  5038.4  629.68  5080.7  630.40
  5081.3  630.41  5168.4  630.55  5198.4  631.25  5248.4  629.98  5288.4  630.42
  5308.4  630.01  5365.1  630.23  5408.4  631.02  5418.4  631.41  5428.9  631.41
#Mann=5,-1,0
  4629.8    0.08       0  4915.4    0.07       0  4921.4    0.08       0
  5080.7    0.05       0  5081.3    0.08       0
Bank Sta=4813,5365.1
Exp/Cntr=0.3,0.1

Type RM Length L Ch R = 1,42759,120,120,120
BEGIN DESCRIPTION:
Mapping XS 12633d8f
END DESCRIPTION:
XS GIS Cut Line= 3
      2782521.41      7105815.11      2782107.01      7105776.97
      2781698.05      7105785.81
#Sta/Elev= 30
  4597.3  634.69  4656.0  634.03  4664.0  634.23  4674.0  636.09  4684.1  635.43
  4694.1  633.45  4744.3  632.87  4765.8  633.31  4870.6  630.95  4875.6  631.35
  4895.0  631.04  4925.1  630.26  4954.7  628.48  4985.4  628.79  4995.4  627.95
  5011.9  628.57  5065.5  627.97  5142.5  626.39  5143.0  625.59  5148.0  625.59
  5148.5  626.39  5157.1  627.01  5205.5  627.88  5235.5  629.25  5275.5  628.87
  5295.5  628.02  5325.6  628.48  5362.9  628.87  5415.6  630.11  5422.5  629.85
#Mann=5,-1,0
  4597.3    0.08       0  5065.5    0.16       0  5142.5    0.07       0
  5148.5    0.16       0  5362.9    0.05       0
Bank Sta=4954.7,5325.6
Exp/Cntr=0.3,0.1

Type RM Length L Ch R = 1,42639,257,257,257
BEGIN DESCRIPTION:
Mapping XS eb665ad4
END DESCRIPTION:
XS GIS Cut Line= 3
      2782460.43      7105721.04      2782063.79      7105677.81
      2781710.42      7105672.73
#Sta/Elev= 30
  4595.7  633.17  4651.5  633.04  4671.6  633.93  4697.2  632.12  4802.3  631.00
  4862.7  630.29  4880.0  630.96  4885.0  629.93  4923.1  630.90  4963.3  630.26
  4971.4  629.06  4976.5  629.62  4983.4  627.97  4994.7  627.20  5001.1  626.13
  5002.9  625.83  5023.5  625.52  5033.5  626.35  5043.5  626.26  5058.5  623.39
  5060.5  622.86  5061.0  622.06  5066.0  622.06  5066.5  622.86  5083.5  625.93
  5093.5  626.38  5163.5  626.83  5227.0  625.83  5298.3  627.12  5348.1  628.19
#Mann=7,-1,0
  4595.7    0.08       0  4802.3    0.16       0  5001.1    0.08       0
  5058.5    0.16       0  5060.5    0.07       0  5066.5    0.16       0
  5298.3    0.05       0
Bank Sta=5002.9,5227
Exp/Cntr=0.3,0.1

Type RM Length L Ch R = 1,42382,29,29,29
BEGIN DESCRIPTION:
Mapping XS a7c1d58b
END DESCRIPTION:
XS GIS Cut Line= 5
      2782269.80      7105438.96      2782018.09      7105425.94
      2781933.45      7105462.83      2781913.92      7105553.98
      2781725.08      7105649.48
#Sta/Elev= 30
  4669.6  631.79  4678.2  631.72  4841.3  629.04  4846.4  628.41  4864.7  629.75
  4884.7  628.77  4911.8  624.60  4920.7  623.27  4931.1  623.35  4936.6  621.96
  4954.6  622.35  4960.0  621.26  5006.9  621.96  5007.4  620.91  5007.9  620.11
  5012.9  620.11  5013.4  620.91  5025.9  621.19  5036.6  624.56  5067.3  627.28
  5080.4  629.50  5105.2  630.83  5121.7  629.61  5138.3  626.35  5143.9  626.11
  5150.8  624.30  5205.2  623.23  5235.1  624.60  5278.3  626.36  5318.8  627.29
#Mann=5,-1,0
  4669.6    0.05       0  4678.2    0.16       0  5007.4    0.07       0
  5013.4    0.16       0  5278.3    0.05       0
Bank Sta=4911.8,5235.1
Exp/Cntr=0.3,0.1

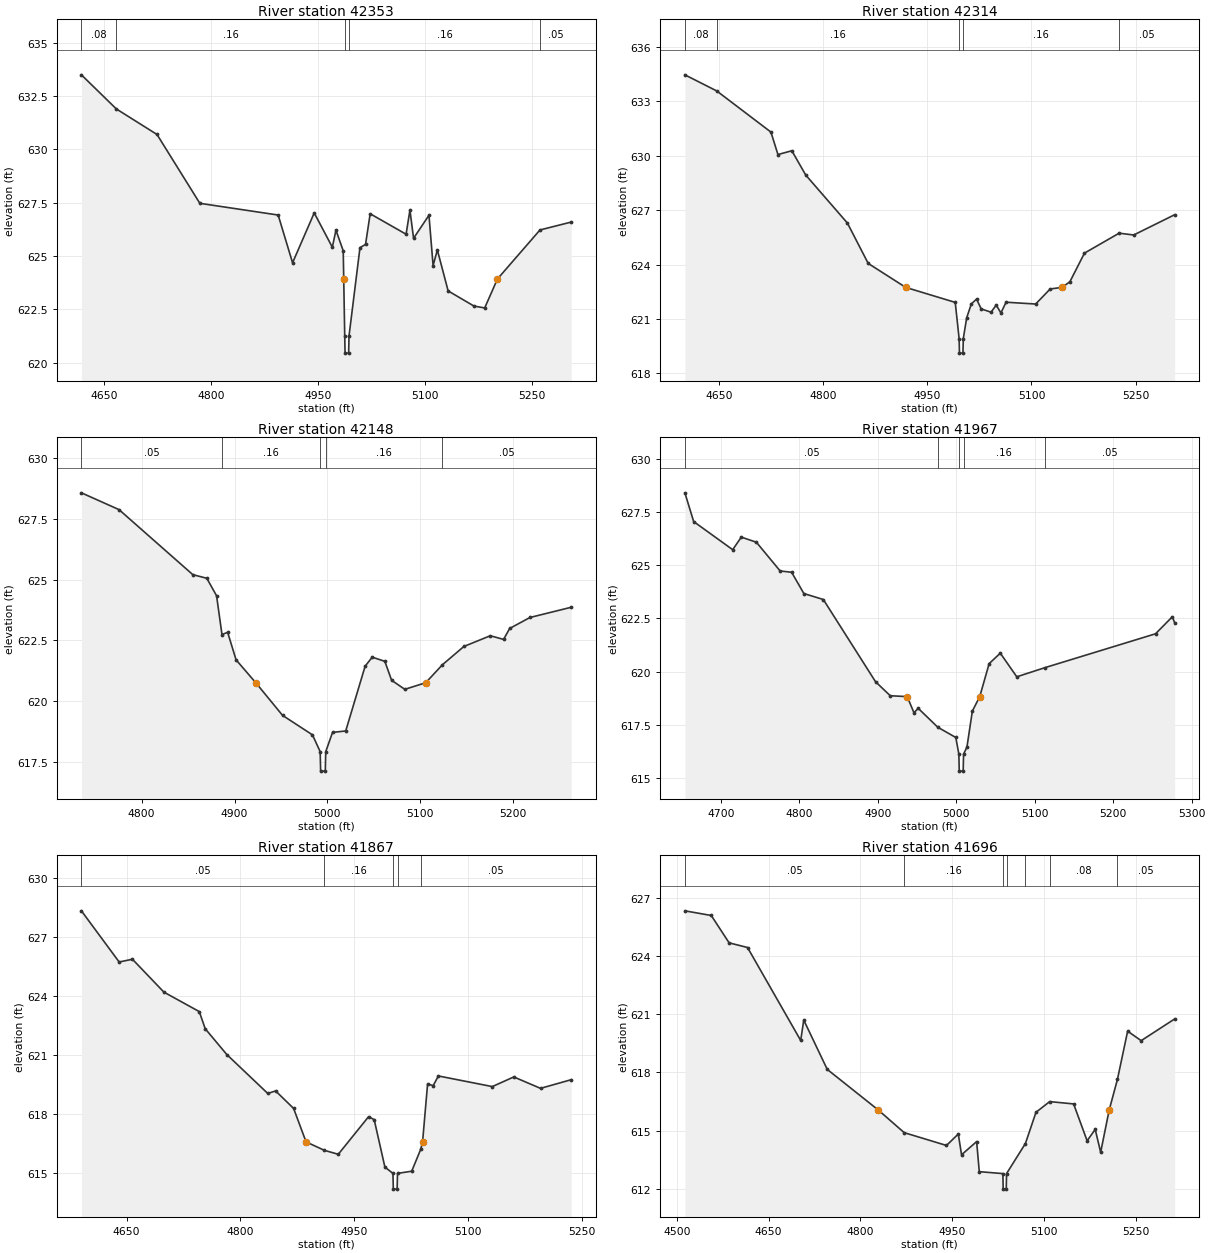
Type RM Length L Ch R = 1,42353,39,39,39
BEGIN DESCRIPTION:
Mapping XS d2fc5b73
END DESCRIPTION:
XS GIS Cut Line= 6
      2782311.07      7105399.90      2782009.41      7105410.75
      2781939.96      7105423.77      2781909.58      7105460.66
      2781894.39      7105523.60      2781725.11      7105634.28
#Sta/Elev= 30
  4617.7  633.50  4666.7  631.90  4723.8  630.70  4783.9  627.47  4893.8  626.92
  4914.0  624.68  4944.4  627.02  4969.8  625.41  4974.9  626.21  4985.1  625.24
  4985.8  623.92  4987.2  621.24  4987.7  620.44  4992.7  620.44  4993.2  621.24
  5008.6  625.39  5016.4  625.54  5022.9  626.98  5073.3  626.02  5078.7  627.15
  5083.8  625.83  5105.4  626.91  5111.2  624.55  5117.2  625.28  5132.3  623.36
  5168.5  622.65  5183.6  622.56  5201.5  623.92  5261.2  626.22  5305.0  626.59
#Mann=5,-1,0
  4617.7    0.08       0  4666.7    0.16       0  4987.2    0.07       0
  4993.2    0.16       0  5261.2    0.05       0
Bank Sta=4985.8,5201.5
Exp/Cntr=0.3,0.1

Type RM Length L Ch R = 1,42314,166,166,166
BEGIN DESCRIPTION:
Mapping XS 9f34812d
END DESCRIPTION:
XS GIS Cut Line= 4
      2782308.85      7105358.67      2781966.00      7105371.69
      2781913.92      7105397.73      2781708.91      7105622.16
#Sta/Elev= 30
  4600.9  634.47  4646.8  633.58  4724.8  631.31  4734.9  630.07  4754.9  630.28
  4774.9  628.94  4834.9  626.29  4864.9  624.06  4918.8  622.74  4990.2  621.91
  4995.8  619.91  4996.3  619.11  5001.3  619.11  5001.8  619.91  5006.7  621.06
  5013.4  621.83  5020.9  622.09  5027.6  621.55  5041.8  621.37  5049.2  621.76
  5056.0  621.33  5063.4  621.92  5106.0  621.82  5126.9  622.65  5144.2  622.74
  5155.3  623.05  5176.3  624.63  5226.2  625.73  5247.2  625.63  5306.2  626.75
#Mann=5,-1,0
  4600.9    0.08       0  4646.8    0.16       0  4995.8    0.07       0
  5001.8    0.16       0  5226.2    0.05       0
Bank Sta=4918.8,5144.2
Exp/Cntr=0.3,0.1

Type RM Length L Ch R = 1,42148,181,181,181
BEGIN DESCRIPTION:
Mapping XS 240eaa1b
END DESCRIPTION:
XS GIS Cut Line= 3
      2782113.61      7105163.34      2781861.84      7105243.65
      2781664.36      7105417.25
#Sta/Elev= 30
  4735.2  628.56  4775.7  627.87  4855.1  625.20  4870.2  625.05  4880.7  624.33
  4886.5  622.74  4892.6  622.83  4901.7  621.70  4922.9  620.76  4951.7  619.42
  4983.9  618.62  4992.2  617.93  4992.7  617.13  4997.7  617.13  4998.2  617.93
  5005.5  618.72  5019.7  618.78  5040.6  621.44  5048.2  621.81  5061.8  621.64
  5069.1  620.86  5083.3  620.49  5105.8  620.76  5123.8  621.50  5146.9  622.25
  5175.3  622.69  5189.6  622.54  5196.2  622.99  5218.0  623.44  5262.4  623.86
#Mann=5,-1,0
  4735.2    0.05       0  4886.5    0.16       0  4992.2    0.07       0
  4998.2    0.16       0  5123.8    0.05       0
Bank Sta=4922.9,5105.8
Exp/Cntr=0.3,0.1

Type RM Length L Ch R = 1,41967,100,100,100
BEGIN DESCRIPTION:
Mapping XS d5c2b90c
END DESCRIPTION:
XS GIS Cut Line= 3
      2782072.30      7104976.74      2781755.50      7105096.08
      2781559.04      7105303.33
#Sta/Elev= 30
  4654.3  628.40  4665.5  627.05  4715.2  625.73  4726.2  626.32  4745.4  626.08
  4775.7  624.73  4790.3  624.67  4805.9  623.67  4830.7  623.39  4897.2  619.53
  4916.0  618.87  4937.6  618.83  4946.2  618.07  4951.6  618.28  4976.6  617.39
  4999.5  616.91  5003.4  616.13  5003.9  615.33  5008.9  615.33  5009.4  616.13
  5013.7  616.46  5020.6  618.15  5030.0  618.83  5042.0  620.38  5056.2  620.87
  5077.2  619.76  5113.1  620.19  5254.0  621.78  5275.4  622.58  5278.4  622.30
#Mann=5,-1,0
  4654.3    0.05       0  4976.6    0.16       0  5003.4    0.07       0
  5009.4    0.16       0  5113.1    0.05       0
Bank Sta=4937.6,5030
Exp/Cntr=0.3,0.1

Type RM Length L Ch R = 1,41867,171,171,171
BEGIN DESCRIPTION:
Mapping XS 368bc17a
END DESCRIPTION:
XS GIS Cut Line= 3
      2782063.24      7104913.35      2781705.59      7105001.90
      2781519.89      7105206.68
#Sta/Elev= 30
  4590.6  628.32  4640.3  625.72  4657.8  625.86  4699.2  624.19  4745.8  623.20
  4753.6  622.33  4782.0  621.02  4836.0  619.04  4846.3  619.17  4870.0  618.28
  4886.4  616.58  4910.6  616.15  4928.8  615.95  4968.7  617.86  4976.1  617.71
  4990.2  615.30  5000.8  614.98  5001.3  614.18  5006.3  614.18  5006.8  614.98
  5025.5  615.09  5037.3  616.20  5039.8  616.58  5046.4  619.52  5053.8  619.44
  5060.6  619.93  5131.6  619.39  5159.9  619.88  5195.1  619.30  5235.5  619.74
#Mann=5,-1,0
  4590.6    0.05       0  4910.6    0.16       0  5000.8    0.07       0
  5006.8    0.16       0  5037.3    0.05       0
Bank Sta=4886.4,5039.8
Exp/Cntr=0.3,0.1

Type RM Length L Ch R = 1,41696,28,28,28
BEGIN DESCRIPTION:
Mapping XS 6f9dc328
END DESCRIPTION:
XS GIS Cut Line= 4
      2782057.17      7104872.56      2781694.74      7104848.68
      2781581.89      7104892.09      2781295.44      7105026.63
#Sta/Elev= 30
  4513.1  626.32  4556.2  626.08  4585.4  624.67  4615.5  624.43  4702.4  619.64
  4707.4  620.69  4745.8  618.15  4829.1  616.06  4871.6  614.89  4940.7  614.23
  4960.0  614.82  4965.3  613.75  4990.0  614.43  4994.3  612.88  5032.9  612.78
  5033.4  611.98  5038.4  611.98  5038.9  612.78  5069.7  614.33  5087.0  615.94
  5109.4  616.49  5148.5  616.37  5170.6  614.47  5183.8  615.06  5192.7  613.88
  5206.6  616.05  5220.1  617.63  5236.8  620.12  5258.9  619.63  5313.7  620.75
#Mann=7,-1,0
  4513.1    0.05       0  4871.6    0.16       0  5032.9    0.07       0
  5038.9    0.16       0  5069.7    0.05       0  5109.4    0.08       0
  5220.1    0.05       0
Bank Sta=4829.1,5206.6
Exp/Cntr=0.3,0.1

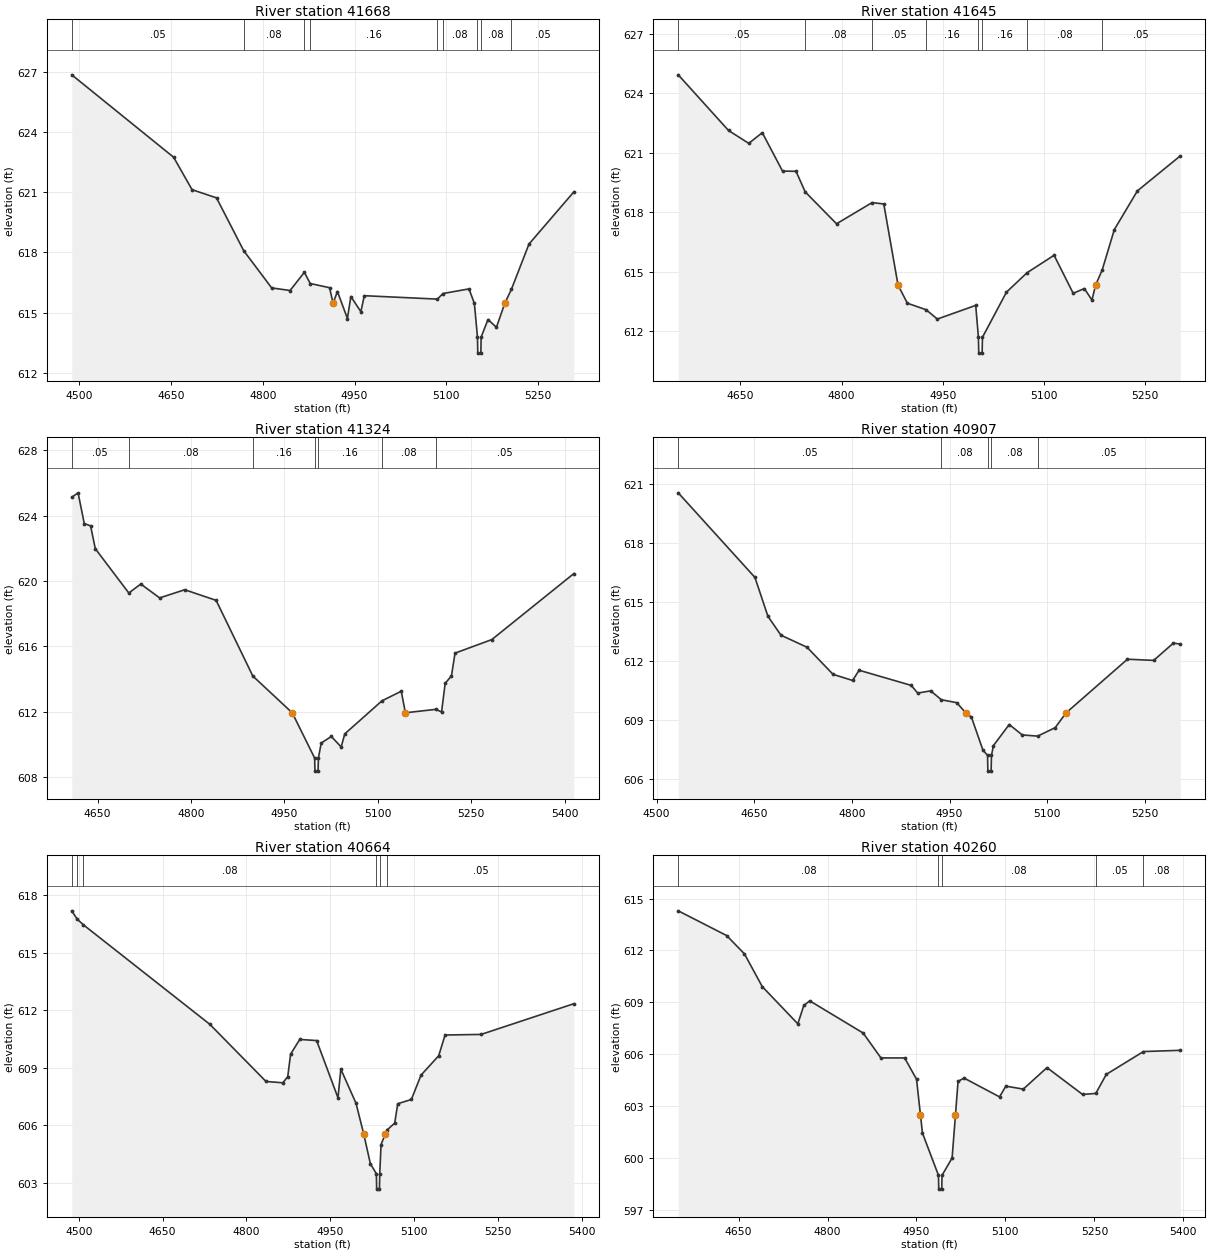
Type RM Length L Ch R = 1,41668,23,23,23
BEGIN DESCRIPTION:
Mapping XS 30cb784f
END DESCRIPTION:
XS GIS Cut Line= 4
      2782061.30      7104830.58      2781679.74      7104807.45
      2781494.72      7104905.74      2781289.22      7105007.53
#Sta/Elev= 30
  4487.6  626.88  4654.2  622.76  4684.3  621.14  4724.3  620.73  4768.8  618.09
  4814.5  616.23  4844.6  616.10  4868.0  617.01  4877.5  616.45  4909.2  616.24
  4914.9  615.47  4922.1  616.05  4938.4  614.70  4944.0  615.80  4960.4  615.04
  4966.0  615.84  5085.6  615.67  5094.7  615.95  5137.2  616.18  5146.0  615.46
  5151.1  613.77  5151.6  612.97  5156.6  612.97  5157.1  613.77  5168.3  614.65
  5182.1  614.26  5195.9  615.47  5206.6  616.16  5235.3  618.42  5308.7  621.03
#Mann=9,-1,0
  4487.6    0.05       0  4768.8    0.08       0  4868.0    0.05       0
  4877.5    0.16       0  5085.6    0.05       0  5094.7    0.08       0
  5151.1    0.07       0  5157.1    0.08       0  5206.6    0.05       0
Bank Sta=4914.9,5195.9
Exp/Cntr=0.3,0.1

Type RM Length L Ch R = 1,41645,321,321,321
BEGIN DESCRIPTION:
Mapping XS c6e1ef58
END DESCRIPTION:
XS GIS Cut Line= 5
      2781969.50      7104779.67      2781658.71      7104777.94
      2781540.66      7104857.80      2781453.85      7104892.52
      2781278.36      7104981.99
#Sta/Elev= 30
  4558.0  624.94  4632.5  622.13  4662.5  621.48  4682.5  622.02  4712.5  620.08
  4732.5  620.07  4746.1  619.03  4792.5  617.42  4845.2  618.49  4862.5  618.42
  4883.6  614.33  4897.4  613.41  4925.3  613.08  4941.8  612.61  4998.7  613.30
  5002.7  611.69  5003.2  610.89  5008.2  610.89  5008.7  611.69  5044.3  613.97
  5074.8  614.95  5114.8  615.83  5143.1  613.91  5159.6  614.15  5170.9  613.57
  5176.4  614.33  5186.0  615.08  5204.1  617.13  5238.2  619.08  5301.8  620.85
#Mann=8,-1,0
  4558.0    0.05       0  4746.1    0.08       0  4845.2    0.05       0
  4925.3    0.16       0  5002.7    0.07       0  5008.7    0.16       0
  5074.8    0.08       0  5186.0    0.05       0
Bank Sta=4883.6,5176.4
Exp/Cntr=0.3,0.1

Type RM Length L Ch R = 1,41324,417,417,417
BEGIN DESCRIPTION:
EAST FORK TURKEY CREEK 70.0
END DESCRIPTION:
XS GIS Cut Line= 3
      2781874.97      7104675.00      2781475.00      7104625.00
      2781275.00      7104975.00
#Sta/Elev= 30
  4608.5  625.13  4618.6  625.40  4628.6  623.52  4638.7  623.38  4646.3  621.98
  4700.1  619.27  4719.3  619.82  4749.6  618.97  4789.9  619.47  4840.3  618.82
  4899.2  614.19  4962.5  611.94  4998.5  609.17  4999.0  608.37  5004.0  608.37
  5004.5  609.17  5009.1  610.09  5025.3  610.49  5041.1  609.85  5046.9  610.65
  5106.5  612.67  5137.6  613.26  5144.2  611.94  5193.0  612.15  5202.3  611.99
  5208.1  613.74  5218.2  614.20  5223.9  615.59  5283.0  616.42  5414.7  620.46
#Mann=7,-1,0
  4608.5    0.05       0  4700.1    0.08       0  4899.2    0.16       0
  4998.5    0.04       0  5004.5    0.16       0  5106.5    0.08       0
  5193.0    0.05       0
Bank Sta=4962.5,5144.2
Exp/Cntr=0.3,0.1

Type RM Length L Ch R = 1,40907,243,243,243
BEGIN DESCRIPTION:
EAST FORK TURKEY CREEK 69.0
END DESCRIPTION:
XS GIS Cut Line= 3
      2781822.73      7104333.49      2781375.00      7104325.00
      2781054.51      7104368.22
#Sta/Elev= 30
  4533.2  620.57  4651.0  616.27  4671.0  614.29  4691.0  613.33  4731.0  612.72
  4771.0  611.34  4801.0  611.03  4811.0  611.55  4891.0  610.78  4901.0  610.39
  4921.0  610.50  4937.4  610.05  4961.0  609.90  4974.9  609.38  4983.5  609.17
  5001.2  607.49  5008.3  607.22  5008.8  606.42  5013.8  606.42  5014.3  607.22
  5017.4  607.72  5041.6  608.79  5061.7  608.26  5085.3  608.20  5112.2  608.63
  5128.9  609.38  5223.2  612.11  5263.5  612.05  5293.8  612.93  5304.4  612.88
#Mann=5,-1,0
  4533.2    0.05       0  4937.4    0.08       0  5008.3    0.07       0
  5014.3    0.08       0  5085.3    0.05       0
Bank Sta=4974.9,5128.9
Exp/Cntr=0.3,0.1

Type RM Length L Ch R = 1,40664,404,404,404
BEGIN DESCRIPTION:
EAST FORK TURKEY CREEK 68.0
END DESCRIPTION:
XS GIS Cut Line= 3
      2781760.32      7104213.71      2781229.02      7104153.81
      2780890.51      7104286.61
#Sta/Elev= 30
  4487.6  617.18  4497.2  616.75  4508.0  616.46  4734.5  611.27  4835.1  608.29
  4865.3  608.22  4874.0  608.54  4879.1  609.71  4895.5  610.48  4925.7  610.42
  4963.9  607.44  4969.0  608.93  4996.1  607.16  5009.8  605.57  5021.8  604.01
  5032.6  603.48  5033.1  602.68  5038.1  602.68  5038.6  603.48  5041.0  605.00
  5048.7  605.57  5052.0  605.77  5065.4  606.12  5070.8  607.13  5095.2  607.35
  5112.5  608.62  5144.1  609.63  5155.5  610.71  5219.9  610.74  5385.9  612.34
#Mann=6,-1,0
  4487.6    0.08       0  4497.2    0.05       0  4508.0    0.08       0
  5032.6    0.07       0  5038.6    0.08       0  5052.0    0.05       0
Bank Sta=5009.8,5048.7
Exp/Cntr=0.3,0.1

Type RM Length L Ch R = 1,40260,228,228,228
BEGIN DESCRIPTION:
EAST FORK TURKEY CREEK 67.0
END DESCRIPTION:
XS GIS Cut Line= 3
      2781606.63      7103854.33      2781158.71      7103841.31
      2780760.26      7103836.10
#Sta/Elev= 30
  4548.3  614.29  4630.0  612.86  4660.0  611.80  4690.0  609.91  4750.0  607.76
  4760.0  608.82  4770.0  609.09  4860.1  607.23  4890.1  605.79  4930.1  605.79
  4950.1  604.56  4956.7  602.51  4960.1  601.45  4987.1  599.01  4987.6  598.21
  4992.6  598.21  4993.1  599.01  5010.1  600.01  5015.8  602.51  5020.1  604.43
  5030.1  604.63  5090.1  603.54  5100.7  604.16  5130.1  603.99  5170.1  605.23
  5230.1  603.68  5252.4  603.74  5270.1  604.84  5332.8  606.16  5394.9  606.23
#Mann=5,-1,0
  4548.3    0.08       0  4987.1    0.07       0  4993.1    0.08       0
  5252.4    0.05       0  5332.8    0.08       0
Bank Sta=4956.7,5015.8
Exp/Cntr=0.3,0.1

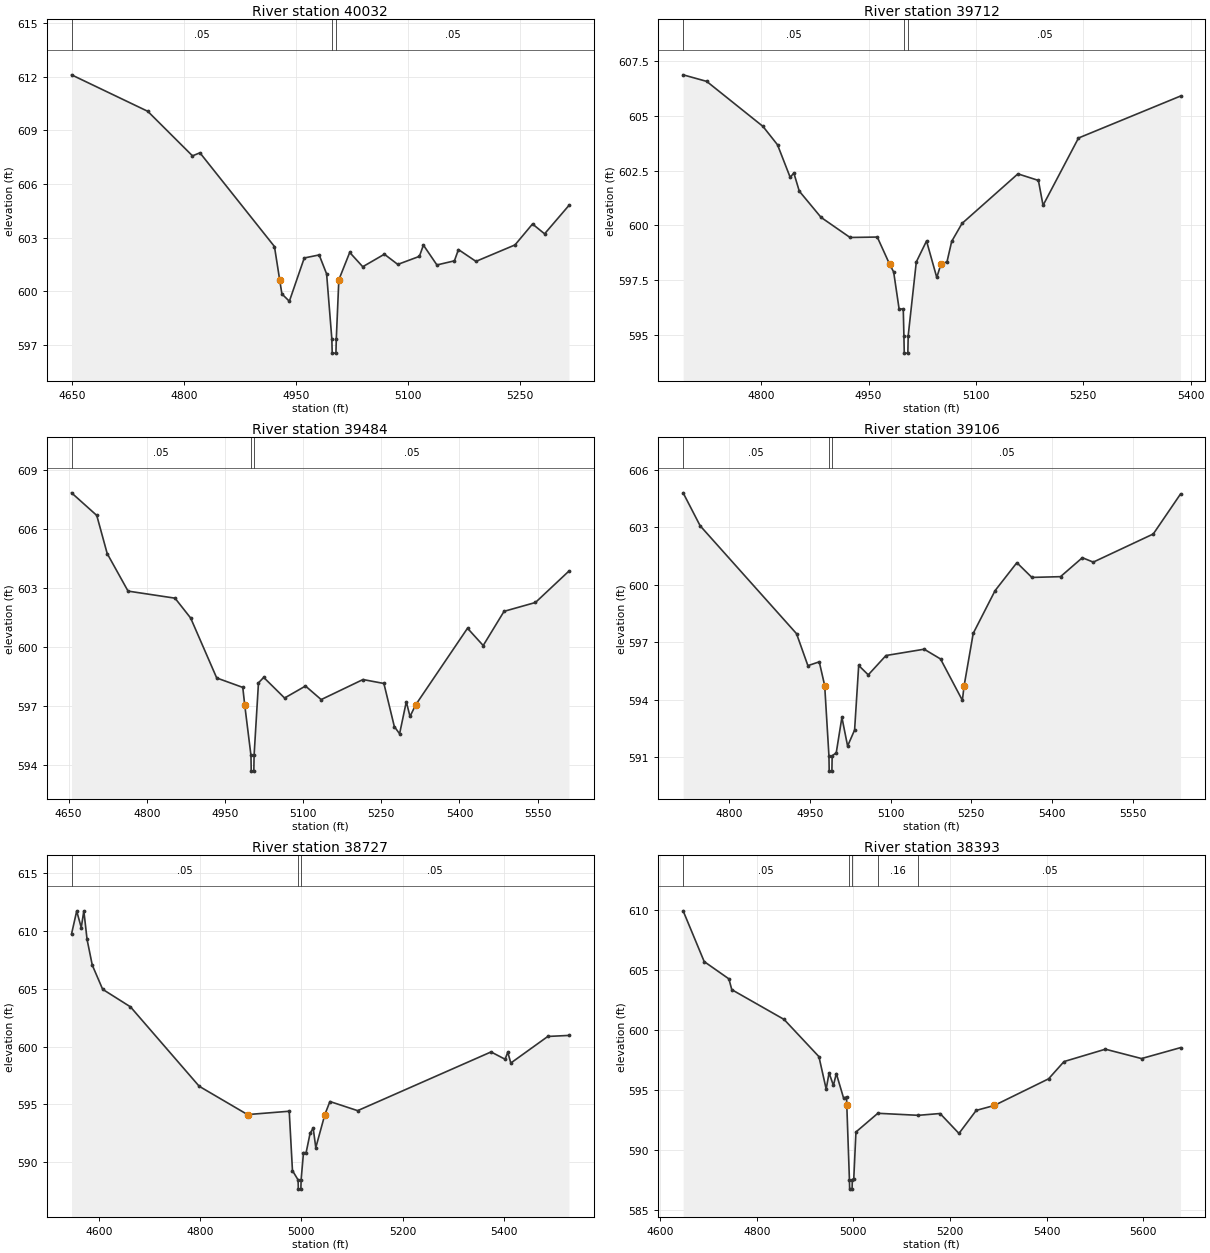
Type RM Length L Ch R = 1,40032,320,320,320
BEGIN DESCRIPTION:
Mapping XS fec85c27
END DESCRIPTION:
XS GIS Cut Line= 3
      2781477.24      7103620.82      2781116.18      7103627.76
      2780834.94      7103749.29
#Sta/Elev= 30
  4648.8  612.11  4751.1  610.07  4811.1  607.58  4821.1  607.75  4921.1  602.51
  4928.1  600.65  4931.1  599.86  4941.1  599.45  4961.1  601.87  4981.1  602.04
  4991.1  600.98  4998.1  597.35  4998.6  596.55  5003.6  596.55  5004.1  597.35
  5007.5  600.65  5022.1  602.18  5039.6  601.38  5068.6  602.08  5086.6  601.51
  5115.6  601.96  5121.0  602.59  5139.1  601.48  5162.6  601.71  5168.0  602.34
  5191.5  601.68  5243.9  602.60  5267.4  603.77  5283.6  603.22  5316.3  604.81
#Mann=3,-1,0
  4648.8    0.05       0  4998.1    0.03       0  5004.1    0.05       0
Bank Sta=4928.1,5007.5
Exp/Cntr=0.3,0.1

Type RM Length L Ch R = 1,39712,228,228,228
BEGIN DESCRIPTION:
EAST FORK TURKEY CREEK 66.0
END DESCRIPTION:
XS GIS Cut Line= 3
      2781224.96      7103375.01      2780925.00      7103425.00
      2780675.01      7103724.99
#Sta/Elev= 30
  4691.1  606.88  4724.0  606.58  4802.6  604.52  4822.9  603.68  4840.6  602.19
  4845.7  602.39  4853.3  601.56  4883.7  600.36  4924.2  599.44  4962.2  599.46
  4979.4  598.22  4985.1  597.86  4992.7  596.17  4998.5  596.17  4999.4  594.95
  4999.9  594.15  5004.9  594.15  5005.4  594.95  5016.7  598.32  5031.0  599.28
  5045.3  597.61  5051.1  598.22  5059.6  598.33  5066.1  599.26  5080.5  600.08
  5158.6  602.35  5187.2  602.05  5193.7  600.91  5243.2  603.99  5385.7  605.91
#Mann=3,-1,0
  4691.1    0.05       0  4999.4    0.03       0  5005.4    0.05       0
Bank Sta=4979.4,5051.1
Exp/Cntr=0.3,0.1

Type RM Length L Ch R = 1,39484,378,378,378
BEGIN DESCRIPTION:
EAST FORK TURKEY CREEK 65.0
END DESCRIPTION:
XS GIS Cut Line= 3
      2781273.40      7103230.85      2780958.00      7103222.44
      2780320.84      7103178.28
#Sta/Elev= 30
  4655.8  607.84  4704.2  606.69  4724.2  604.75  4764.2  602.84  4854.3  602.48
  4884.3  601.47  4934.3  598.42  4984.3  597.94  4988.0  597.05  5000.0  594.48
  5000.5  593.68  5005.5  593.68  5006.0  594.48  5014.4  598.17  5024.4  598.45
  5064.5  597.40  5104.6  598.01  5134.7  597.32  5214.9  598.34  5255.0  598.14
  5275.0  595.95  5285.1  595.58  5298.0  597.21  5305.1  596.46  5315.9  597.05
  5415.4  600.95  5445.5  600.07  5485.5  601.81  5545.7  602.26  5610.0  603.86
#Mann=3,-1,0
  4655.8    0.05       0  5000.0    0.03       0  5006.0    0.05       0
Bank Sta=4988,5315.9
Exp/Cntr=0.3,0.1

Type RM Length L Ch R = 1,39106,379,379,379
BEGIN DESCRIPTION:
EAST FORK TURKEY CREEK 64.0
END DESCRIPTION:
XS GIS Cut Line= 3
      2781174.97      7102974.99      2780875.00      7102875.00
      2780274.97      7102975.00
#Sta/Elev= 30
  4714.5  604.80  4746.1  603.08  4925.3  597.44  4946.4  595.77  4967.5  595.97
  4977.6  594.73  4985.5  591.06  4986.0  590.26  4991.0  590.26  4991.5  591.06
  4999.1  591.22  5009.6  593.07  5020.2  591.57  5033.2  592.41  5040.8  595.78
  5058.6  595.29  5091.5  596.30  5162.5  596.63  5192.9  596.12  5233.5  593.96
  5236.8  594.73  5253.7  597.46  5294.3  599.69  5334.8  601.15  5362.7  600.38
  5415.9  600.42  5456.5  601.41  5476.8  601.18  5588.3  602.65  5639.0  604.74
#Mann=3,-1,0
  4714.5    0.05       0  4985.5    0.03       0  4991.5    0.05       0
Bank Sta=4977.6,5236.8
Exp/Cntr=0.3,0.1

Type RM Length L Ch R = 1,38727,334,334,334
BEGIN DESCRIPTION:
EAST FORK TURKEY CREEK 63.0
END DESCRIPTION:
XS GIS Cut Line= 3
      2781375.00      7102675.00      2780925.00      7102575.00
      2780424.99      7102725.00
#Sta/Elev= 30
  4545.7  609.75  4555.9  611.73  4564.9  610.30  4570.0  611.75  4576.4  609.27
  4586.7  607.05  4607.2  604.96  4662.2  603.44  4798.0  596.57  4893.5  594.12
  4975.9  594.41  4982.3  589.27  4993.4  588.47  4993.9  587.67  4998.9  587.67
  4999.4  588.47  5004.1  590.83  5009.3  590.83  5017.1  592.49  5023.2  592.96
  5028.4  591.26  5046.3  594.12  5056.3  595.25  5111.1  594.46  5374.7  599.54
  5402.5  598.91  5407.8  599.52  5413.8  598.58  5486.9  600.88  5528.7  600.97
#Mann=3,-1,0
  4545.7    0.05       0  4993.4    0.03       0  4999.4    0.05       0
Bank Sta=4893.5,5046.3
Exp/Cntr=0.3,0.1

Type RM Length L Ch R = 1,38393,381,381,381
BEGIN DESCRIPTION:
EAST FORK TURKEY CREEK 62.0
END DESCRIPTION:
XS GIS Cut Line= 3
      2781425.03      7102525.02      2781125.00      7102325.00
      2780499.54      7102561.58
#Sta/Elev= 30
  4647.6  609.89  4691.2  605.66  4742.3  604.22  4748.3  603.32  4856.5  600.84
  4928.6  597.74  4943.6  595.04  4949.6  596.38  4958.6  595.34  4964.6  596.33
  4979.6  594.29  4985.7  594.38  4986.3  593.67  4991.7  587.50  4992.2  586.70
  4997.2  586.70  4997.7  587.50  5000.7  587.55  5005.2  591.46  5050.5  593.02
  5134.1  592.85  5179.3  593.00  5218.4  591.34  5254.1  593.26  5291.4  593.67
  5403.8  595.89  5435.8  597.33  5521.4  598.36  5596.2  597.58  5676.9  598.49
#Mann=5,-1,0
  4647.6    0.05       0  4991.7    0.03       0  4997.7    0.05       0
  5050.5    0.16       0  5134.1    0.05       0
Bank Sta=4986.3,5291.4
Exp/Cntr=0.3,0.1

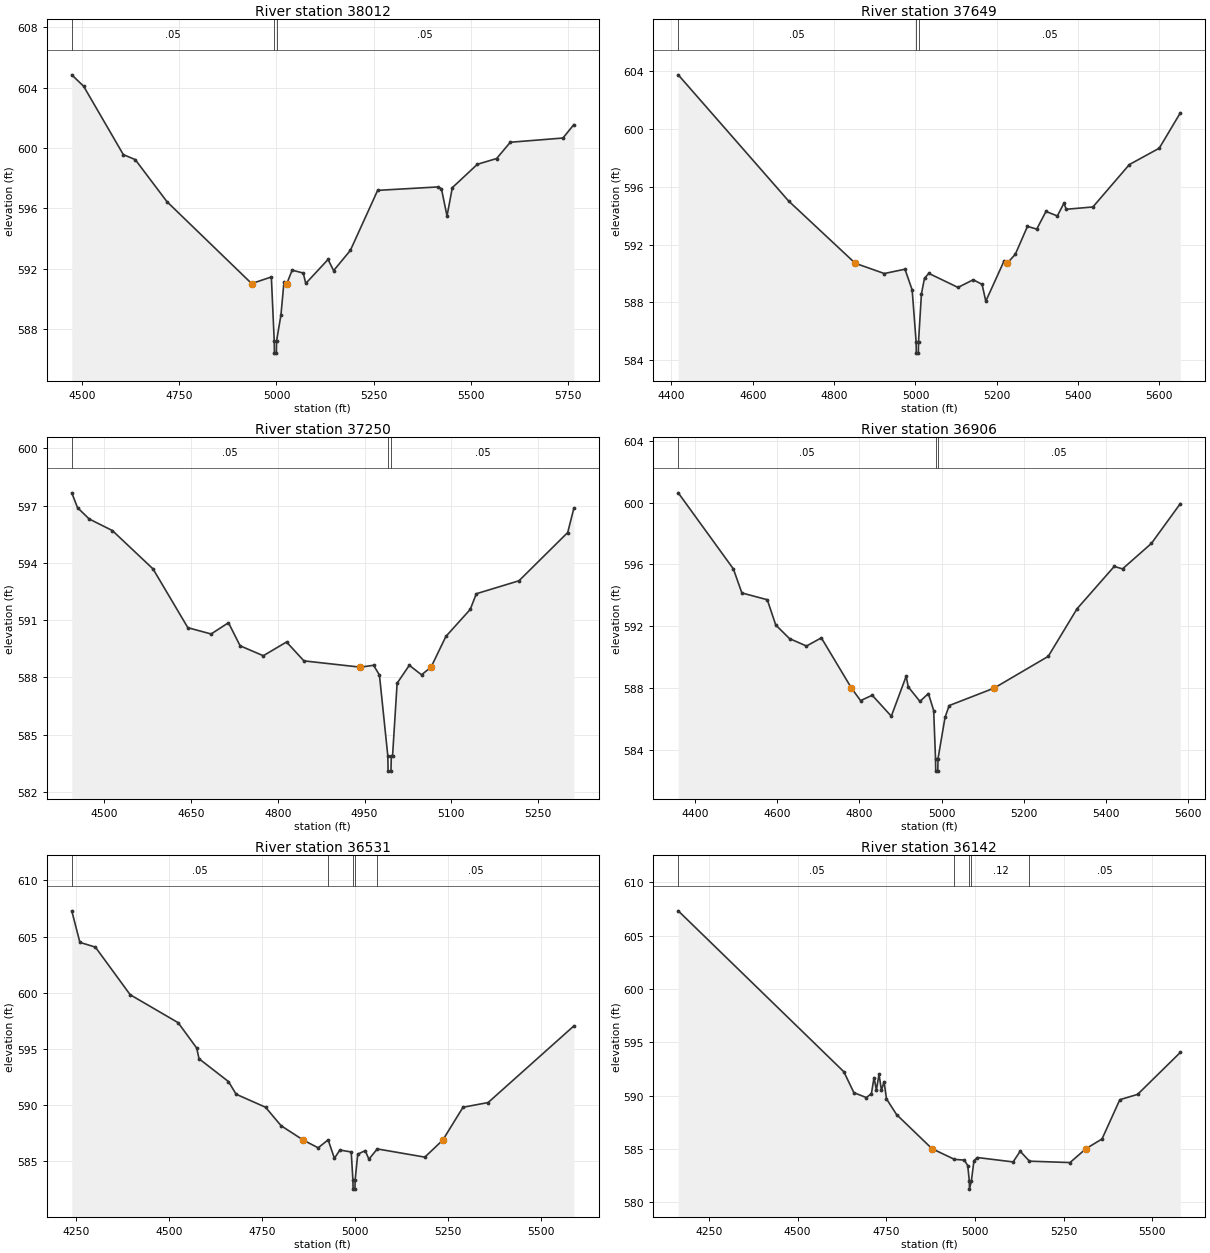
Type RM Length L Ch R = 1,38012,363,363,363
BEGIN DESCRIPTION:
EAST FORK TURKEY CREEK 61.0
END DESCRIPTION:
XS GIS Cut Line= 3
      2781375.03      7102074.99      2780875.00      7102175.00
      2780274.97      7102675.03
#Sta/Elev= 30
  4473.7  604.85  4504.3  604.09  4606.3  599.56  4636.9  599.23  4718.5  596.44
  4936.3  591.01  4986.9  591.45  4994.3  587.20  4994.8  586.40  4999.8  586.40
  5000.3  587.20  5011.6  588.94  5019.4  591.13  5026.7  591.01  5040.3  591.90
  5068.9  591.71  5075.4  591.02  5132.7  592.61  5147.0  591.87  5190.0  593.21
  5260.2  597.19  5416.4  597.42  5424.3  597.29  5438.6  595.49  5452.2  597.37
  5516.7  598.92  5566.1  599.30  5601.3  600.38  5736.7  600.66  5764.7  601.55
#Mann=3,-1,0
  4473.7    0.05       0  4994.3    0.03       0  5000.3    0.05       0
Bank Sta=4936.3,5026.7
Exp/Cntr=0.3,0.1

Type RM Length L Ch R = 1,37649,399,399,399
BEGIN DESCRIPTION:
EAST FORK TURKEY CREEK 60.0
END DESCRIPTION:
XS GIS Cut Line= 3
      2781274.99      7101875.00      2780675.00      7101975.00
      2780124.97      7102275.02
#Sta/Elev= 30
  4416.6  603.73  4687.8  595.02  4851.9  590.71  4923.5  590.00  4974.2  590.30
  4991.9  588.87  5001.6  585.30  5002.1  584.50  5007.1  584.50  5007.6  585.30
  5014.7  588.59  5022.3  589.68  5032.9  590.01  5104.6  589.04  5142.1  589.57
  5163.9  589.25  5173.0  588.09  5218.0  590.87  5225.6  590.71  5245.6  591.33
  5275.5  593.26  5298.3  593.07  5321.0  594.29  5349.0  593.98  5365.2  594.86
  5370.9  594.44  5436.4  594.60  5526.1  597.53  5599.6  598.66  5651.4  601.10
#Mann=3,-1,0
  4416.6    0.05       0  5001.6    0.03       0  5007.6    0.05       0
Bank Sta=4851.9,5225.6
Exp/Cntr=0.3,0.1

Type RM Length L Ch R = 1,37250,344,344,344
BEGIN DESCRIPTION:
EAST FORK TURKEY CREEK 59.0
END DESCRIPTION:
XS GIS Cut Line= 3
      2781024.98      7101775.00      2780475.00      7101725.00
      2780174.97      7101825.01
#Sta/Elev= 30
  4443.5  597.67  4453.5  596.89  4473.6  596.30  4513.8  595.69  4584.1  593.68
  4644.3  590.60  4684.5  590.27  4714.6  590.86  4734.7  589.65  4774.8  589.13
  4815.0  589.85  4845.1  588.86  4942.9  588.53  4965.6  588.63  4975.7  588.12
  4990.2  583.88  4990.7  583.08  4995.7  583.08  4996.2  583.88  4998.4  583.88
  5006.3  587.69  5027.4  588.63  5048.5  588.13  5065.0  588.53  5090.6  590.14
  5132.8  591.56  5143.3  592.38  5217.1  593.06  5301.4  595.59  5312.0  596.86
#Mann=3,-1,0
  4443.5    0.05       0  4990.2    0.03       0  4996.2    0.05       0
Bank Sta=4942.9,5065
Exp/Cntr=0.3,0.1

Type RM Length L Ch R = 1,36906,375,375,375
BEGIN DESCRIPTION:
EAST FORK TURKEY CREEK 58.0
END DESCRIPTION:
XS GIS Cut Line= 3
      2781225.04      7101575.01      2780625.00      7101425.00
      2780024.98      7101375.00
#Sta/Elev= 30
  4359.8  600.64  4493.8  595.71  4514.5  594.15  4576.3  593.71  4596.9  592.07
  4630.4  591.19  4671.6  590.71  4707.7  591.24  4781.0  587.98  4803.1  587.17
  4831.4  587.52  4877.8  586.16  4913.9  588.75  4919.0  588.06  4947.4  587.12
  4968.0  587.63  4980.8  586.53  4985.3  583.40  4985.8  582.60  4990.8  582.60
  4991.3  583.40  5008.4  586.08  5018.4  586.85  5127.6  587.98  5259.3  590.04
  5329.5  593.13  5419.8  595.87  5439.9  595.71  5510.1  597.36  5580.4  599.94
#Mann=3,-1,0
  4359.8    0.05       0  4985.3    0.03       0  4991.3    0.05       0
Bank Sta=4781,5127.6
Exp/Cntr=0.3,0.1

Type RM Length L Ch R = 1,36531,389,389,389
BEGIN DESCRIPTION:
EAST FORK TURKEY CREEK 57.0
END DESCRIPTION:
XS GIS Cut Line= 3
      2781375.03      7101625.02      2780775.00      7101175.00
      2780175.02      7101125.00
#Sta/Elev= 30
  4237.5  607.29  4259.4  604.48  4301.1  604.06  4394.8  599.82  4524.0  597.33
  4574.0  595.07  4580.2  594.12  4659.4  592.09  4680.2  590.96  4759.4  589.80
  4801.1  588.16  4861.2  586.87  4901.1  586.19  4927.9  586.90  4944.8  585.25
  4959.4  585.99  4990.1  585.82  4994.6  583.31  4995.1  582.51  5000.1  582.51
  5000.6  583.31  5007.6  585.62  5027.7  585.94  5037.7  585.18  5060.3  586.09
  5188.2  585.36  5236.5  586.87  5291.1  589.80  5358.8  590.22  5589.6  597.04
#Mann=5,-1,0
  4237.5    0.05       0  4927.9    0.12       0  4994.6    0.07       0
  5000.6    0.12       0  5060.3    0.05       0
Bank Sta=4861.2,5236.5
Exp/Cntr=0.3,0.1

Type RM Length L Ch R = 1,36142,383,383,383
BEGIN DESCRIPTION:
EAST FORK TURKEY CREEK 56.0
END DESCRIPTION:
XS GIS Cut Line= 3
      2781524.98      7101424.98      2780925.00      7100875.00
      2780324.99      7100825.00
#Sta/Elev= 30
  4163.3  607.33  4630.4  592.25  4658.7  590.29  4693.9  589.83  4708.1  590.20
  4715.5  591.70  4722.2  590.54  4729.6  592.02  4736.4  590.51  4743.8  591.32
  4750.6  589.71  4779.0  588.24  4879.0  585.04  4942.4  584.04  4970.1  583.97
  4979.7  583.46  4984.2  582.05  4984.7  581.25  4990.2  582.05  4997.3  583.92
  5007.3  584.21  5107.7  583.80  5127.7  584.80  5153.8  583.87  5268.2  583.74
  5313.2  585.04  5358.5  585.95  5408.7  589.63  5458.9  590.13  5579.3  594.06
#Mann=5,-1,0
  4163.3    0.05       0  4942.4    0.12       0  4984.2    0.07       0
  4990.2    0.12       0  5153.8    0.05       0
Bank Sta=4879,5313.2
Exp/Cntr=0.3,0.1