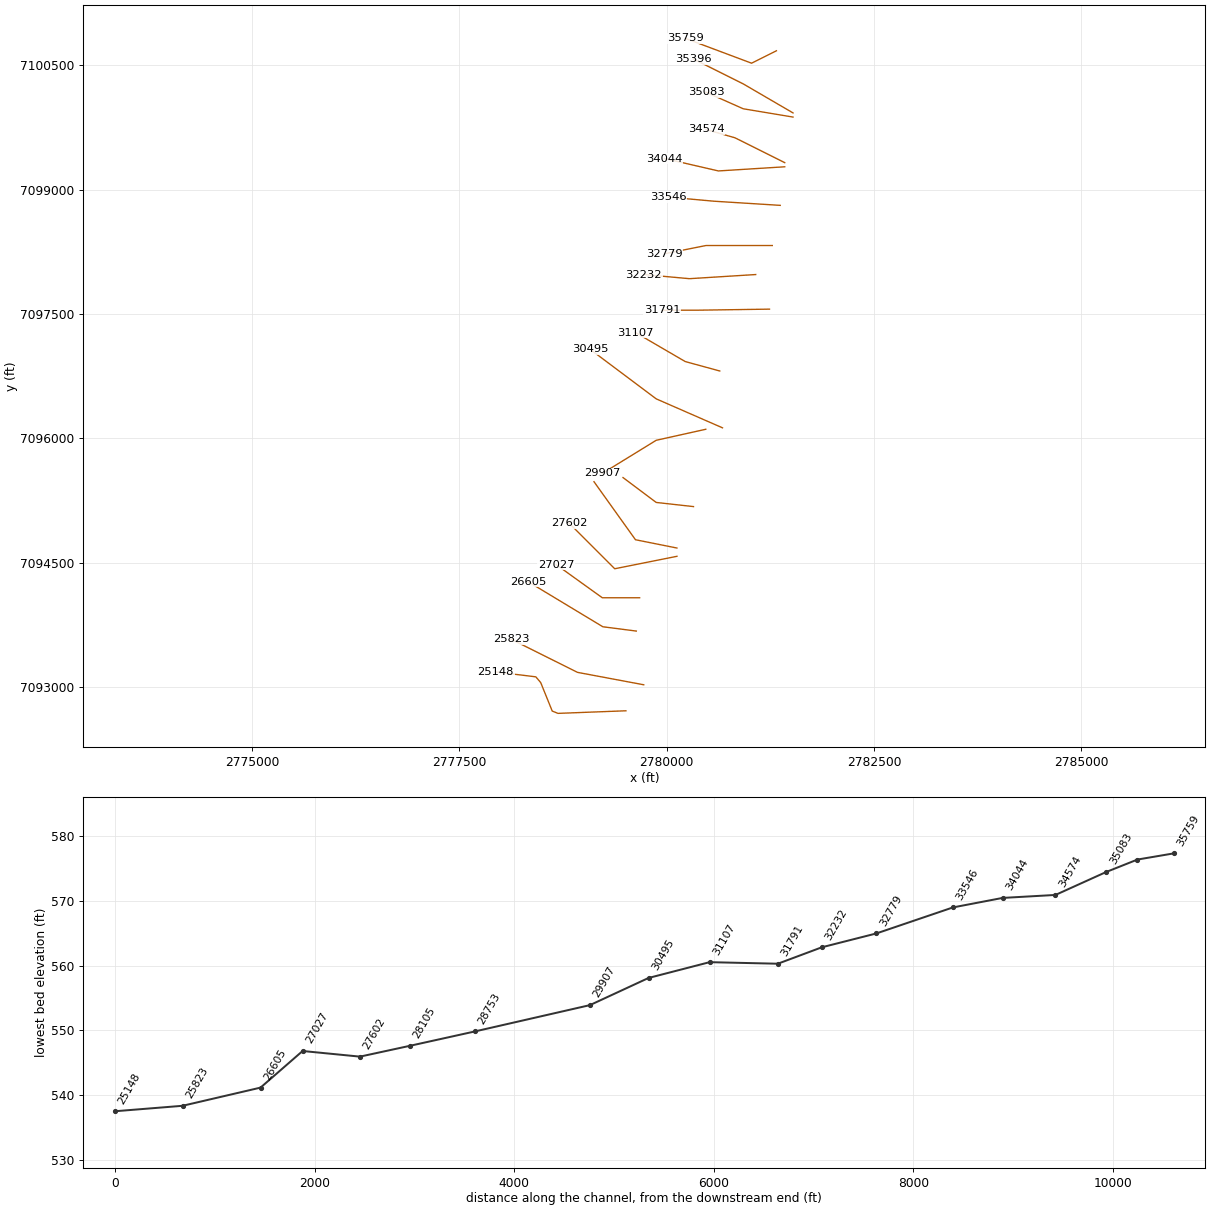
HEC-RAS study EAST FORK TURKEY CREEK.prj: EAST FORK TURKEY CREEK Base Level Engineering

--- EAST FORK TURKEY CREEK.g01 (geometry) --- (continued)

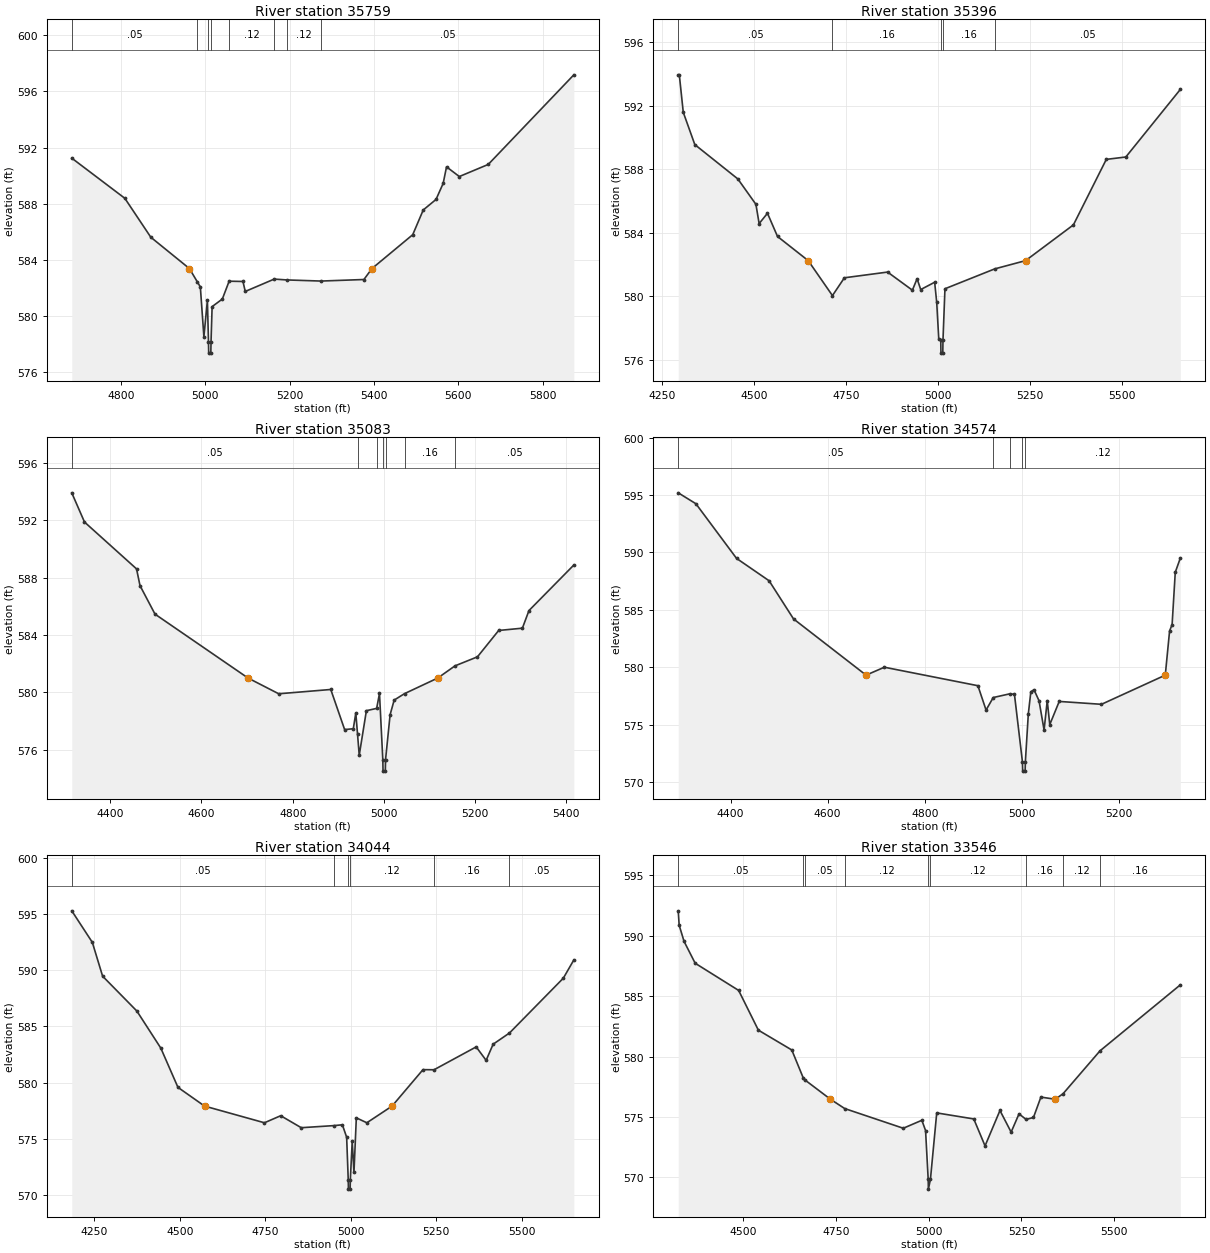
Type RM Length L Ch R = 1,35759,363,363,363
BEGIN DESCRIPTION:
EAST FORK TURKEY CREEK 55.0
END DESCRIPTION:
XS GIS Cut Line= 3
      2781325.01      7100675.01      2781025.00      7100525.00
      2780225.02      7100824.99
#Sta/Elev= 30
  4683.7  591.25  4809.5  588.39  4871.0  585.62  4962.5  583.39  4981.3  582.44
  4988.4  582.08  4996.8  578.54  5005.1  581.13  5007.7  578.17  5008.2  577.37
  5013.2  577.37  5013.7  578.17  5016.3  580.68  5040.5  581.22  5056.6  582.49
  5089.4  582.47  5094.8  581.76  5163.4  582.64  5193.1  582.58  5274.3  582.50
  5376.0  582.61  5395.1  583.39  5491.7  585.80  5516.6  587.56  5546.9  588.31
  5563.8  589.45  5571.8  590.63  5602.1  589.94  5670.6  590.80  5873.5  597.18
#Mann=8,-1,0
  4683.7    0.05       0  4981.3    0.16       0  5007.7    0.07       0
  5013.7    0.16       0  5056.6    0.12       0  5163.4     0.1       0
  5193.1    0.12       0  5274.3    0.05       0
Bank Sta=4962.5,5395.1
Exp/Cntr=0.3,0.1

Type RM Length L Ch R = 1,35396,313,313,313
BEGIN DESCRIPTION:
EAST FORK TURKEY CREEK 54.0
END DESCRIPTION:
XS GIS Cut Line= 3
      2781525.02      7099924.99      2780925.00      7100275.00
      2780324.97      7100575.02
#Sta/Elev= 30
  4294.3  593.93  4297.2  593.93  4308.0  591.57  4339.4  589.54  4456.4  587.38
  4505.6  585.78  4514.3  584.57  4537.0  585.22  4564.3  583.76  4647.8  582.24
  4713.7  580.04  4746.2  581.16  4863.7  581.52  4931.1  580.38  4943.9  581.10
  4953.8  580.42  4991.7  580.88  4997.3  579.61  5002.9  577.30  5008.3  577.22
  5008.8  576.42  5013.8  576.42  5014.3  577.22  5019.7  580.47  5155.0  581.72
  5239.0  582.24  5369.1  584.49  5458.5  588.61  5511.6  588.76  5659.8  593.01
#Mann=5,-1,0
  4294.3    0.05       0  4713.7    0.16       0  5008.3    0.07       0
  5014.3    0.16       0  5155.0    0.05       0
Bank Sta=4647.8,5239
Exp/Cntr=0.3,0.1

Type RM Length L Ch R = 1,35083,509,509,509
BEGIN DESCRIPTION:
EAST FORK TURKEY CREEK 53.0
END DESCRIPTION:
XS GIS Cut Line= 3
      2781525.03      7099874.99      2780925.00      7099975.00
      2780475.05      7100174.98
#Sta/Elev= 30
  4315.6  593.93  4343.5  591.89  4457.6  588.62  4465.2  587.45  4498.1  585.46
  4702.0  581.00  4769.3  579.90  4883.4  580.20  4913.8  577.40  4932.8  577.46
  4938.3  578.56  4942.1  577.07  4945.8  575.61  4961.5  578.72  4984.0  578.88
  4990.2  579.92  4997.5  575.30  4998.0  574.50  5003.0  574.50  5003.5  575.30
  5013.5  578.44  5022.4  579.46  5045.1  579.91  5118.0  581.00  5155.8  581.85
  5205.0  582.48  5251.5  584.32  5303.5  584.48  5317.9  585.71  5416.3  588.89
#Mann=7,-1,0
  4315.6    0.05       0  4942.1    0.16       0  4984.0    0.12       0
  4997.5    0.07       0  5003.5    0.12       0  5045.1    0.16       0
  5155.8    0.05       0
Bank Sta=4702,5118
Exp/Cntr=0.3,0.1

Type RM Length L Ch R = 1,34574,530,530,530
BEGIN DESCRIPTION:
EAST FORK TURKEY CREEK 52.0
END DESCRIPTION:
XS GIS Cut Line= 3
      2781425.03      7099324.99      2780825.00      7099625.00
      2780474.96      7099725.01
#Sta/Elev= 30
  4292.0  595.19  4328.4  594.24  4412.2  589.48  4479.3  587.53  4529.6  584.21
  4679.2  579.31  4716.9  580.00  4909.7  578.39  4926.5  576.27  4941.3  577.36
  4975.1  577.68  4985.0  577.64  5001.5  571.75  5002.0  570.95  5007.0  570.95
  5007.5  571.75  5013.6  575.93  5018.8  577.86  5025.3  578.04  5035.7  577.08
  5046.1  574.53  5052.6  577.09  5057.8  575.00  5077.3  577.02  5164.4  576.77
  5295.9  579.31  5304.8  583.16  5310.0  583.72  5316.5  588.27  5326.9  589.50
#Mann=5,-1,0
  4292.0    0.05       0  4941.3    0.16       0  4975.1    0.12       0
  5001.5    0.07       0  5007.5    0.12       0
Bank Sta=4679.2,5295.9
Exp/Cntr=0.3,0.1

Type RM Length L Ch R = 1,34044,498,498,498
BEGIN DESCRIPTION:
EAST FORK TURKEY CREEK 51.0
END DESCRIPTION:
XS GIS Cut Line= 3
      2781425.02      7099275.00      2780625.00      7099225.00
      2779974.96      7099375.01
#Sta/Elev= 30
  4183.8  595.32  4243.9  592.51  4274.0  589.49  4374.2  586.38  4444.3  583.07
  4494.4  579.57  4572.2  577.90  4747.4  576.41  4795.0  577.04  4855.1  575.97
  4952.0  576.16  4975.4  576.23  4987.9  575.12  4992.6  571.29  4993.1  570.49
  4998.1  570.49  4998.6  571.29  5004.2  574.76  5009.3  571.99  5016.2  576.85
  5047.0  576.41  5120.8  577.90  5211.2  581.15  5243.5  581.14  5366.8  583.18
  5395.9  581.98  5416.4  583.42  5464.2  584.42  5621.7  589.31  5652.5  590.94
#Mann=6,-1,0
  4183.8    0.05       0  4952.0    0.12       0  4992.6    0.07       0
  4998.6    0.12       0  5243.5    0.16       0  5464.2    0.05       0
Bank Sta=4572.2,5120.8
Exp/Cntr=0.3,0.1

Type RM Length L Ch R = 1,33546,767,767,767
BEGIN DESCRIPTION:
EAST FORK TURKEY CREEK 50.0
END DESCRIPTION:
XS GIS Cut Line= 3
      2781370.64      7098809.72      2780570.66      7098859.72
      2780020.67      7098909.72
#Sta/Elev= 30
  4324.7  592.06  4327.2  590.87  4340.4  589.53  4370.4  587.72  4487.6  585.47
  4540.8  582.18  4630.9  580.54  4661.6  578.24  4665.4  578.08  4735.2  576.46
  4773.6  575.69  4931.5  574.06  4981.6  574.72  4991.6  573.87  4998.7  569.82
  4999.2  569.02  5004.7  569.82  5021.7  575.33  5121.6  574.83  5152.0  572.60
  5192.2  575.53  5222.3  573.74  5243.6  575.25  5262.7  574.79  5282.5  574.95
  5302.6  576.64  5341.3  576.46  5362.4  576.92  5462.0  580.47  5678.5  585.93
#Mann=9,-1,0
  4324.7    0.05       0  4661.6    0.16       0  4665.4    0.05       0
  4773.6    0.12       0  4998.7    0.07       0  5004.7    0.12       0
  5262.7    0.16       0  5362.4    0.12       0  5462.0    0.16       0
Bank Sta=4735.2,5341.3
Exp/Cntr=0.3,0.1

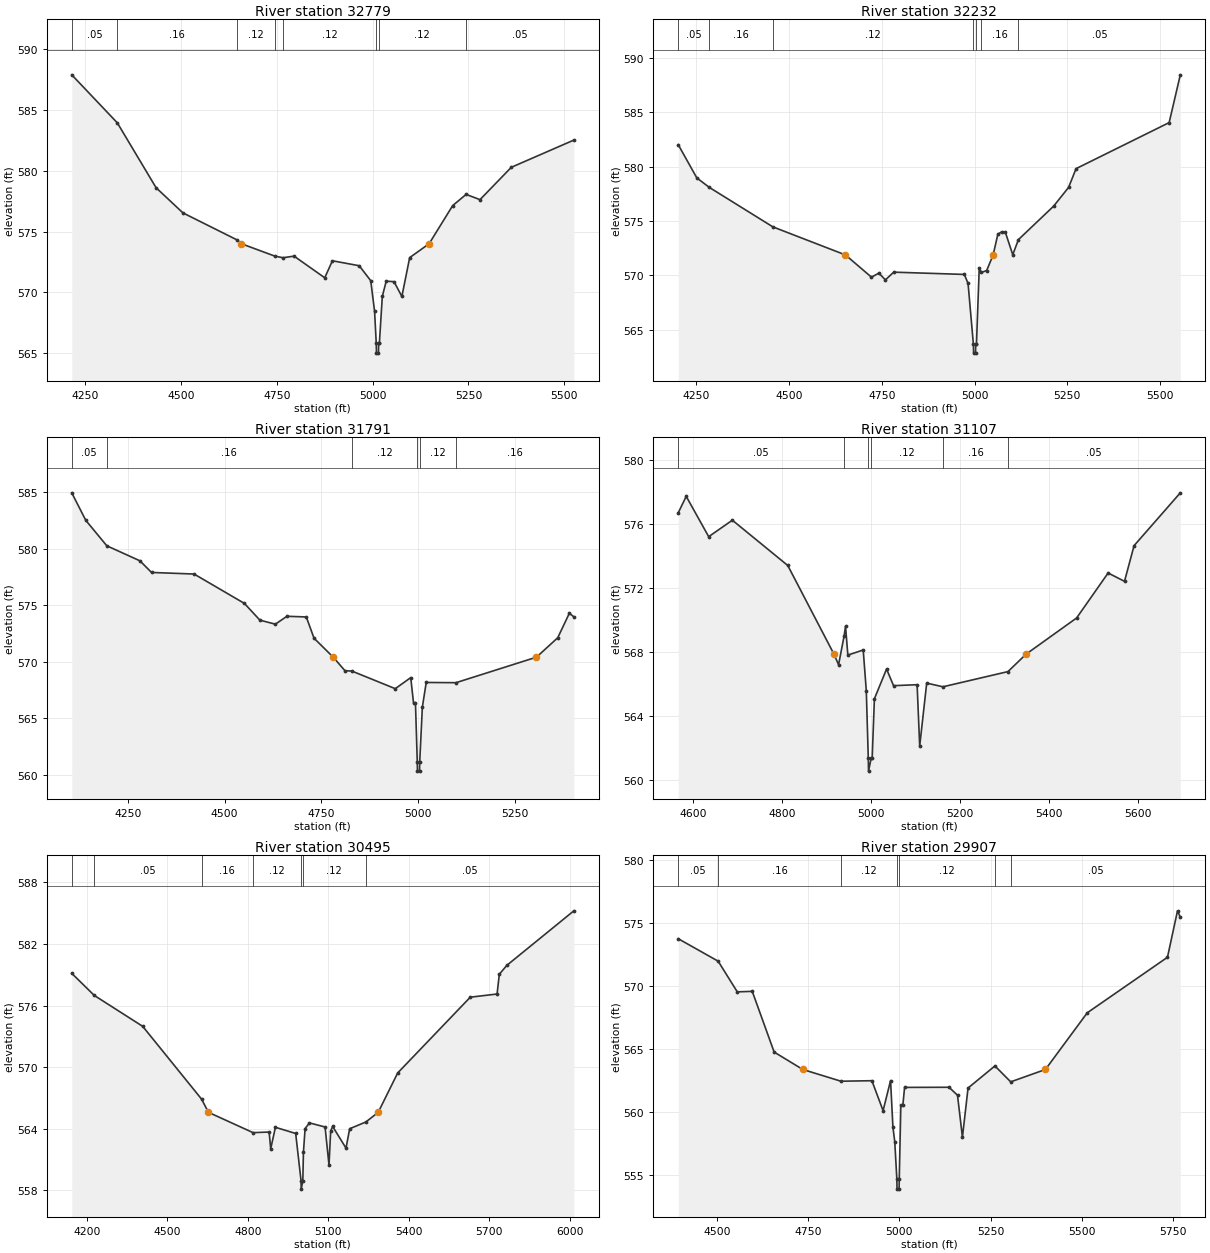
Type RM Length L Ch R = 1,32779,547,547,547
BEGIN DESCRIPTION:
EAST FORK TURKEY CREEK 49.0
END DESCRIPTION:
XS GIS Cut Line= 3
      2781274.99      7098325.00      2780475.00      7098325.00
      2779974.99      7098225.00
#Sta/Elev= 30
  4215.1  587.90  4333.9  583.95  4435.1  578.61  4505.1  576.54  4646.1  574.32
  4657.7  574.00  4745.1  572.98  4766.4  572.85  4795.1  572.98  4875.1  571.20
  4895.1  572.60  4965.1  572.19  4995.1  570.96  5005.1  568.45  5009.5  565.80
  5010.0  565.00  5015.2  565.00  5015.7  565.80  5017.6  565.80  5025.3  569.67
  5035.5  570.92  5055.9  570.88  5076.3  569.66  5096.7  572.86  5147.4  574.00
  5208.9  577.14  5243.9  578.06  5280.2  577.63  5361.8  580.29  5525.0  582.53
#Mann=8,-1,0
  4215.1    0.05       0  4333.9    0.16       0  4646.1    0.12       0
  4745.1    0.16       0  4766.4    0.12       0  5009.5    0.07       0
  5015.7    0.12       0  5243.9    0.05       0
Bank Sta=4657.7,5147.4
Exp/Cntr=0.3,0.1

Type RM Length L Ch R = 1,32232,441,441,441
BEGIN DESCRIPTION:
EAST FORK TURKEY CREEK 48.0
END DESCRIPTION:
XS GIS Cut Line= 3
      2781074.99      7097975.00      2780275.00      7097925.00
      2779725.02      7097975.00
#Sta/Elev= 30
  4200.8  582.01  4250.9  578.96  4284.5  578.09  4456.0  574.46  4651.8  571.88
  4721.8  569.84  4741.8  570.21  4759.4  569.59  4781.9  570.30  4972.3  570.09
  4982.3  569.26  4996.7  563.66  4997.2  562.86  5002.4  562.86  5002.9  563.66
  5004.9  563.66  5012.4  570.64  5018.4  570.27  5032.5  570.45  5049.9  571.88
  5062.6  573.78  5072.6  574.00  5082.7  573.98  5102.8  571.90  5118.1  573.29
  5213.2  576.37  5253.4  578.09  5273.5  579.81  5524.5  584.04  5554.6  588.43
#Mann=7,-1,0
  4200.8    0.05       0  4284.5    0.16       0  4456.0    0.12       0
  4996.7    0.07       0  5002.9    0.12       0  5018.4    0.16       0
  5118.1    0.05       0
Bank Sta=4651.8,5049.9
Exp/Cntr=0.3,0.1

Type RM Length L Ch R = 1,31791,684,684,684
BEGIN DESCRIPTION:
EAST FORK TURKEY CREEK 47.0
END DESCRIPTION:
XS GIS Cut Line= 3
      2781241.14      7097557.45      2780355.76      7097544.43
      2779943.43      7097544.43
#Sta/Elev= 30
  4105.1  584.96  4141.2  582.53  4195.7  580.27  4281.3  578.94  4311.3  577.91
  4421.3  577.77  4551.3  575.17  4591.3  573.69  4631.3  573.33  4661.3  574.03
  4711.3  573.97  4731.3  572.09  4780.9  570.41  4811.3  569.21  4829.1  569.18
  4941.3  567.62  4981.3  568.60  4988.5  566.35  4993.5  566.35  4998.2  561.12
  4998.7  560.32  5004.0  560.32  5004.5  561.12  5011.3  565.98  5021.3  568.17
  5098.2  568.15  5306.3  570.41  5361.3  572.13  5391.3  574.30  5402.9  573.98
#Mann=6,-1,0
  4105.1    0.05       0  4195.7    0.16       0  4829.1    0.12       0
  4998.2    0.07       0  5004.5    0.12       0  5098.2    0.16       0
Bank Sta=4780.9,5306.3
Exp/Cntr=0.3,0.1

Type RM Length L Ch R = 1,31107,612,612,612
BEGIN DESCRIPTION:
EAST FORK TURKEY CREEK 46.0
END DESCRIPTION:
XS GIS Cut Line= 3
      2780642.23      7096810.92      2780225.00      7096925.00
      2779624.97      7097275.02
#Sta/Elev= 30
  4567.5  576.70  4585.4  577.73  4635.9  575.21  4689.0  576.24  4813.4  573.41
  4917.1  567.87  4927.5  567.21  4939.9  569.01  4943.1  569.61  4948.3  567.81
  4982.8  568.13  4989.7  565.59  4994.2  561.36  4994.7  560.56  5000.6  561.36
  5002.9  561.36  5007.9  565.08  5035.2  566.94  5050.9  565.90  5103.8  565.96
  5109.6  562.13  5125.3  566.06  5161.8  565.83  5307.8  566.78  5348.5  567.87
  5461.9  570.13  5532.6  572.94  5569.4  572.42  5590.9  574.65  5694.7  577.95
#Mann=6,-1,0
  4567.5    0.05       0  4939.9    0.12       0  4994.2    0.07       0
  5000.6    0.12       0  5161.8    0.16       0  5307.8    0.05       0
Bank Sta=4917.1,5348.5
Exp/Cntr=0.3,0.1

Type RM Length L Ch R = 1,30495,588,588,588
BEGIN DESCRIPTION:
EAST FORK TURKEY CREEK 45.0
END DESCRIPTION:
XS GIS Cut Line= 3
      2780675.01      7096125.00      2779875.00      7096475.00
      2779075.02      7097074.99
#Sta/Elev= 30
  4143.0  579.13  4227.1  576.98  4407.7  573.97  4627.1  566.89  4652.9  565.60
  4819.4  563.62  4879.4  563.68  4885.2  562.05  4902.8  564.14  4978.4  563.54
  4998.5  558.92  4999.0  558.12  5005.0  558.92  5007.3  561.71  5013.5  564.01
  5029.8  564.57  5088.1  564.17  5102.7  560.47  5108.9  563.76  5116.2  564.23
  5166.2  562.11  5179.8  564.00  5240.4  564.66  5286.3  565.60  5358.9  569.43
  5629.8  576.81  5729.8  577.12  5738.1  579.04  5766.2  579.91  6016.2  585.22
#Mann=7,-1,0
  4143.0    0.16       0  4227.1    0.05       0  4627.1    0.16       0
  4819.4    0.12       0  4998.5    0.07       0  5005.0    0.12       0
  5240.4    0.05       0
Bank Sta=4652.9,5286.3
Exp/Cntr=0.3,0.1

Type RM Length L Ch R = 1,29907,1154,1154,1154
BEGIN DESCRIPTION:
EAST FORK TURKEY CREEK 44.0
END DESCRIPTION:
XS GIS Cut Line= 3
      2780472.94      7096107.80      2779875.00      7095975.00
      2779225.02      7095575.01
#Sta/Elev= 30
  4394.3  573.76  4503.7  571.98  4556.1  569.55  4597.1  569.59  4657.1  564.78
  4735.6  563.40  4840.1  562.47  4924.9  562.51  4955.6  560.14  4976.1  562.52
  4982.5  558.85  4987.6  557.67  4993.3  554.72  4993.8  553.92  4999.4  553.92
  4999.9  554.72  5004.2  560.55  5009.7  560.55  5014.5  561.98  5136.3  561.99
  5159.5  561.36  5173.0  558.04  5188.4  561.93  5262.0  563.68  5305.3  562.42
  5400.4  563.40  5515.0  567.89  5734.8  572.29  5762.3  575.97  5770.0  575.47
#Mann=7,-1,0
  4394.3    0.05       0  4503.7    0.16       0  4840.1    0.12       0
  4993.3    0.07       0  4999.9    0.12       0  5262.0    0.16       0
  5305.3    0.05       0
Bank Sta=4735.6,5400.4
Exp/Cntr=0.3,0.1

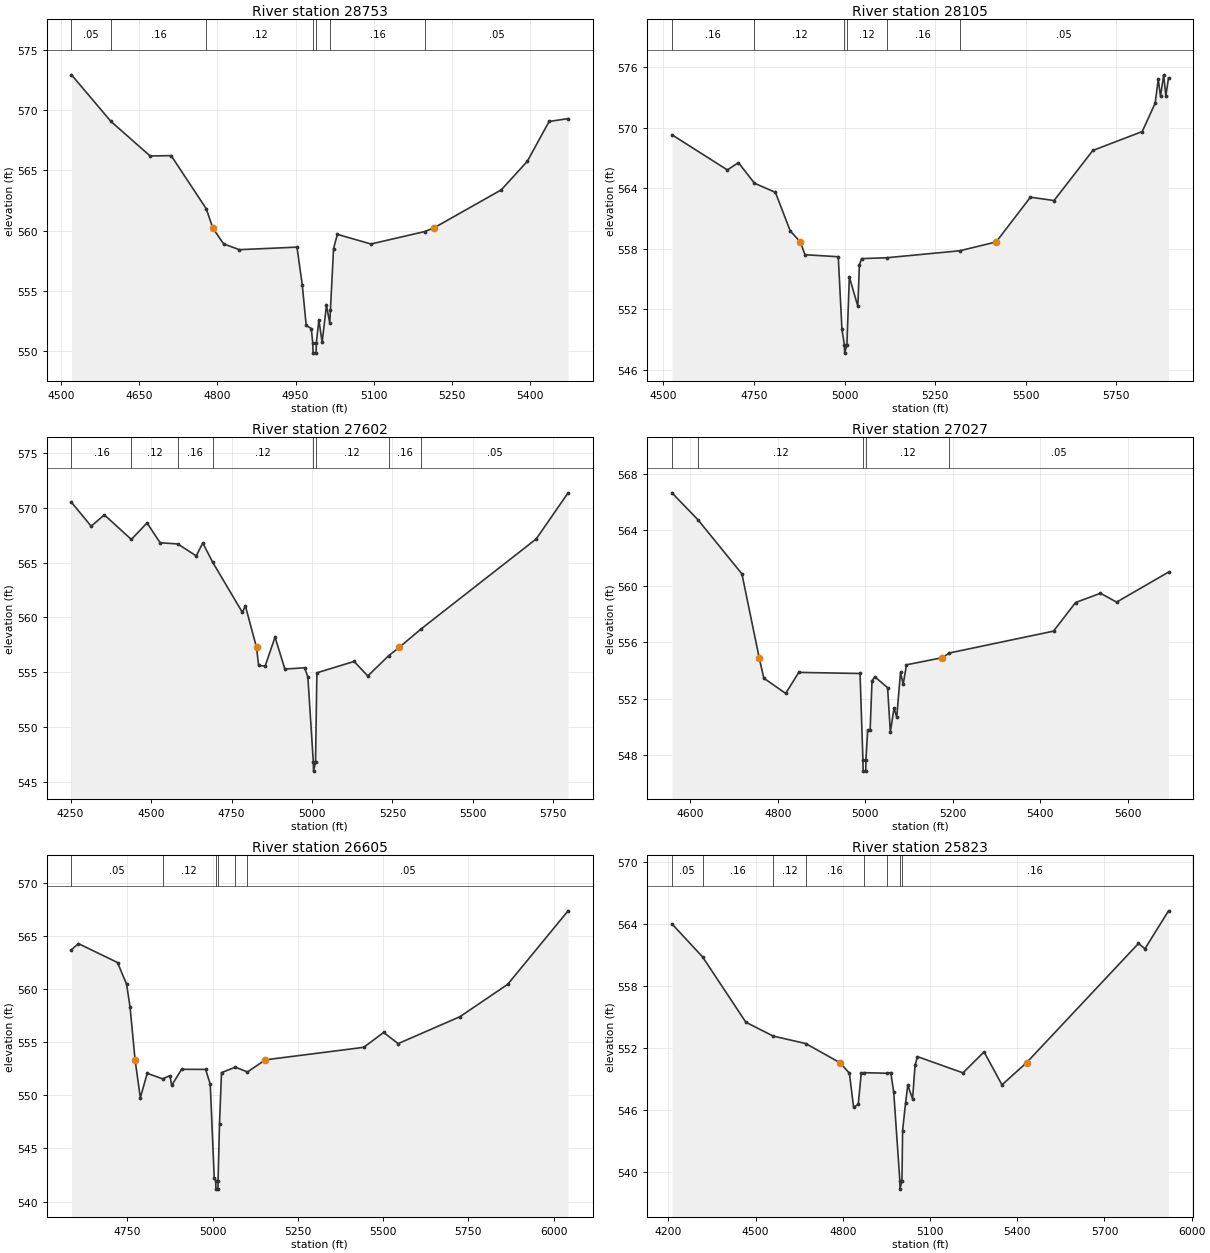
Type RM Length L Ch R = 1,28753,648,648,648
BEGIN DESCRIPTION:
EAST FORK TURKEY CREEK 43.0
END DESCRIPTION:
XS GIS Cut Line= 3
      2780325.00      7095175.00      2779875.00      7095225.00
      2779474.97      7095525.02
#Sta/Elev= 30
  4520.0  572.93  4595.6  569.07  4670.9  566.20  4711.2  566.23  4778.6  561.82
  4791.2  560.22  4811.8  558.91  4842.0  558.43  4952.6  558.64  4962.7  555.54
  4970.3  552.15  4980.1  551.89  4983.0  550.65  4983.5  549.85  4989.2  549.85
  4989.7  550.65  4994.6  552.61  5000.9  550.75  5009.2  553.81  5015.5  552.34
  5016.8  553.44  5022.8  558.52  5030.1  559.70  5094.6  558.90  5197.4  559.93
  5214.8  560.22  5344.6  563.39  5394.6  565.76  5436.3  569.06  5472.8  569.30
#Mann=7,-1,0
  4520.0    0.05       0  4595.6    0.16       0  4778.6    0.12       0
  4983.0    0.07       0  4989.7    0.12       0  5016.8    0.16       0
  5197.4    0.05       0
Bank Sta=4791.2,5214.8
Exp/Cntr=0.3,0.1

Type RM Length L Ch R = 1,28105,503,503,503
BEGIN DESCRIPTION:
EAST FORK TURKEY CREEK 42.0
END DESCRIPTION:
XS GIS Cut Line= 3
      2780124.96      7094675.01      2779625.00      7094775.00
      2779125.00      7095475.00
#Sta/Elev= 30
  4523.8  569.32  4676.7  565.83  4707.3  566.55  4751.5  564.51  4809.3  563.60
  4850.1  559.78  4877.9  558.68  4890.9  557.41  4982.7  557.21  4992.9  550.00
  4999.7  548.44  5000.2  547.64  5006.5  548.44  5013.3  555.20  5036.7  552.29
  5041.0  556.41  5047.2  557.02  5116.3  557.11  5317.7  557.80  5418.3  558.68
  5512.9  563.12  5578.1  562.79  5685.0  567.76  5821.4  569.64  5857.0  572.45
  5865.6  574.84  5871.8  573.13  5880.4  575.27  5886.5  573.19  5893.9  574.97
#Mann=6,-1,0
  4523.8    0.16       0  4751.5    0.12       0  4999.7    0.07       0
  5006.5    0.12       0  5116.3    0.16       0  5317.7    0.05       0
Bank Sta=4877.9,5418.3
Exp/Cntr=0.3,0.1

Type RM Length L Ch R = 1,27602,575,575,575
BEGIN DESCRIPTION:
EAST FORK TURKEY CREEK 41.0
END DESCRIPTION:
XS GIS Cut Line= 3
      2780125.01      7094575.00      2779375.00      7094425.00
      2778824.99      7094975.01
#Sta/Elev= 30
  4252.9  570.51  4314.1  568.33  4354.9  569.37  4438.8  567.12  4487.5  568.63
  4528.3  566.82  4583.2  566.71  4640.4  565.62  4660.8  566.80  4691.3  565.05
  4783.2  560.49  4793.4  561.02  4827.7  557.26  4834.2  555.61  4854.6  555.56
  4885.2  558.20  4915.8  555.28  4977.0  555.40  4987.2  554.57  5004.2  546.76
  5004.7  545.96  5011.0  546.76  5015.2  554.94  5130.9  555.98  5173.3  554.65
  5238.1  556.50  5270.9  557.26  5339.5  558.96  5696.6  567.17  5795.6  571.38
#Mann=8,-1,0
  4252.9    0.16       0  4438.8    0.12       0  4583.2    0.16       0
  4691.3    0.12       0  5004.2    0.07       0  5011.0    0.12       0
  5238.1    0.16       0  5339.5    0.05       0
Bank Sta=4827.7,5270.9
Exp/Cntr=0.3,0.1

Type RM Length L Ch R = 1,27027,422,422,422
BEGIN DESCRIPTION:
EAST FORK TURKEY CREEK 40.0
END DESCRIPTION:
XS GIS Cut Line= 3
      2779675.04      7094075.00      2779225.00      7094075.00
      2778668.67      7094474.93
#Sta/Elev= 30
  4557.8  566.67  4617.3  564.75  4717.8  560.89  4757.2  554.92  4767.8  553.46
  4817.8  552.37  4847.8  553.87  4987.8  553.79  4994.4  547.63  4994.9  546.83
  5000.8  546.83  5001.3  547.63  5005.3  549.77  5010.9  549.77  5015.2  553.27
  5021.4  553.56  5050.8  552.78  5057.1  549.61  5065.5  551.32  5071.7  550.68
  5080.3  553.87  5086.4  553.02  5094.0  554.41  5176.1  554.92  5191.6  555.25
  5430.1  556.81  5480.5  558.85  5537.4  559.51  5574.4  558.88  5693.0  561.02
#Mann=5,-1,0
  4557.8    0.05       0  4617.3    0.12       0  4994.4    0.07       0
  5001.3    0.12       0  5191.6    0.05       0
Bank Sta=4757.2,5176.1
Exp/Cntr=0.3,0.1

Type RM Length L Ch R = 1,26605,782,782,782
BEGIN DESCRIPTION:
EAST FORK TURKEY CREEK 39.0
END DESCRIPTION:
XS GIS Cut Line= 3
      2779635.27      7093672.90      2779231.63      7093724.99
      2778333.22      7094267.51
#Sta/Elev= 30
  4585.8  563.73  4606.2  564.30  4720.8  562.52  4747.4  560.47  4757.5  558.34
  4772.3  553.35  4787.7  549.78  4807.9  552.08  4853.2  551.56  4874.6  551.86
  4879.6  550.94  4908.7  552.46  4979.3  552.45  4992.8  551.04  5004.4  542.26
  5008.8  541.97  5009.3  541.17  5015.2  541.17  5015.7  541.97  5019.9  547.34
  5025.8  552.15  5066.5  552.66  5102.0  552.21  5154.2  553.35  5443.0  554.53
  5501.2  555.93  5543.9  554.88  5724.8  557.41  5865.0  560.46  6042.3  567.39
#Mann=6,-1,0
  4585.8    0.05       0  4853.2    0.12       0  5008.8    0.07       0
  5015.7    0.12       0  5066.5    0.16       0  5102.0    0.05       0
Bank Sta=4772.3,5154.2
Exp/Cntr=0.3,0.1

Type RM Length L Ch R = 1,25823,675,675,675
BEGIN DESCRIPTION:
EAST FORK TURKEY CREEK 38.0
END DESCRIPTION:
XS GIS Cut Line= 3
      2779725.00      7093025.00      2778925.00      7093175.00
      2778124.98      7093575.01
#Sta/Elev= 30
  4212.0  564.05  4317.4  560.85  4466.4  554.52  4560.4  553.18  4672.1  552.46
  4790.2  550.60  4822.5  549.59  4836.9  546.29  4853.0  546.57  4863.2  549.56
  4871.1  549.64  4952.4  549.58  4964.9  549.65  4975.1  547.73  4996.1  539.16
  4996.6  538.36  5003.3  539.16  5005.6  544.03  5015.8  546.72  5023.4  548.43
  5039.9  547.10  5048.3  550.34  5056.7  551.19  5213.2  549.62  5285.9  551.65
  5347.4  548.46  5431.8  550.60  5817.0  562.15  5839.3  561.64  5920.4  565.31
#Mann=8,-1,0
  4212.0    0.05       0  4317.4    0.16       0  4560.4    0.12       0
  4672.1    0.16       0  4871.1    0.12       0  4952.4    0.16       0
  4996.1    0.07       0  5003.3    0.16       0
Bank Sta=4790.2,5431.8
Exp/Cntr=0.3,0.1

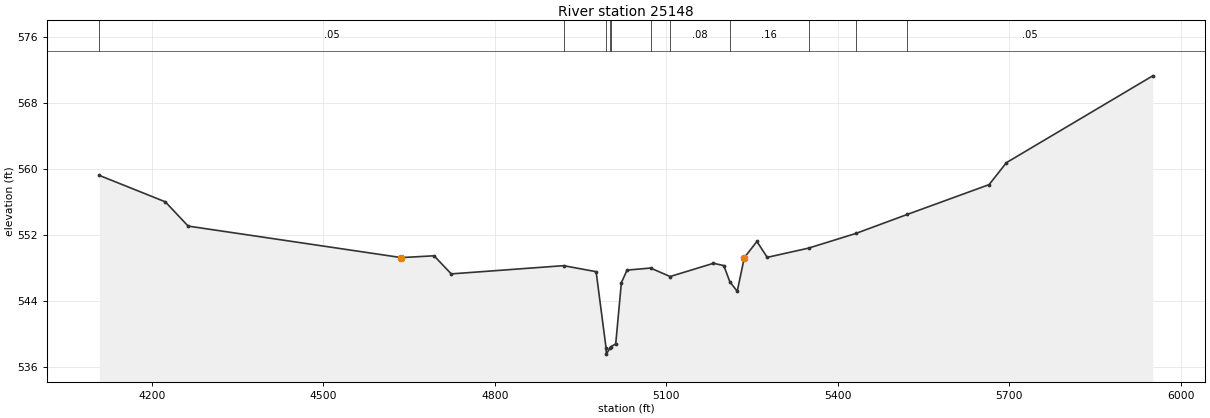
Type RM Length L Ch R = 1,25148,140,140,140
BEGIN DESCRIPTION:
Mapping XS 1cffce01
END DESCRIPTION:
XS GIS Cut Line= 6
      2779510.30      7092711.10      2778690.83      7092679.85
      2778621.39      7092707.62      2778482.50      7093051.37
      2778423.47      7093120.82      2777940.85      7093179.84
#Sta/Elev= 30
  4107.8  559.24  4223.2  556.03  4263.2  553.08  4636.2  549.25  4693.5  549.47
  4723.5  547.27  4920.0  548.27  4977.0  547.54  4994.3  538.32  4994.9  537.52
  5001.7  538.32  5003.3  538.44  5011.3  538.77  5021.2  546.20  5031.1  547.73
  5072.3  547.98  5106.5  546.95  5182.3  548.56  5200.4  548.28  5211.0  546.31
  5223.9  545.16  5236.3  549.25  5258.3  551.21  5276.4  549.28  5348.6  550.40
  5431.2  552.18  5521.6  554.50  5664.6  558.12  5694.9  560.79  5950.9  571.34
#Mann=11,-1,0
  4107.8    0.05       0  4920.0    0.08       0  4994.3    0.07       0
  5001.7    0.08       0  5003.3    0.12       0  5072.3    0.05       0
  5106.5    0.08       0  5211.0    0.16       0  5348.6    0.05       0
  5431.2    0.16       0  5521.6    0.05       0
Bank Sta=4636.2,5236.3
Exp/Cntr=0.3,0.1