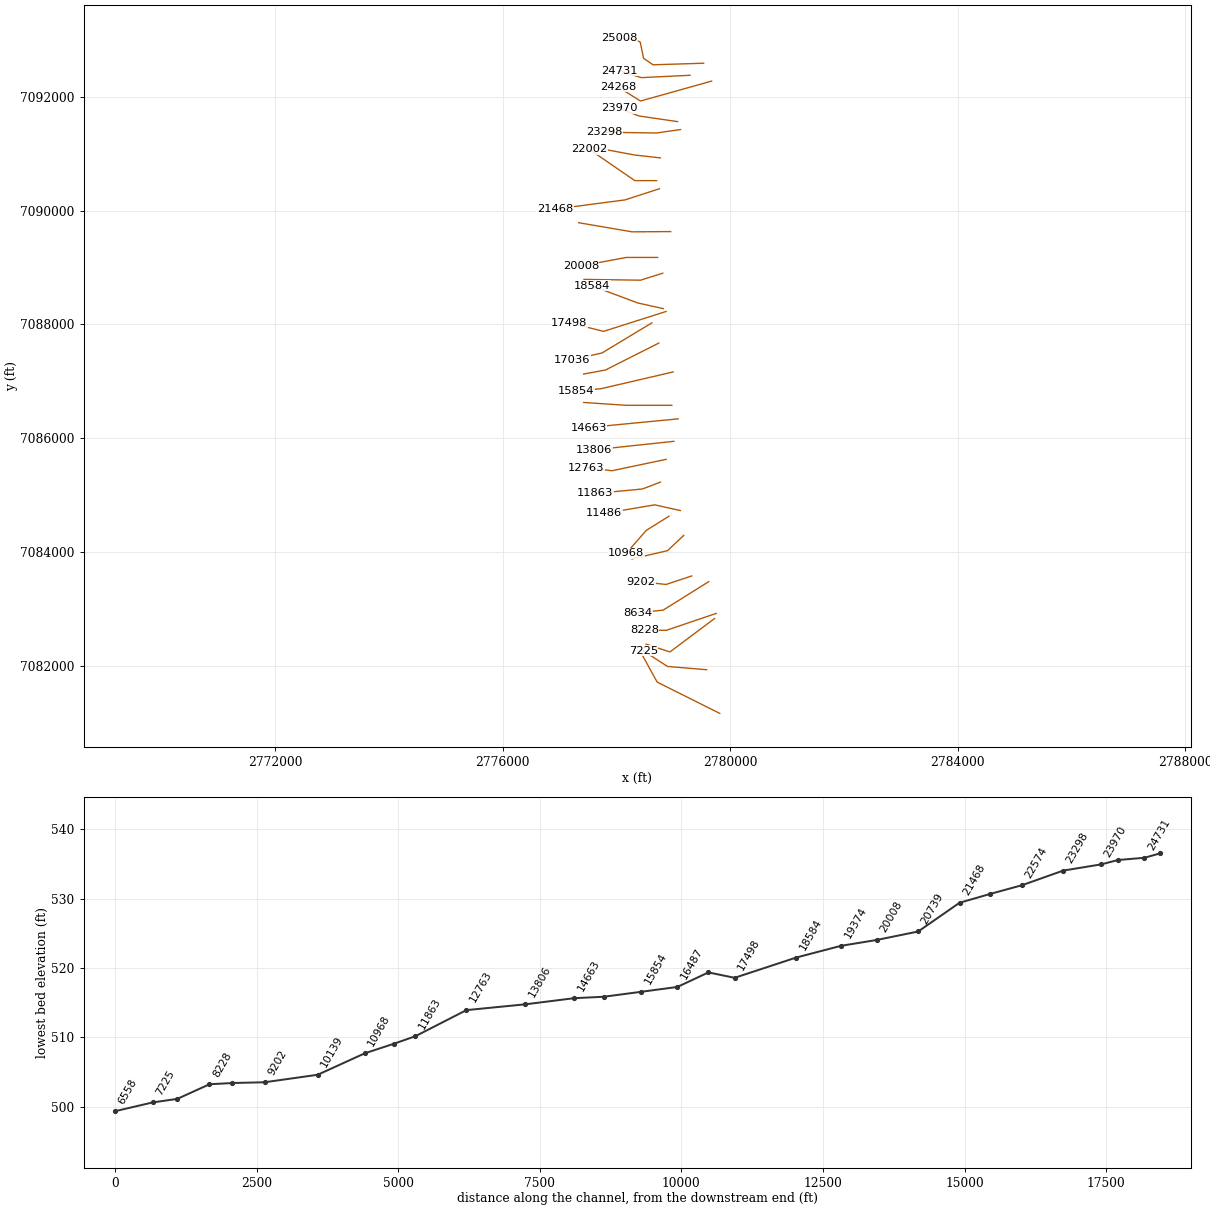
HEC-RAS study EAST FORK TURKEY CREEK.prj: EAST FORK TURKEY CREEK Base Level Engineering

--- EAST FORK TURKEY CREEK.g01 (geometry) --- (continued)

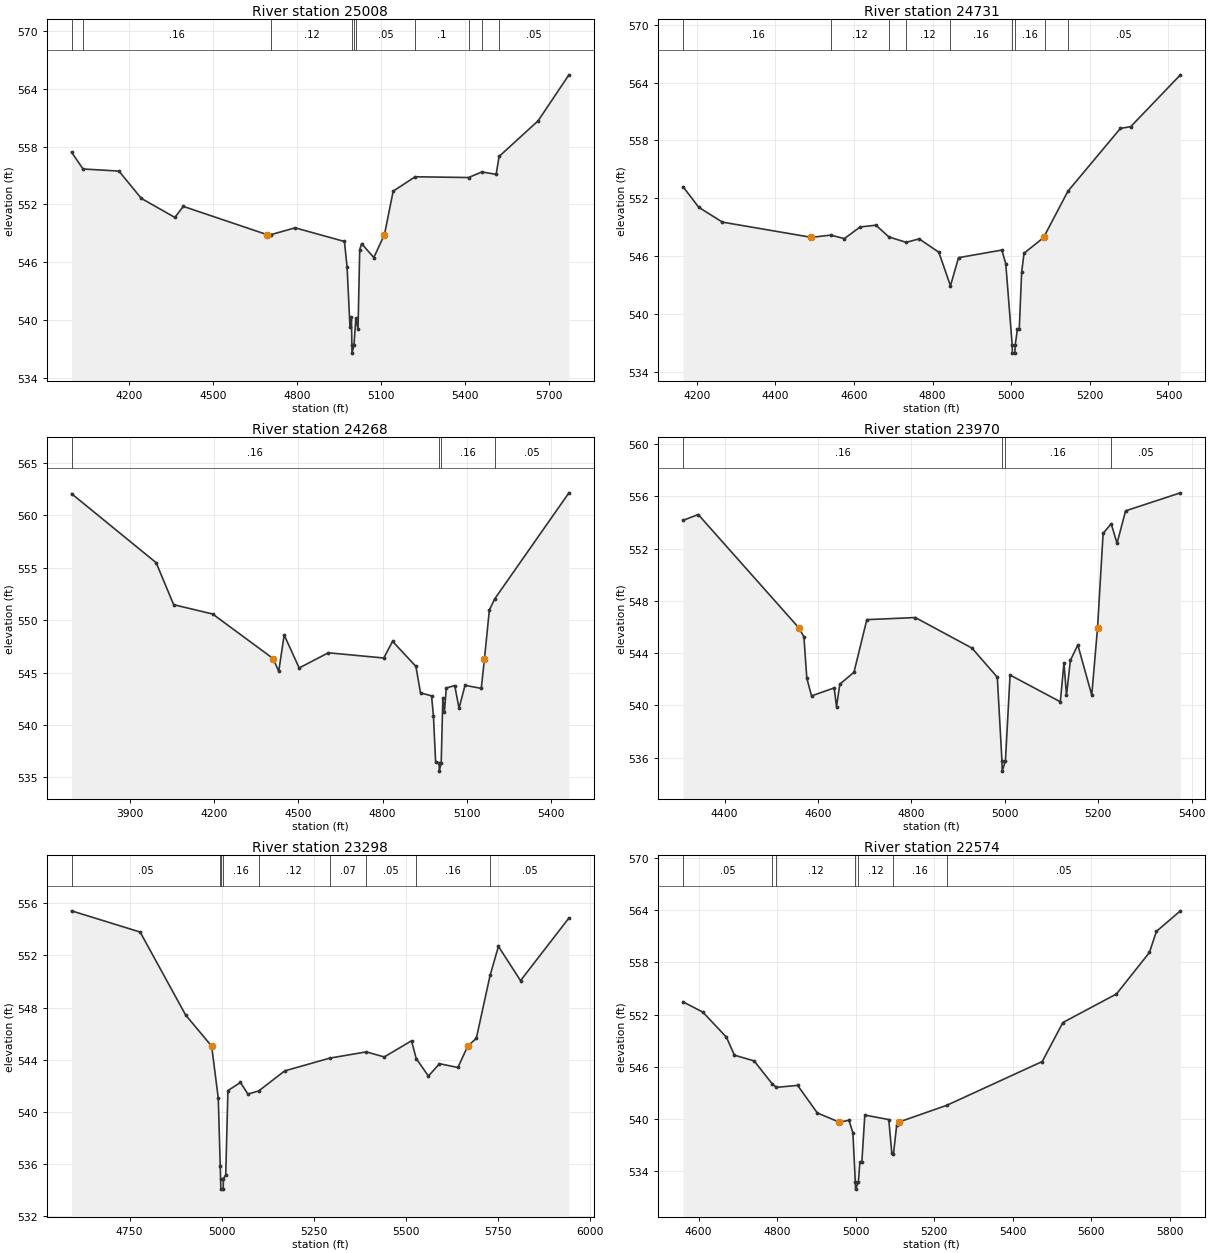
Type RM Length L Ch R = 1,25008,277,277,277
BEGIN DESCRIPTION:
Mapping XS 5dbac837
END DESCRIPTION:
XS GIS Cut Line= 6
      2779534.55      7092589.57      2778645.69      7092561.79
      2778479.02      7092676.37      2778420.00      7092961.10
      2778315.83      7093013.18      2778045.05      7093027.07
#Sta/Elev= 30
  3993.8  557.44  4034.9  555.69  4163.4  555.47  4243.5  552.63  4363.5  550.65
  4393.5  551.80  4692.3  548.87  4707.0  548.86  4793.7  549.57  4970.0  548.15
  4979.6  545.46  4989.9  539.21  4995.2  540.26  4996.6  537.34  4997.1  536.54
  5004.0  537.34  5010.8  540.18  5018.6  539.04  5024.7  547.31  5031.5  547.92
  5075.1  546.48  5113.2  548.87  5144.3  553.38  5223.0  554.88  5413.8  554.80
  5461.8  555.38  5512.7  555.13  5523.2  556.99  5662.9  560.70  5773.0  565.48
#Mann=10,-1,0
  3993.8    0.05       0  4034.9    0.16       0  4707.0    0.12       0
  4996.6    0.07       0  5004.0    0.12       0  5010.8    0.05       0
  5223.0     0.1       0  5413.8    0.05       0  5461.8    0.08       0
  5523.2    0.05       0
Bank Sta=4692.3,5113.2
Exp/Cntr=0.3,0.1

Type RM Length L Ch R = 1,24731,463,463,463
BEGIN DESCRIPTION:
Mapping XS f5b7b352
END DESCRIPTION:
XS GIS Cut Line= 3
      2779294.97      7092377.76      2778440.83      7092336.10
      2778049.24      7092457.39
#Sta/Elev= 30
  4165.3  553.19  4205.3  551.05  4265.4  549.51  4491.7  547.93  4540.7  548.16
  4575.8  547.80  4615.8  549.01  4655.9  549.19  4689.0  547.97  4733.0  547.41
  4766.0  547.77  4816.0  546.38  4845.5  542.90  4866.1  545.82  4976.2  546.61
  4986.2  545.19  5002.6  536.71  5003.1  535.91  5009.4  535.91  5010.0  536.71
  5015.9  538.40  5020.5  538.40  5026.6  544.32  5032.7  546.28  5083.2  547.93
  5086.2  548.21  5144.3  552.72  5277.8  559.24  5304.0  559.42  5430.4  564.80
#Mann=9,-1,0
  4165.3    0.16       0  4540.7    0.12       0  4689.0    0.16       0
  4733.0    0.12       0  4845.5    0.16       0  5002.6    0.07       0
  5010.0    0.16       0  5086.2    0.12       0  5144.3    0.05       0
Bank Sta=4491.7,5083.2
Exp/Cntr=0.3,0.1

Type RM Length L Ch R = 1,24268,298,298,298
BEGIN DESCRIPTION:
EAST FORK TURKEY CREEK 35.0
END DESCRIPTION:
XS GIS Cut Line= 3
      2779674.99      7092275.00      2778425.00      7091925.00
      2778024.97      7092175.02
#Sta/Elev= 30
  3692.9  562.08  3994.0  555.49  4056.3  551.48  4195.1  550.59  4410.0  546.34
  4430.2  545.12  4449.5  548.59  4502.9  545.44  4606.7  546.89  4804.0  546.39
  4835.2  547.98  4918.3  545.59  4934.6  543.06  4973.9  542.78  4980.6  540.89
  4988.4  536.48  5000.8  536.39  5001.4  535.59  5008.3  536.39  5014.0  542.56
  5019.9  541.28  5026.3  543.53  5056.4  543.76  5071.7  541.59  5093.0  543.78
  5150.8  543.49  5162.3  546.34  5179.6  550.97  5198.5  552.03  5462.7  562.16
#Mann=4,-1,0
  3692.9    0.16       0  5000.8    0.07       0  5008.3    0.16       0
  5198.5    0.05       0
Bank Sta=4410,5162.3
Exp/Cntr=0.3,0.1

Type RM Length L Ch R = 1,23970,672,672,672
BEGIN DESCRIPTION:
EAST FORK TURKEY CREEK 34.0
END DESCRIPTION:
XS GIS Cut Line= 3
      2779077.16      7091562.65      2778395.69      7091662.49
      2778045.84      7091800.70
#Sta/Elev= 30
  4311.1  554.16  4343.6  554.61  4558.9  545.94  4569.9  545.25  4576.1  542.09
  4586.2  540.72  4634.7  541.33  4639.7  539.89  4646.8  541.62  4677.1  542.53
  4704.6  546.56  4808.5  546.72  4929.8  544.38  4984.0  542.15  4993.9  535.76
  4994.5  534.96  5001.4  535.76  5011.3  542.32  5118.9  540.27  5126.7  543.26
  5132.1  540.76  5140.4  543.44  5156.4  544.62  5186.2  540.78  5198.6  545.94
  5210.5  553.17  5227.9  553.90  5240.3  552.40  5258.6  554.89  5376.0  556.27
#Mann=4,-1,0
  4311.1    0.16       0  4993.9    0.07       0  5001.4    0.16       0
  5227.9    0.05       0
Bank Sta=4558.9,5198.6
Exp/Cntr=0.3,0.1

Type RM Length L Ch R = 1,23298,724,724,724
BEGIN DESCRIPTION:
Mapping XS e029e559
END DESCRIPTION:
XS GIS Cut Line= 3
      2779129.25      7091423.78      2778708.19      7091363.01
      2777783.70      7091376.03
#Sta/Elev= 30
  4592.2  555.43  4778.4  553.80  4901.7  547.44  4972.5  545.04  4990.5  541.04
  4995.8  535.84  4996.8  534.86  4997.4  534.06  5003.8  534.06  5004.4  534.86
  5010.7  535.16  5016.7  541.63  5050.8  542.25  5070.8  541.36  5100.2  541.60
  5170.8  543.14  5293.3  544.12  5392.4  544.60  5440.9  544.21  5515.0  545.45
  5527.7  544.09  5560.9  542.74  5590.9  543.69  5640.9  543.40  5667.5  545.04
  5690.9  545.64  5728.2  550.47  5750.9  552.70  5810.9  550.07  5942.2  554.88
#Mann=9,-1,0
  4592.2    0.05       0  4995.8    0.16       0  4996.8    0.07       0
  5004.4    0.16       0  5100.2    0.12       0  5293.3    0.07       0
  5392.4    0.05       0  5527.7    0.16       0  5728.2    0.05       0
Bank Sta=4972.5,5667.5
Exp/Cntr=0.3,0.1

Type RM Length L Ch R = 1,22574,572,572,572
BEGIN DESCRIPTION:
EAST FORK TURKEY CREEK 32.0
END DESCRIPTION:
XS GIS Cut Line= 3
      2778775.04      7090925.00      2778325.00      7090975.00
      2777524.95      7091125.01
#Sta/Elev= 30
  4560.5  553.47  4610.8  552.30  4671.2  549.41  4691.3  547.35  4741.6  546.69
  4787.2  544.08  4798.4  543.65  4852.3  543.88  4902.6  540.71  4958.8  539.65
  4983.1  539.87  4993.2  538.43  4999.3  532.76  5000.0  531.96  5007.1  532.76
  5010.8  535.02  5015.9  535.02  5023.5  540.47  5084.5  539.95  5092.2  536.14
  5096.4  535.98  5104.9  539.38  5109.4  539.65  5232.4  541.59  5475.4  546.62
  5528.0  551.10  5664.5  554.38  5748.4  559.15  5766.2  561.57  5827.3  563.93
#Mann=7,-1,0
  4560.5    0.05       0  4787.2    0.16       0  4798.4    0.12       0
  4999.3    0.07       0  5007.1    0.12       0  5096.4    0.16       0
  5232.4    0.05       0
Bank Sta=4958.8,5109.4
Exp/Cntr=0.3,0.1

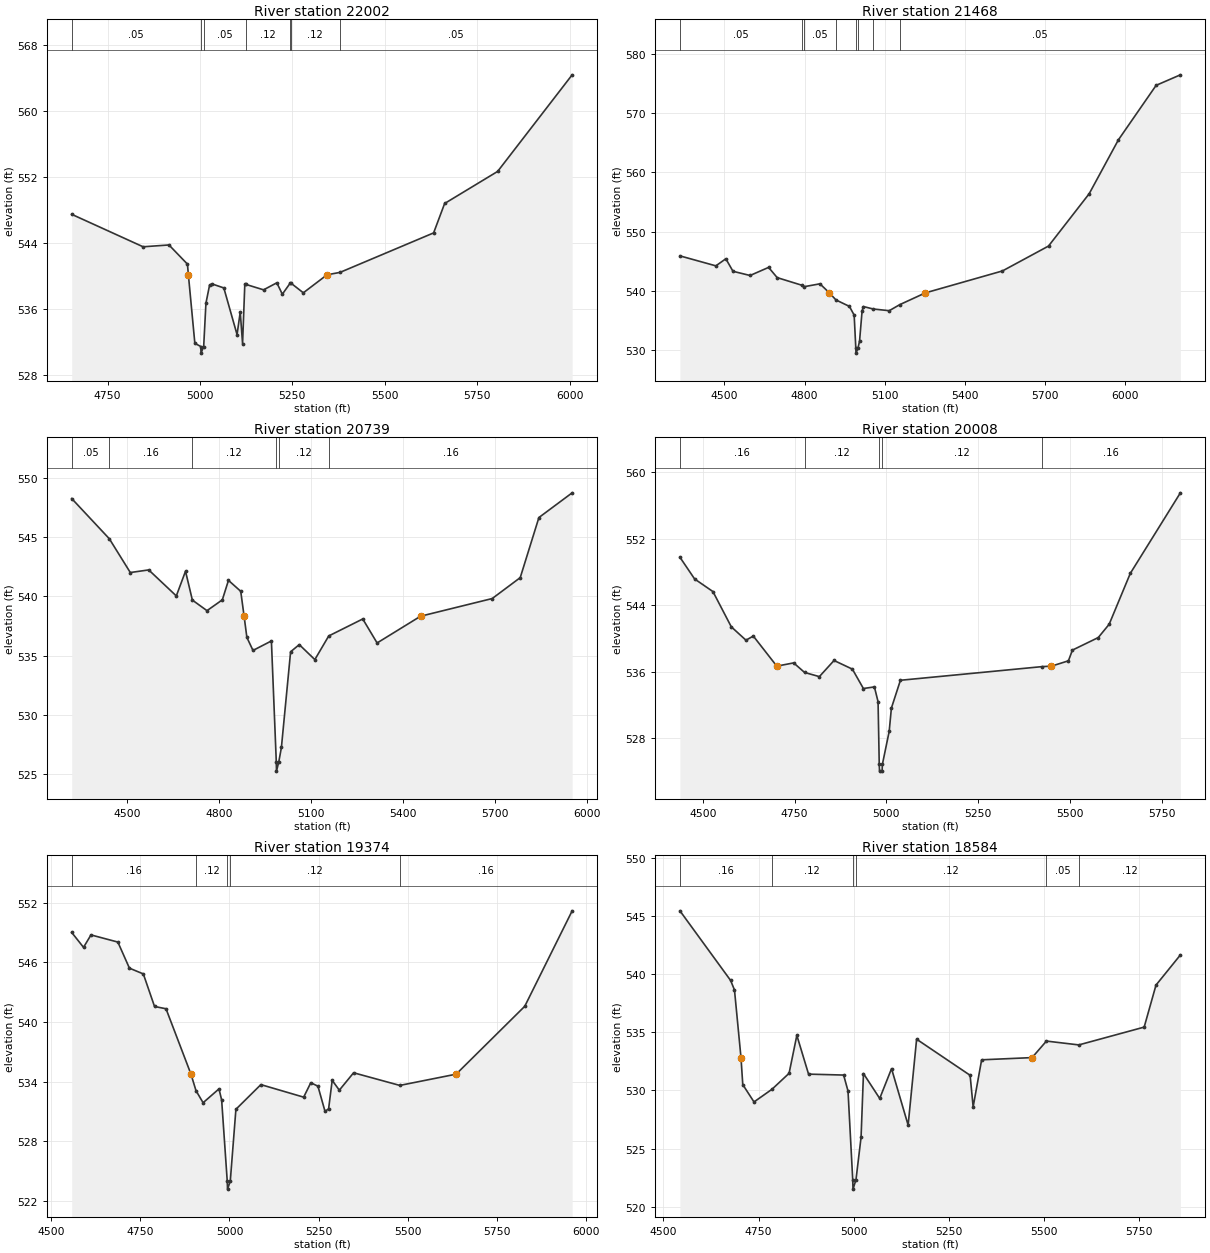
Type RM Length L Ch R = 1,22002,534,534,534
BEGIN DESCRIPTION:
EAST FORK TURKEY CREEK 31.0
END DESCRIPTION:
XS GIS Cut Line= 3
      2778708.16      7090525.33      2778325.00      7090525.00
      2777524.99      7091075.01
#Sta/Elev= 30
  4653.0  547.48  4846.2  543.55  4916.2  543.77  4966.2  541.45  4968.7  540.16
  4986.2  531.87  5002.3  531.48  5002.9  530.68  5010.1  531.48  5016.2  536.72
  5026.2  538.94  5033.7  539.04  5064.6  538.57  5100.4  532.92  5109.0  535.66
  5115.3  531.83  5121.4  539.04  5123.4  539.01  5172.1  538.34  5208.0  539.19
  5222.9  537.81  5244.6  539.18  5245.6  539.17  5279.7  537.98  5343.8  540.16
  5378.9  540.45  5632.2  545.23  5662.0  548.79  5805.4  552.67  6007.0  564.36
#Mann=7,-1,0
  4653.0    0.05       0  5002.3    0.03       0  5010.1    0.05       0
  5123.4    0.12       0  5244.6    0.05       0  5245.6    0.12       0
  5378.9    0.05       0
Bank Sta=4968.7,5343.8
Exp/Cntr=0.3,0.1

Type RM Length L Ch R = 1,21468,729,729,729
BEGIN DESCRIPTION:
EAST FORK TURKEY CREEK 30.0
END DESCRIPTION:
XS GIS Cut Line= 3
      2778755.94      7090382.10      2778152.64      7090186.79
      2776924.98      7090025.00
#Sta/Elev= 30
  4333.6  545.88  4468.1  544.19  4505.4  545.39  4532.1  543.27  4596.1  542.56
  4665.4  543.93  4697.4  542.20  4790.5  540.90  4799.2  540.67  4857.4  541.15
  4892.8  539.62  4917.4  538.42  4967.7  537.33  4985.5  535.85  4991.7  530.22
  4992.3  529.42  4999.5  530.22  5005.7  531.47  5015.2  536.59  5020.3  537.30
  5056.7  536.89  5116.6  536.60  5156.3  537.63  5252.1  539.62  5540.3  543.33
  5712.6  547.54  5864.8  556.40  5974.0  565.51  6115.2  574.74  6206.0  576.52
#Mann=8,-1,0
  4333.6    0.05       0  4790.5    0.12       0  4799.2    0.05       0
  4917.4    0.16       0  4991.7    0.07       0  4999.5    0.16       0
  5056.7    0.12       0  5156.3    0.05       0
Bank Sta=4892.8,5252.1
Exp/Cntr=0.3,0.1

Type RM Length L Ch R = 1,20739,731,731,731
BEGIN DESCRIPTION:
EAST FORK TURKEY CREEK 29.0
END DESCRIPTION:
XS GIS Cut Line= 3
      2778956.13      7089629.46      2778275.00      7089625.00
      2777338.18      7089785.40
#Sta/Elev= 30
  4320.2  548.23  4443.0  544.84  4511.3  542.00  4571.3  542.22  4661.3  540.03
  4691.3  542.11  4713.6  539.68  4761.3  538.79  4811.3  539.70  4831.3  541.34
  4871.3  540.42  4882.3  538.32  4891.3  536.54  4911.3  535.44  4971.3  536.24
  4987.2  526.08  4987.9  525.28  4995.5  526.08  5003.9  527.27  5033.9  535.33
  5062.2  535.93  5112.9  534.67  5158.2  536.66  5269.1  538.09  5315.9  536.07
  5457.4  538.32  5691.2  539.81  5782.5  541.57  5843.4  546.63  5951.8  548.71
#Mann=6,-1,0
  4320.2    0.05       0  4443.0    0.16       0  4713.6    0.12       0
  4987.2    0.07       0  4995.5    0.12       0  5158.2    0.16       0
Bank Sta=4882.3,5457.4
Exp/Cntr=0.3,0.1

Type RM Length L Ch R = 1,20008,634,634,634
BEGIN DESCRIPTION:
EAST FORK TURKEY CREEK 28.0
END DESCRIPTION:
XS GIS Cut Line= 3
      2778724.99      7089175.00      2778175.00      7089175.00
      2777375.03      7089025.01
#Sta/Elev= 30
  4437.4  549.79  4477.4  547.18  4527.4  545.66  4577.4  541.42  4617.4  539.81
  4637.4  540.31  4701.4  536.69  4747.4  537.08  4777.1  535.93  4817.4  535.43
  4857.4  537.37  4907.4  536.33  4937.4  534.00  4967.4  534.19  4977.4  532.41
  4980.6  524.86  4981.4  524.06  4988.4  524.06  4989.1  524.86  5007.7  528.84
  5013.7  531.64  5038.3  534.99  5423.9  536.63  5450.0  536.69  5496.1  537.33
  5507.1  538.62  5577.5  540.13  5607.2  541.73  5664.8  547.85  5801.3  557.54
#Mann=5,-1,0
  4437.4    0.16       0  4777.1    0.12       0  4980.6    0.07       0
  4989.1    0.12       0  5423.9    0.16       0
Bank Sta=4701.4,5450
Exp/Cntr=0.3,0.1

Type RM Length L Ch R = 1,19374,790,790,790
BEGIN DESCRIPTION:
EAST FORK TURKEY CREEK 27.0
END DESCRIPTION:
XS GIS Cut Line= 3
      2778816.68      7088897.72      2778425.00      7088775.00
      2777432.15      7088789.22
#Sta/Elev= 30
  4557.5  549.00  4590.7  547.50  4611.6  548.75  4687.0  548.03  4719.4  545.41
  4758.4  544.83  4789.8  541.56  4822.0  541.33  4892.0  534.76  4906.1  533.10
  4926.0  531.89  4970.5  533.28  4978.0  532.17  4993.7  524.01  4994.5  523.21
  5002.2  524.01  5018.0  531.23  5088.0  533.71  5208.0  532.45  5228.0  533.90
  5248.0  533.55  5268.0  531.01  5278.0  531.29  5288.0  534.14  5308.0  533.15
  5348.0  534.90  5477.6  533.63  5635.6  534.76  5828.0  541.58  5960.9  551.17
#Mann=5,-1,0
  4557.5    0.16       0  4906.1    0.12       0  4993.7    0.07       0
  5002.2    0.12       0  5477.6    0.16       0
Bank Sta=4892,5635.6
Exp/Cntr=0.3,0.1

Type RM Length L Ch R = 1,18584,1086,1086,1086
BEGIN DESCRIPTION:
EAST FORK TURKEY CREEK 26.0
END DESCRIPTION:
XS GIS Cut Line= 3
      2778825.02      7088275.00      2778375.00      7088375.00
      2777575.00      7088675.00
#Sta/Elev= 30
  4543.2  545.43  4676.4  539.45  4686.6  538.63  4703.7  532.82  4708.4  530.50
  4737.9  529.01  4785.2  530.10  4830.1  531.47  4850.5  534.73  4881.3  531.40
  4973.5  531.32  4985.0  529.95  4997.4  522.32  4998.1  521.52  5005.9  522.32
  5019.3  525.97  5025.6  531.45  5068.3  529.31  5099.4  531.87  5143.0  527.02
  5165.3  534.40  5305.9  531.30  5313.9  528.59  5336.2  532.63  5468.8  532.82
  5506.5  534.24  5591.6  533.91  5763.4  535.44  5794.5  539.05  5858.6  541.64
#Mann=6,-1,0
  4543.2    0.16       0  4785.2    0.12       0  4997.4    0.07       0
  5005.9    0.12       0  5506.5    0.05       0  5591.6    0.12       0
Bank Sta=4703.7,5468.8
Exp/Cntr=0.3,0.1

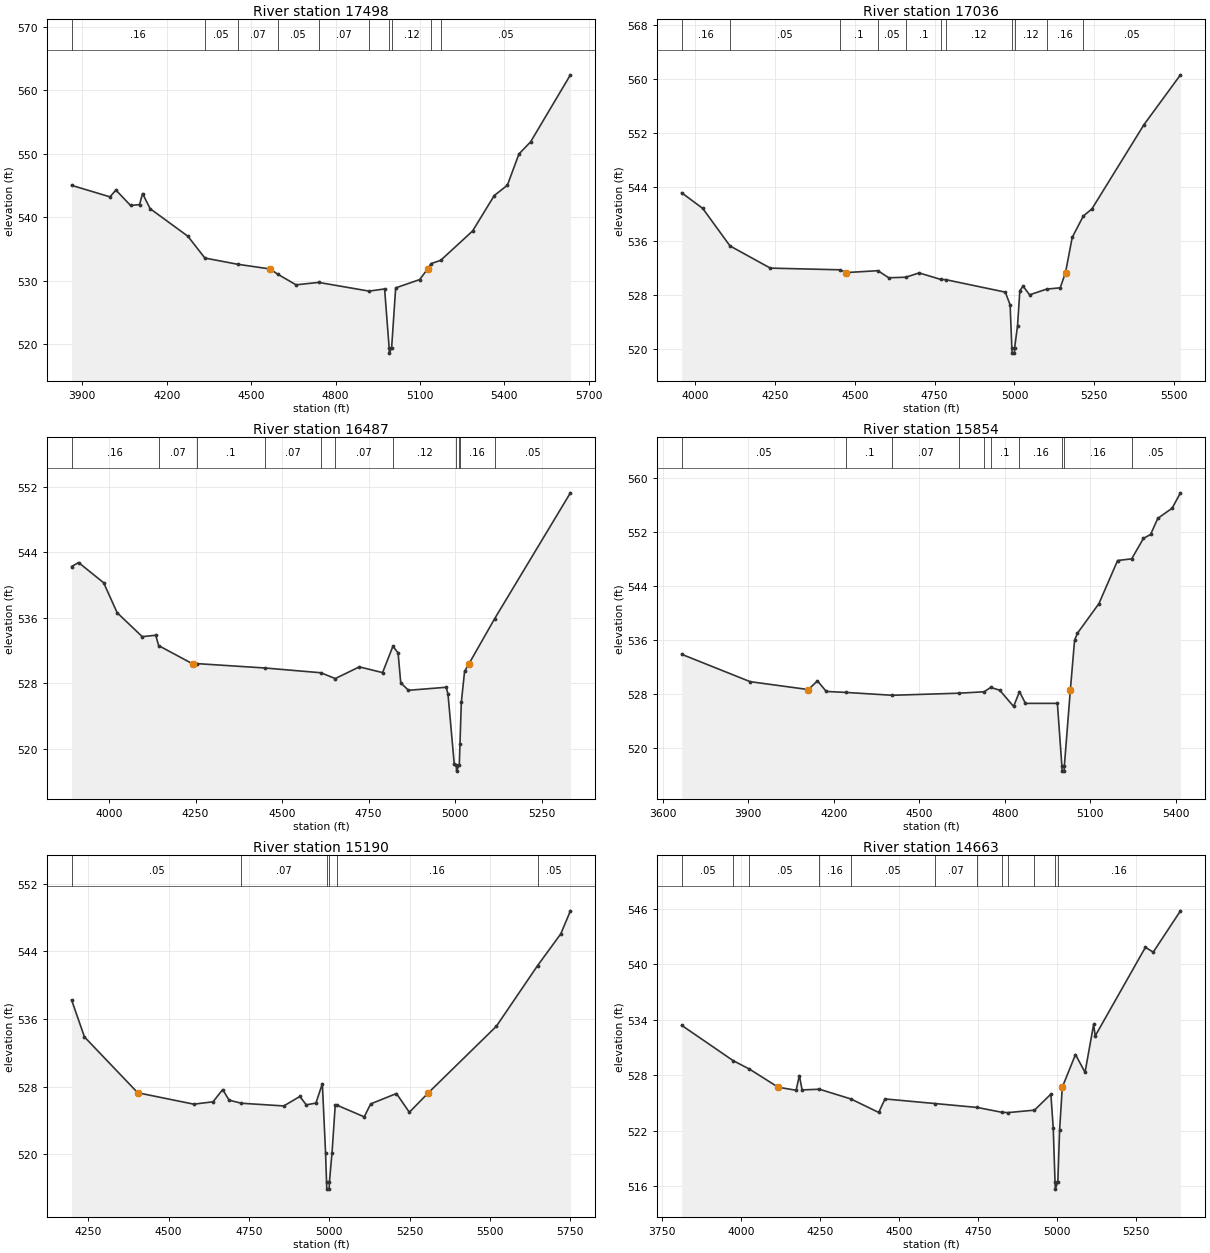
Type RM Length L Ch R = 1,17498,462,462,462
BEGIN DESCRIPTION:
EAST FORK TURKEY CREEK 25.0
END DESCRIPTION:
XS GIS Cut Line= 3
      2778875.01      7088225.00      2777775.00      7087875.00
      2777175.01      7088025.00
#Sta/Elev= 30
  3862.0  545.03  3998.4  543.22  4019.4  544.29  4071.5  541.86  4103.4  542.00
  4114.2  543.74  4141.2  541.35  4275.4  537.01  4335.6  533.58  4451.9  532.60
  4567.2  531.86  4595.2  531.02  4659.6  529.36  4740.0  529.74  4918.9  528.37
  4974.4  528.71  4990.6  519.40  4991.4  518.60  4999.3  519.40  5013.7  528.88
  5098.8  530.18  5127.3  531.86  5140.0  532.71  5173.5  533.21  5286.9  537.83
  5364.2  543.43  5410.6  545.04  5451.9  549.98  5493.1  551.87  5634.8  562.44
#Mann=10,-1,0
  3862.0    0.16       0  4335.6    0.05       0  4451.9    0.07       0
  4595.2    0.05       0  4740.0    0.07       0  4918.9    0.12       0
  4990.6    0.07       0  4999.3    0.12       0  5140.0    0.16       0
  5173.5    0.05       0
Bank Sta=4567.2,5127.3
Exp/Cntr=0.3,0.1

Type RM Length L Ch R = 1,17036,549,549,549
BEGIN DESCRIPTION:
EAST FORK TURKEY CREEK 24.0
END DESCRIPTION:
XS GIS Cut Line= 3
      2778625.03      7088025.02      2777748.99      7087495.82
      2777225.01      7087375.00
#Sta/Elev= 30
  3958.4  543.15  4024.4  540.83  4109.7  535.27  4235.9  531.98  4454.2  531.73
  4473.7  531.32  4572.6  531.60  4606.6  530.55  4659.7  530.63  4701.7  531.27
  4769.5  530.30  4785.0  530.27  4971.4  528.42  4986.5  526.52  4991.8  520.18
  4992.6  519.38  4999.8  519.38  5000.6  520.18  5009.7  523.46  5016.8  528.62
  5027.0  529.32  5047.3  528.02  5100.8  528.87  5143.2  529.06  5159.8  531.32
  5180.8  536.54  5215.5  539.70  5242.5  540.76  5405.0  553.22  5519.6  560.63
#Mann=11,-1,0
  3958.4    0.16       0  4109.7    0.05       0  4454.2     0.1       0
  4572.6    0.05       0  4659.7     0.1       0  4769.5    0.07       0
  4785.0    0.12       0  4991.8    0.07       0  5000.6    0.12       0
  5100.8    0.16       0  5215.5    0.05       0
Bank Sta=4473.7,5159.8
Exp/Cntr=0.3,0.1

Type RM Length L Ch R = 1,16487,633,633,633
BEGIN DESCRIPTION:
EAST FORK TURKEY CREEK 23.0
END DESCRIPTION:
XS GIS Cut Line= 3
      2778747.24      7087669.42      2777809.75      7087196.34
      2777425.00      7087125.00
#Sta/Elev= 30
  3891.8  542.26  3911.9  542.75  3984.4  540.28  4023.4  536.62  4095.9  533.70
  4134.9  533.87  4143.4  532.60  4243.8  530.33  4253.0  530.41  4451.0  529.87
  4612.4  529.29  4653.6  528.58  4723.2  530.01  4790.4  529.31  4820.2  532.52
  4835.2  531.72  4842.9  528.06  4865.2  527.15  4974.4  527.52  4979.5  526.65
  4997.6  518.09  5003.3  518.08  5004.1  517.28  5012.1  518.08  5014.0  520.56
  5017.9  525.66  5027.3  529.45  5039.2  530.33  5114.3  535.90  5333.2  551.26
#Mann=11,-1,0
  3891.8    0.16       0  4143.4    0.07       0  4253.0     0.1       0
  4451.0    0.07       0  4612.4     0.1       0  4653.6    0.07       0
  4820.2    0.12       0  5003.3    0.07       0  5012.1    0.12       0
  5014.0    0.16       0  5114.3    0.05       0
Bank Sta=4243.8,5039.2
Exp/Cntr=0.3,0.1

Type RM Length L Ch R = 1,15854,664,664,664
BEGIN DESCRIPTION:
EAST FORK TURKEY CREEK 22.0
END DESCRIPTION:
XS GIS Cut Line= 3
      2778999.03      7087161.63      2777735.94      7086868.40
      2777285.89      7086818.40
#Sta/Elev= 30
  3666.6  533.92  3906.9  529.86  4110.7  528.69  4143.0  529.98  4173.8  528.41
  4244.6  528.26  4405.5  527.84  4640.1  528.15  4727.4  528.36  4750.4  529.00
  4782.0  528.60  4830.8  526.19  4851.5  528.37  4872.4  526.64  4984.4  526.64
  5000.1  517.39  5000.9  516.59  5008.1  516.59  5008.9  517.39  5030.0  528.69
  5044.7  536.00  5054.8  537.05  5130.1  541.44  5195.6  547.83  5244.9  548.08
  5286.2  551.11  5311.2  551.69  5336.5  554.08  5386.8  555.59  5416.1  557.87
#Mann=10,-1,0
  3666.6    0.05       0  4244.6     0.1       0  4405.5    0.07       0
  4640.1     0.1       0  4727.4    0.12       0  4750.4     0.1       0
  4851.5    0.16       0  5000.1    0.07       0  5008.9    0.16       0
  5244.9    0.05       0
Bank Sta=4110.7,5030
Exp/Cntr=0.3,0.1

Type RM Length L Ch R = 1,15190,527,527,527
BEGIN DESCRIPTION:
EAST FORK TURKEY CREEK 21.0
END DESCRIPTION:
XS GIS Cut Line= 3
      2778975.05      7086575.00      2778175.00      7086575.00
      2777425.01      7086625.00
#Sta/Elev= 30
  4198.4  538.24  4238.4  533.87  4404.1  527.27  4578.4  525.92  4638.4  526.20
  4668.4  527.65  4688.4  526.39  4726.7  526.03  4858.4  525.71  4908.4  526.83
  4928.4  525.84  4958.4  526.05  4978.4  528.34  4988.4  520.17  4991.5  516.67
  4992.3  515.87  4999.5  515.87  5000.3  516.67  5008.5  520.17  5018.5  525.82
  5024.0  525.80  5108.7  524.42  5128.7  525.95  5208.9  527.18  5249.0  524.96
  5308.3  527.27  5519.6  535.13  5647.9  542.31  5720.0  546.06  5750.1  548.79
#Mann=6,-1,0
  4198.4    0.05       0  4726.7    0.07       0  4991.5    0.07       0
  5000.3    0.07       0  5024.0    0.16       0  5647.9    0.05       0
Bank Sta=4404.1,5308.3
Exp/Cntr=0.3,0.1

Type RM Length L Ch R = 1,14663,857,857,857
BEGIN DESCRIPTION:
EAST FORK TURKEY CREEK 20.0
END DESCRIPTION:
XS GIS Cut Line= 3
      2779085.77      7086336.96      2777925.00      7086225.00
      2777514.64      7086180.72
#Sta/Elev= 30
  3812.9  533.39  3975.7  529.57  4027.6  528.65  4118.4  526.69  4175.3  526.36
  4185.4  527.95  4194.2  526.40  4249.2  526.47  4348.5  525.42  4436.6  523.96
  4456.6  525.42  4615.8  524.92  4748.5  524.50  4826.1  523.98  4845.0  523.94
  4929.7  524.21  4981.6  525.94  4989.1  522.24  4994.7  516.46  4995.6  515.66
  5003.6  516.46  5009.2  522.07  5017.7  526.69  5059.5  530.23  5089.7  528.30
  5116.9  533.48  5121.9  532.24  5280.8  541.83  5305.6  541.31  5391.8  545.78
#Mann=12,-1,0
  3812.9    0.05       0  3975.7    0.16       0  4027.6    0.05       0
  4249.2    0.16       0  4348.5    0.05       0  4615.8    0.07       0
  4748.5    0.12       0  4826.1    0.07       0  4845.0    0.12       0
  4929.7    0.16       0  4994.7    0.07       0  5003.6    0.16       0
Bank Sta=4118.4,5017.7
Exp/Cntr=0.3,0.1

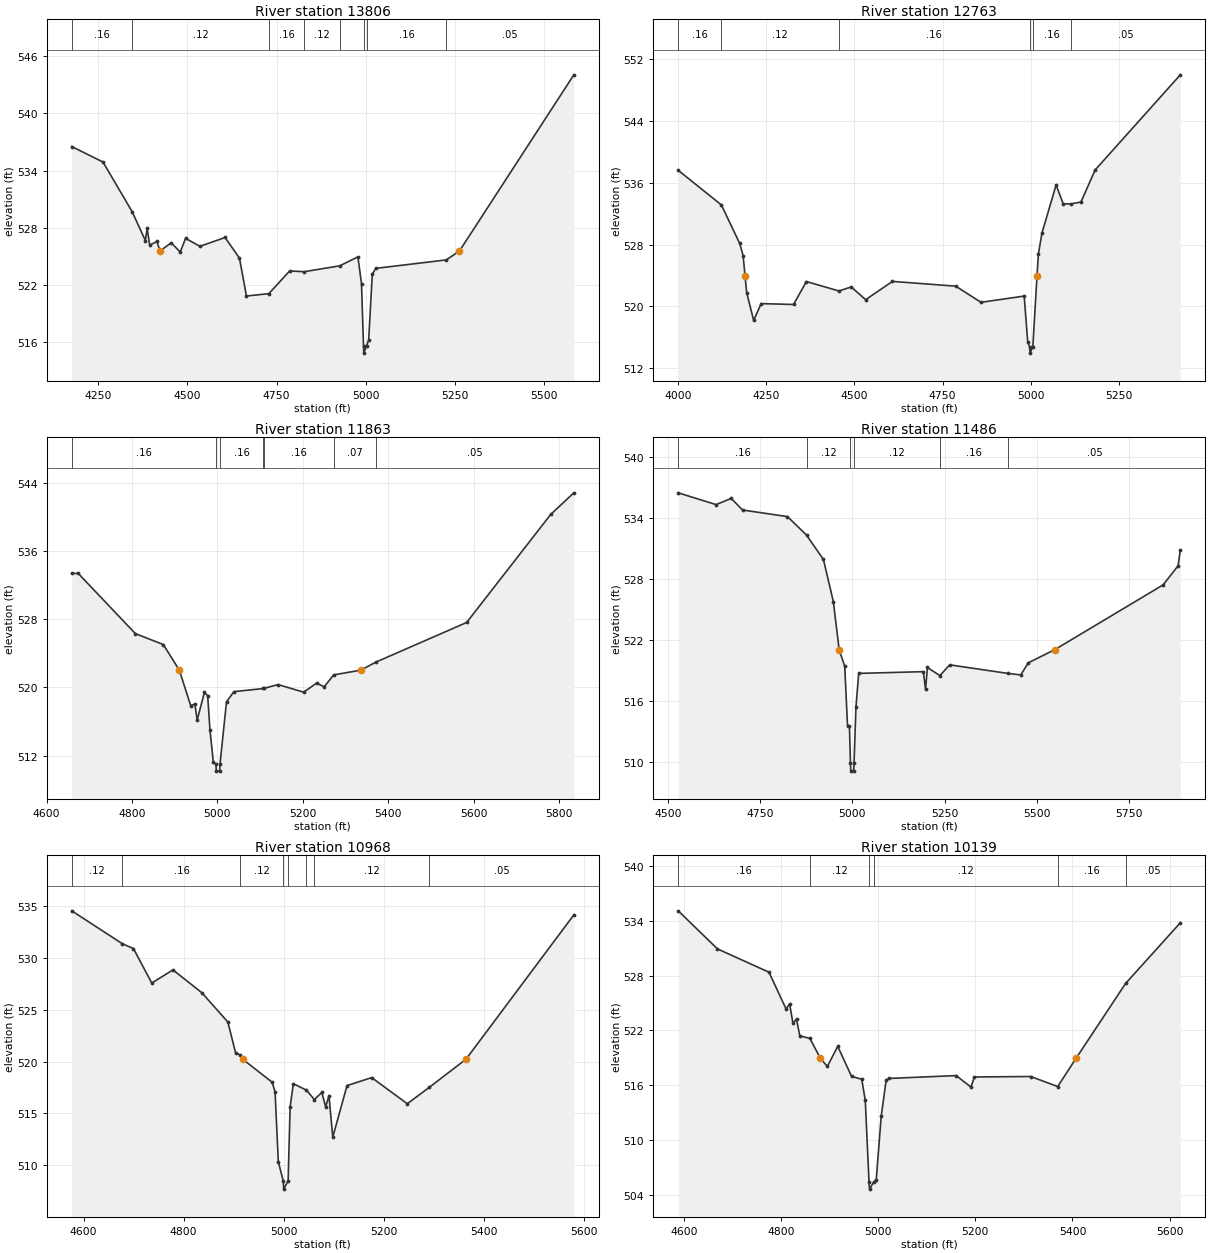
Type RM Length L Ch R = 1,13806,1043,1043,1043
BEGIN DESCRIPTION:
double EAST FORK TURKEY CREEK 19.0
END DESCRIPTION:
XS GIS Cut Line= 3
      2779012.05      7085942.00      2778274.16      7085863.87
      2777613.76      7085791.20
#Sta/Elev= 30
  4176.2  536.52  4263.7  534.89  4345.3  529.67  4382.3  526.63  4387.3  527.91
  4394.5  526.14  4414.6  526.53  4423.4  525.53  4454.8  526.39  4480.0  525.42
  4495.0  526.86  4535.2  526.02  4605.6  526.95  4645.9  524.78  4665.5  520.79
  4728.2  521.04  4786.6  523.43  4827.6  523.35  4927.0  523.97  4977.7  524.91
  4987.8  522.09  4993.4  515.58  4994.2  514.78  5002.3  515.58  5007.9  516.16
  5018.0  523.10  5028.0  523.70  5225.2  524.59  5262.2  525.53  5582.6  544.07
#Mann=8,-1,0
  4176.2    0.16       0  4345.3    0.12       0  4728.2    0.16       0
  4827.6    0.12       0  4927.0    0.16       0  4993.4    0.07       0
  5002.3    0.16       0  5225.2    0.05       0
Bank Sta=4423.4,5262.2
Exp/Cntr=0.3,0.1

Type RM Length L Ch R = 1,12763,900,900,900
BEGIN DESCRIPTION:
double EAST FORK TURKEY CREEK 18.0
END DESCRIPTION:
XS GIS Cut Line= 3
      2778874.98      7085625.00      2777925.00      7085425.00
      2777474.98      7085475.00
#Sta/Elev= 30
  4000.6  537.61  4122.8  533.14  4174.9  528.14  4184.5  526.58  4190.0  523.96
  4194.7  521.77  4214.5  518.17  4235.6  520.35  4327.6  520.24  4364.0  523.21
  4456.3  521.99  4491.1  522.51  4532.0  520.86  4608.0  523.23  4787.5  522.61
  4859.0  520.52  4981.5  521.33  4991.5  515.41  4997.1  514.74  4997.9  513.94
  5006.0  514.74  5017.9  523.96  5021.7  526.73  5031.8  529.47  5072.0  535.71
  5092.1  533.28  5113.6  533.26  5142.5  533.51  5182.7  537.66  5424.2  549.98
#Mann=6,-1,0
  4000.6    0.16       0  4122.8    0.12       0  4456.3    0.16       0
  4997.1    0.07       0  5006.0    0.16       0  5113.6    0.05       0
Bank Sta=4190,5017.9
Exp/Cntr=0.3,0.1

Type RM Length L Ch R = 1,11863,377,377,377
BEGIN DESCRIPTION:
EAST FORK TURKEY CREEK 17.0
END DESCRIPTION:
XS GIS Cut Line= 3
      2778775.04      7085225.02      2778460.80      7085104.33
      2777624.98      7085025.00
#Sta/Elev= 30
  4658.8  533.39  4673.9  533.39  4807.9  526.32  4873.2  525.04  4910.8  522.03
  4937.4  517.87  4947.2  518.05  4952.6  516.17  4969.5  519.42  4977.2  519.04
  4982.6  514.96  4990.5  511.22  4996.5  510.98  4997.4  510.18  5005.1  510.18
  5006.0  510.98  5021.3  518.32  5038.8  519.51  5107.9  519.88  5108.0  519.88
  5141.9  520.34  5202.1  519.45  5232.3  520.51  5250.1  520.08  5272.5  521.48
  5335.7  522.03  5371.8  522.99  5583.9  527.63  5780.9  540.32  5835.0  542.85
#Mann=7,-1,0
  4658.8    0.16       0  4996.5    0.07       0  5006.0    0.16       0
  5107.9    0.12       0  5108.0    0.16       0  5272.5    0.07       0
  5371.8    0.05       0
Bank Sta=4910.8,5335.7
Exp/Cntr=0.3,0.1

Type RM Length L Ch R = 1,11486,518,518,518
BEGIN DESCRIPTION:
EAST FORK TURKEY CREEK 16.0
END DESCRIPTION:
XS GIS Cut Line= 3
      2779125.04      7084724.99      2778675.00      7084825.00
      2777789.06      7084674.81
#Sta/Elev= 30
  4528.4  536.49  4630.9  535.33  4671.9  535.94  4702.6  534.80  4824.2  534.15
  4875.8  532.33  4921.6  529.93  4948.4  525.79  4964.1  521.06  4979.2  519.43
  4986.9  513.55  4992.0  513.55  4994.7  509.90  4995.7  509.10  5003.5  509.10
  5004.5  509.90  5009.7  515.43  5017.1  518.72  5192.3  518.89  5198.1  517.15
  5203.2  519.30  5237.0  518.50  5263.5  519.56  5422.3  518.71  5456.0  518.57
  5476.3  519.76  5548.3  521.06  5841.4  527.43  5882.0  529.31  5888.0  530.88
#Mann=6,-1,0
  4528.4    0.16       0  4875.8    0.12       0  4994.7    0.07       0
  5004.5    0.12       0  5237.0    0.16       0  5422.3    0.05       0
Bank Sta=4964.1,5548.3
Exp/Cntr=0.3,0.1

Type RM Length L Ch R = 1,10968,829,829,829
BEGIN DESCRIPTION:
EAST FORK TURKEY CREEK 15.0
END DESCRIPTION:
XS GIS Cut Line= 3
      2778924.98      7084624.99      2778525.00      7084375.00
      2778174.99      7083974.98
#Sta/Elev= 30
  4576.4  534.51  4677.5  531.34  4699.6  530.88  4736.2  527.56  4778.6  528.82
  4836.4  526.62  4888.3  523.80  4903.6  520.86  4913.5  520.61  4917.9  520.22
  4976.7  518.01  4982.6  517.08  4989.1  510.35  4998.9  508.51  4999.9  507.71
  5008.7  508.51  5012.7  515.65  5019.2  517.86  5045.4  517.24  5061.0  516.34
  5076.1  517.02  5083.7  515.63  5090.3  516.71  5097.9  512.72  5126.4  517.68
  5175.7  518.45  5246.9  515.93  5290.7  517.51  5364.1  520.22  5579.6  534.12
#Mann=8,-1,0
  4576.4    0.12       0  4677.5    0.16       0  4913.5    0.12       0
  4998.9    0.07       0  5008.7    0.12       0  5045.4    0.16       0
  5061.0    0.12       0  5290.7    0.05       0
Bank Sta=4917.9,5364.1
Exp/Cntr=0.3,0.1

Type RM Length L Ch R = 1,10139,937,937,937
BEGIN DESCRIPTION:
EAST FORK TURKEY CREEK 14.0
END DESCRIPTION:
XS GIS Cut Line= 3
      2779185.65      7084288.38      2778899.16      7084019.26
      2778274.98      7083875.00
#Sta/Elev= 30
  4588.3  535.09  4669.1  530.92  4775.1  528.37  4810.3  524.35  4817.6  524.90
  4824.5  522.77  4831.8  523.25  4838.6  521.40  4859.4  521.12  4880.8  518.96
  4895.3  518.05  4916.7  520.25  4945.1  516.97  4966.1  516.65  4973.4  514.33
  4981.1  505.42  4982.1  504.62  4991.0  505.42  4995.9  505.61  5006.2  512.61
  5016.4  516.55  5022.0  516.74  5160.5  517.05  5190.9  515.80  5198.1  516.90
  5314.1  516.95  5369.5  515.85  5407.6  518.96  5509.5  527.15  5622.0  533.78
#Mann=6,-1,0
  4588.3    0.16       0  4859.4    0.12       0  4981.1    0.07       0
  4991.0    0.12       0  5369.5    0.16       0  5509.5    0.05       0
Bank Sta=4880.8,5407.6
Exp/Cntr=0.3,0.1

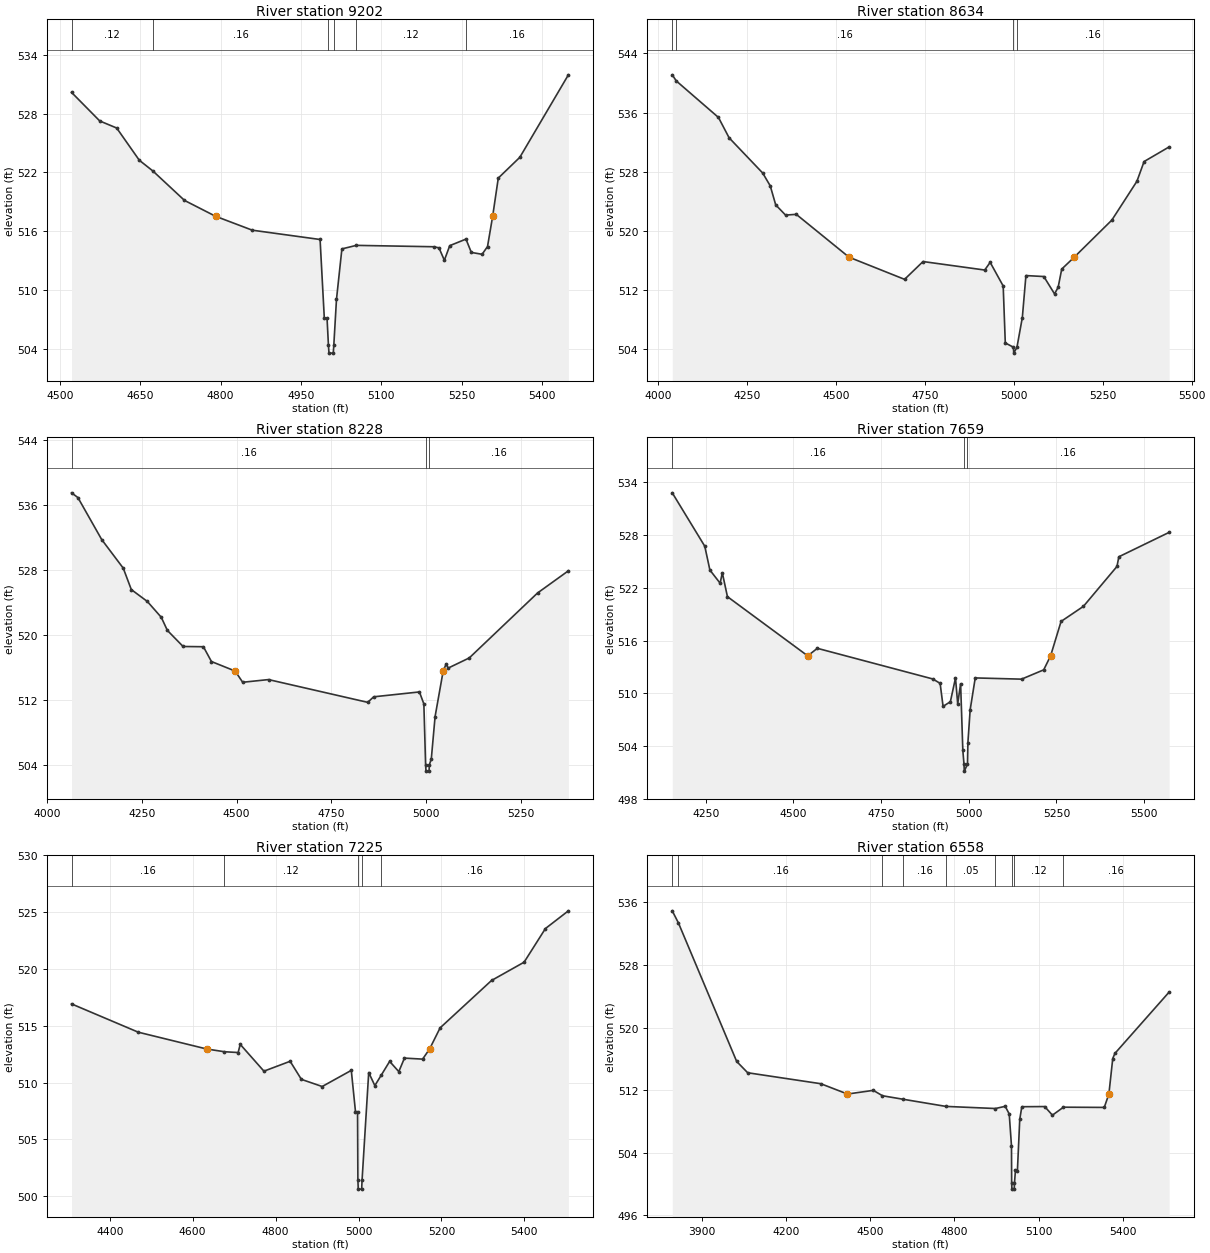
Type RM Length L Ch R = 1,9202,568,568,568
BEGIN DESCRIPTION:
EAST FORK TURKEY CREEK 13.0
END DESCRIPTION:
XS GIS Cut Line= 3
      2779324.97      7083574.99      2778875.00      7083425.00
      2778424.98      7083475.00
#Sta/Elev= 30
  4521.8  530.16  4574.5  527.24  4606.1  526.52  4648.3  523.23  4673.5  522.14
  4732.6  519.13  4790.6  517.51  4859.1  516.09  4985.6  515.14  4993.5  507.09
  4998.6  507.09  5001.2  504.34  5002.2  503.54  5010.2  503.54  5011.2  504.34
  5016.2  509.03  5026.3  514.18  5053.2  514.54  5197.3  514.40  5207.4  514.29
  5217.5  513.02  5227.5  514.51  5257.8  515.18  5267.8  513.82  5287.9  513.63
  5298.0  514.42  5307.6  517.51  5318.1  521.41  5358.3  523.53  5448.9  531.95
#Mann=6,-1,0
  4521.8    0.12       0  4673.5    0.16       0  5001.2    0.07       0
  5011.2    0.16       0  5053.2    0.12       0  5257.8    0.16       0
Bank Sta=4790.6,5307.6
Exp/Cntr=0.3,0.1

Type RM Length L Ch R = 1,8634,406,406,406
BEGIN DESCRIPTION:
EAST FORK TURKEY CREEK 12.0
END DESCRIPTION:
XS GIS Cut Line= 3
      2779625.04      7083475.03      2778825.00      7082975.00
      2778375.02      7082925.00
#Sta/Elev= 30
  4040.5  541.11  4051.9  540.28  4170.3  535.34  4200.3  532.58  4294.7  527.81
  4315.9  526.07  4331.2  523.50  4358.9  522.12  4389.0  522.22  4537.2  516.42
  4693.3  513.42  4745.2  515.83  4918.5  514.68  4933.8  515.72  4970.4  512.52
  4976.3  504.81  4999.1  504.23  5000.1  503.43  5009.1  504.23  5024.2  508.25
  5034.3  513.93  5084.6  513.80  5114.7  511.45  5124.8  512.34  5134.9  514.81
  5170.0  516.42  5275.7  521.44  5346.2  526.70  5366.3  529.37  5436.7  531.35
#Mann=4,-1,0
  4040.5    0.05       0  4051.9    0.16       0  4999.1    0.07       0
  5009.1    0.16       0
Bank Sta=4537.2,5170
Exp/Cntr=0.3,0.1

Type RM Length L Ch R = 1,8228,569,569,569
BEGIN DESCRIPTION:
EAST FORK TURKEY CREEK 11.0
END DESCRIPTION:
XS GIS Cut Line= 3
      2779754.21      7082915.96      2778879.20      7082619.08
      2778493.74      7082624.29
#Sta/Elev= 30
  4065.1  537.48  4081.9  536.90  4144.7  531.73  4201.5  528.21  4222.7  525.58
  4264.9  524.12  4301.7  522.17  4317.7  520.56  4359.2  518.58  4412.7  518.55
  4433.9  516.73  4496.3  515.56  4516.2  514.18  4584.3  514.51  4845.7  511.71
  4861.5  512.39  4982.0  512.99  4993.7  511.52  4998.3  504.05  4999.3  503.25
  5007.3  503.25  5008.3  504.05  5013.3  504.74  5023.3  509.96  5044.6  515.56
  5052.6  516.44  5057.6  515.92  5113.3  517.17  5293.3  525.16  5374.6  527.89
#Mann=3,-1,0
  4065.1    0.16       0  4998.3    0.07       0  5008.3    0.16       0
Bank Sta=4496.3,5044.6
Exp/Cntr=0.3,0.1

Type RM Length L Ch R = 1,7659,434,434,434
BEGIN DESCRIPTION:
EAST FORK TURKEY CREEK 10.0
END DESCRIPTION:
XS GIS Cut Line= 3
      2779724.97      7082824.98      2778941.70      7082238.87
      2778525.04      7082374.99
#Sta/Elev= 30
  4154.6  532.82  4247.3  526.74  4261.9  524.03  4291.1  522.53  4297.3  523.72
  4311.9  521.00  4540.8  514.26  4568.2  515.12  4897.5  511.63  4918.3  511.13
  4926.7  508.51  4947.5  509.04  4962.1  511.74  4968.4  508.80  4976.7  511.09
  4983.0  503.52  4986.3  501.94  4987.2  501.14  4996.3  501.94  4997.5  504.39
  5003.9  508.12  5018.4  511.75  5150.4  511.61  5213.6  512.67  5233.2  514.26
  5263.1  518.18  5326.9  519.90  5422.5  524.44  5427.8  525.54  5571.2  528.32
#Mann=3,-1,0
  4154.6    0.16       0  4986.3    0.07       0  4996.3    0.16       0
Bank Sta=4540.8,5233.2
Exp/Cntr=0.3,0.1

Type RM Length L Ch R = 1,7225,667,667,667
BEGIN DESCRIPTION:
Mapping XS 56c7685b
END DESCRIPTION:
XS GIS Cut Line= 3
      2779587.51      7081926.38      2778900.03      7081983.67
      2778472.93      7082259.72
#Sta/Elev= 30
  4307.8  516.93  4468.8  514.44  4634.0  512.96  4676.7  512.72  4709.7  512.65
  4714.7  513.37  4771.9  511.01  4835.1  511.88  4862.2  510.29  4912.4  509.66
  4982.6  511.08  4992.7  507.45  4997.7  507.45  4998.5  501.43  4999.4  500.63
  5007.6  500.63  5008.6  501.43  5024.6  510.89  5039.4  509.74  5055.2  510.68
  5075.1  511.87  5097.2  510.97  5110.8  512.16  5154.6  512.07  5171.4  512.96
  5196.8  514.82  5320.8  518.99  5399.4  520.60  5450.8  523.56  5506.2  525.12
#Mann=5,-1,0
  4307.8    0.16       0  4676.7    0.12       0  4998.5    0.07       0
  5008.6    0.12       0  5055.2    0.16       0
Bank Sta=4634,5171.4
Exp/Cntr=0.3,0.1

Type RM Length L Ch R = 1,6558,665,665,665
BEGIN DESCRIPTION:
EAST FORK TURKEY CREEK 9.0
END DESCRIPTION:
XS GIS Cut Line= 3
      2779817.84      7081158.77      2778717.81      7081708.79
      2778457.75      7082180.81
#Sta/Elev= 30
  3795.4  534.92  3817.5  533.36  4024.8  515.67  4063.9  514.23  4324.1  512.83
  4419.2  511.51  4511.1  511.98  4543.8  511.29  4617.8  510.84  4769.6  509.93
  4945.7  509.66  4980.7  509.94  4994.9  508.97  5003.0  504.87  5003.6  500.16
  5004.5  499.36  5012.7  499.36  5013.7  500.16  5017.2  501.81  5024.1  501.72
  5032.4  508.27  5039.8  509.89  5121.2  509.91  5148.7  508.81  5188.0  509.83
  5333.3  509.80  5349.7  511.51  5363.5  516.05  5371.1  516.70  5564.2  524.54
#Mann=9,-1,0
  3795.4    0.05       0  3817.5    0.16       0  4543.8    0.05       0
  4617.8    0.16       0  4769.6    0.05       0  4945.7    0.12       0
  5003.6    0.07       0  5013.7    0.12       0  5188.0    0.16       0
Bank Sta=4419.2,5349.7
Exp/Cntr=0.3,0.1