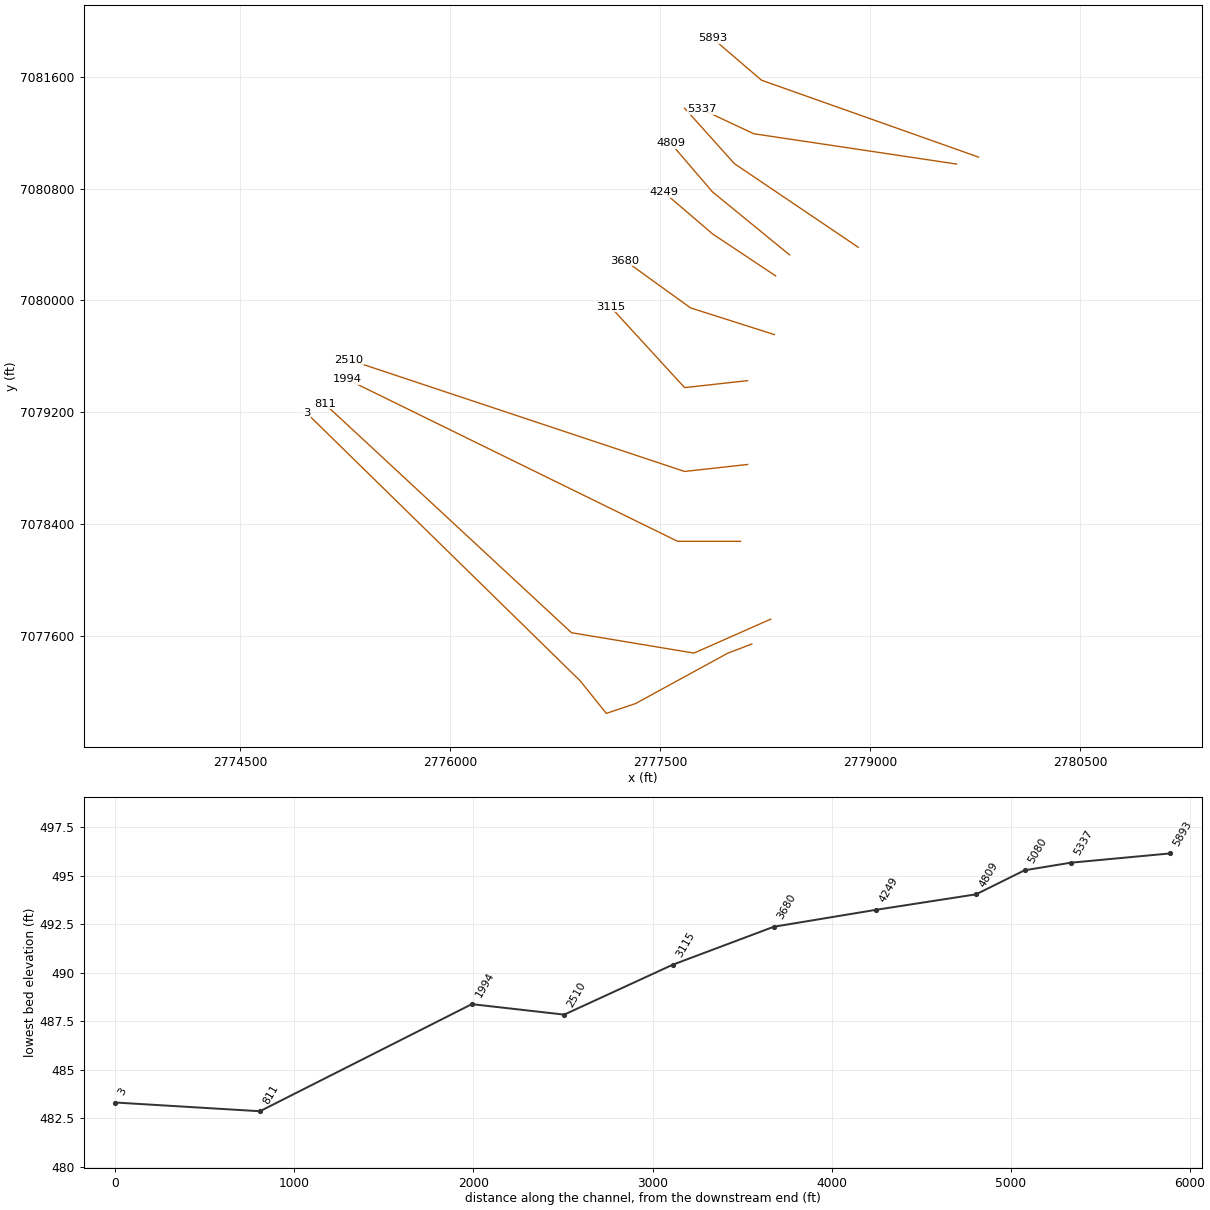
HEC-RAS study EAST FORK TURKEY CREEK.prj: EAST FORK TURKEY CREEK Base Level Engineering

--- EAST FORK TURKEY CREEK.g01 (geometry) --- (continued)

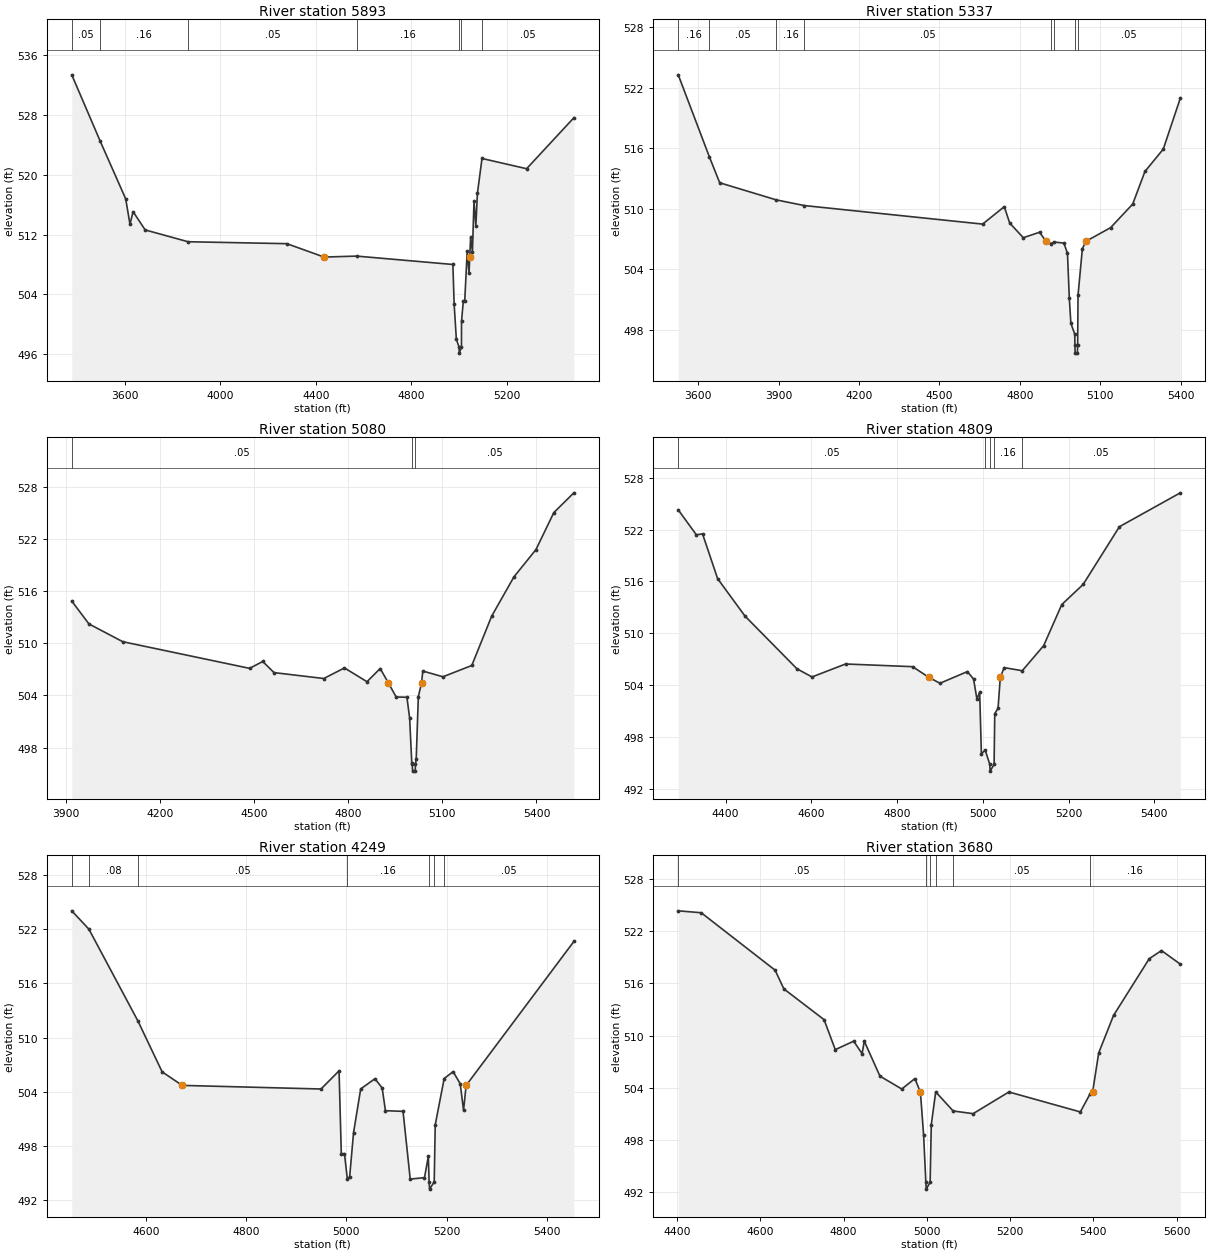
Type RM Length L Ch R = 1,5893,556,556,556
BEGIN DESCRIPTION:
EAST FORK TURKEY CREEK 8.0
END DESCRIPTION:
XS GIS Cut Line= 3
      2779775.03      7081024.99      2778225.00      7081575.00
      2777875.00      7081875.00
#Sta/Elev= 30
  3376.6  533.35  3496.4  524.44  3602.8  516.77  3620.7  513.38  3633.7  515.06
  3684.4  512.62  3864.3  511.04  4278.6  510.78  4434.8  508.99  4571.3  509.12
  4975.0  508.00  4980.3  502.68  4989.5  498.03  5000.8  496.95  5001.8  496.15
  5011.0  496.95  5011.2  500.42  5018.7  503.06  5024.6  503.06  5035.0  509.76
  5042.7  506.86  5045.7  508.99  5049.3  511.61  5057.0  509.73  5063.6  516.51
  5071.3  513.16  5077.8  517.49  5097.1  522.17  5284.2  520.80  5482.3  527.61
#Mann=7,-1,0
  3376.6    0.05       0  3496.4    0.16       0  3864.3    0.05       0
  4571.3    0.16       0  5000.8    0.07       0  5011.0    0.16       0
  5097.1    0.05       0
Bank Sta=4434.8,5045.7
Exp/Cntr=0.3,0.1

Type RM Length L Ch R = 1,5337,257,257,257
BEGIN DESCRIPTION:
XS3097A
END DESCRIPTION:
XS GIS Cut Line= 3
      2779618.10      7080975.27      2778168.46      7081192.28
      2777799.74      7081365.80
#Sta/Elev= 30
  3525.9  523.28  3642.4  515.12  3680.7  512.57  3892.1  510.87  3996.5  510.31
  4661.5  508.47  4742.4  510.20  4762.6  508.58  4813.2  507.12  4873.9  507.66
  4898.5  506.77  4915.5  506.53  4927.9  506.69  4964.9  506.59  4978.2  505.56
  4985.1  501.10  4990.9  498.62  5005.4  497.55  5005.9  496.47  5006.8  495.67
  5015.1  495.67  5016.1  496.47  5017.6  501.42  5033.8  506.04  5047.5  506.77
  5139.2  508.12  5221.6  510.46  5267.2  513.69  5335.6  515.91  5399.2  520.96
#Mann=8,-1,0
  3525.9    0.16       0  3642.4    0.05       0  3892.1    0.16       0
  3996.5    0.05       0  4915.5    0.16       0  4927.9    0.05       0
  5005.9    0.03       0  5016.1    0.05       0
Bank Sta=4898.5,5047.5
Exp/Cntr=0.3,0.1

Type RM Length L Ch R = 1,5080,271,271,271
BEGIN DESCRIPTION:
double EAST FORK TURKEY CREEK 7.0
END DESCRIPTION:
XS GIS Cut Line= 3
      2778915.62      7080379.52      2778030.24      7080978.46
      2777675.02      7081374.98
#Sta/Elev= 30
  3917.9  514.87  3972.6  512.24  4080.5  510.19  4485.0  507.12  4527.0  507.91
  4562.9  506.63  4721.7  505.95  4787.6  507.17  4859.5  505.58  4901.5  507.10
  4927.7  505.45  4952.4  503.82  4986.8  503.79  4995.5  501.39  5002.3  496.23
  5003.9  496.08  5004.9  495.28  5013.2  495.28  5014.1  496.08  5016.5  496.71
  5023.2  503.86  5033.5  505.45  5037.4  506.81  5101.7  506.15  5193.7  507.45
  5257.2  513.14  5328.2  517.66  5398.5  520.81  5455.3  525.06  5519.2  527.34
#Mann=3,-1,0
  3917.9    0.05       0  5003.9    0.03       0  5014.1    0.05       0
Bank Sta=4927.7,5033.5
Exp/Cntr=0.3,0.1

Type RM Length L Ch R = 1,4809,560,560,560
BEGIN DESCRIPTION:
double EAST FORK TURKEY CREEK 6.0
END DESCRIPTION:
XS GIS Cut Line= 3
      2778424.98      7080325.02      2777875.00      7080775.00
      2777574.99      7081125.01
#Sta/Elev= 30
  4289.3  524.28  4331.6  521.39  4346.0  521.50  4381.2  516.32  4445.0  511.99
  4566.4  505.88  4601.5  504.94  4679.8  506.44  4836.2  506.13  4874.5  504.88
  4900.1  504.21  4964.0  505.56  4978.4  504.70  4986.3  502.38  4992.7  503.17
  4996.7  496.07  5005.7  496.45  5016.2  494.84  5017.2  494.04  5026.4  494.84
  5027.9  500.70  5035.6  501.31  5040.8  504.88  5049.8  506.02  5092.1  505.66
  5142.0  508.56  5184.3  513.32  5234.2  515.65  5318.8  522.33  5460.9  526.25
#Mann=5,-1,0
  4289.3    0.05       0  5005.7    0.16       0  5016.2    0.03       0
  5026.4    0.16       0  5092.1    0.05       0
Bank Sta=4874.5,5040.8
Exp/Cntr=0.3,0.1

Type RM Length L Ch R = 1,4249,569,569,569
BEGIN DESCRIPTION:
double EAST FORK TURKEY CREEK 5.0
END DESCRIPTION:
XS GIS Cut Line= 3
      2778324.99      7080175.01      2777875.00      7080475.00
      2777525.00      7080775.00
#Sta/Elev= 30
  4452.0  524.01  4486.2  521.98  4584.0  511.83  4632.3  506.21  4672.3  504.71
  4949.3  504.31  4985.3  506.32  4989.8  497.16  4996.1  497.16  5001.8  494.38
  5006.5  494.62  5014.2  499.47  5028.5  504.32  5057.0  505.45  5071.3  504.42
  5077.9  501.91  5113.0  501.84  5127.3  494.35  5155.8  494.51  5163.5  496.87
  5165.0  494.04  5165.9  493.24  5175.2  494.04  5177.2  500.35  5195.1  505.47
  5212.9  506.23  5227.1  504.89  5233.7  501.96  5238.9  504.71  5453.8  520.62
#Mann=7,-1,0
  4452.0    0.05       0  4486.2    0.08       0  4584.0    0.05       0
  5001.8    0.16       0  5165.0    0.03       0  5175.2    0.16       0
  5195.1    0.05       0
Bank Sta=4672.3,5238.9
Exp/Cntr=0.3,0.1

Type RM Length L Ch R = 1,3680,565,565,565
BEGIN DESCRIPTION:
Mapping XS 1f6aad4c
END DESCRIPTION:
XS GIS Cut Line= 3
      2778316.72      7079754.49      2777717.74      7079945.47
      2777249.48      7080283.66
#Sta/Elev= 30
  4402.6  524.31  4457.9  524.09  4635.3  517.50  4656.4  515.35  4753.0  511.82
  4779.9  508.38  4824.2  509.35  4844.3  507.91  4849.6  509.35  4887.2  505.34
  4939.7  503.86  4971.2  505.06  4984.5  503.48  4992.2  498.54  4997.5  493.17
  4998.5  492.37  5007.8  493.17  5010.6  499.78  5021.2  503.53  5063.1  501.34
  5111.1  501.03  5197.0  503.52  5368.7  501.23  5392.1  503.30  5398.1  503.48
  5412.8  508.00  5448.4  512.30  5534.3  518.82  5563.7  519.75  5608.9  518.19
#Mann=6,-1,0
  4402.6    0.05       0  4997.5    0.03       0  5007.8    0.05       0
  5021.2    0.16       0  5063.1    0.05       0  5392.1    0.16       0
Bank Sta=4984.5,5398.1
Exp/Cntr=0.3,0.1

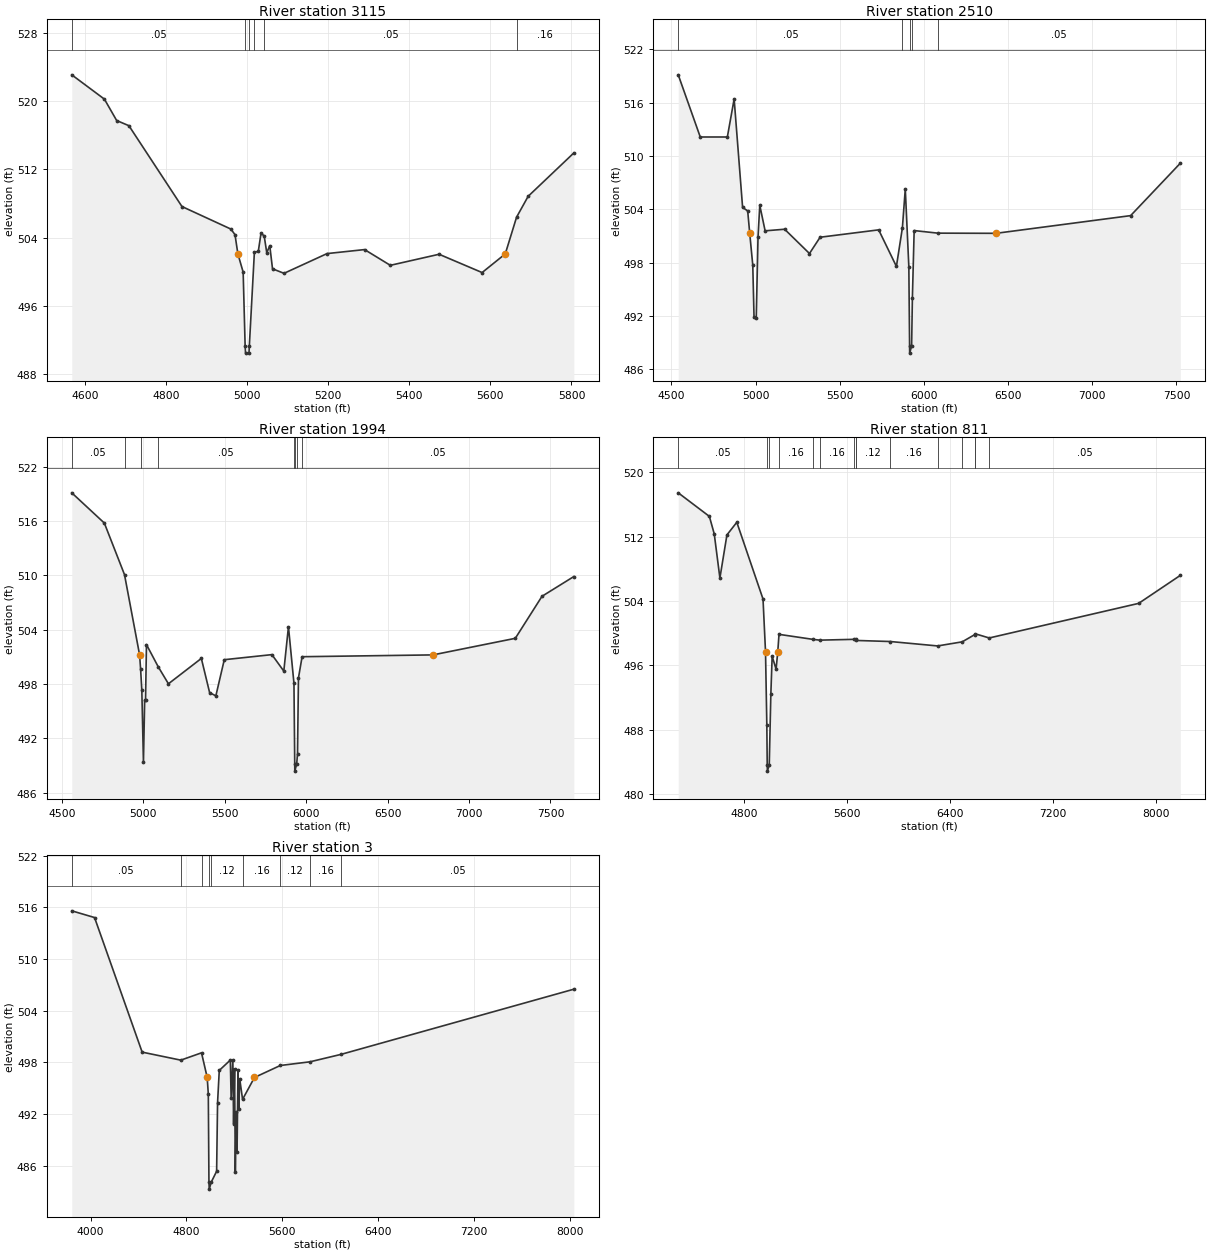
Type RM Length L Ch R = 1,3115,605,605,605
BEGIN DESCRIPTION:
EAST FORK TURKEY CREEK 3.0
END DESCRIPTION:
XS GIS Cut Line= 3
      2778125.01      7079425.00      2777675.00      7079375.00
      2777144.80      7079954.18
#Sta/Elev= 30
  4567.8  523.12  4648.3  520.26  4678.5  517.75  4708.7  517.14  4839.5  507.64
  4960.2  504.99  4970.3  504.33  4977.4  502.07  4990.4  499.93  4995.3  491.21
  4996.3  490.41  5004.7  490.41  5005.6  491.21  5018.1  502.28  5027.7  502.36
  5034.5  504.52  5042.3  504.17  5048.6  502.21  5056.0  503.04  5062.8  500.32
  5091.2  499.79  5197.3  502.11  5289.8  502.58  5353.3  500.73  5473.5  502.03
  5579.6  499.88  5636.7  502.07  5664.6  506.39  5693.1  508.84  5805.8  513.94
#Mann=6,-1,0
  4567.8    0.05       0  4995.3    0.03       0  5005.6    0.05       0
  5018.1    0.16       0  5042.3    0.05       0  5664.6    0.16       0
Bank Sta=4977.4,5636.7
Exp/Cntr=0.3,0.1

Type RM Length L Ch R = 1,2510,516,516,516
BEGIN DESCRIPTION:
double EAST FORK TURKEY CREEK 2.0
END DESCRIPTION:
XS GIS Cut Line= 3
      2778125.05      7078825.01      2777675.00      7078775.00
      2775275.04      7079574.99
#Sta/Elev= 30
  4540.4  519.13  4671.2  512.14  4832.2  512.14  4872.5  516.41  4922.8  504.22
  4953.0  503.83  4965.1  501.31  4983.2  497.72  4990.7  491.86  5003.8  491.74
  5014.3  500.86  5024.8  504.46  5056.5  501.59  5172.4  501.77  5320.0  499.04
  5383.2  500.87  5731.1  501.70  5836.5  497.59  5872.0  501.92  5889.2  506.30
  5910.3  497.56  5914.8  488.64  5915.3  487.84  5926.8  488.64  5931.4  494.05
  5941.9  501.62  6082.5  501.33  6428.1  501.31  7227.9  503.30  7523.0  509.19
#Mann=5,-1,0
  4540.4    0.05       0  5872.0    0.16       0  5914.8    0.03       0
  5926.8    0.16       0  6082.5    0.05       0
Bank Sta=4965.1,6428.1
Exp/Cntr=0.3,0.1

Type RM Length L Ch R = 1,1994,1183,1183,1183
BEGIN DESCRIPTION:
double EAST FORK TURKEY CREEK 1.0
END DESCRIPTION:
XS GIS Cut Line= 3
      2778075.02      7078275.00      2777625.00      7078275.00
      2775262.44      7079435.02
#Sta/Elev= 30
  4561.4  519.10  4761.4  515.76  4885.1  510.07  4977.8  501.21  4984.1  499.60
  4991.4  497.32  5001.4  489.36  5008.9  496.18  5014.2  496.18  5019.9  502.35
  5092.3  499.89  5154.8  498.02  5356.8  500.82  5407.7  497.04  5445.9  496.69
  5497.6  500.68  5789.9  501.24  5863.0  499.42  5891.5  504.32  5925.3  498.08
  5930.1  489.18  5930.6  488.38  5942.1  489.18  5947.2  490.32  5952.9  498.66
  5975.3  501.01  6778.7  501.21  7284.1  503.04  7448.0  507.68  7643.4  509.86
#Mann=8,-1,0
  4561.4    0.05       0  4885.1    0.12       0  4984.1    0.16       0
  5092.3    0.05       0  5925.3    0.16       0  5930.1    0.07       0
  5942.1    0.16       0  5975.3    0.05       0
Bank Sta=4977.8,6778.7
Exp/Cntr=0.3,0.1

Type RM Length L Ch R = 1,811,808,808,808
BEGIN DESCRIPTION:
Mapping XS cbfd1787
END DESCRIPTION:
XS GIS Cut Line= 4
      2778290.46      7077718.02      2777741.83      7077474.96
      2776866.83      7077620.79      2775102.93      7079259.70
#Sta/Elev= 30
  4290.2  517.45  4531.8  514.52  4569.6  512.34  4613.4  506.86  4668.0  512.22
  4744.6  513.79  4947.9  504.25  4967.3  497.70  4977.5  488.58  4980.5  483.66
  4982.1  482.86  4996.3  483.66  5008.7  492.45  5018.8  497.13  5049.3  495.53
  5062.4  497.70  5071.9  499.86  5338.2  499.23  5388.4  499.14  5654.8  499.24
  5667.4  499.27  5672.4  499.10  5934.5  498.97  6302.5  498.42  6493.2  498.93
  6591.6  499.84  6596.1  499.92  6702.8  499.41  7861.9  503.71  8185.1  507.19
#Mann=15,-1,0
  4290.2    0.05       0  4980.5    0.03       0  4996.3    0.05       0
  5071.9    0.16       0  5338.2    0.12       0  5388.4    0.16       0
  5654.8    0.12       0  5667.4    0.16       0  5672.4    0.12       0
  5934.5    0.16       0  6302.5    0.05       0  6493.2     0.1       0
  6591.6    0.05       0  6596.1     0.1       0  6702.8    0.05       0
Bank Sta=4967.3,5062.4
Exp/Cntr=0.3,0.1

Type RM Length L Ch R = 1,3,0,0,0
BEGIN DESCRIPTION:
Mapping XS b1b3fd43
END DESCRIPTION:
XS GIS Cut Line= 6
      2778155.13      7077539.65      2777984.06      7077474.73
      2777324.34      7077113.62      2777115.56      7077043.46
      2776927.81      7077277.29      2774975.85      7079191.21
#Sta/Elev= 30
  3843.2  515.59  4033.4  514.81  4430.8  499.20  4753.5  498.27  4926.4  499.12
  4973.9  496.26  4983.1  494.32  4988.4  484.11  4990.9  483.31  5007.2  484.11
  5052.5  485.38  5060.3  493.32  5074.6  497.08  5167.0  498.28  5173.5  493.93
  5187.8  498.31  5194.3  490.87  5202.1  497.26  5208.6  485.34  5216.4  492.27
  5223.0  487.63  5230.8  497.13  5237.3  492.56  5245.1  496.12  5269.1  493.72
  5368.3  496.26  5584.1  497.65  5832.8  498.08  6091.3  498.94  8034.7  506.50
#Mann=9,-1,0
  3843.2    0.05       0  4753.5    0.07       0  4926.4    0.12       0
  4988.4    0.07       0  5007.2    0.12       0  5269.1    0.16       0
  5584.1    0.12       0  5832.8    0.16       0  6091.3    0.05       0
Bank Sta=4973.9,5368.3
Exp/Cntr=0.3,0.1

Chan Stop Cuts=-1