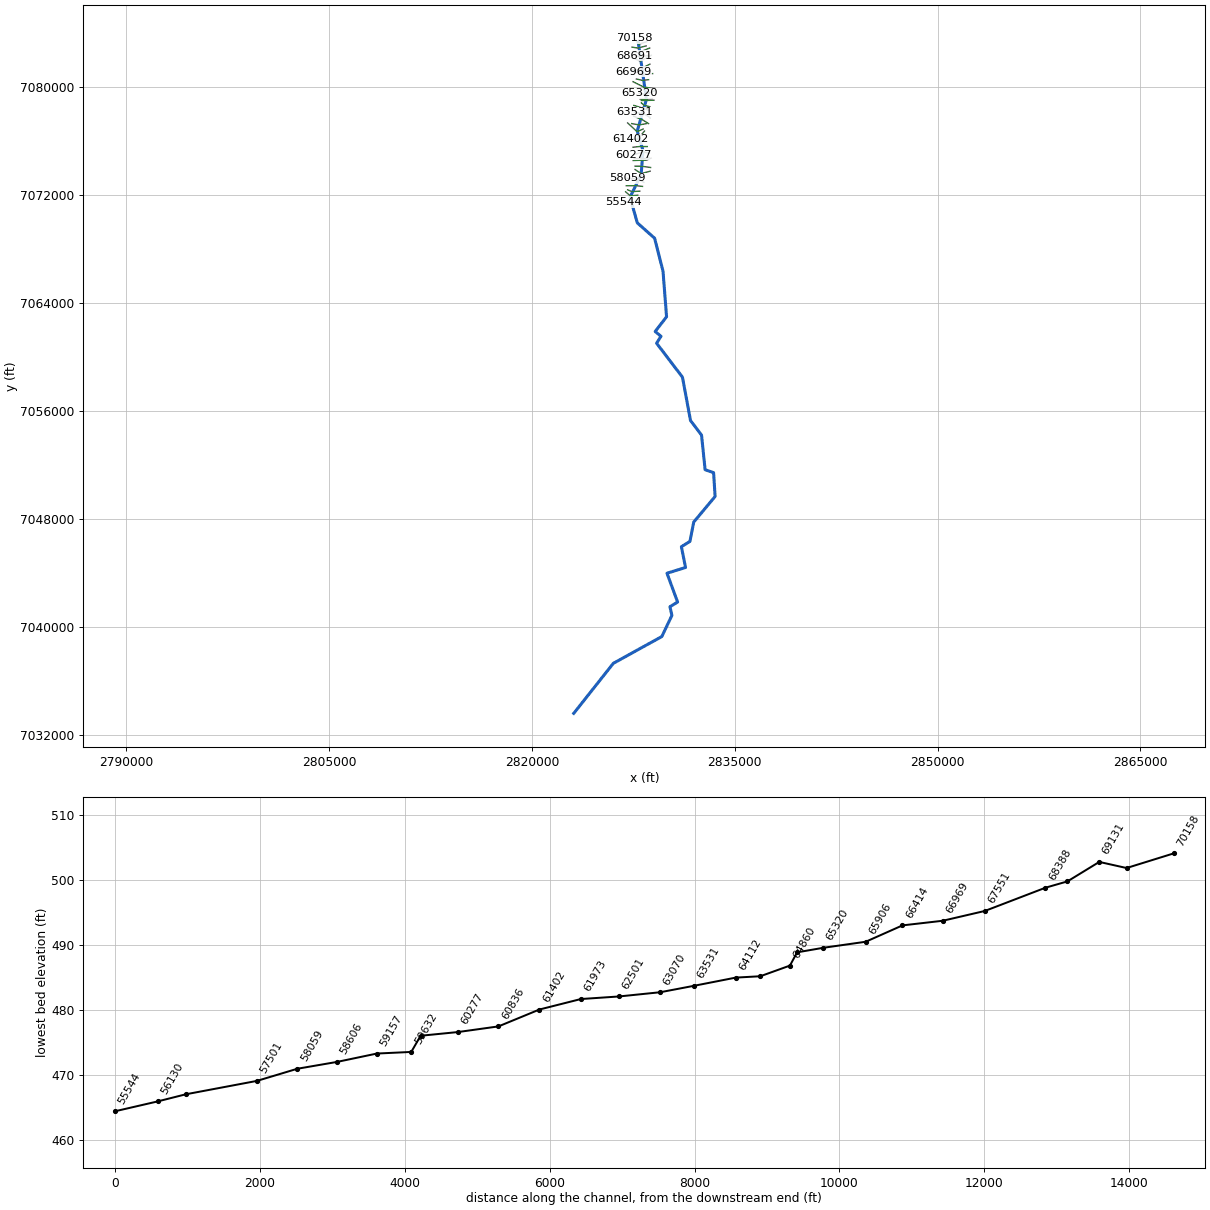
--- ELM CREEK.prj (project) ---

Proj Title=ELM CREEK Base Level Engineering
Current Plan=p01
Default Exp/Contr=0.3,0.1
English Units
Geom File=g01
Flow File=f01
Plan File=p01
BEGIN DESCRIPTION:
ELM CREEK
END DESCRIPTION:

--- ELM CREEK.p01 (plan) ---

Plan Title=Multiple Run
Short Identifier=Multiple
Geom File=g01
Flow File=f01
Subcritical Flow
K Sum by GR= 0
Std Step Tol= 0.01
Critical Tol= 0.01
Num of Std Step Trials= 20
Max Error Tol= 0.3
Flow Tol Ratio= 0.001
Split Flow NTrial= 30
Split Flow Tol= 0.02
Split Flow Ratio= 0.02
Log Output Level= 0
Friction Slope Method= 1
Unsteady Friction Slope Method= 2
Unsteady Bridges Friction Slope Method= 1
Parabolic Critical Depth
Global Vel Dist=  1 , 1 , 1
Global Log Level= 0
CheckData=True
Encroach Param= -1, 0, 0, 0
BEGIN DESCRIPTION:
Multiple Run
END DESCRIPTION:

--- ELM CREEK.f01 (steady flow) ---

Flow Title=Multiple
Program Version=5.07
Number of Profiles= 7
Profile Names=10-year,25-year,50-year,1pct_min,100-year,1pct_plu,500-year
River Rch & RM=ELM CREEK,Reach-1         ,70158
     805    1084    1312     787    1570    3132    2243
River Rch & RM=ELM CREEK,Reach-1         ,69508
    1347    1863    2294    1397    2788    5563    4112
River Rch & RM=ELM CREEK,Reach-1         ,64112
    1663    2325    2882    1766    3524    7032    5264
River Rch & RM=ELM CREEK,Reach-1         ,61402
    1916    2696    3358    2066    4123    8225    6208
River Rch & RM=ELM CREEK,Reach-1         ,60836
    2219    3130    3903    2403    4794    9565    7227
River Rch & RM=ELM CREEK,Reach-1         ,52758
    2633    3742    4691    2901    5788   11550    8808
River Rch & RM=ELM CREEK,Reach-1         ,50149
    2880    4100    5143    3182    6349   12668    9669
River Rch & RM=ELM CREEK,Reach-1         ,44523
    3699    5313    6706    4172    8324   16608   12814
River Rch & RM=ELM CREEK,Reach-1         ,36669
    3855    5547    7009    4365    8709   17376   13437
River Rch & RM=ELM CREEK,Reach-1         ,34958
    3744    5365    6761    4199    8379   16718   12859
River Rch & RM=ELM CREEK,Reach-1         ,31818
    4528    6529    8264    5153   10282   20516   15914
River Rch & RM=ELM CREEK,Reach-1         ,26879
    4711    6803    8619    5381   10737   21423   16659
River Rch & RM=ELM CREEK,Reach-1         ,22751
    4625    6660    8422    5248   10471   20892   16183
River Rch & RM=ELM CREEK,Reach-1         ,17432
    5003    7221    9146    5708   11388   22722   17660
River Rch & RM=ELM CREEK,Reach-1         ,12682
    5122    7390    9359    5839   11651   23247   18065
River Rch & RM=ELM CREEK,Reach-1         ,6468
    5136    7396    9353    5828   11628   23200   17978
River Rch & RM=ELM CREEK,Reach-1         ,318
    5154    7418    9378    5841   11654   23254   18008
Boundary for River Rch & Prof#=ELM CREEK,Reach-1         , 1
Up Type= 0
Dn Type= 3
Dn Slope=0.00013
Boundary for River Rch & Prof#=ELM CREEK,Reach-1         , 2
Up Type= 0
Dn Type= 3
Dn Slope=0.00013
Boundary for River Rch & Prof#=ELM CREEK,Reach-1         , 3
Up Type= 0
Dn Type= 3
Dn Slope=0.00013
Boundary for River Rch & Prof#=ELM CREEK,Reach-1         , 4
Up Type= 0
Dn Type= 3
Dn Slope=0.00013
Boundary for River Rch & Prof#=ELM CREEK,Reach-1         , 5
Up Type= 0
Dn Type= 3
Dn Slope=0.00013
Boundary for River Rch & Prof#=ELM CREEK,Reach-1         , 6
Up Type= 0
Dn Type= 3
Dn Slope=0.00013
Boundary for River Rch & Prof#=ELM CREEK,Reach-1         , 7
Up Type= 0
Dn Type= 3
Dn Slope=0.00013
DSS Import GetInterval= 0
DSS Import GetPeak= 0
DSS Import FillOption= 0

--- ELM CREEK.g01 (geometry) ---

Geom Title=Existing Conditions

River Reach=ELM CREEK,Reach-1
Reach XY= 30
      2827859.34      7083335.64      2828467.42      7079076.30
      2827786.40      7076725.54      2828215.21      7075265.51
      2828074.51      7073520.92      2827256.41      7071821.02
      2827790.91      7069928.05      2829072.17      7068789.12
      2829693.90      7066340.62      2829955.25      7062976.05
      2829111.38      7061883.40      2829545.24      7061530.09
      2829217.55      7061016.57      2831131.17      7058504.05
      2831726.73      7055296.18      2832541.62      7054220.04
      2832807.22      7051656.66      2833434.21      7051435.13
      2833545.32      7049675.60      2831964.20      7047777.66
      2831684.31      7046350.32      2831052.31      7045955.69
      2831359.17      7044417.29      2829987.58      7043992.01
      2830773.26      7041857.40      2830204.85      7041512.44
      2830351.07      7040874.02      2829605.55      7039305.75
      2826018.74      7037323.98      2823089.30      7033618.54

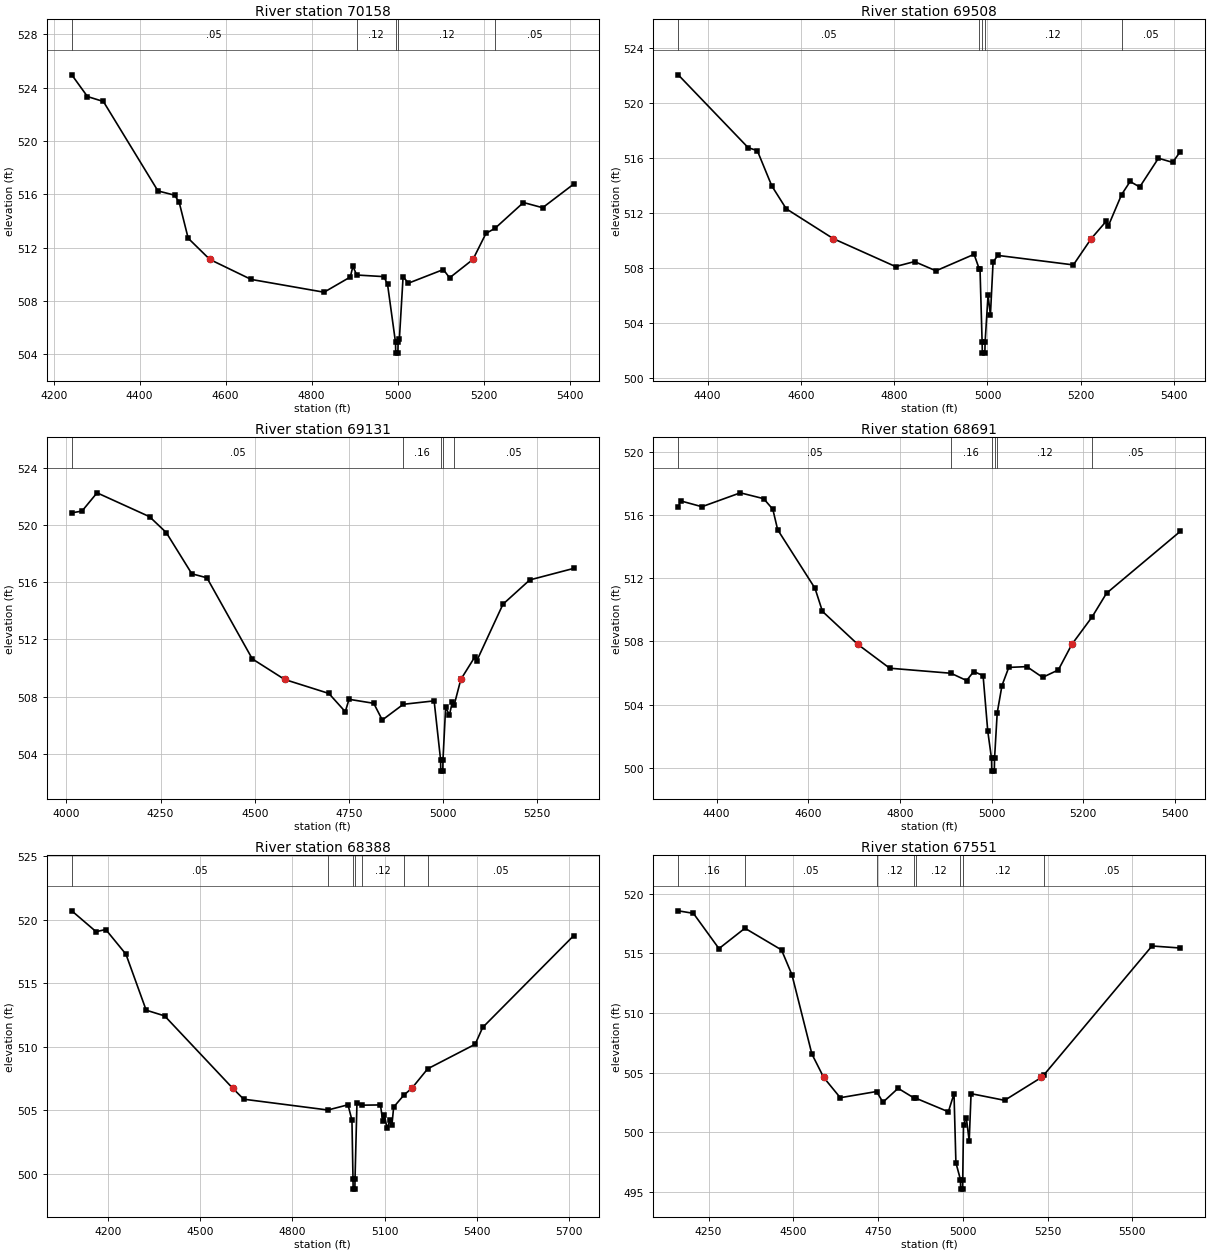
Type RM Length L Ch R = 1,70158,650,650,650
BEGIN DESCRIPTION:
ELM CREEK 82.0
END DESCRIPTION:
XS GIS Cut Line= 3
      2828492.03      7083342.34      2827888.70      7083142.68
      2827593.55      7083585.41
#Sta/Elev= 30
  4242.1  524.97  4278.6  523.34  4315.6  522.97  4442.5  516.26  4481.2  515.94
  4491.8  515.42  4512.8  512.71  4563.1  511.12  4659.2  509.62  4828.8  508.66
  4889.8  509.80  4895.9  510.60  4904.8  509.95  4968.0  509.83  4976.5  509.24
  4995.0  504.89  4995.5  504.09  5000.5  504.09  5001.0  504.89  5004.0  505.17
  5012.6  509.82  5025.1  509.34  5106.2  510.36  5120.8  509.74  5175.1  511.12
  5205.3  513.07  5226.6  513.46  5292.5  515.39  5337.1  515.00  5409.7  516.78
#Mann=5,-1,0
  4242.1    0.05       0  4904.8    0.12       0  4995.0    0.07       0
  5001.0    0.12       0  5226.6    0.05       0
Bank Sta=4563.1,5175.1
Exp/Cntr=0.3,0.1

Type RM Length L Ch R = 1,69508,377,377,377
BEGIN DESCRIPTION:
Mapping XS 5ae93057
END DESCRIPTION:
XS GIS Cut Line= 3
      2828449.16      7083026.20      2827825.25      7082866.14
      2827398.71      7082934.52
#Sta/Elev= 30
  4337.2  522.06  4487.0  516.77  4506.7  516.55  4537.7  513.99  4568.6  512.33
  4669.4  510.16  4802.9  508.13  4843.6  508.49  4889.6  507.82  4971.3  509.02
  4982.3  507.96  4984.0  507.96  4988.5  502.64  4989.0  501.84  4994.4  501.84
  4994.9  502.64  5001.2  506.05  5006.3  504.60  5012.0  508.45  5022.1  508.94
  5184.1  508.25  5222.4  510.16  5254.2  511.41  5259.2  511.10  5287.5  513.36
  5305.7  514.31  5326.3  513.91  5366.4  516.00  5396.8  515.70  5413.3  516.48
#Mann=5,-1,0
  4337.2    0.05       0  4982.3    0.12       0  4988.5    0.07       0
  4994.9    0.12       0  5287.5    0.05       0
Bank Sta=4669.4,5222.4
Exp/Cntr=0.3,0.1

Type RM Length L Ch R = 1,69131,440,440,440
BEGIN DESCRIPTION:
Mapping XS bd70eb63
END DESCRIPTION:
XS GIS Cut Line= 3
      2828707.18      7082869.40      2827841.58      7082516.63
      2827449.76      7082585.20
#Sta/Elev= 30
  4014.4  520.87  4041.5  520.99  4081.5  522.27  4220.7  520.60  4265.1  519.49
  4333.0  516.60  4373.1  516.32  4493.5  510.64  4579.3  509.20  4696.7  508.22
  4740.3  506.94  4750.2  507.81  4815.8  507.53  4838.5  506.36  4894.3  507.46
  4976.1  507.70  4993.2  503.58  4993.7  502.78  4999.1  502.78  4999.6  503.58
  5006.6  507.25  5016.7  506.71  5024.2  507.60  5029.4  507.42  5046.9  509.20
  5083.7  510.76  5088.8  510.48  5158.8  514.47  5229.9  516.17  5346.9  516.98
#Mann=5,-1,0
  4014.4    0.05       0  4894.3    0.16       0  4993.2    0.07       0
  4999.6    0.16       0  5029.4    0.05       0
Bank Sta=4579.3,5046.9
Exp/Cntr=0.3,0.1

Type RM Length L Ch R = 1,68691,303,303,303
BEGIN DESCRIPTION:
Mapping XS 2bf1aad9
END DESCRIPTION:
XS GIS Cut Line= 3
      2828667.98      7082330.44      2827998.37      7082199.78
      2827599.85      7082309.94
#Sta/Elev= 30
  4316.2  516.51  4321.4  516.90  4367.9  516.53  4451.7  517.41  4502.6  517.04
  4522.6  516.37  4533.2  515.07  4614.7  511.36  4630.9  509.90  4708.1  507.81
  4777.7  506.30  4911.4  505.98  4945.5  505.52  4961.1  506.09  4981.5  505.83
  4991.7  502.31  4999.9  500.58  5000.4  499.78  5006.0  499.78  5006.5  500.58
  5012.3  503.47  5022.7  505.20  5037.5  506.35  5077.0  506.40  5111.4  505.72
  5145.7  506.19  5175.2  507.81  5219.2  509.54  5250.9  511.05  5411.9  514.97
#Mann=6,-1,0
  4316.2    0.05       0  4911.4    0.16       0  4999.9    0.07       0
  5006.5    0.16       0  5012.3    0.12       0  5219.2    0.05       0
Bank Sta=4708.1,5175.2
Exp/Cntr=0.3,0.1

Type RM Length L Ch R = 1,68388,837,837,837
BEGIN DESCRIPTION:
Mapping XS 5ccf817c
END DESCRIPTION:
XS GIS Cut Line= 3
      2828824.78      7082333.70      2828021.23      7081902.53
      2827349.14      7082166.80
#Sta/Elev= 30
  4082.1  520.69  4161.3  519.05  4192.7  519.22  4258.4  517.28  4324.2  512.88
  4384.3  512.43  4606.0  506.74  4641.7  505.88  4915.7  505.03  4981.1  505.44
  4994.0  504.23  4997.4  499.61  4997.9  498.81  5003.5  498.81  5004.0  499.61
  5010.3  505.61  5025.6  505.41  5086.7  505.43  5094.2  504.17  5099.6  504.64
  5108.2  503.59  5118.6  504.28  5124.0  503.82  5129.7  505.26  5163.7  506.22
  5188.9  506.74  5240.5  508.27  5395.0  510.20  5419.4  511.52  5716.2  518.75
#Mann=7,-1,0
  4082.1    0.05       0  4915.7    0.16       0  4997.4    0.07       0
  5004.0    0.16       0  5025.6    0.12       0  5163.7    0.16       0
  5240.5    0.05       0
Bank Sta=4606,5188.9
Exp/Cntr=0.3,0.1

Type RM Length L Ch R = 1,67551,582,582,582
BEGIN DESCRIPTION:
ELM CREEK 81.0
END DESCRIPTION:
XS GIS Cut Line= 3
      2828724.96      7081674.98      2827925.00      7081275.00
      2827340.13      7081233.91
#Sta/Elev= 30
  4160.6  518.58  4205.3  518.37  4280.7  515.41  4357.3  517.12  4465.2  515.30
  4496.0  513.21  4554.7  506.57  4589.6  504.60  4638.5  502.90  4745.6  503.42
  4764.3  502.52  4809.0  503.69  4855.1  502.89  4862.9  502.84  4957.2  501.72
  4973.9  503.23  4979.5  497.44  4992.9  496.03  4993.4  495.23  4999.1  495.23
  4999.6  496.03  5001.9  500.65  5010.3  501.21  5018.7  499.26  5024.2  503.24
  5123.2  502.68  5231.6  504.60  5238.4  504.79  5557.8  515.63  5641.3  515.46
#Mann=8,-1,0
  4160.6    0.16       0  4357.3    0.05       0  4745.6    0.12       0
  4855.1    0.16       0  4862.9    0.12       0  4992.9    0.07       0
  4999.6    0.12       0  5238.4    0.05       0
Bank Sta=4589.6,5231.6
Exp/Cntr=0.3,0.1

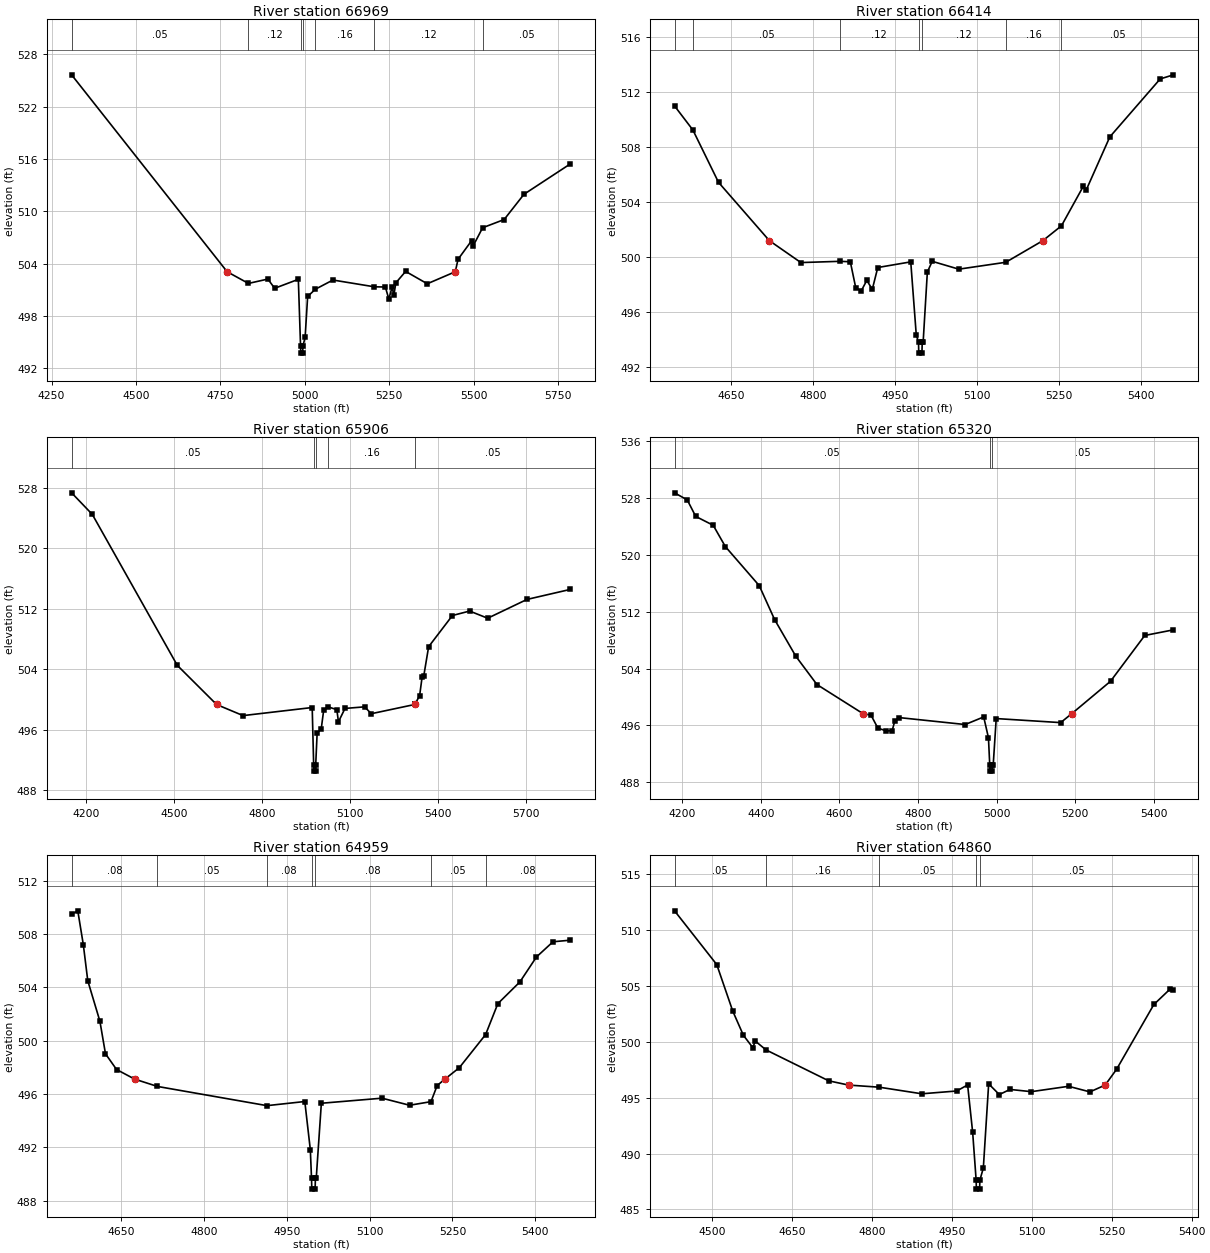
Type RM Length L Ch R = 1,66969,555,555,555
BEGIN DESCRIPTION:
ELM CREEK 80.0
END DESCRIPTION:
XS GIS Cut Line= 3
      2828925.00      7080975.00      2828225.00      7080925.00
      2827475.00      7081125.00
#Sta/Elev= 30
  4309.3  525.66  4770.1  503.06  4833.2  501.72  4890.8  502.22  4910.8  501.16
  4981.0  502.19  4987.6  494.52  4988.1  493.72  4993.9  493.72  4994.4  494.52
  5001.1  495.52  5008.6  500.22  5031.3  501.05  5083.5  502.11  5206.4  501.33
  5238.8  501.31  5249.1  499.93  5258.8  501.29  5264.0  500.36  5269.8  501.78
  5298.9  503.10  5363.0  501.68  5446.0  503.06  5454.2  504.49  5494.3  506.62
  5499.5  506.07  5527.0  508.11  5590.7  509.05  5649.5  511.95  5787.3  515.45
#Mann=7,-1,0
  4309.3    0.05       0  4833.2    0.12       0  4987.6    0.07       0
  4994.4    0.12       0  5031.3    0.16       0  5206.4    0.12       0
  5527.0    0.05       0
Bank Sta=4770.1,5446
Exp/Cntr=0.3,0.1

Type RM Length L Ch R = 1,66414,508,508,508
BEGIN DESCRIPTION:
ELM CREEK 79.0
END DESCRIPTION:
XS GIS Cut Line= 3
      2828624.96      7080525.00      2828175.00      7080475.00
      2827725.00      7080575.00
#Sta/Elev= 30
  4546.4  510.97  4580.0  509.22  4626.9  505.42  4720.1  501.18  4777.8  499.59
  4849.1  499.68  4868.3  499.65  4878.4  497.73  4888.5  497.55  4898.5  498.29
  4908.6  497.65  4918.6  499.23  4979.0  499.64  4989.1  494.33  4993.2  493.81
  4993.7  493.01  4999.5  493.01  5000.0  493.81  5001.7  493.81  5009.4  498.90
  5018.3  499.68  5067.0  499.11  5153.0  499.61  5220.9  501.18  5255.0  502.26
  5294.9  505.12  5300.0  504.83  5343.6  508.72  5435.8  512.93  5460.1  513.23
#Mann=7,-1,0
  4546.4    0.16       0  4580.0    0.05       0  4849.1    0.12       0
  4993.2    0.07       0  5000.0    0.12       0  5153.0    0.16       0
  5255.0    0.05       0
Bank Sta=4720.1,5220.9
Exp/Cntr=0.3,0.1

Type RM Length L Ch R = 1,65906,586,586,586
BEGIN DESCRIPTION:
ELM CREEK 78.0
END DESCRIPTION:
XS GIS Cut Line= 3
      2829075.03      7079875.00      2828275.00      7079975.00
      2827474.98      7080375.01
#Sta/Elev= 30
  4151.5  527.33  4222.1  524.47  4511.8  504.49  4645.7  499.31  4736.0  497.84
  4971.7  498.91  4976.7  491.29  4977.2  490.49  4983.1  490.49  4983.6  491.29
  4988.5  495.52  5002.5  496.09  5010.9  498.58  5024.8  499.01  5055.6  498.63
  5061.2  497.02  5083.5  498.79  5150.6  499.00  5173.0  498.09  5321.0  499.31
  5322.6  499.39  5337.9  500.48  5346.3  502.93  5351.9  503.06  5368.6  506.96
  5449.7  511.09  5508.4  511.68  5569.9  510.73  5704.0  513.22  5852.2  514.55
#Mann=5,-1,0
  4151.5    0.05       0  4976.7    0.03       0  4983.6    0.05       0
  5024.8    0.16       0  5322.6    0.05       0
Bank Sta=4645.7,5321
Exp/Cntr=0.3,0.1

Type RM Length L Ch R = 1,65320,361,361,361
BEGIN DESCRIPTION:
ELM CREEK 77.0
END DESCRIPTION:
XS GIS Cut Line= 3
      2829124.99      7079725.00      2828375.00      7079425.00
      2827925.04      7079524.99
#Sta/Elev= 30
  4180.9  528.74  4213.2  527.74  4234.7  525.42  4279.2  524.17  4310.1  521.17
  4396.3  515.67  4435.3  510.90  4489.2  505.74  4543.0  501.75  4660.8  497.63
  4680.4  497.45  4697.9  495.62  4719.4  495.22  4734.2  495.25  4740.9  496.59
  4751.7  497.10  4920.0  496.12  4967.1  497.19  4979.2  494.25  4982.5  490.36
  4983.0  489.56  4988.9  489.56  4989.4  490.36  4991.2  490.36  4998.9  496.96
  5162.8  496.39  5190.6  497.63  5289.6  502.21  5376.7  508.66  5449.6  509.45
#Mann=3,-1,0
  4180.9    0.05       0  4982.5    0.03       0  4989.4    0.05       0
Bank Sta=4660.8,5190.6
Exp/Cntr=0.3,0.1

Type RM Length L Ch R = 1,64959,99,99,99
BEGIN DESCRIPTION:
Mapping XS f77908dc
END DESCRIPTION:
XS GIS Cut Line= 3
      2828906.15      7079122.81      2828468.63      7079084.61
      2828003.33      7079088.08
#Sta/Elev= 30
  4559.6  509.47  4570.8  509.73  4580.8  507.20  4588.9  504.49  4610.9  501.45
  4621.0  499.01  4641.1  497.83  4673.9  497.11  4715.3  496.56  4913.8  495.12
  4982.4  495.43  4992.4  491.82  4994.6  489.66  4995.1  488.86  5001.1  488.86
  5001.6  489.66  5003.1  489.66  5012.4  495.30  5122.4  495.68  5172.4  495.15
  5211.2  495.42  5222.4  496.63  5236.4  497.11  5262.4  497.96  5310.2  500.45
  5332.4  502.77  5372.4  504.40  5402.4  506.27  5432.4  507.41  5464.1  507.53
#Mann=7,-1,0
  4559.6    0.08       0  4715.3    0.05       0  4913.8    0.08       0
  4994.6    0.07       0  5001.6    0.08       0  5211.2    0.05       0
  5310.2    0.08       0
Bank Sta=4673.9,5236.4
Exp/Cntr=0.3,0.1

Type RM Length L Ch R = 1,64860,409,409,409
BEGIN DESCRIPTION:
Mapping XS 2a41bf4b
END DESCRIPTION:
XS GIS Cut Line= 3
      2829024.15      7079004.75      2828479.05      7078987.39
      2828088.34      7078983.93
#Sta/Elev= 30
  4429.7  511.72  4508.9  506.91  4538.9  502.75  4558.9  500.58  4576.4  499.49
  4581.4  500.06  4601.2  499.28  4719.0  496.51  4756.2  496.13  4813.8  495.94
  4893.6  495.35  4959.1  495.60  4979.6  496.14  4989.1  491.89  4995.6  487.62
  4996.1  486.82  5002.1  486.82  5002.6  487.62  5009.1  488.71  5019.1  496.24
  5039.1  495.28  5059.1  495.74  5099.1  495.54  5169.1  496.02  5209.1  495.52
  5237.7  496.13  5259.1  497.54  5329.1  503.34  5359.1  504.70  5365.8  504.61
#Mann=5,-1,0
  4429.7    0.05       0  4601.2    0.16       0  4813.8    0.05       0
  4995.6    0.03       0  5002.6    0.05       0
Bank Sta=4756.2,5237.7
Exp/Cntr=0.3,0.1

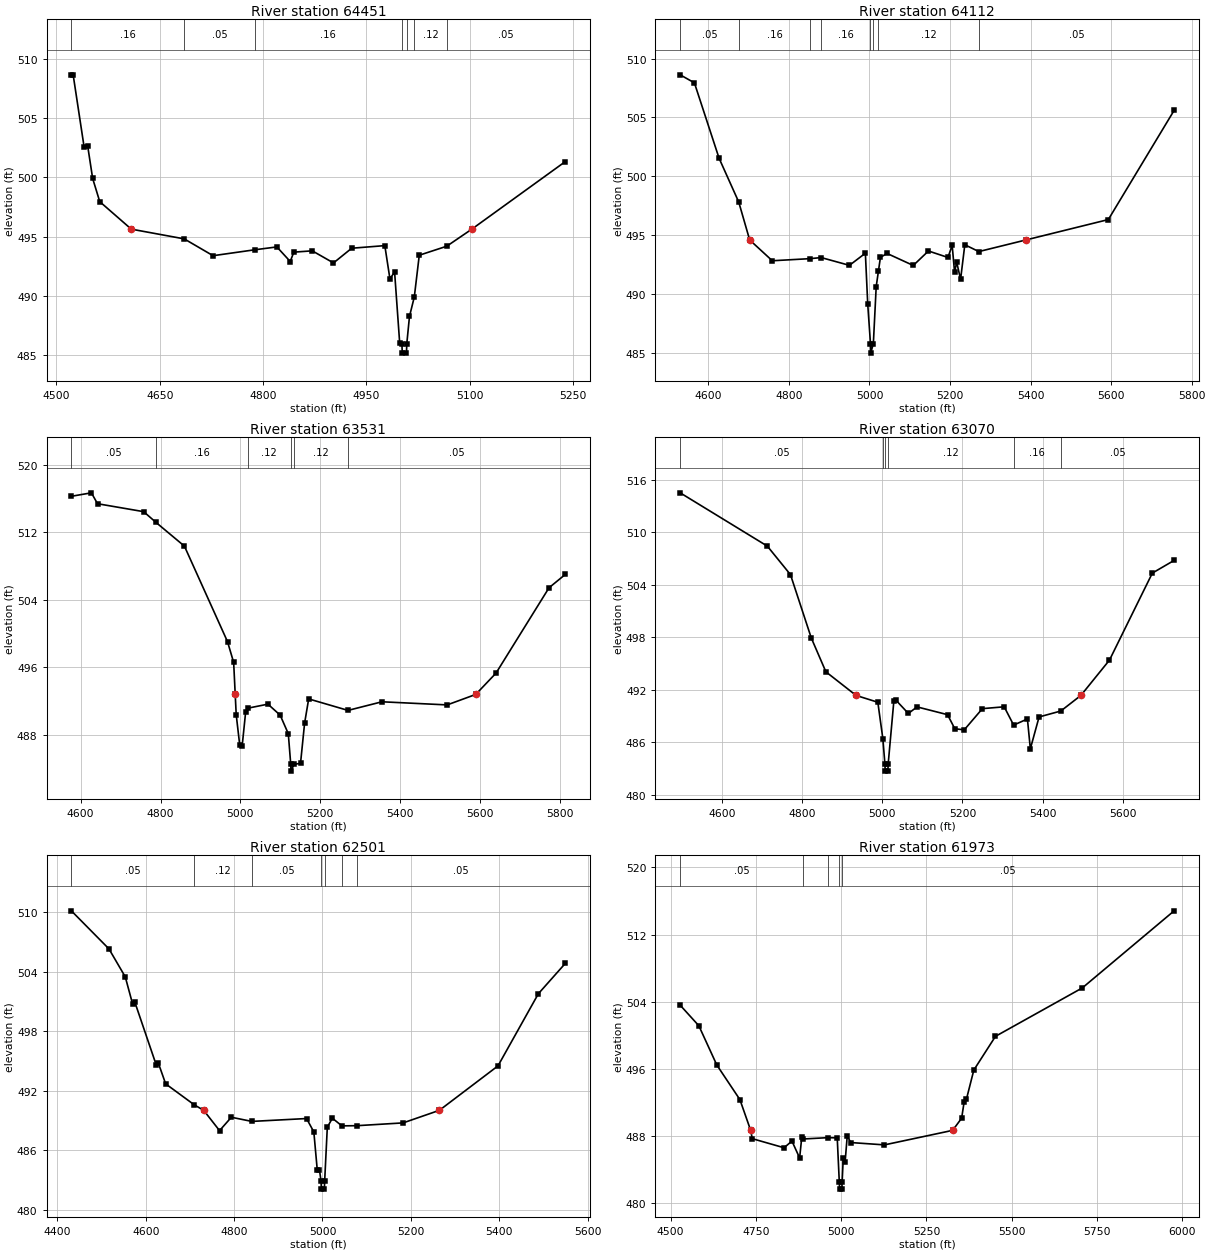
Type RM Length L Ch R = 1,64451,339,339,339
BEGIN DESCRIPTION:
ELM CREEK 75.0
END DESCRIPTION:
XS GIS Cut Line= 3
      2828725.04      7078524.99      2828288.07      7078629.75
      2828090.34      7078810.13
#Sta/Elev= 30
  4521.7  508.66  4524.3  508.66  4540.2  502.57  4545.3  502.69  4552.6  499.92
  4562.9  497.96  4608.7  495.64  4685.5  494.82  4727.4  493.40  4788.0  493.90
  4820.0  494.14  4839.4  492.91  4844.6  493.70  4871.4  493.81  4902.2  492.79
  4928.6  494.03  4976.7  494.25  4984.1  491.45  4990.9  492.02  4998.3  486.01
  5001.5  485.98  5002.0  485.18  5008.1  485.18  5008.6  485.98  5012.5  488.28
  5019.5  489.92  5026.7  493.44  5066.6  494.20  5103.0  495.64  5238.7  501.34
#Mann=7,-1,0
  4521.7    0.16       0  4685.5    0.05       0  4788.0    0.16       0
  5001.5    0.07       0  5008.6    0.16       0  5019.5    0.12       0
  5066.6    0.05       0
Bank Sta=4608.7,5103
Exp/Cntr=0.3,0.1

Type RM Length L Ch R = 1,64112,581,581,581
BEGIN DESCRIPTION:
double Mapping XS eabf44b4
END DESCRIPTION:
XS GIS Cut Line= 3
      2828697.82      7078223.49      2828270.71      7078393.64
      2827539.03      7078622.51
#Sta/Elev= 30
  4530.1  508.62  4565.4  507.94  4626.7  501.53  4675.5  497.81  4702.6  494.59
  4758.8  492.82  4853.1  493.00  4880.3  493.09  4950.3  492.43  4989.9  493.46
  4995.8  489.11  5002.6  485.77  5003.1  484.97  5009.7  485.77  5016.8  490.63
  5022.2  491.91  5027.3  493.11  5043.8  493.44  5108.8  492.42  5146.5  493.65
  5194.9  493.10  5205.4  494.13  5211.4  491.84  5216.6  492.70  5226.3  491.24
  5236.8  494.18  5271.6  493.60  5388.8  494.59  5593.1  496.32  5756.5  505.60
#Mann=8,-1,0
  4530.1    0.05       0  4675.5    0.16       0  4853.1    0.12       0
  4880.3    0.16       0  5002.6    0.07       0  5009.7    0.16       0
  5022.2    0.12       0  5271.6    0.05       0
Bank Sta=4702.6,5388.8
Exp/Cntr=0.3,0.1

Type RM Length L Ch R = 1,63531,461,461,461
BEGIN DESCRIPTION:
ELM CREEK 74.0
END DESCRIPTION:
XS GIS Cut Line= 3
      2828725.00      7077725.00      2828325.00      7077975.00
      2827574.96      7078125.01
#Sta/Elev= 30
  4576.8  516.24  4626.9  516.65  4642.3  515.36  4757.8  514.42  4788.6  513.15
  4859.8  510.34  4967.7  499.03  4983.1  496.57  4987.0  492.78  4989.5  490.37
  4998.4  486.74  5004.3  486.64  5013.1  490.69  5018.4  491.15  5068.9  491.63
  5099.5  490.33  5119.9  488.13  5126.0  484.50  5126.7  483.70  5134.1  484.50
  5150.5  484.63  5160.7  489.38  5170.9  492.25  5269.4  490.89  5354.4  491.91
  5517.6  491.54  5589.1  492.78  5640.0  495.31  5772.6  505.41  5813.4  506.99
#Mann=6,-1,0
  4576.8    0.05       0  4788.6    0.16       0  5018.4    0.12       0
  5126.0    0.07       0  5134.1    0.12       0  5269.4    0.05       0
Bank Sta=4987,5589.1
Exp/Cntr=0.3,0.1

Type RM Length L Ch R = 1,63070,569,569,569
BEGIN DESCRIPTION:
ELM CREEK 73.0
END DESCRIPTION:
XS GIS Cut Line= 3
      2828625.04      7077274.98      2828225.00      7077525.00
      2827525.02      7077824.99
#Sta/Elev= 30
  4495.3  514.52  4712.9  508.43  4770.7  505.17  4822.6  497.94  4859.1  494.07
  4934.5  491.37  4988.8  490.59  5001.3  486.44  5006.5  483.52  5007.2  482.72
  5013.9  482.72  5014.6  483.52  5028.7  490.68  5034.1  490.82  5065.0  489.31
  5086.7  490.06  5162.9  489.17  5181.0  487.56  5204.6  487.44  5249.9  489.86
  5304.3  490.07  5327.9  487.98  5362.3  488.68  5369.6  485.27  5391.4  488.91
  5445.7  489.59  5495.8  491.37  5567.2  495.41  5674.2  505.35  5728.6  506.80
#Mann=6,-1,0
  4495.3    0.05       0  5001.3    0.12       0  5006.5    0.03       0
  5014.6    0.12       0  5327.9    0.16       0  5445.7    0.05       0
Bank Sta=4934.5,5495.8
Exp/Cntr=0.3,0.1

Type RM Length L Ch R = 1,62501,528,528,528
BEGIN DESCRIPTION:
ELM CREEK 72.0
END DESCRIPTION:
XS GIS Cut Line= 3
      2828474.99      7077275.00      2827925.00      7077175.00
      2827375.02      7077275.00
#Sta/Elev= 30
  4431.7  510.14  4516.8  506.30  4553.7  503.48  4570.2  500.76  4575.3  500.94
  4623.5  494.63  4628.6  494.78  4645.1  492.69  4710.3  490.56  4731.2  490.02
  4767.1  487.97  4793.8  489.32  4840.2  488.90  4964.0  489.19  4980.5  487.84
  4988.2  484.03  4993.2  484.03  4996.8  482.87  4997.5  482.07  5004.3  482.07
  5005.0  482.87  5011.0  488.32  5022.5  489.22  5044.0  488.45  5078.3  488.47
  5182.5  488.75  5264.7  490.02  5397.3  494.50  5488.7  501.78  5549.7  504.84
#Mann=7,-1,0
  4431.7    0.05       0  4710.3    0.12       0  4840.2    0.05       0
  4996.8    0.03       0  5005.0    0.05       0  5044.0    0.12       0
  5078.3    0.05       0
Bank Sta=4731.2,5264.7
Exp/Cntr=0.3,0.1

Type RM Length L Ch R = 1,61973,571,571,571
BEGIN DESCRIPTION:
ELM CREEK 71.0
END DESCRIPTION:
XS GIS Cut Line= 3
      2828224.96      7076874.98      2827775.00      7076675.00
      2827074.97      7077325.03
#Sta/Elev= 30
  4528.1  503.58  4582.8  501.13  4635.4  496.46  4703.2  492.33  4734.7  488.67
  4739.4  487.68  4832.4  486.60  4855.7  487.39  4878.2  485.38  4884.4  487.83
  4887.2  487.64  4960.7  487.80  4988.4  487.78  4994.5  482.47  4995.2  481.67
  5002.0  481.67  5002.7  482.47  5006.1  485.40  5011.6  484.96  5017.8  488.04
  5027.6  487.22  5126.8  486.94  5326.7  488.67  5353.0  490.12  5360.4  492.07
  5367.2  492.40  5388.7  495.85  5452.2  499.87  5706.8  505.64  5975.8  514.82
#Mann=5,-1,0
  4528.1    0.05       0  4887.2    0.16       0  4960.7    0.05       0
  4994.5    0.03       0  5002.7    0.05       0
Bank Sta=4734.7,5326.7
Exp/Cntr=0.3,0.1

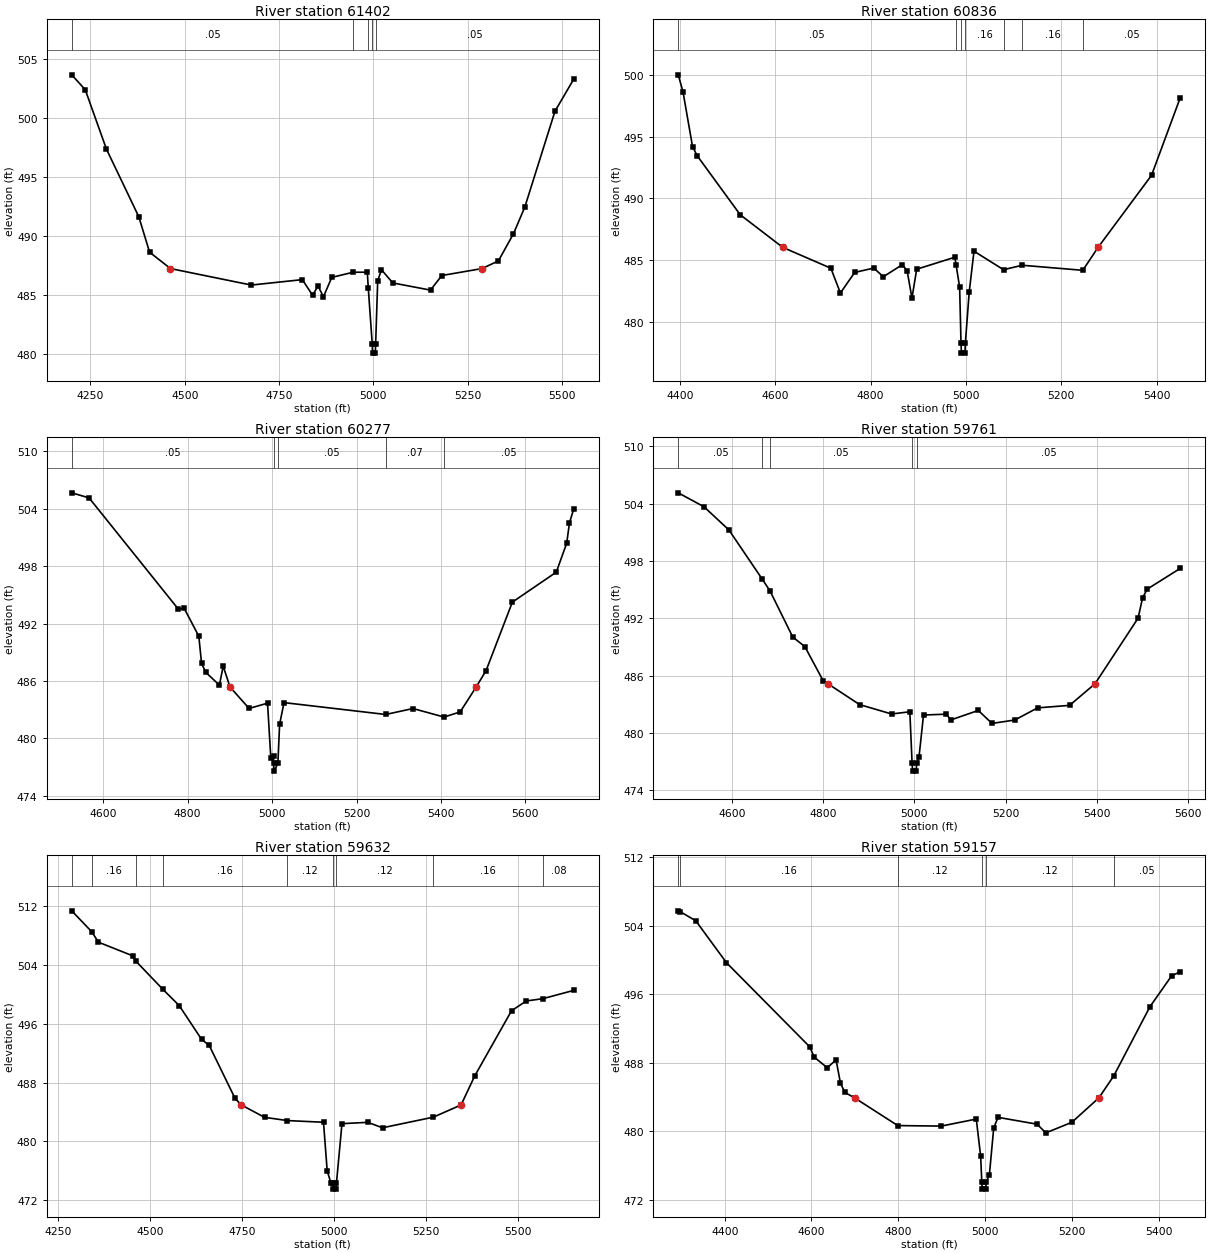
Type RM Length L Ch R = 1,61402,566,566,566
BEGIN DESCRIPTION:
ELM CREEK 70.0
END DESCRIPTION:
XS GIS Cut Line= 3
      2828325.00      7076725.00      2827825.00      7076125.00
      2827275.03      7076125.00
#Sta/Elev= 30
  4200.4  503.69  4236.2  502.42  4292.2  497.39  4378.1  491.64  4406.7  488.63
  4462.1  487.24  4676.2  485.84  4811.6  486.30  4838.9  484.97  4853.2  485.77
  4867.5  484.84  4889.7  486.49  4946.5  486.93  4983.9  486.93  4986.5  485.56
  4996.9  480.86  4997.7  480.06  5005.1  480.06  5006.0  480.86  5011.4  486.20
  5021.4  487.14  5051.4  486.02  5151.4  485.41  5181.4  486.65  5287.9  487.24
  5331.4  487.89  5371.4  490.20  5401.4  492.46  5481.4  500.60  5531.4  503.34
#Mann=5,-1,0
  4200.4    0.05       0  4946.5    0.16       0  4986.5    0.05       0
  4996.9    0.03       0  5006.0    0.05       0
Bank Sta=4462.1,5287.9
Exp/Cntr=0.3,0.1

Type RM Length L Ch R = 1,60836,559,559,559
BEGIN DESCRIPTION:
double ELM CREEK 69.0
END DESCRIPTION:
XS GIS Cut Line= 3
      2828524.98      7075575.00      2827925.00      7075575.00
      2827475.05      7075525.01
#Sta/Elev= 30
  4396.8  500.01  4406.8  498.63  4426.8  494.19  4436.8  493.44  4526.8  488.67
  4615.9  486.03  4716.8  484.34  4736.8  482.33  4766.8  484.00  4806.8  484.35
  4826.8  483.65  4866.8  484.63  4876.8  484.12  4886.8  481.92  4896.8  484.26
  4976.8  485.23  4979.4  484.60  4986.8  482.81  4989.7  478.26  4990.6  477.46
  4998.0  477.46  4998.8  478.26  5006.8  482.38  5016.9  485.72  5078.8  484.22
  5118.0  484.58  5245.0  484.17  5277.1  486.03  5389.2  491.87  5449.5  498.17
#Mann=7,-1,0
  4396.8    0.05       0  4979.4    0.16       0  4989.7    0.07       0
  4998.8    0.16       0  5078.8    0.05       0  5118.0    0.16       0
  5245.0    0.05       0
Bank Sta=4615.9,5277.1
Exp/Cntr=0.3,0.1

Type RM Length L Ch R = 1,60277,516,516,516
BEGIN DESCRIPTION:
ELM CREEK 68.0
END DESCRIPTION:
XS GIS Cut Line= 3
      2828675.03      7075074.99      2828225.00      7075175.00
      2827525.02      7074975.00
#Sta/Elev= 30
  4525.7  505.67  4566.7  505.14  4778.0  493.52  4792.1  493.59  4826.6  490.68
  4833.0  487.85  4843.3  486.90  4875.3  485.58  4884.3  487.56  4900.4  485.38
  4945.7  483.14  4989.3  483.69  4997.1  477.96  5003.6  478.12  5003.8  477.39
  5004.8  476.59  5013.8  477.39  5017.9  481.48  5028.3  483.75  5269.0  482.51
  5333.8  483.13  5407.4  482.24  5445.6  482.78  5483.3  485.38  5506.7  487.08
  5569.1  494.25  5673.1  497.38  5697.8  500.41  5704.3  502.53  5714.7  504.03
#Mann=5,-1,0
  4525.7    0.05       0  5003.8    0.03       0  5013.8    0.05       0
  5269.0    0.07       0  5407.4    0.05       0
Bank Sta=4900.4,5483.3
Exp/Cntr=0.3,0.1

Type RM Length L Ch R = 1,59761,129,129,129
BEGIN DESCRIPTION:
Mapping XS 5a280a80
END DESCRIPTION:
XS GIS Cut Line= 3
      2828645.74      7074779.07      2828409.60      7074688.78
      2827562.42      7074688.78
#Sta/Elev= 30
  4482.8  505.14  4539.3  503.68  4594.1  501.24  4667.2  496.08  4683.8  494.88
  4733.7  490.05  4760.2  489.05  4800.2  485.49  4810.8  485.16  4880.2  482.98
  4950.2  482.00  4990.2  482.23  4995.2  476.82  4996.2  476.02  5004.2  476.02
  5005.2  476.82  5010.2  477.46  5020.2  481.89  5070.2  481.98  5080.2  481.38
  5140.2  482.37  5170.2  481.01  5220.2  481.37  5270.2  482.64  5340.2  482.90
  5395.9  485.16  5490.2  492.02  5500.2  494.16  5510.2  495.06  5582.8  497.24
#Mann=5,-1,0
  4482.8    0.05       0  4667.2    0.08       0  4683.8    0.05       0
  4995.2    0.04       0  5005.2    0.05       0
Bank Sta=4810.8,5395.9
Exp/Cntr=0.3,0.1

Type RM Length L Ch R = 1,59632,475,475,475
BEGIN DESCRIPTION:
Mapping XS fc5e1421
END DESCRIPTION:
XS GIS Cut Line= 3
      2828815.81      7074720.01      2828485.99      7074570.72
      2827486.00      7074542.94
#Sta/Elev= 30
  4288.1  511.32  4342.0  508.49  4360.6  507.06  4453.0  505.22  4461.8  504.50
  4535.1  500.67  4579.5  498.46  4640.2  493.88  4661.1  493.04  4731.1  485.86
  4748.2  484.96  4811.2  483.28  4873.0  482.84  4971.2  482.61  4981.2  476.00
  4991.3  474.38  4996.2  474.33  4997.2  473.53  5005.4  473.53  5006.3  474.33
  5021.3  482.42  5091.3  482.60  5131.3  481.86  5269.1  483.30  5344.5  484.96
  5381.4  488.89  5481.4  497.75  5521.5  499.08  5566.2  499.39  5650.5  500.52
#Mann=9,-1,0
  4288.1    0.05       0  4342.0    0.16       0  4461.8    0.08       0
  4535.1    0.16       0  4873.0    0.12       0  4996.2    0.07       0
  5006.3    0.12       0  5269.1    0.16       0  5566.2    0.08       0
Bank Sta=4748.2,5344.5
Exp/Cntr=0.3,0.1

Type RM Length L Ch R = 1,59157,551,551,551
BEGIN DESCRIPTION:
ELM CREEK 66.0
END DESCRIPTION:
XS GIS Cut Line= 3
      2828775.04      7074024.99      2828075.00      7074125.00
      2827625.05      7074125.00
#Sta/Elev= 30
  4292.9  505.73  4296.8  505.65  4333.3  504.57  4404.1  499.68  4596.0  489.87
  4606.1  488.68  4636.4  487.43  4656.6  488.36  4666.7  485.65  4676.8  484.56
  4699.4  483.92  4798.8  480.69  4899.0  480.63  4979.8  481.45  4989.9  477.10
  4992.5  474.08  4993.4  473.28  5001.6  473.28  5002.6  474.08  5010.0  474.96
  5020.0  480.43  5030.0  481.65  5120.0  480.85  5140.0  479.84  5200.0  481.07
  5262.3  483.92  5296.8  486.50  5380.0  494.55  5430.0  498.15  5450.0  498.63
#Mann=6,-1,0
  4292.9    0.05       0  4296.8    0.16       0  4798.8    0.12       0
  4992.5    0.07       0  5002.6    0.12       0  5296.8    0.05       0
Bank Sta=4699.4,5262.3
Exp/Cntr=0.3,0.1

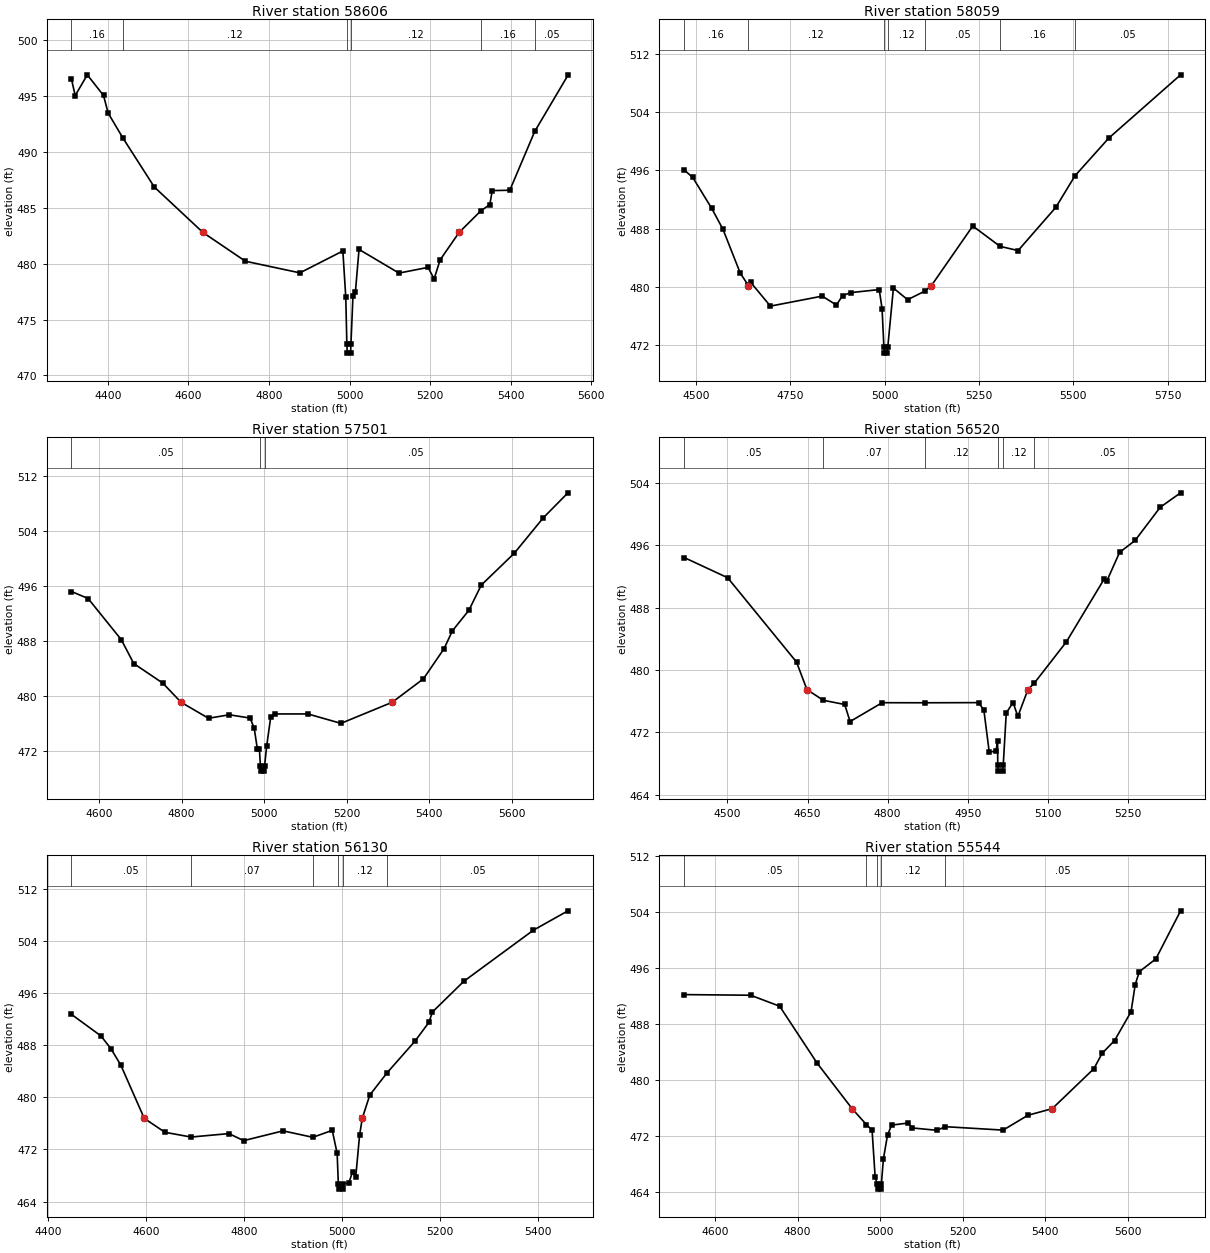
Type RM Length L Ch R = 1,58606,547,547,547
BEGIN DESCRIPTION:
ELM CREEK 65.0
END DESCRIPTION:
XS GIS Cut Line= 3
      2828742.98      7073751.29      2828075.00      7073575.00
      2827624.99      7073875.01
#Sta/Elev= 30
  4310.1  496.53  4319.3  495.06  4349.3  496.92  4389.6  495.07  4401.1  493.49
  4437.5  491.27  4515.6  486.87  4636.2  482.80  4741.7  480.22  4876.8  479.18
  4983.4  481.14  4990.6  477.00  4993.3  472.79  4994.3  471.99  5002.5  471.99
  5003.4  472.79  5008.5  477.15  5014.5  477.47  5023.5  481.28  5122.6  479.16
  5194.7  479.67  5209.8  478.64  5224.8  480.35  5271.8  482.80  5325.3  484.72
  5348.0  485.30  5354.0  486.55  5397.6  486.58  5459.4  491.85  5541.8  496.88
#Mann=6,-1,0
  4310.1    0.16       0  4437.5    0.12       0  4993.3    0.07       0
  5003.4    0.12       0  5325.3    0.16       0  5459.4    0.05       0
Bank Sta=4636.2,5271.8
Exp/Cntr=0.3,0.1

Type RM Length L Ch R = 1,58059,558,558,558
BEGIN DESCRIPTION:
ELM CREEK 64.0
END DESCRIPTION:
XS GIS Cut Line= 3
      2828275.02      7072924.99      2827825.00      7073175.00
      2827024.96      7073225.00
#Sta/Elev= 30
  4468.1  496.07  4491.0  495.04  4541.3  490.79  4571.1  487.92  4616.8  481.93
  4636.6  480.35  4638.6  480.17  4644.3  480.66  4696.9  477.39  4834.2  478.76
  4871.9  477.54  4888.0  478.82  4909.7  479.24  4985.4  479.66  4992.9  477.04
  4997.8  471.74  4998.8  470.94  5007.1  470.94  5008.0  471.74  5023.0  479.87
  5060.6  478.27  5106.9  479.46  5123.3  480.17  5233.4  488.38  5305.7  485.59
  5353.6  485.01  5453.8  490.95  5504.5  495.27  5594.1  500.44  5784.5  509.12
#Mann=7,-1,0
  4468.1    0.16       0  4636.6    0.12       0  4997.8    0.07       0
  5008.0    0.12       0  5106.9    0.05       0  5305.7    0.16       0
  5504.5    0.05       0
Bank Sta=4638.6,5123.3
Exp/Cntr=0.3,0.1

Type RM Length L Ch R = 1,57501,981,981,981
BEGIN DESCRIPTION:
ELM CREEK 63.0
END DESCRIPTION:
XS GIS Cut Line= 3
      2828175.02      7072625.00      2827725.00      7072675.00
      2826974.99      7072675.00
#Sta/Elev= 30
  4533.4  495.17  4573.7  494.15  4654.2  488.16  4684.3  484.70  4754.8  481.85
  4798.7  479.08  4865.4  476.75  4915.8  477.26  4966.1  476.78  4976.1  475.31
  4983.7  472.29  4988.7  472.29  4991.1  469.87  4992.0  469.07  5000.4  469.07
  5001.3  469.87  5006.2  472.65  5016.2  476.98  5026.2  477.38  5106.2  477.38
  5186.2  476.01  5310.6  479.08  5386.2  482.49  5436.2  486.88  5456.2  489.45
  5496.2  492.44  5526.2  496.10  5606.2  500.73  5676.2  505.86  5736.2  509.51
#Mann=3,-1,0
  4533.4    0.05       0  4991.1    0.03       0  5001.3    0.05       0
Bank Sta=4798.7,5310.6
Exp/Cntr=0.3,0.1

Type RM Length L Ch R = 1,56520,390,390,390
BEGIN DESCRIPTION:
ELM CREEK 62.0
END DESCRIPTION:
XS GIS Cut Line= 3
      2827974.98      7072275.00      2827395.18      7072237.67
      2827074.99      7072375.00
#Sta/Elev= 30
  4419.0  494.45  4500.5  491.85  4629.4  481.02  4648.9  477.48  4679.6  476.11
  4719.6  475.57  4729.6  473.38  4789.7  475.80  4869.8  475.79  4970.1  475.81
  4980.1  474.86  4990.2  469.43  5002.8  469.61  5005.8  470.84  5006.1  467.81
  5007.0  467.01  5015.4  467.01  5016.4  467.81  5022.0  474.48  5034.8  475.82
  5043.7  474.04  5062.6  477.48  5074.7  478.33  5134.5  483.61  5205.2  491.67
  5210.6  491.48  5234.2  495.11  5263.2  496.64  5310.3  500.91  5348.4  502.76
#Mann=6,-1,0
  4419.0    0.05       0  4679.6    0.07       0  4869.8    0.12       0
  5006.1    0.07       0  5016.4    0.12       0  5074.7    0.05       0
Bank Sta=4648.9,5062.6
Exp/Cntr=0.3,0.1

Type RM Length L Ch R = 1,56130,586,586,586
BEGIN DESCRIPTION:
ELM CREEK 61.0
END DESCRIPTION:
XS GIS Cut Line= 3
      2827824.98      7071975.00      2827275.00      7071925.00
      2826925.02      7072224.98
#Sta/Elev= 30
  4447.4  492.75  4507.6  489.44  4527.7  487.50  4547.8  485.00  4596.0  476.77
  4638.2  474.64  4691.4  473.91  4768.7  474.44  4798.8  473.36  4879.2  474.86
  4940.0  473.87  4979.6  474.94  4989.6  471.39  4992.0  466.71  4992.9  465.91
  5001.3  465.91  5002.3  466.71  5013.4  466.86  5021.1  468.58  5027.6  467.83
  5035.3  474.15  5040.8  476.77  5056.2  480.36  5091.6  483.79  5148.4  488.64
  5176.9  491.53  5184.0  493.12  5248.2  497.84  5389.8  505.67  5460.6  508.66
#Mann=6,-1,0
  4447.4    0.05       0  4691.4    0.07       0  4940.0    0.12       0
  4992.0    0.07       0  5002.3    0.12       0  5091.6    0.05       0
Bank Sta=4596,5040.8
Exp/Cntr=0.3,0.1

Type RM Length L Ch R = 1,55544,618,618,618
BEGIN DESCRIPTION:
ELM CREEK 60.0
END DESCRIPTION:
XS GIS Cut Line= 3
      2827974.99      7071525.00      2827525.00      7071475.00
      2826774.96      7071475.00
#Sta/Elev= 30
  4525.3  492.22  4686.3  492.13  4756.7  490.56  4847.3  482.43  4932.2  475.91
  4966.8  473.63  4980.6  472.85  4988.1  466.08  4992.9  465.20  4993.9  464.40
  5002.3  464.40  5003.2  465.20  5008.1  468.73  5018.1  472.16  5028.1  473.56
  5068.1  473.85  5078.1  473.15  5138.1  472.81  5158.0  473.33  5298.1  472.84
  5358.1  474.96  5417.2  475.91  5518.1  481.63  5538.1  483.83  5568.1  485.65
  5608.1  489.77  5618.1  493.64  5628.1  495.50  5668.1  497.32  5728.1  504.20
#Mann=5,-1,0
  4525.3    0.05       0  4966.8    0.12       0  4992.9    0.07       0
  5003.2    0.12       0  5158.0    0.05       0
Bank Sta=4932.2,5417.2
Exp/Cntr=0.3,0.1