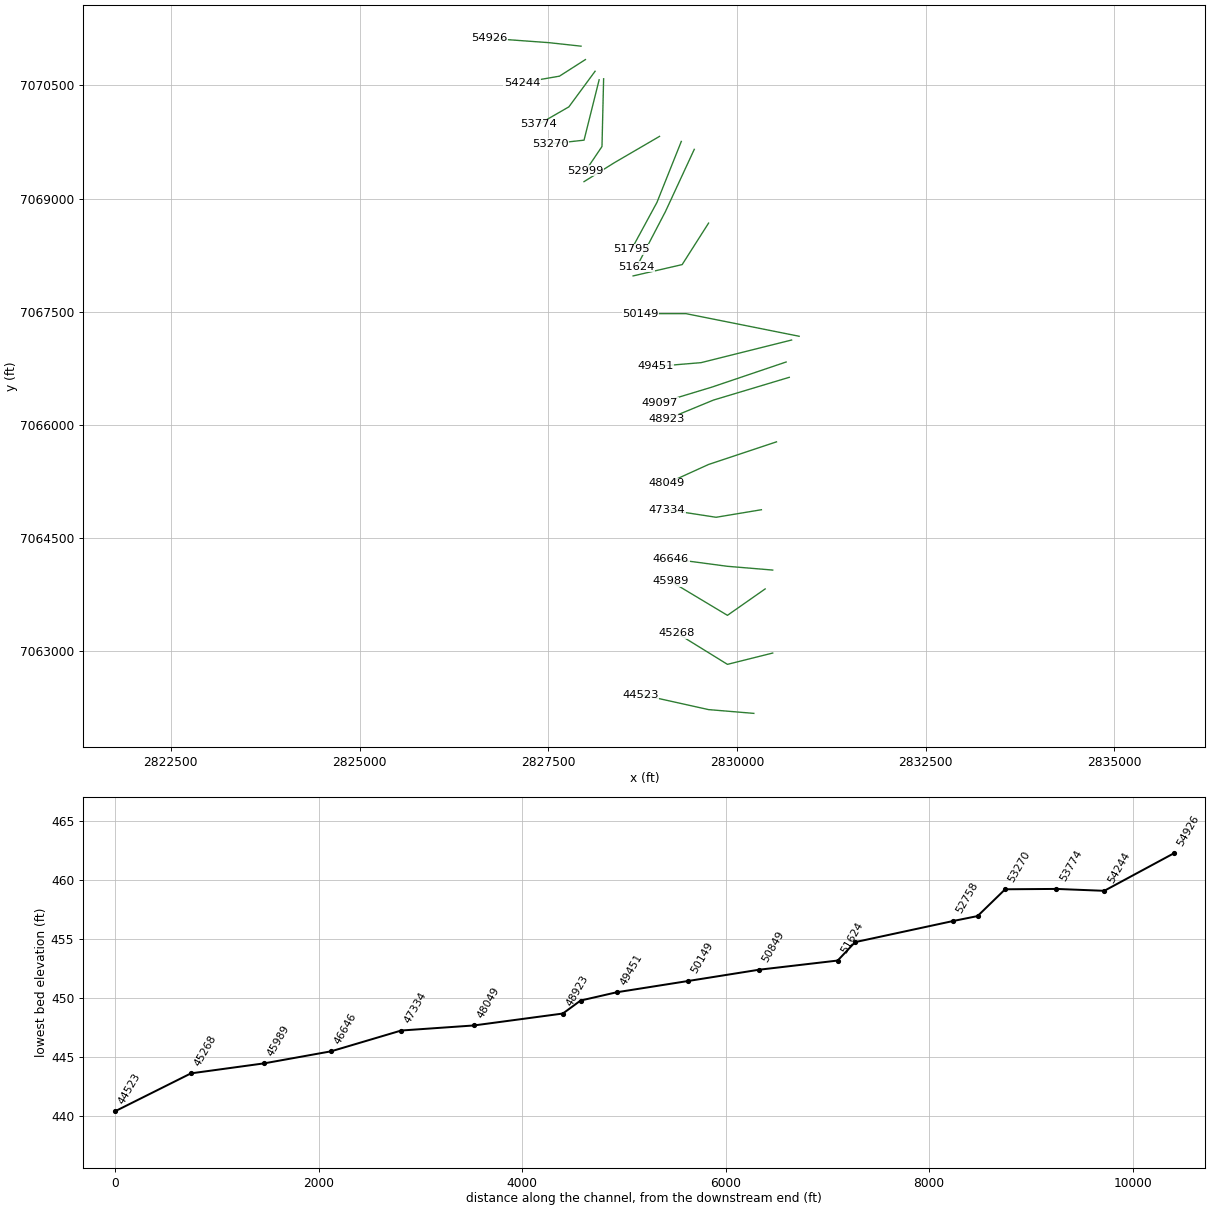
HEC-RAS study ELM CREEK.prj: ELM CREEK Base Level Engineering

--- ELM CREEK.g01 (geometry) --- (continued)

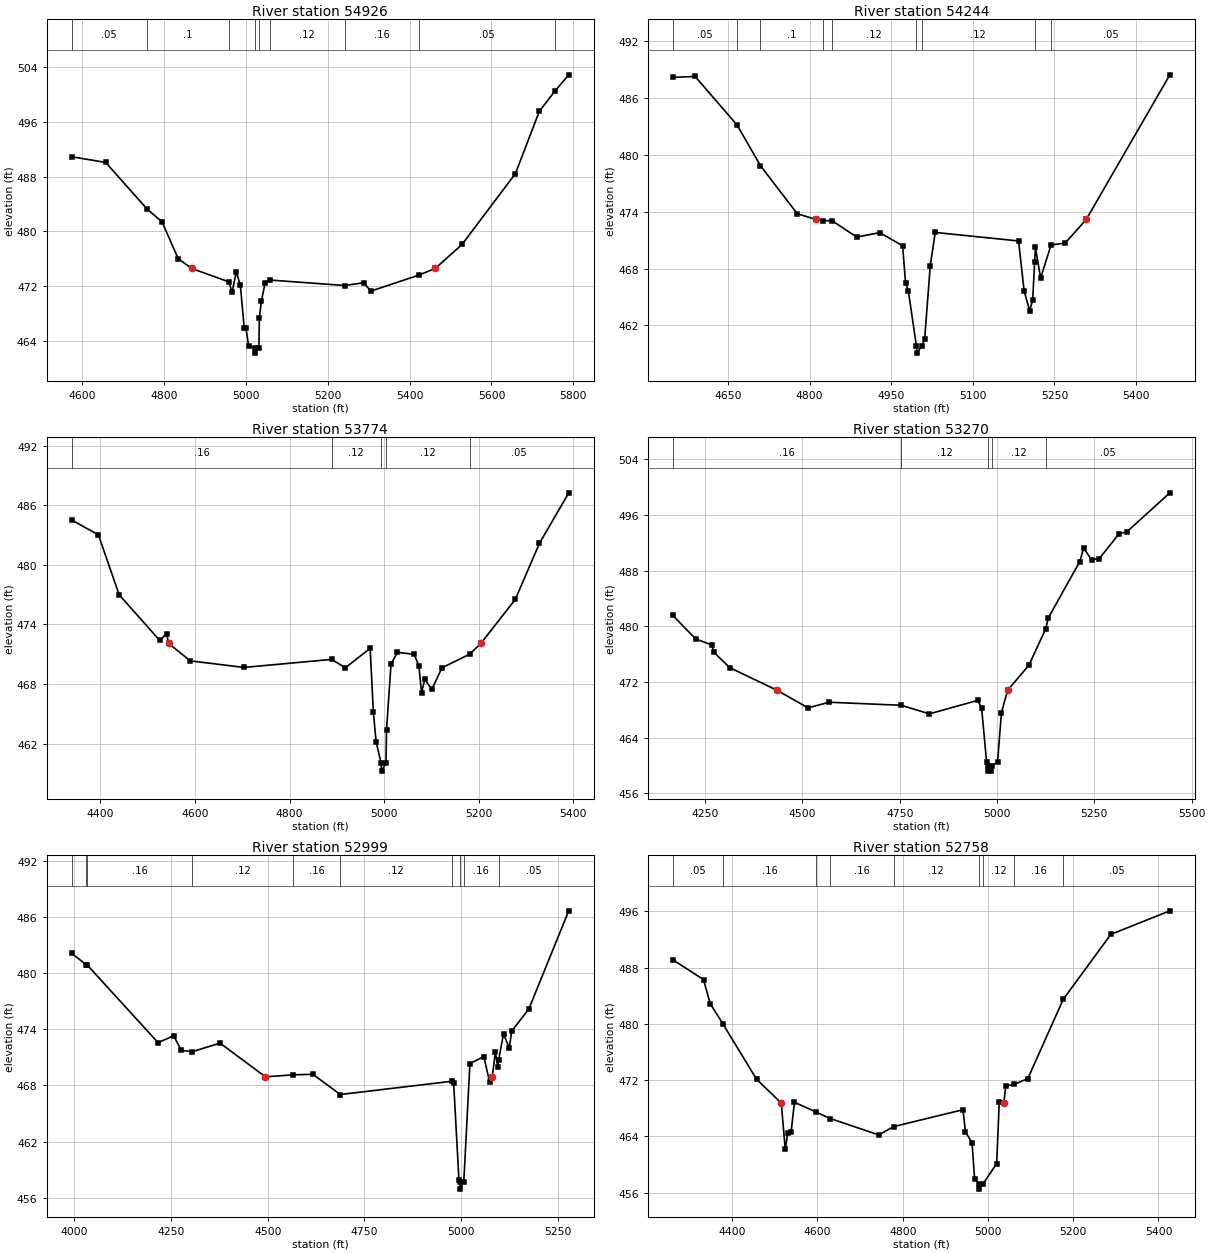
Type RM Length L Ch R = 1,54926,682,682,682
BEGIN DESCRIPTION:
ELM CREEK 59.0
END DESCRIPTION:
XS GIS Cut Line= 3
      2827934.98      7071021.22      2827511.60      7071067.50
      2826725.00      7071125.00
#Sta/Elev= 30
  4574.1  490.90  4657.3  490.08  4758.7  483.27  4795.4  481.38  4834.8  476.01
  4867.6  474.60  4958.5  472.64  4966.4  471.10  4976.5  474.10  4986.5  472.15
  4995.8  465.98  5000.0  465.98  5006.6  463.31  5021.5  463.04  5022.5  462.24
  5031.8  463.04  5033.0  467.42  5038.0  469.87  5046.7  472.41  5058.2  472.91
  5241.2  472.11  5287.4  472.51  5305.5  471.30  5421.7  473.61  5462.6  474.60
  5528.0  478.10  5658.4  488.44  5716.8  497.53  5754.7  500.47  5788.7  502.86
#Mann=9,-1,0
  4574.1    0.05       0  4758.7     0.1       0  4958.5    0.16       0
  5021.5    0.07       0  5031.8    0.16       0  5058.2    0.12       0
  5241.2    0.16       0  5421.7    0.05       0  5754.7    0.08       0
Bank Sta=4867.6,5462.6
Exp/Cntr=0.3,0.1

Type RM Length L Ch R = 1,54244,470,470,470
BEGIN DESCRIPTION:
Mapping XS 2ab2378b
END DESCRIPTION:
XS GIS Cut Line= 3
      2827993.10      7070843.35      2827649.23      7070623.47
      2827151.05      7070536.93
#Sta/Elev= 30
  4548.4  488.20  4589.7  488.30  4666.9  483.16  4709.7  478.88  4777.5  473.79
  4812.2  473.19  4825.5  473.06  4841.4  473.06  4886.6  471.33  4928.9  471.80
  4971.0  470.41  4976.4  466.52  4981.5  465.67  4996.3  459.87  4997.3  459.07
  5006.6  459.87  5011.6  460.59  5021.8  468.29  5031.0  471.82  5184.1  470.92
  5194.3  465.67  5204.4  463.57  5210.0  464.63  5213.7  468.69  5215.1  470.23
  5224.7  467.00  5243.8  470.50  5269.7  470.69  5308.5  473.19  5462.2  488.47
#Mann=9,-1,0
  4548.4    0.05       0  4666.9    0.16       0  4709.7     0.1       0
  4825.5    0.16       0  4841.4    0.12       0  4996.3    0.07       0
  5006.6    0.12       0  5213.7    0.16       0  5243.8    0.05       0
Bank Sta=4812.2,5308.5
Exp/Cntr=0.3,0.1

Type RM Length L Ch R = 1,53774,504,504,504
BEGIN DESCRIPTION:
Mapping XS 63c3dc35
END DESCRIPTION:
XS GIS Cut Line= 3
      2828121.40      7070688.77      2827774.18      7070216.56
      2827371.38      7069983.90
#Sta/Elev= 30
  4339.1  484.52  4395.9  483.02  4439.8  476.99  4525.5  472.39  4540.1  473.07
  4544.5  472.08  4590.3  470.33  4703.7  469.67  4888.9  470.48  4918.2  469.64
  4970.5  471.59  4977.3  465.16  4983.1  462.20  4993.7  460.03  4994.6  459.23
  5004.0  460.03  5005.1  463.37  5014.6  470.00  5028.2  471.19  5063.5  470.99
  5073.5  469.83  5079.2  467.13  5086.0  468.46  5100.8  467.46  5122.3  469.63
  5180.8  471.00  5204.5  472.08  5277.4  476.52  5328.5  482.17  5390.4  487.25
#Mann=5,-1,0
  4339.1    0.16       0  4888.9    0.12       0  4993.7    0.07       0
  5004.0    0.12       0  5180.8    0.05       0
Bank Sta=4544.5,5204.5
Exp/Cntr=0.3,0.1

Type RM Length L Ch R = 1,53270,271,271,271
BEGIN DESCRIPTION:
ELM CREEK 57.0
END DESCRIPTION:
XS GIS Cut Line= 3
      2828175.00      7070575.00      2827975.00      7069775.00
      2827524.99      7069725.00
#Sta/Elev= 30
  4166.6  481.59  4225.9  478.19  4267.1  477.34  4272.3  476.29  4313.5  474.06
  4434.7  470.82  4514.5  468.29  4568.6  469.10  4753.8  468.66  4826.3  467.43
  4950.0  469.36  4960.3  468.29  4973.2  460.49  4975.8  460.00  4976.7  459.20
  4985.2  459.20  4986.1  460.00  5001.3  460.50  5011.3  467.61  5027.2  470.82
  5081.8  474.42  5125.0  479.64  5132.1  481.26  5212.6  489.31  5222.6  491.25
  5242.8  489.56  5262.9  489.75  5313.2  493.29  5333.3  493.58  5444.0  499.19
#Mann=5,-1,0
  4166.6    0.16       0  4753.8    0.12       0  4975.8    0.07       0
  4986.1    0.12       0  5125.0    0.05       0
Bank Sta=4434.7,5027.2
Exp/Cntr=0.3,0.1

Type RM Length L Ch R = 1,52999,241,241,241
BEGIN DESCRIPTION:
XS3689A
END DESCRIPTION:
XS GIS Cut Line= 3
      2828234.45      7070588.91      2828212.75      7069690.49
      2827995.97      7069369.65
#Sta/Elev= 30
  3992.4  482.11  4029.9  480.91  4032.2  480.89  4216.4  472.56  4256.4  473.31
  4276.4  471.74  4304.7  471.60  4376.4  472.52  4493.9  468.92  4564.9  469.13
  4616.5  469.19  4687.6  467.03  4976.9  468.45  4980.7  468.22  4994.3  457.94
  4996.6  457.73  4997.5  456.93  5006.9  457.73  5022.7  470.33  5058.7  471.08
  5073.7  468.35  5080.4  468.92  5088.6  471.55  5094.7  470.00  5096.9  470.70
  5109.6  473.50  5124.6  471.99  5130.6  473.78  5175.3  476.18  5278.3  486.64
#Mann=10,-1,0
  3992.4    0.16       0  4029.9    0.05       0  4032.2    0.16       0
  4304.7    0.12       0  4564.9    0.16       0  4687.6    0.12       0
  4976.9    0.16       0  4996.6    0.07       0  5006.9    0.16       0
  5096.9    0.05       0
Bank Sta=4493.9,5080.4
Exp/Cntr=0.3,0.1

Type RM Length L Ch R = 1,52758,963,963,963
BEGIN DESCRIPTION:
double ELM CREEK 56.0
END DESCRIPTION:
XS GIS Cut Line= 3
      2828975.02      7069825.01      2828375.00      7069475.00
      2827975.03      7069225.02
#Sta/Elev= 30
  4260.4  489.14  4332.8  486.30  4348.5  482.89  4378.0  480.03  4457.2  472.14
  4515.1  468.76  4524.6  462.15  4530.4  464.55  4538.3  464.68  4546.1  468.86
  4596.8  467.47  4630.0  466.55  4743.8  464.22  4778.6  465.40  4941.4  467.80
  4947.2  464.64  4962.7  463.12  4968.6  458.01  4978.8  457.31  4979.7  456.51
  4989.1  457.31  5020.5  460.15  5026.4  468.84  5037.2  468.74  5041.7  471.18
  5061.3  471.40  5093.6  472.23  5176.5  483.49  5288.2  492.73  5426.7  496.08
#Mann=9,-1,0
  4260.4    0.05       0  4378.0    0.16       0  4596.8    0.12       0
  4630.0    0.16       0  4778.6    0.12       0  4978.8    0.07       0
  4989.1    0.12       0  5061.3    0.16       0  5176.5    0.05       0
Bank Sta=4515.1,5037.2
Exp/Cntr=0.3,0.1

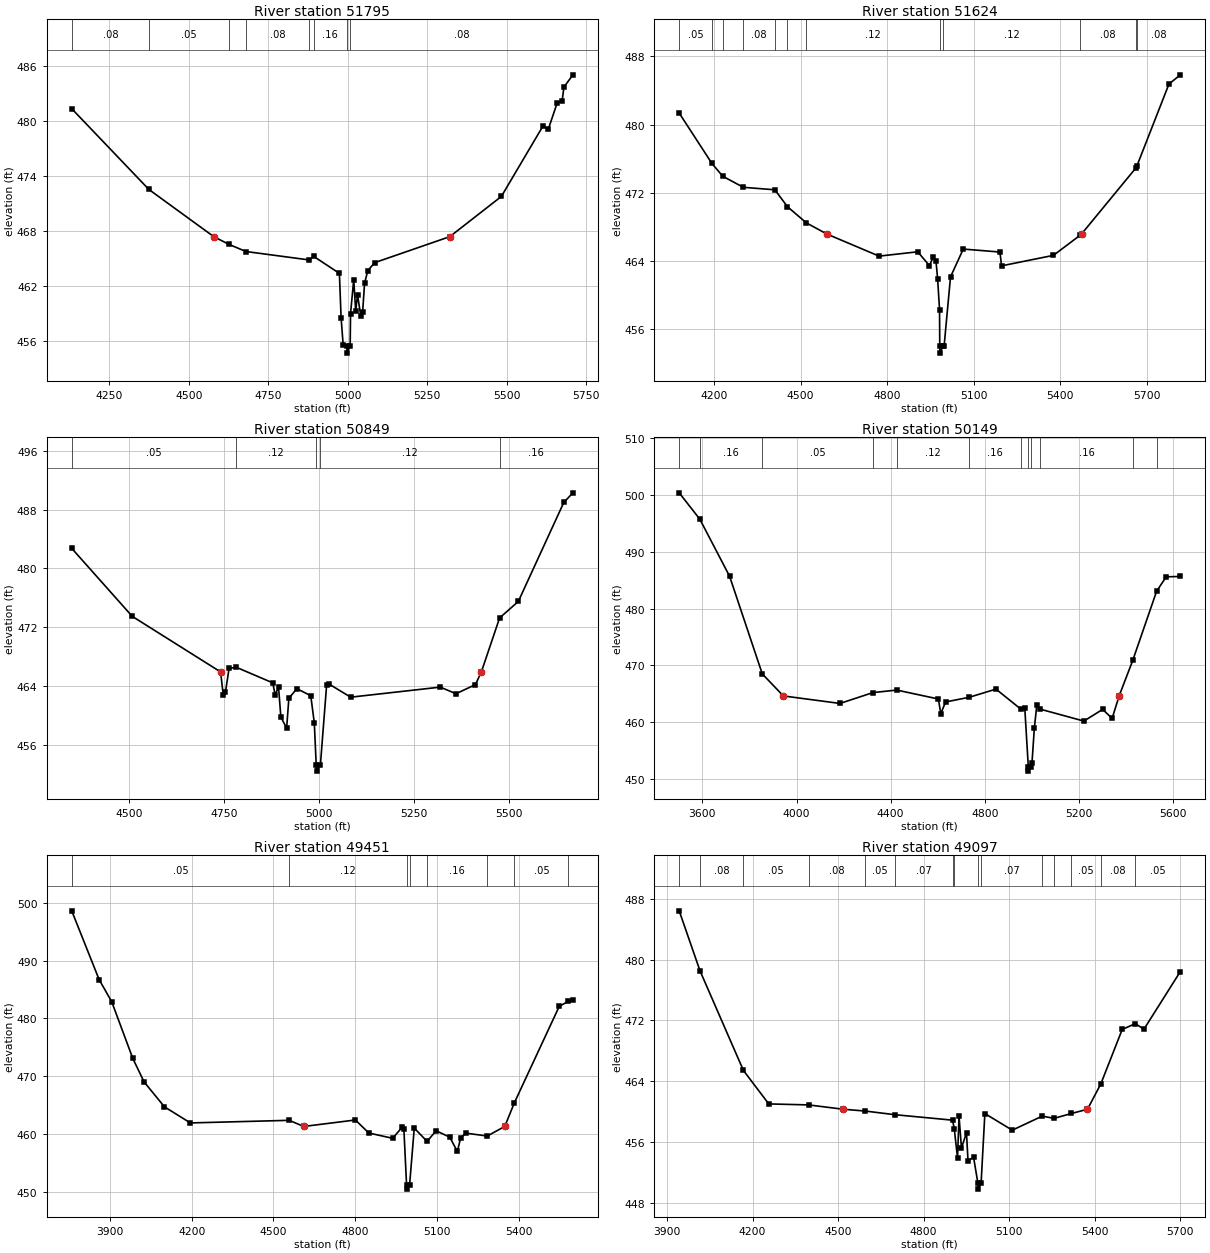
Type RM Length L Ch R = 1,51795,171,171,171
BEGIN DESCRIPTION:
ELM CREEK 55.0
END DESCRIPTION:
XS GIS Cut Line= 3
      2829263.76      7069758.20      2828940.85      7068949.19
      2828604.66      7068328.80
#Sta/Elev= 30
  4131.5  481.35  4374.3  472.55  4578.4  467.41  4626.7  466.56  4679.6  465.79
  4879.1  464.87  4892.3  465.27  4973.6  463.41  4979.0  458.56  4985.6  455.56
  4996.7  455.52  4997.5  454.72  5007.5  455.52  5008.7  459.03  5018.7  462.72
  5024.9  459.30  5030.6  461.08  5041.1  458.73  5046.7  459.20  5052.8  462.32
  5062.9  463.71  5084.8  464.58  5321.0  467.41  5483.2  471.79  5614.4  479.48
  5630.6  479.09  5658.2  481.92  5674.4  482.21  5680.0  483.70  5708.2  485.04
#Mann=8,-1,0
  4131.5    0.08       0  4374.3    0.05       0  4626.7    0.16       0
  4679.6    0.08       0  4879.1    0.12       0  4892.3    0.16       0
  4996.7    0.07       0  5007.5    0.08       0
Bank Sta=4578.4,5321
Exp/Cntr=0.3,0.1

Type RM Length L Ch R = 1,51624,775,775,775
BEGIN DESCRIPTION:
ELM CREEK 54.0
END DESCRIPTION:
XS GIS Cut Line= 3
      2829435.64      7069653.18      2829053.70      7068828.53
      2828671.75      7068095.02
#Sta/Elev= 30
  4079.8  481.35  4193.2  475.43  4230.6  473.93  4302.1  472.63  4411.1  472.34
  4454.9  470.35  4520.1  468.46  4591.1  467.15  4772.1  464.55  4906.0  465.06
  4946.4  463.44  4959.4  464.41  4969.3  463.92  4974.8  461.92  4981.5  458.28
  4982.3  453.96  4983.1  453.16  4993.2  453.96  4997.4  454.01  5019.5  462.11
  5063.7  465.38  5190.7  465.03  5196.3  463.41  5375.9  464.64  5468.4  467.00
  5473.4  467.15  5662.7  474.95  5665.0  475.13  5776.1  484.76  5815.6  485.84
#Mann=12,-1,0
  4079.8    0.05       0  4193.2    0.16       0  4230.6    0.05       0
  4302.1    0.08       0  4411.1    0.05       0  4454.9    0.08       0
  4520.1    0.12       0  4982.3    0.07       0  4993.2    0.12       0
  5468.4    0.08       0  5662.7    0.16       0  5665.0    0.08       0
Bank Sta=4591.1,5473.4
Exp/Cntr=0.3,0.1

Type RM Length L Ch R = 1,50849,700,700,700
BEGIN DESCRIPTION:
ELM CREEK 53.0
END DESCRIPTION:
XS GIS Cut Line= 3
      2829625.02      7068675.04      2829275.00      7068125.00
      2828625.05      7067975.01
#Sta/Elev= 30
  4348.6  482.72  4507.8  473.46  4740.4  465.89  4747.4  462.71  4753.3  463.18
  4762.7  466.37  4781.8  466.52  4877.8  464.40  4883.7  462.80  4893.0  463.78
  4899.0  459.75  4914.2  458.23  4920.1  462.31  4941.3  463.61  4977.7  462.65
  4987.0  458.97  4992.1  453.18  4992.9  452.38  5003.0  453.18  5019.4  464.05
  5024.5  464.28  5082.7  462.45  5318.7  463.82  5359.8  462.92  5411.1  464.16
  5426.7  465.89  5474.7  473.24  5524.0  475.49  5643.7  488.97  5667.6  490.28
#Mann=5,-1,0
  4348.6    0.05       0  4781.8    0.12       0  4992.1    0.07       0
  5003.0    0.12       0  5474.7    0.16       0
Bank Sta=4740.4,5426.7
Exp/Cntr=0.3,0.1

Type RM Length L Ch R = 1,50149,698,698,698
BEGIN DESCRIPTION:
double ELM CREEK 52.0
END DESCRIPTION:
XS GIS Cut Line= 3
      2830825.03      7067174.99      2829325.00      7067475.00
      2828725.04      7067475.00
#Sta/Elev= 30
  3501.4  500.35  3589.3  495.70  3715.6  485.68  3854.4  468.52  3944.0  464.64
  4184.7  463.32  4324.7  465.23  4426.2  465.67  4602.8  464.10  4613.0  461.52
  4633.4  463.58  4733.4  464.40  4847.6  465.84  4955.1  462.26  4969.9  462.57
  4984.9  452.22  4985.6  451.42  4995.8  452.22  5000.5  452.82  5010.7  459.01
  5020.9  462.96  5035.1  462.32  5221.1  460.22  5301.1  462.28  5341.1  460.68
  5370.9  464.64  5428.7  470.88  5530.4  483.07  5571.1  485.58  5631.1  485.65
#Mann=12,-1,0
  3501.4    0.05       0  3589.3    0.16       0  3854.4    0.05       0
  4324.7    0.07       0  4426.2    0.12       0  4733.4    0.16       0
  4955.1    0.12       0  4984.9    0.07       0  4995.8    0.12       0
  5035.1    0.16       0  5428.7    0.05       0  5530.4    0.12       0
Bank Sta=3944,5370.9
Exp/Cntr=0.3,0.1

Type RM Length L Ch R = 1,49451,354,354,354
BEGIN DESCRIPTION:
double ELM CREEK 51.0
END DESCRIPTION:
XS GIS Cut Line= 3
      2830725.04      7067125.01      2829525.00      7066825.00
      2828924.95      7066775.00
#Sta/Elev= 30
  3759.6  498.61  3860.1  486.72  3906.5  482.87  3983.8  473.07  4025.1  469.02
  4099.8  464.71  4195.1  461.92  4557.3  462.37  4611.3  461.31  4800.7  462.43
  4849.7  460.18  4937.3  459.26  4973.4  461.25  4978.5  460.83  4988.3  451.27
  4989.0  450.47  4999.6  451.27  5016.6  461.03  5063.6  458.73  5096.9  460.57
  5147.1  459.45  5174.7  456.98  5187.2  459.40  5207.3  460.14  5284.7  459.66
  5348.7  461.31  5384.0  465.41  5548.5  482.07  5582.4  482.98  5598.7  483.18
#Mann=8,-1,0
  3759.6    0.05       0  4557.3    0.12       0  4988.3    0.07       0
  4999.6    0.12       0  5063.6    0.16       0  5284.7    0.07       0
  5384.0    0.05       0  5582.4    0.16       0
Bank Sta=4611.3,5348.7
Exp/Cntr=0.3,0.1

Type RM Length L Ch R = 1,49097,174,174,174
BEGIN DESCRIPTION:
Mapping XS c46c048e
END DESCRIPTION:
XS GIS Cut Line= 3
      2830652.64      7066833.74      2829668.28      7066500.41
      2828980.82      7066292.09
#Sta/Elev= 30
  3942.7  486.45  4015.6  478.55  4167.8  465.42  4256.9  461.00  4396.4  460.87
  4517.8  460.30  4595.4  460.06  4699.1  459.58  4901.4  458.86  4907.4  457.73
  4918.8  453.90  4924.1  459.36  4932.6  455.20  4950.3  457.18  4955.6  453.48
  4974.9  454.01  4990.2  450.57  4990.9  449.77  5001.5  450.57  5014.7  459.73
  5110.8  457.54  5215.7  459.39  5257.7  459.10  5318.5  459.74  5374.6  460.30
  5421.3  463.63  5496.4  470.82  5542.3  471.58  5572.7  470.85  5700.3  478.45
#Mann=15,-1,0
  3942.7    0.05       0  4015.6    0.08       0  4167.8    0.05       0
  4396.4    0.08       0  4595.4    0.05       0  4699.1    0.07       0
  4901.4    0.08       0  4907.4    0.07       0  4990.2    0.07       0
  5001.5    0.07       0  5215.7    0.12       0  5257.7    0.07       0
  5318.5    0.05       0  5421.3    0.08       0  5542.3    0.05       0
Bank Sta=4517.8,5374.6
Exp/Cntr=0.3,0.1

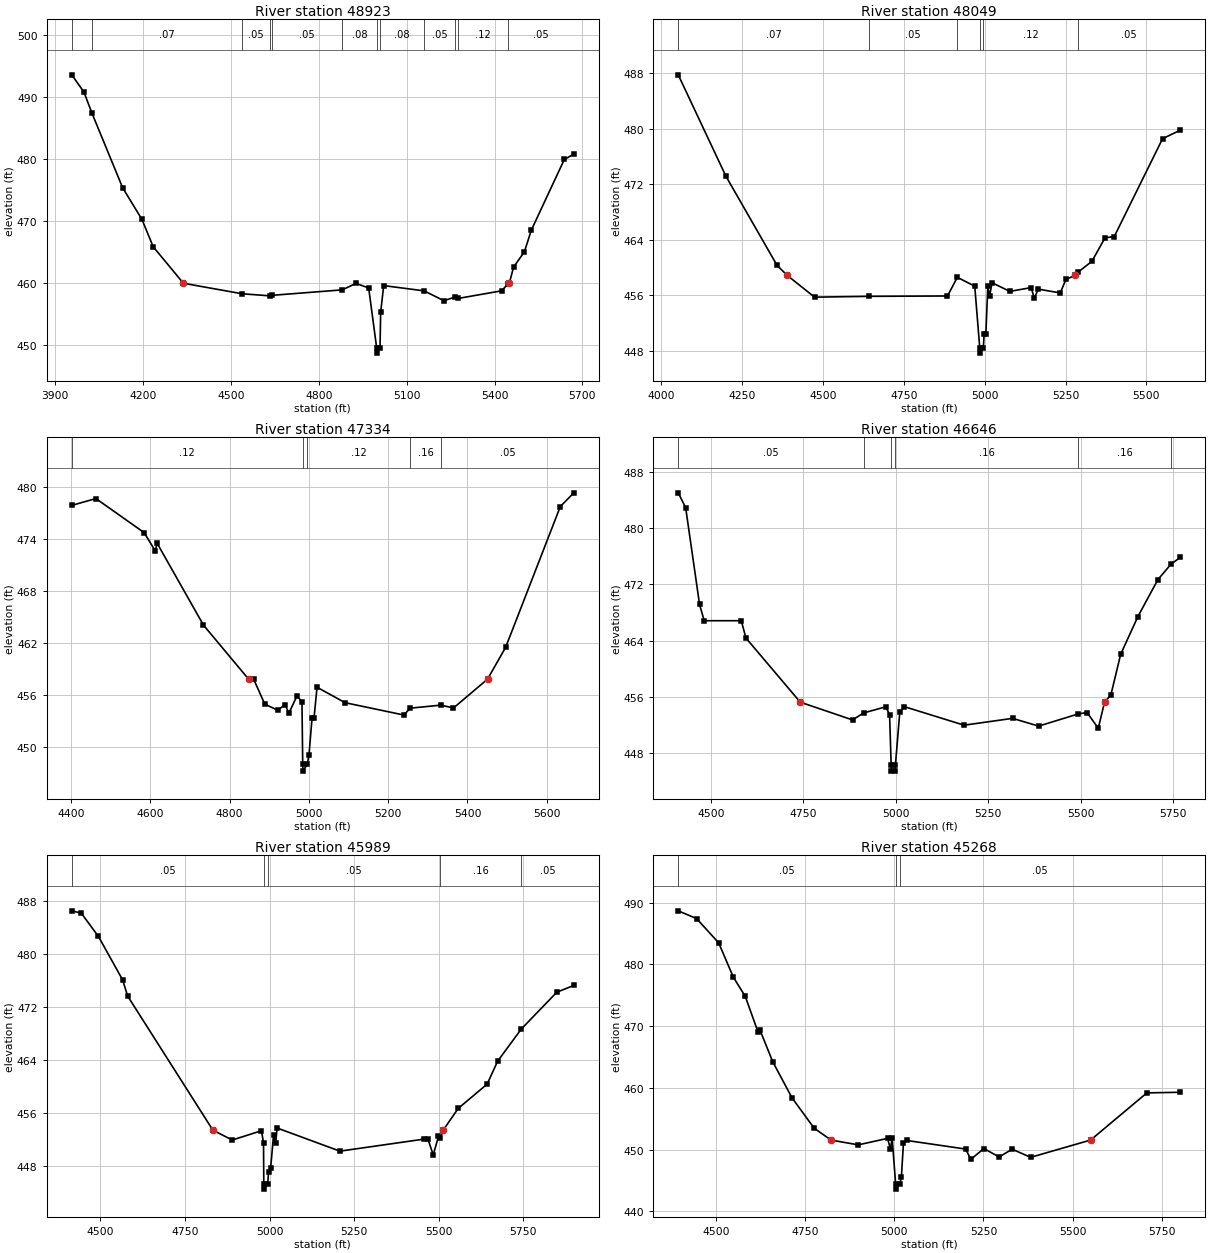
Type RM Length L Ch R = 1,48923,874,874,874
BEGIN DESCRIPTION:
ELM CREEK 50.0
END DESCRIPTION:
XS GIS Cut Line= 3
      2830694.32      7066630.62      2829689.12      7066328.53
      2829075.00      7066075.00
#Sta/Elev= 30
  3956.7  493.59  3998.3  490.80  4024.8  487.50  4130.4  475.36  4196.1  470.27
  4234.7  465.84  4337.7  459.95  4538.3  458.25  4634.6  457.91  4640.3  458.00
  4880.1  458.88  4926.8  459.92  4970.3  459.19  4997.7  449.47  4998.4  448.67
  5009.0  449.47  5011.2  455.28  5021.6  459.57  5159.6  458.72  5227.1  457.13
  5265.7  457.73  5276.0  457.50  5424.5  458.73  5445.2  459.84  5450.3  459.95
  5465.1  462.57  5501.7  465.01  5525.6  468.53  5638.2  479.93  5670.7  480.79
#Mann=12,-1,0
  3956.7    0.12       0  4024.8    0.07       0  4538.3    0.05       0
  4634.6    0.07       0  4640.3    0.05       0  4880.1    0.08       0
  4997.7    0.07       0  5009.0    0.08       0  5159.6    0.05       0
  5265.7    0.08       0  5276.0    0.12       0  5445.2    0.05       0
Bank Sta=4337.7,5450.3
Exp/Cntr=0.3,0.1

Type RM Length L Ch R = 1,48049,715,715,715
BEGIN DESCRIPTION:
ELM CREEK 49.0
END DESCRIPTION:
XS GIS Cut Line= 3
      2830525.04      7065775.01      2829625.00      7065475.00
      2829074.98      7065224.99
#Sta/Elev= 30
  4052.1  487.79  4199.7  473.16  4357.8  460.31  4389.2  458.87  4473.8  455.73
  4642.1  455.85  4884.9  455.90  4915.4  458.59  4969.2  457.31  4984.6  448.46
  4985.3  447.66  4995.9  448.46  4998.2  450.45  5003.6  450.45  5009.6  457.30
  5015.1  455.91  5022.8  457.81  5077.7  456.56  5143.6  457.11  5153.5  455.57
  5165.6  456.89  5233.7  456.34  5251.3  458.30  5280.1  458.87  5288.1  459.31
  5331.5  460.89  5372.1  464.29  5400.7  464.47  5550.1  478.58  5605.0  479.81
#Mann=6,-1,0
  4052.1    0.07       0  4642.1    0.05       0  4915.4    0.12       0
  4984.6    0.07       0  4995.9    0.12       0  5288.1    0.05       0
Bank Sta=4389.2,5280.1
Exp/Cntr=0.3,0.1

Type RM Length L Ch R = 1,47334,688,688,688
BEGIN DESCRIPTION:
ELM CREEK 48.0
END DESCRIPTION:
XS GIS Cut Line= 3
      2830325.01      7064875.00      2829725.00      7064775.00
      2829075.03      7064874.99
#Sta/Elev= 30
  4402.3  477.87  4463.1  478.66  4584.8  474.73  4612.7  472.64  4617.7  473.49
  4734.3  464.07  4848.2  457.83  4861.1  457.81  4888.9  454.96  4921.9  454.24
  4939.6  454.91  4949.8  453.92  4970.0  455.89  4982.7  455.24  4984.6  448.03
  4985.3  447.23  4996.0  448.03  5000.4  449.07  5008.1  453.37  5013.1  453.37
  5020.7  456.90  5091.5  455.12  5239.5  453.70  5255.9  454.49  5333.1  454.84
  5364.7  454.51  5450.5  457.83  5496.2  461.50  5634.1  477.74  5668.2  479.32
#Mann=5,-1,0
  4402.3    0.12       0  4984.6    0.07       0  4996.0    0.12       0
  5255.9    0.16       0  5333.1    0.05       0
Bank Sta=4848.2,5450.5
Exp/Cntr=0.3,0.1

Type RM Length L Ch R = 1,46646,657,657,657
BEGIN DESCRIPTION:
ELM CREEK 47.0
END DESCRIPTION:
XS GIS Cut Line= 3
      2830475.04      7064075.00      2829875.00      7064125.00
      2829124.95      7064225.01
#Sta/Elev= 30
  4411.2  485.03  4431.3  482.92  4468.9  469.16  4481.5  466.85  4581.8  466.85
  4594.4  464.39  4741.5  455.27  4882.9  452.75  4912.9  453.74  4973.2  454.62
  4983.2  453.48  4987.5  446.27  4988.2  445.47  4998.3  445.47  4998.9  446.27
  5010.8  453.88  5023.4  454.63  5184.8  452.00  5316.0  452.97  5386.6  451.87
  5494.4  453.61  5517.7  453.80  5548.0  451.56  5564.9  455.27  5582.1  456.30
  5608.5  462.07  5655.2  467.44  5709.4  472.70  5744.5  474.87  5770.0  475.86
#Mann=6,-1,0
  4411.2    0.05       0  4912.9    0.16       0  4987.5    0.03       0
  4998.9    0.16       0  5494.4    0.16       0  5744.5    0.05       0
Bank Sta=4741.5,5564.9
Exp/Cntr=0.3,0.1

Type RM Length L Ch R = 1,45989,721,721,721
BEGIN DESCRIPTION:
ELM CREEK 46.0
END DESCRIPTION:
XS GIS Cut Line= 3
      2830374.98      7063824.99      2829875.00      7063475.00
      2829125.04      7063924.98
#Sta/Elev= 30
  4415.2  486.52  4443.5  486.16  4494.1  482.64  4565.6  476.08  4580.4  473.64
  4832.6  453.36  4889.9  451.87  4976.2  453.28  4982.3  451.45  4983.1  445.25
  4983.8  444.45  4994.6  445.25  4997.2  446.99  5003.3  447.61  5012.0  452.62
  5018.1  451.39  5022.5  453.69  5208.2  450.19  5457.0  452.01  5468.7  451.98
  5484.2  449.63  5499.8  452.41  5504.8  452.11  5513.7  453.36  5558.1  456.65
  5643.6  460.32  5674.7  463.79  5744.5  468.64  5849.6  474.21  5900.1  475.25
#Mann=5,-1,0
  4415.2    0.05       0  4983.1    0.03       0  4994.6    0.05       0
  5504.8    0.16       0  5744.5    0.05       0
Bank Sta=4832.6,5513.7
Exp/Cntr=0.3,0.1

Type RM Length L Ch R = 1,45268,745,745,745
BEGIN DESCRIPTION:
ELM CREEK 45.0
END DESCRIPTION:
XS GIS Cut Line= 3
      2830475.00      7062975.00      2829875.00      7062825.00
      2829202.68      7063240.85
#Sta/Elev= 30
  4393.5  488.68  4445.0  487.42  4506.9  483.50  4548.1  477.94  4581.6  474.82
  4617.7  469.00  4622.8  469.38  4658.9  464.21  4713.0  458.37  4774.9  453.47
  4822.2  451.55  4898.6  450.77  4981.0  451.82  4988.8  450.14  4993.9  451.84
  5003.6  444.40  5004.2  443.60  5015.1  444.40  5019.7  445.49  5025.5  451.04
  5035.0  451.48  5200.1  450.09  5214.7  448.43  5251.3  450.17  5294.2  448.81
  5330.5  450.07  5382.5  448.75  5550.8  451.55  5708.7  459.19  5802.5  459.29
#Mann=3,-1,0
  4393.5    0.05       0  5003.6    0.03       0  5015.1    0.05       0
Bank Sta=4822.2,5550.8
Exp/Cntr=0.3,0.1

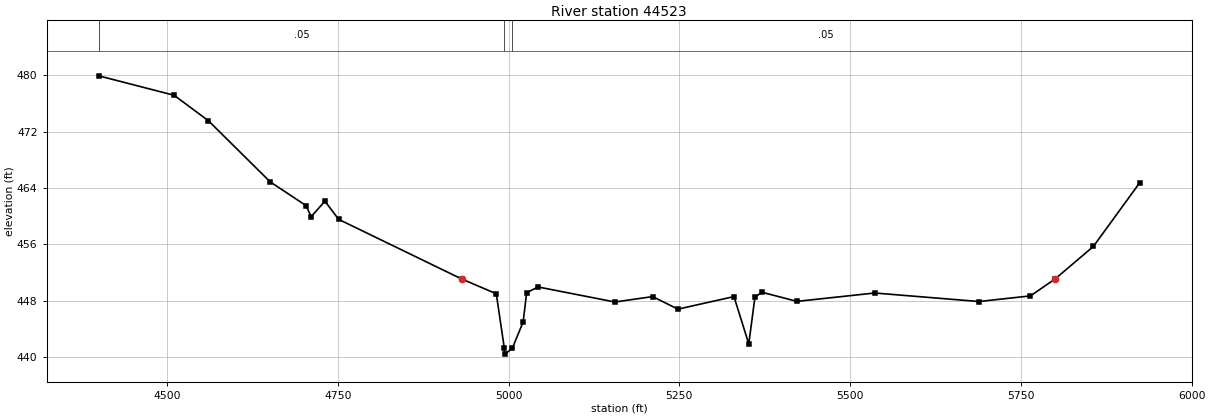
Type RM Length L Ch R = 1,44523,714,714,714
BEGIN DESCRIPTION:
double ELM CREEK 44.0
END DESCRIPTION:
XS GIS Cut Line= 3
      2830224.97      7062175.00      2829625.00      7062225.00
      2828725.00      7062425.00
#Sta/Elev= 30
  4400.1  479.91  4510.4  477.15  4560.6  473.54  4650.9  464.87  4703.6  461.48
  4711.1  459.91  4731.2  462.11  4751.3  459.53  4931.2  451.07  4982.1  448.96
  4993.9  441.19  4994.5  440.39  5005.4  441.19  5021.4  444.97  5026.5  449.10
  5043.1  449.93  5155.8  447.79  5210.9  448.56  5248.0  446.78  5330.0  448.56
  5351.7  441.84  5360.7  448.48  5370.9  449.18  5422.1  447.88  5536.1  449.07
  5688.5  447.86  5764.0  448.66  5800.2  451.07  5856.2  455.69  5924.1  464.75
#Mann=3,-1,0
  4400.1    0.05       0  4993.9    0.03       0  5005.4    0.05       0
Bank Sta=4931.2,5800.2
Exp/Cntr=0.3,0.1