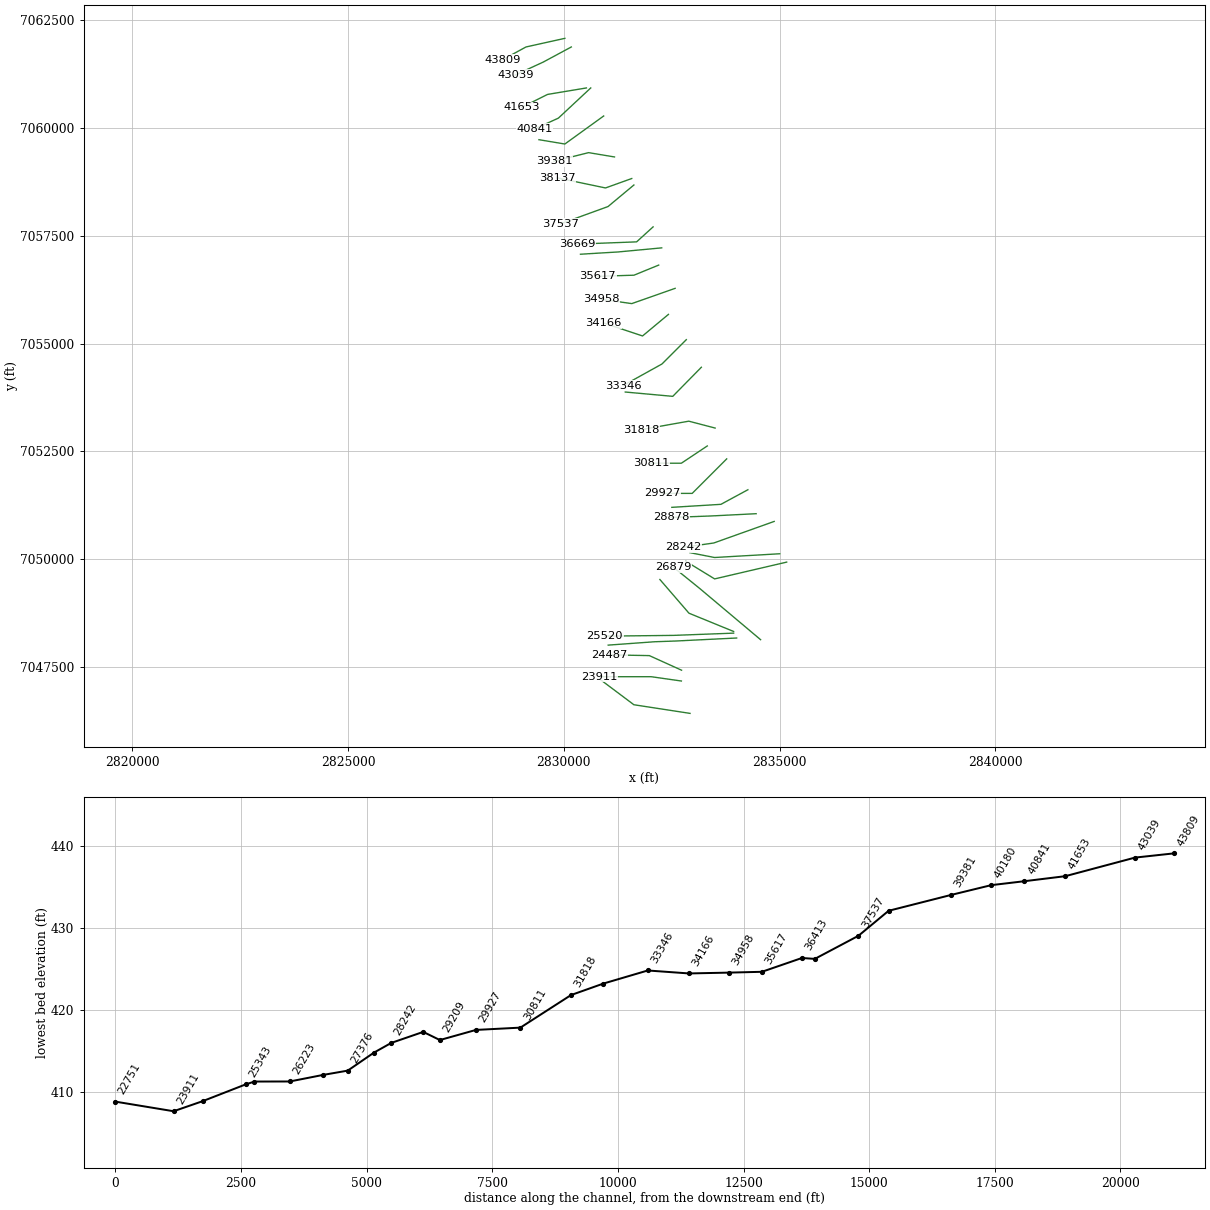
HEC-RAS study ELM CREEK.prj: ELM CREEK Base Level Engineering

--- ELM CREEK.g01 (geometry) --- (continued)

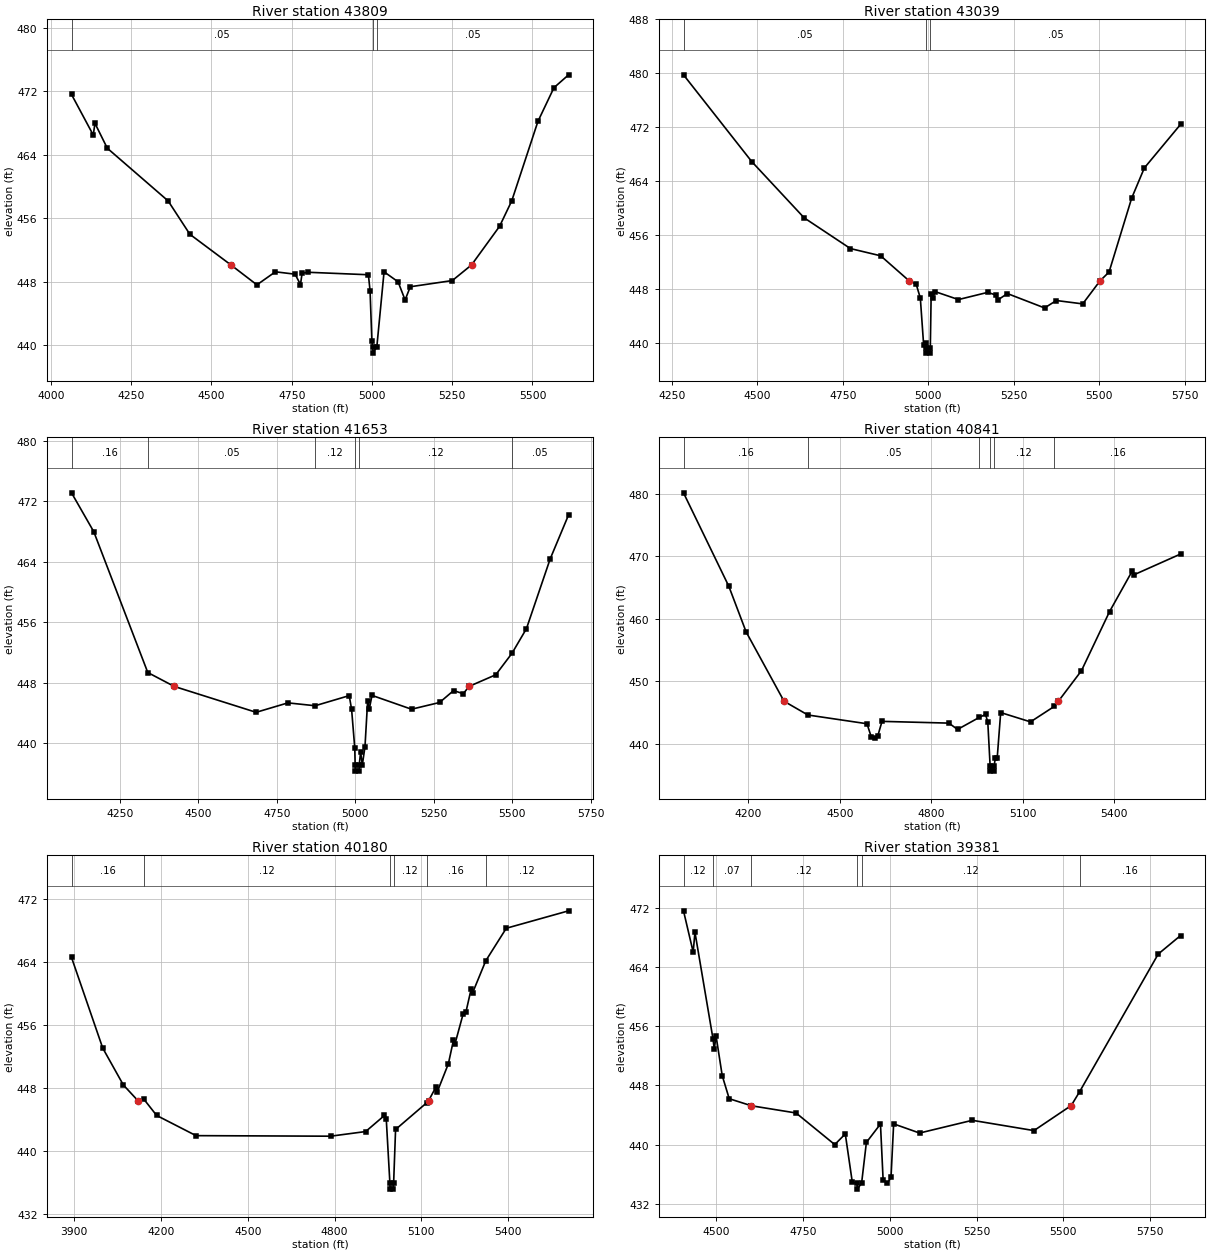
Type RM Length L Ch R = 1,43809,770,770,770
BEGIN DESCRIPTION:
ELM CREEK 43.0
END DESCRIPTION:
XS GIS Cut Line= 3
      2830024.96      7062074.99      2829125.00      7061875.00
      2828575.01      7061575.01
#Sta/Elev= 30
  4064.0  471.58  4131.8  466.47  4136.9  467.96  4175.4  464.82  4364.9  458.19
  4432.7  453.99  4560.7  450.13  4641.5  447.63  4699.1  449.27  4760.5  448.97
  4777.2  447.67  4782.3  449.09  4801.5  449.21  4988.8  448.90  4994.0  446.88
  4999.7  440.54  5002.3  439.84  5002.8  439.04  5015.1  439.84  5037.6  449.27
  5081.3  448.01  5103.1  445.73  5119.3  447.39  5250.3  448.17  5310.0  450.13
  5397.4  454.99  5435.4  458.20  5517.0  468.20  5566.8  472.43  5612.4  474.05
#Mann=3,-1,0
  4064.0    0.05       0  5002.3    0.03       0  5015.1    0.05       0
Bank Sta=4560.7,5310
Exp/Cntr=0.3,0.1

Type RM Length L Ch R = 1,43039,1386,1386,1386
BEGIN DESCRIPTION:
ELM CREEK 42.0
END DESCRIPTION:
XS GIS Cut Line= 3
      2830175.00      7061875.00      2829525.00      7061525.00
      2828875.03      7061225.02
#Sta/Elev= 30
  4283.7  479.79  4483.3  466.93  4636.6  458.59  4772.1  454.03  4860.5  452.96
  4943.7  449.25  4964.3  448.76  4976.5  446.70  4986.3  439.67  4991.9  440.01
  4992.8  439.33  4993.3  438.53  5005.2  438.53  5005.7  439.33  5008.2  447.23
  5013.8  446.74  5019.1  447.66  5088.0  446.47  5173.8  447.54  5196.8  447.15
  5202.3  446.38  5231.2  447.36  5340.0  445.23  5374.4  446.33  5451.5  445.83
  5502.3  449.25  5528.6  450.55  5594.7  461.50  5631.8  465.98  5737.8  472.44
#Mann=3,-1,0
  4283.7    0.05       0  4992.8    0.03       0  5005.7    0.05       0
Bank Sta=4943.7,5502.3
Exp/Cntr=0.3,0.1

Type RM Length L Ch R = 1,41653,812,812,812
BEGIN DESCRIPTION:
ELM CREEK 41.0
END DESCRIPTION:
XS GIS Cut Line= 3
      2830524.95      7060924.99      2829625.00      7060775.00
      2829024.99      7060474.99
#Sta/Elev= 30
  4096.3  473.13  4167.2  467.98  4339.2  449.33  4423.5  447.49  4684.3  444.06
  4785.6  445.31  4872.2  444.93  4980.8  446.27  4988.4  444.45  4998.5  439.32
  4999.7  437.07  5000.2  436.27  5012.1  436.27  5012.6  437.07  5017.1  438.79
  5022.6  437.11  5031.0  439.49  5039.4  445.54  5045.0  444.56  5053.4  446.30
  5179.2  444.47  5268.6  445.36  5313.3  446.94  5344.1  446.52  5362.4  447.49
  5447.5  449.03  5499.3  451.88  5545.3  455.14  5620.8  464.37  5679.5  470.21
#Mann=6,-1,0
  4096.3    0.16       0  4339.2    0.05       0  4872.2    0.12       0
  4999.7    0.07       0  5012.6    0.12       0  5499.3    0.05       0
Bank Sta=4423.5,5362.4
Exp/Cntr=0.3,0.1

Type RM Length L Ch R = 1,40841,661,661,661
BEGIN DESCRIPTION:
ELM CREEK 40.0
END DESCRIPTION:
XS GIS Cut Line= 3
      2830625.03      7060925.03      2829875.00      7060225.00
      2829325.00      7059975.00
#Sta/Elev= 30
  3987.5  480.18  4136.3  465.21  4192.7  457.95  4317.2  446.84  4395.4  444.64
  4589.2  443.24  4603.1  441.16  4617.0  441.02  4624.3  441.23  4638.5  443.62
  4857.9  443.34  4886.2  442.33  4958.1  444.27  4978.0  444.73  4985.4  443.52
  4993.1  436.46  4993.6  435.66  5005.5  435.66  5006.0  436.46  5010.0  437.72
  5016.2  437.72  5027.7  445.03  5125.5  443.54  5203.6  446.02  5216.9  446.84
  5292.5  451.72  5384.7  461.18  5459.4  467.70  5464.9  467.07  5617.6  470.39
#Mann=6,-1,0
  3987.5    0.16       0  4395.4    0.05       0  4958.1    0.12       0
  4993.1    0.07       0  5006.0    0.12       0  5203.6    0.16       0
Bank Sta=4317.2,5216.9
Exp/Cntr=0.3,0.1

Type RM Length L Ch R = 1,40180,799,799,799
BEGIN DESCRIPTION:
ELM CREEK 39.0
END DESCRIPTION:
XS GIS Cut Line= 3
      2830924.96      7060274.97      2830025.00      7059625.00
      2829425.01      7059725.00
#Sta/Elev= 30
  3890.7  464.55  3998.6  453.06  4069.8  448.39  4120.6  446.38  4141.2  446.56
  4185.0  444.52  4321.2  441.96  4786.2  441.89  4907.6  442.48  4972.6  444.52
  4978.8  444.06  4991.3  435.98  4991.8  435.18  5003.8  435.18  5004.3  435.98
  5011.0  442.74  5118.7  446.13  5125.0  446.38  5150.4  448.11  5155.4  447.54
  5193.5  451.07  5211.2  454.07  5216.3  453.58  5244.1  457.33  5254.3  457.64
  5272.0  460.50  5277.1  460.05  5322.7  464.12  5393.7  468.25  5609.1  470.46
#Mann=6,-1,0
  3890.7    0.16       0  4141.2    0.12       0  4991.3    0.07       0
  5004.3    0.12       0  5118.7    0.16       0  5322.7    0.12       0
Bank Sta=4120.6,5125
Exp/Cntr=0.3,0.1

Type RM Length L Ch R = 1,39381,1244,1244,1244
BEGIN DESCRIPTION:
ELM CREEK 38.0
END DESCRIPTION:
XS GIS Cut Line= 3
      2831175.04      7059324.99      2830575.00      7059425.00
      2829775.04      7059225.01
#Sta/Elev= 30
  4405.1  471.60  4433.0  466.02  4438.1  468.71  4490.1  454.31  4493.8  452.90
  4498.9  454.71  4516.7  449.33  4536.9  446.21  4598.6  445.29  4600.1  445.26
  4729.6  444.28  4841.1  440.01  4871.5  441.45  4891.8  434.89  4905.5  434.79
  4906.0  433.99  4918.5  434.79  4932.3  440.30  4972.9  442.79  4980.5  435.28
  4993.1  434.80  5003.3  435.60  5010.9  442.81  5085.6  441.57  5237.6  443.29
  5415.4  441.90  5522.9  445.29  5547.3  447.18  5773.6  465.76  5838.0  468.26
#Mann=6,-1,0
  4405.1    0.12       0  4490.1    0.07       0  4600.1    0.12       0
  4905.5    0.07       0  4918.5    0.12       0  5547.3    0.16       0
Bank Sta=4598.6,5522.9
Exp/Cntr=0.3,0.1

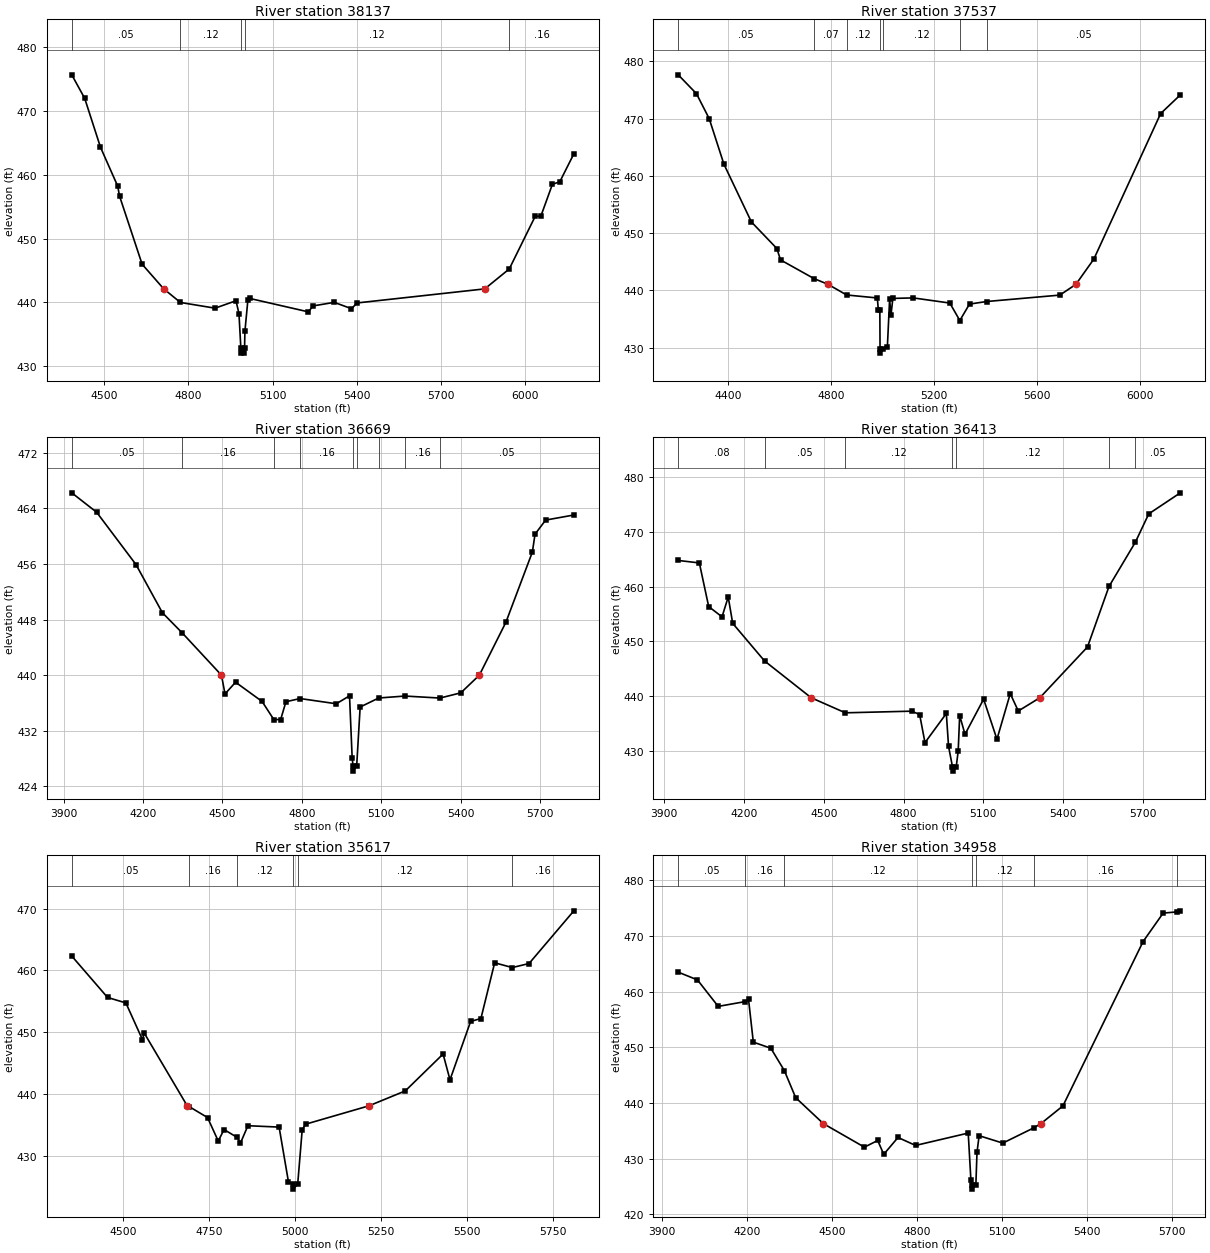
Type RM Length L Ch R = 1,38137,600,600,600
BEGIN DESCRIPTION:
ELM CREEK 37.0
END DESCRIPTION:
XS GIS Cut Line= 3
      2831574.97      7058824.99      2830966.89      7058606.31
      2829850.19      7058840.04
#Sta/Elev= 30
  4385.3  475.64  4431.3  471.96  4487.5  464.30  4548.9  458.20  4555.3  456.66
  4635.7  445.98  4712.7  442.12  4772.1  439.99  4895.4  439.10  4969.8  440.26
  4980.4  438.26  4987.1  432.86  4987.7  432.06  4999.7  432.06  5000.3  432.86
  5001.6  435.47  5012.3  440.45  5019.1  440.62  5227.6  438.52  5243.8  439.45
  5319.5  440.01  5380.8  439.02  5401.2  439.92  5855.3  442.12  5942.5  445.24
  6034.7  453.47  6055.1  453.52  6096.0  458.49  6122.5  458.90  6172.4  463.27
#Mann=5,-1,0
  4385.3    0.05       0  4772.1    0.12       0  4987.1    0.07       0
  5000.3    0.12       0  5942.5    0.16       0
Bank Sta=4712.7,5855.3
Exp/Cntr=0.3,0.1

Type RM Length L Ch R = 1,37537,868,868,868
BEGIN DESCRIPTION:
ELM CREEK 36.0
END DESCRIPTION:
XS GIS Cut Line= 3
      2831624.97      7058674.97      2831025.00      7058175.00
      2829924.96      7057774.98
#Sta/Elev= 30
  4205.2  477.65  4276.1  474.35  4325.6  469.99  4382.8  462.03  4489.6  451.94
  4588.5  447.30  4602.8  445.31  4733.2  442.04  4787.5  441.04  4859.7  439.18
  4979.0  438.66  4982.9  436.61  4988.8  436.61  4989.6  429.82  4990.2  429.02
  5002.8  429.82  5018.1  430.13  5026.8  438.43  5032.1  435.68  5039.4  438.58
  5118.5  438.67  5260.8  437.77  5299.7  434.72  5337.3  437.59  5404.2  438.04
  5688.5  439.16  5750.9  441.04  5820.8  445.47  6080.2  470.88  6156.7  474.14
#Mann=7,-1,0
  4205.2    0.05       0  4733.2    0.07       0  4859.7    0.12       0
  4989.6    0.07       0  5002.8    0.12       0  5299.7    0.16       0
  5404.2    0.05       0
Bank Sta=4787.5,5750.9
Exp/Cntr=0.3,0.1

Type RM Length L Ch R = 1,36669,256,256,256
BEGIN DESCRIPTION:
Mapping XS c8883421
END DESCRIPTION:
XS GIS Cut Line= 3
      2832069.32      7057703.53      2831687.38      7057356.31
      2830308.54      7057304.28
#Sta/Elev= 30
  3930.8  466.24  4024.9  463.44  4173.5  455.91  4272.9  449.00  4348.9  446.05
  4496.2  440.01  4509.4  437.31  4549.4  439.00  4649.5  436.23  4693.8  433.63
  4719.6  433.63  4739.6  436.19  4792.9  436.65  4929.7  435.90  4979.7  437.04
  4989.7  428.08  4992.8  427.01  4993.7  426.21  5006.8  427.01  5019.8  435.43
  5090.0  436.73  5189.1  437.01  5321.1  436.72  5400.0  437.47  5469.9  440.01
  5570.2  447.62  5670.2  457.73  5680.2  460.29  5720.3  462.32  5826.8  463.05
#Mann=9,-1,0
  3930.8    0.05       0  4348.9    0.16       0  4693.8    0.12       0
  4792.9    0.16       0  4992.8    0.07       0  5006.8    0.16       0
  5090.0    0.12       0  5189.1    0.16       0  5321.1    0.05       0
Bank Sta=4496.2,5469.9
Exp/Cntr=0.3,0.1

Type RM Length L Ch R = 1,36413,796,796,796
BEGIN DESCRIPTION:
Mapping XS ad8799d9
END DESCRIPTION:
XS GIS Cut Line= 3
      2832269.01      7057217.43      2831253.35      7057121.94
      2830386.55      7057069.93
#Sta/Elev= 30
  3952.6  464.76  4032.0  464.31  4067.1  456.35  4117.3  454.47  4140.6  458.10
  4157.5  453.28  4277.3  446.42  4452.7  439.71  4581.1  436.96  4830.5  437.26
  4860.6  436.65  4880.7  431.52  4961.0  436.84  4969.4  430.82  4984.1  427.12
  4985.0  426.32  4998.1  427.12  5005.6  429.94  5011.2  436.47  5031.2  433.04
  5101.3  439.45  5151.4  432.14  5201.5  440.46  5231.6  437.29  5312.8  439.71
  5492.0  448.98  5572.8  460.01  5671.9  468.08  5722.4  473.26  5841.1  477.10
#Mann=7,-1,0
  3952.6    0.08       0  4277.3    0.05       0  4581.1    0.12       0
  4984.1    0.07       0  4998.1    0.12       0  5572.8    0.16       0
  5671.9    0.05       0
Bank Sta=4452.7,5312.8
Exp/Cntr=0.3,0.1

Type RM Length L Ch R = 1,35617,659,659,659
BEGIN DESCRIPTION:
Mapping XS 95f2342b
END DESCRIPTION:
XS GIS Cut Line= 3
      2832199.54      7056818.12      2831626.62      7056583.74
      2830784.63      7056557.70
#Sta/Elev= 30
  4349.6  462.32  4453.7  455.63  4507.1  454.74  4555.2  448.82  4560.6  449.86
  4685.6  438.11  4691.1  437.99  4744.8  436.21  4775.9  432.42  4792.9  434.27
  4830.4  433.02  4840.7  432.10  4862.3  434.89  4953.1  434.67  4980.2  425.85
  4993.2  425.44  4994.1  424.64  5007.2  425.44  5020.3  434.23  5030.3  435.14
  5214.8  438.11  5320.4  440.52  5430.4  446.48  5450.5  442.31  5510.5  451.75
  5540.5  452.22  5580.5  461.23  5631.8  460.46  5680.6  461.11  5811.0  469.63
#Mann=6,-1,0
  4349.6    0.05       0  4691.1    0.16       0  4830.4    0.12       0
  4993.2    0.07       0  5007.2    0.12       0  5631.8    0.16       0
Bank Sta=4685.6,5214.8
Exp/Cntr=0.3,0.1

Type RM Length L Ch R = 1,34958,792,792,792
BEGIN DESCRIPTION:
ELM CREEK 33.0
END DESCRIPTION:
XS GIS Cut Line= 3
      2832578.94      7056278.24      2831575.00      7055925.00
      2830874.98      7056025.00
#Sta/Elev= 30
  3957.4  463.52  4025.2  462.13  4098.4  457.37  4194.5  458.24  4205.4  458.64
  4222.3  450.95  4284.2  449.85  4331.6  445.85  4371.8  440.97  4469.4  436.31
  4614.2  432.08  4661.2  433.28  4682.4  430.79  4732.8  433.82  4794.7  432.39
  4980.5  434.61  4989.9  426.22  4993.4  425.34  4994.4  424.54  5007.5  425.34
  5011.5  431.16  5019.0  434.14  5102.5  432.81  5211.9  435.55  5237.0  436.31
  5314.6  439.49  5597.5  469.02  5668.2  474.13  5717.1  474.35  5728.8  474.54
#Mann=7,-1,0
  3957.4    0.05       0  4194.5    0.16       0  4331.6    0.12       0
  4993.4    0.07       0  5007.5    0.12       0  5211.9    0.16       0
  5717.1    0.05       0
Bank Sta=4469.4,5237
Exp/Cntr=0.3,0.1

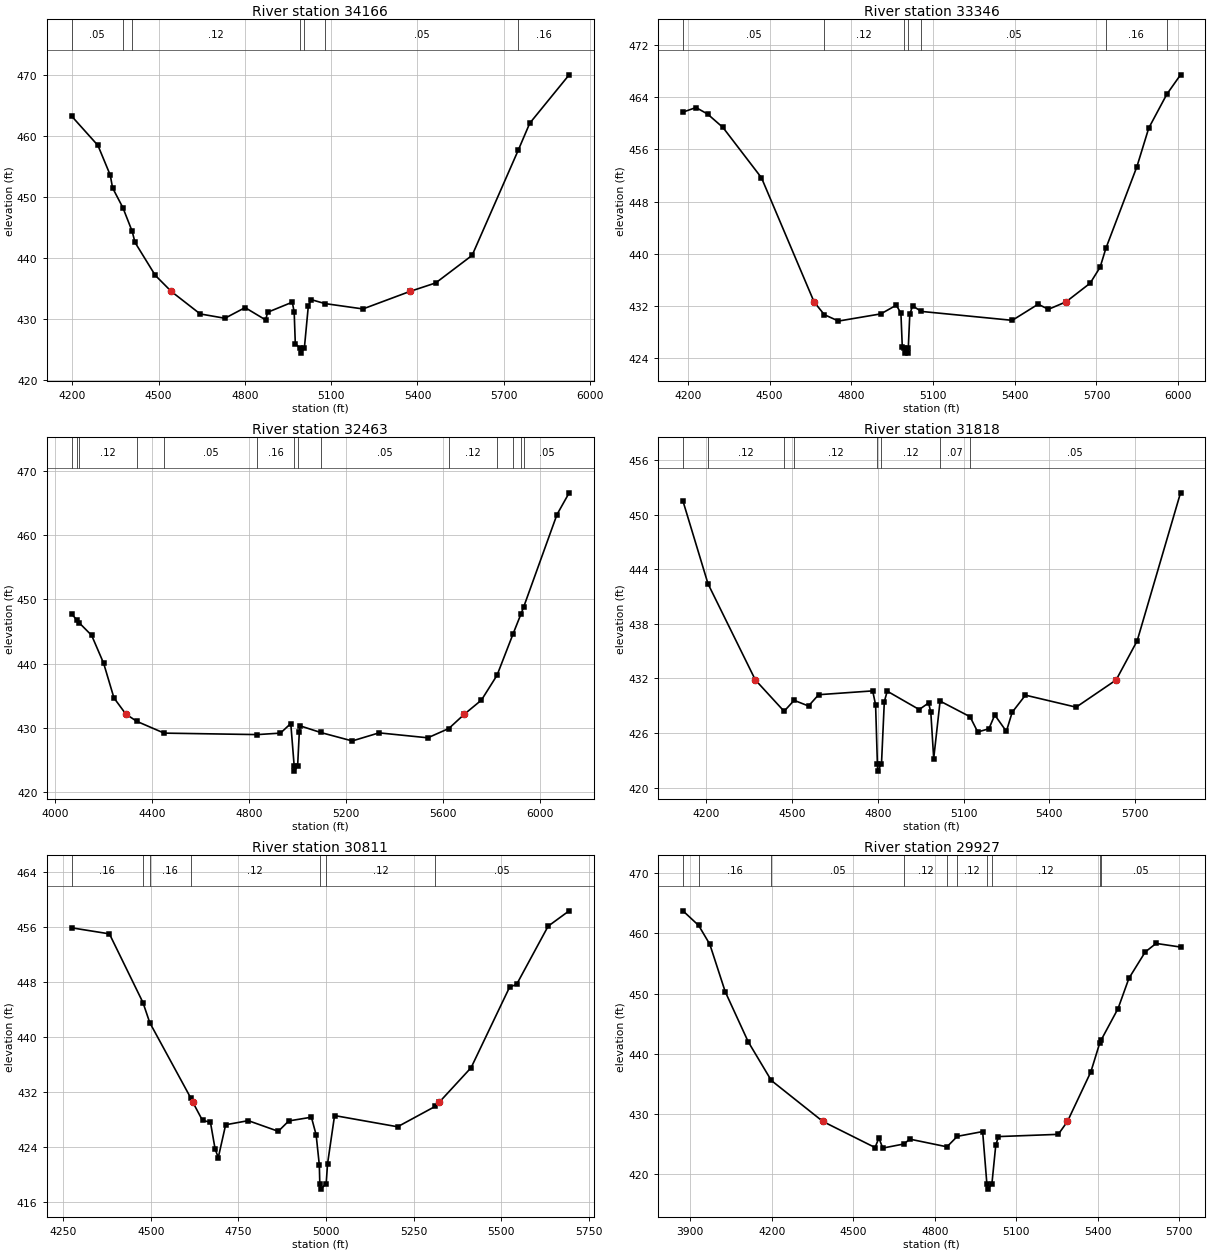
Type RM Length L Ch R = 1,34166,820,820,820
BEGIN DESCRIPTION:
ELM CREEK 32.0
END DESCRIPTION:
XS GIS Cut Line= 3
      2832425.00      7055675.00      2831825.00      7055175.00
      2830925.01      7055475.00
#Sta/Elev= 30
  4197.5  463.34  4289.3  458.51  4332.2  453.62  4340.0  451.56  4376.2  448.28
  4408.4  444.40  4418.1  442.60  4488.4  437.21  4544.2  434.56  4644.6  430.87
  4730.6  430.16  4800.8  431.91  4872.4  429.88  4878.9  431.14  4964.9  432.80
  4971.4  431.16  4975.3  425.97  4992.6  425.24  4993.5  424.44  5006.7  425.24
  5020.7  432.25  5031.2  433.21  5078.1  432.57  5210.4  431.69  5373.6  434.56
  5463.4  435.96  5589.9  440.48  5750.7  457.79  5790.2  462.16  5927.2  470.10
#Mann=7,-1,0
  4197.5    0.05       0  4376.2    0.16       0  4408.4    0.12       0
  4992.6    0.07       0  5006.7    0.12       0  5078.1    0.05       0
  5750.7    0.16       0
Bank Sta=4544.2,5373.6
Exp/Cntr=0.3,0.1

Type RM Length L Ch R = 1,33346,883,883,883
BEGIN DESCRIPTION:
ELM CREEK 31.0
END DESCRIPTION:
XS GIS Cut Line= 3
      2832838.93      7055088.93      2832275.00      7054525.00
      2831374.99      7054024.99
#Sta/Elev= 30
  4181.5  461.70  4229.5  462.40  4271.9  461.41  4328.5  459.35  4469.9  451.65
  4663.1  432.64  4700.6  430.69  4752.7  429.71  4908.3  430.81  4964.9  432.14
  4981.9  430.92  4987.0  425.74  4994.8  425.60  4995.8  424.80  5008.0  424.80
  5009.0  425.60  5014.5  430.73  5024.8  432.05  5056.2  431.19  5390.8  429.82
  5485.8  432.29  5523.5  431.51  5587.8  432.64  5676.8  435.51  5713.4  437.96
  5734.6  440.86  5848.4  453.35  5891.9  459.26  5958.3  464.44  6008.6  467.41
#Mann=7,-1,0
  4181.5    0.05       0  4700.6    0.12       0  4994.8    0.07       0
  5009.0    0.12       0  5056.2    0.05       0  5734.6    0.16       0
  5958.3    0.05       0
Bank Sta=4663.1,5587.8
Exp/Cntr=0.3,0.1

Type RM Length L Ch R = 1,32463,645,645,645
BEGIN DESCRIPTION:
ELM CREEK 30.0
END DESCRIPTION:
XS GIS Cut Line= 3
      2833187.74      7054449.38      2832525.00      7053775.00
      2831424.96      7053875.00
#Sta/Elev= 30
  4068.8  447.73  4092.7  446.72  4099.5  446.38  4151.6  444.39  4201.1  440.03
  4243.5  434.63  4292.7  432.10  4338.1  430.97  4450.2  429.14  4833.9  428.91
  4929.5  429.14  4972.0  430.64  4986.0  424.01  4987.0  423.21  5000.2  424.01
  5007.2  429.35  5010.8  430.27  5094.9  429.24  5225.2  427.92  5335.6  429.18
  5536.5  428.41  5623.1  429.86  5687.4  432.10  5757.4  434.29  5821.8  438.17
  5888.3  444.67  5919.7  447.66  5931.4  448.81  6068.7  463.24  6118.9  466.63
#Mann=14,-1,0
  4068.8    0.12       0  4092.7    0.05       0  4099.5    0.12       0
  4338.1    0.16       0  4450.2    0.05       0  4833.9    0.16       0
  4986.0    0.07       0  5000.2    0.16       0  5094.9    0.05       0
  5623.1    0.12       0  5821.8    0.16       0  5888.3    0.12       0
  5919.7    0.16       0  5931.4    0.05       0
Bank Sta=4292.7,5687.4
Exp/Cntr=0.3,0.1

Type RM Length L Ch R = 1,31818,1007,1007,1007
BEGIN DESCRIPTION:
double ELM CREEK 29.0
END DESCRIPTION:
XS GIS Cut Line= 3
      2833507.21      7053039.64      2832896.07      7053199.38
      2831805.75      7053004.92
#Sta/Elev= 30
  4119.0  451.51  4206.7  442.40  4372.2  431.83  4472.6  428.39  4507.7  429.59
  4558.0  428.97  4593.3  430.21  4782.2  430.63  4792.4  429.10  4798.7  422.61
  4799.7  421.81  4813.0  422.61  4822.9  429.44  4833.0  430.60  4944.8  428.58
  4977.6  429.30  4985.4  428.28  4995.5  423.19  5017.8  429.51  5122.5  427.79
  5149.4  426.11  5188.5  426.47  5208.9  427.98  5249.5  426.18  5269.8  428.28
  5316.1  430.16  5493.3  428.84  5633.1  431.83  5706.6  436.13  5858.2  452.40
#Mann=8,-1,0
  4119.0    0.16       0  4206.7    0.12       0  4472.6    0.16       0
  4507.7    0.12       0  4798.7    0.07       0  4813.0    0.12       0
  5017.8    0.07       0  5122.5    0.05       0
Bank Sta=4372.2,5633.1
Exp/Cntr=0.3,0.1

Type RM Length L Ch R = 1,30811,884,884,884
BEGIN DESCRIPTION:
ELM CREEK 28.0
END DESCRIPTION:
XS GIS Cut Line= 3
      2833324.97      7052624.98      2832725.00      7052225.00
      2832024.98      7052225.00
#Sta/Elev= 30
  4273.3  455.86  4381.4  454.98  4477.3  444.98  4496.6  442.07  4613.8  431.10
  4619.5  430.50  4647.3  427.84  4669.9  427.59  4683.4  423.65  4692.4  422.45
  4713.4  427.21  4778.0  427.81  4863.7  426.26  4893.7  427.77  4958.3  428.31
  4971.8  425.75  4980.9  421.36  4982.3  418.65  4984.8  417.85  5000.5  418.65
  5004.4  421.54  5024.4  428.55  5204.4  426.92  5311.7  429.88  5323.6  430.50
  5414.4  435.52  5524.4  447.24  5544.4  447.63  5634.4  456.10  5694.4  458.33
#Mann=7,-1,0
  4273.3    0.16       0  4477.3    0.05       0  4496.6    0.16       0
  4613.8    0.12       0  4982.3    0.07       0  5000.5    0.12       0
  5311.7    0.05       0
Bank Sta=4619.5,5323.6
Exp/Cntr=0.3,0.1

Type RM Length L Ch R = 1,29927,718,718,718
BEGIN DESCRIPTION:
ELM CREEK 27.0
END DESCRIPTION:
XS GIS Cut Line= 3
      2833775.01      7052325.01      2832975.00      7051525.00
      2832274.99      7051525.00
#Sta/Elev= 30
  3872.8  463.75  3930.8  461.32  3971.8  458.19  4028.4  450.34  4113.2  442.01
  4198.1  435.60  4387.8  428.80  4579.9  424.47  4594.1  426.06  4608.2  424.38
  4687.2  425.07  4707.2  425.87  4844.6  424.59  4882.6  426.33  4975.9  427.12
  4991.6  418.37  4994.1  417.57  5009.8  418.37  5024.2  424.87  5034.2  426.29
  5254.2  426.66  5288.0  428.80  5374.2  437.04  5407.4  441.90  5411.4  442.26
  5474.2  447.53  5514.2  452.55  5574.2  456.92  5614.2  458.34  5704.2  457.74
#Mann=10,-1,0
  3872.8    0.05       0  3930.8    0.16       0  4198.1    0.05       0
  4687.2    0.12       0  4844.6    0.16       0  4882.6    0.12       0
  4991.6    0.07       0  5009.8    0.12       0  5407.4    0.07       0
  5411.4    0.05       0
Bank Sta=4387.8,5288
Exp/Cntr=0.3,0.1

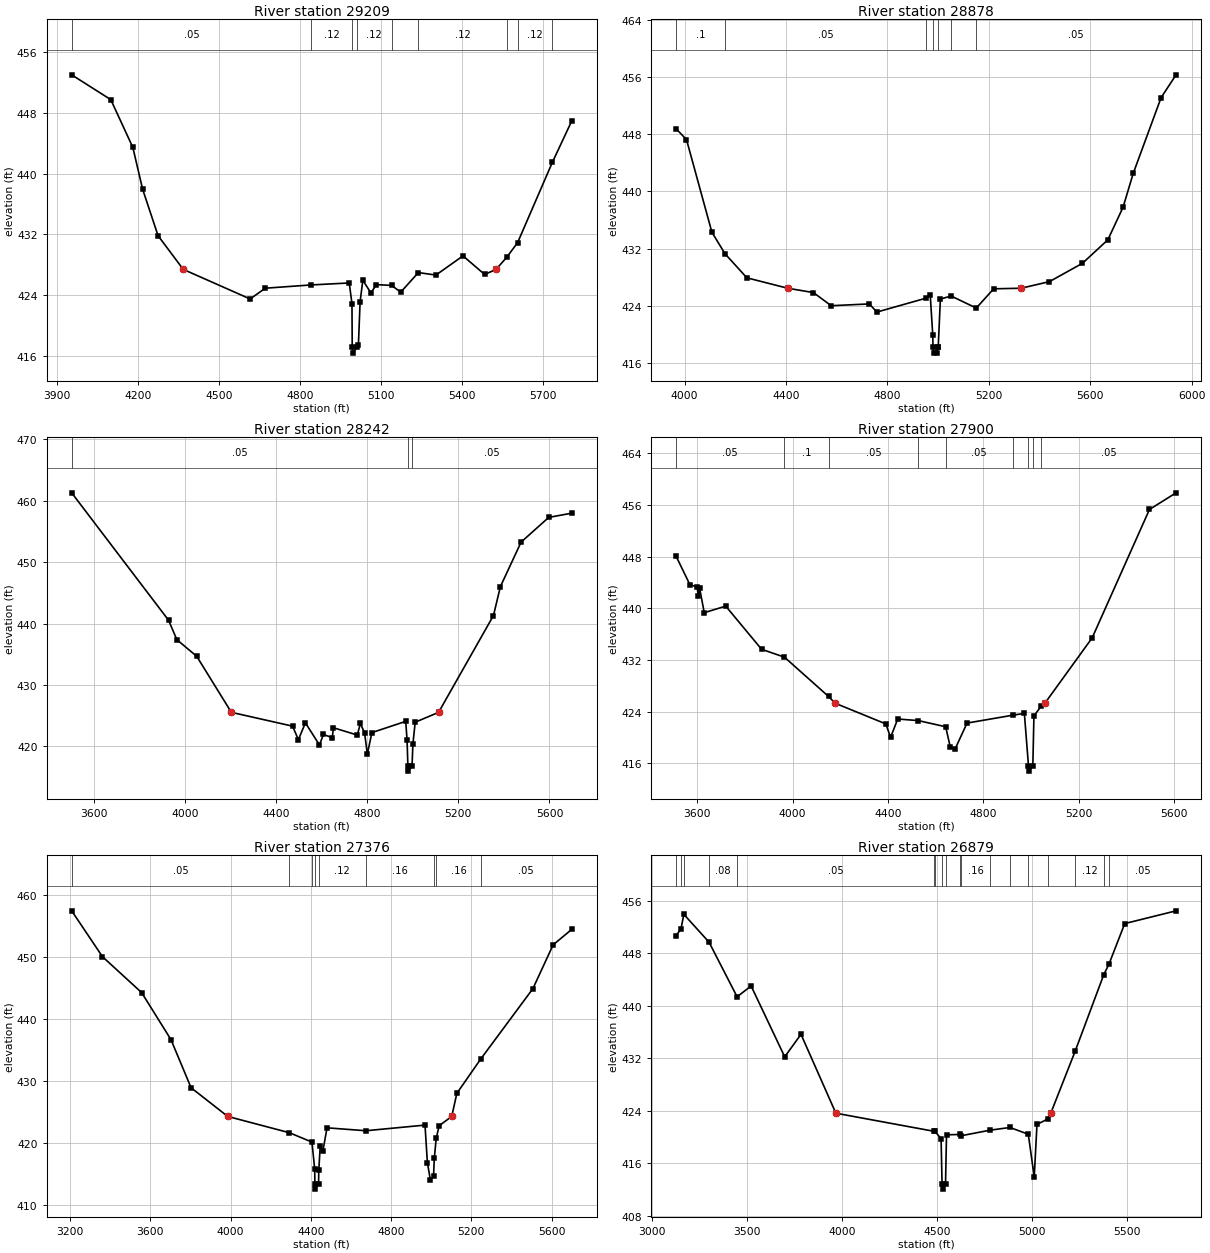
Type RM Length L Ch R = 1,29209,331,331,331
BEGIN DESCRIPTION:
Mapping XS 4de2c635
END DESCRIPTION:
XS GIS Cut Line= 3
      2834265.53      7051609.80      2833640.50      7051271.24
      2832503.35      7051201.80
#Sta/Elev= 30
  3955.7  453.03  4100.4  449.76  4182.1  443.45  4217.9  437.98  4275.3  431.82
  4368.5  427.38  4615.9  423.48  4672.0  424.90  4841.9  425.33  4982.6  425.59
  4992.6  422.87  4993.6  417.14  4996.1  416.34  5011.8  417.14  5016.4  417.35
  5022.7  423.09  5032.7  425.94  5062.8  424.28  5082.8  425.37  5139.2  425.27
  5173.0  424.38  5238.3  426.96  5303.2  426.63  5403.4  429.16  5483.5  426.71
  5525.8  427.38  5565.6  429.00  5605.3  430.90  5733.8  441.48  5805.8  446.96
#Mann=9,-1,0
  3955.7    0.05       0  4841.9    0.12       0  4993.6    0.07       0
  5011.8    0.12       0  5139.2    0.16       0  5238.3    0.12       0
  5565.6    0.07       0  5605.3    0.12       0  5733.8    0.05       0
Bank Sta=4368.5,5525.8
Exp/Cntr=0.3,0.1

Type RM Length L Ch R = 1,28878,636,636,636
BEGIN DESCRIPTION:
ELM CREEK 26.0
END DESCRIPTION:
XS GIS Cut Line= 3
      2834456.47      7051054.23      2833423.49      7051002.15
      2832486.03      7050967.42
#Sta/Elev= 30
  3966.2  448.81  4007.7  447.28  4107.9  434.28  4160.0  431.25  4245.9  427.89
  4407.0  426.43  4508.4  425.82  4578.4  423.98  4728.6  424.23  4758.7  423.09
  4952.5  425.04  4968.9  425.54  4979.0  419.83  4979.9  418.13  4982.4  417.33
  4995.6  417.33  4998.1  418.13  5000.5  418.21  5009.0  424.91  5051.5  425.34
  5150.6  423.65  5219.1  426.35  5327.6  426.43  5439.3  427.36  5569.4  429.93
  5669.4  433.22  5729.5  437.79  5769.5  442.53  5879.6  453.17  5938.6  456.36
#Mann=7,-1,0
  3966.2     0.1       0  4160.0    0.05       0  4952.5    0.12       0
  4979.9    0.07       0  4998.1    0.12       0  5051.5    0.07       0
  5150.6    0.05       0
Bank Sta=4407,5327.6
Exp/Cntr=0.3,0.1

Type RM Length L Ch R = 1,28242,342,342,342
BEGIN DESCRIPTION:
ELM CREEK 25.0
END DESCRIPTION:
XS GIS Cut Line= 3
      2834875.05      7050875.02      2833475.00      7050375.00
      2832774.96      7050274.99
#Sta/Elev= 30
  3504.2  461.29  3929.0  440.56  3965.6  437.39  4052.7  434.68  4204.7  425.56
  4473.2  423.31  4498.7  421.11  4529.5  423.85  4591.1  420.25  4608.6  421.96
  4647.3  421.44  4652.7  423.05  4757.2  421.86  4770.5  423.75  4789.1  422.21
  4801.3  418.74  4821.0  422.26  4969.6  424.09  4975.5  421.00  4979.1  416.79
  4981.6  415.99  4997.3  416.79  5001.0  420.38  5011.1  423.95  5113.8  425.56
  5354.5  441.32  5384.8  446.02  5475.7  453.27  5596.9  457.29  5698.0  457.98
#Mann=3,-1,0
  3504.2    0.05       0  4979.1    0.03       0  4997.3    0.05       0
Bank Sta=4204.7,5113.8
Exp/Cntr=0.3,0.1

Type RM Length L Ch R = 1,27900,524,524,524
BEGIN DESCRIPTION:
Mapping XS b643f5e1
END DESCRIPTION:
XS GIS Cut Line= 3
      2835003.31      7050125.41      2833492.93      7050038.60
      2832920.01      7050151.45
#Sta/Elev= 30
  3511.4  448.09  3569.8  443.65  3599.9  443.30  3605.2  441.87  3610.3  443.16
  3629.9  439.32  3720.1  440.33  3870.3  433.66  3966.2  432.44  4150.9  426.37
  4178.8  425.32  4391.2  422.12  4411.2  420.04  4441.2  422.88  4527.7  422.63
  4642.2  421.68  4661.6  418.51  4681.6  418.23  4731.7  422.25  4924.0  423.47
  4972.1  423.75  4989.4  415.62  4991.9  414.82  5007.6  415.62  5012.2  423.35
  5043.6  424.92  5058.2  425.32  5256.6  435.44  5496.6  455.28  5608.2  457.85
#Mann=9,-1,0
  3511.4    0.05       0  3966.2     0.1       0  4150.9    0.05       0
  4527.7    0.12       0  4642.2    0.05       0  4924.0    0.16       0
  4989.4    0.07       0  5007.6    0.16       0  5043.6    0.05       0
Bank Sta=4178.8,5058.2
Exp/Cntr=0.3,0.1

Type RM Length L Ch R = 1,27376,497,497,497
BEGIN DESCRIPTION:
Mapping XS ee8f9a58
END DESCRIPTION:
XS GIS Cut Line= 3
      2835164.54      7049931.84      2833495.32      7049542.45
      2832831.12      7049948.85
#Sta/Elev= 30
  3208.2  457.52  3361.8  450.12  3556.9  444.33  3703.1  436.74  3803.3  428.98
  3985.9  424.35  4293.5  421.72  4405.8  420.21  4419.4  415.90  4420.6  413.42
  4423.1  412.62  4438.8  413.42  4439.9  415.65  4446.9  419.50  4460.5  418.80
  4481.0  422.51  4674.5  422.04  4969.3  422.95  4981.2  416.90  4996.5  414.03
  5011.9  414.68  5015.6  417.59  5025.2  420.82  5039.8  422.85  5102.6  424.35
  5128.0  428.07  5246.6  433.59  5507.2  444.97  5607.9  452.03  5700.9  454.53
#Mann=9,-1,0
  3208.2    0.05       0  4293.5    0.16       0  4405.8    0.12       0
  4420.6    0.07       0  4438.8    0.12       0  4674.5    0.16       0
  5015.6    0.12       0  5025.2    0.16       0  5246.6    0.05       0
Bank Sta=3985.9,5102.6
Exp/Cntr=0.3,0.1

Type RM Length L Ch R = 1,26879,656,656,656
BEGIN DESCRIPTION:
double ELM CREEK 24.0
END DESCRIPTION:
XS GIS Cut Line= 3
      2834560.31      7048133.22      2833154.02      7049316.91
      2832535.98      7049816.90
#Sta/Elev= 30
  3124.3  450.64  3150.7  451.67  3165.7  453.90  3298.4  449.66  3446.2  441.35
  3519.9  443.00  3696.8  432.22  3782.6  435.64  3966.2  423.64  4480.7  420.90
  4486.5  420.91  4520.1  419.78  4525.3  412.89  4527.8  412.09  4543.5  412.89
  4548.7  420.35  4618.5  420.41  4625.5  420.21  4776.3  421.05  4882.7  421.47
  4979.4  420.44  5010.6  413.92  5025.0  421.94  5080.9  422.74  5097.6  423.64
  5225.5  433.03  5376.7  444.72  5403.5  446.28  5487.1  452.49  5757.4  454.43
#Mann=18,-1,0
  3124.3    0.16       0  3150.7    0.12       0  3165.7     0.1       0
  3298.4    0.08       0  3446.2    0.05       0  4480.7    0.16       0
  4486.5    0.05       0  4525.3    0.07       0  4543.5    0.05       0
  4618.5    0.07       0  4625.5    0.16       0  4776.3    0.12       0
  4882.7    0.16       0  4979.4    0.12       0  5080.9    0.16       0
  5225.5    0.12       0  5376.7    0.16       0  5403.5    0.05       0
Bank Sta=3966.2,5097.6
Exp/Cntr=0.3,0.1

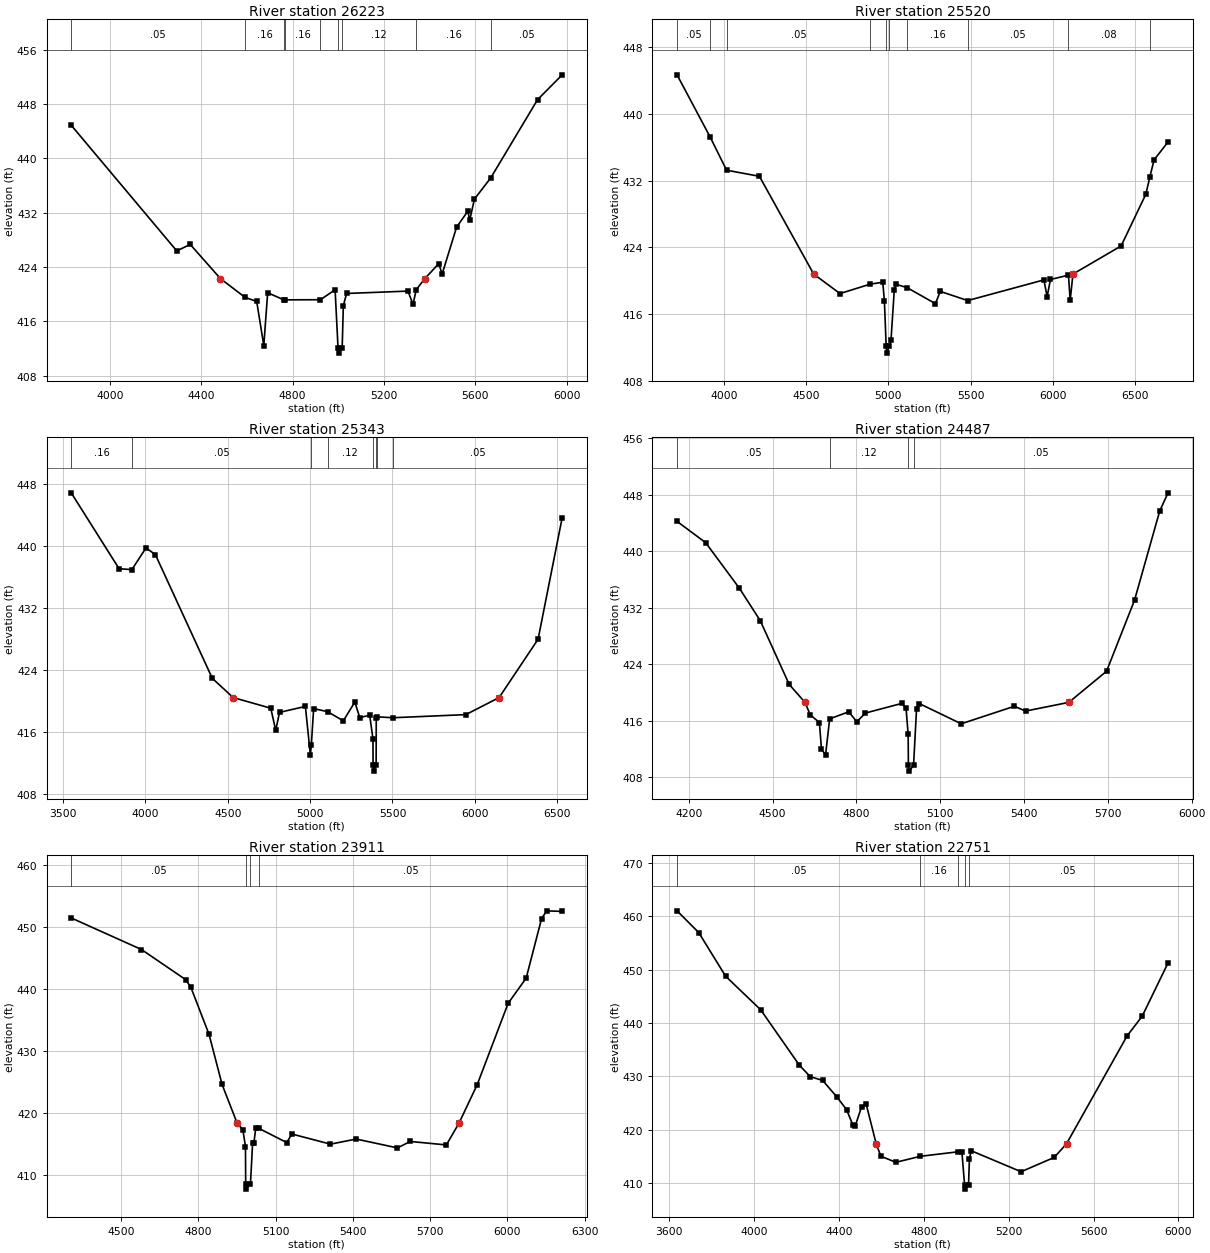
Type RM Length L Ch R = 1,26223,703,703,703
BEGIN DESCRIPTION:
double ELM CREEK 23.0
END DESCRIPTION:
XS GIS Cut Line= 3
      2833935.25      7048323.86      2832900.54      7048747.47
      2832226.94      7049528.71
#Sta/Elev= 30
  3830.9  444.88  4293.1  426.36  4351.9  427.32  4484.3  422.28  4591.8  419.52
  4643.0  418.91  4674.0  412.42  4691.0  420.20  4764.5  419.11  4765.9  419.15
  4922.0  419.17  4986.2  420.64  4999.0  412.10  5001.5  411.30  5017.2  412.10
  5022.3  418.31  5036.6  420.09  5305.4  420.44  5327.3  418.47  5341.4  420.65
  5379.2  422.28  5440.3  424.50  5454.6  422.93  5518.2  429.87  5567.6  432.23
  5575.3  430.86  5596.1  433.99  5667.8  437.13  5872.6  448.65  5980.5  452.31
#Mann=9,-1,0
  3830.9    0.05       0  4591.8    0.16       0  4764.5    0.12       0
  4765.9    0.16       0  4922.0    0.12       0  4999.0    0.07       0
  5017.2    0.12       0  5341.4    0.16       0  5667.8    0.05       0
Bank Sta=4484.3,5379.2
Exp/Cntr=0.3,0.1

Type RM Length L Ch R = 1,25520,177,177,177
BEGIN DESCRIPTION:
Mapping XS d40db136
END DESCRIPTION:
XS GIS Cut Line= 3
      2833935.62      7048285.13      2832538.07      7048233.05
      2830949.78      7048215.69
#Sta/Elev= 30
  3714.4  444.70  3916.7  437.20  4015.7  433.25  4215.4  432.52  4545.8  420.78
  4705.7  418.44  4889.0  419.57  4965.9  419.80  4975.9  417.55  4986.7  412.09
  4989.2  411.29  5005.1  412.09  5015.9  412.81  5035.9  418.83  5045.9  419.56
  5115.2  419.14  5286.0  417.23  5316.0  418.70  5482.6  417.60  5946.0  420.08
  5966.0  418.08  5986.0  420.13  6095.5  420.65  6106.0  417.63  6123.0  420.78
  6416.1  424.16  6566.1  430.36  6590.7  432.43  6616.1  434.48  6701.3  436.64
#Mann=10,-1,0
  3714.4    0.05       0  3916.7    0.08       0  4015.7    0.05       0
  4889.0    0.12       0  4986.7    0.07       0  5005.1    0.12       0
  5115.2    0.16       0  5482.6    0.05       0  6095.5    0.08       0
  6590.7    0.05       0
Bank Sta=4545.8,6123
Exp/Cntr=0.3,0.1

Type RM Length L Ch R = 1,25343,856,856,856
BEGIN DESCRIPTION:
Mapping XS 2363d6d6
END DESCRIPTION:
XS GIS Cut Line= 4
      2834005.11      7048172.29      2832598.84      7048102.84
      2832104.05      7048085.48      2831028.86      7048007.44
#Sta/Elev= 30
  3549.3  446.85  3839.8  437.06  3917.6  436.94  4003.1  439.74  4060.0  438.89
  4406.0  422.91  4532.9  420.43  4760.9  419.06  4790.9  416.20  4814.0  418.52
  4971.1  419.29  5001.2  413.05  5007.2  414.27  5021.2  419.01  5106.2  418.61
  5201.3  417.43  5271.3  419.85  5301.3  417.85  5361.4  418.15  5381.4  415.10
  5382.2  411.74  5384.7  410.94  5400.6  411.74  5401.4  417.82  5403.4  417.95
  5502.4  417.83  5945.1  418.23  6147.3  420.43  6383.9  427.96  6530.4  443.66
#Mann=8,-1,0
  3549.3    0.16       0  3917.6    0.05       0  5007.2    0.16       0
  5106.2    0.12       0  5382.2    0.03       0  5400.6    0.12       0
  5403.4     0.1       0  5502.4    0.05       0
Bank Sta=4532.9,6147.3
Exp/Cntr=0.3,0.1

Type RM Length L Ch R = 1,24487,576,576,576
BEGIN DESCRIPTION:
Mapping XS 3822386e
END DESCRIPTION:
XS GIS Cut Line= 3
      2832729.02      7047425.77      2831982.52      7047764.30
      2831045.06      7047781.66
#Sta/Elev= 30
  4158.1  444.25  4260.5  441.24  4381.5  434.77  4456.2  430.18  4559.5  421.17
  4616.2  418.63  4634.7  416.87  4667.6  415.78  4675.0  412.05  4689.6  411.17
  4704.4  416.30  4772.8  417.30  4801.4  415.88  4832.3  417.12  4963.0  418.49
  4977.8  417.77  4985.3  414.10  4986.1  409.70  4988.6  408.90  5004.6  409.70
  5015.3  417.69  5025.3  418.46  5175.3  415.60  5365.4  418.08  5405.4  417.40
  5560.3  418.63  5695.4  423.04  5795.4  433.08  5885.5  445.70  5915.4  448.29
#Mann=4,-1,0
  4158.1    0.05       0  4704.4    0.12       0  4986.1    0.03       0
  5004.6    0.05       0
Bank Sta=4616.2,5560.3
Exp/Cntr=0.3,0.1

Type RM Length L Ch R = 1,23911,1160,1160,1160
BEGIN DESCRIPTION:
ELM CREEK 20.0
END DESCRIPTION:
XS GIS Cut Line= 3
      2832725.02      7047175.00      2832025.00      7047275.00
      2830825.02      7047275.00
#Sta/Elev= 30
  4306.1  451.43  4578.9  446.34  4750.6  441.48  4770.8  440.25  4841.5  432.64
  4892.0  424.57  4950.5  418.33  4972.8  417.24  4982.9  414.55  4983.8  408.48
  4986.3  407.68  5002.3  408.48  5010.7  415.16  5015.7  415.16  5023.2  417.62
  5035.2  417.48  5143.2  415.19  5163.2  416.57  5313.2  414.94  5413.2  415.76
  5573.2  414.33  5623.2  415.37  5763.2  414.81  5812.4  418.33  5883.2  424.55
  6003.2  437.66  6073.2  441.72  6133.2  451.34  6153.2  452.58  6213.2  452.48
#Mann=4,-1,0
  4306.1    0.05       0  4983.8    0.07       0  5002.3    0.05       0
  5035.2    0.05       0
Bank Sta=4950.5,5812.4
Exp/Cntr=0.3,0.1

Type RM Length L Ch R = 1,22751,1029,1029,1029
BEGIN DESCRIPTION:
ELM CREEK 19.0
END DESCRIPTION:
XS GIS Cut Line= 3
      2832924.97      7046425.00      2831625.00      7046625.00
      2830824.97      7047225.02
#Sta/Elev= 30
  3636.1  461.03  3738.5  456.95  3865.0  448.78  4030.7  442.47  4212.8  432.09
  4264.6  429.93  4322.8  429.23  4391.1  426.07  4435.4  423.76  4465.7  420.84
  4475.8  420.62  4506.2  424.28  4527.7  424.83  4575.2  417.36  4597.2  415.02
  4668.1  413.88  4782.7  415.00  4959.4  415.84  4979.5  415.72  4992.1  409.65
  4994.6  408.85  5010.6  409.65  5014.9  414.51  5023.2  416.05  5258.7  412.11
  5414.9  414.80  5472.9  417.36  5758.7  437.60  5829.5  441.27  5951.4  451.26
#Mann=5,-1,0
  3636.1    0.05       0  4782.7    0.16       0  4959.4    0.05       0
  4992.1    0.03       0  5010.6    0.05       0
Bank Sta=4575.2,5472.9
Exp/Cntr=0.3,0.1