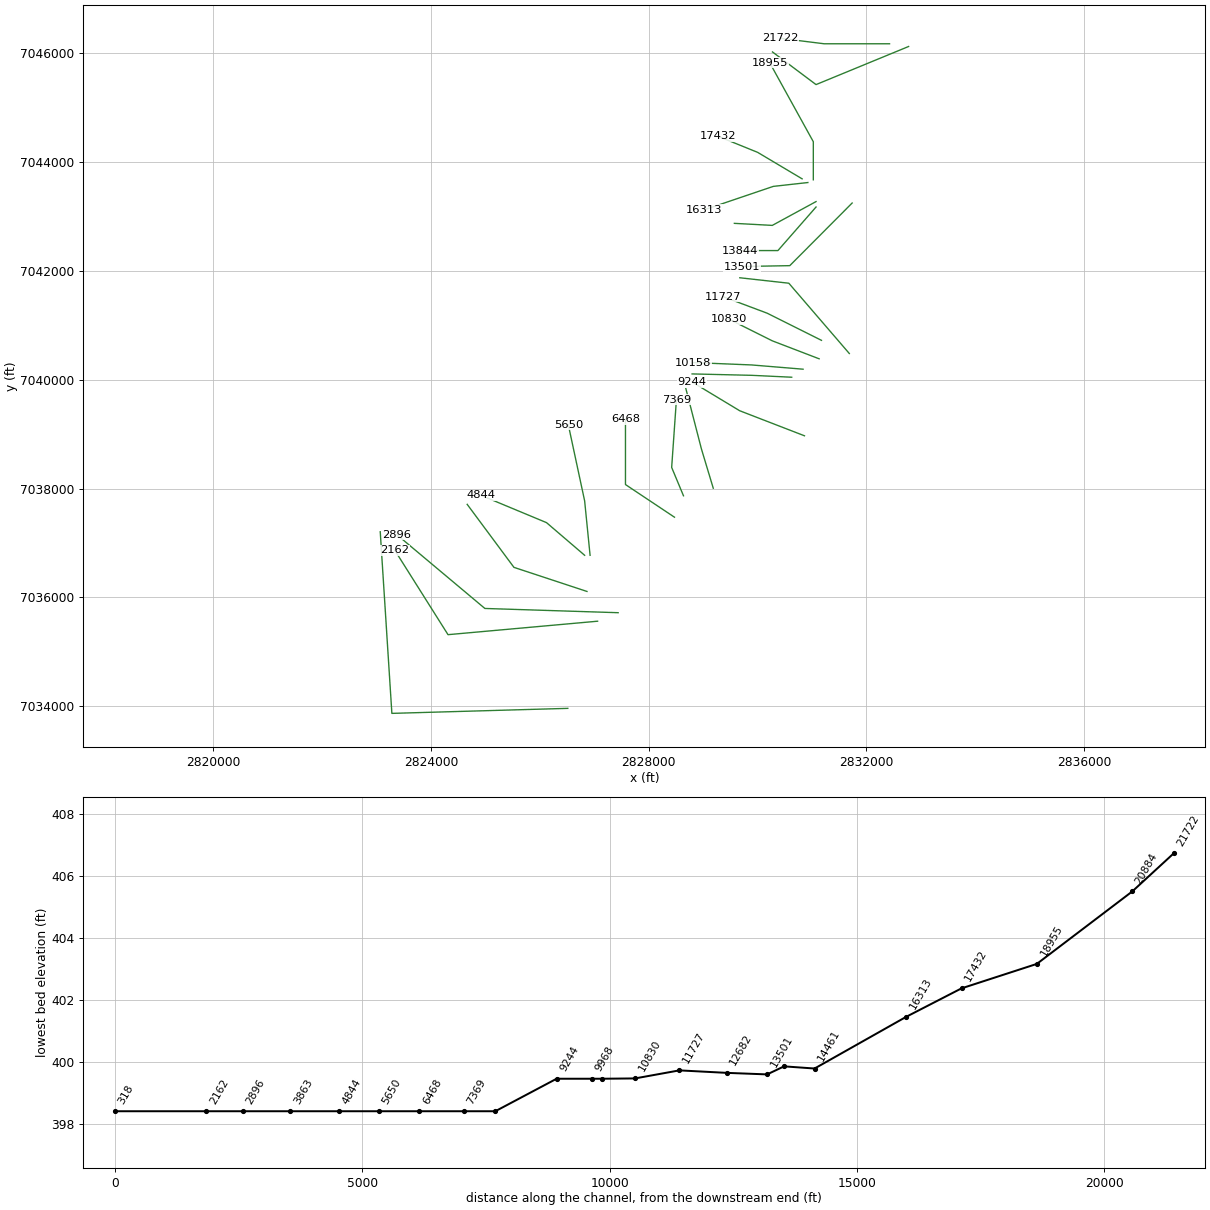
HEC-RAS study ELM CREEK.prj: ELM CREEK Base Level Engineering

--- ELM CREEK.g01 (geometry) --- (continued)

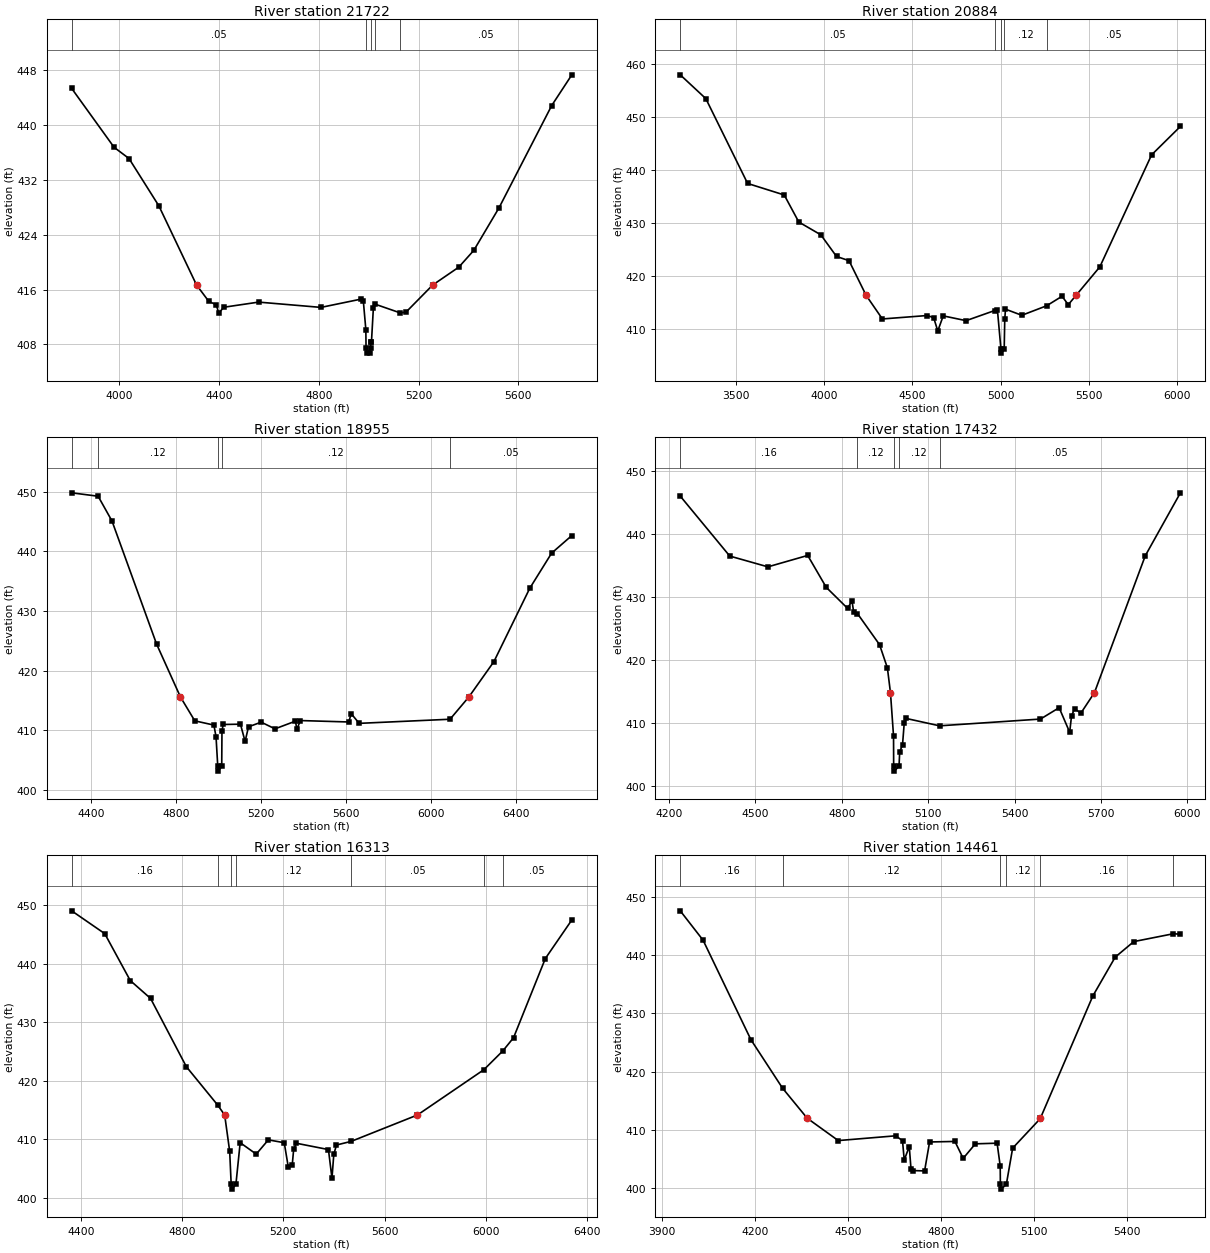
Type RM Length L Ch R = 1,21722,838,838,838
BEGIN DESCRIPTION:
ELM CREEK 18.0
END DESCRIPTION:
XS GIS Cut Line= 3
      2832425.03      7046175.00      2831225.00      7046175.00
      2830424.95      7046275.01
#Sta/Elev= 30
  3808.6  445.29  3978.6  436.72  4038.6  435.08  4158.6  428.17  4309.5  416.66
  4358.6  414.28  4388.6  413.78  4398.6  412.57  4418.6  413.42  4558.6  414.17
  4808.6  413.40  4968.6  414.60  4978.6  414.29  4988.6  410.17  4989.4  407.54
  4991.9  406.74  5005.4  406.74  5007.9  407.54  5008.6  408.35  5011.1  408.35
  5018.7  413.24  5026.5  413.86  5126.6  412.60  5149.7  412.71  5256.8  416.66
  5361.4  419.26  5421.8  421.71  5522.6  427.89  5734.2  442.80  5814.9  447.27
#Mann=5,-1,0
  3808.6    0.05       0  4989.4    0.03       0  5007.9    0.05       0
  5026.5    0.12       0  5126.6    0.05       0
Bank Sta=4309.5,5256.8
Exp/Cntr=0.3,0.1

Type RM Length L Ch R = 1,20884,1929,1929,1929
BEGIN DESCRIPTION:
ELM CREEK 17.0
END DESCRIPTION:
XS GIS Cut Line= 3
      2832774.97      7046124.99      2831075.00      7045425.00
      2830275.03      7046024.98
#Sta/Elev= 30
  3182.0  457.88  3327.2  453.40  3564.3  437.44  3772.1  435.27  3854.8  430.18
  3979.9  427.77  4068.8  423.70  4139.8  422.91  4236.9  416.38  4329.1  411.94
  4584.8  412.59  4620.3  412.17  4643.5  409.68  4674.4  412.52  4804.1  411.62
  4966.0  413.52  4981.8  413.69  5001.9  406.31  5004.4  405.51  5020.4  406.31
  5023.6  411.85  5027.7  413.78  5120.4  412.63  5261.3  414.42  5348.6  416.21
  5384.0  414.63  5428.2  416.38  5563.1  421.74  5856.9  442.82  6020.4  448.17
#Mann=5,-1,0
  3182.0    0.05       0  4966.0    0.12       0  5001.9    0.07       0
  5020.4    0.12       0  5261.3    0.05       0
Bank Sta=4236.9,5428.2
Exp/Cntr=0.3,0.1

Type RM Length L Ch R = 1,18955,1523,1523,1523
BEGIN DESCRIPTION:
ELM CREEK 16.0
END DESCRIPTION:
XS GIS Cut Line= 3
      2831025.00      7043674.98      2831025.00      7044375.00
      2830224.98      7045825.03
#Sta/Elev= 30
  4307.7  449.83  4432.3  449.26  4497.7  445.10  4707.7  424.47  4820.1  415.60
  4887.7  411.60  4977.7  410.89  4987.7  408.94  4995.9  403.97  4998.4  403.17
  5014.5  403.97  5015.7  409.92  5021.5  410.99  5102.8  411.04  5124.6  408.15
  5140.7  410.60  5200.3  411.38  5265.6  410.26  5361.8  411.55  5368.7  410.16
  5384.6  411.65  5612.9  411.41  5624.5  412.80  5662.1  411.18  6090.0  411.87
  6178.6  415.60  6297.0  421.55  6465.5  433.82  6568.6  439.72  6663.8  442.67
#Mann=5,-1,0
  4307.7    0.16       0  4432.3    0.12       0  4995.9    0.07       0
  5014.5    0.12       0  6090.0    0.05       0
Bank Sta=4820.1,6178.6
Exp/Cntr=0.3,0.1

Type RM Length L Ch R = 1,17432,1119,1119,1119
BEGIN DESCRIPTION:
double ELM CREEK 15.0
END DESCRIPTION:
XS GIS Cut Line= 3
      2830819.31      7043693.13      2830003.35      7044179.23
      2829275.00      7044475.00
#Sta/Elev= 30
  4239.6  445.96  4411.4  436.46  4543.8  434.75  4682.0  436.56  4746.2  431.51
  4820.2  428.18  4835.8  429.34  4841.6  427.55  4854.5  427.35  4931.2  422.43
  4958.5  418.75  4969.2  414.82  4979.9  407.92  4980.3  403.18  4982.8  402.38
  4998.9  403.18  5001.3  405.45  5011.0  406.53  5016.9  409.96  5024.5  410.72
  5139.5  409.56  5489.8  410.63  5554.6  412.43  5591.2  408.54  5597.7  411.17
  5608.5  412.26  5630.1  411.57  5677.2  414.82  5853.6  436.51  5975.5  446.48
#Mann=5,-1,0
  4239.6    0.16       0  4854.5    0.12       0  4980.3    0.07       0
  4998.9    0.12       0  5139.5    0.05       0
Bank Sta=4969.2,5677.2
Exp/Cntr=0.3,0.1

Type RM Length L Ch R = 1,16313,1852,1852,1852
BEGIN DESCRIPTION:
double ELM CREEK 14.0
END DESCRIPTION:
XS GIS Cut Line= 3
      2830925.03      7043625.00      2830289.81      7043554.23
      2829025.00      7043125.00
#Sta/Elev= 30
  4364.2  449.02  4494.8  445.12  4595.6  437.10  4675.7  434.05  4817.0  422.38
  4940.0  415.86  4968.3  414.13  4988.1  407.91  4994.0  402.26  4996.5  401.46
  5012.6  402.26  5029.5  409.40  5092.9  407.44  5140.7  409.88  5203.5  409.39
  5219.6  405.19  5234.9  405.53  5240.7  408.26  5251.3  409.30  5378.0  408.22
  5391.9  403.31  5399.2  407.41  5409.7  409.00  5467.7  409.62  5729.4  414.13
  5991.7  421.87  6066.3  425.07  6108.8  427.33  6234.4  440.87  6339.0  447.46
#Mann=7,-1,0
  4364.2    0.16       0  4940.0    0.12       0  4994.0    0.07       0
  5012.6    0.12       0  5467.7    0.05       0  5991.7    0.16       0
  6066.3    0.05       0
Bank Sta=4968.3,5729.4
Exp/Cntr=0.3,0.1

Type RM Length L Ch R = 1,14461,617,617,617
BEGIN DESCRIPTION:
ELM CREEK 13.0
END DESCRIPTION:
XS GIS Cut Line= 3
      2831074.96      7043274.98      2830271.68      7042837.49
      2829574.98      7042875.00
#Sta/Elev= 30
  3959.6  447.65  4033.2  442.60  4187.3  425.50  4289.3  417.16  4368.8  411.99
  4469.0  408.14  4654.2  408.96  4676.1  408.12  4681.7  404.79  4697.9  407.12
  4703.6  403.19  4711.1  402.98  4747.3  402.92  4763.4  407.90  4845.1  407.99
  4871.7  405.08  4911.0  407.58  4981.1  407.69  4991.1  403.76  4991.6  400.59
  4994.1  399.79  5010.8  400.59  5031.2  406.84  5118.6  411.82  5120.7  411.99
  5289.8  433.02  5361.7  439.68  5421.8  442.36  5549.4  443.71  5572.0  443.63
#Mann=6,-1,0
  3959.6    0.16       0  4289.3    0.12       0  4991.6    0.07       0
  5010.8    0.12       0  5118.6    0.16       0  5549.4    0.05       0
Bank Sta=4368.8,5120.7
Exp/Cntr=0.3,0.1

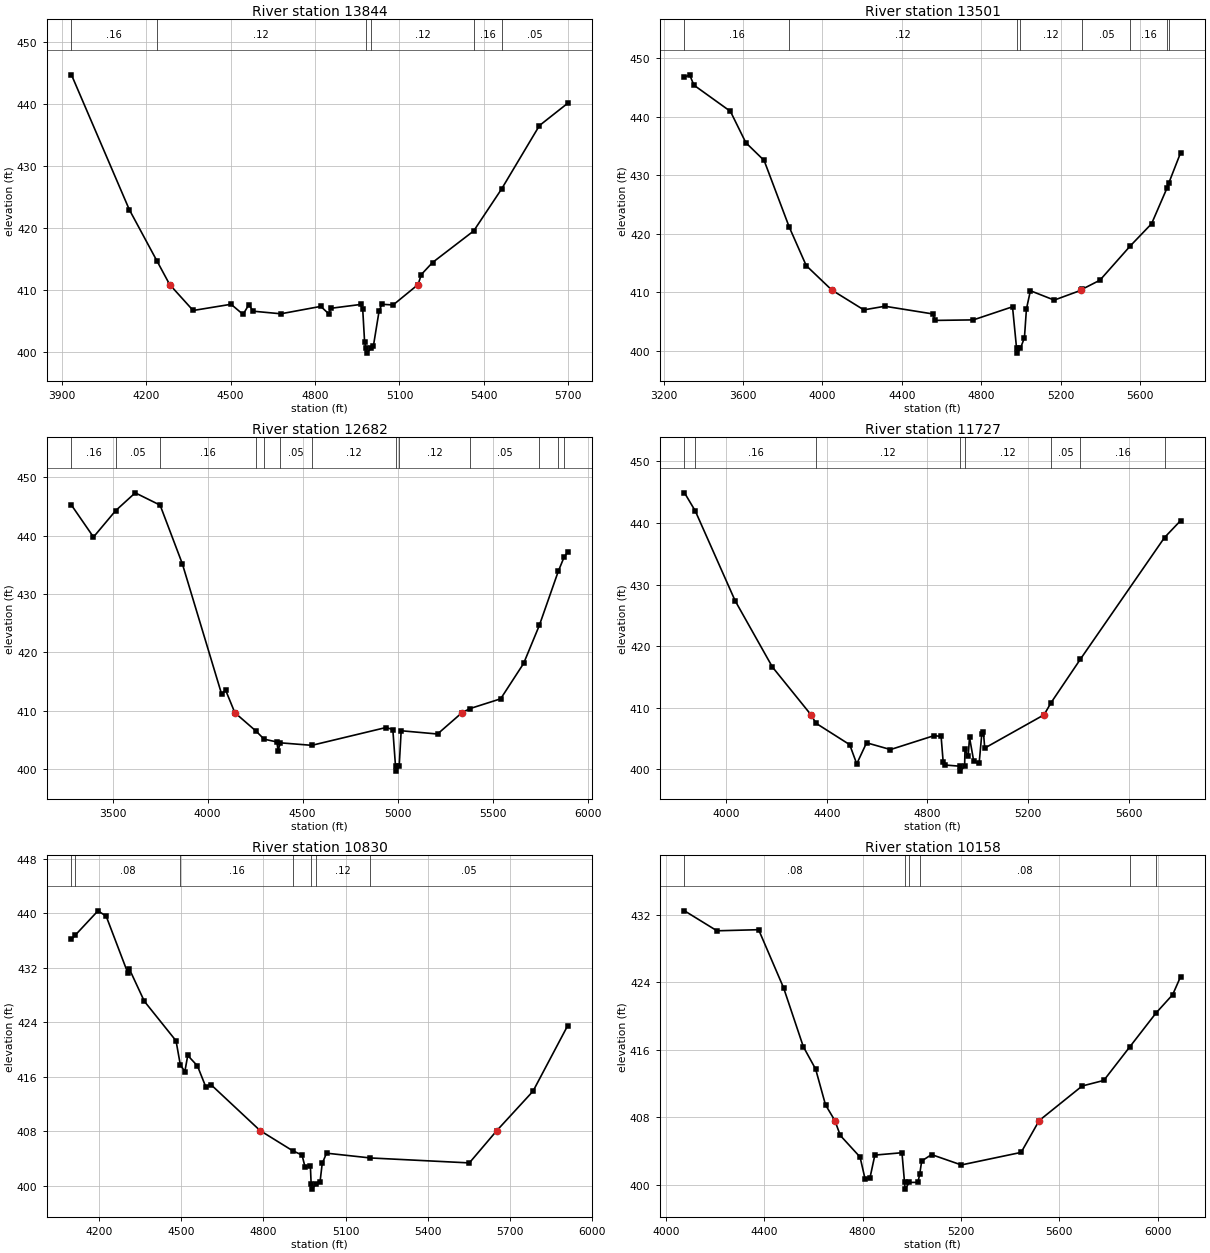
Type RM Length L Ch R = 1,13844,343,343,343
BEGIN DESCRIPTION:
ELM CREEK 12.0
END DESCRIPTION:
XS GIS Cut Line= 3
      2831074.99      7043174.99      2830375.00      7042375.00
      2829675.00      7042375.00
#Sta/Elev= 30
  3934.5  444.64  4140.0  422.95  4237.8  414.73  4283.4  410.90  4366.8  406.72
  4501.6  407.72  4544.3  406.09  4565.2  407.68  4579.4  406.61  4678.6  406.19
  4820.5  407.38  4849.0  406.17  4855.6  407.07  4961.9  407.69  4969.5  406.90
  4976.1  401.71  4980.8  400.66  4983.3  399.86  5000.0  400.66  5007.5  401.03
  5027.5  406.59  5037.5  407.72  5077.5  407.61  5166.4  410.90  5177.5  412.50
  5217.5  414.44  5363.8  419.52  5462.8  426.26  5597.5  436.48  5697.5  440.05
#Mann=6,-1,0
  3934.5    0.16       0  4237.8    0.12       0  4980.8    0.07       0
  5000.0    0.12       0  5363.8    0.16       0  5462.8    0.05       0
Bank Sta=4283.4,5166.4
Exp/Cntr=0.3,0.1

Type RM Length L Ch R = 1,13501,819,819,819
BEGIN DESCRIPTION:
Mapping XS f5c01a00
END DESCRIPTION:
XS GIS Cut Line= 3
      2831738.33      7043248.61      2830592.47      7042097.55
      2829718.78      7042081.94
#Sta/Elev= 30
  3305.3  446.74  3331.4  447.15  3352.6  445.39  3536.5  440.91  3614.3  435.55
  3706.2  432.52  3832.4  421.16  3918.3  414.55  4047.4  410.37  4208.2  406.99
  4314.3  407.61  4554.7  406.30  4568.8  405.19  4759.8  405.28  4956.9  407.52
  4977.4  400.40  4979.9  399.60  4996.6  400.40  5017.0  402.24  5027.0  407.14
  5047.0  410.26  5167.0  408.66  5304.1  410.37  5308.5  410.53  5397.0  412.06
  5550.5  417.94  5657.1  421.71  5734.0  427.74  5743.8  428.66  5803.3  433.84
#Mann=8,-1,0
  3305.3    0.16       0  3832.4    0.12       0  4977.4    0.07       0
  4996.6    0.12       0  5308.5    0.05       0  5550.5    0.16       0
  5734.0    0.12       0  5743.8    0.16       0
Bank Sta=4047.4,5304.1
Exp/Cntr=0.3,0.1

Type RM Length L Ch R = 1,12682,955,955,955
BEGIN DESCRIPTION:
double ELM CREEK 11.0
END DESCRIPTION:
XS GIS Cut Line= 3
      2831686.21      7040482.98      2830575.00      7041775.00
      2829674.98      7041875.00
#Sta/Elev= 30
  3284.0  445.23  3399.8  439.76  3516.2  444.28  3619.3  447.34  3750.3  445.23
  3867.3  435.17  4073.6  412.87  4094.4  413.56  4143.4  409.66  4256.2  406.47
  4297.1  405.13  4364.3  404.65  4370.9  403.17  4382.7  404.50  4548.2  404.07
  4938.2  407.12  4974.4  406.78  4988.6  400.45  4991.1  399.65  5007.8  400.45
  5018.3  406.57  5209.5  406.01  5338.0  409.66  5379.6  410.36  5541.5  412.04
  5662.3  418.10  5745.0  424.62  5844.9  433.91  5874.9  436.29  5893.7  437.16
#Mann=13,-1,0
  3284.0    0.16       0  3516.2    0.05       0  3750.3    0.16       0
  4256.2    0.12       0  4297.1    0.07       0  4382.7    0.05       0
  4548.2    0.12       0  4988.6    0.07       0  5007.8    0.12       0
  5379.6    0.05       0  5745.0    0.12       0  5844.9    0.16       0
  5874.9    0.12       0
Bank Sta=4143.4,5338
Exp/Cntr=0.3,0.1

Type RM Length L Ch R = 1,11727,897,897,897
BEGIN DESCRIPTION:
double ELM CREEK 10.0
END DESCRIPTION:
XS GIS Cut Line= 3
      2831175.01      7040725.00      2830175.00      7041225.00
      2829375.04      7041524.99
#Sta/Elev= 30
  3834.0  444.89  3877.0  441.94  4035.3  427.38  4183.4  416.63  4337.0  408.87
  4357.1  407.49  4490.9  404.02  4518.8  400.91  4557.9  404.33  4653.0  403.23
  4826.3  405.49  4854.2  405.36  4862.6  401.14  4871.0  400.72  4928.5  400.53
  4931.0  399.73  4947.7  400.53  4949.2  403.27  4961.8  402.13  4967.2  405.20
  4984.1  401.31  5005.4  400.98  5016.1  405.82  5022.4  406.08  5027.7  403.47
  5263.5  408.87  5291.6  410.85  5407.9  417.89  5742.5  437.64  5806.4  440.38
#Mann=8,-1,0
  3834.0    0.05       0  3877.0    0.16       0  4357.1    0.12       0
  4928.5    0.07       0  4947.7    0.12       0  5291.6    0.05       0
  5407.9    0.16       0  5742.5    0.05       0
Bank Sta=4337,5263.5
Exp/Cntr=0.3,0.1

Type RM Length L Ch R = 1,10830,672,672,672
BEGIN DESCRIPTION:
Mapping XS df4c70d7
END DESCRIPTION:
XS GIS Cut Line= 3
      2831131.86      7040385.81      2830272.45      7040715.69
      2829473.86      7041114.98
#Sta/Elev= 30
  4098.3  436.14  4112.2  436.77  4195.2  440.34  4225.2  439.55  4304.6  431.17
  4309.9  431.79  4364.6  427.06  4480.5  421.25  4496.2  417.72  4512.7  416.74
  4523.3  419.10  4558.7  417.57  4588.7  414.54  4608.0  414.82  4787.7  408.07
  4906.2  405.12  4941.1  404.47  4952.2  402.69  4971.5  402.90  4974.3  400.27
  4976.8  399.47  4993.7  400.27  5006.9  400.55  5014.8  403.24  5030.6  404.75
  5190.1  404.05  5552.6  403.32  5653.1  408.07  5785.3  413.85  5911.7  423.45
#Mann=7,-1,0
  4098.3    0.05       0  4112.2    0.08       0  4496.2    0.16       0
  4906.2    0.12       0  4974.3    0.07       0  4993.7    0.12       0
  5190.1    0.05       0
Bank Sta=4787.7,5653.1
Exp/Cntr=0.3,0.1

Type RM Length L Ch R = 1,10158,190,190,190
BEGIN DESCRIPTION:
Mapping XS 80e4fdba
END DESCRIPTION:
XS GIS Cut Line= 3
      2830836.65      7040194.86      2829890.50      7040272.98
      2828822.75      7040316.38
#Sta/Elev= 30
  4075.6  432.49  4207.7  430.12  4377.2  430.25  4478.6  423.36  4558.9  416.37
  4609.1  413.70  4649.2  409.46  4687.2  407.60  4709.4  405.83  4789.7  403.27
  4809.7  400.72  4829.8  400.76  4849.9  403.50  4960.2  403.78  4970.6  400.26
  4973.1  399.46  4990.1  400.26  5025.0  400.26  5032.2  401.21  5040.5  402.80
  5080.5  403.56  5201.7  402.33  5444.9  403.82  5518.4  407.60  5693.1  411.70
  5781.1  412.36  5886.2  416.32  5994.1  420.38  6061.3  422.54  6093.6  424.68
#Mann=6,-1,0
  4075.6    0.08       0  4970.6    0.04       0  4990.1    0.08       0
  5032.2    0.08       0  5886.2    0.05       0  5994.1    0.08       0
Bank Sta=4687.2,5518.4
Exp/Cntr=0.3,0.1

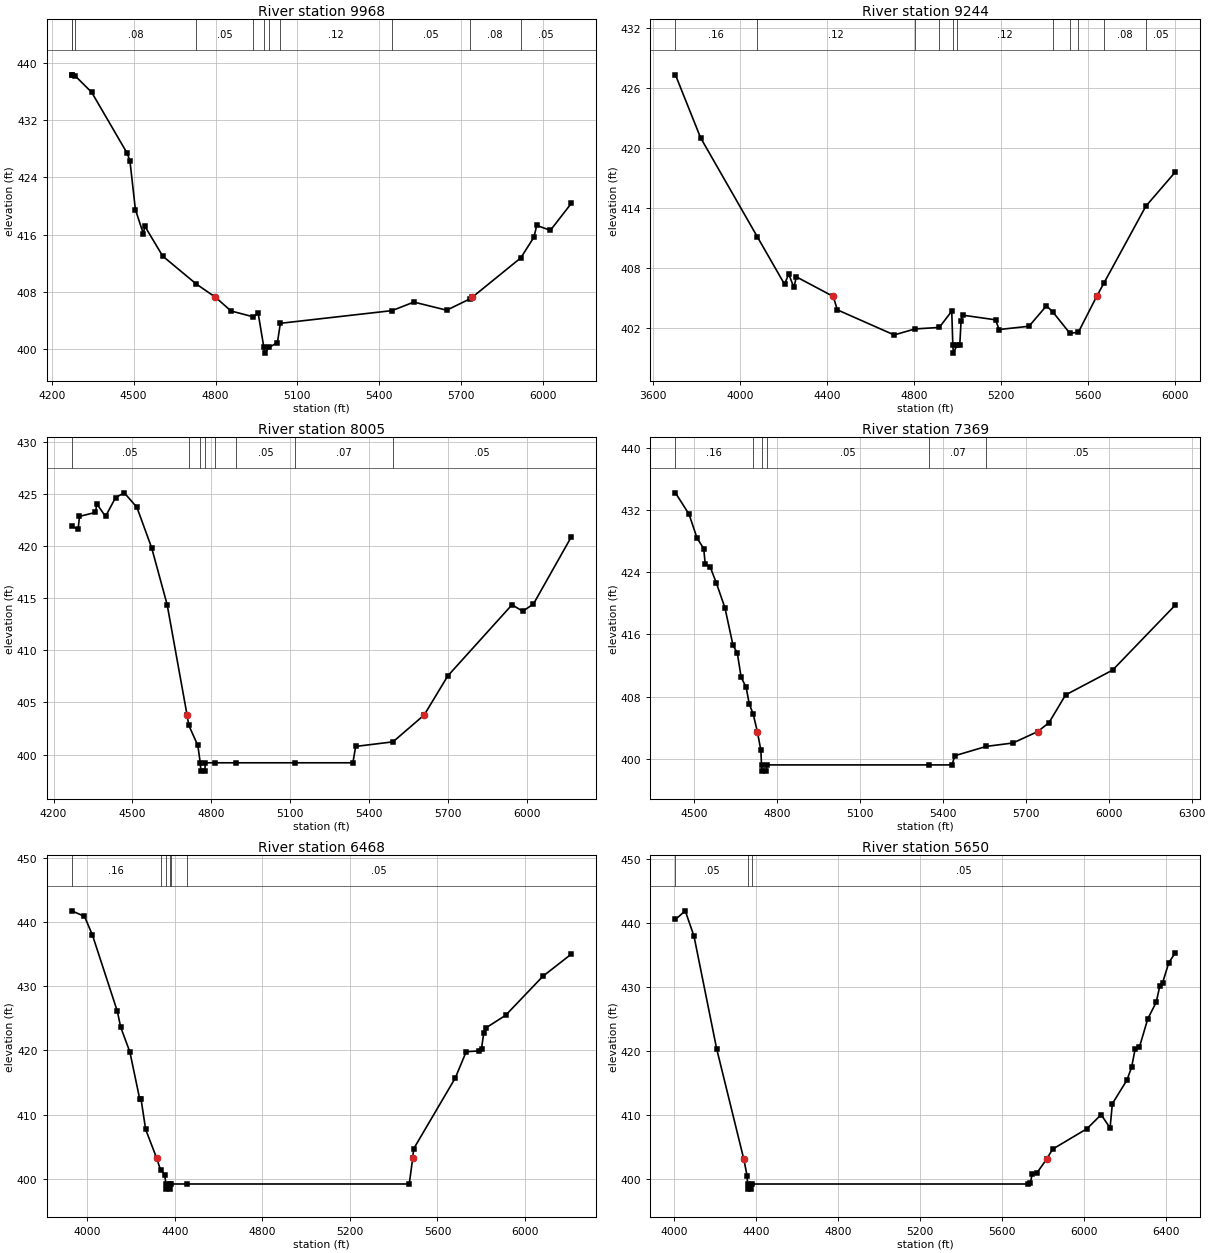
Type RM Length L Ch R = 1,9968,724,724,724
BEGIN DESCRIPTION:
Mapping XS fdca467a
END DESCRIPTION:
XS GIS Cut Line= 3
      2830628.34      7040047.28      2829899.18      7040082.01
      2828798.38      7040108.01
#Sta/Elev= 30
  4272.8  438.29  4274.5  438.29  4286.9  438.10  4346.2  435.85  4476.4  427.34
  4486.4  426.29  4506.4  419.49  4535.8  416.09  4540.8  417.18  4606.5  413.00
  4729.6  409.10  4799.6  407.27  4856.8  405.34  4938.4  404.53  4956.3  405.04
  4977.2  400.26  4979.7  399.46  4996.7  400.26  5027.0  400.94  5037.6  403.62
  5446.6  405.39  5527.1  406.58  5647.2  405.45  5731.5  407.01  5741.5  407.27
  5918.8  412.75  5967.2  415.65  5977.2  417.28  6027.3  416.59  6103.9  420.35
#Mann=11,-1,0
  4272.8    0.08       0  4274.5     0.1       0  4286.9    0.08       0
  4729.6    0.05       0  4938.4     0.1       0  4977.2    0.07       0
  4996.7     0.1       0  5037.6    0.12       0  5446.6    0.05       0
  5731.5    0.08       0  5918.8    0.05       0
Bank Sta=4799.6,5741.5
Exp/Cntr=0.3,0.1

Type RM Length L Ch R = 1,9244,1239,1239,1239
BEGIN DESCRIPTION:
Mapping XS eb80dca0
END DESCRIPTION:
XS GIS Cut Line= 3
      2830862.70      7038970.91      2829673.49      7039430.96
      2828798.74      7039959.28
#Sta/Elev= 30
  3704.5  427.30  3820.0  421.01  4080.4  411.12  4206.1  406.35  4225.3  407.38
  4248.9  406.03  4260.6  407.09  4430.0  405.13  4448.8  403.79  4709.9  401.28
  4806.1  401.88  4917.6  402.03  4974.8  403.66  4979.8  400.26  4982.3  399.46
  4999.3  400.26  5011.7  400.28  5017.6  402.65  5024.6  403.26  5176.7  402.79
  5192.2  401.82  5330.0  402.15  5410.1  404.19  5439.5  403.58  5518.0  401.44
  5556.9  401.55  5641.0  405.13  5674.3  406.46  5867.2  414.16  6001.5  417.55
#Mann=11,-1,0
  3704.5    0.16       0  4080.4    0.12       0  4806.1    0.05       0
  4917.6    0.12       0  4979.8    0.07       0  4999.3    0.12       0
  5439.5     0.1       0  5518.0    0.08       0  5556.9    0.05       0
  5674.3    0.08       0  5867.2    0.05       0
Bank Sta=4430,5641
Exp/Cntr=0.3,0.1

Type RM Length L Ch R = 1,8005,636,636,636
BEGIN DESCRIPTION:
Mapping XS 8df110ae
END DESCRIPTION:
XS GIS Cut Line= 3
      2829187.38      7038007.36      2828970.37      7038727.84
      2828683.91      7039838.95
#Sta/Elev= 30
  4268.7  421.91  4293.3  421.61  4298.5  422.85  4359.3  423.23  4364.5  424.05
  4397.5  422.84  4435.8  424.66  4468.8  425.11  4516.9  423.72  4573.0  419.83
  4631.8  414.39  4707.5  403.80  4714.2  402.80  4748.5  400.88  4757.7  399.21
  4760.2  398.41  4774.8  398.41  4777.3  399.21  4815.6  399.21  4892.0  399.21
  5119.0  399.21  5338.1  399.21  5348.7  400.78  5490.7  401.22  5609.4  403.80
  5699.1  407.55  5943.2  414.37  5983.9  413.75  6024.6  414.44  6168.6  420.88
#Mann=8,-1,0
  4268.7    0.05       0  4714.2    0.16       0  4757.7   0.033       0
  4777.3    0.16       0  4815.6    0.07       0  4892.0    0.05       0
  5119.0    0.07       0  5490.7    0.05       0
Bank Sta=4707.5,5609.4
Exp/Cntr=0.3,0.1

Type RM Length L Ch R = 1,7369,901,901,901
BEGIN DESCRIPTION:
Mapping XS 1921f685
END DESCRIPTION:
XS GIS Cut Line= 3
      2828640.52      7037868.44      2828423.49      7038389.30
      2828510.27      7039630.30
#Sta/Elev= 30
  4431.7  434.21  4480.9  431.46  4510.1  428.37  4534.0  427.04  4539.4  425.11
  4557.8  424.65  4579.6  422.63  4610.9  419.41  4640.1  414.59  4655.5  413.63
  4669.4  410.50  4687.8  409.17  4698.8  407.05  4712.9  405.79  4728.1  403.50
  4740.9  401.09  4743.2  399.21  4745.7  398.41  4760.3  398.41  4762.8  399.21
  5351.0  399.21  5432.7  399.21  5442.8  400.39  5556.7  401.59  5653.3  402.03
  5743.1  403.50  5783.6  404.64  5843.7  408.21  6014.1  411.41  6240.0  419.74
#Mann=6,-1,0
  4431.7    0.16       0  4712.9    0.05       0  4743.2   0.033       0
  4762.8    0.05       0  5351.0    0.07       0  5556.7    0.05       0
Bank Sta=4728.1,5743.1
Exp/Cntr=0.3,0.1

Type RM Length L Ch R = 1,6468,818,818,818
BEGIN DESCRIPTION:
ELM CREEK 4.0
END DESCRIPTION:
XS GIS Cut Line= 3
      2828475.00      7037475.00      2827575.00      7038075.00
      2827575.00      7039275.03
#Sta/Elev= 30
  3929.3  441.74  3987.9  440.88  4023.9  438.00  4138.1  426.08  4153.1  423.64
  4195.2  419.76  4240.3  412.42  4246.3  412.41  4267.3  407.70  4317.5  403.24
  4335.1  401.40  4354.5  400.66  4359.6  399.21  4362.1  398.41  4376.9  398.41
  4379.4  399.21  4382.6  399.21  4456.0  399.21  5471.0  399.21  5486.9  403.24
  5491.0  404.68  5681.0  415.70  5731.0  419.80  5791.0  419.93  5801.0  420.28
  5811.0  422.66  5821.0  423.51  5911.0  425.47  6081.0  431.54  6211.0  435.00
#Mann=6,-1,0
  3929.3    0.16       0  4335.1    0.05       0  4359.6   0.033       0
  4379.4    0.05       0  4382.6    0.07       0  4456.0    0.05       0
Bank Sta=4317.5,5486.9
Exp/Cntr=0.3,0.1

Type RM Length L Ch R = 1,5650,806,806,806
BEGIN DESCRIPTION:
ELM CREEK 3.0
END DESCRIPTION:
XS GIS Cut Line= 3
      2826925.00      7036774.96      2826825.00      7037775.00
      2826525.00      7039174.99
#Sta/Elev= 30
  4007.2  440.53  4055.0  441.88  4097.7  437.92  4208.2  420.34  4340.7  403.08
  4356.5  400.52  4359.1  399.21  4361.6  398.41  4376.4  398.41  4378.9  399.21
  5728.1  399.21  5738.3  399.44  5747.7  400.82  5769.0  400.90  5817.4  403.08
  5846.6  404.65  6014.5  407.85  6083.5  410.04  6127.0  407.96  6138.1  411.75
  6208.8  415.42  6231.8  417.42  6249.7  420.37  6270.2  420.59  6311.1  425.04
  6352.0  427.59  6369.9  430.20  6382.7  430.59  6413.3  433.78  6444.0  435.28
#Mann=3,-1,0
  4007.2    0.05       0  4359.1   0.033       0  4378.9    0.05       0
Bank Sta=4340.7,5817.4
Exp/Cntr=0.3,0.1

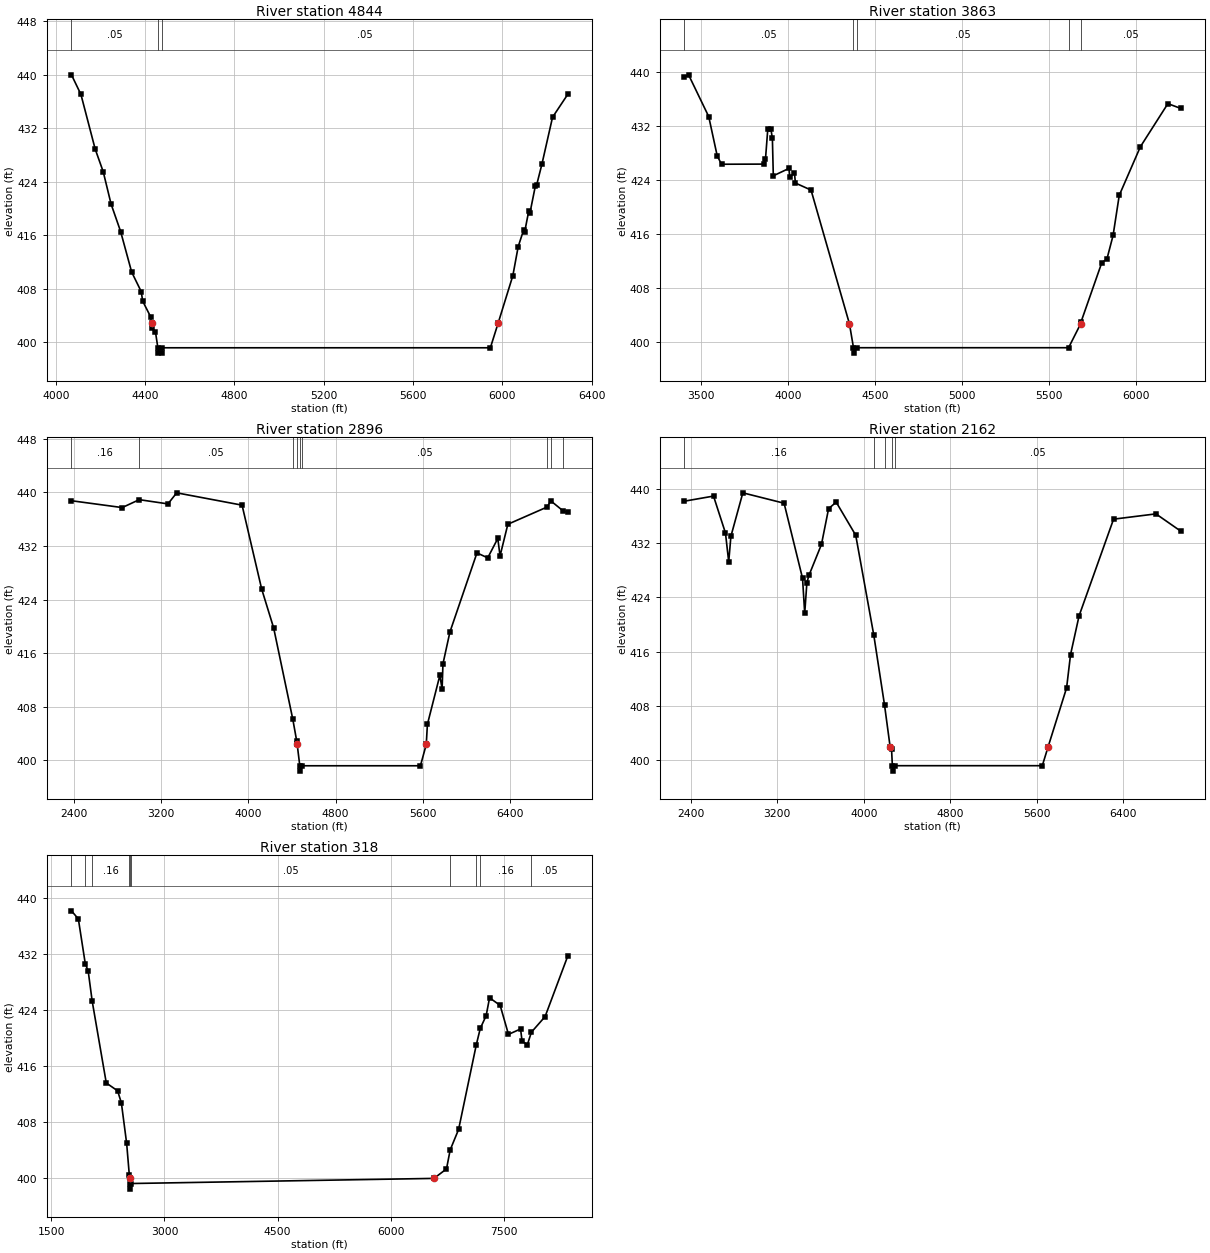
Type RM Length L Ch R = 1,4844,981,981,981
BEGIN DESCRIPTION:
ELM CREEK 2.0
END DESCRIPTION:
XS GIS Cut Line= 3
      2826825.04      7036774.97      2826125.00      7037375.00
      2824925.00      7037875.00
#Sta/Elev= 30
  4070.4  440.01  4112.7  437.08  4176.4  428.93  4212.6  425.52  4247.7  420.70
  4290.5  416.59  4339.9  410.53  4382.7  407.61  4389.3  406.18  4425.5  403.80
  4428.8  402.95  4432.1  402.10  4446.4  401.60  4457.3  399.21  4459.8  398.41
  4474.6  398.41  4477.1  399.21  5946.3  399.21  5981.6  402.95  6047.0  410.00
  6070.9  414.33  6094.7  416.77  6100.1  416.57  6118.5  419.71  6123.9  419.42
  6147.8  423.41  6153.2  423.50  6177.0  426.64  6224.7  433.67  6292.4  437.07
#Mann=3,-1,0
  4070.4    0.05       0  4457.3   0.033       0  4477.1    0.05       0
Bank Sta=4428.8,5981.6
Exp/Cntr=0.3,0.1

Type RM Length L Ch R = 1,3863,967,967,967
BEGIN DESCRIPTION:
Mapping XS f7919cc6
END DESCRIPTION:
XS GIS Cut Line= 3
      2826867.66      7036110.49      2825526.56      7036553.18
      2824667.96      7037710.98
#Sta/Elev= 30
  3403.6  439.23  3427.5  439.56  3543.3  433.39  3592.1  427.58  3617.0  426.34
  3859.2  426.36  3869.8  427.09  3883.1  431.58  3901.3  431.49  3909.5  430.15
  3914.8  424.63  4004.8  425.72  4010.1  424.43  4036.5  425.05  4041.8  423.56
  4131.8  422.52  4352.7  402.74  4375.9  399.21  4378.4  398.41  4395.7  399.21
  5613.0  399.21  5682.3  402.74  5683.8  402.96  5804.2  411.80  5833.5  412.32
  5868.9  415.81  5904.4  421.74  6025.8  428.92  6184.1  435.30  6257.3  434.60
#Mann=5,-1,0
  3403.6    0.05       0  4375.9   0.033       0  4395.7    0.05       0
  5613.0    0.07       0  5683.8    0.05       0
Bank Sta=4352.7,5682.3
Exp/Cntr=0.3,0.1

Type RM Length L Ch R = 1,2896,734,734,734
BEGIN DESCRIPTION:
Mapping XS 9b4487f2
END DESCRIPTION:
XS GIS Cut Line= 3
      2827440.66      7035719.84      2824992.70      7035797.97
      2823378.11      7037152.14
#Sta/Elev= 30
  2375.0  438.74  2840.9  437.72  2997.3  438.90  3261.1  438.27  3341.2  439.92
  3941.5  438.08  4121.6  425.57  4231.6  419.77  4407.8  406.12  4443.3  402.90
  4447.7  402.39  4471.8  399.21  4474.3  398.41  4491.7  399.21  5579.5  399.21
  5633.1  402.39  5643.5  405.38  5757.7  412.68  5778.6  410.65  5786.3  414.41
  5850.1  419.15  6098.6  430.96  6197.5  430.22  6289.8  433.11  6310.7  430.51
  6382.2  435.23  6744.1  437.81  6776.1  438.73  6892.4  437.19  6931.5  437.04
#Mann=9,-1,0
  2375.0    0.16       0  2997.3    0.05       0  4407.8    0.16       0
  4443.3    0.05       0  4471.8   0.033       0  4491.7    0.05       0
  6744.1    0.16       0  6776.1    0.12       0  6892.4    0.05       0
Bank Sta=4447.7,5633.1
Exp/Cntr=0.3,0.1

Type RM Length L Ch R = 1,2162,1844,1844,1844
BEGIN DESCRIPTION:
Mapping XS 5d95762f
END DESCRIPTION:
XS GIS Cut Line= 3
      2827063.07      7035563.60      2824315.62      7035316.20
      2823339.54      7036864.91
#Sta/Elev= 30
  2342.0  438.17  2611.1  438.92  2721.6  433.48  2751.7  429.23  2771.8  432.99
  2882.2  439.40  3263.8  437.87  3434.5  426.81  3454.5  421.64  3474.6  426.17
  3493.4  427.23  3609.4  431.80  3675.4  437.07  3745.7  438.03  3926.4  433.15
  4093.4  418.45  4192.7  408.15  4244.2  402.03  4257.8  401.60  4265.3  399.21
  4267.8  398.41  4285.2  399.21  5651.9  399.21  5706.5  402.03  5876.7  410.67
  5913.2  415.57  5992.1  421.28  6311.1  435.52  6703.0  436.30  6931.2  433.77
#Mann=5,-1,0
  2342.0    0.16       0  4093.4    0.12       0  4192.7    0.05       0
  4265.3   0.033       0  4285.2    0.05       0
Bank Sta=4244.2,5706.5
Exp/Cntr=0.3,0.1

Type RM Length L Ch R = 1,318,0,0,0
BEGIN DESCRIPTION:
ELM CREEK 1.0
END DESCRIPTION:
XS GIS Cut Line= 3
      2826516.19      7033962.03      2823284.61      7033869.83
      2823070.87      7037207.99
#Sta/Elev= 30
  1767.1  438.10  1858.3  436.94  1950.2  430.55  1988.4  429.53  2041.8  425.21
  2228.5  413.55  2378.5  412.43  2428.6  410.71  2498.6  404.93  2534.3  400.37
  2536.9  399.94  2538.6  399.21  2541.1  398.41  2558.6  399.21  6572.3  399.94
  6738.7  401.29  6787.6  404.00  6899.1  406.92  7134.3  419.02  7186.8  421.34
  7263.9  423.13  7309.9  425.70  7450.2  424.61  7560.4  420.48  7720.7  421.25
  7740.8  419.51  7810.9  419.01  7864.4  420.79  8046.0  423.02  8345.0  431.61
#Mann=10,-1,0
  1767.1    0.16       0  1950.2    0.05       0  2041.8    0.16       0
  2534.3    0.05       0  2538.6   0.033       0  2558.6    0.05       0
  6787.6     0.1       0  7134.3    0.05       0  7186.8    0.16       0
  7864.4    0.05       0
Bank Sta=2536.9,6572.3
Exp/Cntr=0.3,0.1

Chan Stop Cuts=-1