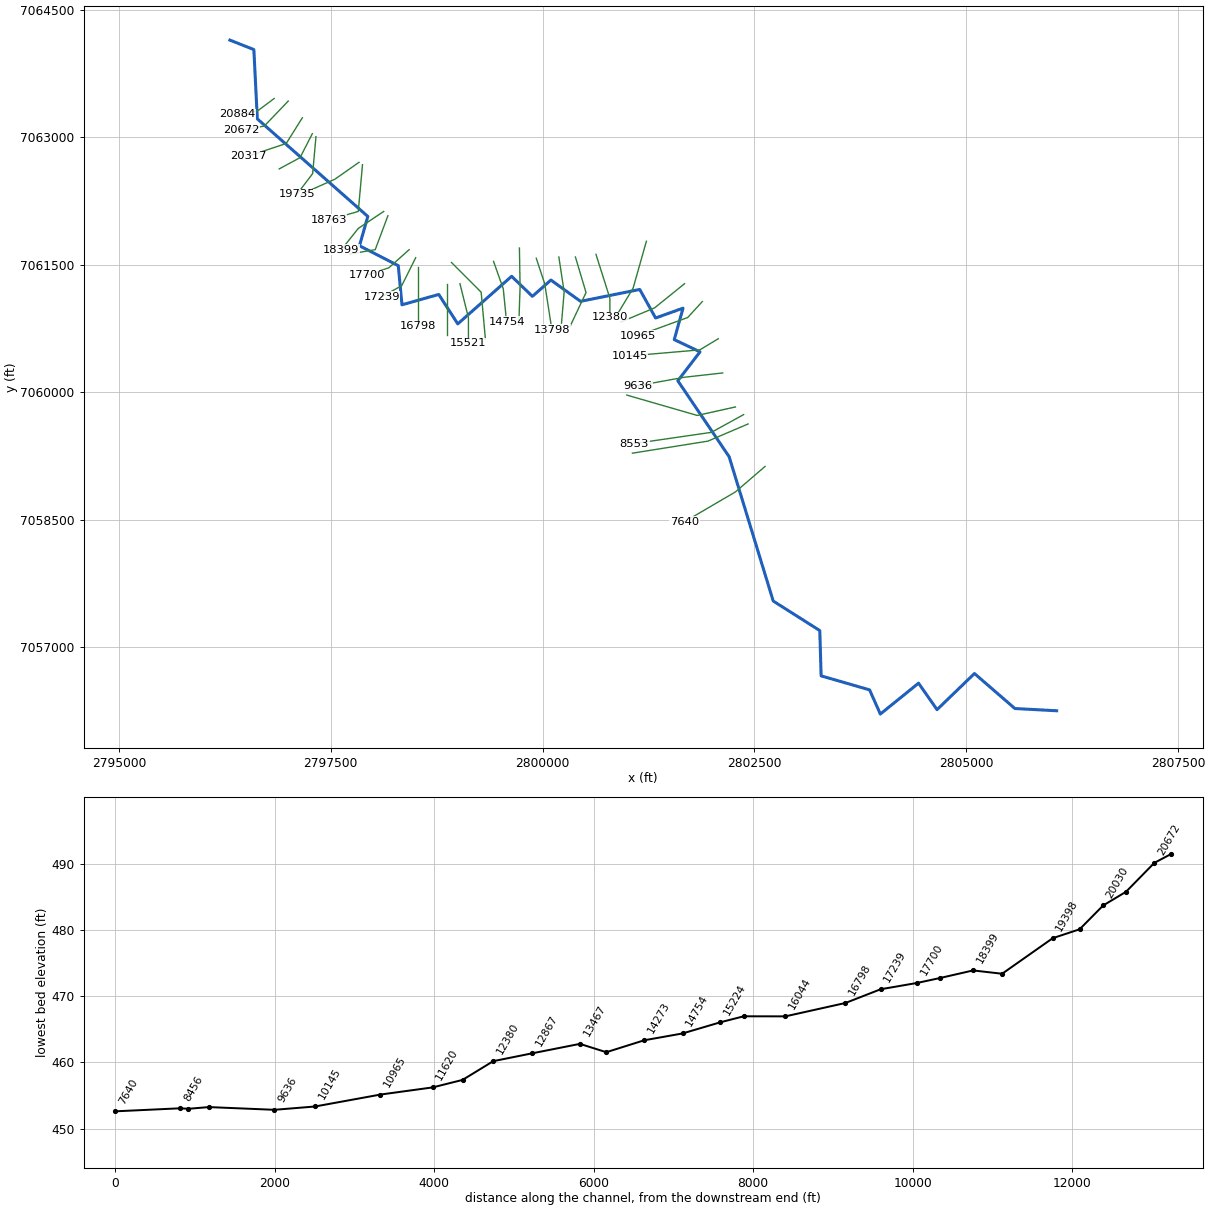
--- GARRETT CREEK.prj (project) ---

Proj Title=GARRETT CREEK Base Level Engineering
Current Plan=p01
Default Exp/Contr=0.3,0.1
English Units
Geom File=g01
Flow File=f01
Plan File=p01
BEGIN DESCRIPTION:
GARRETT CREEK
END DESCRIPTION:

--- GARRETT CREEK.p01 (plan) ---

Plan Title=Multiple Run
Short Identifier=Multiple
Geom File=g01
Flow File=f01
Subcritical Flow
K Sum by GR= 0
Std Step Tol= 0.01
Critical Tol= 0.01
Num of Std Step Trials= 20
Max Error Tol= 0.3
Flow Tol Ratio= 0.001
Split Flow NTrial= 30
Split Flow Tol= 0.02
Split Flow Ratio= 0.02
Log Output Level= 0
Friction Slope Method= 1
Unsteady Friction Slope Method= 2
Unsteady Bridges Friction Slope Method= 1
Parabolic Critical Depth
Global Vel Dist=  1 , 1 , 1
Global Log Level= 0
CheckData=True
Encroach Param= -1, 0, 0, 0
BEGIN DESCRIPTION:
Multiple Run
END DESCRIPTION:

--- GARRETT CREEK.f01 (steady flow) ---

Flow Title=Multiple
Number of Profiles=7
Profile Names=10-year,25-year,50-year,1pct_min,100-year,1pct_plu,500-year
River Rch & RM= GARRETT CREEK,Reach-1,20884
     578     763     911     539    1076    2146    1497
River Rch & RM= GARRETT CREEK,Reach-1,16798
     899    1211    1464     877    1749    3490    2492
River Rch & RM= GARRETT CREEK,Reach-1,8553
    1080    1470    1789    1078    2150    4291    3102
River Rch & RM= GARRETT CREEK,Reach-1,5381
    1348    1857    2279    1384    2761    5509    4052
Boundary for River Rch & Prof#=GARRETT CREEK,Reach-1,1
Up Type=0
Dn Type=3
Dn Slope=0.005
Boundary for River Rch & Prof#=GARRETT CREEK,Reach-1,2
Up Type=0
Dn Type=3
Dn Slope=0.005
Boundary for River Rch & Prof#=GARRETT CREEK,Reach-1,3
Up Type=0
Dn Type=3
Dn Slope=0.005
Boundary for River Rch & Prof#=GARRETT CREEK,Reach-1,4
Up Type=0
Dn Type=3
Dn Slope=0.005
Boundary for River Rch & Prof#=GARRETT CREEK,Reach-1,5
Up Type=0
Dn Type=3
Dn Slope=0.005
Boundary for River Rch & Prof#=GARRETT CREEK,Reach-1,6
Up Type=0
Dn Type=3
Dn Slope=0.005
Boundary for River Rch & Prof#=GARRETT CREEK,Reach-1,7
Up Type=0
Dn Type=3
Dn Slope=0.005

--- GARRETT CREEK.g01 (geometry) ---

Geom Title=Existing Conditions

River Reach=GARRETT CREEK,Reach-1
Reach XY= 30
      2796310.59      7064140.71      2796593.19      7064029.55
      2796633.93      7063214.35      2797937.67      7062066.12
      2797839.22      7061721.58      2798297.13      7061487.34
      2798340.94      7061026.88      2798774.58      7061148.41
      2798999.47      7060802.44      2799634.65      7061362.16
      2799879.57      7061126.26      2800098.19      7061317.84
      2800447.53      7061067.66      2801146.23      7061207.40
      2801333.29      7060871.58      2801657.10      7060987.28
      2801553.42      7060616.89      2801857.69      7060473.40
      2801595.49      7060133.07      2802201.02      7059239.80
      2802721.22      7057541.54      2803270.73      7057194.16
      2803286.45      7056661.20      2803858.28      7056496.66
      2803985.31      7056212.04      2804436.10      7056575.33
      2804654.14      7056263.79      2805095.66      7056688.83
      2805572.75      7056276.99      2806065.59      7056250.71

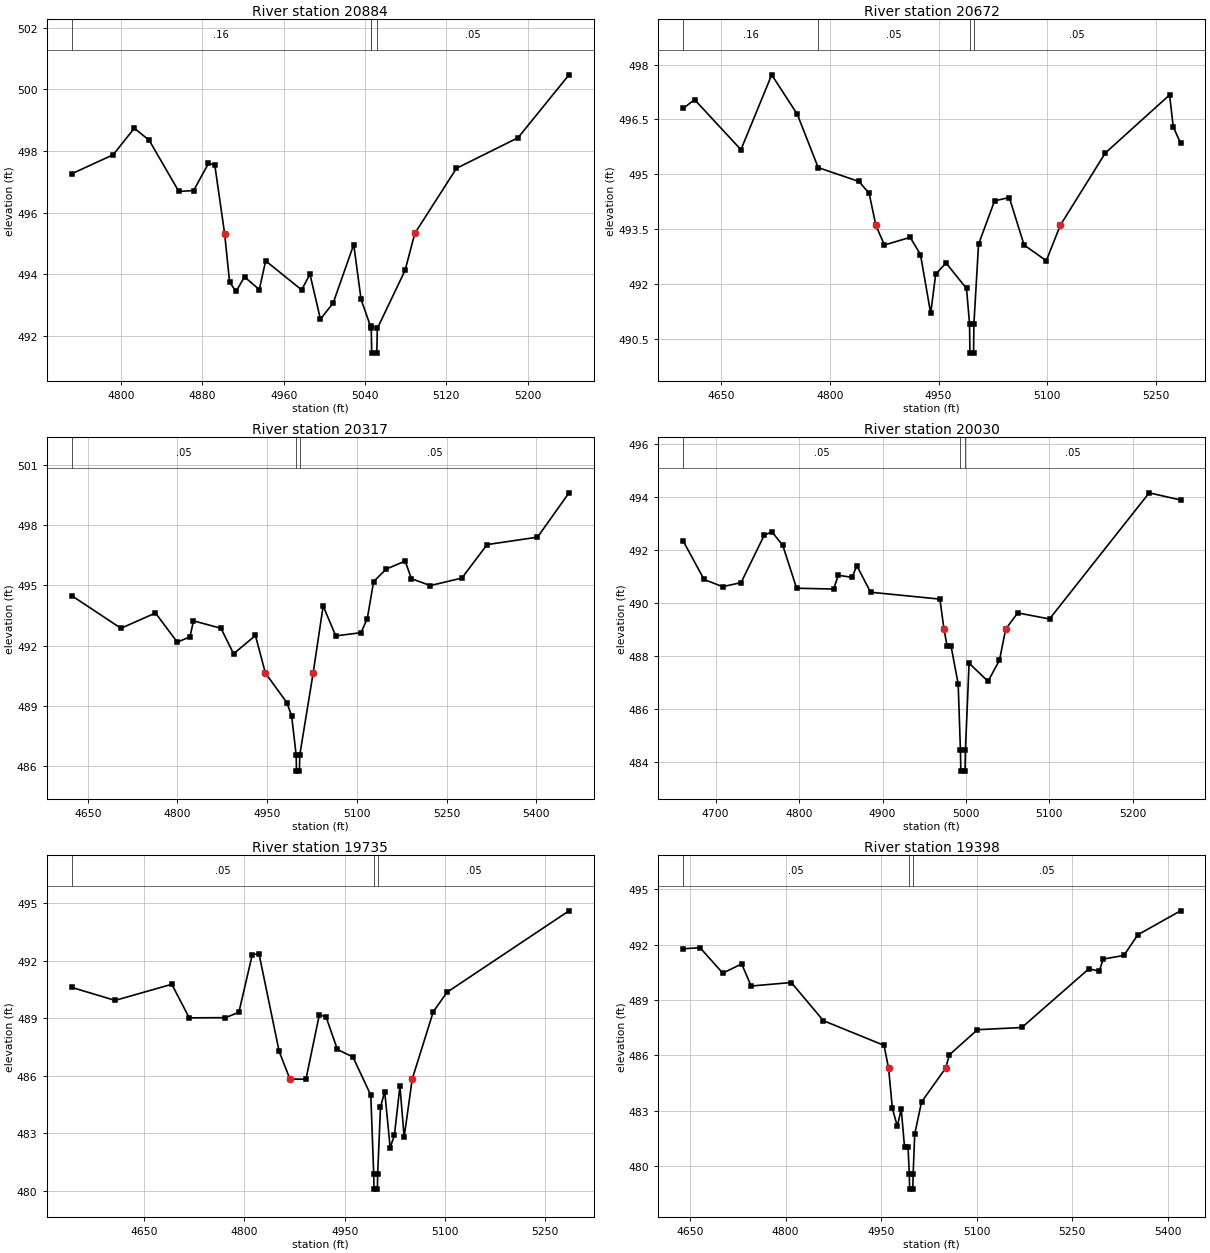
Type RM Length L Ch R = 1,20884,212,212,212
BEGIN DESCRIPTION:
GARRETT CREEK 33.0
END DESCRIPTION:
XS GIS Cut Line= 3
      2796833.22      7063454.18      2796633.83      7063305.62
      2796395.36      7063270.43
#Sta/Elev= 30
  4751.1  497.26  4792.1  497.88  4812.9  498.74  4827.5  498.35  4856.7  496.69
  4871.3  496.72  4885.9  497.60  4892.1  497.55  4901.8  495.32  4906.7  493.75
  4913.0  493.45  4921.4  493.92  4935.9  493.51  4942.2  494.44  4977.6  493.50
  4985.8  494.01  4996.1  492.55  5008.7  493.08  5028.9  494.97  5036.1  493.19
  5045.4  492.32  5046.1  492.25  5046.6  491.45  5051.6  491.45  5052.1  492.25
  5079.4  494.13  5089.0  495.33  5130.0  497.44  5190.6  498.43  5240.8  500.47
#Mann=4,-1,0
  4751.1    0.16       0  5045.4    0.05       0  5046.1    0.07       0
  5052.1    0.05       0
Bank Sta=4901.8,5089
Exp/Cntr=0.3,0.1

Type RM Length L Ch R = 1,20672,355,355,355
BEGIN DESCRIPTION:
Mapping XS be293ed2
END DESCRIPTION:
XS GIS Cut Line= 3
      2796998.87      7063423.78      2796716.62      7063129.89
      2796443.16      7063077.53
#Sta/Elev= 30
  4597.7  496.80  4613.6  497.04  4677.5  495.67  4719.9  497.72  4755.2  496.64
  4784.0  495.18  4840.1  494.80  4854.2  494.48  4863.5  493.60  4875.3  493.06
  4910.8  493.27  4925.0  492.80  4939.1  491.19  4946.0  492.26  4960.2  492.57
  4988.5  491.87  4992.7  490.90  4993.2  490.10  4998.2  490.10  4998.7  490.90
  5005.1  493.08  5027.2  494.27  5047.5  494.36  5067.9  493.06  5098.5  492.63
  5117.8  493.60  5179.9  495.58  5268.5  497.17  5273.5  496.30  5283.6  495.85
#Mann=4,-1,0
  4597.7    0.16       0  4784.0    0.05       0  4992.7    0.03       0
  4998.7    0.05       0
Bank Sta=4863.5,5117.8
Exp/Cntr=0.3,0.1

Type RM Length L Ch R = 1,20317,287,287,287
BEGIN DESCRIPTION:
GARRETT CREEK 32.0
END DESCRIPTION:
XS GIS Cut Line= 3
      2797165.61      7063227.45      2796975.00      7062925.00
      2796525.04      7062775.01
#Sta/Elev= 30
  4623.0  494.49  4705.6  492.86  4763.3  493.62  4799.8  492.17  4821.0  492.43
  4826.9  493.23  4872.8  492.86  4894.0  491.59  4930.5  492.50  4947.1  490.63
  4983.1  489.15  4991.0  488.49  4998.6  486.54  4999.1  485.74  5004.1  485.74
  5004.6  486.54  5027.0  490.63  5043.7  493.97  5064.8  492.48  5107.0  492.64
  5117.5  493.34  5128.1  495.19  5149.2  495.81  5180.8  496.21  5191.3  495.33
  5222.9  494.99  5275.6  495.36  5317.8  497.03  5402.1  497.40  5454.8  499.61
#Mann=3,-1,0
  4623.0    0.05       0  4998.6    0.03       0  5004.6    0.05       0
Bank Sta=4947.1,5027
Exp/Cntr=0.3,0.1

Type RM Length L Ch R = 1,20030,295,295,295
BEGIN DESCRIPTION:
Mapping XS 4a92680d
END DESCRIPTION:
XS GIS Cut Line= 3
      2797282.88      7063039.73      2797138.21      7062758.22
      2796891.90      7062625.29
#Sta/Elev= 30
  4660.9  492.36  4686.1  490.90  4708.3  490.63  4730.4  490.78  4758.2  492.57
  4767.4  492.70  4780.4  492.19  4797.0  490.57  4841.4  490.54  4847.0  491.06
  4863.5  490.98  4869.2  491.42  4885.7  490.42  4968.8  490.16  4973.7  489.03
  4977.4  488.40  4982.1  488.40  4990.7  486.96  4993.4  484.47  4993.9  483.67
  4998.9  483.67  4999.4  484.47  5003.8  487.74  5026.5  487.06  5040.2  487.85
  5047.7  489.03  5062.1  489.64  5100.2  489.41  5219.7  494.17  5257.3  493.90
#Mann=3,-1,0
  4660.9    0.05       0  4993.4    0.03       0  4999.4    0.05       0
Bank Sta=4973.7,5047.7
Exp/Cntr=0.3,0.1

Type RM Length L Ch R = 1,19735,337,337,337
BEGIN DESCRIPTION:
Mapping XS 03b2f6e2
END DESCRIPTION:
XS GIS Cut Line= 3
      2797325.89      7063004.52      2797286.79      7062570.54
      2797099.54      7062324.78
#Sta/Elev= 30
  4541.1  490.60  4606.3  489.92  4691.2  490.76  4717.3  489.01  4771.5  489.02
  4791.6  489.30  4811.7  492.31  4821.8  492.34  4851.9  487.26  4868.0  485.82
  4892.0  485.81  4912.1  489.18  4922.2  489.05  4939.1  487.36  4962.3  486.97
  4989.1  484.98  4993.4  480.88  4993.9  480.08  4998.9  480.08  4999.4  480.88
  5003.6  484.37  5009.9  485.16  5018.1  482.24  5024.4  482.89  5032.7  485.45
  5039.0  482.79  5051.1  485.82  5082.6  489.33  5103.4  490.35  5285.8  494.59
#Mann=3,-1,0
  4541.1    0.05       0  4993.4    0.03       0  4999.4    0.05       0
Bank Sta=4868,5051.1
Exp/Cntr=0.3,0.1

Type RM Length L Ch R = 1,19398,635,635,635
BEGIN DESCRIPTION:
Mapping XS d5206ff3
END DESCRIPTION:
XS GIS Cut Line= 3
      2797834.22      7062703.50      2797548.76      7062504.07
      2797153.81      7062328.11
#Sta/Elev= 30
  4639.2  491.78  4665.8  491.84  4701.5  490.46  4731.2  490.96  4746.0  489.76
  4809.0  489.95  4859.4  487.88  4954.5  486.54  4961.7  485.30  4967.6  483.12
  4975.4  482.15  4981.5  483.09  4986.7  481.03  4992.2  481.03  4994.2  479.54
  4994.7  478.74  4999.7  478.74  5000.2  479.54  5002.7  481.73  5013.4  483.47
  5051.1  485.30  5057.2  486.03  5101.1  487.39  5170.8  487.51  5276.2  490.70
  5292.4  490.56  5298.1  491.22  5330.9  491.42  5352.8  492.54  5419.8  493.84
#Mann=3,-1,0
  4639.2    0.05       0  4994.2    0.03       0  5000.2    0.05       0
Bank Sta=4961.7,5051.1
Exp/Cntr=0.3,0.1

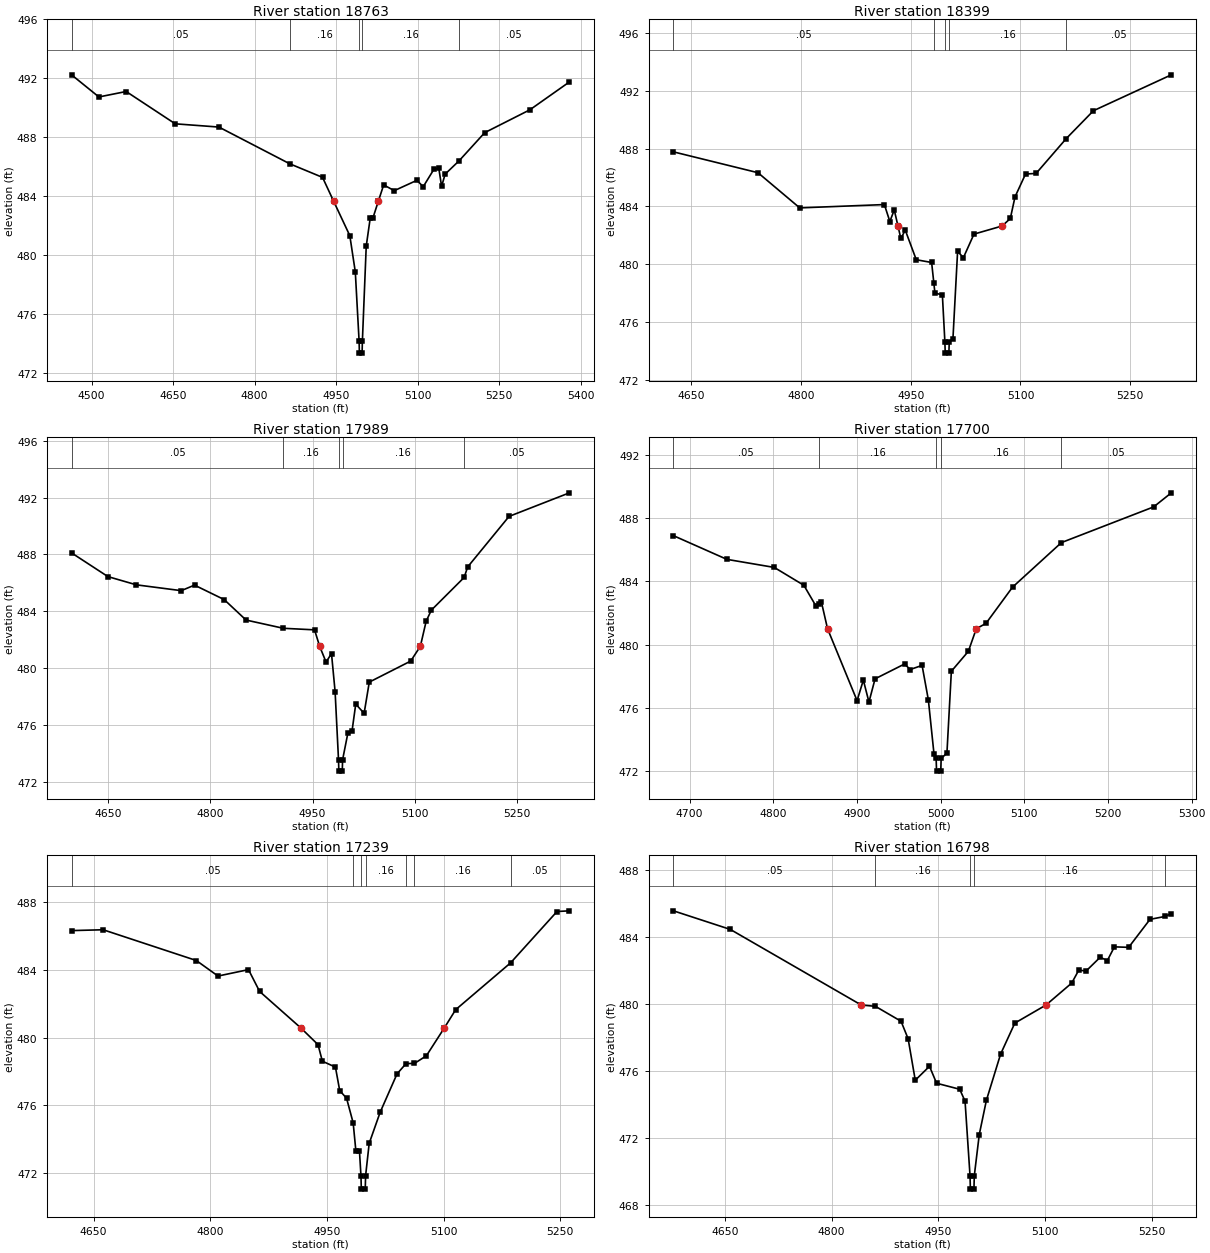
Type RM Length L Ch R = 1,18763,364,364,364
BEGIN DESCRIPTION:
GARRETT CREEK 28.0
END DESCRIPTION:
XS GIS Cut Line= 3
      2797875.00      7062675.04      2797825.00      7062125.00
      2797475.02      7062025.00
#Sta/Elev= 30
  4463.3  492.23  4513.6  490.73  4563.8  491.10  4654.1  488.91  4734.5  488.69
  4864.9  486.20  4925.2  485.28  4945.4  483.68  4975.4  481.33  4985.5  478.87
  4992.5  474.17  4993.0  473.37  4998.0  473.37  4998.5  474.17  5005.6  480.62
  5013.1  482.56  5018.2  482.56  5028.0  483.68  5037.7  484.77  5057.2  484.38
  5098.8  485.08  5110.5  484.65  5130.0  485.82  5139.1  485.91  5144.3  484.67
  5150.8  485.50  5176.4  486.40  5223.6  488.31  5306.8  489.86  5379.6  491.75
#Mann=5,-1,0
  4463.3    0.05       0  4864.9    0.16       0  4992.5    0.07       0
  4998.5    0.16       0  5176.4    0.05       0
Bank Sta=4945.4,5028
Exp/Cntr=0.3,0.1

Type RM Length L Ch R = 1,18399,410,410,410
BEGIN DESCRIPTION:
GARRETT CREEK 27.0
END DESCRIPTION:
XS GIS Cut Line= 3
      2798124.97      7062124.98      2797825.00      7061925.00
      2797624.99      7061674.98
#Sta/Elev= 30
  4625.5  487.77  4741.1  486.33  4798.2  483.90  4913.9  484.13  4921.4  482.96
  4927.4  483.76  4932.5  482.65  4936.4  481.79  4942.5  482.36  4957.5  480.32
  4978.5  480.13  4981.6  478.68  4983.0  478.02  4993.2  477.89  4996.6  474.67
  4997.1  473.87  5002.1  473.87  5002.6  474.67  5007.6  474.82  5014.0  480.89
  5022.0  480.47  5036.4  482.09  5074.9  482.65  5086.1  483.17  5092.5  484.66
  5106.9  486.24  5121.3  486.28  5162.6  488.69  5199.7  490.61  5306.2  493.09
#Mann=5,-1,0
  4625.5    0.05       0  4981.6    0.16       0  4996.6    0.07       0
  5002.6    0.16       0  5162.6    0.05       0
Bank Sta=4932.5,5074.9
Exp/Cntr=0.3,0.1

Type RM Length L Ch R = 1,17989,289,289,289
BEGIN DESCRIPTION:
GARRETT CREEK 26.0
END DESCRIPTION:
XS GIS Cut Line= 3
      2798174.99      7062074.97      2798025.00      7061675.00
      2797725.01      7061625.00
#Sta/Elev= 30
  4596.0  488.11  4649.4  486.44  4691.2  485.86  4757.1  485.45  4776.6  485.84
  4820.2  484.82  4852.3  483.38  4907.0  482.80  4952.9  482.69  4960.4  481.53
  4969.8  480.42  4977.8  481.02  4983.1  478.33  4988.1  473.54  4988.6  472.74
  4993.6  472.74  4994.1  473.54  5001.8  475.41  5008.0  475.58  5013.4  477.46
  5025.7  476.81  5033.3  479.01  5094.1  480.49  5108.3  481.53  5116.9  483.31
  5124.5  484.08  5172.6  486.38  5177.8  487.12  5238.6  490.68  5327.3  492.34
#Mann=5,-1,0
  4596.0    0.05       0  4907.0    0.16       0  4988.1    0.07       0
  4994.1    0.16       0  5172.6    0.05       0
Bank Sta=4960.4,5108.3
Exp/Cntr=0.3,0.1

Type RM Length L Ch R = 1,17700,461,461,461
BEGIN DESCRIPTION:
GARRETT CREEK 25.0
END DESCRIPTION:
XS GIS Cut Line= 3
      2798424.98      7061674.98      2798186.41      7061462.60
      2797925.00      7061375.00
#Sta/Elev= 30
  4680.6  486.89  4744.5  485.39  4801.1  484.88  4836.5  483.75  4850.7  482.46
  4854.2  482.59  4857.4  482.71  4864.8  481.00  4900.1  476.45  4907.6  477.75
  4914.3  476.36  4921.6  477.83  4956.9  478.77  4963.6  478.42  4977.8  478.68
  4985.3  476.50  4992.0  473.10  4994.6  472.79  4995.1  471.99  5000.1  471.99
  5000.6  472.79  5007.5  473.13  5012.8  478.31  5033.1  479.57  5042.6  481.00
  5054.2  481.34  5085.9  483.63  5144.3  486.45  5254.6  488.71  5275.7  489.60
#Mann=5,-1,0
  4680.6    0.05       0  4854.2    0.16       0  4994.6    0.07       0
  5000.6    0.16       0  5144.3    0.05       0
Bank Sta=4864.8,5042.6
Exp/Cntr=0.3,0.1

Type RM Length L Ch R = 1,17239,441,441,441
BEGIN DESCRIPTION:
Mapping XS 570577c5
END DESCRIPTION:
XS GIS Cut Line= 3
      2798502.79      7061581.31      2798338.57      7061252.88
      2798100.11      7061119.97
#Sta/Elev= 30
  4621.7  486.33  4662.3  486.38  4782.1  484.56  4810.0  483.64  4849.2  484.02
  4863.5  482.73  4916.5  480.57  4938.6  479.58  4944.2  478.60  4961.0  478.25
  4966.5  476.86  4975.3  476.41  4983.8  474.95  4987.3  473.28  4991.9  473.28
  4993.8  471.83  4994.3  471.03  4999.3  471.03  4999.8  471.83  5004.4  473.74
  5018.5  475.58  5040.2  477.85  5051.8  478.46  5062.6  478.47  5077.9  478.92
  5101.0  480.57  5115.6  481.65  5186.2  484.42  5245.9  487.46  5261.9  487.50
#Mann=7,-1,0
  4621.7    0.05       0  4983.8    0.16       0  4993.8    0.07       0
  4999.8    0.16       0  5051.8    0.05       0  5062.6    0.16       0
  5186.2    0.05       0
Bank Sta=4916.5,5101
Exp/Cntr=0.3,0.1

Type RM Length L Ch R = 1,16798,754,754,754
BEGIN DESCRIPTION:
GARRETT CREEK 24.0
END DESCRIPTION:
XS GIS Cut Line= 3
      2798525.00      7061474.96      2798525.00      7061075.00
      2798525.00      7060774.96
#Sta/Elev= 30
  4577.6  485.57  4657.6  484.46  4841.6  479.95  4861.6  479.87  4897.6  478.98
  4907.6  477.93  4917.6  475.46  4937.6  476.29  4947.6  475.28  4980.1  474.92
  4987.6  474.21  4994.6  469.76  4995.1  468.96  5000.1  468.96  5000.6  469.76
  5007.6  472.22  5017.6  474.26  5037.6  477.02  5057.6  478.87  5101.5  479.95
  5137.6  481.26  5147.6  482.04  5157.6  481.97  5177.6  482.80  5187.6  482.60
  5197.6  483.42  5217.6  483.39  5247.6  485.06  5269.4  485.24  5277.6  485.41
#Mann=5,-1,0
  4577.6    0.05       0  4861.6    0.16       0  4994.6    0.07       0
  5000.6    0.16       0  5269.4    0.05       0
Bank Sta=4841.6,5101.5
Exp/Cntr=0.3,0.1

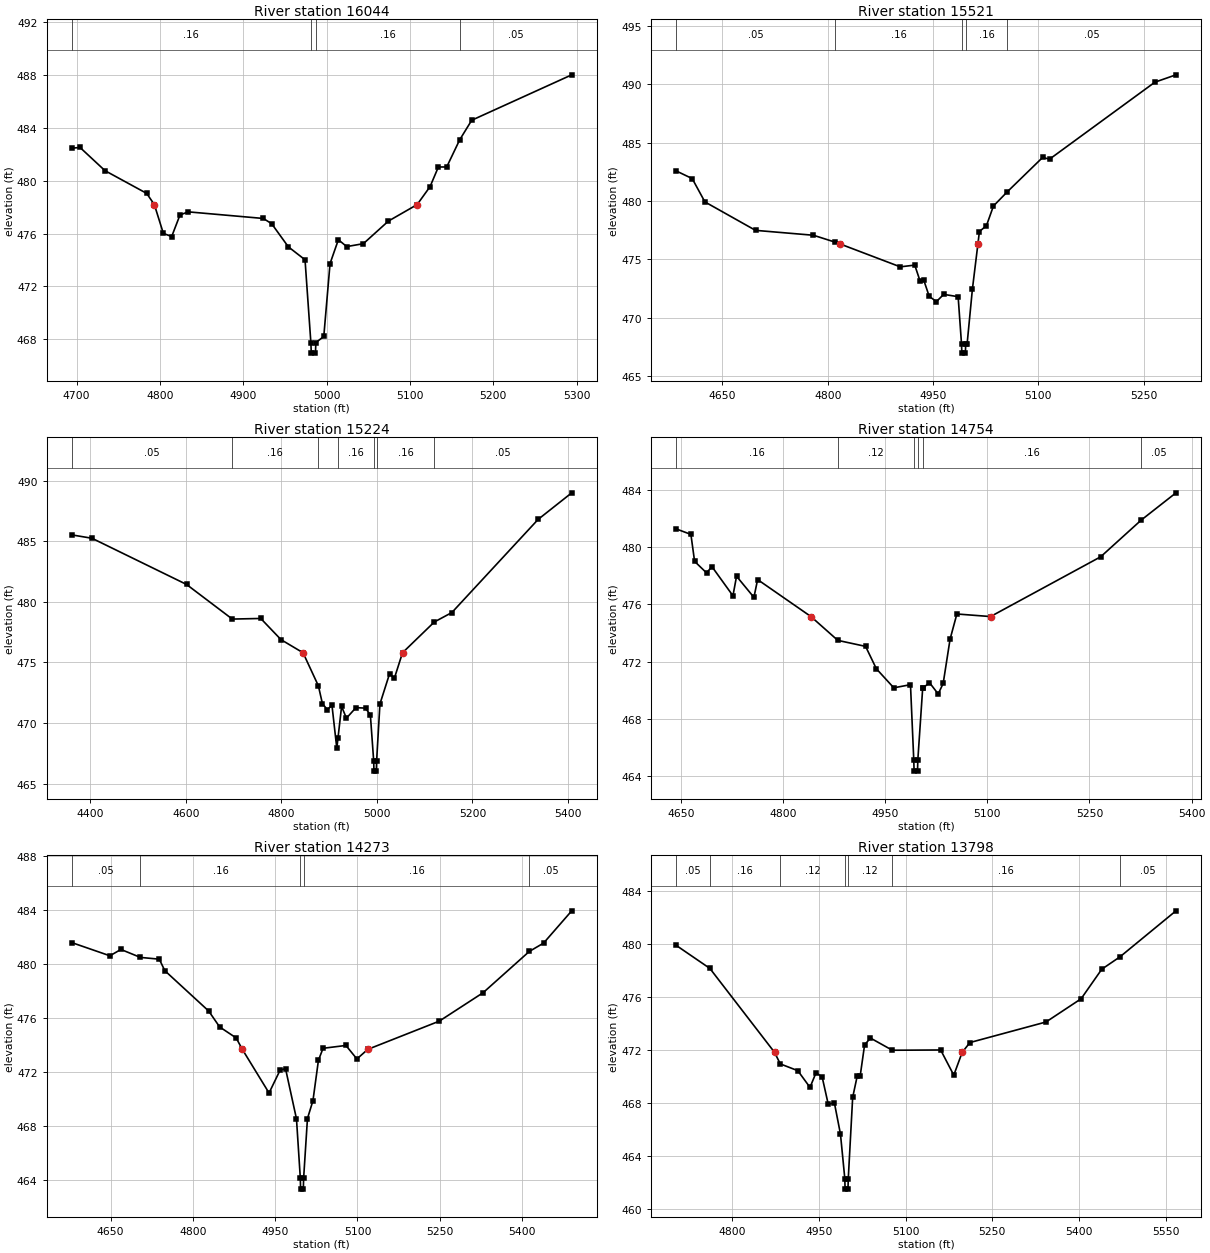
Type RM Length L Ch R = 1,16044,523,523,523
BEGIN DESCRIPTION:
GARRETT CREEK 23.0
END DESCRIPTION:
XS GIS Cut Line= 3
      2798875.00      7061275.05      2798875.00      7060975.00
      2798875.00      7060675.05
#Sta/Elev= 30
  4694.1  482.46  4704.1  482.52  4734.1  480.76  4784.1  479.04  4793.3  478.19
  4804.1  476.01  4814.1  475.77  4824.1  477.41  4834.1  477.64  4924.1  477.14
  4934.1  476.74  4954.1  474.99  4974.1  474.01  4981.1  467.74  4981.6  466.94
  4986.6  466.94  4987.1  467.74  4996.6  468.20  5004.1  473.72  5014.1  475.53
  5024.1  475.01  5044.1  475.23  5074.1  476.94  5108.6  478.19  5124.1  479.55
  5134.1  481.04  5144.1  481.04  5159.6  483.09  5174.1  484.58  5294.1  488.02
#Mann=4,-1,0
  4694.1    0.16       0  4981.1    0.07       0  4987.1    0.16       0
  5159.6    0.05       0
Bank Sta=4793.3,5108.6
Exp/Cntr=0.3,0.1

Type RM Length L Ch R = 1,15521,297,297,297
BEGIN DESCRIPTION:
GARRETT CREEK 22.0
END DESCRIPTION:
XS GIS Cut Line= 3
      2799024.99      7061275.04      2799125.00      7060875.00
      2799125.00      7060575.05
#Sta/Elev= 30
  4583.8  482.59  4607.0  481.92  4625.1  479.92  4697.2  477.48  4779.7  477.06
  4811.0  476.46  4816.9  476.33  4903.4  474.35  4924.0  474.50  4931.7  473.11
  4936.9  473.20  4944.6  471.82  4954.9  471.37  4965.2  471.99  4985.8  471.79
  4990.6  467.75  4991.1  466.95  4996.1  466.95  4996.6  467.75  4998.6  467.75
  5006.1  472.43  5014.0  476.33  5016.1  477.38  5026.1  477.88  5036.1  479.57
  5055.7  480.78  5106.1  483.73  5116.1  483.59  5266.1  490.19  5296.1  490.82
#Mann=5,-1,0
  4583.8    0.05       0  4811.0    0.16       0  4990.6    0.07       0
  4996.6    0.16       0  5055.7    0.05       0
Bank Sta=4816.9,5014
Exp/Cntr=0.3,0.1

Type RM Length L Ch R = 1,15224,470,470,470
BEGIN DESCRIPTION:
GARRETT CREEK 21.0
END DESCRIPTION:
XS GIS Cut Line= 3
      2798924.97      7061525.03      2799275.00      7061175.00
      2799325.00      7060624.99
#Sta/Elev= 30
  4360.7  485.53  4403.2  485.25  4601.2  481.44  4697.1  478.58  4756.7  478.63
  4799.2  476.88  4845.3  475.80  4877.4  473.07  4885.8  471.61  4895.9  471.11
  4905.9  471.45  4916.0  467.91  4918.4  468.74  4926.0  471.37  4936.1  470.40
  4956.1  471.27  4976.2  471.23  4986.3  470.66  4993.3  466.83  4993.8  466.03
  4998.8  466.03  4999.3  466.83  5006.3  471.57  5026.4  474.06  5036.5  473.69
  5053.6  475.80  5120.2  478.34  5157.0  479.12  5337.7  486.81  5408.0  489.00
#Mann=7,-1,0
  4360.7    0.05       0  4697.1    0.16       0  4877.4    0.12       0
  4918.4    0.16       0  4993.3    0.07       0  4999.3    0.16       0
  5120.2    0.05       0
Bank Sta=4845.3,5053.6
Exp/Cntr=0.3,0.1

Type RM Length L Ch R = 1,14754,481,481,481
BEGIN DESCRIPTION:
GARRETT CREEK 20.0
END DESCRIPTION:
XS GIS Cut Line= 3
      2799421.36      7061537.27      2799535.91      7061215.45
      2799575.00      7060825.00
#Sta/Elev= 30
  4643.0  481.26  4665.0  480.87  4670.4  478.99  4687.9  478.19  4695.9  478.62
  4726.7  476.59  4732.0  477.95  4757.5  476.48  4762.9  477.72  4841.2  475.14
  4880.6  473.48  4921.4  473.06  4937.2  471.50  4962.8  470.17  4987.3  470.39
  4992.1  465.16  4992.6  464.36  4997.6  464.36  4998.1  465.16  5005.2  470.14
  5006.2  470.18  5015.2  470.53  5028.0  469.74  5035.3  470.48  5045.4  473.56
  5055.4  475.32  5104.8  475.14  5266.5  479.31  5326.0  481.87  5377.0  483.77
#Mann=6,-1,0
  4643.0    0.16       0  4880.6    0.12       0  4992.1    0.07       0
  4998.1    0.12       0  5006.2    0.16       0  5326.0    0.05       0
Bank Sta=4841.2,5104.8
Exp/Cntr=0.3,0.1

Type RM Length L Ch R = 1,14273,475,475,475
BEGIN DESCRIPTION:
GARRETT CREEK 19.0
END DESCRIPTION:
XS GIS Cut Line= 3
      2799726.61      7061694.67      2799734.43      7061233.33
      2799718.79      7060783.70
#Sta/Elev= 30
  4579.2  481.59  4648.9  480.61  4668.9  481.08  4704.5  480.49  4738.9  480.36
  4748.9  479.51  4828.9  476.52  4848.9  475.34  4878.9  474.53  4890.2  473.68
  4938.9  470.45  4958.9  472.13  4968.9  472.26  4988.9  468.53  4995.9  464.13
  4996.4  463.33  5001.4  463.33  5001.9  464.13  5008.9  468.56  5018.9  469.88
  5028.9  472.87  5037.3  473.76  5079.0  473.97  5099.0  472.97  5118.8  473.68
  5249.1  475.77  5329.1  477.88  5413.1  480.93  5439.2  481.55  5490.5  483.94
#Mann=5,-1,0
  4579.2    0.05       0  4704.5    0.16       0  4995.9    0.07       0
  5001.9    0.16       0  5413.1    0.05       0
Bank Sta=4890.2,5118.8
Exp/Cntr=0.3,0.1

Type RM Length L Ch R = 1,13798,331,331,331
BEGIN DESCRIPTION:
GARRETT CREEK 18.0
END DESCRIPTION:
XS GIS Cut Line= 3
      2799925.01      7061574.98      2800025.00      7061275.00
      2800109.79      7060732.89
#Sta/Elev= 30
  4702.9  479.92  4761.6  478.17  4873.5  471.84  4883.4  470.97  4913.7  470.46
  4934.8  469.20  4945.3  470.31  4955.9  469.97  4966.4  467.92  4976.9  468.05
  4987.5  465.68  4995.0  462.33  4995.5  461.53  5000.5  461.53  5001.0  462.33
  5008.6  468.44  5016.5  470.06  5021.6  470.06  5029.2  472.40  5039.3  472.92
  5077.2  472.00  5160.8  472.02  5183.5  470.12  5198.0  471.84  5211.4  472.58
  5343.0  474.13  5403.7  475.88  5439.5  478.11  5470.9  479.04  5567.8  482.51
#Mann=7,-1,0
  4702.9    0.05       0  4761.6    0.16       0  4883.4    0.12       0
  4995.0    0.07       0  5001.0    0.12       0  5077.2    0.16       0
  5470.9    0.05       0
Bank Sta=4873.5,5198
Exp/Cntr=0.3,0.1

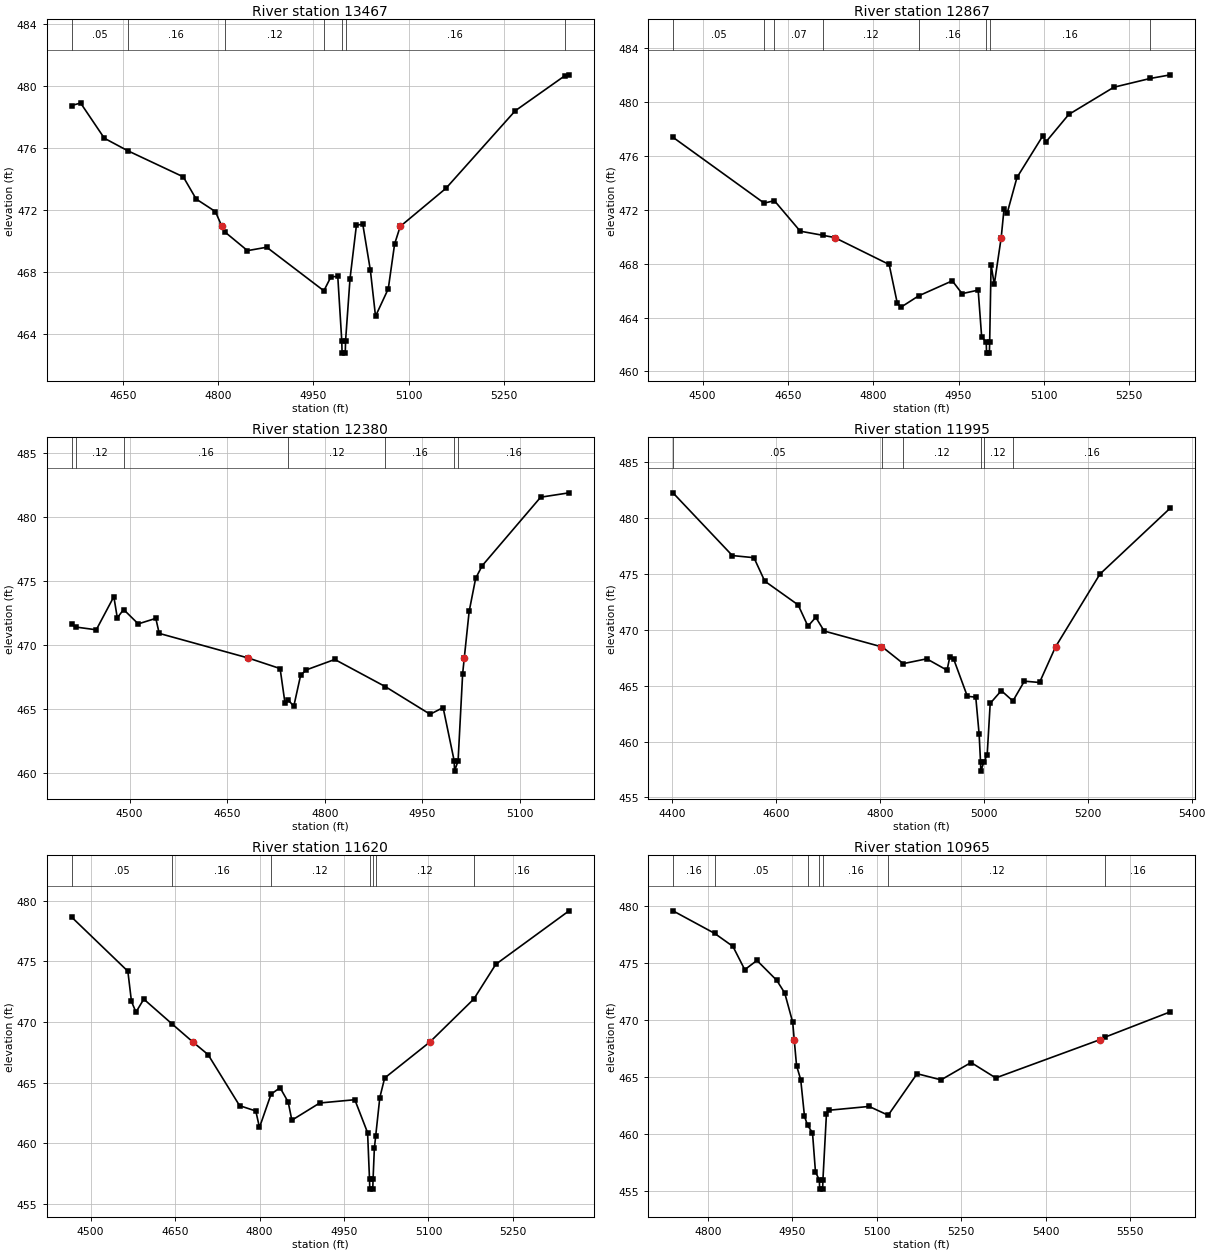
Type RM Length L Ch R = 1,13467,600,600,600
BEGIN DESCRIPTION:
GARRETT CREEK 17.0
END DESCRIPTION:
XS GIS Cut Line= 3
      2800191.90      7061589.11      2800254.46      7061178.59
      2800223.18      7060811.08
#Sta/Elev= 30
  4568.9  478.76  4583.2  478.92  4620.6  476.65  4657.2  475.85  4745.0  474.16
  4765.3  472.73  4795.6  471.92  4805.9  470.96  4811.0  470.59  4846.2  469.40
  4876.5  469.62  4966.6  466.81  4977.7  467.71  4988.5  467.74  4994.8  463.59
  4995.3  462.79  5000.3  462.79  5000.8  463.59  5007.8  467.59  5017.9  471.04
  5027.9  471.11  5039.9  468.13  5048.0  465.17  5068.1  466.94  5078.1  469.83
  5086.9  470.96  5159.0  473.42  5268.2  478.42  5346.7  480.69  5353.0  480.74
#Mann=7,-1,0
  4568.9    0.05       0  4657.2    0.16       0  4811.0    0.12       0
  4966.6    0.16       0  4994.8    0.07       0  5000.8    0.16       0
  5346.7    0.05       0
Bank Sta=4805.9,5086.9
Exp/Cntr=0.3,0.1

Type RM Length L Ch R = 1,12867,487,487,487
BEGIN DESCRIPTION:
GARRETT CREEK 16.0
END DESCRIPTION:
XS GIS Cut Line= 3
      2800387.38      7061589.19      2800512.52      7061170.77
      2800324.99      7060774.98
#Sta/Elev= 30
  4447.8  477.36  4608.1  472.48  4626.1  472.66  4671.5  470.40  4711.9  470.09
  4731.9  469.93  4827.9  467.93  4842.2  465.06  4848.8  464.77  4879.5  465.60
  4938.9  466.72  4956.1  465.77  4984.4  466.03  4990.5  462.58  4998.6  462.16
  4999.1  461.36  5004.1  461.36  5004.6  462.16  5007.1  467.92  5012.7  466.45
  5024.9  469.93  5029.9  472.06  5035.4  471.74  5052.6  474.38  5098.1  477.47
  5103.6  477.02  5143.6  479.05  5222.9  481.07  5286.8  481.72  5322.5  481.99
#Mann=8,-1,0
  4447.8    0.05       0  4608.1    0.16       0  4626.1    0.07       0
  4711.9    0.12       0  4879.5    0.16       0  4998.6    0.07       0
  5004.6    0.16       0  5286.8    0.05       0
Bank Sta=4731.9,5024.9
Exp/Cntr=0.3,0.1

Type RM Length L Ch R = 1,12380,385,385,385
BEGIN DESCRIPTION:
Mapping XS cea6afc7
END DESCRIPTION:
XS GIS Cut Line= 3
      2800629.81      7061620.45      2800794.04      7061104.30
      2800794.04      7060881.45
#Sta/Elev= 30
  4410.9  471.61  4418.1  471.40  4448.9  471.19  4475.9  473.77  4481.2  472.12
  4490.9  472.77  4513.4  471.65  4540.4  472.08  4545.6  470.91  4682.6  468.99
  4731.4  468.17  4739.0  465.45  4743.7  465.74  4752.4  465.23  4762.9  467.64
  4771.3  468.06  4815.4  468.88  4893.2  466.76  4961.9  464.61  4981.9  465.13
  4998.9  460.98  4999.4  460.18  5004.9  460.98  5011.9  467.76  5014.4  468.99
  5021.9  472.62  5031.9  475.20  5041.9  476.18  5131.8  481.52  5175.4  481.86
#Mann=7,-1,0
  4410.9    0.05       0  4418.1    0.12       0  4490.9    0.16       0
  4743.7    0.12       0  4893.2    0.16       0  4998.9    0.07       0
  5004.9    0.16       0
Bank Sta=4682.6,5014.4
Exp/Cntr=0.3,0.1

Type RM Length L Ch R = 1,11995,375,375,375
BEGIN DESCRIPTION:
GARRETT CREEK 15.0
END DESCRIPTION:
XS GIS Cut Line= 3
      2801224.99      7061774.97      2801067.73      7061221.60
      2800869.16      7060894.54
#Sta/Elev= 30
  4401.3  482.28  4515.6  476.66  4557.2  476.47  4578.0  474.37  4642.3  472.24
  4661.2  470.33  4676.2  471.13  4692.4  469.90  4802.7  468.49  4804.7  468.46
  4844.7  466.98  4889.9  467.41  4929.0  466.39  4934.2  467.55  4941.9  467.37
  4968.1  464.05  4984.3  463.98  4990.8  460.65  4993.5  458.15  4994.0  457.35
  4999.8  458.15  5006.3  458.82  5012.1  463.42  5033.5  464.56  5055.8  463.63
  5077.9  465.41  5107.1  465.29  5137.9  468.48  5223.4  475.00  5359.2  480.93
#Mann=6,-1,0
  4401.3    0.05       0  4804.7    0.16       0  4844.7    0.12       0
  4993.5    0.07       0  4999.8    0.12       0  5055.8    0.16       0
Bank Sta=4802.7,5137.9
Exp/Cntr=0.3,0.1

Type RM Length L Ch R = 1,11620,655,655,655
BEGIN DESCRIPTION:
GARRETT CREEK 14.0
END DESCRIPTION:
XS GIS Cut Line= 3
      2801675.00      7061275.00      2801321.88      7060990.91
      2800924.97      7060824.99
#Sta/Elev= 30
  4466.2  478.65  4566.2  474.18  4572.6  471.69  4580.6  470.81  4594.5  471.88
  4644.6  469.84  4681.6  468.35  4708.6  467.31  4764.6  463.10  4793.4  462.66
  4799.9  461.30  4820.5  464.05  4836.5  464.58  4850.9  463.40  4857.4  461.90
  4906.9  463.32  4969.2  463.59  4991.9  460.87  4995.3  457.02  4995.8  456.22
  5001.1  456.22  5001.6  457.02  5003.9  459.57  5006.2  460.57  5013.6  463.77
  5022.2  465.38  5102.6  468.35  5180.7  471.90  5219.5  474.75  5349.6  479.16
#Mann=7,-1,0
  4466.2    0.05       0  4644.6    0.16       0  4820.5    0.12       0
  4995.3    0.07       0  5001.6    0.12       0  5006.2    0.12       0
  5180.7    0.16       0
Bank Sta=4681.6,5102.6
Exp/Cntr=0.3,0.1

Type RM Length L Ch R = 1,10965,820,820,820
BEGIN DESCRIPTION:
Mapping XS 89a59e21
END DESCRIPTION:
XS GIS Cut Line= 3
      2801884.90      7061065.18      2801712.88      7060877.53
      2801122.49      7060662.48
#Sta/Elev= 30
  4738.3  479.54  4812.3  477.56  4844.7  476.42  4865.7  474.38  4887.3  475.19
  4922.4  473.45  4936.6  472.34  4950.8  469.76  4953.5  468.23  4957.6  465.97
  4965.0  464.74  4971.7  461.52  4977.3  460.72  4985.9  460.09  4991.2  456.64
  4998.1  455.94  4998.6  455.14  5003.9  455.14  5004.4  455.94  5010.7  461.77
  5016.0  462.06  5086.4  462.39  5120.2  461.62  5171.5  465.26  5214.1  464.72
  5267.3  466.24  5311.1  464.89  5495.3  468.23  5504.8  468.46  5621.2  470.69
#Mann=7,-1,0
  4738.3    0.16       0  4812.3    0.05       0  4977.3    0.16       0
  4998.1    0.07       0  5004.4    0.16       0  5120.2    0.12       0
  5504.8    0.16       0
Bank Sta=4953.5,5495.3
Exp/Cntr=0.3,0.1

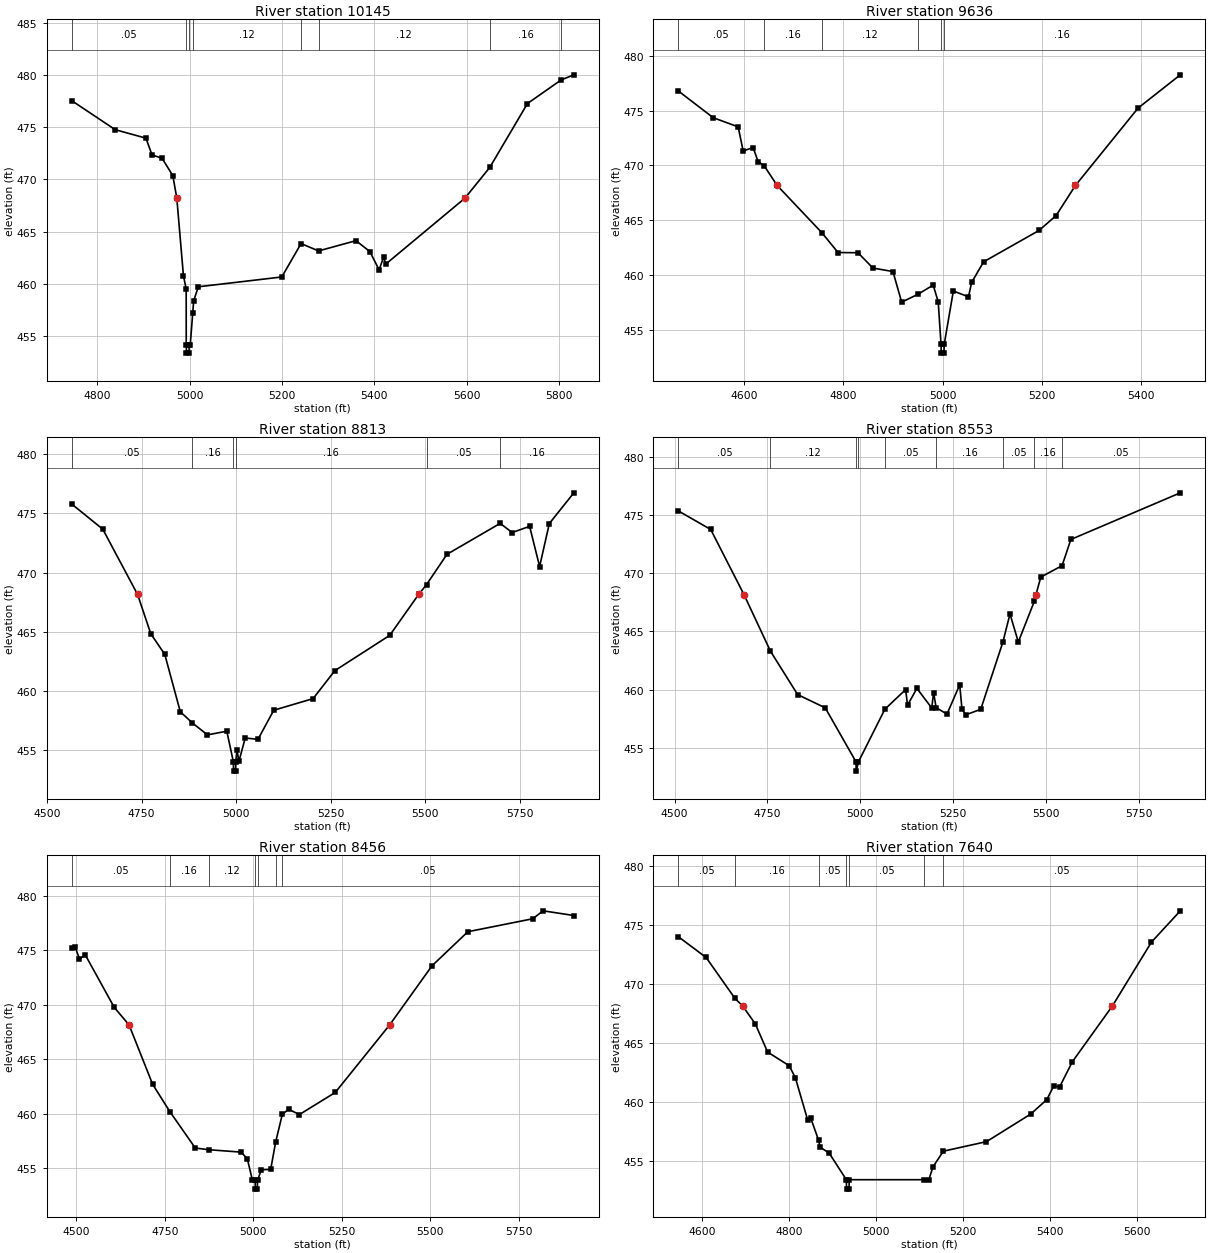
Type RM Length L Ch R = 1,10145,509,509,509
BEGIN DESCRIPTION:
GARRETT CREEK 13.0
END DESCRIPTION:
XS GIS Cut Line= 3
      2802072.60      7060627.29      2801854.70      7060496.52
      2801025.00      7060425.00
#Sta/Elev= 30
  4744.8  477.54  4838.9  474.76  4905.3  473.95  4918.6  472.34  4940.3  472.02
  4963.6  470.35  4972.2  468.19  4986.6  460.73  4992.5  459.49  4992.6  454.14
  4993.1  453.34  4998.5  453.34  4999.0  454.14  5001.3  454.14  5006.6  457.16
  5008.7  458.35  5018.7  459.70  5199.4  460.64  5241.2  463.84  5279.1  463.14
  5360.0  464.12  5390.1  463.08  5410.1  461.32  5419.7  462.53  5424.7  461.88
  5595.8  468.19  5649.8  471.15  5731.3  477.27  5804.2  479.53  5831.7  480.02
#Mann=8,-1,0
  4744.8    0.05       0  4992.6    0.04       0  4999.0    0.05       0
  5006.6    0.12       0  5241.2    0.16       0  5279.1    0.12       0
  5649.8    0.16       0  5804.2    0.12       0
Bank Sta=4972.2,5595.8
Exp/Cntr=0.3,0.1

Type RM Length L Ch R = 1,9636,823,823,823
BEGIN DESCRIPTION:
GARRETT CREEK 12.0
END DESCRIPTION:
XS GIS Cut Line= 3
      2802125.02      7060225.00      2801675.00      7060175.00
      2801125.01      7060075.00
#Sta/Elev= 30
  4467.4  476.82  4537.9  474.37  4588.2  473.53  4598.2  471.33  4618.3  471.64
  4628.4  470.35  4640.5  469.98  4666.8  468.17  4757.1  463.84  4789.4  462.04
  4829.6  462.02  4859.8  460.62  4900.1  460.30  4917.7  457.50  4949.9  458.21
  4981.2  459.06  4991.3  457.54  4997.0  453.64  4997.5  452.84  5002.9  452.84
  5003.4  453.64  5021.8  458.52  5052.3  457.99  5058.7  459.31  5082.8  461.19
  5194.6  464.06  5228.9  465.42  5267.8  468.17  5394.1  475.25  5479.2  478.29
#Mann=6,-1,0
  4467.4    0.05       0  4640.5    0.16       0  4757.1    0.12       0
  4949.9    0.16       0  4997.0    0.07       0  5003.4    0.16       0
Bank Sta=4666.8,5267.8
Exp/Cntr=0.3,0.1

Type RM Length L Ch R = 1,8813,260,260,260
BEGIN DESCRIPTION:
GARRETT CREEK 11.0
END DESCRIPTION:
XS GIS Cut Line= 3
      2802275.04      7059825.01      2801825.00      7059725.00
      2800992.72      7059964.96
#Sta/Elev= 30
  4565.3  475.79  4647.3  473.67  4739.3  468.16  4774.1  464.85  4811.2  463.10
  4852.2  458.26  4884.4  457.31  4923.9  456.31  4975.1  456.62  4992.4  454.05
  4992.9  453.25  4998.3  453.25  4998.8  454.05  5002.0  455.03  5007.1  454.07
  5023.8  456.05  5057.5  455.93  5099.2  458.39  5203.2  459.37  5260.7  461.73
  5405.8  464.71  5482.2  468.16  5503.2  469.00  5557.1  471.55  5697.7  474.16
  5729.5  473.39  5775.6  473.91  5802.0  470.52  5827.7  474.15  5892.5  476.74
#Mann=6,-1,0
  4565.3    0.05       0  4884.4    0.16       0  4992.4    0.07       0
  4998.8    0.16       0  5503.2    0.05       0  5697.7    0.16       0
Bank Sta=4739.3,5482.2
Exp/Cntr=0.3,0.1

Type RM Length L Ch R = 1,8553,97,97,97
BEGIN DESCRIPTION:
Mapping XS 8ca40a49
END DESCRIPTION:
XS GIS Cut Line= 3
      2802371.61      7059734.89      2801993.16      7059526.57
      2801083.47      7059394.63
#Sta/Elev= 30
  4510.0  475.36  4597.4  473.76  4687.0  468.16  4758.0  463.31  4831.3  459.57
  4905.6  458.43  4988.4  453.79  4988.9  452.99  4995.0  453.79  5066.1  458.31
  5122.0  460.00  5127.1  458.66  5152.3  460.10  5192.2  458.42  5197.3  459.73
  5204.0  458.45  5233.2  457.89  5267.5  460.41  5273.6  458.32  5283.7  457.83
  5324.1  458.30  5383.6  464.07  5402.8  466.50  5425.2  464.09  5468.1  467.57
  5472.7  468.16  5485.8  469.67  5543.0  470.65  5566.6  472.90  5861.2  476.91
#Mann=9,-1,0
  4510.0    0.05       0  4758.0    0.12       0  4988.4    0.07       0
  4995.0    0.12       0  5066.1    0.05       0  5204.0    0.16       0
  5383.6    0.05       0  5468.1    0.16       0  5543.0    0.05       0
Bank Sta=4687,5472.7
Exp/Cntr=0.3,0.1

Type RM Length L Ch R = 1,8456,816,816,816
BEGIN DESCRIPTION:
GARRETT CREEK 10.0
END DESCRIPTION:
XS GIS Cut Line= 3
      2802425.04      7059625.02      2801951.39      7059423.02
      2801059.34      7059281.04
#Sta/Elev= 30
  4487.3  475.27  4496.4  475.34  4509.1  474.23  4525.5  474.59  4607.2  469.77
  4649.1  468.16  4715.6  462.71  4764.2  460.20  4836.1  456.85  4874.1  456.69
  4965.7  456.47  4983.2  455.85  4997.5  453.90  5005.4  453.87  5005.9  453.07
  5011.5  453.07  5012.0  453.87  5022.7  454.85  5049.2  454.88  5063.1  457.38
  5082.0  459.94  5099.8  460.41  5130.2  459.92  5231.5  461.95  5385.3  468.16
  5504.9  473.59  5606.1  476.72  5789.2  477.91  5818.8  478.64  5905.5  478.21
#Mann=7,-1,0
  4487.3    0.05       0  4764.2    0.16       0  4874.1    0.12       0
  5005.4    0.07       0  5012.0    0.12       0  5063.1    0.16       0
  5082.0    0.05       0
Bank Sta=4649.1,5385.3
Exp/Cntr=0.3,0.1

Type RM Length L Ch R = 1,7640,528,528,528
BEGIN DESCRIPTION:
GARRETT CREEK 9.0
END DESCRIPTION:
XS GIS Cut Line= 3
      2802625.02      7059125.01      2802275.00      7058825.00
      2801675.02      7058475.01
#Sta/Elev= 30
  4544.5  474.04  4608.7  472.27  4675.2  468.79  4692.6  468.16  4721.8  466.64
  4750.3  464.24  4799.7  463.09  4814.0  462.07  4842.5  458.47  4849.1  458.68
  4867.7  456.74  4871.0  456.17  4891.9  455.67  4931.4  453.41  4931.9  452.61
  4937.6  452.61  4938.1  453.41  5109.9  453.41  5121.3  453.41  5130.8  454.50
  5154.7  455.83  5254.0  456.64  5355.7  458.98  5392.9  460.21  5408.6  461.36
  5422.3  461.28  5451.6  463.42  5543.9  468.16  5633.6  473.57  5700.1  476.23
#Mann=7,-1,0
  4544.5    0.05       0  4675.2    0.16       0  4867.7    0.05       0
  4931.4   0.033       0  4938.1    0.05       0  5109.9    0.16       0
  5154.7    0.05       0
Bank Sta=4692.6,5543.9
Exp/Cntr=0.3,0.1