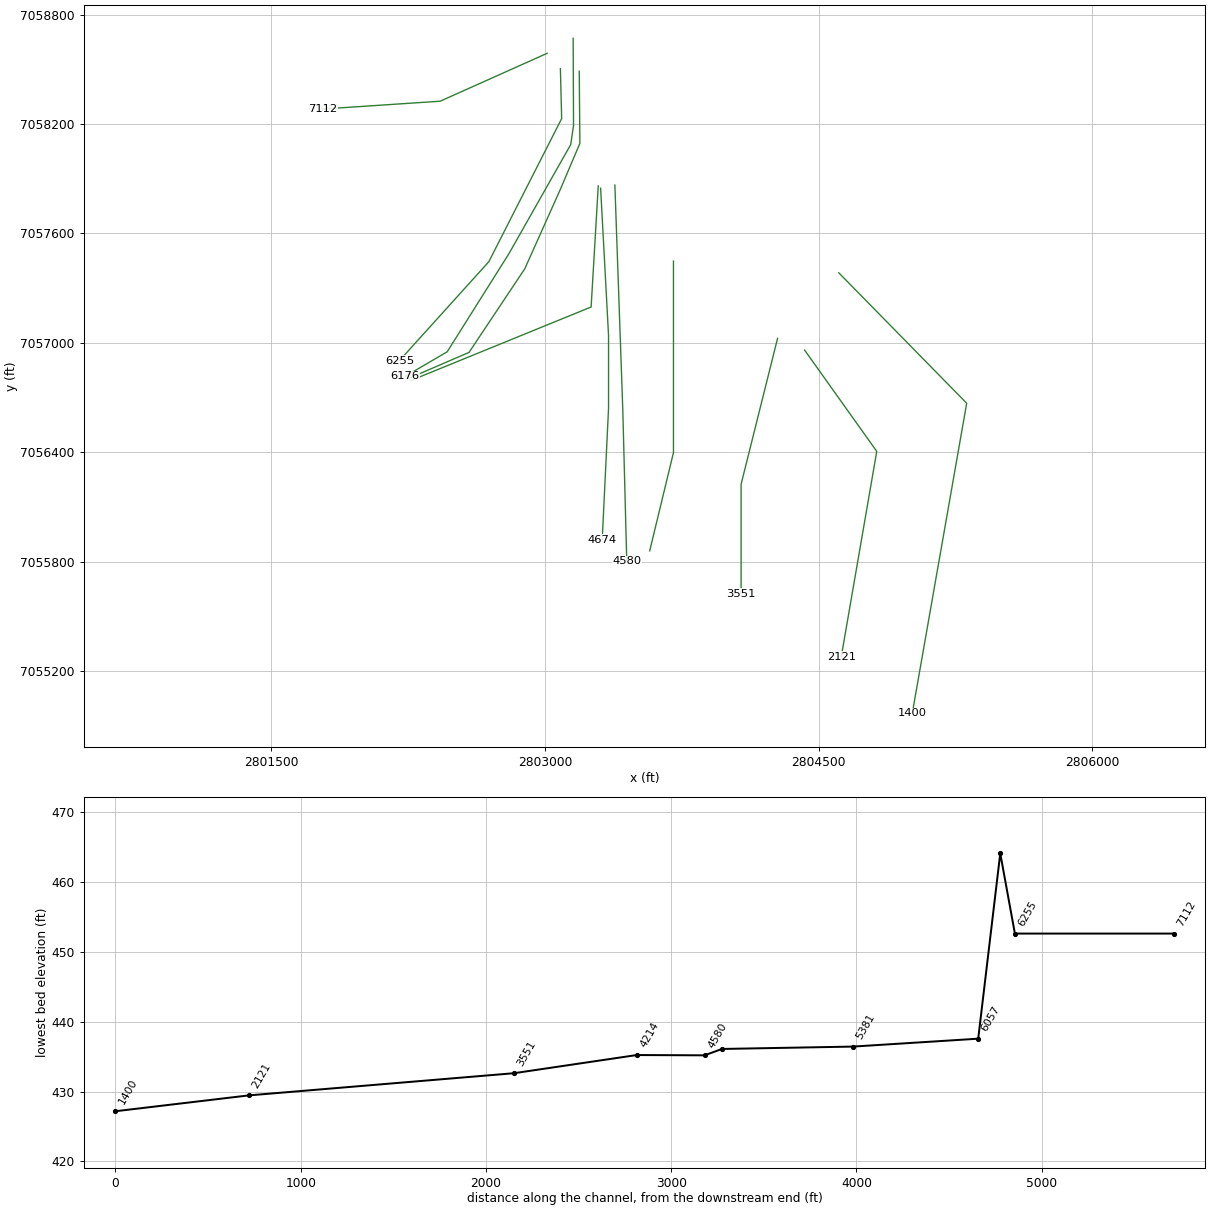
HEC-RAS study GARRETT CREEK.prj: GARRETT CREEK Base Level Engineering

--- GARRETT CREEK.g01 (geometry) --- (continued)

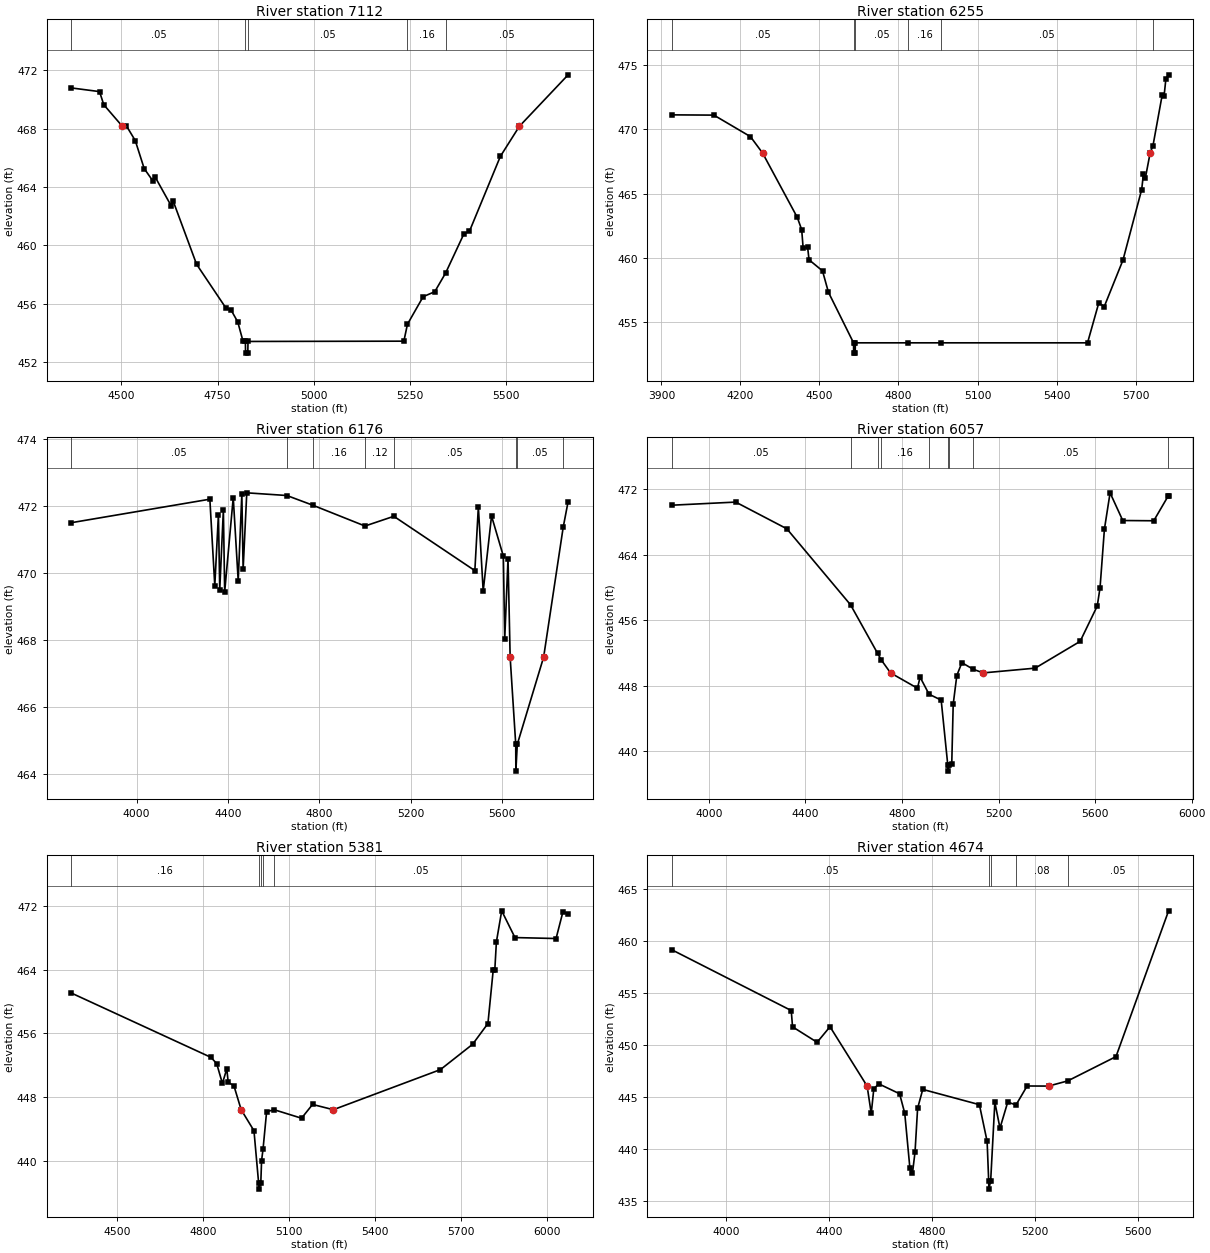
Type RM Length L Ch R = 1,7112,857,857,857
BEGIN DESCRIPTION:
GARRETT CREEK 8.0
END DESCRIPTION:
XS GIS Cut Line= 3
      2803011.44      7058587.52      2802425.00      7058325.00
      2801779.45      7058282.02
#Sta/Elev= 30
  4370.7  470.79  4443.5  470.54  4454.5  469.64  4502.8  468.16  4513.1  468.20
  4536.3  467.18  4559.5  465.26  4582.7  464.39  4588.2  464.67  4629.1  462.73
  4634.5  463.05  4695.5  458.70  4772.2  455.68  4784.7  455.58  4802.4  454.75
  4816.0  453.43  4822.2  453.41  4822.7  452.61  4828.5  452.61  4829.0  453.41
  5233.7  453.43  5243.0  454.59  5283.8  456.48  5313.9  456.82  5342.1  458.10
  5389.3  460.77  5404.1  460.97  5484.3  466.10  5533.6  468.16  5660.2  471.69
#Mann=5,-1,0
  4370.7    0.05       0  4822.2   0.033       0  4829.0    0.05       0
  5243.0    0.16       0  5342.1    0.05       0
Bank Sta=4502.8,5533.6
Exp/Cntr=0.3,0.1

Type RM Length L Ch R = 1,6255,79,79,79
BEGIN DESCRIPTION:
Mapping XS bc02141b
END DESCRIPTION:
XS GIS Cut Line= 4
      2803084.28      7058504.04      2803091.22      7058229.78
      2802691.92      7057445.06      2802202.31      7056903.36
#Sta/Elev= 30
  3940.2  471.12  4099.3  471.10  4238.0  469.43  4284.0  468.16  4416.0  463.15
  4432.6  462.20  4438.2  460.75  4454.9  460.87  4460.5  459.86  4511.6  459.00
  4534.1  457.34  4629.4  453.41  4629.9  452.61  4635.7  452.61  4636.2  453.41
  4837.9  453.41  4960.2  453.41  5517.6  453.41  5560.2  456.51  5581.1  456.23
  5652.1  459.84  5723.1  465.32  5729.8  466.53  5737.3  466.24  5755.2  468.16
  5766.0  468.73  5800.8  472.65  5808.2  472.60  5815.0  473.92  5825.2  474.23
#Mann=6,-1,0
  3940.2    0.05       0  4629.4   0.033       0  4636.2    0.05       0
  4837.9    0.16       0  4960.2    0.05       0  5766.0    0.16       0
Bank Sta=4284,5755.2
Exp/Cntr=0.3,0.1

Type RM Length L Ch R = 1,6176,119,119,119
BEGIN DESCRIPTION:
GARRETT CREEK 6.0
END DESCRIPTION:
XS GIS Cut Line= 6
      2803154.23      7058669.77      2803156.40      7058192.37
      2803140.85      7058087.18      2802802.27      7057489.45
      2802463.73      7056951.25      2802233.68      7056816.70
#Sta/Elev= 30
  3715.0  471.49  4320.7  472.19  4342.3  469.61  4358.2  471.73  4364.0  469.49
  4379.9  471.87  4385.6  469.43  4423.1  472.24  4444.8  469.76  4460.7  472.34
  4466.4  470.10  4482.3  472.38  4657.7  472.30  4771.7  472.01  4999.9  471.39
  5126.1  471.68  5480.8  470.06  5496.1  471.96  5517.3  469.45  5553.8  471.69
  5605.6  470.49  5611.5  468.01  5626.0  470.42  5635.3  467.48  5659.8  464.88
  5660.3  464.08  5666.6  464.88  5781.9  467.48  5867.5  471.35  5889.1  472.12
#Mann=8,-1,0
  3715.0    0.05       0  4657.7    0.07       0  4771.7    0.16       0
  4999.9    0.12       0  5126.1    0.05       0  5659.8    0.07       0
  5666.6    0.05       0  5867.5    0.16       0
Bank Sta=5635.3,5781.9
Exp/Cntr=0.3,0.1

Type RM Length L Ch R = 1,6057,676,676,676
BEGIN DESCRIPTION:
Mapping XS aaa14805
END DESCRIPTION:
XS GIS Cut Line= 6
      2803187.65      7058489.67      2803191.12      7058093.85
      2803083.48      7057840.37      2802889.04      7057406.35
      2802583.48      7056948.01      2802253.64      7056805.66
#Sta/Elev= 30
  3847.5  470.03  4111.5  470.41  4323.3  467.15  4587.2  457.87  4699.1  451.95
  4714.5  451.14  4752.8  449.56  4864.2  447.69  4875.2  449.04  4912.2  446.96
  4962.5  446.24  4989.7  438.37  4990.2  437.57  4996.5  438.37  5006.3  438.42
  5012.3  445.72  5027.3  449.24  5048.3  450.81  5094.6  450.01  5136.8  449.56
  5351.8  450.14  5538.1  453.41  5608.9  457.72  5620.5  459.95  5638.6  467.10
  5662.1  471.54  5714.6  468.16  5843.0  468.13  5903.7  471.20  5904.4  471.20
#Mann=9,-1,0
  3847.5    0.05       0  4587.2    0.16       0  4699.1    0.12       0
  4714.5    0.16       0  4912.2    0.12       0  4989.7    0.07       0
  4996.5    0.12       0  5094.6    0.05       0  5903.7    0.16       0
Bank Sta=4752.8,5136.8
Exp/Cntr=0.3,0.1

Type RM Length L Ch R = 1,5381,707,707,707
BEGIN DESCRIPTION:
GARRETT CREEK 5.0
END DESCRIPTION:
XS GIS Cut Line= 3
      2803291.86      7057860.99      2803252.79      7057196.91
      2802263.17      7056793.25
#Sta/Elev= 30
  4340.7  461.07  4827.5  453.00  4847.6  452.22  4867.6  449.72  4882.9  451.56
  4887.9  449.86  4907.7  449.44  4933.1  446.42  4977.8  443.78  4994.0  437.24
  4994.6  436.44  5001.7  437.24  5004.4  440.03  5009.5  441.47  5022.0  446.18
  5049.0  446.41  5143.9  445.35  5182.4  447.08  5255.0  446.42  5628.9  451.46
  5741.2  454.64  5794.7  457.25  5813.3  464.02  5818.7  463.96  5824.3  467.51
  5842.8  471.41  5889.1  468.05  6032.6  467.93  6056.7  471.30  6074.7  471.01
#Mann=5,-1,0
  4340.7    0.16       0  4994.0    0.07       0  5001.7    0.16       0
  5009.5    0.12       0  5049.0    0.05       0
Bank Sta=4933.1,5255
Exp/Cntr=0.3,0.1

Type RM Length L Ch R = 1,4674,94,94,94
BEGIN DESCRIPTION:
Mapping XS 755a81bc
END DESCRIPTION:
XS GIS Cut Line= 4
      2803304.87      7057848.00      2803348.28      7057040.66
      2803348.28      7056641.36      2803313.56      7055920.90
#Sta/Elev= 30
  3789.2  459.16  4252.5  453.31  4257.6  451.74  4353.0  450.25  4403.1  451.75
  4547.3  446.03  4563.3  443.39  4573.3  445.78  4593.0  446.24  4673.4  445.29
  4693.4  443.42  4713.4  438.13  4723.4  437.63  4733.4  439.68  4743.4  443.89
  4763.4  445.71  4983.4  444.24  5013.4  440.70  5019.5  436.90  5020.1  436.10
  5027.2  436.90  5043.4  444.47  5063.4  441.98  5093.5  444.49  5125.6  444.21
  5168.8  446.04  5251.9  446.03  5326.6  446.53  5514.0  448.87  5718.3  462.92
#Mann=5,-1,0
  3789.2    0.05       0  5019.5    0.04       0  5027.2    0.05       0
  5125.6    0.08       0  5326.6    0.05       0
Bank Sta=4547.3,5251.9
Exp/Cntr=0.3,0.1

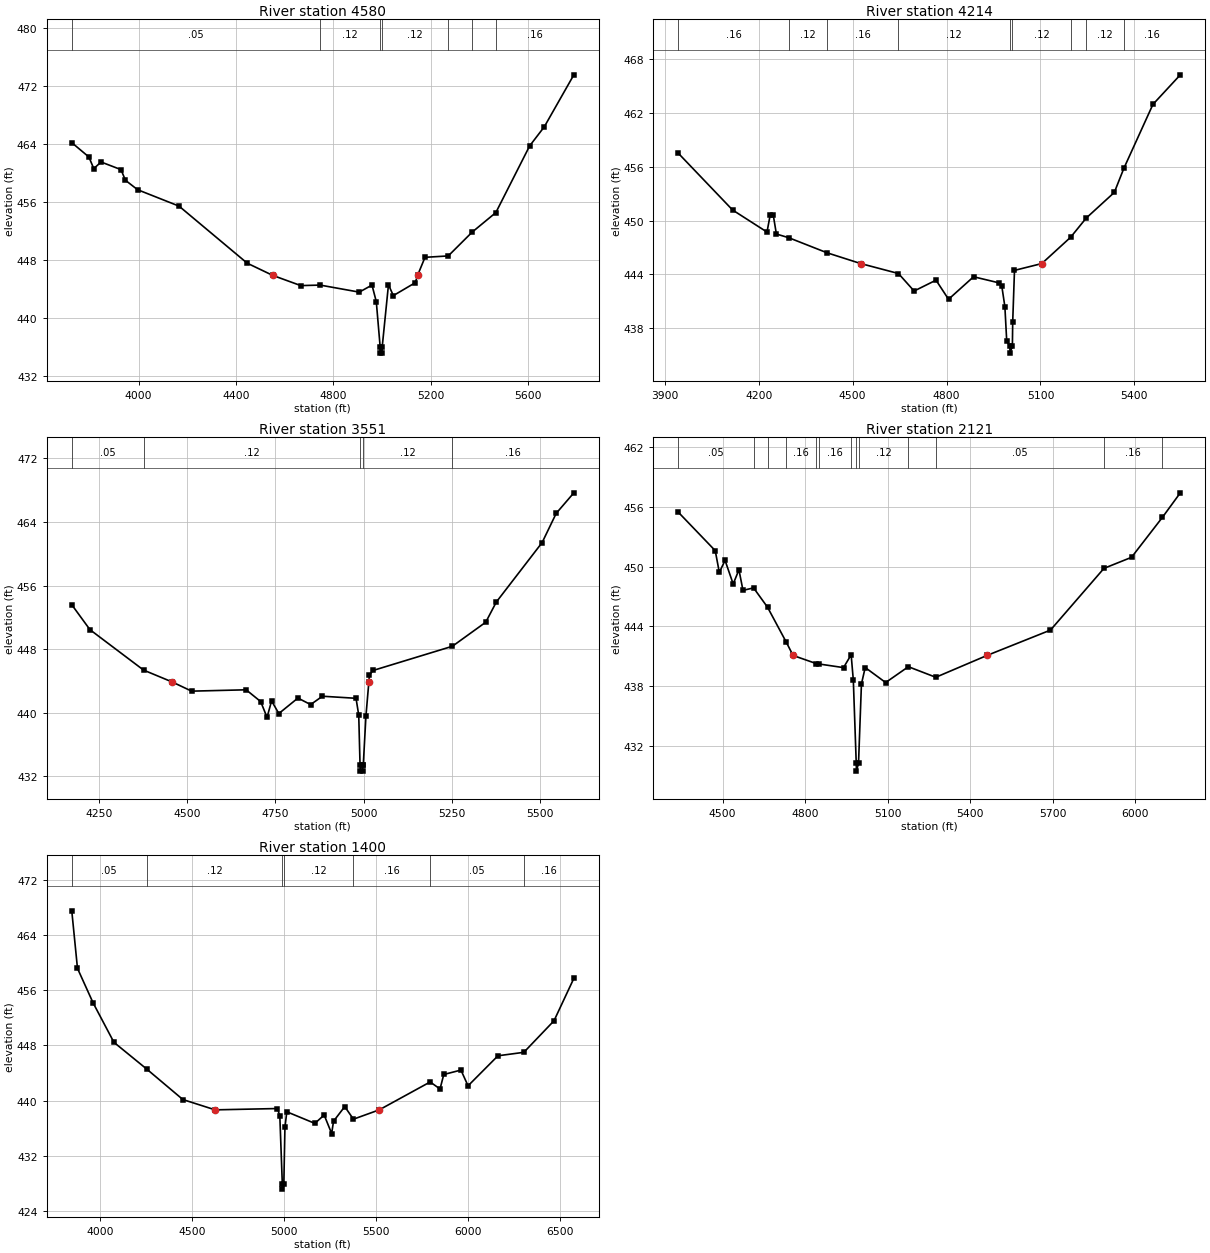
Type RM Length L Ch R = 1,4580,366,366,366
BEGIN DESCRIPTION:
Mapping XS a8bcf717
END DESCRIPTION:
XS GIS Cut Line= 3
      2803383.00      7057865.35      2803426.40      7056632.68
      2803448.10      7055803.70
#Sta/Elev= 30
  3725.5  464.21  3795.9  462.23  3815.9  460.63  3845.9  461.54  3927.7  460.49
  3946.0  459.02  3996.0  457.72  4166.1  455.46  4446.3  447.59  4551.0  445.91
  4666.4  444.50  4746.0  444.57  4906.6  443.60  4958.9  444.57  4976.6  442.29
  4992.6  435.99  4993.2  435.19  5000.0  435.19  5000.7  435.99  5026.6  444.62
  5046.6  443.12  5136.7  444.90  5146.2  445.91  5176.7  448.40  5272.2  448.59
  5370.0  451.86  5467.8  454.57  5606.8  463.77  5666.9  466.40  5788.2  473.56
#Mann=7,-1,0
  3725.5    0.05       0  4746.0    0.12       0  4992.6    0.07       0
  5000.7    0.12       0  5272.2    0.16       0  5370.0    0.12       0
  5467.8    0.16       0
Bank Sta=4551,5146.2
Exp/Cntr=0.3,0.1

Type RM Length L Ch R = 1,4214,663,663,663
BEGIN DESCRIPTION:
Mapping XS b9797558
END DESCRIPTION:
XS GIS Cut Line= 3
      2803704.18      7057448.64      2803704.18      7056398.30
      2803573.96      7055860.07
#Sta/Elev= 30
  3942.7  457.51  4116.3  451.18  4226.3  448.72  4236.3  450.59  4246.3  450.61
  4256.3  448.50  4295.8  448.09  4418.2  446.41  4525.7  445.21  4646.3  444.10
  4696.3  442.15  4766.3  443.36  4806.3  441.23  4886.3  443.74  4966.3  443.07
  4976.3  442.74  4986.3  440.41  4992.2  436.56  5002.1  436.03  5002.8  435.23
  5010.3  436.03  5011.3  438.70  5017.0  444.45  5104.3  445.21  5196.3  448.14
  5246.2  450.28  5336.0  453.14  5366.3  455.81  5459.4  462.95  5546.8  466.24
#Mann=9,-1,0
  3942.7    0.16       0  4295.8    0.12       0  4418.2    0.16       0
  4646.3    0.12       0  5002.1    0.07       0  5010.3    0.12       0
  5196.3    0.16       0  5246.2    0.12       0  5366.3    0.16       0
Bank Sta=4525.7,5104.3
Exp/Cntr=0.3,0.1

Type RM Length L Ch R = 1,3551,1430,1430,1430
BEGIN DESCRIPTION:
GARRETT CREEK 2.0
END DESCRIPTION:
XS GIS Cut Line= 3
      2804275.01      7057025.03      2804075.00      7056225.00
      2804075.00      7055624.96
#Sta/Elev= 30
  4171.9  453.58  4223.5  450.44  4375.7  445.35  4457.1  443.85  4512.1  442.70
  4666.7  442.87  4707.9  441.39  4726.0  439.40  4738.9  441.47  4759.5  439.88
  4813.6  441.83  4849.7  441.01  4883.2  442.06  4978.5  441.80  4986.2  439.69
  4989.9  433.43  4990.6  432.63  4997.4  432.63  4998.1  433.43  4999.1  433.43
  5006.6  439.55  5014.9  443.85  5016.6  444.75  5026.6  445.30  5251.9  448.35
  5346.6  451.38  5376.6  453.92  5506.6  461.41  5546.6  465.09  5596.6  467.67
#Mann=5,-1,0
  4171.9    0.05       0  4375.7    0.12       0  4989.9    0.07       0
  4998.1    0.12       0  5251.9    0.16       0
Bank Sta=4457.1,5014.9
Exp/Cntr=0.3,0.1

Type RM Length L Ch R = 1,2121,721,721,721
BEGIN DESCRIPTION:
GARRETT CREEK 1.0
END DESCRIPTION:
XS GIS Cut Line= 3
      2804422.94      7056960.79      2804818.76      7056405.25
      2804624.32      7055280.26
#Sta/Elev= 30
  4339.2  455.48  4473.6  451.61  4488.4  449.43  4509.3  450.63  4538.8  448.26
  4559.7  449.69  4574.4  447.62  4612.9  447.87  4663.5  445.93  4731.0  442.45
  4756.4  441.08  4840.0  440.27  4849.2  440.23  4939.6  439.86  4967.3  441.15
  4975.2  438.60  4985.8  430.26  4986.5  429.46  4994.1  430.26  5004.7  438.22
  5018.4  439.87  5092.6  438.36  5175.1  439.95  5274.8  438.89  5460.6  441.08
  5691.4  443.63  5885.6  449.83  5985.7  450.94  6097.8  454.95  6163.0  457.42
#Mann=13,-1,0
  4339.2    0.05       0  4612.9    0.16       0  4663.5    0.05       0
  4731.0    0.16       0  4840.0    0.05       0  4849.2    0.16       0
  4967.3    0.12       0  4985.8    0.07       0  4994.1    0.12       0
  5175.1    0.16       0  5274.8    0.05       0  5885.6    0.16       0
  6097.8    0.05       0
Bank Sta=4756.4,5460.6
Exp/Cntr=0.3,0.1

Type RM Length L Ch R = 1,1400,0,0,0
BEGIN DESCRIPTION:
Mapping XS 729cd6b4
END DESCRIPTION:
XS GIS Cut Line= 3
      2804610.46      7057384.38      2805311.82      7056669.13
      2805013.41      7054968.86
#Sta/Elev= 30
  3846.7  467.49  3877.7  459.16  3962.6  454.16  4075.7  448.45  4252.8  444.60
  4450.5  440.16  4625.7  438.67  4964.3  438.86  4977.1  437.80  4990.6  427.99
  4991.3  427.19  4998.9  427.99  5004.9  436.12  5015.1  438.39  5167.4  436.71
  5218.1  437.92  5258.8  435.24  5268.9  437.02  5329.8  439.14  5377.1  437.32
  5517.4  438.67  5794.1  442.71  5847.6  441.69  5867.9  443.79  5961.2  444.43
  5999.9  442.15  6162.4  446.50  6303.0  447.00  6466.9  451.57  6574.7  457.71
#Mann=7,-1,0
  3846.7    0.05       0  4252.8    0.12       0  4990.6    0.07       0
  4998.9    0.12       0  5377.1    0.16       0  5794.1    0.05       0
  6303.0    0.16       0
Bank Sta=4625.7,5517.4
Exp/Cntr=0.3,0.1

Chan Stop Cuts=-1