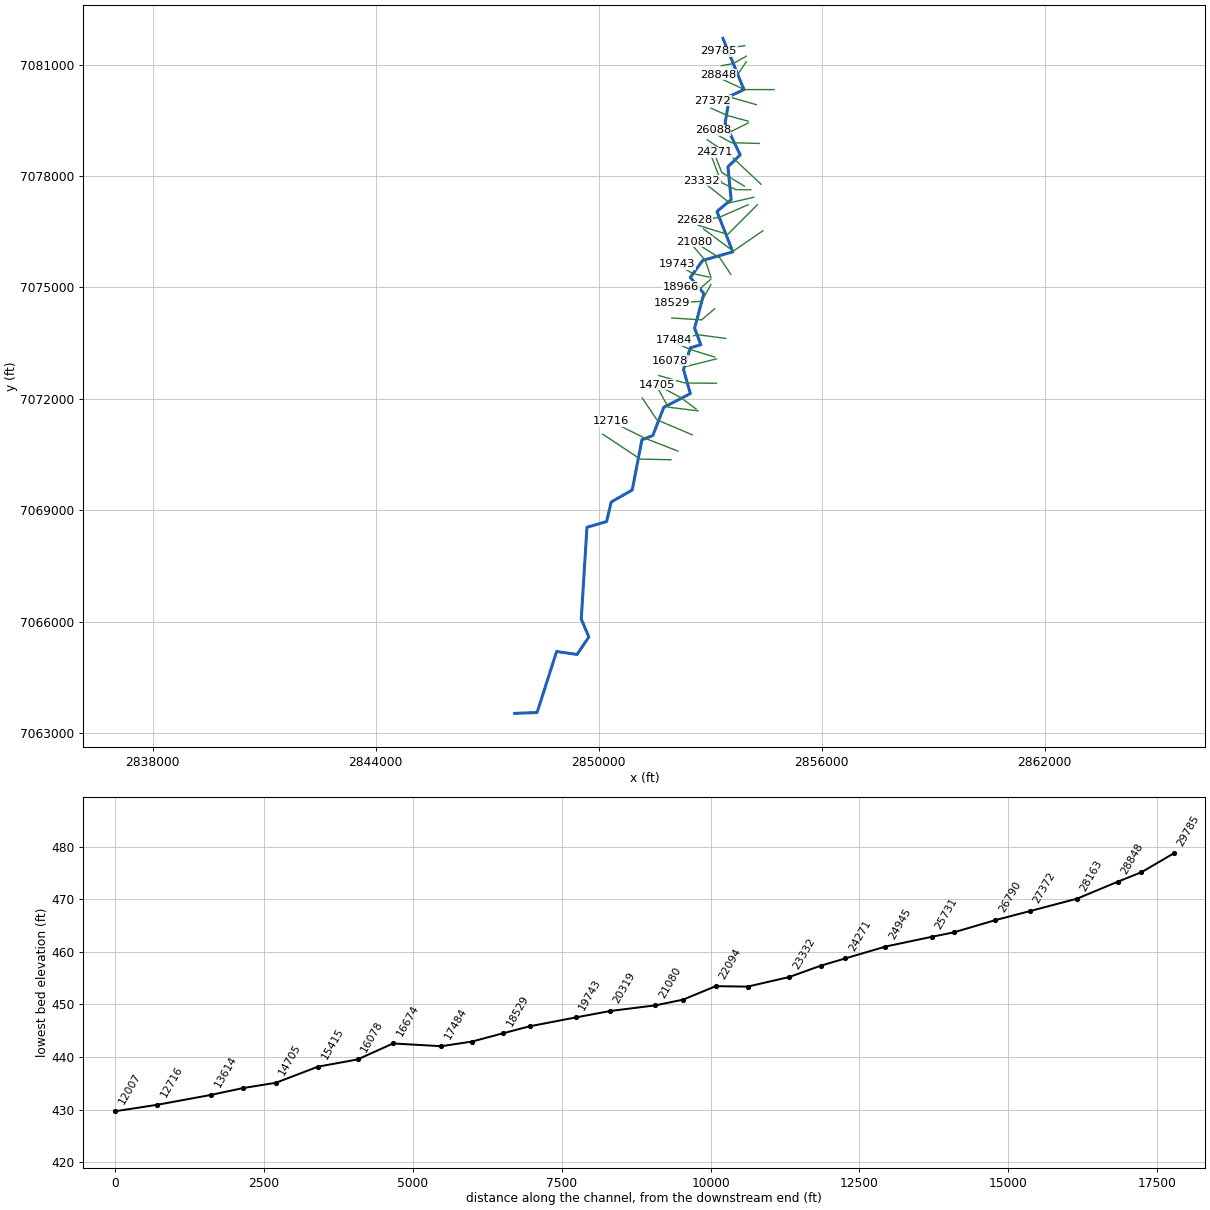
--- GIDEON CREEK.prj (project) ---

Proj Title=GIDEON CREEK Base Level Engineering
Current Plan=p01
Default Exp/Contr=0.3,0.1
English Units
Geom File=g01
Flow File=f01
Plan File=p01
BEGIN DESCRIPTION:
GIDEON CREEK
END DESCRIPTION:

--- GIDEON CREEK.p01 (plan) ---

Plan Title=Multiple Run
Short Identifier=Multiple
Geom File=g01
Flow File=f01
Subcritical Flow
K Sum by GR= 0
Std Step Tol= 0.01
Critical Tol= 0.01
Num of Std Step Trials= 20
Max Error Tol= 0.3
Flow Tol Ratio= 0.001
Split Flow NTrial= 30
Split Flow Tol= 0.02
Split Flow Ratio= 0.02
Log Output Level= 0
Friction Slope Method= 1
Unsteady Friction Slope Method= 2
Unsteady Bridges Friction Slope Method= 1
Parabolic Critical Depth
Global Vel Dist=  1 , 1 , 1
Global Log Level= 0
CheckData=True
Encroach Param= -1, 0, 0, 0
BEGIN DESCRIPTION:
Multiple Run
END DESCRIPTION:

--- GIDEON CREEK.f01 (steady flow) ---

Flow Title=Multiple
Program Version=5.07
Number of Profiles= 7
Profile Names=10-year,25-year,50-year,1pct_min,100-year,1pct_plu,500-year
River Rch & RM=GIDEON CREEK,Reach-1         ,29785
     726     969    1164     694    1384    2762    1952
River Rch & RM=GIDEON CREEK,Reach-1         ,28163
    1569    2183    2698    1650    3291    6567    4889
River Rch & RM=GIDEON CREEK,Reach-1         ,23332
    2115    2977    3707    2280    4550    9078    6844
River Rch & RM=GIDEON CREEK,Reach-1         ,17999
    2205    3102    3862    2374    4736    9450    7116
River Rch & RM=GIDEON CREEK,Reach-1         ,12716
    2713    3853    4828    2985    5955   11882    9052
River Rch & RM=GIDEON CREEK,Reach-1         ,8016
    2667    3771    4708    2900    5786   11544    8729
Boundary for River Rch & Prof#=GIDEON CREEK,Reach-1         , 1
Up Type= 0
Dn Type= 3
Dn Slope=0.005
Boundary for River Rch & Prof#=GIDEON CREEK,Reach-1         , 2
Up Type= 0
Dn Type= 3
Dn Slope=0.005
Boundary for River Rch & Prof#=GIDEON CREEK,Reach-1         , 3
Up Type= 0
Dn Type= 3
Dn Slope=0.005
Boundary for River Rch & Prof#=GIDEON CREEK,Reach-1         , 4
Up Type= 0
Dn Type= 3
Dn Slope=0.005
Boundary for River Rch & Prof#=GIDEON CREEK,Reach-1         , 5
Up Type= 0
Dn Type= 3
Dn Slope=0.005
Boundary for River Rch & Prof#=GIDEON CREEK,Reach-1         , 6
Up Type= 0
Dn Type= 3
Dn Slope=0.005
Boundary for River Rch & Prof#=GIDEON CREEK,Reach-1         , 7
Up Type= 0
Dn Type= 3
Dn Slope=0.005
DSS Import GetInterval= 0
DSS Import GetPeak= 0
DSS Import FillOption= 0

--- GIDEON CREEK.g01 (geometry) ---

Geom Title=Existing Conditions

River Reach=GIDEON CREEK,Reach-1
Reach XY= 30
      2853347.76      7081704.76      2853913.35      7080324.71
      2853527.33      7080144.96      2853406.12      7079410.52
      2853813.08      7078567.20      2853482.53      7078244.68
      2853568.92      7077363.94      2853187.83      7077041.37
      2853613.07      7075956.11      2852803.00      7075725.28
      2852469.31      7075269.32      2852834.82      7074833.75
      2852585.59      7073901.85      2852753.63      7073455.80
      2852470.81      7073373.27      2852287.88      7072785.31
      2852470.99      7072141.76      2851756.25      7071769.65
      2851459.41      7071008.81      2851169.13      7070898.71
      2850906.74      7069544.08      2850341.49      7069222.18
      2850218.79      7068695.89      2849689.36      7068539.93
      2849535.62      7066070.39      2849740.63      7065588.51
      2849422.37      7065116.59      2848873.31      7065197.31
      2848347.96      7063554.18      2847745.59      7063530.71

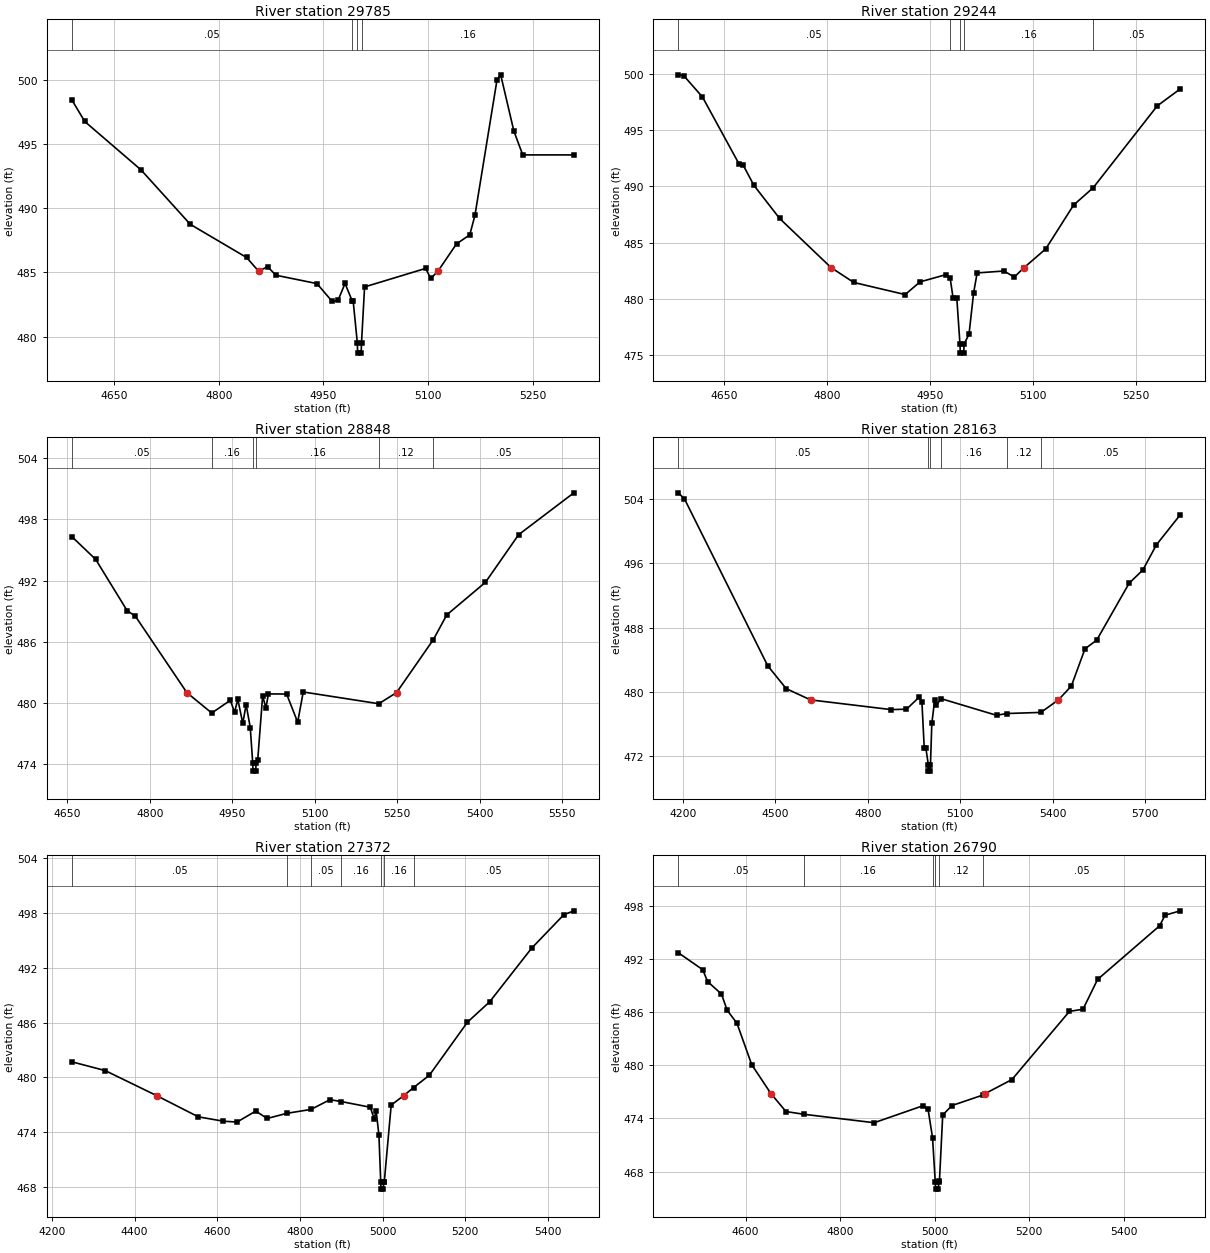
Type RM Length L Ch R = 1,29785,541,541,541
BEGIN DESCRIPTION:
GIDEON CREEK 42.0
END DESCRIPTION:
XS GIS Cut Line= 3
      2853933.49      7081505.85      2853533.53      7081455.86
      2853233.53      7081355.86
#Sta/Elev= 30
  4589.5  498.43  4608.1  496.74  4688.8  492.97  4759.3  488.74  4839.9  486.16
  4857.1  485.10  4870.2  485.44  4881.9  484.78  4940.7  484.13  4962.5  482.75
  4970.9  482.82  4981.0  484.14  4991.1  482.80  4992.6  482.80  4998.6  479.52
  4999.1  478.72  5004.1  478.72  5004.6  479.52  5009.0  483.87  5096.4  485.31
  5103.8  484.53  5114.2  485.10  5140.7  487.22  5159.7  487.92  5167.1  489.44
  5198.7  499.97  5204.0  500.37  5222.9  495.99  5235.6  494.14  5308.8  494.14
#Mann=4,-1,0
  4589.5    0.05       0  4991.1    0.16       0  4998.6    0.07       0
  5004.6    0.16       0
Bank Sta=4857.1,5114.2
Exp/Cntr=0.3,0.1

Type RM Length L Ch R = 1,29244,396,396,396
BEGIN DESCRIPTION:
GIDEON CREEK 41.0
END DESCRIPTION:
XS GIS Cut Line= 3
      2853975.04      7081225.02      2853625.00      7081025.00
      2853301.95      7080967.98
#Sta/Elev= 30
  4582.9  499.95  4590.9  499.88  4618.2  497.97  4671.5  492.00  4677.2  491.93
  4693.1  490.10  4730.5  487.15  4805.4  482.77  4838.5  481.44  4913.4  480.36
  4935.0  481.49  4972.4  482.13  4978.9  481.83  4983.2  480.05  4988.6  480.05
  4993.2  475.94  4993.7  475.14  4998.7  475.14  4999.2  475.94  5006.4  476.84
  5013.1  480.52  5018.2  482.29  5057.1  482.46  5072.4  481.93  5086.7  482.77
  5118.1  484.43  5158.7  488.34  5187.3  489.89  5280.5  497.18  5314.1  498.70
#Mann=5,-1,0
  4582.9    0.05       0  4978.9    0.16       0  4993.2    0.07       0
  4999.2    0.16       0  5187.3    0.05       0
Bank Sta=4805.4,5086.7
Exp/Cntr=0.3,0.1

Type RM Length L Ch R = 1,28848,685,685,685
BEGIN DESCRIPTION:
GIDEON CREEK 40.0
END DESCRIPTION:
XS GIS Cut Line= 3
      2853974.98      7081074.97      2853775.00      7080775.00
      2853224.99      7080725.00
#Sta/Elev= 30
  4658.1  496.32  4701.6  494.08  4758.7  489.07  4773.7  488.52  4867.3  481.04
  4912.6  479.04  4946.5  480.29  4954.0  479.11  4960.0  480.37  4969.0  478.03
  4975.1  479.87  4982.6  477.62  4987.1  474.15  4987.6  473.35  4992.6  473.35
  4993.1  474.15  4996.1  474.40  5005.1  480.72  5011.1  479.54  5015.6  480.91
  5048.7  480.90  5068.8  478.14  5078.9  481.10  5216.3  479.95  5248.6  481.04
  5315.5  486.23  5339.9  488.65  5410.2  491.84  5470.5  496.50  5570.9  500.60
#Mann=6,-1,0
  4658.1    0.05       0  4912.6    0.16       0  4987.1    0.07       0
  4993.1    0.16       0  5216.3    0.12       0  5315.5    0.05       0
Bank Sta=4867.3,5248.6
Exp/Cntr=0.3,0.1

Type RM Length L Ch R = 1,28163,791,791,791
BEGIN DESCRIPTION:
GIDEON CREEK 39.0
END DESCRIPTION:
XS GIS Cut Line= 3
      2854725.02      7080325.00      2853925.00      7080325.00
      2853174.97      7080675.01
#Sta/Elev= 30
  4185.6  504.80  4205.6  504.06  4475.6  483.25  4535.6  480.39  4614.6  478.99
  4875.6  477.78  4925.6  477.83  4965.6  479.29  4975.6  478.74  4983.1  472.99
  4988.4  472.99  4996.3  470.91  4996.8  470.11  5002.8  470.11  5003.3  470.91
  5007.7  476.05  5017.1  479.02  5022.7  478.34  5038.0  479.14  5217.4  477.07
  5250.8  477.29  5361.3  477.43  5418.1  478.99  5460.1  480.72  5504.3  485.36
  5542.1  486.43  5647.7  493.55  5691.9  495.18  5736.0  498.33  5813.3  502.07
#Mann=6,-1,0
  4185.6    0.05       0  4996.3    0.03       0  5003.3    0.05       0
  5038.0    0.16       0  5250.8    0.12       0  5361.3    0.05       0
Bank Sta=4614.6,5418.1
Exp/Cntr=0.3,0.1

Type RM Length L Ch R = 1,27372,582,582,582
BEGIN DESCRIPTION:
GIDEON CREEK 38.0
END DESCRIPTION:
XS GIS Cut Line= 3
      2854249.23      7079918.29      2853525.00      7080125.00
      2853075.03      7080025.01
#Sta/Elev= 30
  4248.3  481.70  4329.0  480.74  4453.3  478.00  4554.3  475.67  4615.2  475.19
  4647.9  475.10  4693.2  476.30  4720.7  475.49  4768.9  476.06  4826.6  476.48
  4872.7  477.55  4900.3  477.34  4970.3  476.72  4979.3  475.48  4984.5  476.27
  4991.1  473.64  4995.4  468.55  4995.9  467.75  5001.9  467.75  5002.4  468.55
  5004.0  468.55  5020.7  476.96  5051.1  478.00  5074.9  478.88  5112.9  480.22
  5205.1  486.04  5258.8  488.27  5360.0  494.13  5438.1  497.81  5462.4  498.24
#Mann=7,-1,0
  4248.3    0.05       0  4768.9    0.07       0  4826.6    0.05       0
  4900.3    0.16       0  4995.4    0.07       0  5002.4    0.16       0
  5074.9    0.05       0
Bank Sta=4453.3,5051.1
Exp/Cntr=0.3,0.1

Type RM Length L Ch R = 1,26790,702,702,702
BEGIN DESCRIPTION:
GIDEON CREEK 37.0
END DESCRIPTION:
XS GIS Cut Line= 3
      2854024.97      7079475.01      2853475.00      7079625.00
      2853025.00      7079825.00
#Sta/Elev= 30
  4457.4  492.70  4509.2  490.78  4519.6  489.44  4548.9  488.03  4561.0  486.20
  4581.7  484.74  4612.8  480.08  4653.5  476.81  4685.4  474.78  4723.6  474.47
  4872.0  473.52  4975.6  475.44  4986.0  475.06  4995.6  471.82  5001.3  466.83
  5001.9  466.03  5008.1  466.03  5008.6  466.83  5010.2  466.97  5017.1  474.38
  5036.3  475.45  5103.2  476.66  5107.1  476.81  5163.6  478.39  5285.3  486.08
  5314.0  486.32  5344.8  489.68  5476.1  495.73  5487.7  496.93  5519.9  497.42
#Mann=6,-1,0
  4457.4    0.05       0  4723.6    0.16       0  4995.6    0.12       0
  5001.3    0.07       0  5008.6    0.12       0  5103.2    0.05       0
Bank Sta=4653.5,5107.1
Exp/Cntr=0.3,0.1

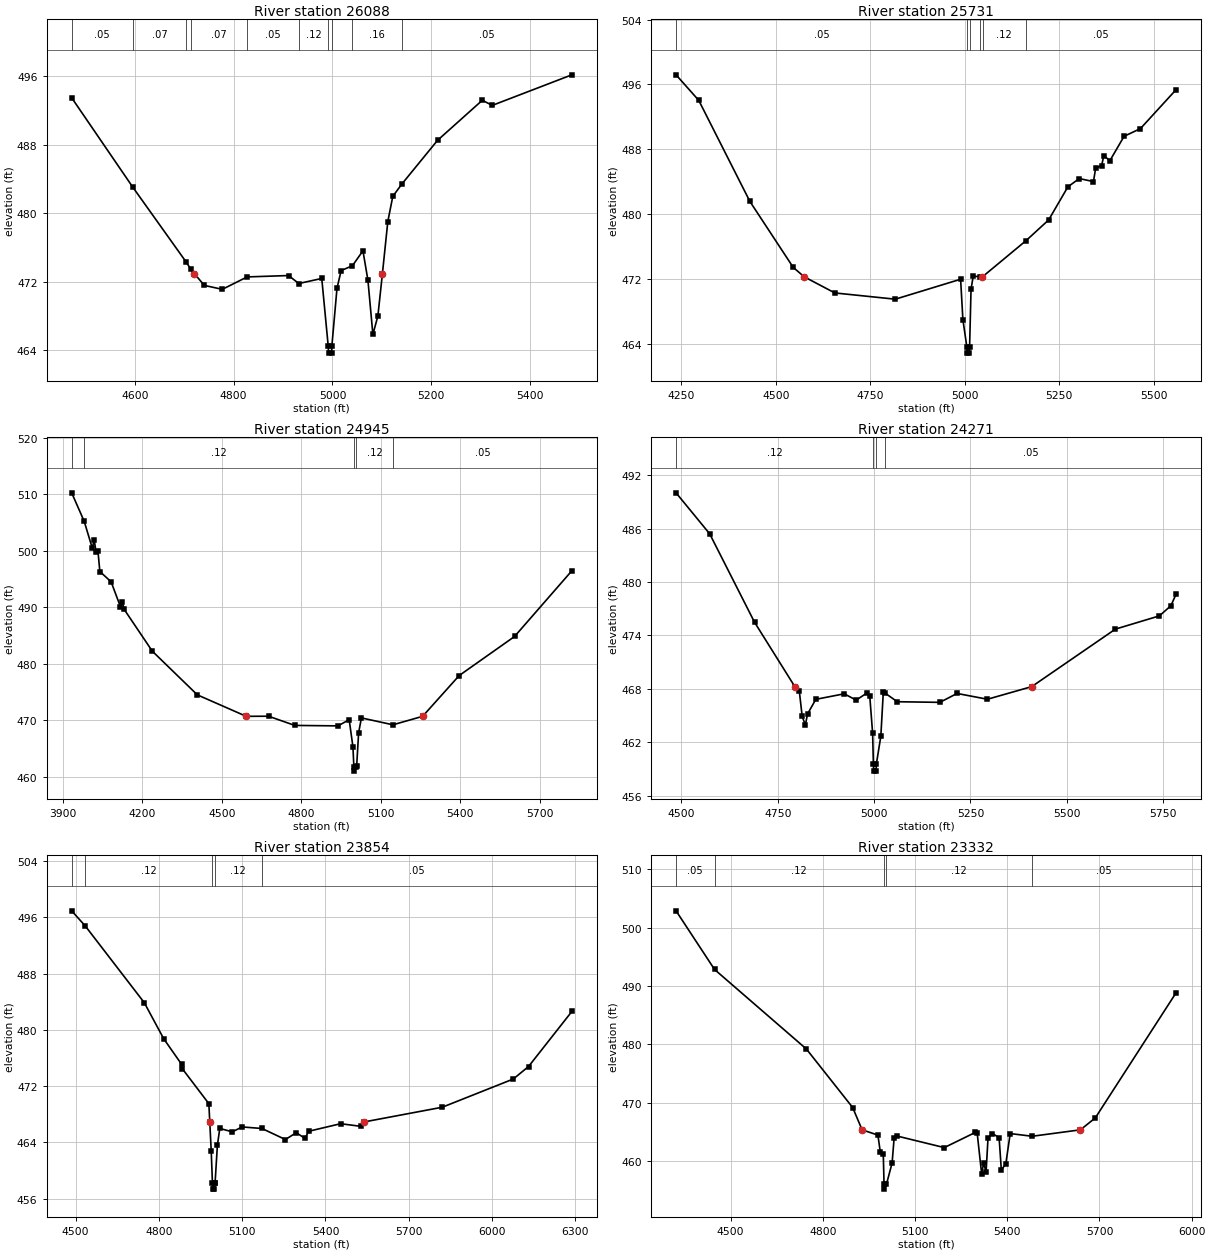
Type RM Length L Ch R = 1,26088,357,357,357
BEGIN DESCRIPTION:
GIDEON CREEK 36.0
END DESCRIPTION:
XS GIS Cut Line= 3
      2854025.01      7079425.00      2853525.00      7079175.00
      2853075.00      7079225.00
#Sta/Elev= 30
  4472.4  493.51  4595.9  483.08  4703.6  474.36  4713.5  473.49  4720.7  472.97
  4740.7  471.60  4777.1  471.14  4827.4  472.59  4911.2  472.75  4931.8  471.82
  4978.3  472.41  4991.4  464.49  4992.0  463.69  4998.2  463.69  4998.7  464.49
  5009.1  471.26  5017.5  473.33  5040.4  473.90  5061.6  475.64  5071.7  472.20
  5081.7  465.87  5091.8  468.02  5101.0  472.97  5111.9  479.05  5122.0  482.00
  5140.4  483.44  5212.5  488.54  5303.1  493.22  5323.2  492.62  5484.2  496.19
#Mann=10,-1,0
  4472.4    0.05       0  4595.9    0.07       0  4703.6    0.05       0
  4713.5    0.07       0  4827.4    0.05       0  4931.8    0.12       0
  4991.4    0.07       0  4998.7    0.12       0  5040.4    0.16       0
  5140.4    0.05       0
Bank Sta=4720.7,5101
Exp/Cntr=0.3,0.1

Type RM Length L Ch R = 1,25731,786,786,786
BEGIN DESCRIPTION:
GIDEON CREEK 35.0
END DESCRIPTION:
XS GIS Cut Line= 3
      2854325.04      7078875.00      2853575.05      7078894.19
      2853075.03      7079174.98
#Sta/Elev= 30
  4236.1  497.19  4296.2  494.04  4431.4  481.59  4546.2  473.45  4575.3  472.29
  4656.3  470.30  4816.3  469.53  4989.2  471.99  4995.2  467.02  5005.6  463.68
  5006.2  462.88  5012.4  462.88  5013.0  463.68  5016.8  470.78  5022.6  472.37
  5041.5  472.29  5045.2  472.29  5047.3  472.30  5162.4  476.75  5222.2  479.30
  5273.1  483.38  5303.2  484.40  5340.8  484.03  5346.5  485.67  5362.5  486.01
  5368.2  487.24  5384.2  486.60  5421.8  489.61  5465.1  490.56  5559.8  495.38
#Mann=6,-1,0
  4236.1    0.05       0  5005.6    0.03       0  5013.0    0.05       0
  5041.5    0.16       0  5047.3    0.12       0  5162.4    0.05       0
Bank Sta=4575.3,5045.2
Exp/Cntr=0.3,0.1

Type RM Length L Ch R = 1,24945,674,674,674
BEGIN DESCRIPTION:
GIDEON CREEK 34.0
END DESCRIPTION:
XS GIS Cut Line= 3
      2854375.03      7077774.97      2853575.00      7078525.00
      2852925.00      7078975.00
#Sta/Elev= 30
  3933.3  510.26  3980.6  505.21  4011.2  500.45  4018.1  501.96  4025.4  499.76
  4032.3  500.04  4039.6  496.33  4082.1  494.51  4117.3  490.10  4124.6  490.89
  4131.4  489.63  4237.4  482.24  4407.4  474.50  4592.0  470.70  4676.1  470.72
  4775.2  469.09  4937.9  469.01  4980.4  470.10  4994.5  465.30  4998.0  461.80
  4998.6  461.00  5005.6  461.80  5008.7  461.97  5016.0  467.79  5026.5  470.42
  5145.5  469.20  5257.5  470.70  5395.5  477.92  5604.3  484.83  5820.5  496.46
#Mann=5,-1,0
  3933.3    0.05       0  3980.6    0.12       0  4998.0    0.07       0
  5005.6    0.12       0  5145.5    0.05       0
Bank Sta=4592,5257.5
Exp/Cntr=0.3,0.1

Type RM Length L Ch R = 1,24271,417,417,417
BEGIN DESCRIPTION:
GIDEON CREEK 33.0
END DESCRIPTION:
XS GIS Cut Line= 3
      2853925.00      7077725.00      2853316.52      7078093.47
      2853103.93      7078640.14
#Sta/Elev= 30
  4486.1  490.03  4573.4  485.42  4689.7  475.49  4794.3  468.25  4806.1  467.70
  4813.4  464.90  4821.6  463.94  4827.5  465.19  4848.8  466.82  4922.5  467.44
  4953.5  466.73  4980.7  467.51  4988.8  467.16  4996.2  463.01  4998.2  459.55
  4998.8  458.75  5005.2  458.75  5005.9  459.55  5017.5  462.67  5023.9  467.63
  5028.5  467.52  5060.2  466.55  5170.7  466.48  5215.3  467.48  5294.2  466.83
  5409.2  468.25  5626.1  474.71  5740.3  476.20  5770.2  477.34  5784.0  478.68
#Mann=4,-1,0
  4486.1    0.12       0  4998.2    0.07       0  5005.9    0.12       0
  5028.5    0.05       0
Bank Sta=4794.3,5409.2
Exp/Cntr=0.3,0.1

Type RM Length L Ch R = 1,23854,522,522,522
BEGIN DESCRIPTION:
Mapping XS a08a9b38
END DESCRIPTION:
XS GIS Cut Line= 4
      2854096.62      7077627.96      2853700.82      7077627.96
      2853304.98      7077822.40      2852964.70      7078725.18
#Sta/Elev= 30
  4485.9  496.91  4535.0  494.75  4747.5  483.85  4817.5  478.72  4881.7  475.10
  4884.5  474.46  4980.0  469.50  4983.3  466.89  4988.5  462.79  4993.0  458.15
  4993.6  457.35  5000.1  457.35  5000.7  458.15  5002.5  458.28  5010.7  463.56
  5019.4  465.98  5064.3  465.49  5099.9  466.19  5171.1  465.97  5255.8  464.40
  5294.7  465.37  5326.8  464.56  5339.2  465.57  5454.7  466.65  5528.5  466.27
  5537.7  466.89  5820.6  468.99  6076.5  473.00  6131.5  474.78  6287.5  482.60
#Mann=5,-1,0
  4485.9    0.05       0  4535.0    0.12       0  4993.0    0.07       0
  5000.7    0.12       0  5171.1    0.05       0
Bank Sta=4983.3,5537.7
Exp/Cntr=0.3,0.1

Type RM Length L Ch R = 1,23332,704,704,704
BEGIN DESCRIPTION:
double GIDEON CREEK 31.0
END DESCRIPTION:
XS GIS Cut Line= 3
      2854174.97      7077424.99      2853525.00      7077275.00
      2852775.02      7077874.99
#Sta/Elev= 30
  4322.3  502.86  4447.6  492.82  4746.5  479.20  4897.0  469.19  4927.7  465.37
  4979.1  464.47  4986.8  461.62  4996.6  461.29  4999.1  456.02  4999.7  455.22
  5006.8  456.02  5025.4  459.72  5031.8  463.93  5039.8  464.33  5195.1  462.33
  5295.9  464.92  5302.3  464.76  5316.7  457.80  5323.1  459.72  5331.1  458.13
  5337.5  464.04  5351.9  464.74  5373.5  464.03  5380.7  458.53  5395.2  459.51
  5409.6  464.73  5481.1  464.27  5638.0  465.37  5686.5  467.41  5949.8  488.87
#Mann=5,-1,0
  4322.3    0.05       0  4447.6    0.12       0  4999.1    0.07       0
  5006.8    0.12       0  5481.1    0.05       0
Bank Sta=4927.7,5638
Exp/Cntr=0.3,0.1

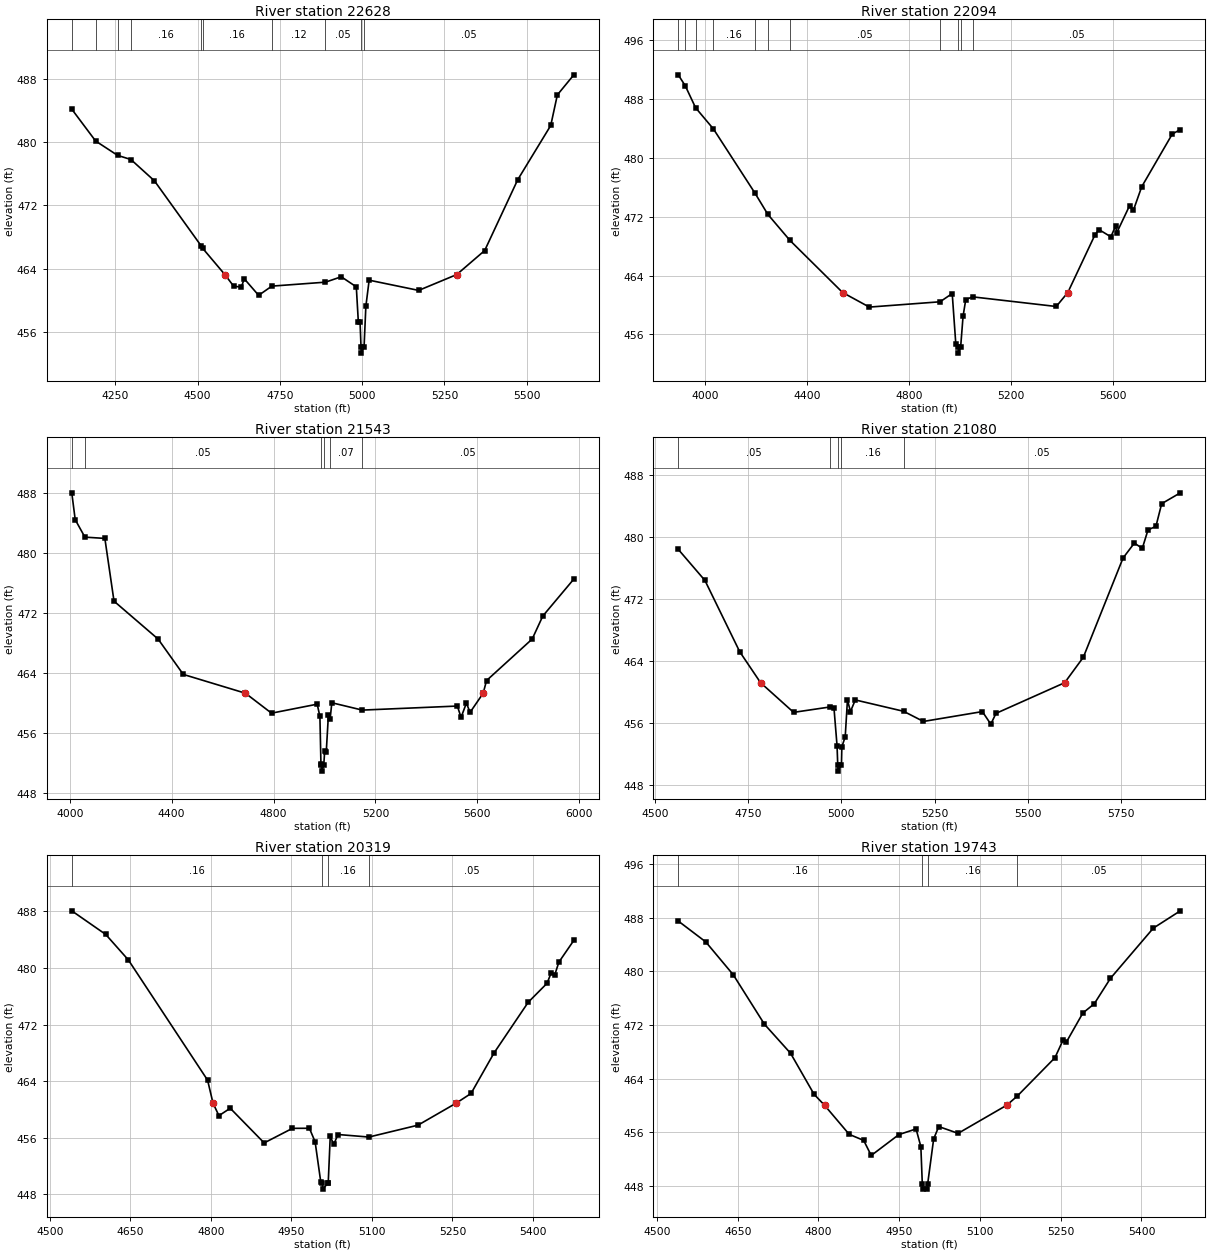
Type RM Length L Ch R = 1,22628,534,534,534
BEGIN DESCRIPTION:
GIDEON CREEK 30.0
END DESCRIPTION:
XS GIS Cut Line= 3
      2854025.00      7077225.00      2853225.00      7076875.00
      2852575.04      7076825.00
#Sta/Elev= 30
  4117.9  484.15  4190.4  480.13  4257.2  478.32  4297.5  477.80  4369.0  475.11
  4510.6  466.93  4515.1  466.62  4582.9  463.29  4609.5  461.83  4632.9  461.70
  4641.8  462.76  4685.5  460.67  4725.6  461.83  4888.6  462.33  4936.5  463.01
  4982.2  461.74  4988.4  457.29  4993.6  457.29  4996.5  454.18  4997.4  453.38
  5005.8  454.18  5011.2  459.27  5021.2  462.58  5171.6  461.29  5287.3  463.29
  5372.2  466.32  5472.5  475.25  5572.8  482.09  5592.9  485.95  5643.0  488.48
#Mann=10,-1,0
  4117.9    0.12       0  4190.4    0.16       0  4257.2    0.12       0
  4297.5    0.16       0  4510.6    0.12       0  4515.1    0.16       0
  4725.6    0.12       0  4888.6    0.05       0  4996.5    0.03       0
  5005.8    0.05       0
Bank Sta=4582.9,5287.3
Exp/Cntr=0.3,0.1

Type RM Length L Ch R = 1,22094,551,551,551
BEGIN DESCRIPTION:
GIDEON CREEK 29.0
END DESCRIPTION:
XS GIS Cut Line= 3
      2854275.03      7077225.03      2853475.00      7076425.00
      2852674.96      7076675.01
#Sta/Elev= 30
  3895.4  491.25  3923.0  489.76  3963.5  486.78  4033.5  483.90  4196.8  475.17
  4246.8  472.31  4333.7  468.77  4540.2  461.70  4645.0  459.72  4922.6  460.44
  4970.2  461.56  4984.4  454.65  4993.9  454.27  4994.8  453.47  5003.2  454.27
  5012.7  458.46  5023.3  460.74  5050.0  461.11  5378.3  459.80  5423.7  461.70
  5529.7  469.49  5545.9  470.24  5592.6  469.26  5610.9  470.71  5616.1  469.84
  5665.9  473.48  5681.1  472.88  5713.6  476.06  5833.5  483.21  5865.0  483.82
#Mann=11,-1,0
  3895.4    0.12       0  3923.0    0.16       0  3963.5    0.12       0
  4033.5    0.16       0  4196.8    0.12       0  4246.8    0.16       0
  4333.7    0.05       0  4922.6    0.12       0  4993.9    0.07       0
  5003.2    0.12       0  5050.0    0.05       0
Bank Sta=4540.2,5423.7
Exp/Cntr=0.3,0.1

Type RM Length L Ch R = 1,21543,463,463,463
BEGIN DESCRIPTION:
GIDEON CREEK 28.0
END DESCRIPTION:
XS GIS Cut Line= 3
      2854425.00      7076525.00      2853625.00      7075975.00
      2852825.02      7076574.98
#Sta/Elev= 30
  4007.8  488.02  4021.3  484.44  4059.3  482.11  4137.7  481.94  4173.6  473.57
  4346.8  468.51  4445.5  463.80  4689.6  461.29  4791.9  458.63  4971.2  459.83
  4981.8  458.19  4985.9  451.81  4987.5  451.70  4988.4  450.90  4996.9  451.70
  5000.5  453.52  5006.8  453.49  5015.1  458.35  5022.1  457.91  5028.6  460.02
  5148.2  459.04  5521.3  459.58  5535.9  458.07  5556.8  459.97  5571.3  458.74
  5622.7  461.29  5635.9  462.98  5815.1  468.52  5856.8  471.59  5978.6  476.52
#Mann=6,-1,0
  4007.8    0.16       0  4059.3    0.05       0  4987.5    0.03       0
  4996.9    0.05       0  5022.1    0.07       0  5148.2    0.05       0
Bank Sta=4689.6,5622.7
Exp/Cntr=0.3,0.1

Type RM Length L Ch R = 1,21080,761,761,761
BEGIN DESCRIPTION:
GIDEON CREEK 27.0
END DESCRIPTION:
XS GIS Cut Line= 3
      2853559.60      7075350.38      2853268.78      7075788.78
      2852575.01      7076224.99
#Sta/Elev= 30
  4563.0  478.39  4634.6  474.38  4727.8  465.20  4783.7  461.21  4872.2  457.39
  4969.0  458.08  4980.4  457.95  4988.6  453.11  4990.5  450.62  4991.5  449.82
  5000.4  450.62  5001.5  452.96  5010.5  454.23  5016.5  458.98  5024.6  457.50
  5037.6  458.99  5166.8  457.53  5220.2  456.22  5378.1  457.49  5400.7  455.87
  5414.6  457.26  5598.7  461.21  5648.7  464.49  5755.1  477.27  5785.5  479.20
  5806.7  478.51  5822.0  480.89  5843.3  481.36  5858.6  484.27  5908.6  485.67
#Mann=5,-1,0
  4563.0    0.05       0  4969.0    0.16       0  4990.5    0.07       0
  5000.4    0.16       0  5166.8    0.05       0
Bank Sta=4783.7,5598.7
Exp/Cntr=0.3,0.1

Type RM Length L Ch R = 1,20319,576,576,576
BEGIN DESCRIPTION:
GIDEON CREEK 26.0
END DESCRIPTION:
XS GIS Cut Line= 3
      2853025.01      7075274.98      2852875.00      7075725.00
      2852575.03      7076074.97
#Sta/Elev= 30
  4540.9  488.07  4604.2  484.73  4646.3  481.13  4793.9  464.14  4804.0  460.90
  4815.0  459.12  4836.1  460.17  4899.3  455.27  4952.0  457.33  4983.6  457.34
  4994.2  455.43  5004.7  449.78  5007.6  449.54  5008.6  448.74  5017.6  449.54
  5018.6  449.54  5022.4  456.19  5029.0  455.05  5036.7  456.46  5094.4  456.10
  5185.9  457.78  5257.2  460.90  5284.7  462.26  5327.5  467.98  5391.2  475.15
  5426.3  477.83  5434.0  479.31  5440.6  479.01  5448.3  480.82  5476.2  483.90
#Mann=4,-1,0
  4540.9    0.16       0  5007.6    0.07       0  5017.6    0.16       0
  5094.4    0.05       0
Bank Sta=4804,5257.2
Exp/Cntr=0.3,0.1

Type RM Length L Ch R = 1,19743,777,777,777
BEGIN DESCRIPTION:
GIDEON CREEK 25.0
END DESCRIPTION:
XS GIS Cut Line= 3
      2852975.01      7075275.00      2852525.00      7075375.00
      2852124.99      7075625.01
#Sta/Elev= 30
  4539.5  487.51  4590.7  484.39  4641.9  479.47  4699.6  472.12  4748.2  467.78
  4791.8  461.67  4811.3  460.03  4857.1  455.69  4884.0  454.79  4898.0  452.54
  4949.3  455.65  4981.3  456.50  4990.2  453.86  4992.9  448.32  4993.9  447.52
  5001.9  447.52  5002.9  448.32  5014.0  455.01  5023.5  456.85  5059.4  455.84
  5149.6  460.03  5169.1  461.38  5239.3  467.12  5254.6  469.79  5260.5  469.45
  5291.2  473.79  5312.4  475.17  5342.5  478.97  5422.1  486.45  5472.2  489.03
#Mann=4,-1,0
  4539.5    0.16       0  4992.9    0.07       0  5002.9    0.16       0
  5169.1    0.05       0
Bank Sta=4811.3,5149.6
Exp/Cntr=0.3,0.1

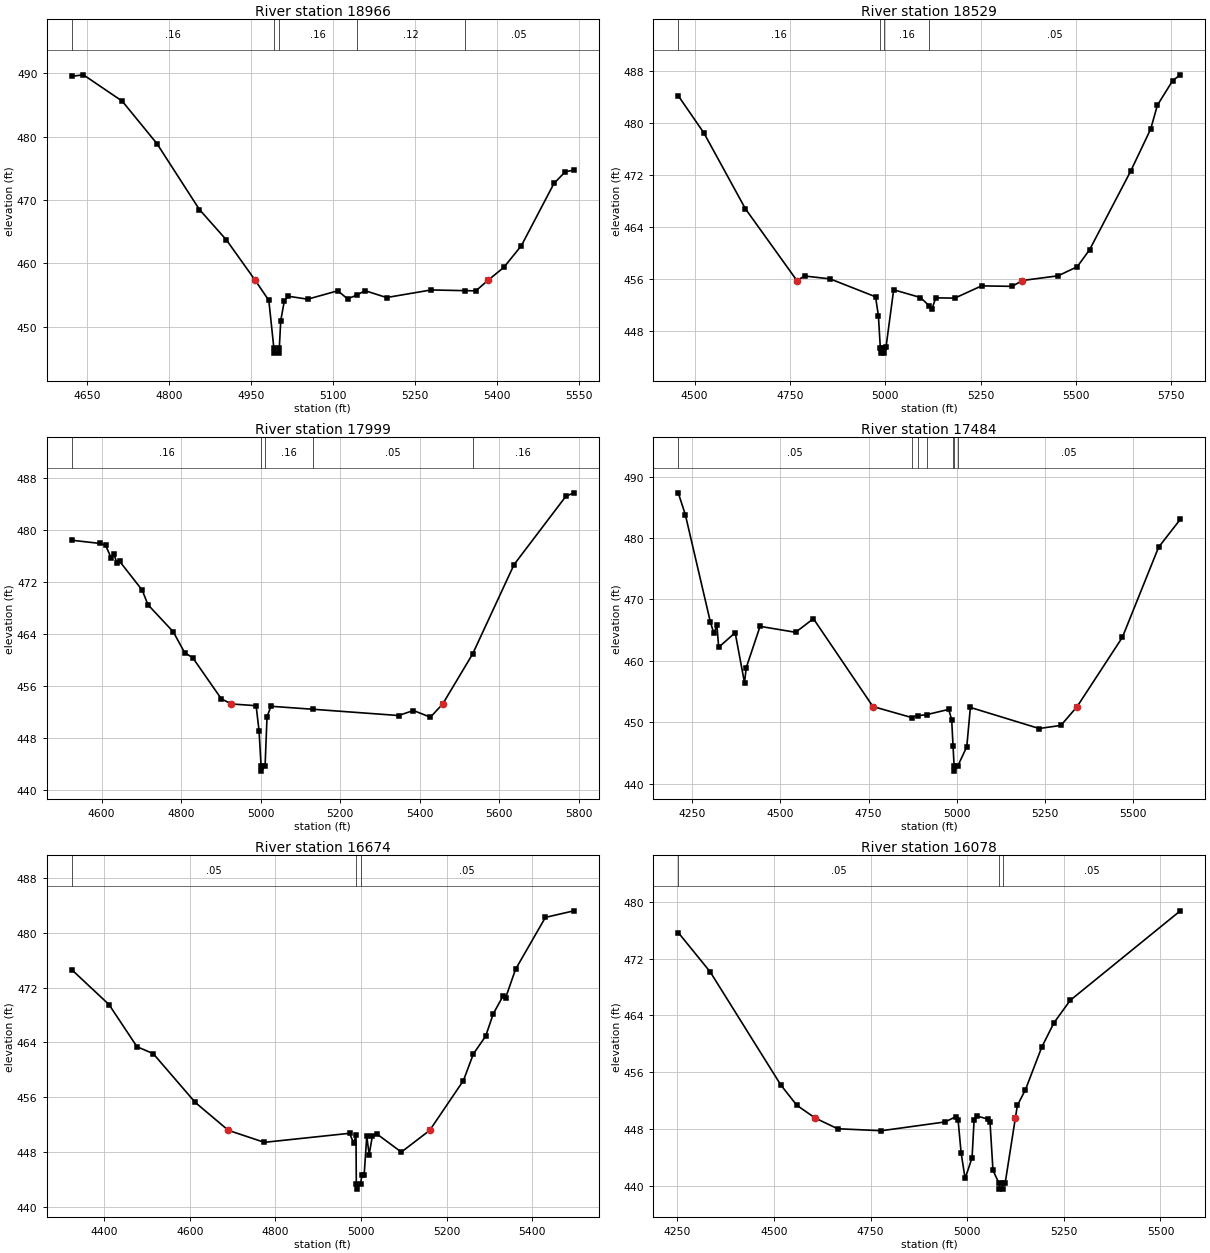
Type RM Length L Ch R = 1,18966,437,437,437
BEGIN DESCRIPTION:
GIDEON CREEK 24.0
END DESCRIPTION:
XS GIS Cut Line= 3
      2853024.98      7075224.98      2852683.92      7074923.82
      2852229.46      7075019.90
#Sta/Elev= 30
  4621.8  489.55  4643.1  489.79  4714.2  485.63  4777.8  478.92  4855.6  468.51
  4904.9  463.72  4957.8  457.33  4982.7  454.15  4991.9  446.63  4992.9  445.83
  5000.9  445.83  5001.9  446.63  5004.5  450.95  5011.2  454.13  5018.7  454.81
  5053.8  454.35  5109.1  455.68  5126.8  454.40  5143.9  455.00  5158.8  455.70
  5198.3  454.61  5280.1  455.81  5341.1  455.70  5361.9  455.67  5384.0  457.33
  5413.0  459.37  5445.1  462.79  5505.0  472.65  5525.4  474.46  5541.3  474.75
#Mann=5,-1,0
  4621.8    0.16       0  4991.9    0.07       0  5001.9    0.16       0
  5143.9    0.12       0  5341.1    0.05       0
Bank Sta=4957.8,5384
Exp/Cntr=0.3,0.1

Type RM Length L Ch R = 1,18529,530,530,530
BEGIN DESCRIPTION:
GIDEON CREEK 23.0
END DESCRIPTION:
XS GIS Cut Line= 3
      2853024.99      7075074.97      2852775.00      7074625.00
      2851975.01      7074575.00
#Sta/Elev= 30
  4457.1  484.19  4524.6  478.43  4633.2  466.77  4768.1  455.72  4788.8  456.41
  4855.2  455.97  4974.4  453.21  4981.9  450.28  4986.9  445.33  4987.9  444.53
  4995.9  444.53  4996.9  445.33  5001.9  445.48  5021.9  454.29  5092.1  453.10
  5115.2  451.81  5122.1  451.31  5132.2  453.04  5182.3  453.01  5252.4  454.89
  5332.6  454.82  5359.2  455.72  5452.8  456.44  5502.9  457.83  5535.4  460.44
  5643.2  472.56  5695.8  479.06  5713.3  482.73  5753.4  486.52  5773.4  487.41
#Mann=4,-1,0
  4457.1    0.16       0  4986.9    0.07       0  4996.9    0.16       0
  5115.2    0.05       0
Bank Sta=4768.1,5359.2
Exp/Cntr=0.3,0.1

Type RM Length L Ch R = 1,17999,515,515,515
BEGIN DESCRIPTION:
GIDEON CREEK 22.0
END DESCRIPTION:
XS GIS Cut Line= 3
      2853124.99      7074424.99      2852775.00      7074125.00
      2851975.03      7074175.00
#Sta/Elev= 30
  4524.8  478.43  4595.6  477.94  4609.8  477.66  4624.1  475.68  4630.7  476.36
  4638.4  474.86  4645.0  475.20  4702.0  470.75  4716.3  468.52  4780.0  464.35
  4808.5  461.16  4829.4  460.33  4900.7  454.06  4925.5  453.26  4988.3  452.99
  4995.8  449.12  5000.8  443.73  5001.7  442.93  5010.9  443.73  5015.8  451.30
  5025.8  452.90  5131.6  452.44  5346.5  451.48  5384.0  452.25  5426.6  451.22
  5457.6  453.26  5532.6  460.92  5637.0  474.69  5767.3  485.19  5787.3  485.72
#Mann=5,-1,0
  4524.8    0.16       0  5000.8    0.07       0  5010.9    0.16       0
  5131.6    0.05       0  5532.6    0.16       0
Bank Sta=4925.5,5457.6
Exp/Cntr=0.3,0.1

Type RM Length L Ch R = 1,17484,810,810,810
BEGIN DESCRIPTION:
GIDEON CREEK 21.0
END DESCRIPTION:
XS GIS Cut Line= 3
      2853424.97      7073625.00      2852675.00      7073725.00
      2852024.99      7073575.00
#Sta/Elev= 30
  4210.2  487.36  4230.3  483.81  4301.0  466.41  4311.1  464.49  4319.9  465.76
  4324.9  462.21  4371.6  464.59  4398.1  456.45  4403.1  458.90  4442.2  465.62
  4543.1  464.65  4593.5  466.87  4762.2  452.57  4871.7  450.78  4889.1  451.07
  4914.4  451.24  4977.1  452.10  4985.6  450.42  4989.5  446.06  4992.5  442.85
  4993.5  442.05  5002.6  442.85  5028.4  446.02  5038.6  452.42  5233.6  448.99
  5295.2  449.49  5341.5  452.57  5469.7  463.85  5572.3  478.50  5633.9  483.05
#Mann=7,-1,0
  4210.2    0.05       0  4871.7    0.07       0  4889.1    0.05       0
  4914.4    0.07       0  4989.5    0.05       0  4992.5    0.03       0
  5002.6    0.05       0
Bank Sta=4762.2,5341.5
Exp/Cntr=0.3,0.1

Type RM Length L Ch R = 1,16674,596,596,596
BEGIN DESCRIPTION:
GIDEON CREEK 20.0
END DESCRIPTION:
XS GIS Cut Line= 3
      2853124.95      7073125.01      2852475.00      7073325.00
      2852024.97      7073525.01
#Sta/Elev= 30
  4324.6  474.60  4411.5  469.52  4476.9  463.36  4514.8  462.35  4612.9  455.23
  4690.3  451.15  4774.4  449.40  4973.2  450.72  4983.0  449.30  4988.3  450.43
  4989.1  443.37  4990.0  442.57  4999.3  443.37  5002.0  444.61  5007.4  444.61
  5013.5  450.32  5019.0  447.61  5026.5  450.26  5036.8  450.64  5094.2  447.98
  5160.5  451.15  5239.2  458.42  5262.5  462.31  5291.2  464.91  5309.0  468.18
  5332.2  470.81  5337.7  470.48  5361.0  474.67  5430.7  482.24  5497.1  483.20
#Mann=3,-1,0
  4324.6    0.05       0  4989.1    0.03       0  4999.3    0.05       0
Bank Sta=4690.3,5160.5
Exp/Cntr=0.3,0.1

Type RM Length L Ch R = 1,16078,663,663,663
BEGIN DESCRIPTION:
GIDEON CREEK 19.0
END DESCRIPTION:
XS GIS Cut Line= 3
      2853175.02      7073075.01      2852375.00      7072875.00
      2851924.99      7073025.00
#Sta/Elev= 30
  4252.3  475.69  4334.8  470.16  4517.8  454.20  4559.0  451.35  4606.9  449.54
  4664.6  448.04  4778.0  447.76  4942.9  449.00  4971.3  449.76  4976.4  449.23
  4984.2  444.63  4994.5  441.03  5012.5  443.95  5017.7  449.22  5025.4  449.83
  5053.8  449.39  5058.9  449.00  5066.6  442.18  5082.4  440.33  5083.3  439.53
  5091.6  439.53  5092.6  440.33  5098.0  440.33  5124.5  449.54  5129.7  451.32
  5150.7  453.55  5192.9  459.55  5224.5  462.98  5266.7  466.15  5551.3  478.75
#Mann=3,-1,0
  4252.3    0.05       0  5082.4    0.03       0  5092.6    0.05       0
Bank Sta=4606.9,5124.5
Exp/Cntr=0.3,0.1

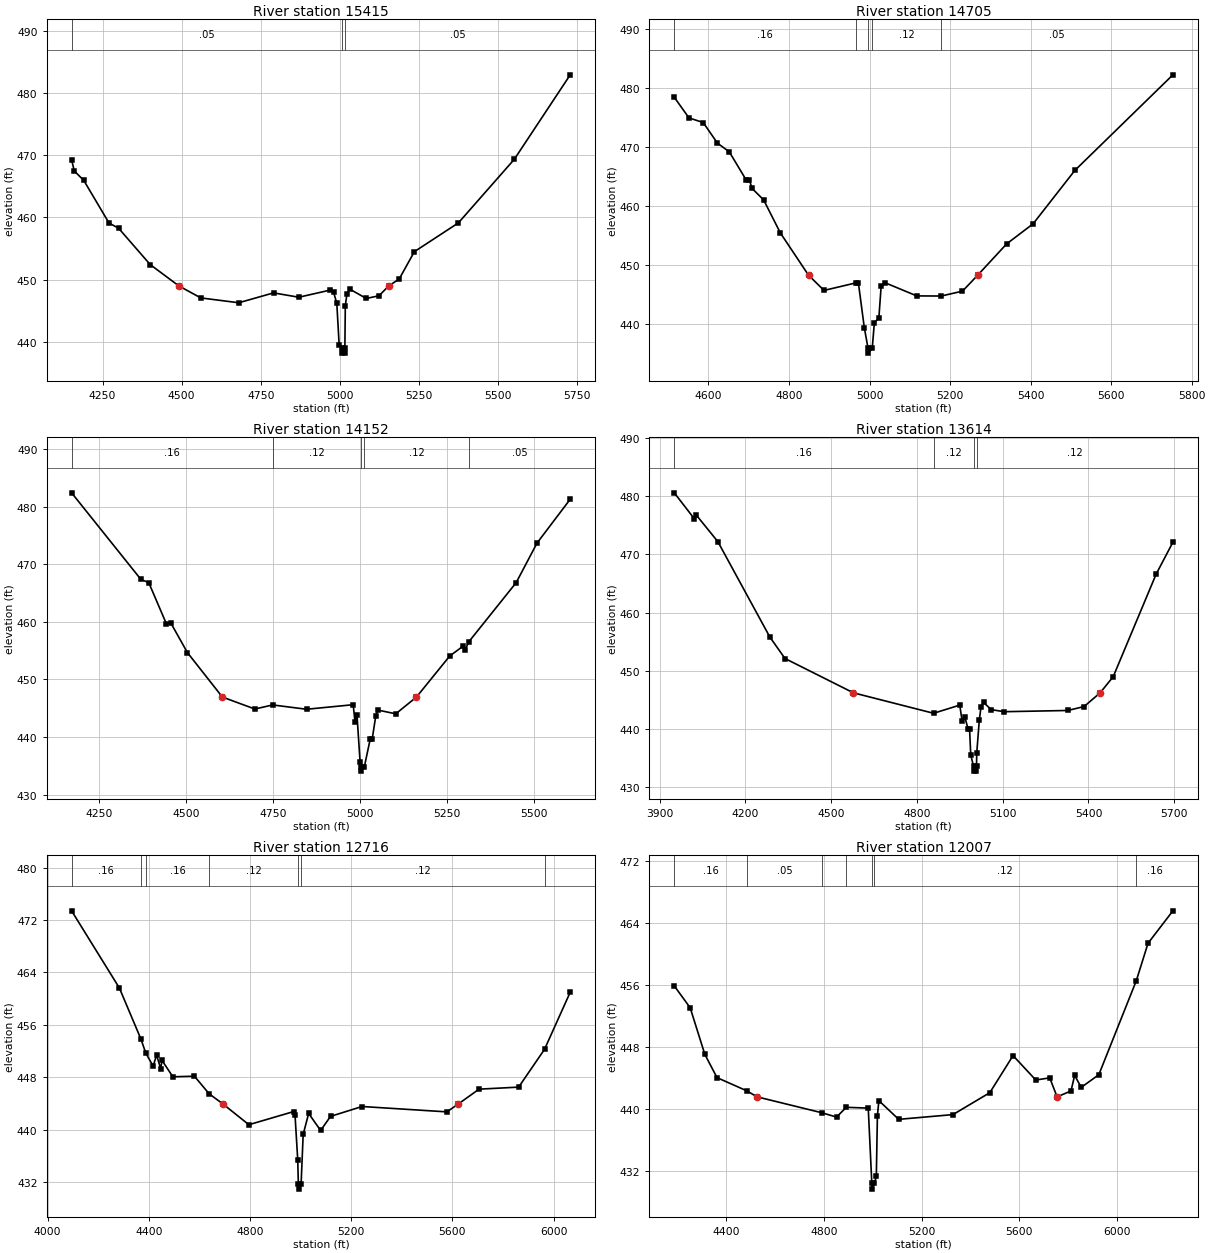
Type RM Length L Ch R = 1,15415,710,710,710
BEGIN DESCRIPTION:
GIDEON CREEK 18.0
END DESCRIPTION:
XS GIS Cut Line= 3
      2853173.44      7072418.54      2852325.00      7072425.00
      2851624.98      7072625.01
#Sta/Elev= 30
  4152.0  469.31  4160.4  467.49  4190.4  465.98  4270.4  459.10  4300.4  458.28
  4400.5  452.42  4490.6  449.00  4560.5  447.05  4680.5  446.27  4790.5  447.86
  4870.5  447.16  4970.5  448.32  4980.5  447.93  4990.5  446.18  4998.0  439.43
  5005.8  438.96  5006.7  438.16  5015.0  438.16  5016.0  438.96  5017.4  445.76
  5022.6  447.72  5031.7  448.46  5083.7  446.96  5124.0  447.40  5155.1  449.00
  5187.7  450.09  5235.8  454.50  5374.9  459.13  5551.7  469.37  5728.5  482.97
#Mann=3,-1,0
  4152.0    0.05       0  5005.8    0.03       0  5016.0    0.05       0
Bank Sta=4490.6,5155.1
Exp/Cntr=0.3,0.1

Type RM Length L Ch R = 1,14705,553,553,553
BEGIN DESCRIPTION:
GIDEON CREEK 17.0
END DESCRIPTION:
XS GIS Cut Line= 3
      2852625.03      7071724.98      2852225.00      7072025.00
      2851574.98      7072375.01
#Sta/Elev= 30
  4515.1  478.47  4551.6  474.97  4587.0  474.18  4622.4  470.68  4651.6  469.23
  4693.3  464.49  4701.6  464.52  4707.8  463.05  4737.0  461.07  4778.7  455.45
  4848.6  448.30  4887.0  445.72  4966.3  447.00  4972.4  446.97  4987.0  439.43
  4996.4  435.89  4997.4  435.09  5006.7  435.89  5012.0  440.25  5023.2  441.06
  5028.9  446.48  5037.9  447.04  5117.4  444.79  5178.1  444.77  5230.9  445.60
  5268.6  448.30  5340.4  453.60  5406.2  457.01  5510.0  466.07  5753.4  482.27
#Mann=5,-1,0
  4515.1    0.16       0  4966.3    0.12       0  4996.4    0.07       0
  5006.7    0.12       0  5178.1    0.05       0
Bank Sta=4848.6,5268.6
Exp/Cntr=0.3,0.1

Type RM Length L Ch R = 1,14152,538,538,538
BEGIN DESCRIPTION:
GIDEON CREEK 16.0
END DESCRIPTION:
XS GIS Cut Line= 3
      2852674.99      7071675.00      2851875.00      7071775.00
      2851575.01      7072324.98
#Sta/Elev= 30
  4171.6  482.39  4370.6  467.37  4393.3  466.80  4443.7  459.69  4456.3  459.84
  4504.2  454.67  4604.8  446.94  4698.2  444.86  4749.3  445.57  4846.8  444.82
  4980.7  445.61  4985.9  442.63  4991.6  443.85  5000.6  435.60  5002.6  434.88
  5003.5  434.08  5012.9  434.88  5029.6  439.63  5035.2  439.60  5045.7  443.71
  5051.4  444.68  5103.1  444.03  5162.5  446.94  5258.3  454.08  5296.3  455.76
  5302.0  455.07  5312.9  456.53  5449.1  466.81  5508.9  473.67  5604.3  481.28
#Mann=5,-1,0
  4171.6    0.16       0  4749.3    0.12       0  5002.6    0.07       0
  5012.9    0.12       0  5312.9    0.05       0
Bank Sta=4604.8,5162.5
Exp/Cntr=0.3,0.1

Type RM Length L Ch R = 1,13614,898,898,898
BEGIN DESCRIPTION:
GIDEON CREEK 15.0
END DESCRIPTION:
XS GIS Cut Line= 3
      2852521.35      7071030.87      2851570.86      7071434.51
      2851174.97      7072025.04
#Sta/Elev= 30
  3951.6  480.55  4022.2  476.07  4027.6  476.80  4104.0  472.17  4285.9  455.79
  4338.8  452.11  4578.1  446.22  4858.3  442.71  4949.9  444.11  4958.0  441.43
  4968.1  442.00  4979.3  439.95  4984.3  439.95  4988.3  435.58  4998.2  433.58
  4999.1  432.78  5007.5  432.78  5008.5  433.58  5009.3  435.89  5018.3  441.57
  5024.3  443.82  5033.0  444.57  5060.4  443.33  5105.2  442.98  5327.5  443.19
  5384.5  443.86  5440.8  446.22  5486.5  448.99  5636.6  466.59  5695.2  472.07
#Mann=4,-1,0
  3951.6    0.16       0  4858.3    0.12       0  4998.2    0.07       0
  5008.5    0.12       0
Bank Sta=4578.1,5440.8
Exp/Cntr=0.3,0.1

Type RM Length L Ch R = 1,12716,709,709,709
BEGIN DESCRIPTION:
GIDEON CREEK 14.0
END DESCRIPTION:
XS GIS Cut Line= 3
      2852138.06      7070592.35      2851238.02      7070942.36
      2850339.04      7071391.85
#Sta/Elev= 30
  4095.0  473.42  4283.9  461.63  4368.7  453.86  4387.9  451.73  4417.2  449.69
  4430.9  451.38  4447.1  449.33  4452.5  450.56  4495.3  448.07  4580.5  448.16
  4638.4  445.48  4693.1  443.92  4795.7  440.75  4972.1  442.75  4978.1  442.21
  4988.8  435.39  4991.2  431.71  4992.0  430.91  5002.1  431.71  5010.3  439.26
  5031.9  442.47  5079.3  439.87  5118.4  442.02  5243.0  443.53  5578.4  442.71
  5623.7  443.92  5705.4  446.18  5861.9  446.49  5964.3  452.27  6065.8  460.99
#Mann=7,-1,0
  4095.0    0.16       0  4368.7    0.12       0  4387.9    0.16       0
  4638.4    0.12       0  4991.2    0.07       0  5002.1    0.12       0
  5964.3    0.16       0
Bank Sta=4693.1,5623.7
Exp/Cntr=0.3,0.1

Type RM Length L Ch R = 1,12007,693,693,693
BEGIN DESCRIPTION:
GIDEON CREEK 13.0
END DESCRIPTION:
XS GIS Cut Line= 3
      2851950.16      7070359.96      2851125.00      7070375.00
      2850110.16      7071050.14
#Sta/Elev= 30
  4186.2  455.89  4251.4  453.07  4311.4  447.07  4361.4  444.06  4483.3  442.36
  4525.7  441.58  4792.3  439.52  4851.5  438.97  4891.4  440.23  4981.5  440.13
  4996.0  430.48  4996.8  429.68  5006.9  430.48  5014.5  431.31  5019.0  439.13
  5025.0  441.09  5106.2  438.68  5328.6  439.29  5479.9  442.12  5575.1  446.90
  5668.3  443.75  5725.4  444.03  5755.7  441.58  5812.6  442.34  5827.6  444.35
  5854.6  442.80  5926.8  444.44  6080.3  456.55  6128.5  461.39  6230.4  465.57
#Mann=7,-1,0
  4186.2    0.16       0  4483.3    0.05       0  4792.3    0.16       0
  4891.4    0.12       0  4996.0    0.07       0  5006.9    0.12       0
  6080.3    0.16       0
Bank Sta=4525.7,5755.7
Exp/Cntr=0.3,0.1