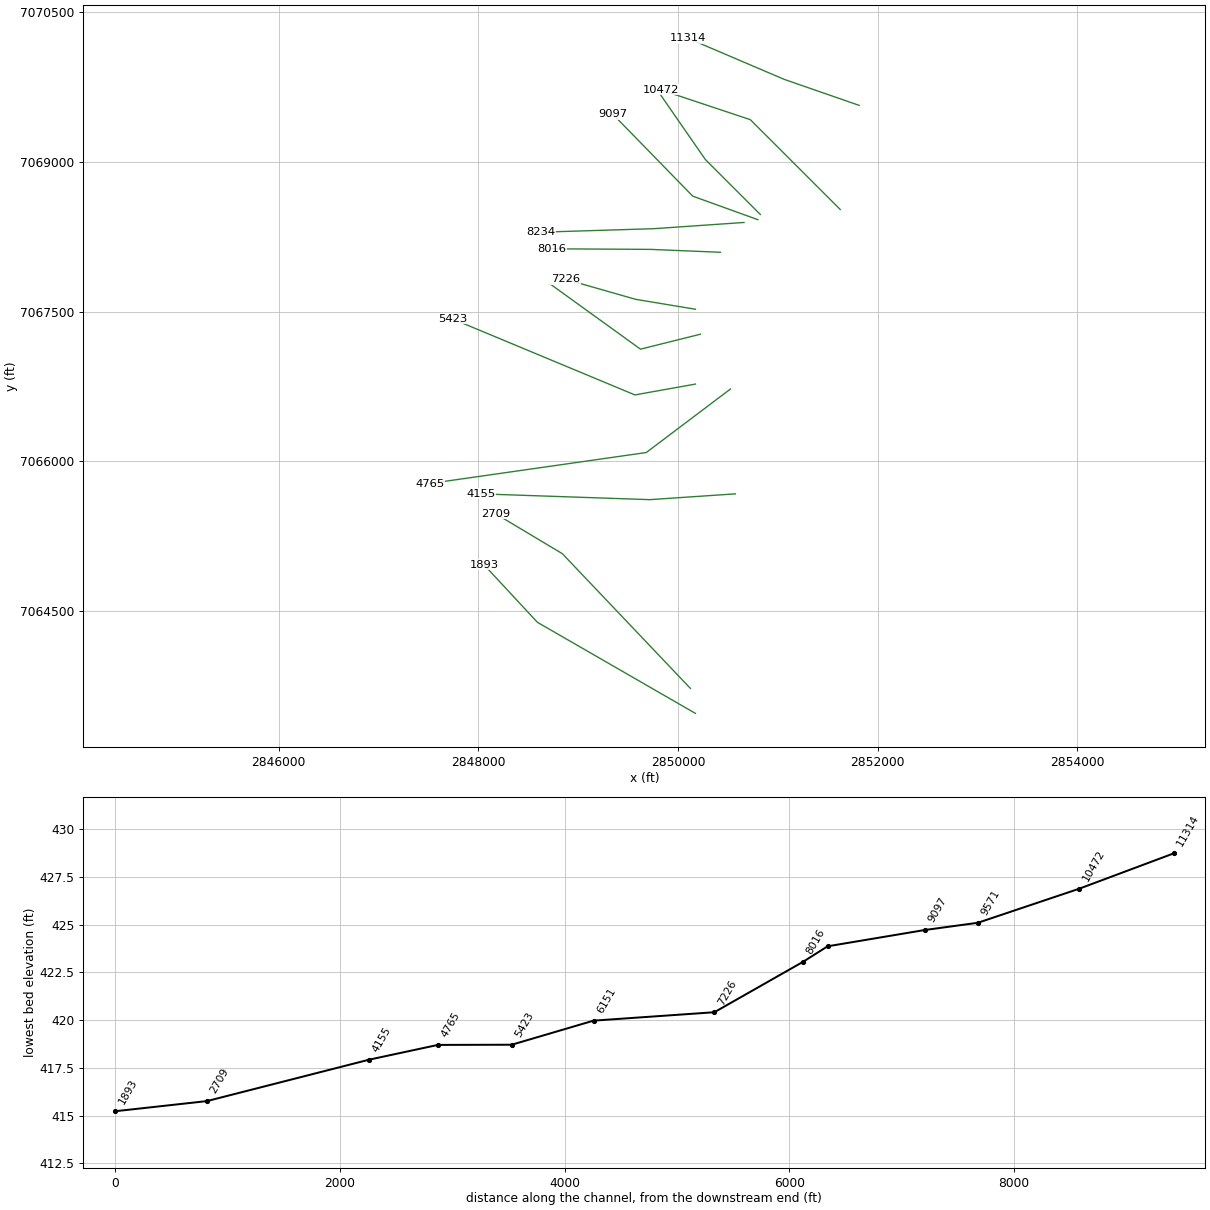
HEC-RAS study GIDEON CREEK.prj: GIDEON CREEK Base Level Engineering

--- GIDEON CREEK.g01 (geometry) --- (continued)

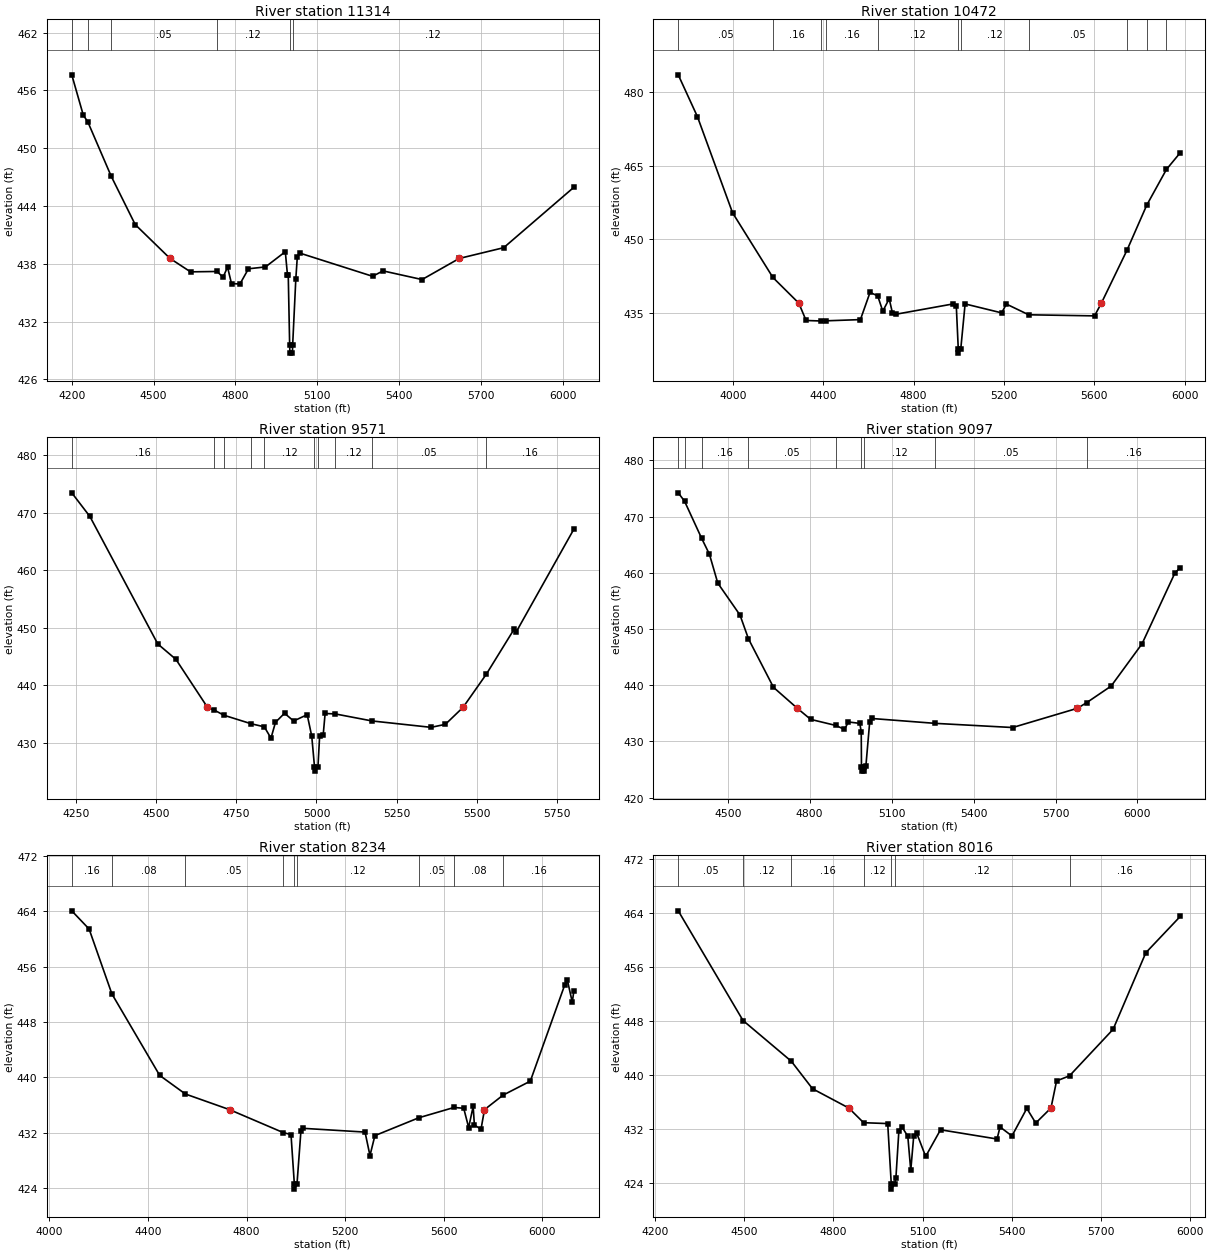
Type RM Length L Ch R = 1,11314,842,842,842
BEGIN DESCRIPTION:
GIDEON CREEK 12.0
END DESCRIPTION:
XS GIS Cut Line= 3
      2851814.83      7069568.28      2851064.79      7069828.71
      2850101.41      7070240.10
#Sta/Elev= 30
  4199.7  457.62  4241.9  453.44  4258.6  452.73  4344.5  447.08  4432.4  442.07
  4560.2  438.55  4635.3  437.16  4732.6  437.20  4754.5  436.60  4771.1  437.65
  4785.6  435.93  4816.7  435.91  4847.8  437.48  4910.1  437.67  4982.9  439.25
  4990.9  436.82  4993.7  436.82  4998.9  429.52  4999.7  428.72  5009.0  428.72
  5009.8  429.52  5021.5  436.45  5027.0  438.75  5036.9  439.10  5302.9  436.70
  5341.4  437.26  5484.5  436.36  5620.8  438.55  5784.0  439.67  6041.2  445.94
#Mann=6,-1,0
  4199.7    0.05       0  4258.6    0.16       0  4344.5    0.05       0
  4732.6    0.12       0  4998.9    0.07       0  5009.8    0.12       0
Bank Sta=4560.2,5620.8
Exp/Cntr=0.3,0.1

Type RM Length L Ch R = 1,10472,901,901,901
BEGIN DESCRIPTION:
GIDEON CREEK 11.0
END DESCRIPTION:
XS GIS Cut Line= 3
      2851625.02      7068524.98      2850725.00      7069425.00
      2849825.00      7069725.00
#Sta/Elev= 30
  3758.9  483.49  3843.8  474.98  3999.3  455.42  4177.8  442.26  4292.3  437.04
  4324.6  433.51  4390.0  433.41  4410.9  433.44  4565.0  433.69  4607.5  439.22
  4641.3  438.53  4664.0  435.41  4692.3  437.93  4706.4  435.10  4720.6  434.77
  4975.1  436.88  4989.3  436.39  4998.0  427.67  4998.8  426.87  5008.9  427.67
  5028.2  436.88  5189.8  435.06  5210.9  436.85  5309.6  434.67  5600.9  434.45
  5631.1  437.04  5744.3  447.79  5831.9  456.98  5919.1  464.25  5980.4  467.66
#Mann=11,-1,0
  3758.9    0.05       0  4177.8    0.16       0  4390.0    0.05       0
  4410.9    0.16       0  4641.3    0.12       0  4998.0    0.07       0
  5008.9    0.12       0  5309.6    0.05       0  5744.3    0.16       0
  5831.9    0.12       0  5919.1    0.16       0
Bank Sta=4292.3,5631.1
Exp/Cntr=0.3,0.1

Type RM Length L Ch R = 1,9571,474,474,474
BEGIN DESCRIPTION:
GIDEON CREEK 10.0
END DESCRIPTION:
XS GIS Cut Line= 3
      2850825.02      7068474.98      2850275.00      7069025.00
      2849825.00      7069674.99
#Sta/Elev= 30
  4235.6  473.46  4292.2  469.35  4504.3  447.19  4560.9  444.52  4659.5  436.18
  4679.7  435.73  4710.6  434.81  4795.6  433.33  4837.0  432.79  4857.9  430.82
  4872.0  433.58  4900.3  435.15  4928.6  433.80  4971.0  434.90  4985.2  431.18
  4993.8  425.89  4994.6  425.09  5004.7  425.89  5009.9  431.18  5020.9  431.32
  5027.0  435.11  5058.9  435.03  5173.6  433.81  5358.0  432.70  5402.6  433.22
  5458.0  436.18  5531.0  441.97  5617.5  449.77  5623.6  449.25  5804.0  467.14
#Mann=10,-1,0
  4235.6    0.16       0  4679.7    0.12       0  4710.6    0.05       0
  4795.6    0.07       0  4837.0    0.12       0  4993.8    0.07       0
  5004.7    0.12       0  5058.9    0.12       0  5173.6    0.05       0
  5531.0    0.16       0
Bank Sta=4659.5,5458
Exp/Cntr=0.3,0.1

Type RM Length L Ch R = 1,9097,863,863,863
BEGIN DESCRIPTION:
Mapping XS 1177fb03
END DESCRIPTION:
XS GIS Cut Line= 3
      2850800.90      7068422.46      2850148.12      7068658.57
      2849349.79      7069477.73
#Sta/Elev= 30
  4318.8  474.24  4341.8  472.76  4404.3  466.16  4432.9  463.32  4463.6  458.17
  4544.9  452.49  4576.0  448.24  4667.5  439.62  4754.8  435.89  4803.6  433.92
  4895.5  432.84  4927.4  432.14  4941.8  433.46  4983.4  433.21  4988.7  431.73
  4989.6  425.51  4990.3  424.71  4999.7  424.71  5000.5  425.51  5005.6  425.55
  5019.8  433.52  5026.8  434.08  5259.9  433.21  5543.0  432.47  5779.9  435.89
  5814.7  436.92  5903.6  439.85  6016.8  447.38  6137.1  459.98  6156.8  460.93
#Mann=9,-1,0
  4318.8    0.16       0  4341.8    0.05       0  4404.3    0.16       0
  4576.0    0.05       0  4895.5    0.12       0  4989.6    0.07       0
  5000.5    0.12       0  5259.9    0.05       0  5814.7    0.16       0
Bank Sta=4754.8,5779.9
Exp/Cntr=0.3,0.1

Type RM Length L Ch R = 1,8234,218,218,218
BEGIN DESCRIPTION:
GIDEON CREEK 9.0
END DESCRIPTION:
XS GIS Cut Line= 3
      2850662.05      7068394.69      2849752.29      7068332.18
      2848628.63      7068297.50
#Sta/Elev= 30
  4091.4  464.06  4161.7  461.43  4254.1  452.06  4447.9  440.29  4552.1  437.60
  4731.4  435.34  4948.7  432.03  4980.5  431.74  4993.9  424.66  4994.6  423.86
  5004.9  424.66  5020.6  432.21  5030.6  432.64  5280.7  432.10  5300.7  428.71
  5320.7  431.59  5498.9  434.17  5642.0  435.66  5680.9  435.54  5700.9  432.76
  5719.2  435.81  5724.2  433.12  5751.0  432.51  5765.1  435.34  5840.1  437.43
  5951.0  439.46  6091.1  453.41  6101.1  454.07  6121.1  450.87  6127.5  452.45
#Mann=9,-1,0
  4091.4    0.16       0  4254.1    0.08       0  4552.1    0.05       0
  4948.7    0.12       0  4993.9    0.07       0  5004.9    0.12       0
  5498.9    0.05       0  5642.0    0.08       0  5840.1    0.16       0
Bank Sta=4731.4,5765.1
Exp/Cntr=0.3,0.1

Type RM Length L Ch R = 1,8016,790,790,790
BEGIN DESCRIPTION:
GIDEON CREEK 8.0
END DESCRIPTION:
XS GIS Cut Line= 3
      2850425.93      7068096.07      2849725.00      7068125.00
      2848739.15      7068130.79
#Sta/Elev= 30
  4278.7  464.36  4496.4  448.08  4658.8  442.03  4730.0  437.95  4851.9  435.09
  4901.7  432.91  4982.7  432.78  4994.6  423.85  4995.3  423.05  5005.8  423.85
  5010.2  424.68  5020.2  431.68  5030.2  432.31  5050.2  430.90  5060.2  425.84
  5070.2  430.97  5080.2  431.36  5110.2  427.90  5160.2  431.86  5350.2  430.49
  5360.2  432.28  5400.2  430.94  5450.2  435.03  5480.2  432.86  5531.4  435.09
  5550.2  439.11  5593.7  439.87  5740.2  446.77  5850.2  458.14  5966.1  463.54
#Mann=7,-1,0
  4278.7    0.05       0  4496.4    0.12       0  4658.8    0.16       0
  4901.7    0.12       0  4994.6    0.07       0  5005.8    0.12       0
  5593.7    0.16       0
Bank Sta=4851.9,5531.4
Exp/Cntr=0.3,0.1

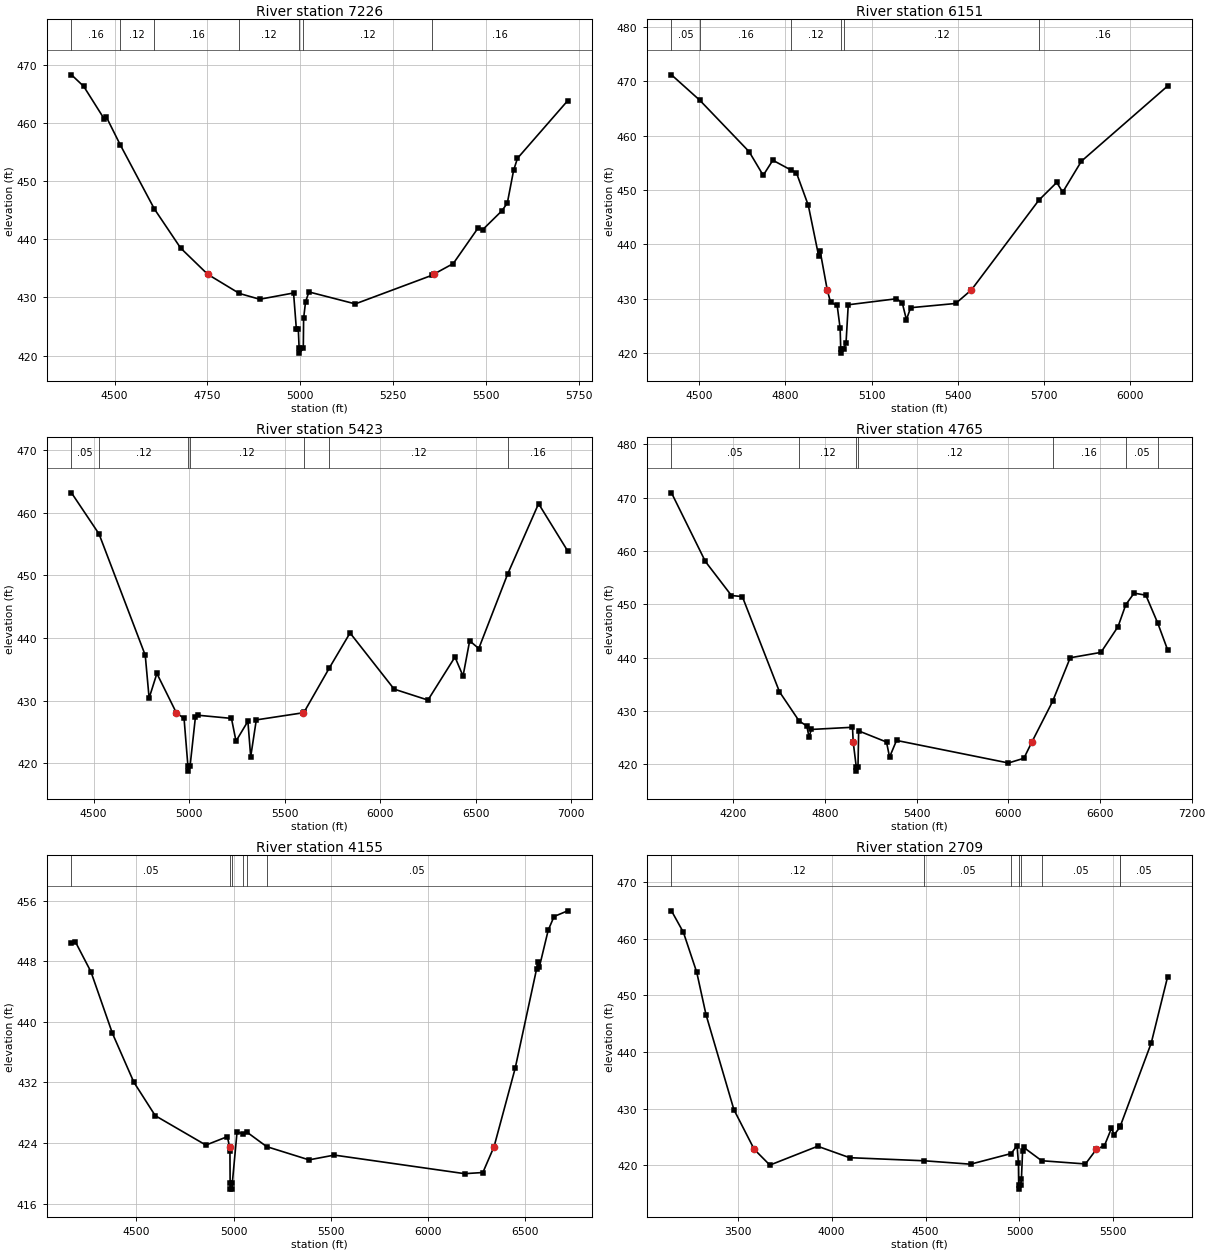
Type RM Length L Ch R = 1,7226,1075,1075,1075
BEGIN DESCRIPTION:
GIDEON CREEK 7.0
END DESCRIPTION:
XS GIS Cut Line= 3
      2850175.00      7067525.00      2849575.00      7067625.00
      2848874.99      7067825.00
#Sta/Elev= 30
  4384.1  468.35  4417.1  466.36  4472.8  460.70  4477.9  461.10  4515.4  456.30
  4607.3  445.25  4678.1  438.51  4750.8  434.00  4836.2  430.69  4891.0  429.69
  4982.2  430.77  4989.8  424.51  4995.0  424.51  4997.2  421.21  4997.9  420.41
  5008.4  421.21  5009.3  426.41  5014.5  429.25  5023.6  430.95  5148.4  428.89
  5354.6  433.81  5359.7  434.00  5412.3  435.84  5479.9  442.04  5491.6  441.68
  5543.6  444.95  5557.9  446.27  5574.8  451.90  5585.2  453.97  5720.4  463.89
#Mann=7,-1,0
  4384.1    0.16       0  4515.4    0.12       0  4607.3    0.16       0
  4836.2    0.12       0  4997.2    0.07       0  5008.4    0.12       0
  5354.6    0.16       0
Bank Sta=4750.8,5359.7
Exp/Cntr=0.3,0.1

Type RM Length L Ch R = 1,6151,728,728,728
BEGIN DESCRIPTION:
GIDEON CREEK 6.0
END DESCRIPTION:
XS GIS Cut Line= 3
      2850225.02      7067275.01      2849625.00      7067125.00
      2848724.98      7067775.02
#Sta/Elev= 30
  4402.9  471.19  4501.6  466.51  4673.5  457.04  4722.5  452.69  4756.0  455.47
  4820.6  453.63  4838.4  453.14  4879.7  447.15  4915.7  437.85  4920.9  438.73
  4945.6  431.61  4957.0  429.34  4980.2  428.74  4990.5  424.54  4992.6  420.77
  4993.3  419.97  5003.8  420.77  5011.1  421.90  5018.8  428.87  5185.8  429.97
  5206.7  429.28  5221.4  426.13  5236.1  428.33  5393.1  429.11  5447.9  431.61
  5683.0  448.13  5745.1  451.38  5766.0  449.60  5831.0  455.29  6131.6  469.14
#Mann=6,-1,0
  4402.9    0.05       0  4501.6    0.16       0  4820.6    0.12       0
  4992.6    0.07       0  5003.8    0.12       0  5683.0    0.16       0
Bank Sta=4945.6,5447.9
Exp/Cntr=0.3,0.1

Type RM Length L Ch R = 1,5423,658,658,658
BEGIN DESCRIPTION:
GIDEON CREEK 5.0
END DESCRIPTION:
XS GIS Cut Line= 3
      2850175.04      7066775.01      2849569.08      7066666.49
      2847739.98      7067428.80
#Sta/Elev= 30
  4384.4  463.20  4528.7  456.62  4770.5  437.24  4790.8  430.38  4831.4  434.32
  4933.4  428.03  4973.7  427.13  4993.9  419.51  4994.6  418.71  5005.1  419.51
  5033.3  427.40  5047.8  427.64  5221.8  427.14  5245.6  423.51  5307.8  426.68
  5322.5  421.00  5351.8  426.90  5595.2  428.03  5602.6  428.18  5734.8  435.24
  5842.5  440.80  6073.2  431.82  6250.3  430.07  6391.7  436.95  6433.9  433.91
  6468.6  439.54  6516.3  438.31  6666.8  450.17  6829.3  461.46  6981.6  453.91
#Mann=7,-1,0
  4384.4    0.05       0  4528.7    0.12       0  4993.9    0.07       0
  5005.1    0.12       0  5602.6    0.16       0  5734.8    0.12       0
  6666.8    0.16       0
Bank Sta=4933.4,5595.2
Exp/Cntr=0.3,0.1

Type RM Length L Ch R = 1,4765,610,610,610
BEGIN DESCRIPTION:
GIDEON CREEK 4.0
END DESCRIPTION:
XS GIS Cut Line= 3
      2850525.01      7066725.01      2849682.84      7066089.13
      2847513.71      7065778.75
#Sta/Elev= 30
  3796.1  470.92  4017.8  458.04  4188.5  451.65  4259.7  451.45  4502.8  433.58
  4631.0  428.12  4681.7  427.16  4696.3  425.07  4710.8  426.52  4980.5  426.93
  4985.2  424.11  5005.2  419.50  5005.9  418.70  5016.4  419.50  5020.9  426.25
  5203.0  424.16  5223.0  421.33  5268.6  424.46  6000.8  420.23  6101.8  421.11
  6153.2  424.11  6289.6  431.78  6404.9  439.97  6606.0  440.98  6718.0  445.82
  6768.2  449.91  6823.0  452.10  6899.9  451.71  6977.9  446.46  7042.6  441.43
#Mann=7,-1,0
  3796.1    0.05       0  4631.0    0.12       0  5005.2    0.07       0
  5016.4    0.12       0  6289.6    0.16       0  6768.2    0.05       0
  6977.9    0.16       0
Bank Sta=4985.2,6153.2
Exp/Cntr=0.3,0.1

Type RM Length L Ch R = 1,4155,1446,1446,1446
BEGIN DESCRIPTION:
GIDEON CREEK 3.0
END DESCRIPTION:
XS GIS Cut Line= 3
      2850575.02      7065675.00      2849717.56      7065616.91
      2848024.98      7065675.00
#Sta/Elev= 30
  4165.8  450.41  4185.9  450.55  4266.0  446.60  4376.3  438.49  4486.6  432.04
  4596.8  427.62  4857.4  423.74  4967.7  424.85  4979.0  423.54  4981.1  422.92
  4982.1  418.73  4982.7  417.93  4992.6  417.93  4993.3  418.73  5017.8  425.50
  5050.3  425.17  5070.6  425.41  5169.8  423.54  5388.0  421.79  5518.1  422.42
  6188.5  419.97  6282.5  420.12  6340.1  423.54  6448.6  433.86  6558.7  446.95
  6568.4  447.92  6573.4  447.26  6618.7  452.09  6648.7  453.89  6718.8  454.64
#Mann=6,-1,0
  4165.8    0.05       0  4982.1    0.03       0  4993.3    0.05       0
  5050.3    0.16       0  5070.6    0.12       0  5169.8    0.05       0
Bank Sta=4979,6340.1
Exp/Cntr=0.3,0.1

Type RM Length L Ch R = 1,2709,816,816,816
BEGIN DESCRIPTION:
double GIDEON CREEK 2.0
END DESCRIPTION:
XS GIS Cut Line= 3
      2850124.98      7063725.02      2848842.56      7065075.24
      2848174.98      7065475.01
#Sta/Elev= 30
  3148.3  464.96  3212.0  461.14  3282.8  454.09  3332.1  446.60  3480.6  429.80
  3588.5  422.80  3671.9  420.01  3926.3  423.34  4096.2  421.32  4493.9  420.77
  4739.8  420.17  4955.8  422.05  4987.3  423.44  4994.6  420.30  4995.8  416.56
  4996.5  415.76  5007.1  416.56  5010.5  417.59  5016.6  422.52  5022.4  423.14
  5118.1  420.78  5351.1  420.21  5409.3  422.80  5452.2  423.45  5489.1  426.48
  5504.7  425.40  5535.3  426.74  5537.0  426.94  5701.1  441.58  5788.6  453.34
#Mann=8,-1,0
  3148.3    0.12       0  4493.9    0.05       0  4955.8    0.12       0
  4995.8    0.07       0  5007.1    0.12       0  5118.1    0.05       0
  5535.3    0.16       0  5537.0    0.05       0
Bank Sta=3588.5,5409.3
Exp/Cntr=0.3,0.1

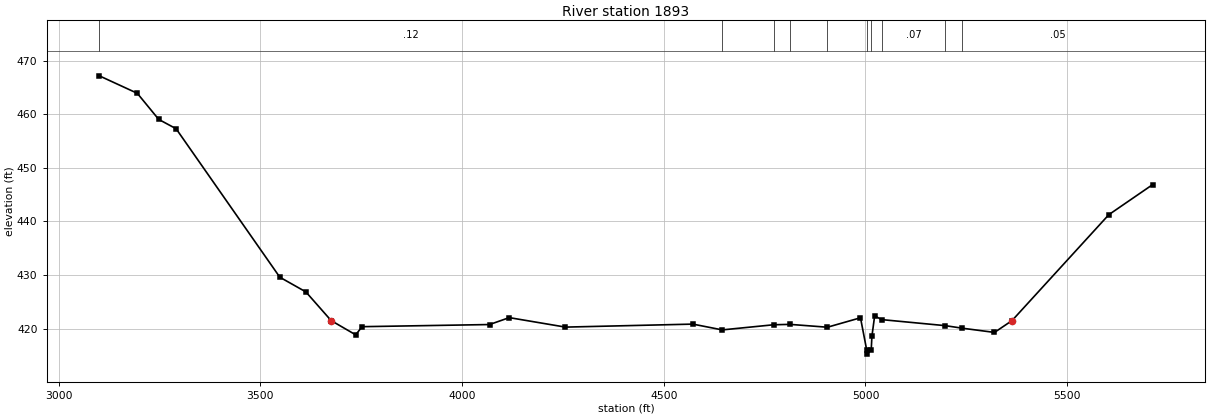
Type RM Length L Ch R = 1,1893,0,0,0
BEGIN DESCRIPTION:
double GIDEON CREEK 1.0
END DESCRIPTION:
XS GIS Cut Line= 3
      2850174.97      7063475.02      2848592.56      7064387.74
      2848058.93      7064962.96
#Sta/Elev= 30
  3100.7  467.15  3194.8  463.89  3247.9  459.02  3291.0  457.28  3548.1  429.58
  3612.7  426.84  3675.3  421.49  3736.2  418.83  3752.0  420.35  4068.0  420.75
  4116.9  422.04  4256.2  420.27  4572.1  420.83  4644.8  419.75  4772.6  420.71
  4812.7  420.78  4905.6  420.25  4987.6  422.01  5002.9  416.03  5003.6  415.23
  5014.2  416.03  5015.9  418.54  5022.7  422.37  5039.9  421.67  5198.1  420.54
  5239.6  420.07  5319.8  419.28  5363.3  421.49  5603.3  441.25  5712.1  446.87
#Mann=10,-1,0
  3100.7    0.12       0  4644.8    0.07       0  4772.6    0.12       0
  4812.7    0.07       0  4905.6    0.12       0  5002.9    0.07       0
  5014.2    0.12       0  5039.9    0.07       0  5198.1    0.12       0
  5239.6    0.05       0
Bank Sta=3675.3,5363.3
Exp/Cntr=0.3,0.1

Chan Stop Cuts=-1