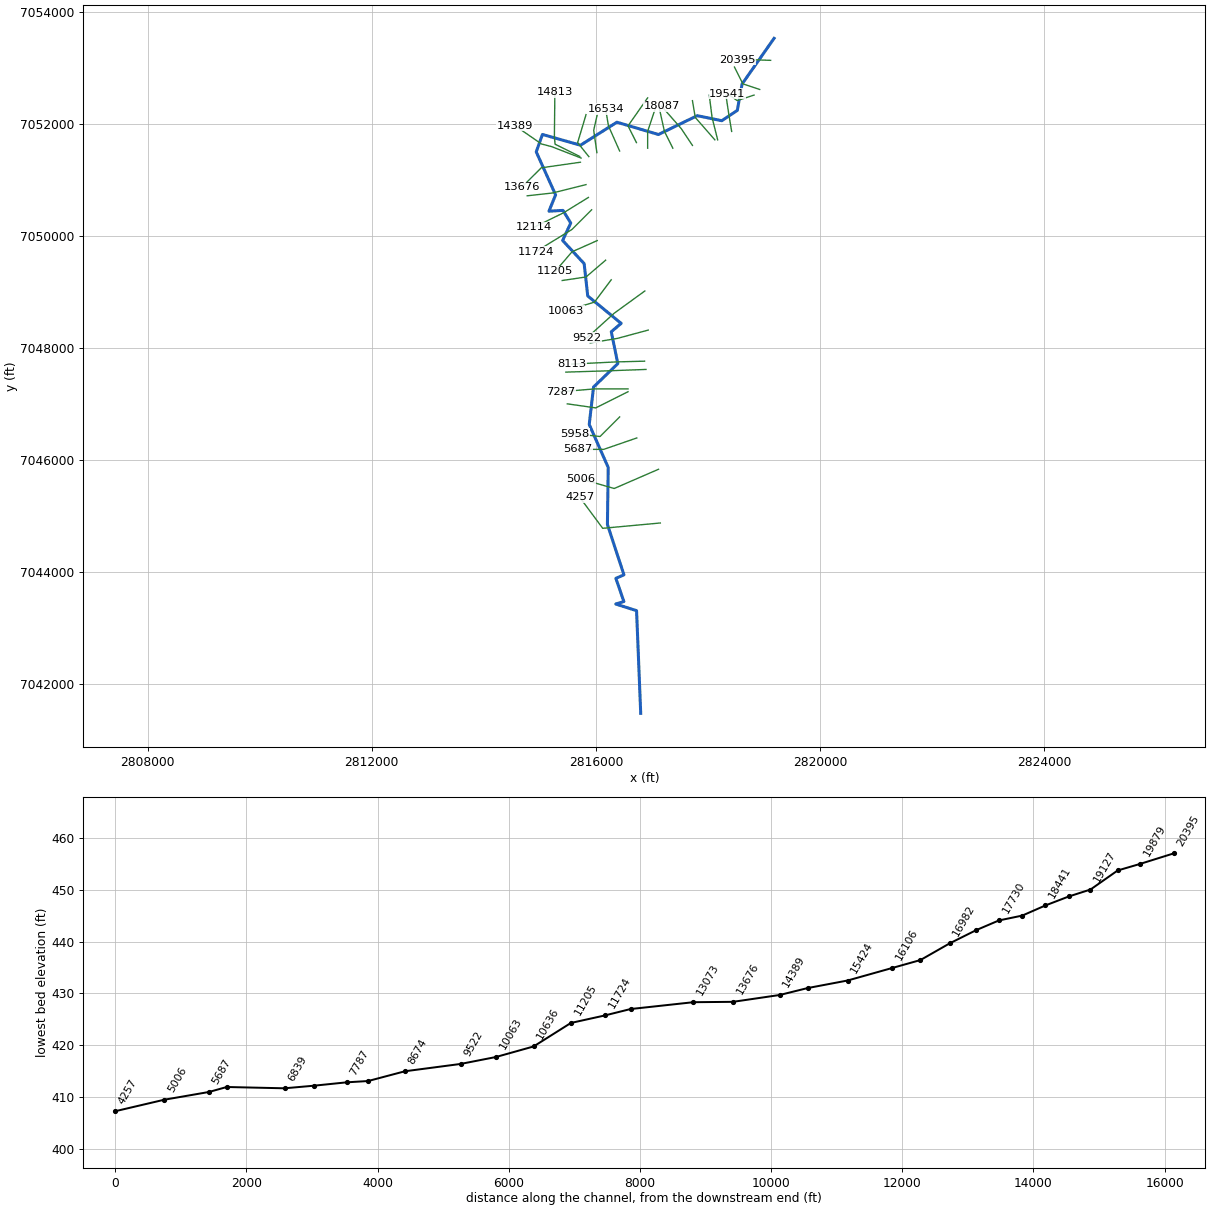
--- GORDON BRANCH.prj (project) ---

Proj Title=GORDON BRANCH Base Level Engineering
Current Plan=p01
Default Exp/Contr=0.3,0.1
English Units
Geom File=g01
Flow File=f01
Plan File=p01
BEGIN DESCRIPTION:
GORDON BRANCH
END DESCRIPTION:

--- GORDON BRANCH.p01 (plan) ---

Plan Title=Multiple Run
Short Identifier=Multiple
Geom File=g01
Flow File=f01
Subcritical Flow
K Sum by GR= 0
Std Step Tol= 0.01
Critical Tol= 0.01
Num of Std Step Trials= 20
Max Error Tol= 0.3
Flow Tol Ratio= 0.001
Split Flow NTrial= 30
Split Flow Tol= 0.02
Split Flow Ratio= 0.02
Log Output Level= 0
Friction Slope Method= 1
Unsteady Friction Slope Method= 2
Unsteady Bridges Friction Slope Method= 1
Parabolic Critical Depth
Global Vel Dist=  1 , 1 , 1
Global Log Level= 0
CheckData=True
Encroach Param= -1, 0, 0, 0
BEGIN DESCRIPTION:
Multiple Run
END DESCRIPTION:

--- GORDON BRANCH.f01 (steady flow) ---

Flow Title=Multiple
Number of Profiles=7
Profile Names=10-year,25-year,50-year,1pct_min,100-year,1pct_plu,500-year
River Rch & RM= GORDON BRANCH,Reach-1,20395
     312     401     470     274     547    1092     743
River Rch & RM= GORDON BRANCH,Reach-1,19127
     531     704     842     502    1001    1997    1414
River Rch & RM= GORDON BRANCH,Reach-1,14389
    1016    1390    1699    1029    2054    4098    3010
Boundary for River Rch & Prof#=GORDON BRANCH,Reach-1,1
Up Type=0
Dn Type=3
Dn Slope=0.005
Boundary for River Rch & Prof#=GORDON BRANCH,Reach-1,2
Up Type=0
Dn Type=3
Dn Slope=0.005
Boundary for River Rch & Prof#=GORDON BRANCH,Reach-1,3
Up Type=0
Dn Type=3
Dn Slope=0.005
Boundary for River Rch & Prof#=GORDON BRANCH,Reach-1,4
Up Type=0
Dn Type=3
Dn Slope=0.005
Boundary for River Rch & Prof#=GORDON BRANCH,Reach-1,5
Up Type=0
Dn Type=3
Dn Slope=0.005
Boundary for River Rch & Prof#=GORDON BRANCH,Reach-1,6
Up Type=0
Dn Type=3
Dn Slope=0.005
Boundary for River Rch & Prof#=GORDON BRANCH,Reach-1,7
Up Type=0
Dn Type=3
Dn Slope=0.005

--- GORDON BRANCH.g01 (geometry) ---

Geom Title=Existing Conditions

River Reach=GORDON BRANCH,Reach-1
Reach XY= 30
      2819181.81      7053538.17      2818611.39      7052723.02
      2818525.59      7052250.71      2818248.27      7052066.62
      2817810.78      7052156.43      2817117.97      7051819.91
      2816376.20      7052039.81      2815726.23      7051628.78
      2815046.63      7051820.94      2814936.00      7051509.96
      2815281.54      7050741.42      2815163.14      7050450.52
      2815413.43      7050464.05      2815552.14      7050239.28
      2815407.63      7049926.89      2815791.25      7049513.61
      2815855.33      7048935.60      2816452.40      7048445.81
      2816275.82      7048296.72      2816392.41      7047726.61
      2815959.42      7047309.18      2815882.03      7046640.16
      2816221.21      7045871.68      2816206.96      7044852.81
      2816501.94      7043953.65      2816358.01      7043890.95
      2816500.51      7043476.28      2816355.16      7043432.11
      2816727.08      7043313.83      2816801.33      7041478.66

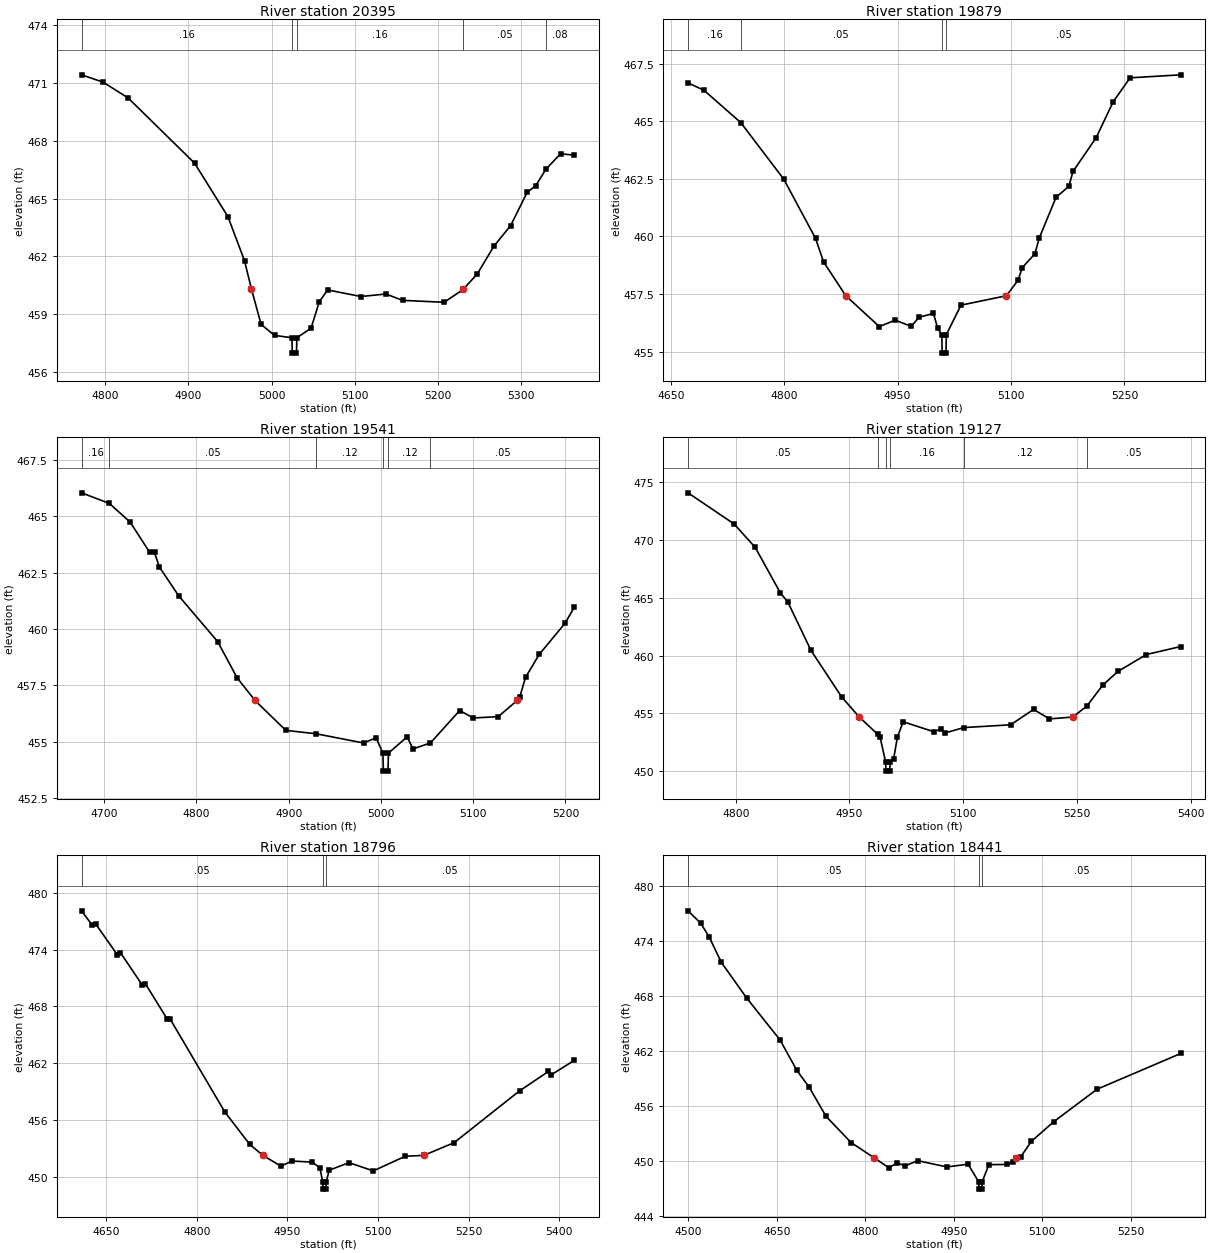
Type RM Length L Ch R = 1,20395,516,516,516
BEGIN DESCRIPTION:
GORDON BRANCH 24.0
END DESCRIPTION:
XS GIS Cut Line= 3
      2819120.92      7053144.94      2818887.72      7053152.46
      2818528.36      7053156.21
#Sta/Elev= 30
  4771.5  471.43  4797.4  471.05  4827.5  470.23  4907.5  466.84  4947.5  464.07
  4967.5  461.78  4975.9  460.30  4987.5  458.47  5003.7  457.90  5024.5  457.78
  5025.0  456.98  5030.0  456.98  5030.5  457.78  5047.5  458.27  5057.5  459.65
  5067.5  460.26  5107.6  459.92  5137.6  460.05  5157.6  459.72  5207.6  459.62
  5230.4  460.28  5230.8  460.30  5247.6  461.10  5267.6  462.54  5287.6  463.60
  5307.6  465.34  5317.6  465.66  5330.1  466.53  5347.6  467.33  5364.2  467.26
#Mann=5,-1,0
  4771.5    0.16       0  5024.5    0.07       0  5030.5    0.16       0
  5230.4    0.05       0  5330.1    0.08       0
Bank Sta=4975.9,5230.8
Exp/Cntr=0.3,0.1

Type RM Length L Ch R = 1,19879,338,338,338
BEGIN DESCRIPTION:
GORDON BRANCH 23.0
END DESCRIPTION:
XS GIS Cut Line= 3
      2818924.98      7052625.01      2818625.00      7052725.00
      2818475.01      7053024.98
#Sta/Elev= 30
  4672.9  466.66  4694.0  466.34  4742.6  464.94  4799.4  462.49  4841.5  459.92
  4852.1  458.90  4881.5  457.43  4925.9  456.09  4946.9  456.37  4968.0  456.10
  4978.6  456.50  4997.5  456.66  5003.1  456.01  5008.5  455.74  5009.0  454.94
  5014.0  454.94  5014.5  455.74  5033.8  457.02  5094.0  457.43  5109.3  458.10
  5114.9  458.65  5131.7  459.25  5137.2  459.92  5159.6  461.70  5176.4  462.17
  5182.0  462.82  5212.7  464.29  5235.1  465.84  5257.4  466.88  5324.5  467.01
#Mann=4,-1,0
  4672.9    0.16       0  4742.6    0.05       0  5008.5    0.03       0
  5014.5    0.05       0
Bank Sta=4881.5,5094
Exp/Cntr=0.3,0.1

Type RM Length L Ch R = 1,19541,414,414,414
BEGIN DESCRIPTION:
GORDON BRANCH 22.0
END DESCRIPTION:
XS GIS Cut Line= 3
      2818825.00      7052525.00      2818525.00      7052425.00
      2818346.69      7052550.37
#Sta/Elev= 30
  4675.4  466.05  4705.5  465.58  4728.1  464.75  4749.2  463.41  4754.5  463.40
  4759.7  462.76  4780.8  461.47  4823.0  459.44  4844.1  457.83  4863.4  456.83
  4896.8  455.50  4929.5  455.35  4981.1  454.94  4994.7  455.17  5002.1  454.49
  5002.6  453.69  5007.6  453.69  5008.1  454.49  5028.3  455.21  5034.8  454.68
  5053.6  454.94  5085.3  456.38  5100.1  456.05  5127.1  456.11  5147.8  456.83
  5150.5  456.99  5156.7  457.85  5171.5  458.87  5199.4  460.25  5209.6  460.97
#Mann=6,-1,0
  4675.4    0.16       0  4705.5    0.05       0  4929.5    0.12       0
  5002.1    0.07       0  5008.1    0.12       0  5053.6    0.05       0
Bank Sta=4863.4,5147.8
Exp/Cntr=0.3,0.1

Type RM Length L Ch R = 1,19127,331,331,331
BEGIN DESCRIPTION:
GORDON BRANCH 21.0
END DESCRIPTION:
XS GIS Cut Line= 3
      2818425.00      7051875.01      2818375.00      7052175.00
      2818323.60      7052516.93
#Sta/Elev= 30
  4737.1  474.05  4797.9  471.36  4825.8  469.33  4858.7  465.43  4868.9  464.60
  4899.3  460.44  4939.8  456.42  4963.0  454.69  4987.2  453.20  4990.5  452.93
  4997.7  450.82  4998.2  450.02  5003.2  450.02  5003.7  450.82  5008.3  451.07
  5013.3  452.98  5020.9  454.28  5061.4  453.42  5070.7  453.67  5075.7  453.31
  5100.8  453.78  5162.6  454.02  5192.9  455.35  5213.8  454.53  5244.6  454.69
  5263.2  455.64  5283.9  457.43  5304.1  458.63  5341.7  460.09  5387.0  460.78
#Mann=6,-1,0
  4737.1    0.05       0  4987.2    0.16       0  4997.7    0.07       0
  5003.7    0.16       0  5100.8    0.12       0  5263.2    0.05       0
Bank Sta=4963,5244.6
Exp/Cntr=0.3,0.1

Type RM Length L Ch R = 1,18796,355,355,355
BEGIN DESCRIPTION:
GORDON BRANCH 20.0
END DESCRIPTION:
XS GIS Cut Line= 3
      2818175.00      7051725.02      2818075.00      7052125.00
      2818025.00      7052524.99
#Sta/Elev= 30
  4609.3  478.12  4627.3  476.57  4632.5  476.75  4668.6  473.46  4673.7  473.69
  4709.8  470.27  4714.9  470.41  4751.0  466.67  4756.2  466.64  4846.4  456.84
  4887.6  453.41  4909.5  452.25  4939.1  451.11  4957.2  451.65  4990.7  451.54
  5003.6  450.95  5008.3  449.48  5008.8  448.68  5013.8  448.68  5014.3  449.48
  5019.0  450.68  5051.8  451.48  5092.1  450.61  5145.0  452.16  5175.6  452.25
  5225.7  453.59  5334.0  459.07  5381.9  461.13  5386.9  460.79  5424.7  462.30
#Mann=3,-1,0
  4609.3    0.05       0  5008.3    0.03       0  5014.3    0.05       0
Bank Sta=4909.5,5175.6
Exp/Cntr=0.3,0.1

Type RM Length L Ch R = 1,18441,354,354,354
BEGIN DESCRIPTION:
GORDON BRANCH 19.0
END DESCRIPTION:
XS GIS Cut Line= 3
      2818125.00      7051725.00      2817775.00      7052125.00
      2817724.99      7052425.05
#Sta/Elev= 30
  4499.3  477.30  4520.7  475.96  4534.9  474.49  4555.8  471.68  4598.5  467.82
  4655.4  463.22  4683.9  459.90  4704.8  458.07  4733.3  454.90  4776.0  452.03
  4814.7  450.39  4839.6  449.30  4853.8  449.79  4868.0  449.52  4888.9  450.06
  4938.3  449.38  4974.3  449.68  4992.2  447.76  4992.7  446.96  4997.7  446.96
  4998.2  447.76  5009.5  449.63  5041.0  449.65  5051.1  449.90  5056.3  450.39
  5063.8  450.50  5081.5  452.16  5119.5  454.31  5193.0  457.85  5335.0  461.75
#Mann=3,-1,0
  4499.3    0.05       0  4992.2    0.03       0  4998.2    0.05       0
Bank Sta=4814.7,5056.3
Exp/Cntr=0.3,0.1

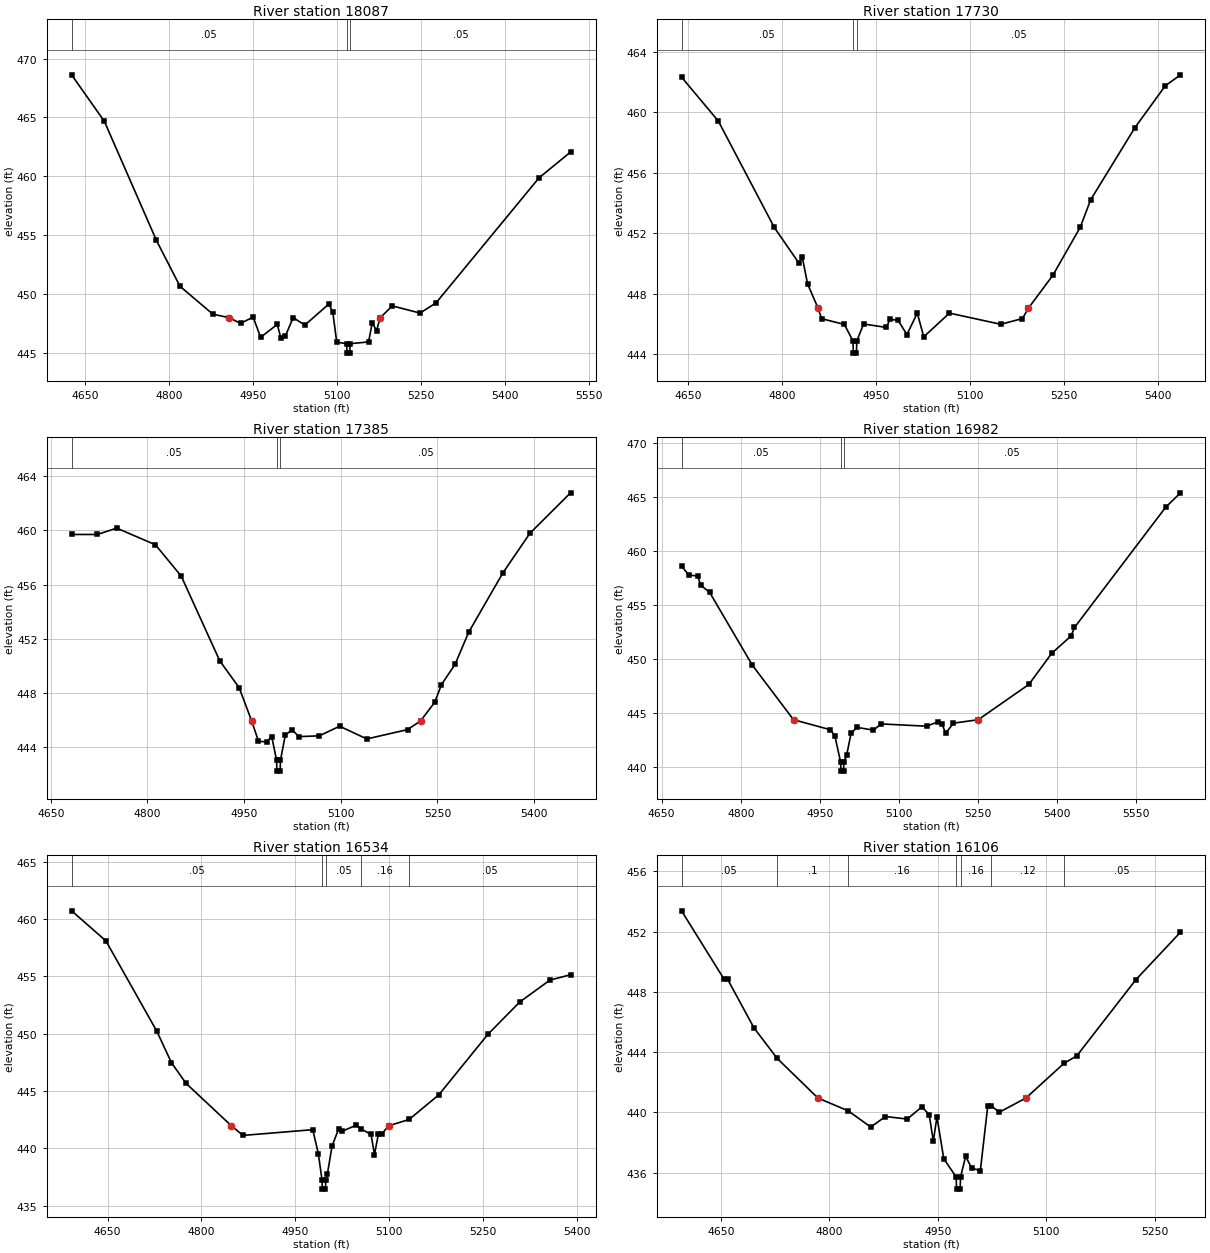
Type RM Length L Ch R = 1,18087,357,357,357
BEGIN DESCRIPTION:
GORDON BRANCH 18.0
END DESCRIPTION:
XS GIS Cut Line= 3
      2817725.01      7051624.99      2817525.00      7051925.00
      2817174.99      7052325.02
#Sta/Elev= 30
  4625.6  468.62  4684.2  464.67  4777.3  454.56  4819.4  450.67  4878.0  448.31
  4907.8  448.00  4927.6  447.52  4950.1  448.06  4963.6  446.34  4993.3  447.44
  4999.9  446.25  5007.5  446.43  5021.8  448.01  5042.6  447.38  5085.4  449.16
  5092.5  448.51  5099.6  445.93  5117.5  445.80  5118.0  445.00  5123.0  445.00
  5123.5  445.80  5156.5  445.95  5163.2  447.57  5170.8  446.92  5177.4  448.00
  5198.8  449.01  5248.6  448.40  5277.1  449.26  5461.2  459.87  5517.7  462.07
#Mann=3,-1,0
  4625.6    0.05       0  5117.5    0.03       0  5123.5    0.05       0
Bank Sta=4907.8,5177.4
Exp/Cntr=0.3,0.1

Type RM Length L Ch R = 1,17730,345,345,345
BEGIN DESCRIPTION:
GORDON BRANCH 17.0
END DESCRIPTION:
XS GIS Cut Line= 3
      2817374.98      7051575.04      2817225.00      7051875.00
      2817125.01      7052324.96
#Sta/Elev= 30
  4639.1  462.34  4697.8  459.43  4787.2  452.38  4826.3  450.03  4831.9  450.40
  4840.3  448.64  4857.1  447.03  4862.7  446.34  4899.0  445.96  4912.8  444.86
  4913.3  444.06  4918.3  444.06  4918.8  444.86  4929.7  445.99  4966.1  445.76
  4971.7  446.30  4984.7  446.23  4998.8  445.29  5015.4  446.71  5025.7  445.14
  5066.7  446.71  5148.6  445.97  5183.2  446.35  5192.6  447.03  5231.8  449.22
  5275.4  452.39  5292.0  454.21  5362.5  458.98  5411.1  461.76  5435.4  462.49
#Mann=3,-1,0
  4639.1    0.05       0  4912.8    0.03       0  4918.8    0.05       0
Bank Sta=4857.1,5192.6
Exp/Cntr=0.3,0.1

Type RM Length L Ch R = 1,17385,403,403,403
BEGIN DESCRIPTION:
GORDON BRANCH 16.0
END DESCRIPTION:
XS GIS Cut Line= 3
      2816925.00      7051575.03      2816925.00      7051875.00
      2817074.99      7052324.98
#Sta/Elev= 30
  4682.3  459.70  4722.3  459.70  4752.3  460.17  4812.3  458.94  4852.3  456.63
  4912.3  450.35  4942.3  448.37  4961.7  445.91  4972.3  444.41  4984.9  444.36
  4992.8  444.76  5000.4  443.00  5000.9  442.20  5005.9  442.20  5006.4  443.00
  5013.9  444.86  5024.4  445.26  5035.0  444.75  5066.6  444.81  5098.2  445.52
  5140.4  444.58  5203.6  445.27  5223.8  445.91  5245.8  447.29  5256.3  448.60
  5277.4  450.10  5298.5  452.47  5351.2  456.83  5393.4  459.78  5456.6  462.78
#Mann=3,-1,0
  4682.3    0.05       0  5000.4    0.03       0  5006.4    0.05       0
Bank Sta=4961.7,5223.8
Exp/Cntr=0.3,0.1

Type RM Length L Ch R = 1,16982,448,448,448
BEGIN DESCRIPTION:
GORDON BRANCH 15.0
END DESCRIPTION:
XS GIS Cut Line= 3
      2816724.99      7051675.01      2816575.00      7051975.00
      2816924.99      7052474.98
#Sta/Elev= 30
  4687.8  458.60  4701.8  457.77  4718.5  457.69  4724.1  456.83  4740.9  456.19
  4822.0  449.45  4900.1  444.41  4970.1  443.48  4978.5  442.91  4989.5  440.46
  4990.0  439.66  4995.0  439.66  4995.5  440.46  5000.8  441.13  5009.2  443.17
  5020.4  443.70  5051.5  443.45  5066.4  444.02  5152.7  443.81  5173.6  444.21
  5181.9  443.98  5188.4  443.15  5203.2  444.09  5250.2  444.41  5346.2  447.67
  5389.4  450.54  5426.0  452.14  5432.6  452.93  5605.2  464.02  5633.5  465.37
#Mann=3,-1,0
  4687.8    0.05       0  4989.5    0.03       0  4995.5    0.05       0
Bank Sta=4900.1,5250.2
Exp/Cntr=0.3,0.1

Type RM Length L Ch R = 1,16534,428,428,428
BEGIN DESCRIPTION:
GORDON BRANCH 14.0
END DESCRIPTION:
XS GIS Cut Line= 3
      2816424.99      7051525.01      2816225.00      7051975.00
      2816174.99      7052275.03
#Sta/Elev= 30
  4592.7  460.73  4647.4  458.11  4728.8  450.21  4752.0  447.48  4775.3  445.67
  4847.8  441.96  4866.3  441.12  4977.7  441.62  4986.6  439.53  4992.5  437.23
  4993.0  436.43  4998.0  436.43  4998.5  437.23  5001.0  437.73  5008.5  440.19
  5018.8  441.66  5024.3  441.48  5047.5  442.02  5055.5  441.67  5070.8  441.20
  5076.2  439.44  5082.4  441.22  5087.7  441.22  5098.7  441.96  5131.5  442.51
  5178.9  444.66  5257.5  449.96  5308.2  452.77  5356.3  454.68  5389.3  455.15
#Mann=5,-1,0
  4592.7    0.05       0  4992.5    0.03       0  4998.5    0.05       0
  5055.5    0.16       0  5131.5    0.05       0
Bank Sta=4847.8,5098.7
Exp/Cntr=0.3,0.1

Type RM Length L Ch R = 1,16106,682,682,682
BEGIN DESCRIPTION:
GORDON BRANCH 13.0
END DESCRIPTION:
XS GIS Cut Line= 3
      2816018.70      7051495.84      2815962.23      7051896.48
      2816025.00      7052174.99
#Sta/Elev= 30
  4595.4  453.38  4653.9  448.87  4659.0  448.85  4695.5  445.62  4727.6  443.59
  4784.0  440.96  4826.1  440.10  4857.1  439.03  4877.5  439.73  4907.6  439.56
  4927.8  440.37  4937.9  439.86  4943.7  438.10  4948.7  439.71  4958.1  436.93
  4975.3  435.71  4975.8  434.91  4980.8  434.91  4981.3  435.71  4988.4  437.09
  4996.7  436.30  5008.7  436.14  5019.0  440.44  5023.6  440.45  5034.8  440.01
  5071.9  440.96  5124.4  443.26  5142.0  443.75  5224.0  448.82  5285.5  451.96
#Mann=7,-1,0
  4595.4    0.05       0  4727.6     0.1       0  4826.1    0.16       0
  4975.3    0.07       0  4981.3    0.16       0  5023.6    0.12       0
  5124.4    0.05       0
Bank Sta=4784,5071.9
Exp/Cntr=0.3,0.1

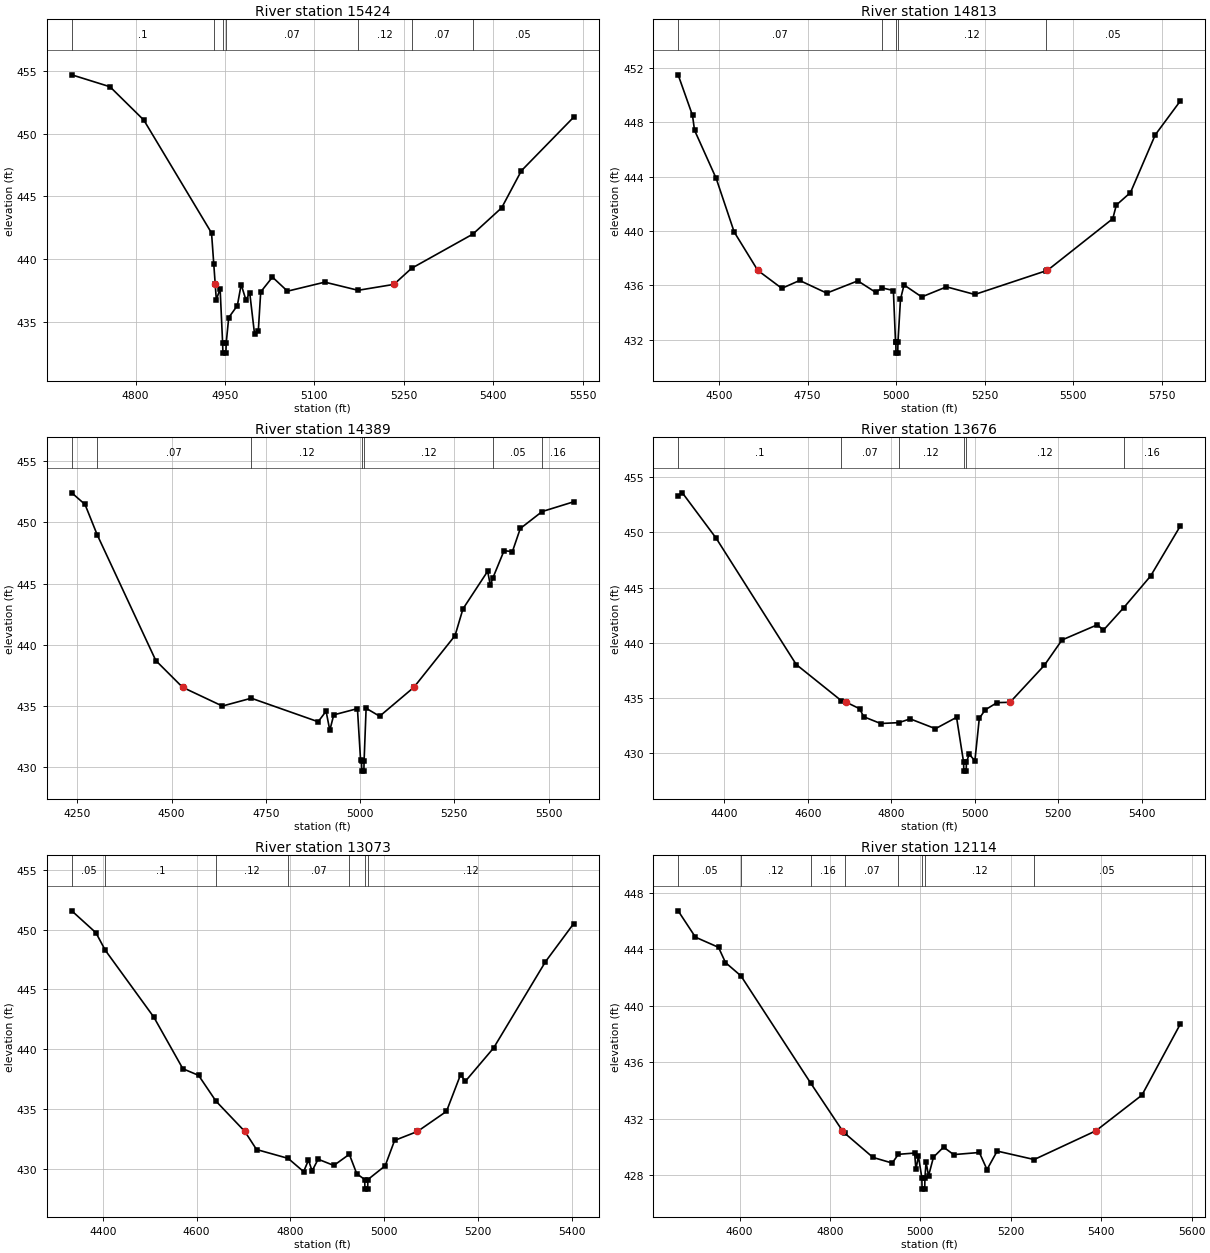
Type RM Length L Ch R = 1,15424,611,611,611
BEGIN DESCRIPTION:
GORDON BRANCH 12.0
END DESCRIPTION:
XS GIS Cut Line= 3
      2815875.01      7051424.98      2815675.00      7051675.00
      2815825.00      7052175.01
#Sta/Elev= 30
  4692.9  454.68  4757.0  453.73  4813.8  451.07  4927.4  442.07  4931.2  439.56
  4933.6  437.97  4935.4  436.75  4941.8  437.62  4946.0  433.29  4946.5  432.49
  4951.5  432.49  4952.0  433.29  4956.2  435.32  4970.7  436.28  4977.1  437.96
  4985.1  436.73  4991.5  437.29  4999.5  434.03  5005.9  434.29  5009.9  437.37
  5029.6  438.55  5054.8  437.43  5117.5  438.15  5173.3  437.50  5233.3  437.97
  5262.9  439.25  5365.8  441.98  5414.2  444.08  5447.2  447.03  5535.1  451.31
#Mann=7,-1,0
  4692.9     0.1       0  4931.2    0.07       0  4946.0    0.07       0
  4952.0    0.07       0  5173.3    0.12       0  5262.9    0.07       0
  5365.8    0.05       0
Bank Sta=4933.6,5233.3
Exp/Cntr=0.3,0.1

Type RM Length L Ch R = 1,14813,424,424,424
BEGIN DESCRIPTION:
Mapping XS 41329464
END DESCRIPTION:
XS GIS Cut Line= 4
      2815711.35      7051429.43      2815272.97      7051646.45
      2815259.94      7051772.31      2815268.63      7052575.27
#Sta/Elev= 30
  4383.9  451.48  4424.5  448.50  4430.2  447.41  4491.4  443.87  4542.3  439.93
  4609.0  437.11  4676.9  435.79  4727.3  436.37  4803.8  435.44  4891.7  436.34
  4942.0  435.50  4960.9  435.82  4992.2  435.63  4998.2  431.88  4999.1  431.83
  4999.6  431.03  5004.6  431.03  5005.1  431.83  5012.3  434.99  5022.3  436.04
  5072.3  435.16  5142.3  435.90  5222.3  435.34  5423.7  437.08  5427.5  437.11
  5612.3  440.91  5622.3  441.91  5662.3  442.83  5732.3  447.07  5802.6  449.54
#Mann=5,-1,0
  4383.9    0.07       0  4960.9    0.12       0  4999.1    0.07       0
  5005.1    0.12       0  5423.7    0.05       0
Bank Sta=4609,5427.5
Exp/Cntr=0.3,0.1

Type RM Length L Ch R = 1,14389,713,713,713
BEGIN DESCRIPTION:
Mapping XS f54b3306
END DESCRIPTION:
XS GIS Cut Line= 4
      2815737.36      7051399.06      2815212.20      7051603.04
      2815029.91      7051650.79      2814552.91      7051980.35
#Sta/Elev= 30
  4235.3  452.41  4270.5  451.46  4302.7  448.99  4458.3  438.72  4529.3  436.54
  4634.8  435.01  4711.5  435.65  4888.8  433.73  4909.9  434.59  4919.8  433.03
  4930.2  434.29  4993.1  434.80  5001.3  430.64  5004.0  430.50  5004.5  429.70
  5010.2  429.70  5010.7  430.50  5016.1  434.83  5052.0  434.18  5142.8  436.54
  5252.0  440.76  5273.0  442.94  5338.5  446.01  5345.6  444.87  5351.9  445.43
  5382.0  447.69  5404.1  447.61  5425.1  449.50  5482.9  450.88  5566.9  451.68
#Mann=7,-1,0
  4235.3     0.1       0  4302.7    0.07       0  4711.5    0.12       0
  5004.0    0.07       0  5010.7    0.12       0  5351.9    0.05       0
  5482.9    0.16       0
Bank Sta=4529.3,5142.8
Exp/Cntr=0.3,0.1

Type RM Length L Ch R = 1,13676,603,603,603
BEGIN DESCRIPTION:
GORDON BRANCH 11.0
END DESCRIPTION:
XS GIS Cut Line= 3
      2815725.00      7051325.00      2815025.00      7051225.00
      2814674.99      7050874.99
#Sta/Elev= 30
  4289.7  453.31  4299.8  453.57  4380.6  449.47  4572.5  438.03  4680.7  434.75
  4692.6  434.61  4724.1  434.03  4734.2  433.30  4774.6  432.69  4818.4  432.77
  4845.3  433.11  4905.9  432.22  4956.4  433.25  4973.3  429.18  4973.8  428.38
  4979.5  428.38  4980.0  429.18  4986.7  429.92  5000.3  429.31  5010.9  433.16
  5025.1  433.93  5053.4  434.58  5084.5  434.61  5166.5  437.95  5208.9  440.25
  5293.8  441.63  5307.9  441.13  5357.1  443.19  5421.1  446.04  5491.8  450.54
#Mann=6,-1,0
  4289.7     0.1       0  4680.7    0.07       0  4818.4    0.12       0
  4973.3    0.07       0  4980.0    0.12       0  5357.1    0.16       0
Bank Sta=4692.6,5084.5
Exp/Cntr=0.3,0.1

Type RM Length L Ch R = 1,13073,959,959,959
BEGIN DESCRIPTION:
GORDON BRANCH 10.0
END DESCRIPTION:
XS GIS Cut Line= 3
      2815824.99      7050925.00      2815225.00      7050775.00
      2814775.02      7050725.00
#Sta/Elev= 30
  4333.6  451.57  4385.1  449.74  4405.2  448.27  4508.8  442.68  4570.7  438.37
  4604.2  437.82  4641.2  435.67  4702.9  433.13  4727.9  431.62  4795.3  430.88
  4828.4  429.77  4838.7  430.74  4846.4  429.83  4859.3  430.81  4892.8  430.29
  4925.9  431.22  4941.7  429.60  4958.7  429.11  4959.2  428.31  4965.0  428.31
  4965.5  429.11  5002.4  430.26  5022.5  432.38  5071.3  433.13  5133.2  434.81
  5163.3  437.88  5173.4  437.32  5233.8  440.11  5344.5  447.32  5404.8  450.51
#Mann=7,-1,0
  4333.6    0.05       0  4405.2     0.1       0  4641.2    0.12       0
  4795.3    0.07       0  4925.9    0.12       0  4958.7    0.07       0
  4965.5    0.12       0
Bank Sta=4702.9,5071.3
Exp/Cntr=0.3,0.1

Type RM Length L Ch R = 1,12114,390,390,390
BEGIN DESCRIPTION:
Mapping XS 5fc4114c
END DESCRIPTION:
XS GIS Cut Line= 3
      2815867.59      7050695.93      2815424.88      7050422.49
      2814895.39      7050162.09
#Sta/Elev= 30
  4464.2  446.74  4502.5  444.87  4553.5  444.15  4568.9  443.07  4603.2  442.12
  4757.7  434.50  4827.7  431.13  4832.7  430.96  4895.2  429.24  4937.7  428.84
  4951.3  429.46  4987.3  429.55  4990.1  428.39  4995.7  429.32  5003.3  427.79
  5003.8  426.99  5009.6  426.99  5010.1  427.79  5012.6  428.92  5018.1  427.93
  5029.0  429.26  5051.3  429.97  5073.6  429.44  5130.5  429.59  5147.4  428.38
  5169.9  429.69  5251.8  429.09  5388.3  431.13  5490.1  433.66  5574.6  438.68
#Mann=8,-1,0
  4464.2    0.05       0  4603.2    0.12       0  4757.7    0.16       0
  4832.7    0.07       0  4951.3    0.12       0  5003.3    0.07       0
  5010.1    0.12       0  5251.8    0.05       0
Bank Sta=4827.7,5388.3
Exp/Cntr=0.3,0.1

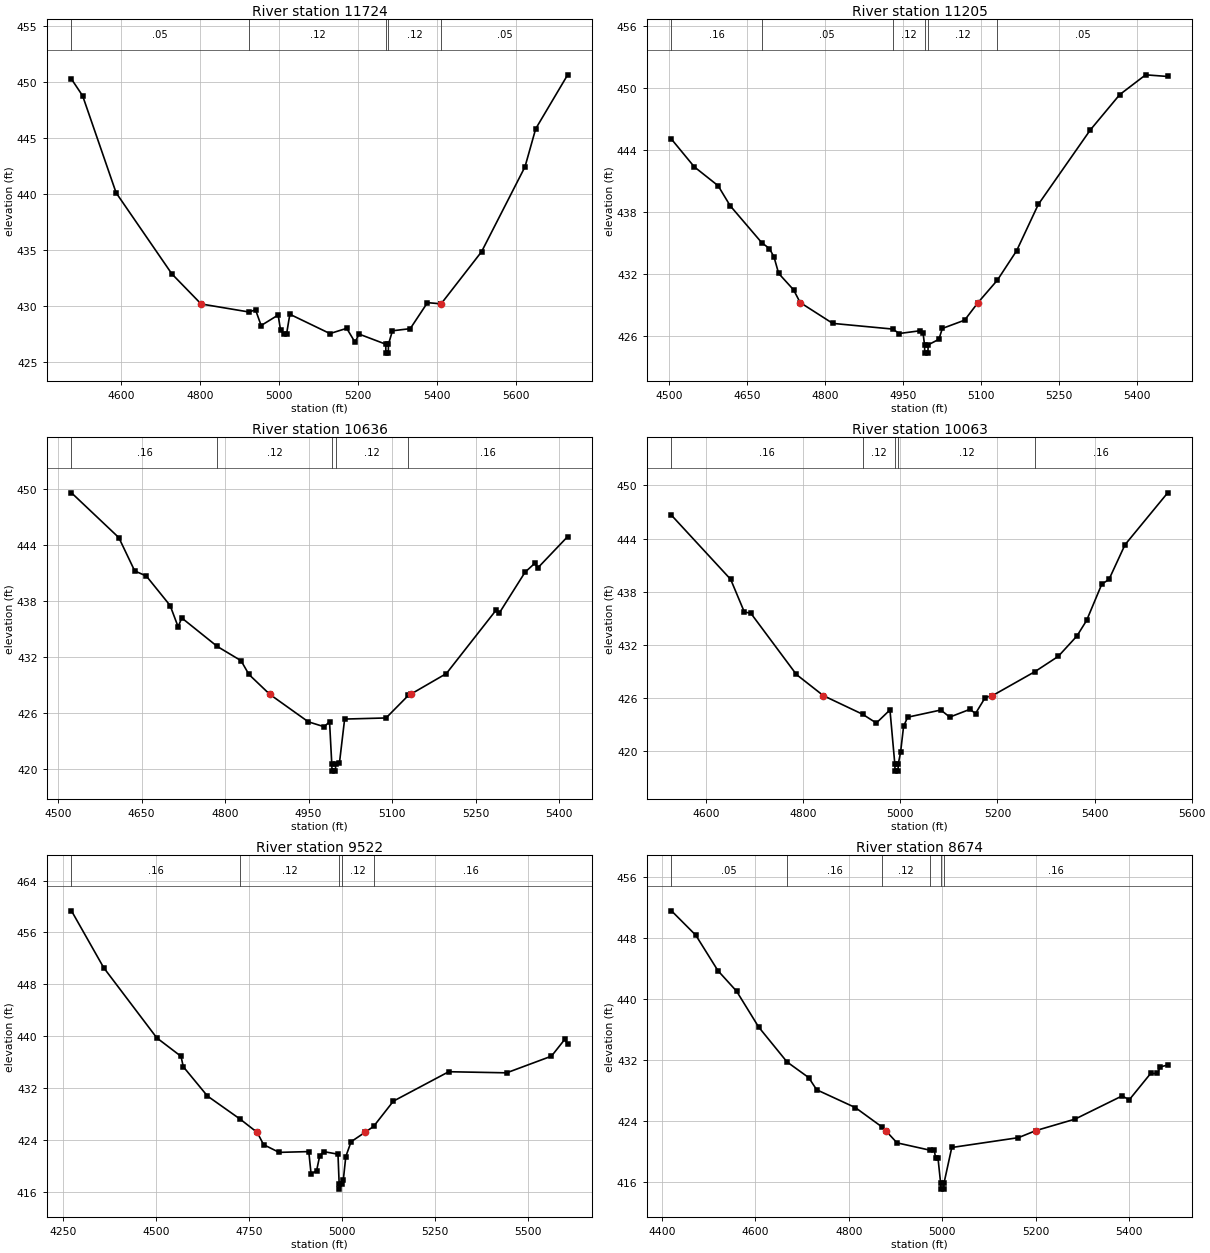
Type RM Length L Ch R = 1,11724,519,519,519
BEGIN DESCRIPTION:
GORDON BRANCH 9.0
END DESCRIPTION:
XS GIS Cut Line= 3
      2815925.04      7050475.04      2815575.00      7050125.00
      2814925.04      7049725.02
#Sta/Elev= 30
  4473.4  450.29  4501.7  448.79  4586.6  440.11  4728.0  432.85  4802.1  430.16
  4923.8  429.44  4940.1  429.64  4954.3  428.23  4997.4  429.17  5003.7  427.79
  5012.8  427.48  5018.7  427.45  5027.1  429.24  5128.8  427.51  5171.3  427.98
  5192.6  426.72  5202.2  427.47  5270.2  426.56  5270.7  425.76  5276.7  425.76
  5277.2  426.56  5287.3  427.76  5332.4  427.95  5376.1  430.28  5410.6  430.17
  5410.8  430.18  5513.3  434.84  5623.4  442.44  5650.5  445.84  5731.6  450.67
#Mann=5,-1,0
  4473.4    0.05       0  4923.8    0.12       0  5270.2    0.07       0
  5277.2    0.12       0  5410.8    0.05       0
Bank Sta=4802.1,5410.6
Exp/Cntr=0.3,0.1

Type RM Length L Ch R = 1,11205,569,569,569
BEGIN DESCRIPTION:
GORDON BRANCH 8.0
END DESCRIPTION:
XS GIS Cut Line= 3
      2816024.99      7049924.99      2815575.00      7049725.00
      2815275.00      7049375.00
#Sta/Elev= 30
  4505.3  445.03  4549.1  442.35  4594.9  440.52  4618.1  438.58  4678.8  435.00
  4693.4  434.44  4702.3  433.62  4711.2  432.03  4739.9  430.44  4752.5  429.21
  4815.1  427.19  4930.2  426.64  4943.0  426.21  4983.4  426.48  4988.8  426.22
  4991.5  425.11  4992.0  424.31  4998.0  424.31  4998.5  425.11  5019.1  425.65
  5025.7  426.70  5068.5  427.50  5094.4  429.21  5131.5  431.38  5168.4  434.22
  5210.1  438.71  5310.0  445.92  5366.5  449.34  5416.4  451.26  5458.7  451.10
#Mann=6,-1,0
  4505.3    0.16       0  4678.8    0.05       0  4930.2    0.12       0
  4991.5    0.07       0  4998.5    0.12       0  5131.5    0.05       0
Bank Sta=4752.5,5094.4
Exp/Cntr=0.3,0.1

Type RM Length L Ch R = 1,10636,573,573,573
BEGIN DESCRIPTION:
GORDON BRANCH 7.0
END DESCRIPTION:
XS GIS Cut Line= 3
      2816174.98      7049574.98      2815825.00      7049275.00
      2815399.44      7049211.64
#Sta/Elev= 30
  4524.2  449.56  4609.2  444.77  4637.8  441.20  4658.6  440.66  4701.4  437.50
  4715.7  435.23  4722.3  436.17  4786.1  433.12  4828.7  431.60  4843.0  430.12
  4880.3  428.00  4949.5  425.06  4978.0  424.53  4987.7  425.06  4991.7  420.58
  4992.2  419.78  4998.3  419.78  4998.8  420.58  5005.4  420.61  5014.8  425.35
  5089.2  425.47  5129.5  427.90  5133.2  428.00  5197.5  430.22  5287.1  437.03
  5292.1  436.65  5339.0  441.08  5356.4  442.02  5361.5  441.51  5415.4  444.88
#Mann=5,-1,0
  4524.2    0.16       0  4786.1    0.12       0  4991.7    0.07       0
  4998.8    0.12       0  5129.5    0.16       0
Bank Sta=4880.3,5133.2
Exp/Cntr=0.3,0.1

Type RM Length L Ch R = 1,10063,541,541,541
BEGIN DESCRIPTION:
GORDON BRANCH 6.0
END DESCRIPTION:
XS GIS Cut Line= 3
      2816275.00      7049225.00      2815975.00      7048825.00
      2815475.01      7048675.00
#Sta/Elev= 30
  4528.6  446.64  4650.5  439.40  4678.6  435.72  4692.1  435.57  4785.9  428.66
  4841.5  426.27  4922.3  424.17  4950.5  423.18  4978.6  424.66  4988.6  418.55
  4989.1  417.75  4995.2  417.75  4995.7  418.55  5000.5  419.90  5006.7  422.82
  5015.1  423.84  5083.4  424.65  5101.7  423.85  5143.4  424.73  5154.8  424.25
  5174.8  426.06  5189.6  426.27  5277.1  428.98  5325.3  430.71  5363.6  433.00
  5383.6  434.76  5414.9  438.86  5429.7  439.39  5462.7  443.31  5550.6  449.17
#Mann=5,-1,0
  4528.6    0.16       0  4922.3    0.12       0  4988.6    0.07       0
  4995.7    0.12       0  5277.1    0.16       0
Bank Sta=4841.5,5189.6
Exp/Cntr=0.3,0.1

Type RM Length L Ch R = 1,9522,848,848,848
BEGIN DESCRIPTION:
GORDON BRANCH 5.0
END DESCRIPTION:
XS GIS Cut Line= 3
      2816874.97      7049024.98      2816325.00      7048625.00
      2815841.57      7048187.27
#Sta/Elev= 30
  4273.2  459.34  4359.7  450.57  4502.3  439.74  4567.2  436.90  4573.4  435.29
  4638.3  430.77  4726.7  427.18  4771.8  425.16  4789.0  423.27  4830.7  422.08
  4910.3  422.20  4916.5  418.75  4931.2  419.24  4939.7  421.55  4950.1  422.20
  4988.7  421.80  4991.9  417.21  4992.4  416.41  4999.1  417.21  5002.9  417.76
  5009.7  421.43  5023.9  423.72  5061.0  425.16  5084.3  426.08  5137.4  429.98
  5286.1  434.52  5441.5  434.35  5561.8  436.92  5597.7  439.52  5605.4  438.73
#Mann=5,-1,0
  4273.2    0.16       0  4726.7    0.12       0  4991.9    0.07       0
  4999.1    0.12       0  5084.3    0.16       0
Bank Sta=4771.8,5061
Exp/Cntr=0.3,0.1

Type RM Length L Ch R = 1,8674,561,561,561
BEGIN DESCRIPTION:
Mapping XS 5cdfdccf
END DESCRIPTION:
XS GIS Cut Line= 3
      2816935.27      7048326.13      2816388.42      7048178.56
      2815899.00      7048096.27
#Sta/Elev= 30
  4420.1  451.50  4472.2  448.30  4519.6  443.65  4559.5  440.96  4606.8  436.26
  4667.6  431.68  4713.9  429.63  4731.1  428.03  4814.0  425.69  4871.5  423.13
  4878.8  422.68  4903.1  421.07  4973.4  420.11  4982.9  420.07  4985.7  419.13
  4990.8  419.13  4996.5  415.80  4997.0  415.00  5003.2  415.00  5003.8  415.80
  5020.4  420.46  5163.1  421.75  5200.7  422.68  5284.3  424.18  5385.4  427.23
  5400.3  426.70  5446.3  430.17  5460.9  430.17  5466.6  431.02  5482.8  431.28
#Mann=6,-1,0
  4420.1    0.05       0  4667.6    0.16       0  4871.5    0.12       0
  4973.4    0.16       0  4996.5    0.07       0  5003.8    0.16       0
Bank Sta=4878.8,5200.7
Exp/Cntr=0.3,0.1

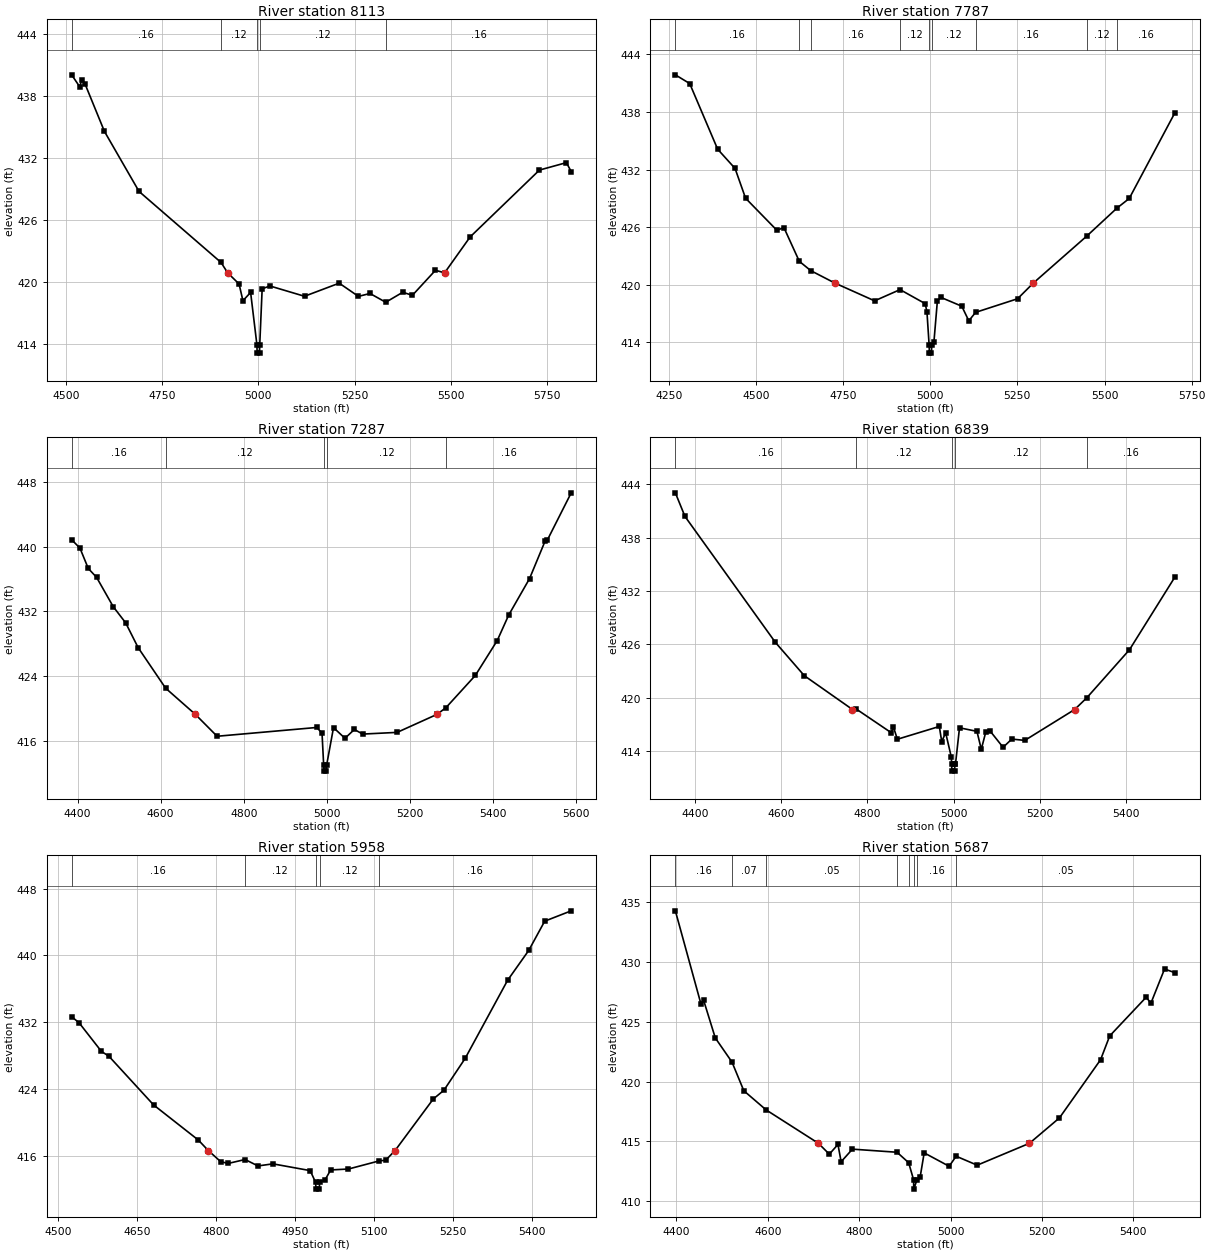
Type RM Length L Ch R = 1,8113,326,326,326
BEGIN DESCRIPTION:
Mapping XS 29830806
END DESCRIPTION:
XS GIS Cut Line= 3
      2816870.15      7047770.58      2816366.72      7047757.56
      2815572.48      7047718.50
#Sta/Elev= 30
  4514.6  440.09  4535.8  438.92  4540.8  439.63  4549.8  439.17  4599.8  434.61
  4689.8  428.79  4902.9  421.91  4920.3  420.90  4949.9  419.82  4959.9  418.20
  4979.9  419.00  4996.3  413.92  4996.8  413.12  5003.0  413.12  5003.6  413.92
  5009.9  419.35  5029.9  419.63  5120.0  418.63  5210.2  419.90  5260.2  418.62
  5290.3  418.90  5331.2  418.05  5375.5  419.02  5400.4  418.72  5460.5  421.15
  5484.2  420.90  5550.6  424.38  5730.8  430.86  5800.9  431.58  5813.4  430.71
#Mann=5,-1,0
  4514.6    0.16       0  4902.9    0.12       0  4996.3    0.07       0
  5003.6    0.12       0  5331.2    0.16       0
Bank Sta=4920.3,5484.2
Exp/Cntr=0.3,0.1

Type RM Length L Ch R = 1,7787,500,500,500
BEGIN DESCRIPTION:
Mapping XS 2565e1a0
END DESCRIPTION:
XS GIS Cut Line= 3
      2816896.22      7047623.01      2816180.08      7047596.97
      2815463.92      7047575.26
#Sta/Elev= 30
  4268.9  441.88  4310.1  440.97  4390.2  434.13  4440.2  432.12  4470.3  429.02
  4560.3  425.67  4580.3  425.96  4624.5  422.44  4657.3  421.47  4725.6  420.19
  4840.5  418.32  4913.5  419.49  4985.5  418.03  4990.6  417.20  4997.0  413.67
  4997.5  412.87  5003.7  412.87  5004.3  413.67  5010.6  414.01  5020.6  418.33
  5030.6  418.68  5090.6  417.76  5110.7  416.24  5130.3  417.12  5250.7  418.54
  5296.3  420.19  5448.5  425.05  5535.5  427.98  5570.9  428.99  5702.0  437.93
#Mann=9,-1,0
  4268.9    0.16       0  4624.5    0.12       0  4657.3    0.16       0
  4913.5    0.12       0  4997.0    0.07       0  5004.3    0.12       0
  5130.3    0.16       0  5448.5    0.12       0  5535.5    0.16       0
Bank Sta=4725.6,5296.3
Exp/Cntr=0.3,0.1

Type RM Length L Ch R = 1,7287,448,448,448
BEGIN DESCRIPTION:
GORDON BRANCH 4.0
END DESCRIPTION:
XS GIS Cut Line= 3
      2816575.02      7047275.00      2815975.00      7047275.00
      2815375.00      7047225.00
#Sta/Elev= 30
  4385.9  440.89  4405.9  439.85  4425.9  437.33  4445.9  436.23  4485.9  432.60
  4515.9  430.59  4545.9  427.52  4612.0  422.50  4683.4  419.26  4735.9  416.54
  4975.9  417.63  4988.4  416.91  4992.3  413.02  4992.9  412.22  4999.1  412.22
  4999.7  413.02  5016.0  417.61  5043.6  416.29  5066.2  417.38  5086.3  416.81
  5169.1  417.02  5265.4  419.26  5286.9  420.10  5357.2  424.07  5409.9  428.39
  5437.5  431.55  5487.7  436.07  5525.3  440.74  5530.3  440.82  5588.0  446.70
#Mann=5,-1,0
  4385.9    0.16       0  4612.0    0.12       0  4992.3    0.07       0
  4999.7    0.12       0  5286.9    0.16       0
Bank Sta=4683.4,5265.4
Exp/Cntr=0.3,0.1

Type RM Length L Ch R = 1,6839,881,881,881
BEGIN DESCRIPTION:
GORDON BRANCH 3.0
END DESCRIPTION:
XS GIS Cut Line= 3
      2816574.97      7047224.99      2815998.42      7046936.05
      2815490.75      7047008.41
#Sta/Elev= 30
  4355.1  443.06  4377.4  440.40  4586.9  426.22  4653.9  422.47  4765.6  418.66
  4774.7  418.70  4855.0  416.06  4860.6  416.67  4869.6  415.31  4966.8  416.75
  4972.4  415.05  4981.5  416.04  4994.7  413.29  4995.4  412.52  4996.0  411.72
  5002.3  411.72  5002.8  412.52  5004.3  412.52  5013.6  416.60  5054.0  416.20
  5064.1  414.18  5074.2  416.07  5084.3  416.25  5114.6  414.40  5134.8  415.33
  5164.9  415.18  5280.5  418.66  5308.8  419.99  5407.5  425.39  5512.8  433.58
#Mann=5,-1,0
  4355.1    0.16       0  4774.7    0.12       0  4995.4    0.07       0
  5002.8    0.12       0  5308.8    0.16       0
Bank Sta=4765.6,5280.5
Exp/Cntr=0.3,0.1

Type RM Length L Ch R = 1,5958,271,271,271
BEGIN DESCRIPTION:
GORDON BRANCH 2.0
END DESCRIPTION:
XS GIS Cut Line= 3
      2816424.99      7046774.99      2816075.00      7046425.00
      2815625.02      7046475.00
#Sta/Elev= 30
  4526.1  432.64  4540.2  431.91  4582.6  428.48  4596.8  427.90  4681.6  422.06
  4766.5  417.85  4785.4  416.59  4808.9  415.26  4823.1  415.05  4855.1  415.52
  4879.6  414.75  4907.9  415.00  4978.6  414.19  4989.0  412.77  4989.6  411.97
  4995.9  411.97  4996.5  412.77  5006.9  413.09  5017.5  414.27  5051.2  414.38
  5109.9  415.36  5121.7  415.43  5139.6  416.59  5212.2  422.78  5232.3  423.82
  5272.6  427.64  5353.1  437.00  5393.3  440.59  5423.5  444.09  5473.8  445.33
#Mann=5,-1,0
  4526.1    0.16       0  4855.1    0.12       0  4989.0    0.07       0
  4996.5    0.12       0  5109.9    0.16       0
Bank Sta=4785.4,5139.6
Exp/Cntr=0.3,0.1

Type RM Length L Ch R = 1,5687,681,681,681
BEGIN DESCRIPTION:
Mapping XS 5bb4b188
END DESCRIPTION:
XS GIS Cut Line= 3
      2816731.26      7046399.04      2816141.02      7046195.06
      2815672.32      7046195.06
#Sta/Elev= 30
  4397.8  434.26  4454.1  426.44  4459.4  426.82  4485.2  423.64  4521.8  421.62
  4547.6  419.23  4596.4  417.63  4710.8  414.84  4734.7  413.93  4753.6  414.74
  4760.6  413.30  4785.3  414.35  4882.9  414.09  4908.3  413.22  4919.0  411.81
  4919.6  411.01  4926.7  411.81  4933.4  412.00  4942.3  414.04  4996.9  412.92
  5012.3  413.76  5058.3  413.01  5172.7  414.84  5238.3  416.96  5328.3  421.82
  5348.3  423.81  5428.3  427.05  5438.3  426.53  5468.3  429.40  5491.0  429.09
#Mann=8,-1,0
  4397.8    0.16       0  4521.8    0.07       0  4596.4    0.05       0
  4882.9    0.12       0  4908.3    0.16       0  4919.0    0.07       0
  4926.7    0.16       0  5012.3    0.05       0
Bank Sta=4710.8,5172.7
Exp/Cntr=0.3,0.1

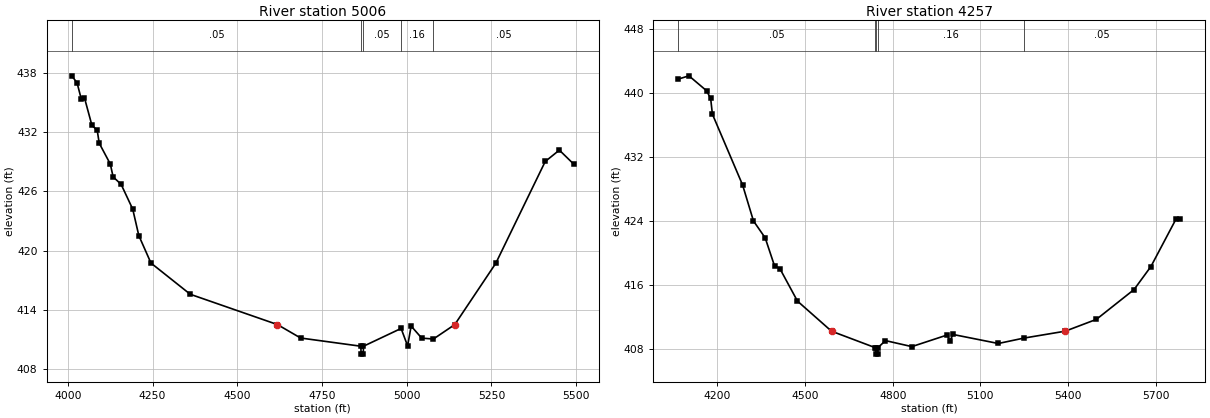
Type RM Length L Ch R = 1,5006,749,749,749
BEGIN DESCRIPTION:
Mapping XS 2f5d9dfe
END DESCRIPTION:
XS GIS Cut Line= 3
      2817119.31      7045839.72      2816327.61      7045495.96
      2815733.89      7045667.82
#Sta/Elev= 30
  4011.8  437.69  4027.4  436.98  4040.0  435.32  4049.2  435.47  4071.0  432.71
  4086.9  432.16  4092.8  430.87  4125.5  428.76  4133.8  427.46  4157.3  426.71
  4191.6  424.20  4209.6  421.52  4245.4  418.74  4361.3  415.58  4618.7  412.51
  4687.0  411.15  4864.7  410.32  4865.3  409.52  4871.8  409.52  4872.4  410.32
  4983.4  412.12  5002.6  410.35  5013.0  412.36  5044.2  411.14  5078.7  411.05
  5141.7  412.51  5262.8  418.72  5408.6  429.02  5450.2  430.17  5493.0  428.74
#Mann=5,-1,0
  4011.8    0.05       0  4864.7    0.07       0  4872.4    0.05       0
  4983.4    0.16       0  5078.7    0.05       0
Bank Sta=4618.7,5141.7
Exp/Cntr=0.3,0.1

Type RM Length L Ch R = 1,4257,0,0,0
BEGIN DESCRIPTION:
GORDON BRANCH 1.0
END DESCRIPTION:
XS GIS Cut Line= 3
      2817151.42      7044880.17      2816122.79      7044784.68
      2815714.83      7045335.87
#Sta/Elev= 30
  4065.7  441.70  4102.3  442.11  4162.5  440.25  4176.7  439.28  4182.6  437.32
  4286.0  428.46  4323.2  423.96  4363.4  421.84  4395.3  418.34  4413.6  418.00
  4473.9  413.93  4590.4  410.17  4739.9  408.11  4741.1  408.10  4741.7  407.30
  4748.3  407.30  4749.0  408.10  4775.2  408.99  4865.5  408.24  4986.1  409.69
  4996.1  408.95  5006.2  409.76  5161.4  408.63  5248.1  409.30  5390.5  410.17
  5497.3  411.65  5626.2  415.38  5683.9  418.26  5770.3  424.23  5784.5  424.19
#Mann=5,-1,0
  4065.7    0.05       0  4739.9    0.16       0  4741.1    0.07       0
  4749.0    0.16       0  5248.1    0.05       0
Bank Sta=4590.4,5390.5
Exp/Cntr=0.3,0.1

Chan Stop Cuts=-1