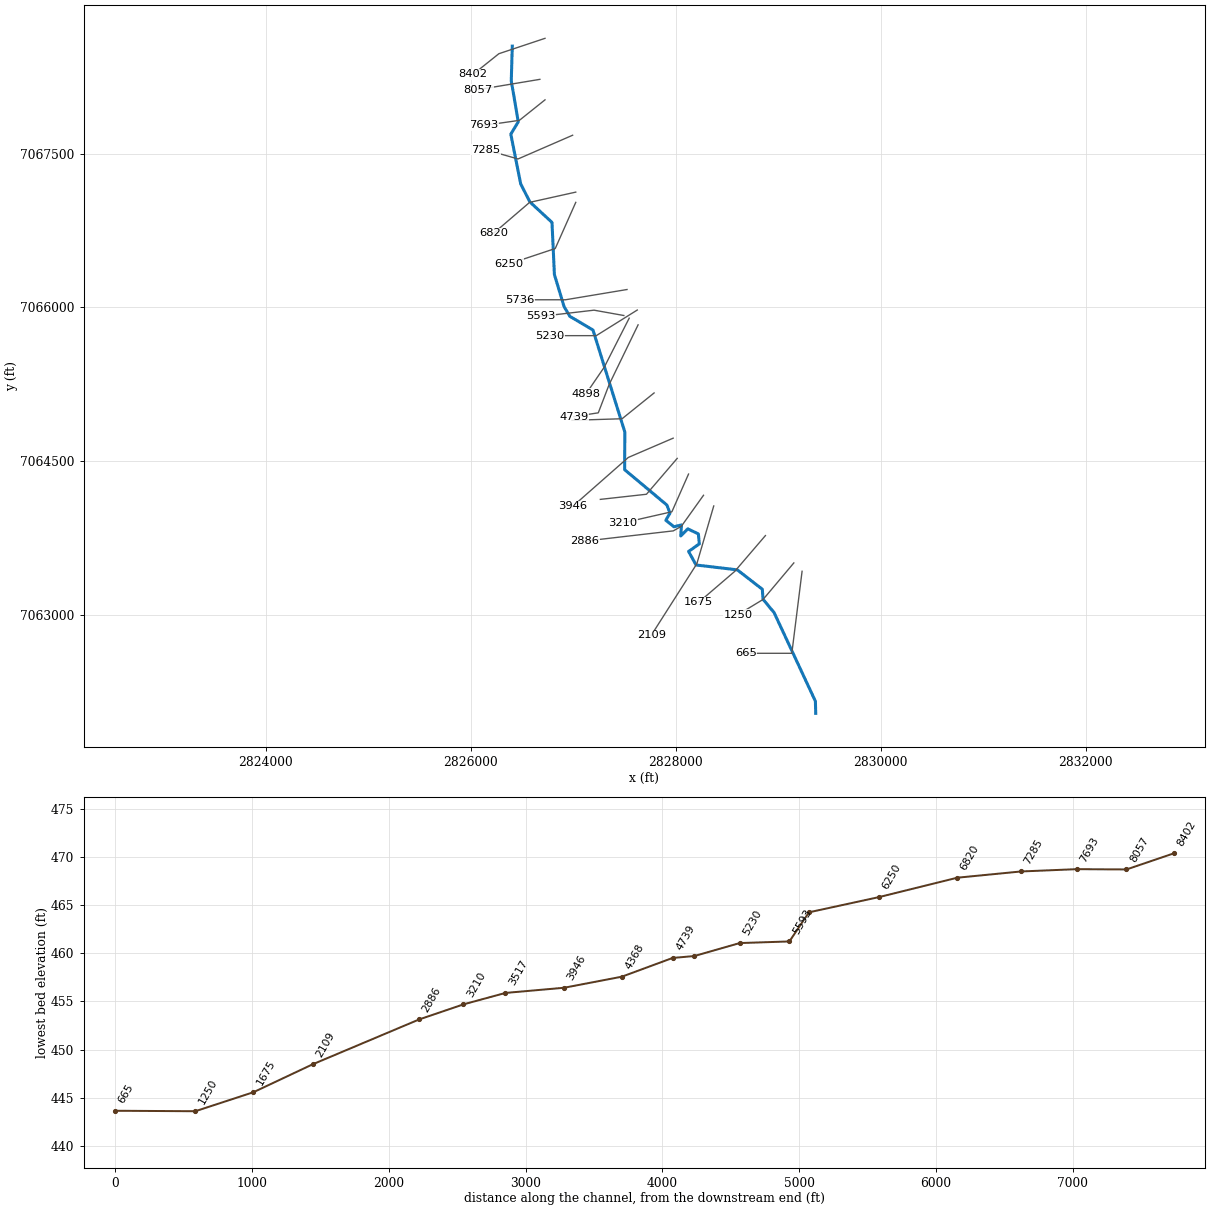
--- GREENVIEW CREEK.prj (project) ---

Proj Title=GREENVIEW CREEK Base Level Engineering
Current Plan=p01
Default Exp/Contr=0.3,0.1
English Units
Geom File=g01
Flow File=f01
Plan File=p01
BEGIN DESCRIPTION:
GREENVIEW CREEK
END DESCRIPTION:

--- GREENVIEW CREEK.p01 (plan) ---

Plan Title=Multiple Run
Short Identifier=Multiple
Geom File=g01
Flow File=f01
Subcritical Flow
K Sum by GR= 0
Std Step Tol= 0.01
Critical Tol= 0.01
Num of Std Step Trials= 20
Max Error Tol= 0.3
Flow Tol Ratio= 0.001
Split Flow NTrial= 30
Split Flow Tol= 0.02
Split Flow Ratio= 0.02
Log Output Level= 0
Friction Slope Method= 1
Unsteady Friction Slope Method= 2
Unsteady Bridges Friction Slope Method= 1
Parabolic Critical Depth
Global Vel Dist=  1 , 1 , 1
Global Log Level= 0
CheckData=True
Encroach Param= -1, 0, 0, 0
BEGIN DESCRIPTION:
Multiple Run
END DESCRIPTION:

--- GREENVIEW CREEK.f01 (steady flow) ---

Flow Title=Multiple
Number of Profiles=7
Profile Names=10-year,25-year,50-year,1pct_min,100-year,1pct_plu,500-year
River Rch & RM= GREENVIEW CREEK,Reach-1,8402
     669     889    1066     633    1264    2522    1773
River Rch & RM= GREENVIEW CREEK,Reach-1,6820
    1133    1551    1895    1146    2287    4563    3325
River Rch & RM= GREENVIEW CREEK,Reach-1,3946
    1283    1768    2172    1319    2633    5253    3863
River Rch & RM= GREENVIEW CREEK,Reach-1,2109
    1450    2008    2473    1505    3004    5993    4427
Boundary for River Rch & Prof#=GREENVIEW CREEK,Reach-1,1
Up Type=0
Dn Type=3
Dn Slope=0.005
Boundary for River Rch & Prof#=GREENVIEW CREEK,Reach-1,2
Up Type=0
Dn Type=3
Dn Slope=0.005
Boundary for River Rch & Prof#=GREENVIEW CREEK,Reach-1,3
Up Type=0
Dn Type=3
Dn Slope=0.005
Boundary for River Rch & Prof#=GREENVIEW CREEK,Reach-1,4
Up Type=0
Dn Type=3
Dn Slope=0.005
Boundary for River Rch & Prof#=GREENVIEW CREEK,Reach-1,5
Up Type=0
Dn Type=3
Dn Slope=0.005
Boundary for River Rch & Prof#=GREENVIEW CREEK,Reach-1,6
Up Type=0
Dn Type=3
Dn Slope=0.005
Boundary for River Rch & Prof#=GREENVIEW CREEK,Reach-1,7
Up Type=0
Dn Type=3
Dn Slope=0.005

--- GREENVIEW CREEK.g01 (geometry) ---

Geom Title=Existing Conditions

River Reach=GREENVIEW CREEK,Reach-1
Reach XY= 30
      2826405.86      7068549.27      2826395.91      7068210.84
      2826464.29      7067810.32      2826391.47      7067690.61
      2826487.69      7067206.41      2826576.49      7067030.37
      2826793.12      7066829.69      2826816.75      7066320.93
      2826911.02      7066008.23      2826967.32      7065913.31
      2827192.95      7065779.92      2827503.63      7064784.87
      2827501.67      7064417.64      2827913.76      7064072.97
      2827944.37      7063993.81      2827903.21      7063924.15
      2827983.43      7063860.83      2828056.25      7063878.77
      2828048.86      7063771.11      2828117.47      7063840.77
      2828220.90      7063791.16      2828230.40      7063694.06
      2828125.46      7063620.11      2828198.76      7063488.04
      2828600.77      7063440.66      2828844.68      7063251.12
      2828851.66      7063153.91      2828959.77      7063023.01
      2829362.42      7062159.35      2829365.59      7062040.71

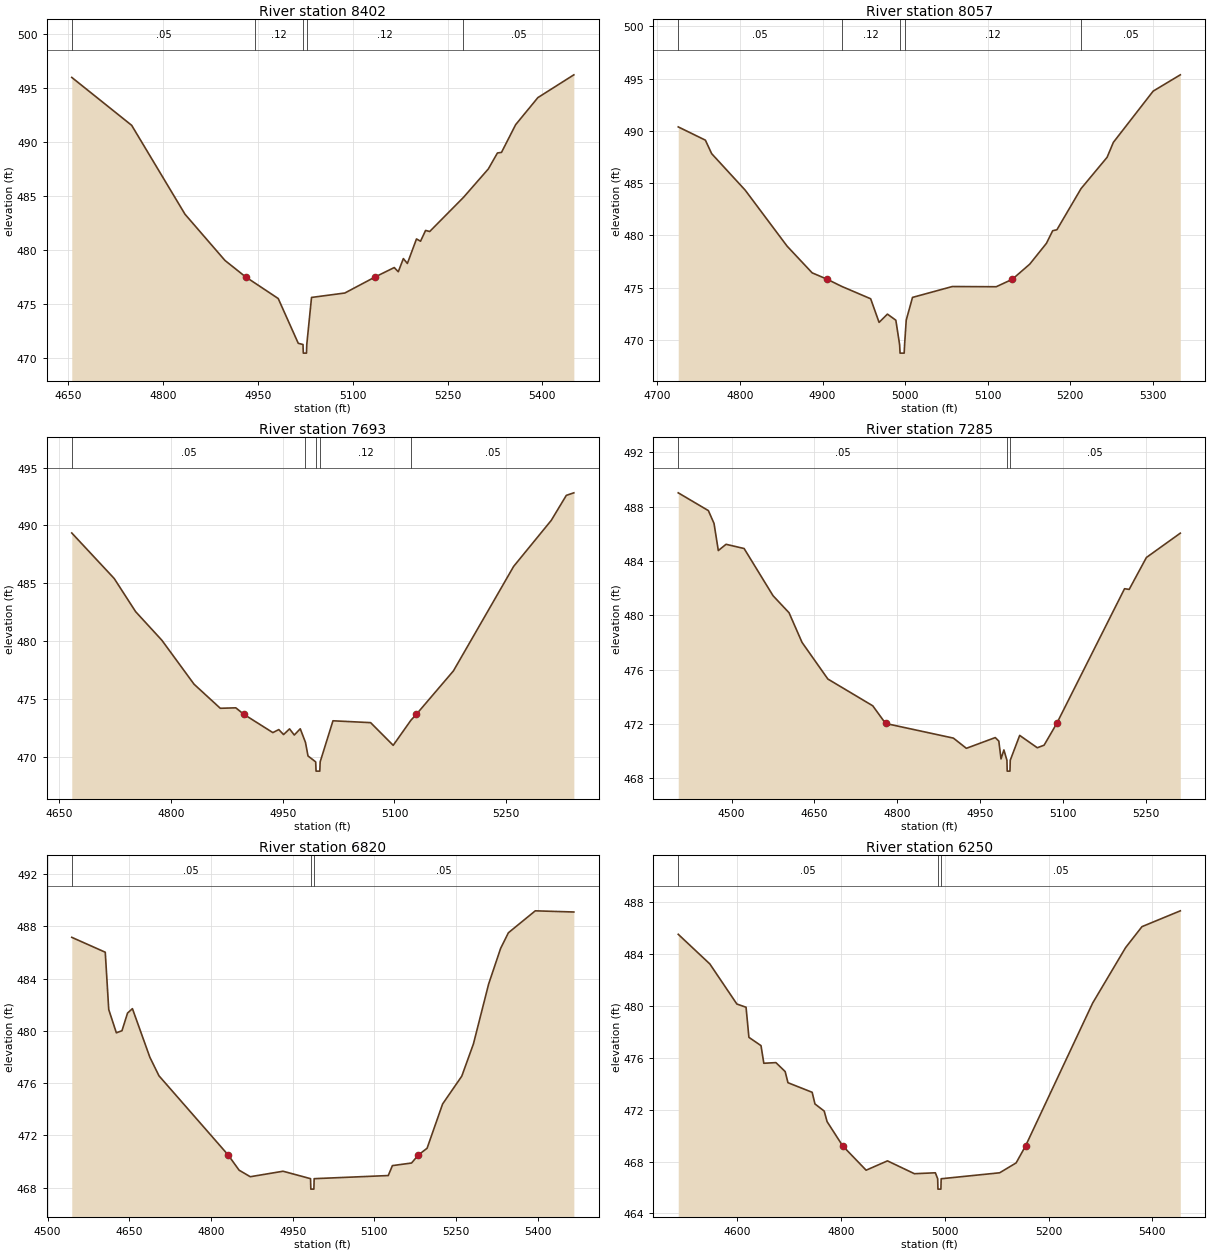
Type RM Length L Ch R = 1,8402,345,345,345
BEGIN DESCRIPTION:
GREENVIEW CREEK 15.0
END DESCRIPTION:
XS GIS Cut Line= 3
      2826724.97      7068624.99      2826275.00      7068475.00
      2826024.97      7068274.98
#Sta/Elev= 30
  4655.4  495.96  4750.2  491.52  4834.6  483.28  4897.8  479.00  4930.6  477.47
  4945.6  476.89  4982.1  475.47  5013.8  471.32  5021.3  471.21  5021.8  470.41
  5026.8  470.41  5027.3  471.21  5034.8  475.57  5087.5  475.98  5135.5  477.47
  5165.7  478.34  5172.1  477.95  5180.1  479.17  5186.5  478.72  5200.9  480.99
  5207.3  480.78  5215.3  481.78  5221.8  481.68  5275.2  484.84  5314.6  487.48
  5329.0  488.96  5335.4  489.01  5357.8  491.58  5393.0  494.09  5449.9  496.20
#Mann=5,-1,0
  4655.4    0.05       0  4945.6    0.12       0  5021.3    0.07       0
  5027.3    0.12       0  5275.2    0.05       0
Bank Sta=4930.6,5135.5
Exp/Cntr=0.3,0.1

Type RM Length L Ch R = 1,8057,364,364,364
BEGIN DESCRIPTION:
GREENVIEW CREEK 14.0
END DESCRIPTION:
XS GIS Cut Line= 3
      2826674.97      7068224.99      2826375.00      7068175.00
      2826075.04      7068125.01
#Sta/Elev= 30
  4725.2  490.38  4758.1  489.11  4765.7  487.82  4806.3  484.33  4857.0  478.98
  4887.4  476.42  4905.8  475.80  4923.3  475.12  4958.3  473.94  4968.5  471.68
  4978.6  472.47  4988.8  471.89  4993.4  469.54  4993.9  468.74  4998.9  468.74
  4999.4  469.54  5001.4  471.90  5009.0  474.07  5057.2  475.11  5110.4  475.09
  5129.8  475.80  5151.0  477.25  5171.2  479.24  5178.8  480.45  5183.9  480.54
  5213.1  484.47  5244.7  487.47  5252.3  488.90  5300.5  493.80  5333.4  495.36
#Mann=5,-1,0
  4725.2    0.05       0  4923.3    0.12       0  4993.4    0.07       0
  4999.4    0.12       0  5213.1    0.05       0
Bank Sta=4905.8,5129.8
Exp/Cntr=0.3,0.1

Type RM Length L Ch R = 1,7693,408,408,408
BEGIN DESCRIPTION:
GREENVIEW CREEK 13.0
END DESCRIPTION:
XS GIS Cut Line= 3
      2826725.03      7068025.02      2826475.00      7067825.00
      2826125.05      7067775.01
#Sta/Elev= 30
  4667.0  489.35  4723.9  485.42  4752.7  482.55  4787.9  480.08  4831.1  476.28
  4866.3  474.20  4887.1  474.24  4897.9  473.68  4936.8  472.10  4944.8  472.36
  4951.2  471.93  4959.2  472.42  4965.6  471.89  4973.6  472.43  4980.6  471.25
  4984.0  470.08  4994.3  469.57  4994.8  468.77  4999.8  468.77  5000.3  469.57
  5017.5  473.12  5068.0  472.96  5098.3  471.00  5122.1  473.17  5129.4  473.68
  5179.1  477.43  5259.9  486.46  5310.4  490.44  5330.6  492.60  5340.7  492.82
#Mann=5,-1,0
  4667.0    0.05       0  4980.6    0.12       0  4994.3    0.07       0
  5000.3    0.12       0  5122.1    0.05       0
Bank Sta=4897.9,5129.4
Exp/Cntr=0.3,0.1

Type RM Length L Ch R = 1,7285,465,465,465
BEGIN DESCRIPTION:
GREENVIEW CREEK 12.0
END DESCRIPTION:
XS GIS Cut Line= 3
      2826994.44      7067679.86      2826461.95      7067448.35
      2826145.94      7067538.64
#Sta/Elev= 30
  4403.5  489.02  4458.1  487.71  4468.3  486.77  4476.1  484.77  4490.1  485.23
  4522.8  484.92  4575.3  481.44  4604.2  480.19  4627.7  478.01  4674.5  475.31
  4755.8  473.34  4779.0  472.04  4901.9  470.96  4925.3  470.21  4977.7  471.00
  4984.1  470.74  4988.1  469.43  4993.3  470.09  4998.8  469.33  4999.3  468.53
  5004.3  468.53  5004.8  469.33  5021.9  471.16  5053.8  470.25  5066.1  470.44
  5089.0  472.04  5211.8  481.96  5220.2  481.91  5251.4  484.26  5312.8  486.05
#Mann=3,-1,0
  4403.5    0.05       0  4998.8    0.03       0  5004.8    0.05       0
Bank Sta=4779,5089
Exp/Cntr=0.3,0.1

Type RM Length L Ch R = 1,6820,570,570,570
BEGIN DESCRIPTION:
GREENVIEW CREEK 11.0
END DESCRIPTION:
XS GIS Cut Line= 3
      2827025.00      7067125.00      2826575.00      7067025.00
      2826224.96      7066724.97
#Sta/Elev= 30
  4544.3  487.16  4605.8  486.02  4612.2  481.63  4626.2  479.85  4636.5  480.01
  4646.7  481.36  4655.7  481.70  4687.7  477.98  4704.4  476.56  4831.4  470.50
  4851.6  469.33  4872.1  468.83  4932.3  469.25  4982.8  468.68  4983.3  467.88
  4988.9  467.88  4989.4  468.68  5125.5  468.92  5133.1  469.68  5168.3  469.88
  5180.9  470.50  5196.8  471.01  5225.3  474.40  5260.5  476.53  5281.9  479.00
  5309.8  483.58  5331.8  486.31  5346.1  487.51  5395.5  489.19  5466.3  489.10
#Mann=3,-1,0
  4544.3    0.05       0  4982.8    0.03       0  4989.4    0.05       0
Bank Sta=4831.4,5180.9
Exp/Cntr=0.3,0.1

Type RM Length L Ch R = 1,6250,514,514,514
BEGIN DESCRIPTION:
GREENVIEW CREEK 10.0
END DESCRIPTION:
XS GIS Cut Line= 3
      2827025.00      7067025.01      2826825.00      7066575.00
      2826374.99      7066425.00
#Sta/Elev= 30
  4487.0  485.53  4547.9  483.24  4599.9  480.15  4617.6  479.90  4623.1  477.58
  4646.4  476.94  4651.8  475.58  4675.1  475.63  4692.9  474.94  4698.3  474.08
  4744.9  473.34  4750.3  472.44  4768.1  471.89  4773.6  471.08  4803.6  469.21
  4848.8  467.33  4889.9  468.05  4941.8  467.06  4982.1  467.13  4986.6  466.67
  4987.1  465.87  4992.8  465.87  4993.3  466.67  5105.9  467.13  5137.6  467.89
  5155.9  469.21  5285.1  480.23  5348.4  484.50  5380.0  486.12  5453.8  487.34
#Mann=3,-1,0
  4487.0    0.05       0  4986.6    0.03       0  4993.3    0.05       0
Bank Sta=4803.6,5155.9
Exp/Cntr=0.3,0.1

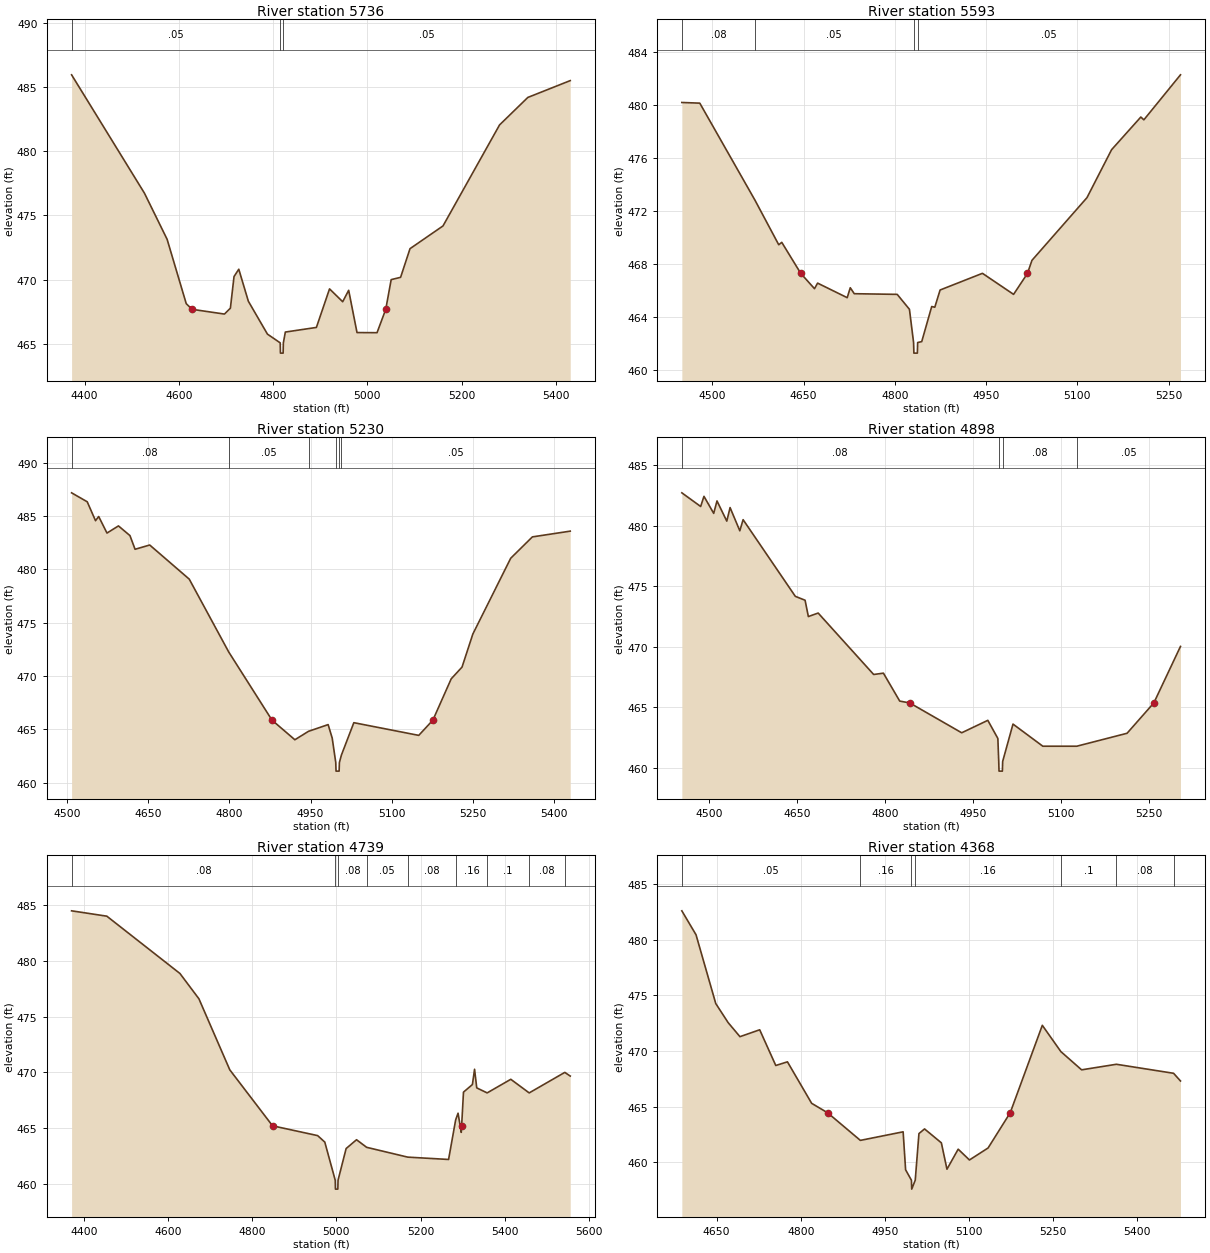
Type RM Length L Ch R = 1,5736,143,143,143
BEGIN DESCRIPTION:
GREENVIEW CREEK 9.0
END DESCRIPTION:
XS GIS Cut Line= 3
      2827524.96      7066174.99      2826925.00      7066075.00
      2826475.04      7066075.00
#Sta/Elev= 30
  4372.4  485.94  4527.0  476.73  4575.1  473.14  4615.7  468.13  4628.0  467.69
  4696.8  467.32  4709.4  467.78  4717.1  470.24  4727.2  470.81  4747.5  468.32
  4788.0  465.76  4815.1  465.08  4815.6  464.28  4821.3  464.28  4821.8  465.08
  4826.0  465.92  4891.9  466.28  4919.8  469.28  4947.7  468.28  4960.4  469.17
  4978.1  465.88  5020.6  465.87  5039.1  467.69  5050.6  470.00  5070.6  470.18
  5090.6  472.41  5160.6  474.18  5280.6  482.04  5340.6  484.18  5430.6  485.49
#Mann=3,-1,0
  4372.4    0.05       0  4815.1    0.03       0  4821.8    0.05       0
Bank Sta=4628,5039.1
Exp/Cntr=0.3,0.1

Type RM Length L Ch R = 1,5593,363,363,363
BEGIN DESCRIPTION:
Mapping XS 31d3bddf
END DESCRIPTION:
XS GIS Cut Line= 3
      2827494.08      7065921.44      2827203.27      7065973.53
      2826682.44      7065912.76
#Sta/Elev= 30
  4449.9  480.19  4479.4  480.14  4570.1  472.81  4609.2  469.44  4614.2  469.62
  4645.5  467.27  4668.0  466.12  4673.1  466.54  4721.8  465.44  4726.8  466.19
  4733.4  465.74  4804.0  465.69  4824.1  464.56  4830.9  462.05  4831.4  461.25
  4837.1  461.25  4837.6  462.05  4844.3  462.12  4860.7  464.77  4865.8  464.72
  4874.5  466.02  4944.1  467.28  4995.3  465.69  5018.1  467.27  5025.5  468.26
  5116.0  473.00  5156.4  476.62  5204.5  479.09  5209.5  478.88  5269.7  482.28
#Mann=4,-1,0
  4449.9    0.08       0  4570.1    0.05       0  4830.9    0.03       0
  4837.6    0.05       0
Bank Sta=4645.5,5018.1
Exp/Cntr=0.3,0.1

Type RM Length L Ch R = 1,5230,332,332,332
BEGIN DESCRIPTION:
GREENVIEW CREEK 8.0
END DESCRIPTION:
XS GIS Cut Line= 3
      2827624.98      7065974.99      2827225.00      7065725.00
      2826774.97      7065725.00
#Sta/Elev= 30
  4508.2  487.16  4537.1  486.32  4552.4  484.55  4558.3  484.94  4573.6  483.39
  4594.8  484.06  4616.1  483.15  4625.5  481.87  4652.6  482.27  4725.7  479.07
  4798.7  472.24  4878.6  465.86  4920.9  464.02  4946.1  464.81  4982.4  465.44
  4989.9  464.18  4996.5  461.88  4997.0  461.08  5002.7  461.08  5003.2  461.88
  5006.9  462.58  5029.9  465.62  5149.9  464.43  5176.0  465.86  5209.9  469.73
  5229.9  470.83  5249.9  473.93  5319.9  481.03  5359.9  483.03  5429.9  483.57
#Mann=6,-1,0
  4508.2    0.08       0  4798.7    0.05       0  4946.1    0.08       0
  4996.5    0.07       0  5003.2    0.08       0  5006.9    0.05       0
Bank Sta=4878.6,5176
Exp/Cntr=0.3,0.1

Type RM Length L Ch R = 1,4898,159,159,159
BEGIN DESCRIPTION:
Mapping XS b880d9c0
END DESCRIPTION:
XS GIS Cut Line= 3
      2827546.17      7065895.43      2827303.10      7065417.97
      2827125.99      7065158.78
#Sta/Elev= 30
  4454.1  482.74  4486.2  481.61  4491.8  482.45  4508.4  481.04  4514.0  482.07
  4530.7  480.40  4536.3  481.52  4552.9  479.60  4558.5  480.52  4647.5  474.18
  4664.1  473.86  4669.7  472.51  4686.4  472.80  4781.0  467.72  4797.6  467.83
  4825.4  465.52  4842.4  465.37  4931.0  462.90  4975.5  463.93  4992.6  462.43
  4994.1  460.53  4994.6  459.73  5000.3  459.73  5000.8  460.53  5018.4  463.62
  5069.2  461.79  5127.1  461.79  5212.8  462.86  5258.4  465.37  5303.8  470.04
#Mann=4,-1,0
  4454.1    0.08       0  4994.1    0.07       0  5000.8    0.08       0
  5127.1    0.05       0
Bank Sta=4842.4,5258.4
Exp/Cntr=0.3,0.1

Type RM Length L Ch R = 1,4739,371,371,371
BEGIN DESCRIPTION:
Mapping XS 691e8af8
END DESCRIPTION:
XS GIS Cut Line= 4
      2827632.95      7065830.27      2827350.84      7065248.70
      2827244.74      7064972.20      2827005.46      7064935.60
#Sta/Elev= 30
  4370.9  484.49  4454.6  484.01  4628.3  478.87  4673.4  476.60  4746.7  470.23
  4848.3  465.21  4955.4  464.33  4972.4  463.75  4997.2  460.33  4997.7  459.53
  5003.4  459.53  5003.9  460.33  5023.1  463.17  5047.8  463.96  5071.8  463.28
  5169.4  462.40  5266.5  462.19  5283.3  465.74  5289.0  466.34  5296.6  464.62
  5297.5  465.21  5301.9  468.23  5323.1  468.91  5328.2  470.28  5333.4  468.61
  5358.1  468.16  5414.3  469.38  5458.0  468.16  5542.6  470.00  5555.5  469.67
#Mann=9,-1,0
  4370.9    0.08       0  4997.2    0.07       0  5003.9    0.08       0
  5071.8    0.05       0  5169.4    0.08       0  5283.3    0.16       0
  5358.1     0.1       0  5458.0    0.08       0  5542.6    0.05       0
Bank Sta=4848.3,5297.5
Exp/Cntr=0.3,0.1

Type RM Length L Ch R = 1,4368,422,422,422
BEGIN DESCRIPTION:
Mapping XS 59d62ca1
END DESCRIPTION:
XS GIS Cut Line= 3
      2827789.22      7065166.24      2827476.71      7064914.50
      2826988.64      7064899.19
#Sta/Elev= 30
  4587.9  482.59  4613.2  480.44  4648.4  474.26  4670.4  472.55  4691.6  471.28
  4726.8  471.90  4755.5  468.69  4776.3  469.02  4819.5  465.29  4848.0  464.44
  4906.4  461.96  4982.7  462.73  4987.1  459.32  4997.5  458.38  4998.0  457.58
  5004.3  458.38  5010.9  462.57  5020.9  462.99  5050.9  461.74  5060.9  459.37
  5080.9  461.17  5101.0  460.20  5134.3  461.28  5173.7  464.44  5231.0  472.30
  5264.1  469.94  5301.1  468.30  5363.1  468.80  5465.2  467.99  5477.5  467.30
#Mann=7,-1,0
  4587.9    0.05       0  4906.4    0.16       0  4997.5    0.07       0
  5004.3    0.16       0  5264.1     0.1       0  5363.1    0.08       0
  5465.2    0.05       0
Bank Sta=4848,5173.7
Exp/Cntr=0.3,0.1

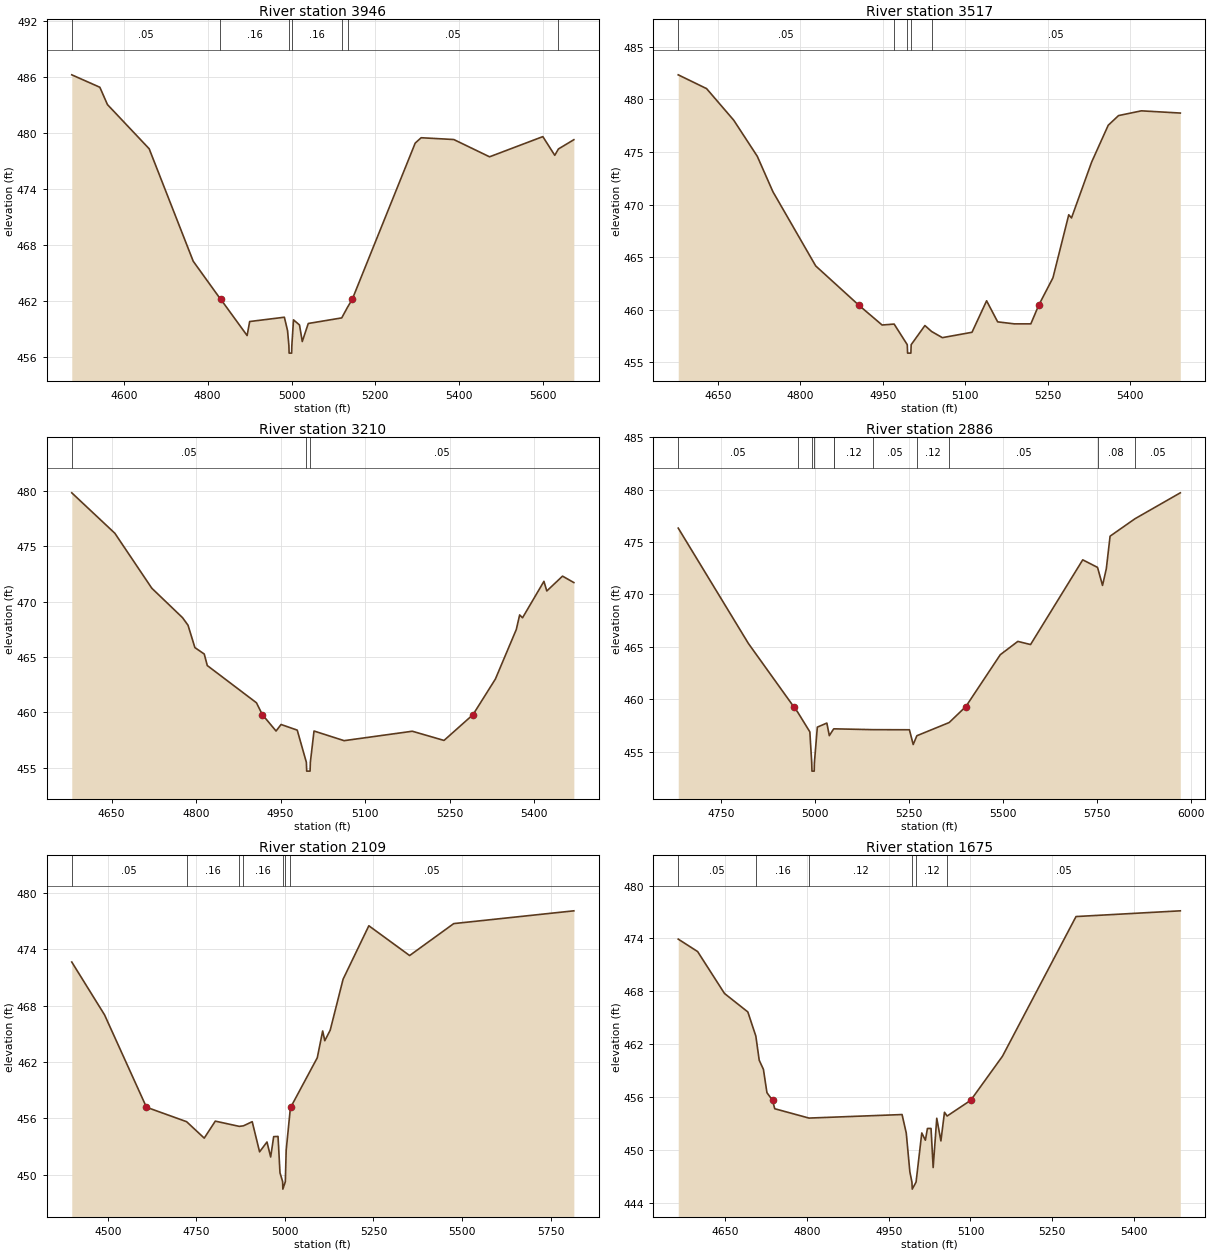
Type RM Length L Ch R = 1,3946,429,429,429
BEGIN DESCRIPTION:
GREENVIEW CREEK 6.0
END DESCRIPTION:
XS GIS Cut Line= 3
      2827975.00      7064725.00      2827537.48      7064536.89
      2826995.53      7064060.22
#Sta/Elev= 30
  4475.7  486.20  4542.7  484.87  4560.8  483.02  4660.4  478.29  4765.5  466.26
  4829.1  462.30  4831.4  462.18  4894.1  458.31  4900.2  459.81  4983.0  460.27
  4990.6  458.83  4993.8  457.23  4994.3  456.43  5000.3  456.43  5000.8  457.23
  5004.8  459.99  5019.1  459.44  5025.7  457.67  5040.0  459.60  5119.9  460.20
  5133.7  461.34  5144.9  462.18  5295.2  478.90  5309.4  479.47  5387.2  479.28
  5472.6  477.43  5599.7  479.59  5628.2  477.59  5636.9  478.27  5673.7  479.26
#Mann=7,-1,0
  4475.7    0.05       0  4829.1    0.16       0  4993.8    0.07       0
  5000.8    0.16       0  5119.9    0.12       0  5133.7    0.05       0
  5636.9    0.08       0
Bank Sta=4831.4,5144.9
Exp/Cntr=0.3,0.1

Type RM Length L Ch R = 1,3517,307,307,307
BEGIN DESCRIPTION:
GREENVIEW CREEK 5.0
END DESCRIPTION:
XS GIS Cut Line= 3
      2828014.59      7064527.96      2827714.62      7064177.99
      2827264.63      7064127.99
#Sta/Elev= 30
  4577.9  482.32  4629.5  481.01  4678.9  478.01  4721.7  474.59  4750.2  471.22
  4828.1  464.17  4906.4  460.45  4948.9  458.56  4970.8  458.65  4994.7  456.69
  4995.3  455.89  5001.3  455.89  5001.8  456.69  5026.8  458.51  5039.1  457.94
  5058.6  457.36  5112.5  457.87  5139.1  460.86  5159.2  458.86  5189.4  458.67
  5219.6  458.67  5234.0  460.45  5259.8  463.04  5288.6  469.03  5293.6  468.73
  5330.2  474.03  5360.4  477.53  5379.2  478.45  5420.8  478.90  5491.6  478.69
#Mann=5,-1,0
  4577.9    0.05       0  4970.8    0.16       0  4994.7    0.07       0
  5001.8    0.16       0  5039.1    0.05       0
Bank Sta=4906.4,5234
Exp/Cntr=0.3,0.1

Type RM Length L Ch R = 1,3210,324,324,324
BEGIN DESCRIPTION:
GREENVIEW CREEK 4.0
END DESCRIPTION:
XS GIS Cut Line= 3
      2828124.99      7064374.98      2827962.82      7064007.38
      2827485.38      7063898.87
#Sta/Elev= 30
  4579.3  479.82  4655.8  476.17  4721.4  471.21  4776.0  468.55  4785.7  467.87
  4797.9  465.85  4814.5  465.27  4819.9  464.23  4907.2  460.87  4917.7  459.80
  4942.0  458.32  4950.9  458.91  4979.6  458.40  4995.8  455.50  4996.4  454.70
  5002.4  454.70  5002.9  455.50  5009.4  458.32  5062.8  457.45  5183.9  458.30
  5240.2  457.47  5291.7  459.80  5331.4  463.01  5368.5  467.48  5374.5  468.80
  5379.6  468.54  5417.6  471.83  5422.7  470.96  5450.6  472.30  5470.7  471.72
#Mann=3,-1,0
  4579.3    0.05       0  4995.8    0.03       0  5002.9    0.05       0
Bank Sta=4917.7,5291.7
Exp/Cntr=0.3,0.1

Type RM Length L Ch R = 1,2886,777,777,777
BEGIN DESCRIPTION:
Mapping XS 458ba514
END DESCRIPTION:
XS GIS Cut Line= 4
      2828271.00      7064167.99      2828053.97      7063864.15
      2827975.84      7063820.75      2827109.59      7063720.51
#Sta/Elev= 30
  4635.8  476.34  4822.2  465.33  4942.5  459.30  4953.3  458.77  4985.7  456.88
  4990.7  453.93  4991.3  453.13  4997.3  453.13  4997.8  453.93  5005.6  457.33
  5030.9  457.72  5037.5  456.52  5048.8  457.15  5049.8  457.17  5153.8  457.09
  5250.4  457.08  5260.5  455.67  5270.2  456.51  5356.1  457.77  5400.5  459.30
  5492.0  464.25  5538.7  465.52  5572.5  465.22  5711.2  473.31  5750.5  472.59
  5763.8  470.87  5773.9  472.46  5783.9  475.57  5849.9  477.23  5970.6  479.71
#Mann=11,-1,0
  4635.8    0.05       0  4953.3    0.12       0  4990.7    0.07       0
  4997.8    0.12       0  5048.8    0.16       0  5049.8    0.12       0
  5153.8    0.05       0  5270.2    0.12       0  5356.1    0.05       0
  5750.5    0.08       0  5849.9    0.05       0
Bank Sta=4942.5,5400.5
Exp/Cntr=0.3,0.1

Type RM Length L Ch R = 1,2109,434,434,434
BEGIN DESCRIPTION:
GREENVIEW CREEK 3.0
END DESCRIPTION:
XS GIS Cut Line= 3
      2828370.82      7064063.84      2828205.88      7063499.57
      2827760.15      7062800.34
#Sta/Elev= 30
  4398.6  472.65  4491.2  467.02  4609.4  457.19  4722.7  455.65  4772.5  453.90
  4803.7  455.71  4871.5  455.15  4883.2  455.21  4907.9  455.65  4928.7  452.44
  4949.6  453.49  4960.0  451.89  4968.5  454.06  4980.8  454.08  4986.3  450.21
  4993.8  449.27  4994.4  448.47  5001.4  449.27  5003.8  452.62  5015.5  457.05
  5016.6  457.19  5091.6  462.46  5106.8  465.31  5112.7  464.27  5128.0  465.39
  5164.4  470.82  5237.1  476.51  5352.2  473.34  5476.7  476.74  5815.7  478.10
#Mann=7,-1,0
  4398.6    0.05       0  4722.7    0.16       0  4871.5    0.12       0
  4883.2    0.16       0  4993.8    0.07       0  5001.4    0.16       0
  5015.5    0.05       0
Bank Sta=4609.4,5016.6
Exp/Cntr=0.3,0.1

Type RM Length L Ch R = 1,1675,425,425,425
BEGIN DESCRIPTION:
GREENVIEW CREEK 2.0
END DESCRIPTION:
XS GIS Cut Line= 3
      2828874.97      7063774.97      2828575.00      7063425.00
      2828225.01      7063125.01
#Sta/Elev= 30
  4563.4  473.92  4599.0  472.51  4648.4  467.75  4691.2  465.66  4705.9  462.92
  4712.1  460.18  4719.8  459.15  4726.3  456.50  4736.5  455.64  4740.6  454.68
  4803.5  453.62  4974.4  454.02  4982.1  451.92  4988.7  447.52  4992.5  446.36
  4993.1  445.56  5000.1  446.36  5010.6  451.93  5017.2  451.11  5021.0  452.44
  5027.6  452.44  5031.5  448.01  5038.1  453.60  5045.7  451.03  5052.3  454.28
  5057.1  453.85  5100.5  455.64  5158.8  460.64  5293.8  476.48  5485.3  477.13
#Mann=6,-1,0
  4563.4    0.05       0  4705.9    0.16       0  4803.5    0.12       0
  4992.5    0.07       0  5000.1    0.12       0  5057.1    0.05       0
Bank Sta=4736.5,5100.5
Exp/Cntr=0.3,0.1

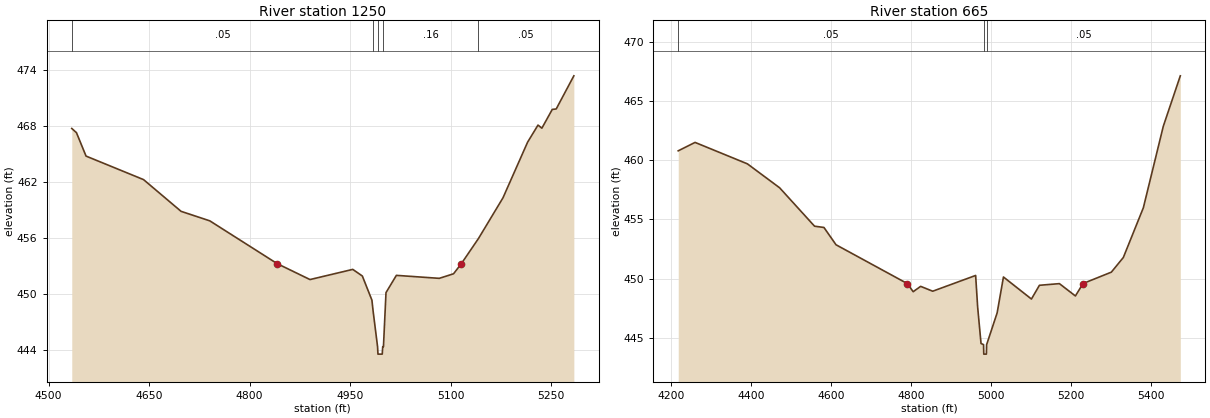
Type RM Length L Ch R = 1,1250,585,585,585
BEGIN DESCRIPTION:
Mapping XS 1e6096f5
END DESCRIPTION:
XS GIS Cut Line= 3
      2829152.07      7063508.26      2828852.58      7063152.35
      2828609.78      7063004.93
#Sta/Elev= 30
  4534.7  467.76  4541.7  467.31  4556.0  464.80  4641.8  462.28  4697.8  458.88
  4740.7  457.86  4841.1  453.28  4890.2  451.57  4954.0  452.66  4968.3  451.95
  4982.6  449.36  4984.3  448.23  4991.0  444.38  4991.6  443.58  4998.0  443.58
  4998.7  444.38  4999.8  444.38  5003.6  450.17  5019.1  452.02  5083.1  451.70
  5104.4  452.19  5116.1  453.28  5141.6  455.97  5178.1  460.32  5214.9  466.29
  5230.4  468.12  5236.2  467.79  5251.7  469.80  5257.6  469.85  5283.9  473.40
#Mann=5,-1,0
  4534.7    0.05       0  4984.3    0.16       0  4991.0    0.07       0
  4998.7    0.16       0  5141.6    0.05       0
Bank Sta=4841.1,5116.1
Exp/Cntr=0.3,0.1

Type RM Length L Ch R = 1,665,0,0,0
BEGIN DESCRIPTION:
GREENVIEW CREEK 1.0
END DESCRIPTION:
XS GIS Cut Line= 3
      2829232.49      7063426.78      2829132.49      7062626.78
      2828682.52      7062626.78
#Sta/Elev= 30
  4218.1  460.79  4260.2  461.50  4391.2  459.69  4471.8  457.67  4559.1  454.43
  4582.7  454.32  4612.9  452.86  4790.9  449.59  4806.0  448.90  4824.6  449.35
  4854.8  448.94  4962.2  450.27  4967.3  447.58  4975.7  444.53  4982.0  444.43
  4982.6  443.63  4989.1  443.63  4989.7  444.43  5016.0  447.11  5031.8  450.14
  5101.8  448.28  5121.8  449.44  5171.8  449.58  5211.8  448.54  5231.0  449.59
  5301.8  450.55  5331.8  451.79  5381.8  455.98  5431.8  462.87  5474.3  467.12
#Mann=3,-1,0
  4218.1    0.05       0  4982.0    0.03       0  4989.7    0.05       0
Bank Sta=4790.9,5231
Exp/Cntr=0.3,0.1

Chan Stop Cuts=-1