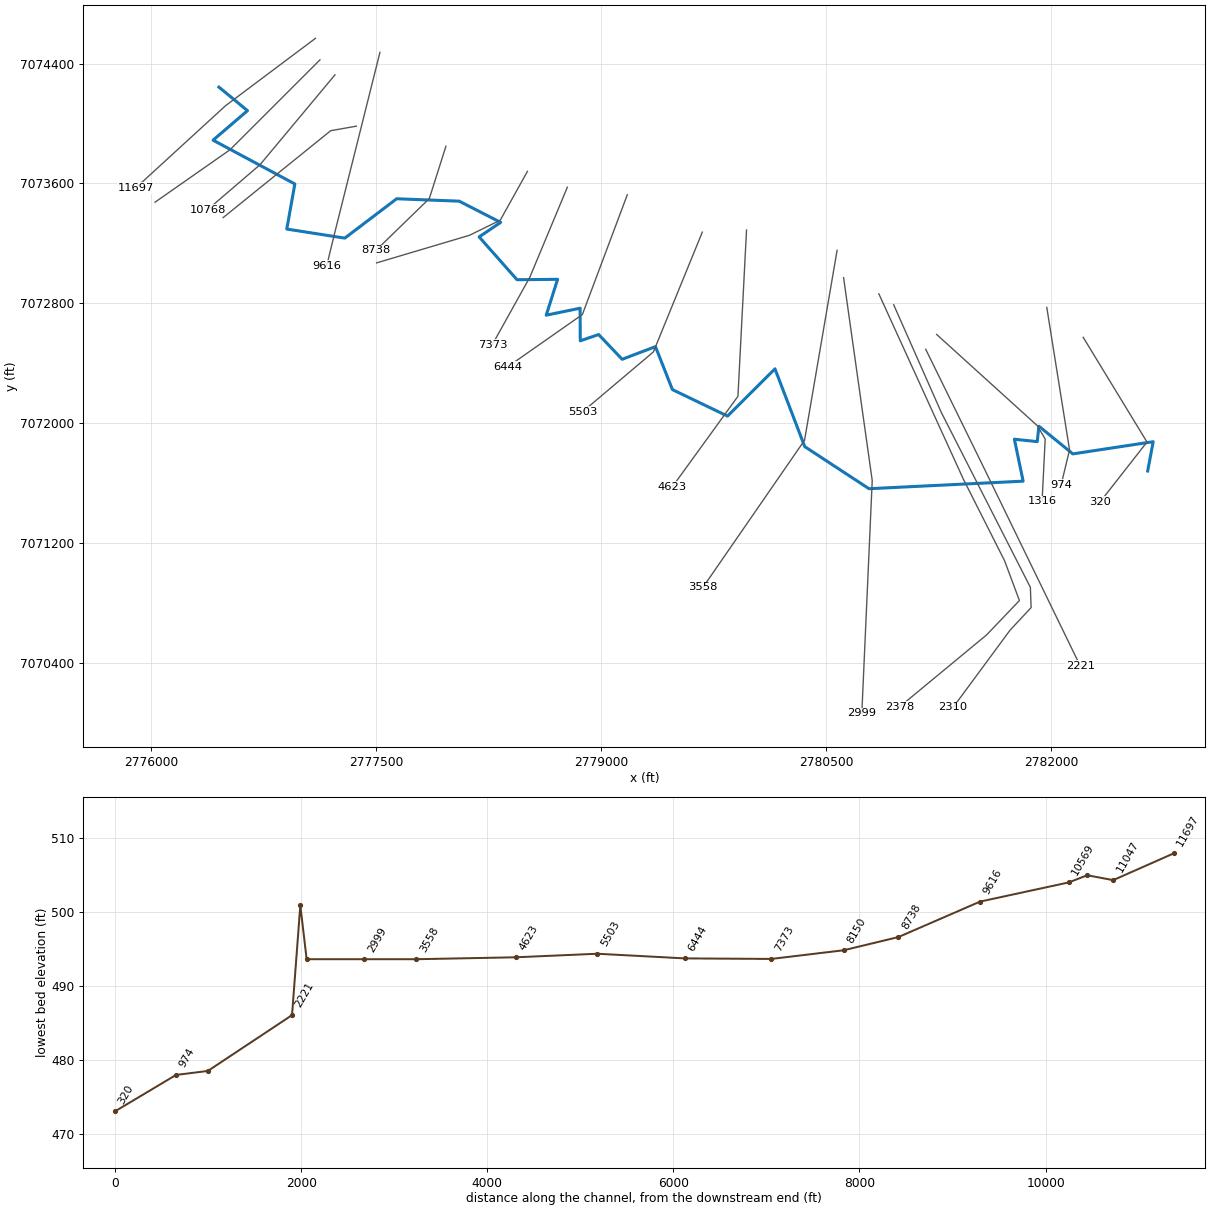
--- HUGHES CREEK.prj (project) ---

Proj Title=HUGHES CREEK Base Level Engineering
Current Plan=p01
Default Exp/Contr=0.3,0.1
English Units
Geom File=g01
Flow File=f01
Plan File=p01
BEGIN DESCRIPTION:
HUGHES CREEK
END DESCRIPTION:

--- HUGHES CREEK.p01 (plan) ---

Plan Title=Multiple Run
Short Identifier=Multiple
Geom File=g01
Flow File=f01
Subcritical Flow
K Sum by GR= 0
Std Step Tol= 0.01
Critical Tol= 0.01
Num of Std Step Trials= 20
Max Error Tol= 0.3
Flow Tol Ratio= 0.001
Split Flow NTrial= 30
Split Flow Tol= 0.02
Split Flow Ratio= 0.02
Log Output Level= 0
Friction Slope Method= 1
Unsteady Friction Slope Method= 2
Unsteady Bridges Friction Slope Method= 1
Parabolic Critical Depth
Global Vel Dist=  1 , 1 , 1
Global Log Level= 0
CheckData=True
Encroach Param= -1, 0, 0, 0
BEGIN DESCRIPTION:
Multiple Run
END DESCRIPTION:

--- HUGHES CREEK.f01 (steady flow) ---

Flow Title=Multiple
Number of Profiles=7
Profile Names=10-year,25-year,50-year,1pct_min,100-year,1pct_plu,500-year
River Rch & RM= HUGHES CREEK,Reach-1,11697
     778    1044    1258     751    1499    2991    2125
River Rch & RM= HUGHES CREEK,Reach-1,7373
    1233    1696    2079    1261    2515    5019    3677
Boundary for River Rch & Prof#=HUGHES CREEK,Reach-1,1
Up Type=0
Dn Type=3
Dn Slope=0.005
Boundary for River Rch & Prof#=HUGHES CREEK,Reach-1,2
Up Type=0
Dn Type=3
Dn Slope=0.005
Boundary for River Rch & Prof#=HUGHES CREEK,Reach-1,3
Up Type=0
Dn Type=3
Dn Slope=0.005
Boundary for River Rch & Prof#=HUGHES CREEK,Reach-1,4
Up Type=0
Dn Type=3
Dn Slope=0.005
Boundary for River Rch & Prof#=HUGHES CREEK,Reach-1,5
Up Type=0
Dn Type=3
Dn Slope=0.005
Boundary for River Rch & Prof#=HUGHES CREEK,Reach-1,6
Up Type=0
Dn Type=3
Dn Slope=0.005
Boundary for River Rch & Prof#=HUGHES CREEK,Reach-1,7
Up Type=0
Dn Type=3
Dn Slope=0.005

--- HUGHES CREEK.g01 (geometry) ---

Geom Title=Existing Conditions

River Reach=HUGHES CREEK,Reach-1
Reach XY= 30
      2776451.09      7074243.02      2776641.41      7074085.88
      2776412.02      7073888.86      2776957.35      7073596.57
      2776903.56      7073295.73      2777290.55      7073235.11
      2777636.58      7073497.92      2778053.60      7073481.77
      2778330.04      7073340.23      2778186.60      7073243.33
      2778439.28      7072957.40      2778710.02      7072960.25
      2778634.02      7072720.86      2778860.11      7072767.41
      2778861.06      7072549.87      2778983.60      7072591.67
      2779140.34      7072426.38      2779362.63      7072510.93
      2779475.67      7072224.04      2779843.30      7072047.35
      2780159.63      7072362.73      2780358.29      7071843.55
      2780786.79      7071562.57      2781814.94      7071613.02
      2781756.54      7071893.14      2781909.04      7071876.73
      2781919.90      7071979.92      2782146.48      7071795.06
      2782682.35      7071876.38      2782645.59      7071680.71

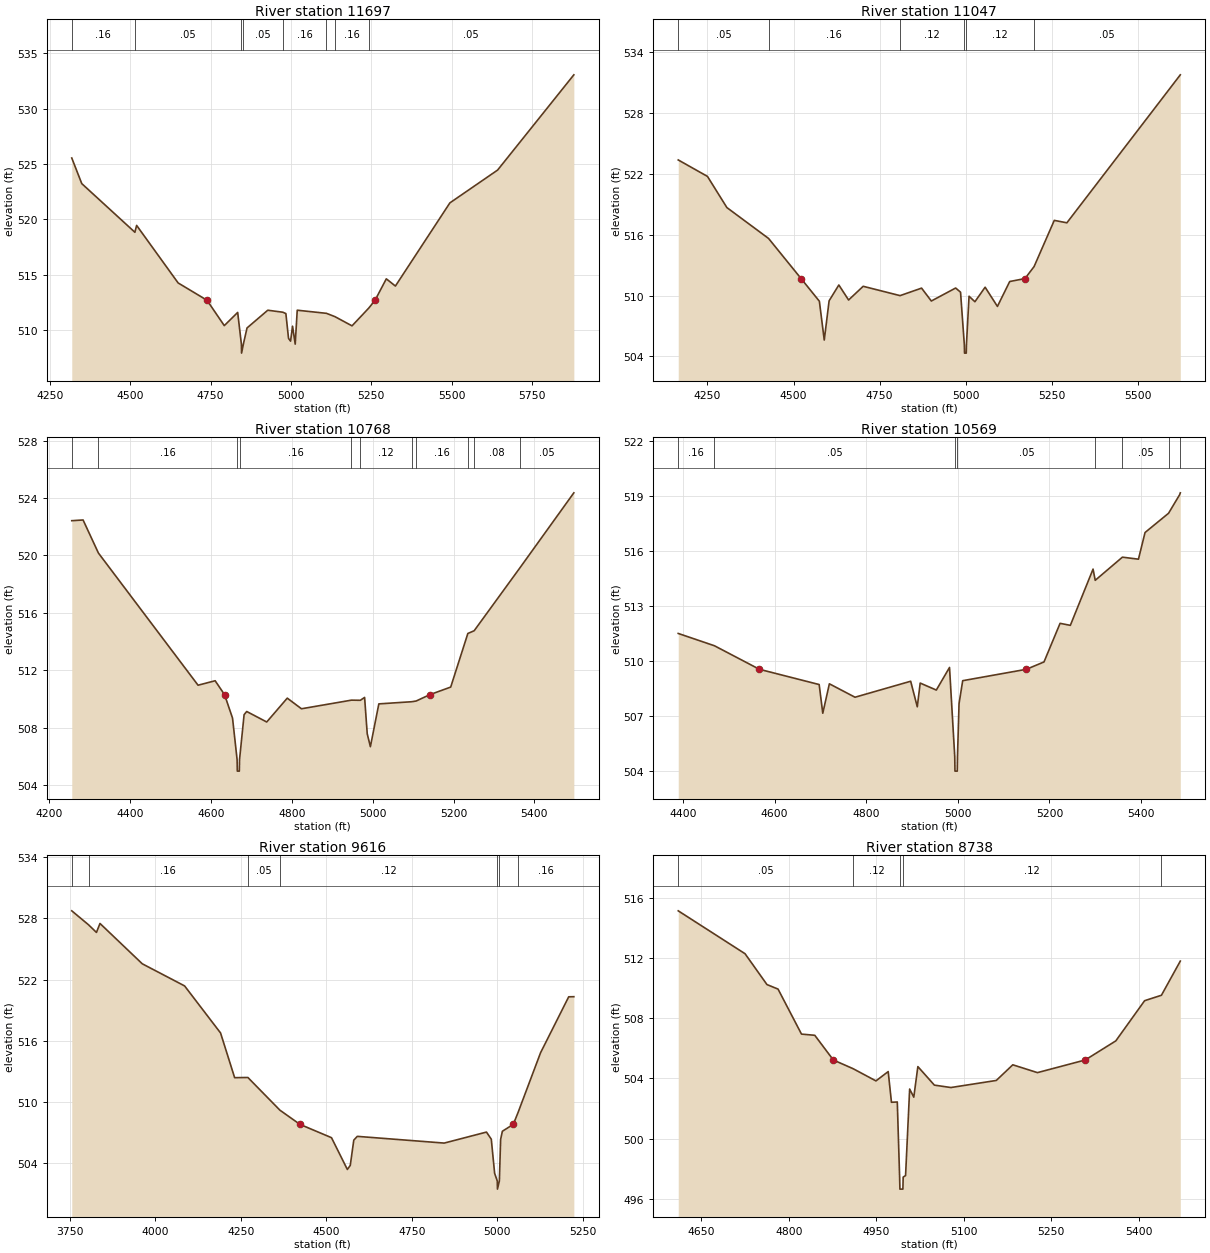
Type RM Length L Ch R = 1,11697,650,650,650
BEGIN DESCRIPTION:
HUGHES CREEK 11.0
END DESCRIPTION:
XS GIS Cut Line= 3
      2777094.83      7074568.64      2776494.80      7074118.62
      2775895.52      7073569.28
#Sta/Elev= 30
  4317.7  525.54  4348.8  523.23  4514.2  518.84  4519.6  519.46  4648.8  514.27
  4738.7  512.71  4792.5  510.42  4834.2  511.61  4845.8  508.74  4846.3  507.94
  4851.8  508.74  4863.3  510.21  4927.9  511.81  4974.6  511.63  4984.2  511.51
  4992.5  509.27  4998.8  509.02  5005.0  510.37  5013.3  508.75  5019.6  511.81
  5110.4  511.53  5137.0  511.23  5190.2  510.40  5241.9  511.99  5261.9  512.71
  5296.9  514.64  5325.2  513.99  5494.8  521.49  5643.4  524.45  5880.7  533.04
#Mann=8,-1,0
  4317.7    0.16       0  4514.2    0.05       0  4845.8    0.07       0
  4851.8    0.05       0  4974.6    0.16       0  5110.4    0.05       0
  5137.0    0.16       0  5241.9    0.05       0
Bank Sta=4738.7,5261.9
Exp/Cntr=0.3,0.1

Type RM Length L Ch R = 1,11047,279,279,279
BEGIN DESCRIPTION:
HUGHES CREEK 10.0
END DESCRIPTION:
XS GIS Cut Line= 3
      2777125.02      7074425.02      2776525.00      7073825.00
      2776024.99      7073474.99
#Sta/Elev= 30
  4165.0  523.35  4249.9  521.73  4306.4  518.66  4427.5  515.62  4522.0  511.67
  4575.1  509.44  4589.3  505.62  4603.4  509.48  4631.7  511.04  4660.0  509.56
  4702.4  510.91  4809.6  509.99  4872.1  510.73  4900.4  509.46  4971.1  510.74
  4985.3  510.33  4996.4  505.13  4996.9  504.33  5001.9  504.33  5002.4  505.13
  5010.0  509.93  5027.1  509.39  5056.7  510.82  5092.5  508.93  5128.2  511.38
  5172.5  511.67  5199.0  512.85  5257.7  517.40  5294.3  517.16  5623.9  531.73
#Mann=6,-1,0
  4165.0    0.05       0  4427.5    0.16       0  4809.6    0.12       0
  4996.4    0.07       0  5002.4    0.12       0  5199.0    0.05       0
Bank Sta=4522,5172.5
Exp/Cntr=0.3,0.1

Type RM Length L Ch R = 1,10768,199,199,199
BEGIN DESCRIPTION:
HUGHES CREEK 9.0
END DESCRIPTION:
XS GIS Cut Line= 3
      2777225.00      7074325.00      2776725.00      7073725.00
      2776375.01      7073425.00
#Sta/Elev= 30
  4255.5  522.42  4283.5  522.47  4321.4  520.17  4567.9  510.97  4610.2  511.28
  4633.5  510.31  4653.2  508.68  4664.5  505.79  4665.0  504.99  4670.0  504.99
  4670.5  505.79  4681.8  508.92  4688.3  509.14  4737.8  508.41  4788.6  510.07
  4823.7  509.33  4947.4  509.93  4969.4  509.92  4979.9  510.12  4986.4  507.59
  4994.2  506.69  5015.1  509.67  5096.3  509.82  5107.4  509.87  5141.1  510.31
  5192.9  510.84  5235.3  514.57  5250.9  514.76  5363.1  519.10  5497.5  524.36
#Mann=11,-1,0
  4255.5    0.05       0  4321.4    0.16       0  4664.5    0.07       0
  4670.5    0.16       0  4947.4    0.05       0  4969.4    0.12       0
  5096.3    0.05       0  5107.4    0.16       0  5235.3    0.05       0
  5250.9    0.08       0  5363.1    0.05       0
Bank Sta=4633.5,5141.1
Exp/Cntr=0.3,0.1

Type RM Length L Ch R = 1,10569,953,953,953
BEGIN DESCRIPTION:
Mapping XS 1775134d
END DESCRIPTION:
XS GIS Cut Line= 4
      2777367.70      7073982.40      2777196.56      7073952.20
      2776864.35      7073683.75      2776479.23      7073372.30
#Sta/Elev= 30
  4389.5  511.51  4468.6  510.84  4566.7  509.56  4697.2  508.73  4705.1  507.17
  4719.5  508.77  4775.5  508.04  4897.0  508.91  4911.4  507.52  4917.8  508.81
  4953.0  508.43  4981.8  509.66  4993.2  504.82  4993.7  504.02  4998.7  504.02
  4999.2  504.82  5002.6  507.69  5010.6  508.94  5149.7  509.56  5188.1  509.96
  5223.2  512.06  5245.6  511.95  5295.2  515.01  5299.9  514.40  5359.3  515.66
  5394.3  515.55  5408.7  517.00  5460.1  518.05  5484.3  519.06  5485.7  519.16
#Mann=8,-1,0
  4389.5    0.16       0  4468.6    0.05       0  4993.2    0.04       0
  4999.2    0.05       0  5299.9    0.16       0  5359.3    0.05       0
  5460.1    0.16       0  5484.3    0.08       0
Bank Sta=4566.7,5149.7
Exp/Cntr=0.3,0.1

Type RM Length L Ch R = 1,9616,878,878,878
BEGIN DESCRIPTION:
HUGHES CREEK 8.0
END DESCRIPTION:
XS GIS Cut Line= 3
      2777525.00      7074475.01      2777223.40      7073271.00
      2777169.92      7073050.40
#Sta/Elev= 30
  3755.3  528.75  3804.3  527.38  3827.5  526.63  3837.8  527.51  3961.5  523.55
  4085.2  521.38  4190.4  516.76  4231.6  512.37  4270.3  512.39  4364.0  509.18
  4422.4  507.79  4514.8  506.48  4561.2  503.36  4569.7  503.76  4580.0  506.24
  4590.3  506.61  4844.4  505.95  4968.0  507.03  4982.1  506.33  4991.9  502.98
  4999.6  502.23  5000.1  501.43  5005.7  502.23  5009.4  506.31  5014.5  507.11
  5046.4  507.79  5059.8  508.90  5126.2  514.82  5208.5  520.31  5223.5  520.32
#Mann=7,-1,0
  3755.3    0.05       0  3804.3    0.16       0  4270.3    0.05       0
  4364.0    0.12       0  4999.6    0.07       0  5005.7    0.12       0
  5059.8    0.16       0
Bank Sta=4422.4,5046.4
Exp/Cntr=0.3,0.1

Type RM Length L Ch R = 1,8738,588,588,588
BEGIN DESCRIPTION:
Mapping XS a2f69a37
END DESCRIPTION:
XS GIS Cut Line= 3
      2777965.01      7073848.21      2777854.26      7073499.19
      2777499.31      7073154.28
#Sta/Elev= 30
  4610.2  515.13  4724.8  512.28  4762.4  510.23  4781.4  509.93  4821.6  506.94
  4844.4  506.86  4876.2  505.22  4910.2  504.64  4949.3  503.83  4970.3  504.45
  4975.9  502.41  4985.9  502.43  4989.9  497.44  4990.4  496.64  4995.5  496.64
  4996.0  497.44  5000.1  497.54  5007.1  503.29  5014.2  502.75  5021.2  504.78
  5049.5  503.55  5077.8  503.39  5155.7  503.86  5184.0  504.90  5226.3  504.38
  5308.2  505.22  5360.7  506.49  5410.1  509.16  5438.9  509.52  5471.3  511.79
#Mann=5,-1,0
  4610.2    0.05       0  4910.2    0.12       0  4989.9    0.07       0
  4996.0    0.12       0  5438.9    0.16       0
Bank Sta=4876.2,5308.2
Exp/Cntr=0.3,0.1

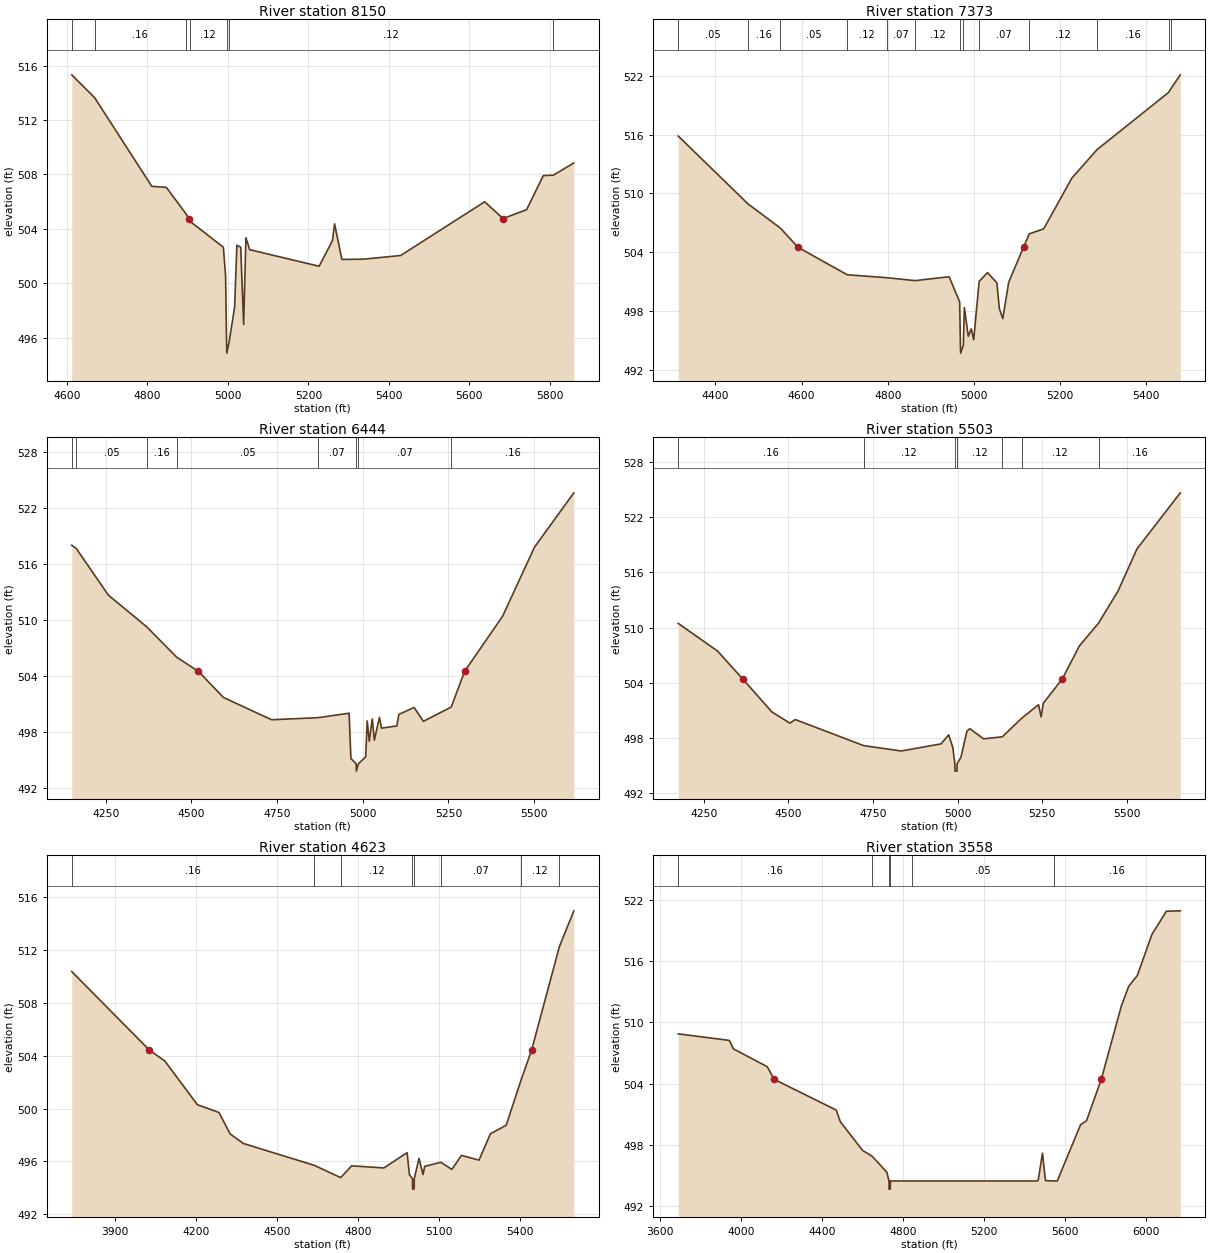
Type RM Length L Ch R = 1,8150,777,777,777
BEGIN DESCRIPTION:
Mapping XS 64270129
END DESCRIPTION:
XS GIS Cut Line= 4
      2778508.61      7073680.39      2778327.41      7073354.89
      2778122.72      7073254.22      2777502.49      7073069.83
#Sta/Elev= 30
  4611.9  515.33  4668.5  513.66  4810.8  507.13  4847.0  507.05  4895.4  505.12
  4903.1  504.76  4905.5  504.56  4988.6  502.65  4994.1  500.58  4996.6  495.66
  4997.1  494.86  5002.8  495.66  5016.6  498.25  5022.2  502.79  5031.7  502.66
  5039.1  496.97  5044.6  503.35  5054.0  502.47  5226.6  501.25  5259.8  503.14
  5265.0  504.37  5283.2  501.75  5336.6  501.77  5429.2  502.04  5637.9  505.99
  5683.8  504.76  5742.2  505.41  5783.8  507.92  5808.7  507.95  5859.6  508.85
#Mann=7,-1,0
  4611.9    0.05       0  4668.5    0.16       0  4895.4    0.05       0
  4905.5    0.12       0  4996.6    0.07       0  5002.8    0.12       0
  5808.7    0.16       0
Bank Sta=4903.1,5683.8
Exp/Cntr=0.3,0.1

Type RM Length L Ch R = 1,7373,929,929,929
BEGIN DESCRIPTION:
HUGHES CREEK 5.0
END DESCRIPTION:
XS GIS Cut Line= 3
      2778775.01      7073575.02      2778525.00      7072975.00
      2778275.00      7072525.00
#Sta/Elev= 30
  4314.0  515.85  4475.7  508.93  4550.8  506.46  4591.7  504.50  4706.0  501.69
  4798.2  501.39  4863.4  501.09  4942.4  501.49  4966.9  498.93  4968.7  494.49
  4969.2  493.69  4975.4  494.49  4977.8  498.34  4986.9  495.41  4993.8  496.17
  4999.5  495.06  5012.1  501.01  5031.5  501.91  5053.3  500.86  5059.0  498.22
  5067.0  497.21  5080.7  500.93  5115.1  504.50  5128.4  505.86  5161.9  506.38
  5227.1  511.55  5285.5  514.46  5451.5  520.30  5458.0  520.75  5478.8  522.10
#Mann=13,-1,0
  4314.0    0.05       0  4475.7    0.16       0  4550.8    0.05       0
  4706.0    0.12       0  4798.2    0.07       0  4863.4    0.12       0
  4968.7    0.07       0  4975.4    0.12       0  5012.1    0.07       0
  5128.4    0.12       0  5285.5    0.16       0  5451.5    0.12       0
  5458.0    0.16       0
Bank Sta=4591.7,5115.1
Exp/Cntr=0.3,0.1

Type RM Length L Ch R = 1,6444,941,941,941
BEGIN DESCRIPTION:
HUGHES CREEK 4.0
END DESCRIPTION:
XS GIS Cut Line= 3
      2779175.02      7073525.04      2778875.00      7072725.00
      2778374.98      7072374.98
#Sta/Elev= 30
  4151.1  517.98  4164.3  517.63  4257.9  512.63  4369.2  509.25  4457.4  505.97
  4520.8  504.45  4593.5  501.66  4734.1  499.27  4869.6  499.49  4960.2  499.97
  4965.5  495.11  4980.8  494.56  4981.3  493.76  4987.6  494.56  5008.6  495.29
  5013.0  499.14  5019.1  496.97  5027.8  499.36  5033.9  497.08  5048.7  499.53
  5054.8  498.37  5099.3  498.60  5105.4  499.84  5149.8  500.59  5176.9  499.10
  5258.2  500.63  5297.1  504.45  5408.4  510.39  5501.2  517.78  5615.9  523.60
#Mann=8,-1,0
  4151.1    0.16       0  4164.3    0.05       0  4369.2    0.16       0
  4457.4    0.05       0  4869.6    0.07       0  4980.8    0.07       0
  4987.6    0.07       0  5258.2    0.16       0
Bank Sta=4520.8,5297.1
Exp/Cntr=0.3,0.1

Type RM Length L Ch R = 1,5503,880,880,880
BEGIN DESCRIPTION:
HUGHES CREEK 3.0
END DESCRIPTION:
XS GIS Cut Line= 3
      2779674.99      7073274.98      2779348.97      7072475.81
      2778875.03      7072075.02
#Sta/Elev= 30
  4174.3  510.45  4290.5  507.44  4364.3  504.43  4451.0  500.83  4504.4  499.60
  4519.9  500.00  4722.5  497.16  4833.1  496.58  4950.9  497.35  4973.5  498.33
  4985.7  496.98  4991.7  495.19  4992.2  494.39  4998.0  494.39  4998.5  495.19
  5009.8  495.90  5027.5  498.73  5036.1  499.01  5076.4  497.90  5132.0  498.12
  5190.3  500.17  5239.1  501.61  5246.7  500.29  5253.2  501.77  5309.6  504.43
  5359.8  508.00  5416.4  510.47  5474.1  513.97  5530.1  518.55  5658.1  524.64
#Mann=7,-1,0
  4174.3    0.16       0  4722.5    0.12       0  4991.7    0.07       0
  4998.5    0.12       0  5132.0    0.07       0  5190.3    0.12       0
  5416.4    0.16       0
Bank Sta=4364.3,5309.6
Exp/Cntr=0.3,0.1

Type RM Length L Ch R = 1,4623,1065,1065,1065
BEGIN DESCRIPTION:
HUGHES CREEK 2.0
END DESCRIPTION:
XS GIS Cut Line= 3
      2779970.02      7073288.97      2779912.73      7072179.63
      2779474.98      7071574.97
#Sta/Elev= 30
  3740.5  510.35  4027.4  504.42  4084.9  503.59  4205.1  500.29  4285.2  499.70
  4326.4  498.08  4375.3  497.36  4637.2  495.71  4735.3  494.78  4775.8  495.67
  4895.2  495.51  4981.0  496.67  4989.5  495.00  5000.8  494.71  5001.3  493.91
  5007.1  493.91  5007.6  494.71  5025.1  496.24  5039.8  495.01  5046.0  495.63
  5106.1  495.94  5146.5  495.40  5182.1  496.46  5247.0  496.10  5289.1  498.09
  5347.6  498.74  5401.5  502.09  5441.6  504.42  5544.4  512.24  5597.8  514.94
#Mann=8,-1,0
  3740.5    0.16       0  4637.2    0.07       0  4735.3    0.12       0
  5000.8    0.07       0  5007.6    0.12       0  5106.1    0.07       0
  5401.5    0.12       0  5544.4    0.16       0
Bank Sta=4027.4,5441.6
Exp/Cntr=0.3,0.1

Type RM Length L Ch R = 1,3558,559,559,559
BEGIN DESCRIPTION:
Mapping XS 2c045f58
END DESCRIPTION:
XS GIS Cut Line= 3
      2780574.03      7073153.45      2780357.01      7071886.04
      2779679.95      7070905.18
#Sta/Elev= 30
  3690.3  508.87  3942.4  508.23  3962.7  507.40  4129.5  505.65  4163.8  504.41
  4469.9  501.40  4490.2  500.26  4599.8  497.45  4648.1  496.86  4720.0  495.30
  4730.3  494.45  4730.8  493.65  4736.7  493.65  4737.2  494.45  4841.8  494.45
  5460.6  494.45  5466.7  494.52  5487.8  497.17  5502.5  494.48  5545.0  494.45
  5560.7  494.45  5675.6  499.95  5705.3  500.36  5778.0  504.41  5876.6  511.57
  5913.0  513.52  5956.1  514.60  6027.8  518.61  6099.4  520.89  6168.0  520.93
#Mann=6,-1,0
  3690.3    0.16       0  4648.1    0.07       0  4730.3   0.033       0
  4737.2    0.07       0  4841.8    0.05       0  5545.0    0.16       0
Bank Sta=4163.8,5778
Exp/Cntr=0.3,0.1

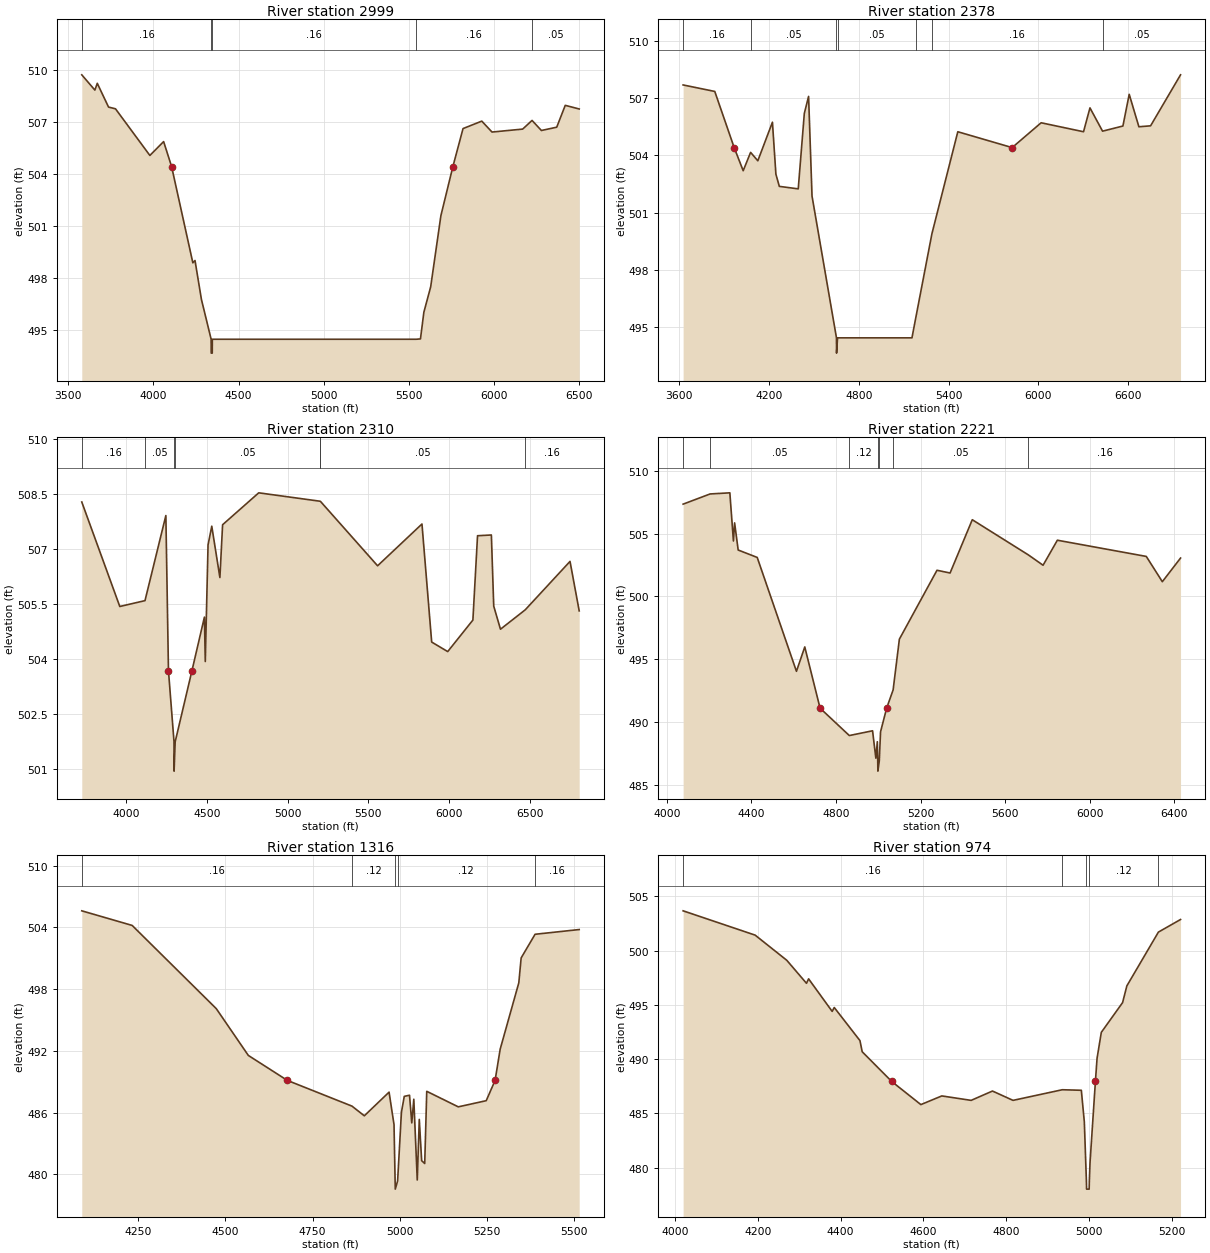
Type RM Length L Ch R = 1,2999,621,621,621
BEGIN DESCRIPTION:
Mapping XS c2f02f88
END DESCRIPTION:
XS GIS Cut Line= 3
      2780617.42      7072971.16      2780808.39      7071616.95
      2780738.95      7070063.11
#Sta/Elev= 30
  3579.1  509.70  3656.0  508.82  3670.2  509.21  3736.3  507.84  3777.2  507.74
  3979.2  505.05  4060.0  505.85  4106.9  504.41  4231.7  498.86  4244.5  498.99
  4282.1  496.75  4339.2  494.45  4339.7  493.65  4345.7  493.65  4346.3  494.45
  5544.0  494.45  5569.3  494.47  5589.3  496.01  5629.3  497.47  5689.4  501.58
  5759.9  504.41  5819.5  506.60  5929.6  507.03  5989.7  506.40  6169.9  506.57
  6225.0  507.07  6280.0  506.49  6370.1  506.68  6420.1  507.94  6502.1  507.73
#Mann=5,-1,0
  3579.1    0.16       0  4339.2   0.033       0  4346.3    0.16       0
  5544.0    0.16       0  6225.0    0.05       0
Bank Sta=4106.9,5759.9
Exp/Cntr=0.3,0.1

Type RM Length L Ch R = 1,2378,68,68,68
BEGIN DESCRIPTION:
Mapping XS 87ec5f5e
END DESCRIPTION:
XS GIS Cut Line= 6
      2780852.65      7072863.07      2781415.17      7071628.66
      2781691.21      7071081.79      2781790.17      7070816.16
      2781571.42      7070587.00      2780990.83      7070106.69
#Sta/Elev= 30
  3626.5  507.69  3837.9  507.35  3967.5  504.41  4027.8  503.20  4077.3  504.16
  4125.5  503.72  4223.1  505.74  4246.2  503.02  4269.2  502.38  4395.5  502.25
  4436.1  506.20  4464.6  507.09  4487.6  501.87  4650.9  494.45  4651.4  493.65
  4658.1  494.45  5155.2  494.45  5180.2  495.48  5288.5  499.90  5461.5  505.24
  5824.5  504.41  6018.1  505.71  6301.3  505.24  6344.3  506.49  6428.4  505.27
  6564.4  505.54  6606.5  507.20  6671.2  505.50  6749.3  505.55  6949.4  508.22
#Mann=7,-1,0
  3626.5    0.16       0  4077.3    0.05       0  4650.9   0.033       0
  4658.1    0.05       0  5180.2    0.12       0  5288.5    0.16       0
  6428.4    0.05       0
Bank Sta=3967.5,5824.5
Exp/Cntr=0.3,0.1

Type RM Length L Ch R = 1,2310,89,89,89
BEGIN DESCRIPTION:
Mapping XS 462b6ce7
END DESCRIPTION:
XS GIS Cut Line= 6
      2780951.61      7072790.15      2781269.33      7072071.37
      2781863.08      7070904.71      2781868.29      7070769.29
      2781727.67      7070618.25      2781347.48      7070102.65
#Sta/Elev= 30
  3727.0  508.27  3962.2  505.42  4118.1  505.58  4247.2  507.90  4263.3  503.67
  4297.6  501.73  4298.1  500.93  4304.8  501.73  4408.7  503.67  4485.7  505.13
  4491.1  503.92  4508.2  507.10  4531.2  507.61  4581.5  506.21  4598.2  507.65
  4821.8  508.52  5202.7  508.29  5203.0  508.29  5557.1  506.53  5831.7  507.67
  5891.8  504.45  5991.0  504.19  6146.8  505.05  6175.5  507.35  6261.1  507.37
  6275.7  505.43  6317.4  504.80  6470.8  505.33  6747.7  506.65  6804.5  505.30
#Mann=7,-1,0
  3727.0    0.16       0  4118.1    0.05       0  4297.6    0.04       0
  4304.8    0.05       0  5202.7    0.12       0  5203.0    0.05       0
  6470.8    0.16       0
Bank Sta=4263.3,4408.7
Exp/Cntr=0.3,0.1

Type RM Length L Ch R = 1,2221,905,905,905
BEGIN DESCRIPTION:
Mapping XS 68248855
END DESCRIPTION:
XS GIS Cut Line= 3
      2781165.17      7072493.24      2781561.00      7071685.96
      2782196.09      7070379.33
#Sta/Elev= 30
  4077.2  507.34  4204.7  508.15  4298.1  508.24  4315.0  504.41  4320.6  505.85
  4337.5  503.69  4427.5  503.10  4613.0  494.04  4652.4  495.98  4724.7  491.11
  4863.0  488.93  4972.9  489.31  4988.5  487.13  4995.5  488.44  4997.4  486.90
  4998.0  486.10  5004.6  486.90  5010.7  489.23  5039.5  491.11  5070.1  492.56
  5099.7  496.60  5277.6  502.08  5339.4  501.86  5444.4  506.10  5709.7  503.30
  5779.1  502.48  5846.7  504.47  6267.1  503.18  6343.0  501.17  6429.1  503.05
#Mann=7,-1,0
  4077.2    0.16       0  4204.7    0.05       0  4863.0    0.12       0
  4997.4    0.07       0  5004.6    0.12       0  5070.1    0.05       0
  5709.7    0.16       0
Bank Sta=4724.7,5039.5
Exp/Cntr=0.3,0.1

Type RM Length L Ch R = 1,1316,342,342,342
BEGIN DESCRIPTION:
Mapping XS a3dbbdce
END DESCRIPTION:
XS GIS Cut Line= 4
      2781238.07      7072592.22      2781909.96      7071982.83
      2781962.04      7071894.29      2781941.27      7071478.81
#Sta/Elev= 30
  4088.4  505.62  4232.8  504.20  4473.9  496.11  4565.8  491.56  4677.7  489.13
  4862.9  486.63  4898.3  485.69  4969.2  487.99  4983.4  484.83  4986.5  479.36
  4987.0  478.56  4993.7  479.36  5004.6  486.03  5012.8  487.58  5027.8  487.69
  5034.3  485.00  5040.1  487.30  5050.0  479.45  5055.8  485.34  5062.6  481.33
  5071.4  481.05  5077.2  488.07  5167.6  486.56  5247.7  487.16  5273.1  489.13
  5287.7  492.17  5341.1  498.62  5347.8  501.04  5387.7  503.34  5514.2  503.80
#Mann=5,-1,0
  4088.4    0.16       0  4862.9    0.12       0  4986.5    0.07       0
  4993.7    0.12       0  5387.7    0.16       0
Bank Sta=4677.7,5273.1
Exp/Cntr=0.3,0.1

Type RM Length L Ch R = 1,974,654,654,654
BEGIN DESCRIPTION:
Mapping XS b83f0fed
END DESCRIPTION:
XS GIS Cut Line= 3
      2781972.63      7072772.50      2782124.54      7071821.99
      2782068.40      7071588.83
#Sta/Elev= 30
  4019.4  503.67  4193.5  501.43  4270.0  499.11  4317.6  496.99  4322.7  497.40
  4379.7  494.40  4384.7  494.76  4446.8  491.71  4452.3  490.68  4523.7  487.94
  4594.1  485.81  4644.7  486.61  4715.6  486.20  4767.2  487.06  4816.9  486.20
  4935.9  487.18  4982.0  487.13  4989.2  484.23  4994.2  478.82  4994.7  478.02
  5000.9  478.02  5001.4  478.82  5003.0  480.47  5016.0  487.94  5020.0  490.08
  5030.3  492.47  5081.7  495.21  5092.0  496.75  5168.3  501.71  5221.8  502.87
#Mann=5,-1,0
  4019.4    0.16       0  4935.9    0.12       0  4994.2    0.07       0
  5001.4    0.12       0  5168.3    0.16       0
Bank Sta=4523.7,5016
Exp/Cntr=0.3,0.1

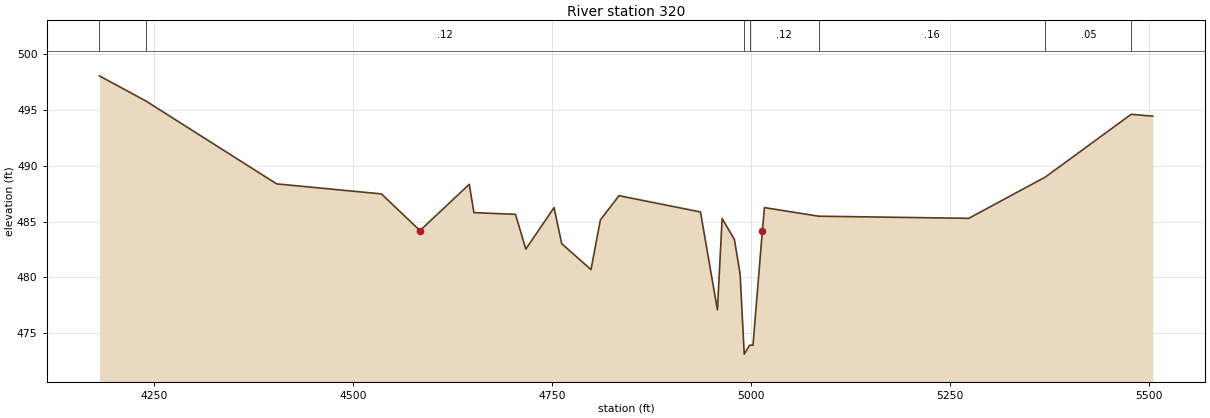
Type RM Length L Ch R = 1,320,0,0,0
BEGIN DESCRIPTION:
HUGHES CREEK 1.0
END DESCRIPTION:
XS GIS Cut Line= 3
      2782215.69      7072572.85      2782641.03      7071874.07
      2782329.27      7071475.72
#Sta/Elev= 30
  4180.7  498.08  4239.3  495.82  4403.5  488.39  4535.2  487.49  4583.7  484.20
  4645.6  488.35  4651.5  485.81  4703.7  485.66  4716.7  482.54  4752.2  486.26
  4761.8  483.03  4798.6  480.70  4810.4  485.16  4833.8  487.33  4936.2  485.87
  4957.5  477.09  4963.4  485.28  4978.8  483.41  4986.0  480.32  4990.6  473.92
  4991.2  473.12  4997.9  473.92  5002.2  473.92  5014.0  484.20  5016.6  486.26
  5084.8  485.49  5273.4  485.30  5369.8  489.01  5477.5  494.63  5504.6  494.46
#Mann=7,-1,0
  4180.7    0.16       0  4239.3    0.12       0  4990.6    0.07       0
  4997.9    0.12       0  5084.8    0.16       0  5369.8    0.05       0
  5477.5    0.16       0
Bank Sta=4583.7,5014
Exp/Cntr=0.3,0.1

Chan Stop Cuts=-1