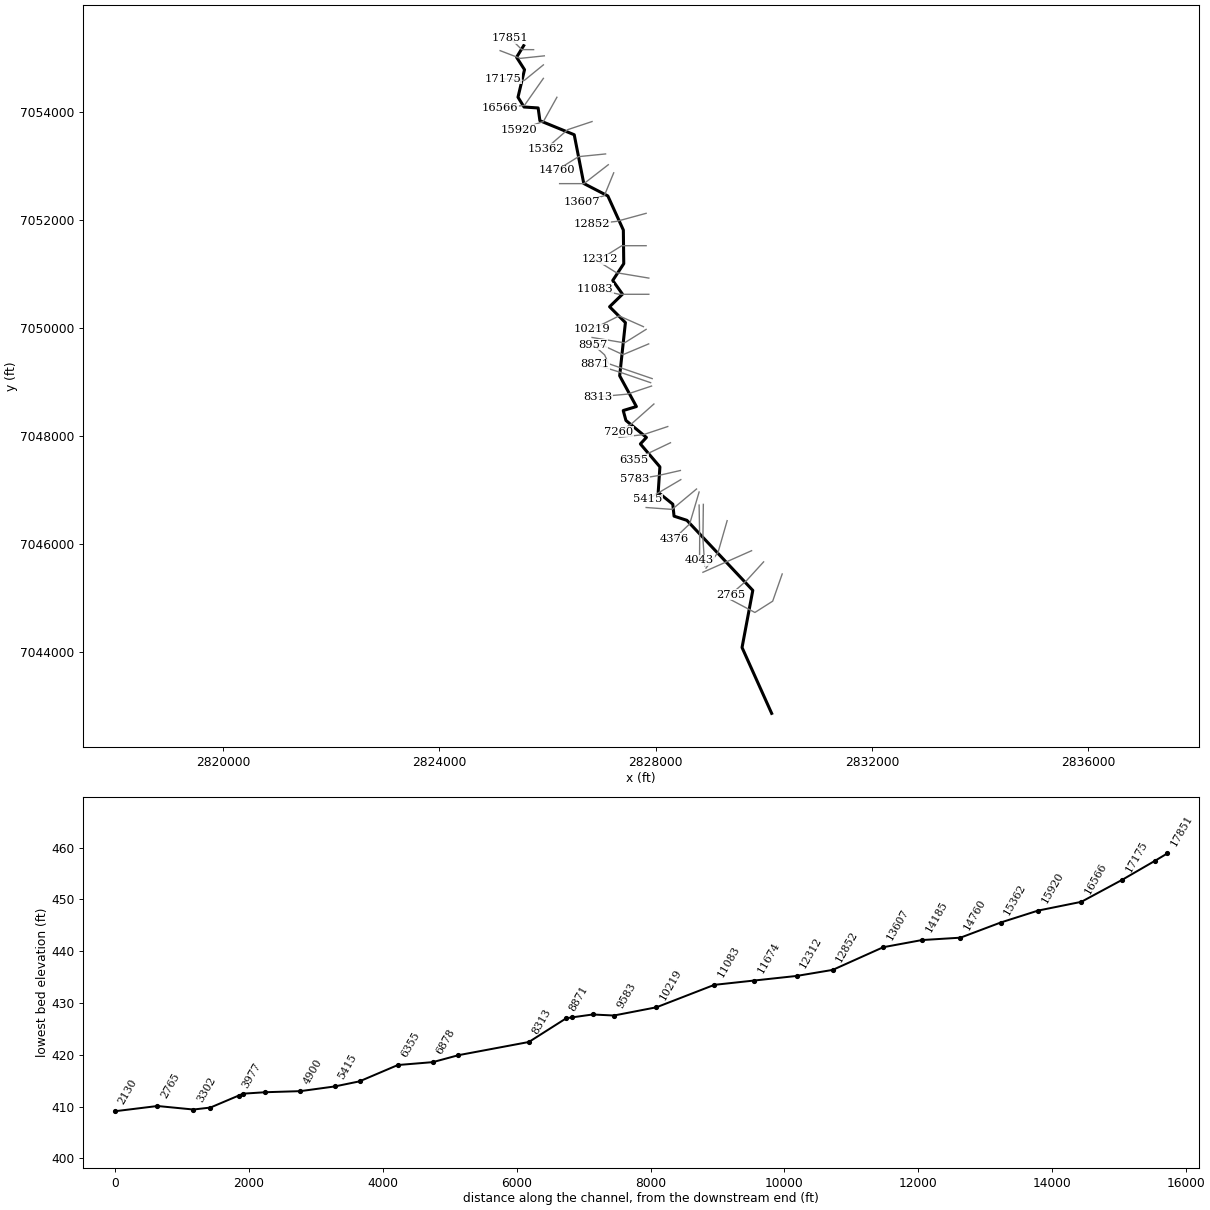
--- ISHMEAL BRANCH.prj (project) ---

Proj Title=ISHMEAL BRANCH Base Level Engineering
Current Plan=p01
Default Exp/Contr=0.3,0.1
English Units
Geom File=g01
Flow File=f01
Plan File=p01
BEGIN DESCRIPTION:
ISHMEAL BRANCH
END DESCRIPTION:

--- ISHMEAL BRANCH.p01 (plan) ---

Plan Title=Multiple Run
Short Identifier=Multiple
Geom File=g01
Flow File=f01
Subcritical Flow
K Sum by GR= 0
Std Step Tol= 0.01
Critical Tol= 0.01
Num of Std Step Trials= 20
Max Error Tol= 0.3
Flow Tol Ratio= 0.001
Split Flow NTrial= 30
Split Flow Tol= 0.02
Split Flow Ratio= 0.02
Log Output Level= 0
Friction Slope Method= 1
Unsteady Friction Slope Method= 2
Unsteady Bridges Friction Slope Method= 1
Parabolic Critical Depth
Global Vel Dist=  1 , 1 , 1
Global Log Level= 0
CheckData=True
Encroach Param= -1, 0, 0, 0
BEGIN DESCRIPTION:
Multiple Run
END DESCRIPTION:

--- ISHMEAL BRANCH.f01 (steady flow) ---

Flow Title=Multiple
Number of Profiles=7
Profile Names=10-year,25-year,50-year,1pct_min,100-year,1pct_plu,500-year
River Rch & RM= ISHMEAL BRANCH,Reach-1,17851
     601     798     956     569    1135    2265    1597
River Rch & RM= ISHMEAL BRANCH,Reach-1,17666
     875    1187    1443     870    1736    3464    2514
River Rch & RM= ISHMEAL BRANCH,Reach-1,10219
    1137    1564    1919    1167    2328    4645    3431
River Rch & RM= ISHMEAL BRANCH,Reach-1,3302
    1200    1652    2028    1233    2461    4910    3629
Boundary for River Rch & Prof#=ISHMEAL BRANCH,Reach-1,1
Up Type=0
Dn Type=3
Dn Slope=0.005
Boundary for River Rch & Prof#=ISHMEAL BRANCH,Reach-1,2
Up Type=0
Dn Type=3
Dn Slope=0.005
Boundary for River Rch & Prof#=ISHMEAL BRANCH,Reach-1,3
Up Type=0
Dn Type=3
Dn Slope=0.005
Boundary for River Rch & Prof#=ISHMEAL BRANCH,Reach-1,4
Up Type=0
Dn Type=3
Dn Slope=0.005
Boundary for River Rch & Prof#=ISHMEAL BRANCH,Reach-1,5
Up Type=0
Dn Type=3
Dn Slope=0.005
Boundary for River Rch & Prof#=ISHMEAL BRANCH,Reach-1,6
Up Type=0
Dn Type=3
Dn Slope=0.005
Boundary for River Rch & Prof#=ISHMEAL BRANCH,Reach-1,7
Up Type=0
Dn Type=3
Dn Slope=0.005

--- ISHMEAL BRANCH.g01 (geometry) ---

Geom Title=Existing Conditions

River Reach=ISHMEAL BRANCH,Reach-1
Reach XY= 30
      2825560.69      7055230.91      2825429.39      7055016.04
      2825576.03      7054785.82      2825455.44      7054275.92
      2825567.03      7054094.24      2825828.00      7054076.78
      2825860.57      7053840.79      2826495.18      7053580.69
      2826671.69      7052677.73      2827116.63      7052447.25
      2827403.66      7051814.98      2827411.11      7051191.78
      2827207.57      7050881.19      2827387.73      7050627.53
      2827149.10      7050394.21      2827441.62      7050100.48
      2827335.59      7049115.03      2827644.81      7048545.30
      2827401.21      7048471.48      2827451.62      7048287.66
      2827830.07      7047973.05      2827718.55      7047852.86
      2828079.63      7047427.51      2828047.81      7046955.66
      2828317.67      7046736.94      2828341.00      7046515.17
      2828578.92      7046437.23      2829797.14      7045139.85
      2829598.42      7044081.41      2830146.16      7042861.38

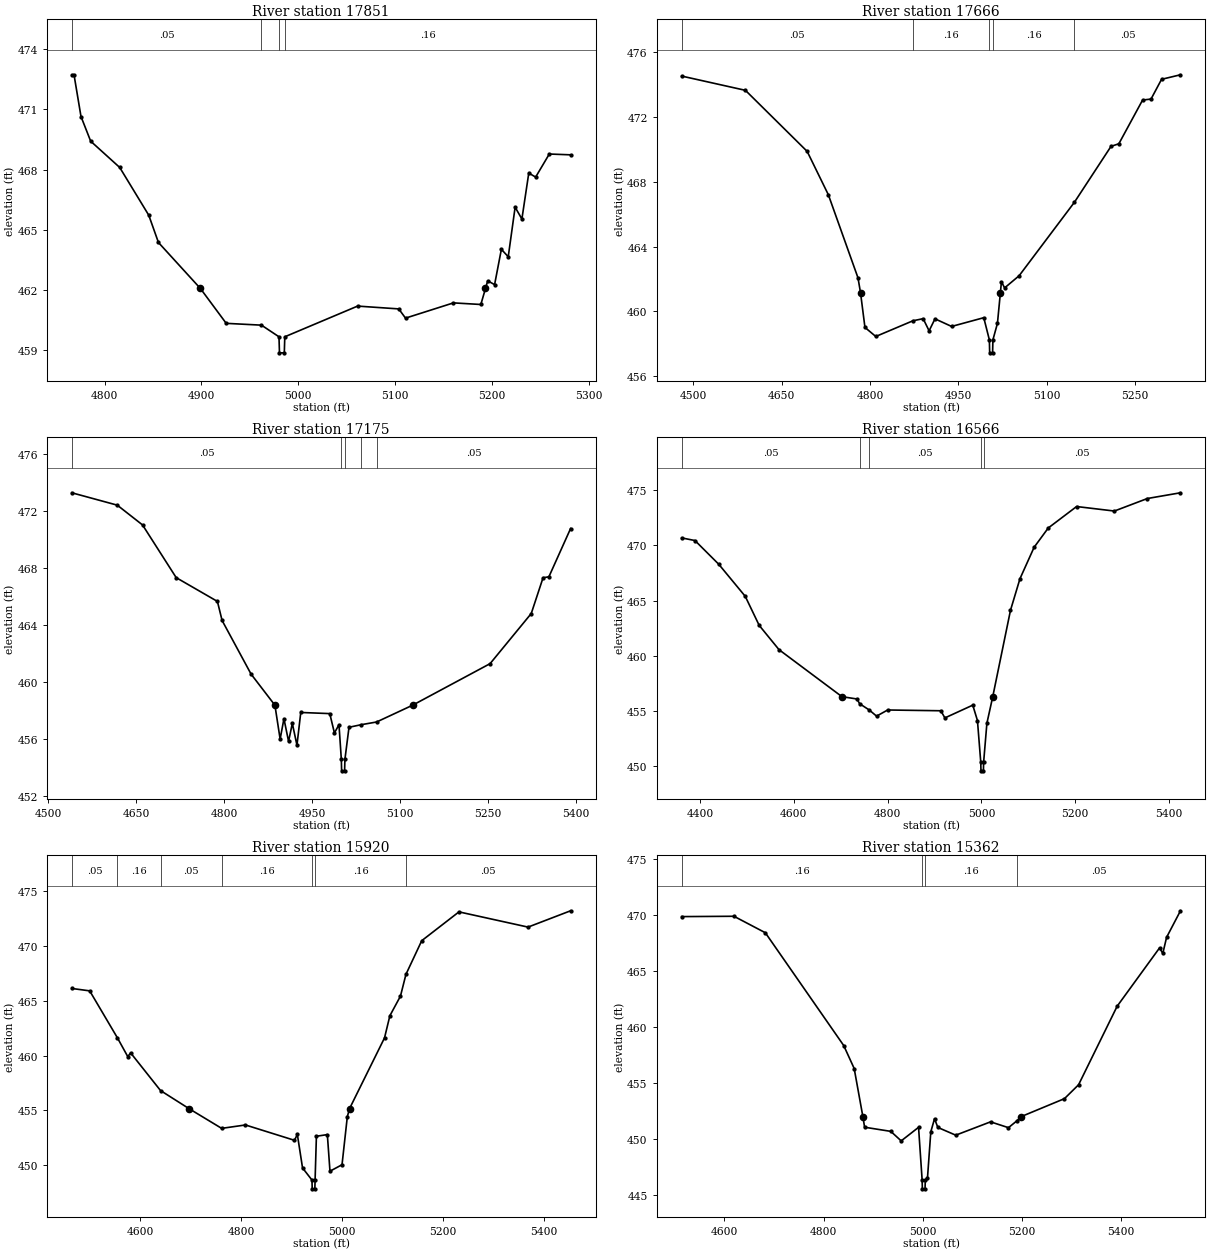
Type RM Length L Ch R = 1,17851,185,185,185
BEGIN DESCRIPTION:
ISHMEAL BRANCH 25.0
END DESCRIPTION:
XS GIS Cut Line= 3
      2825744.47      7055156.76      2825525.00      7055157.85
      2825315.47      7055366.54
#Sta/Elev= 30
  4766.2  472.73  4768.5  472.73  4775.7  470.65  4785.7  469.42  4815.7  468.11
  4845.7  465.73  4855.7  464.37  4899.0  462.08  4925.7  460.34  4962.1  460.25
  4980.2  459.67  4980.7  458.87  4985.7  458.87  4986.2  459.67  5061.4  461.20
  5103.9  461.06  5110.9  460.60  5160.4  461.36  5188.7  461.28  5193.5  462.08
  5195.8  462.46  5202.9  462.27  5209.9  464.03  5217.0  463.66  5224.1  466.13
  5231.1  465.54  5238.2  467.83  5245.3  467.63  5259.4  468.78  5281.4  468.74
#Mann=4,-1,0
  4766.2    0.05       0  4962.1    0.16       0  4980.2    0.07       0
  4986.2    0.16       0
Bank Sta=4899,5193.5
Exp/Cntr=0.3,0.1

Type RM Length L Ch R = 1,17666,491,491,491
BEGIN DESCRIPTION:
Mapping XS 526353df
END DESCRIPTION:
XS GIS Cut Line= 3
      2825942.64      7055042.22      2825497.36      7054995.34
      2825125.00      7055138.56
#Sta/Elev= 30
  4480.4  474.53  4588.6  473.65  4693.4  469.88  4729.4  467.20  4779.7  462.07
  4784.0  461.15  4791.5  459.01  4809.9  458.45  4873.0  459.42  4890.3  459.55
  4900.4  458.80  4910.4  459.54  4938.6  459.07  4993.2  459.61  5002.7  458.24
  5003.2  457.44  5008.2  457.44  5008.7  458.24  5016.4  459.26  5021.4  461.15
  5023.2  461.83  5028.6  461.45  5053.2  462.20  5147.1  466.74  5209.2  470.19
  5222.5  470.35  5262.8  473.05  5277.1  473.11  5295.0  474.33  5327.1  474.61
#Mann=5,-1,0
  4480.4    0.05       0  4873.0    0.16       0  5002.7    0.07       0
  5008.7    0.16       0  5147.1    0.05       0
Bank Sta=4784,5021.4
Exp/Cntr=0.3,0.1

Type RM Length L Ch R = 1,17175,609,609,609
BEGIN DESCRIPTION:
ISHMEAL BRANCH 24.0
END DESCRIPTION:
XS GIS Cut Line= 3
      2825925.03      7054875.03      2825572.00      7054586.72
      2825178.12      7054617.82
#Sta/Elev= 30
  4540.3  473.29  4617.9  472.42  4661.0  471.03  4718.4  467.33  4788.7  465.66
  4796.7  464.32  4846.2  460.55  4886.8  458.37  4895.7  455.99  4902.2  457.42
  4910.1  455.83  4916.5  457.09  4924.4  455.56  4930.9  457.86  4980.4  457.78
  4988.3  456.42  4996.1  457.00  5000.1  454.56  5000.6  453.76  5005.7  453.76
  5006.2  454.56  5013.2  456.82  5033.9  457.00  5060.2  457.19  5121.7  458.37
  5253.9  461.29  5324.1  464.81  5344.2  467.32  5354.2  467.39  5391.2  470.78
#Mann=5,-1,0
  4540.3    0.05       0  5000.1    0.03       0  5006.2    0.05       0
  5033.9    0.07       0  5060.2    0.05       0
Bank Sta=4886.8,5121.7
Exp/Cntr=0.3,0.1

Type RM Length L Ch R = 1,16566,646,646,646
BEGIN DESCRIPTION:
ISHMEAL BRANCH 23.0
END DESCRIPTION:
XS GIS Cut Line= 3
      2825924.98      7054624.97      2825575.00      7054125.00
      2825124.96      7054075.00
#Sta/Elev= 30
  4361.2  470.69  4389.5  470.45  4440.1  468.30  4496.7  465.38  4526.4  462.74
  4568.7  460.53  4702.8  456.26  4734.8  456.05  4740.5  455.62  4761.3  455.04
  4776.6  454.49  4800.2  455.05  4913.5  454.98  4922.2  454.33  4981.6  455.49
  4991.6  454.09  4998.6  450.32  4999.1  449.52  5004.3  449.52  5004.8  450.32
  5011.7  453.84  5024.2  456.26  5062.0  464.11  5082.2  466.98  5112.4  469.84
  5142.5  471.59  5202.9  473.54  5283.4  473.13  5353.8  474.27  5424.3  474.79
#Mann=5,-1,0
  4361.2    0.05       0  4740.5    0.16       0  4761.3    0.05       0
  4998.6    0.03       0  5004.8    0.05       0
Bank Sta=4702.8,5024.2
Exp/Cntr=0.3,0.1

Type RM Length L Ch R = 1,15920,558,558,558
BEGIN DESCRIPTION:
ISHMEAL BRANCH 22.0
END DESCRIPTION:
XS GIS Cut Line= 3
      2826175.02      7054275.03      2825925.00      7053825.00
      2825474.96      7053674.99
#Sta/Elev= 30
  4464.0  466.12  4499.5  465.90  4554.5  461.61  4575.0  459.90  4580.7  460.24
  4640.0  456.80  4696.5  455.15  4761.2  453.35  4808.4  453.66  4905.6  452.26
  4911.3  452.80  4921.6  449.74  4940.3  448.63  4940.8  447.83  4946.0  447.83
  4946.5  448.63  4949.1  452.63  4970.8  452.78  4976.0  449.44  4999.9  450.03
  5010.4  454.41  5014.8  455.15  5084.2  461.61  5094.8  463.63  5115.8  465.42
  5126.7  467.41  5158.0  470.48  5231.8  473.11  5368.8  471.72  5453.2  473.21
#Mann=7,-1,0
  4464.0    0.05       0  4554.5    0.16       0  4640.0    0.05       0
  4761.2    0.16       0  4940.3    0.07       0  4946.5    0.16       0
  5126.7    0.05       0
Bank Sta=4696.5,5014.8
Exp/Cntr=0.3,0.1

Type RM Length L Ch R = 1,15362,602,602,602
BEGIN DESCRIPTION:
ISHMEAL BRANCH 21.0
END DESCRIPTION:
XS GIS Cut Line= 3
      2826825.01      7053825.00      2826375.00      7053675.00
      2825974.97      7053324.98
#Sta/Elev= 30
  4513.7  469.83  4619.1  469.86  4682.4  468.39  4840.5  458.32  4861.6  456.27
  4879.1  451.98  4882.6  451.03  4935.4  450.66  4956.4  449.81  4991.4  451.02
  4998.6  446.33  4999.1  445.53  5004.5  445.53  5005.0  446.33  5009.4  446.50
  5016.1  450.62  5023.6  451.79  5030.3  451.01  5066.4  450.32  5136.6  451.51
  5172.7  450.99  5190.0  451.61  5198.5  451.98  5285.6  453.58  5314.1  454.82
  5391.9  461.83  5477.3  467.03  5484.0  466.55  5491.6  467.98  5519.6  470.35
#Mann=4,-1,0
  4513.7    0.16       0  4998.6    0.07       0  5005.0    0.16       0
  5190.0    0.05       0
Bank Sta=4879.1,5198.5
Exp/Cntr=0.3,0.1

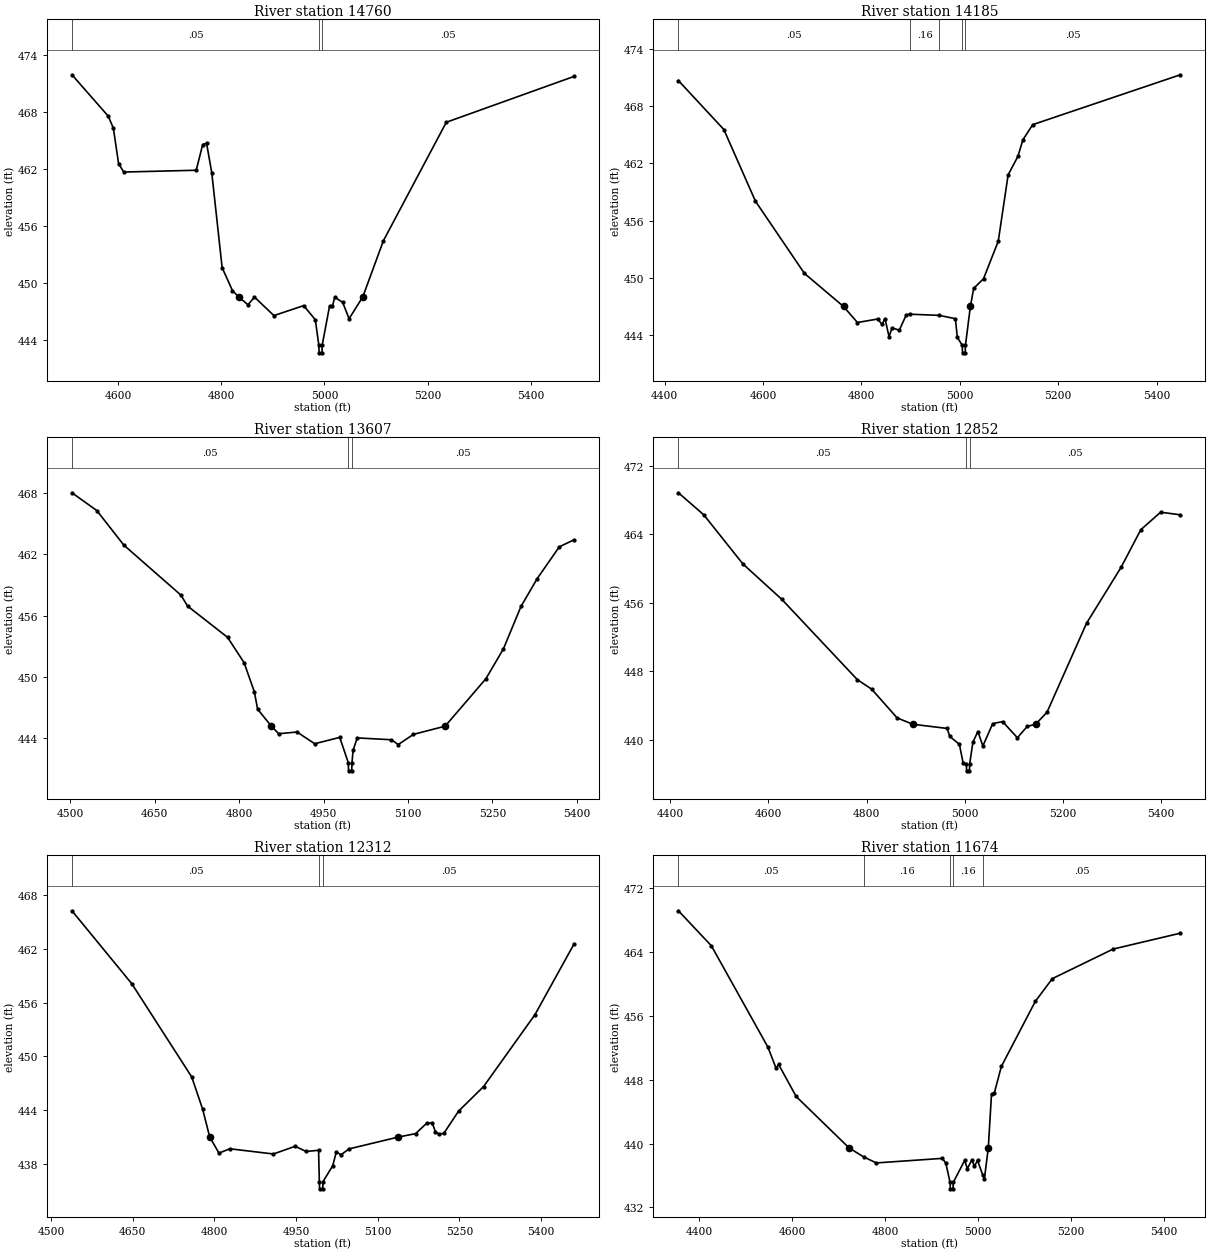
Type RM Length L Ch R = 1,14760,575,575,575
BEGIN DESCRIPTION:
ISHMEAL BRANCH 20.0
END DESCRIPTION:
XS GIS Cut Line= 3
      2827075.04      7053225.00      2826575.00      7053175.00
      2826175.02      7052925.02
#Sta/Elev= 30
  4509.8  471.93  4580.2  467.57  4590.2  466.30  4600.3  462.57  4610.3  461.67
  4751.0  461.86  4763.6  464.57  4771.1  464.71  4781.2  461.59  4801.3  451.59
  4821.4  449.16  4833.4  448.50  4851.5  447.67  4864.1  448.48  4901.8  446.53
  4959.6  447.58  4982.2  446.09  4989.0  443.40  4989.5  442.60  4995.0  442.60
  4995.5  443.40  5009.8  447.53  5015.3  447.53  5020.0  448.46  5035.3  447.92
  5047.7  446.20  5074.3  448.50  5114.3  454.42  5236.4  466.92  5484.0  471.75
#Mann=3,-1,0
  4509.8    0.05       0  4989.0    0.03       0  4995.5    0.05       0
Bank Sta=4833.4,5074.3
Exp/Cntr=0.3,0.1

Type RM Length L Ch R = 1,14185,578,578,578
BEGIN DESCRIPTION:
ISHMEAL BRANCH 19.0
END DESCRIPTION:
XS GIS Cut Line= 3
      2827125.02      7053025.01      2826675.00      7052675.00
      2826225.01      7052675.00
#Sta/Elev= 30
  4428.0  470.69  4520.3  465.56  4584.6  458.04  4684.1  450.47  4763.6  447.00
  4791.8  445.32  4833.4  445.69  4841.6  445.12  4847.9  445.73  4856.0  443.85
  4862.4  444.76  4876.9  444.51  4891.3  446.14  4898.9  446.19  4958.1  446.07
  4990.9  445.72  4994.9  443.75  5004.9  442.94  5005.4  442.14  5010.9  442.14
  5011.4  442.94  5021.4  447.00  5028.1  448.90  5048.1  449.91  5078.1  453.85
  5098.1  460.80  5118.1  462.75  5128.1  464.48  5148.1  466.07  5448.1  471.30
#Mann=5,-1,0
  4428.0    0.05       0  4898.9    0.16       0  4958.1    0.05       0
  5004.9    0.03       0  5011.4    0.05       0
Bank Sta=4763.6,5021.4
Exp/Cntr=0.3,0.1

Type RM Length L Ch R = 1,13607,755,755,755
BEGIN DESCRIPTION:
ISHMEAL BRANCH 18.0
END DESCRIPTION:
XS GIS Cut Line= 3
      2827224.99      7052874.98      2827051.27      7052450.36
      2826634.62      7052333.18
#Sta/Elev= 30
  4503.0  468.04  4547.1  466.30  4595.1  462.91  4696.6  458.00  4708.3  456.93
  4779.4  453.86  4808.8  451.37  4827.1  448.50  4832.8  446.81  4857.3  445.14
  4870.3  444.40  4902.8  444.57  4934.2  443.42  4978.7  444.04  4993.9  441.56
  4994.4  440.76  5000.0  440.76  5000.5  441.56  5002.4  442.77  5009.8  443.99
  5070.5  443.81  5082.6  443.34  5109.7  444.34  5165.9  445.14  5238.4  449.80
  5269.5  452.73  5300.7  456.89  5329.6  459.63  5368.8  462.74  5394.6  463.42
#Mann=3,-1,0
  4503.0    0.05       0  4993.9    0.03       0  5000.5    0.05       0
Bank Sta=4857.3,5165.9
Exp/Cntr=0.3,0.1

Type RM Length L Ch R = 1,12852,540,540,540
BEGIN DESCRIPTION:
ISHMEAL BRANCH 17.0
END DESCRIPTION:
XS GIS Cut Line= 3
      2827824.98      7052124.99      2827275.00      7051975.00
      2826825.03      7051925.00
#Sta/Elev= 30
  4416.6  468.84  4468.4  466.26  4547.9  460.54  4627.3  456.40  4781.1  447.03
  4810.5  445.91  4862.3  442.56  4894.1  441.82  4964.2  441.33  4969.4  440.41
  4989.2  439.47  4996.7  437.32  5003.4  437.18  5003.9  436.38  5009.6  436.38
  5010.1  437.18  5016.8  439.74  5026.9  440.97  5037.0  439.28  5057.1  441.89
  5077.2  442.13  5107.4  440.24  5127.5  441.57  5144.6  441.82  5167.8  443.23
  5248.3  453.61  5318.7  460.14  5358.9  464.53  5399.2  466.57  5439.4  466.27
#Mann=3,-1,0
  4416.6    0.05       0  5003.4    0.03       0  5010.1    0.05       0
Bank Sta=4894.1,5144.6
Exp/Cntr=0.3,0.1

Type RM Length L Ch R = 1,12312,638,638,638
BEGIN DESCRIPTION:
ISHMEAL BRANCH 16.0
END DESCRIPTION:
XS GIS Cut Line= 3
      2827825.00      7051525.00      2827375.00      7051525.00
      2826975.00      7051275.00
#Sta/Elev= 30
  4538.5  466.24  4648.5  458.09  4758.5  447.69  4778.5  444.10  4791.5  440.99
  4808.5  439.20  4828.5  439.68  4908.5  439.10  4948.5  439.96  4968.5  439.38
  4991.4  439.51  4992.8  436.01  4993.3  435.21  4999.0  435.21  4999.5  436.01
  5017.4  437.79  5023.9  439.31  5032.7  439.02  5047.5  439.67  5137.9  440.99
  5169.5  441.37  5190.7  442.57  5200.2  442.55  5206.1  441.57  5212.6  441.31
  5221.4  441.40  5248.5  443.88  5294.5  446.63  5388.9  454.66  5460.2  462.50
#Mann=3,-1,0
  4538.5    0.05       0  4992.8    0.03       0  4999.5    0.05       0
Bank Sta=4791.5,5137.9
Exp/Cntr=0.3,0.1

Type RM Length L Ch R = 1,11674,591,591,591
BEGIN DESCRIPTION:
ISHMEAL BRANCH 15.0
END DESCRIPTION:
XS GIS Cut Line= 3
      2827874.98      7050925.00      2827275.00      7051025.00
      2826874.96      7051275.02
#Sta/Elev= 30
  4355.1  469.19  4426.0  464.80  4547.7  452.09  4565.4  449.42  4570.5  449.94
  4608.5  445.90  4722.6  439.44  4753.6  438.33  4780.9  437.57  4922.8  438.14
  4930.4  437.57  4939.7  435.12  4940.2  434.32  4946.0  434.32  4946.5  435.12
  4971.0  437.88  4976.9  436.85  4986.4  437.93  4992.2  437.16  4998.7  437.90
  5009.9  436.04  5013.5  435.58  5021.9  439.44  5028.8  446.19  5034.7  446.30
  5050.0  449.67  5123.1  457.83  5159.7  460.68  5290.6  464.39  5435.1  466.38
#Mann=5,-1,0
  4355.1    0.05       0  4753.6    0.16       0  4939.7    0.07       0
  4946.5    0.16       0  5009.9    0.05       0
Bank Sta=4722.6,5021.9
Exp/Cntr=0.3,0.1

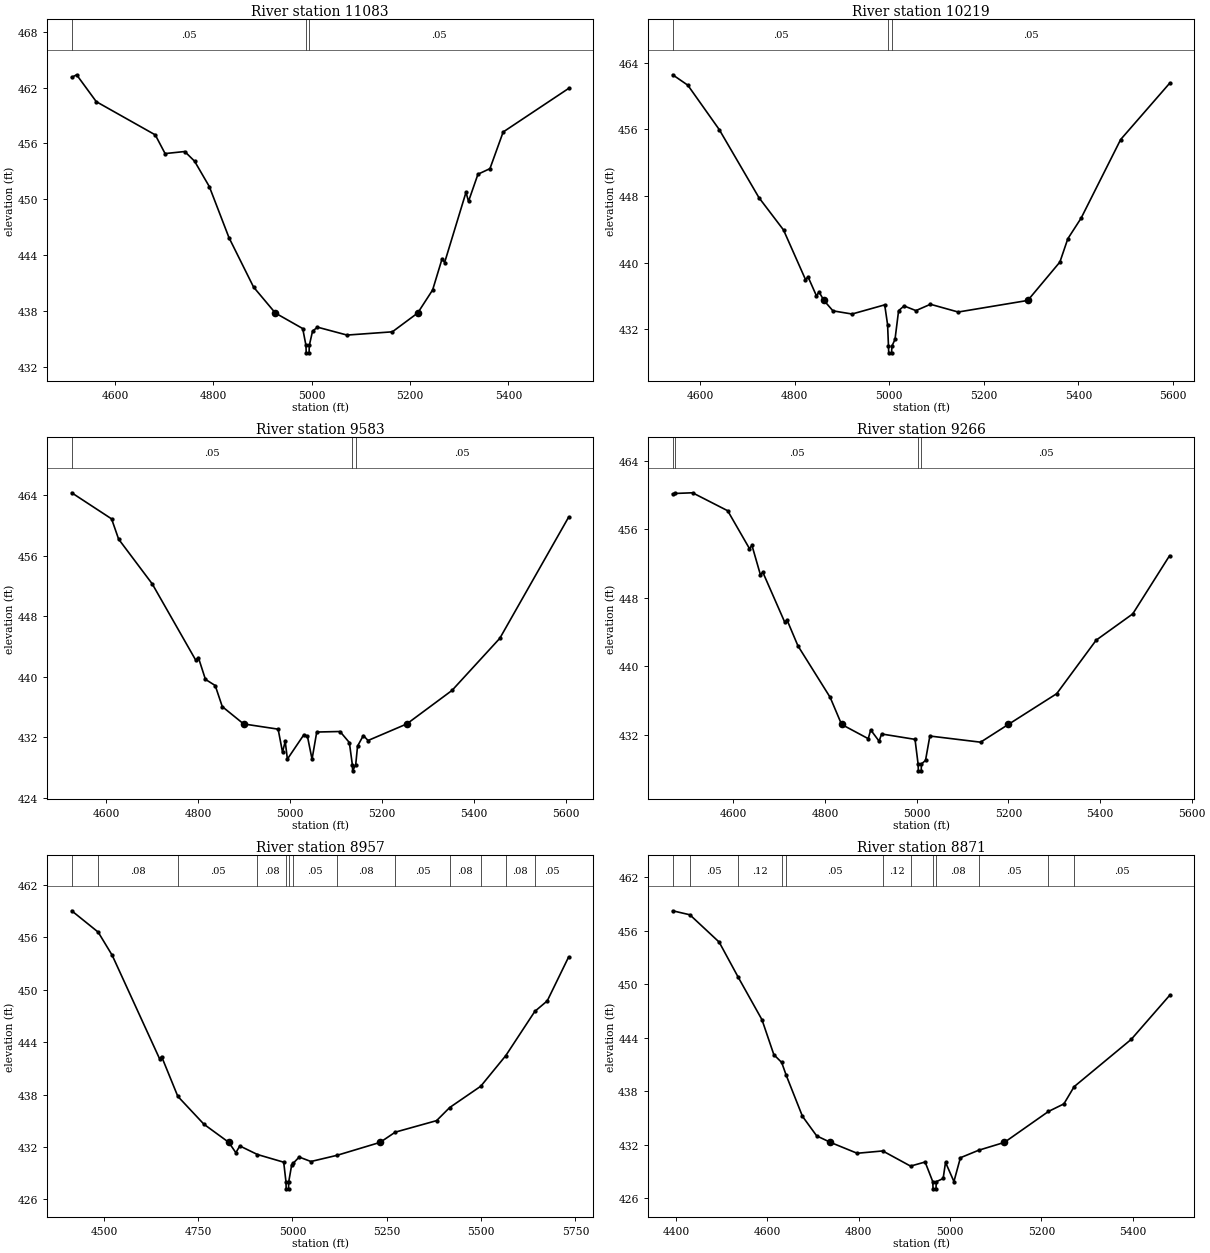
Type RM Length L Ch R = 1,11083,864,864,864
BEGIN DESCRIPTION:
ISHMEAL BRANCH 14.0
END DESCRIPTION:
XS GIS Cut Line= 3
      2827874.95      7050625.00      2827325.00      7050625.00
      2826875.03      7050724.99
#Sta/Elev= 30
  4511.7  463.10  4521.7  463.38  4561.7  460.49  4681.7  456.92  4701.7  454.91
  4741.7  455.13  4761.7  454.09  4791.7  451.36  4831.7  445.87  4881.7  440.56
  4926.0  437.77  4981.7  436.10  4988.3  434.29  4988.8  433.49  4994.6  433.49
  4995.1  434.29  5001.7  435.82  5011.7  436.25  5071.9  435.40  5164.1  435.75
  5215.6  437.77  5246.0  440.25  5265.3  443.61  5270.4  443.20  5313.9  450.75
  5319.0  449.77  5338.2  452.69  5362.6  453.29  5389.5  457.23  5522.6  461.91
#Mann=3,-1,0
  4511.7    0.05       0  4988.3    0.03       0  4995.1    0.05       0
Bank Sta=4926,5215.6
Exp/Cntr=0.3,0.1

Type RM Length L Ch R = 1,10219,636,636,636
BEGIN DESCRIPTION:
ISHMEAL BRANCH 13.0
END DESCRIPTION:
XS GIS Cut Line= 3
      2827774.98      7050025.01      2827325.00      7050225.00
      2826825.04      7049975.02
#Sta/Elev= 30
  4541.5  462.54  4573.6  461.29  4640.0  455.97  4724.1  447.79  4776.1  443.91
  4822.6  437.96  4828.1  438.27  4845.8  436.00  4851.3  436.47  4861.6  435.45
  4880.7  434.20  4921.1  433.82  4990.2  434.92  4996.3  432.55  4998.2  429.96
  4998.7  429.16  5004.8  429.16  5005.4  429.96  5012.0  430.77  5019.6  434.22
  5031.2  434.79  5056.3  434.23  5087.0  434.99  5145.7  434.06  5292.9  435.45
  5360.9  440.06  5377.7  442.86  5405.7  445.32  5489.5  454.77  5592.9  461.51
#Mann=3,-1,0
  4541.5    0.05       0  4998.2    0.03       0  5005.4    0.05       0
Bank Sta=4861.6,5292.9
Exp/Cntr=0.3,0.1

Type RM Length L Ch R = 1,9583,317,317,317
BEGIN DESCRIPTION:
ISHMEAL BRANCH 12.0
END DESCRIPTION:
XS GIS Cut Line= 3
      2827825.02      7049975.01      2827425.00      7049725.00
      2826825.00      7049825.00
#Sta/Elev= 30
  4525.6  464.33  4612.3  460.88  4627.6  458.20  4700.7  452.28  4795.1  442.21
  4801.0  442.54  4816.3  439.66  4837.5  438.85  4852.9  436.06  4899.3  433.77
  4974.3  433.08  4983.8  430.04  4989.7  431.46  4994.4  429.12  5030.3  432.35
  5037.9  432.16  5048.0  429.11  5058.2  432.70  5108.8  432.77  5129.1  431.31
  5135.6  428.37  5136.2  427.57  5142.9  428.37  5146.9  430.84  5159.5  432.24
  5169.7  431.58  5253.9  433.77  5352.2  438.20  5456.1  445.09  5605.6  461.10
#Mann=3,-1,0
  4525.6    0.05       0  5135.6    0.03       0  5142.9    0.05       0
Bank Sta=4899.3,5253.9
Exp/Cntr=0.3,0.1

Type RM Length L Ch R = 1,9266,309,309,309
BEGIN DESCRIPTION:
Mapping XS 91fae023
END DESCRIPTION:
XS GIS Cut Line= 3
      2827871.95      7049706.02      2827396.70      7049506.37
      2826880.18      7049745.10
#Sta/Elev= 30
  4467.2  460.16  4472.4  460.20  4510.6  460.28  4587.3  458.18  4634.8  453.76
  4640.3  454.13  4658.6  450.72  4664.0  450.99  4711.5  445.19  4717.0  445.39
  4740.7  442.38  4811.0  436.36  4835.9  433.20  4894.1  431.53  4899.5  432.55
  4917.8  431.24  4923.3  432.08  4996.2  431.45  5002.9  428.57  5003.5  427.77
  5009.7  427.77  5010.2  428.57  5019.1  428.99  5028.6  431.84  5139.3  431.12
  5200.0  433.20  5305.4  436.79  5391.6  443.05  5471.4  446.12  5551.7  452.92
#Mann=4,-1,0
  4467.2    0.16       0  4472.4    0.05       0  5002.9    0.03       0
  5010.2    0.05       0
Bank Sta=4835.9,5200
Exp/Cntr=0.3,0.1

Type RM Length L Ch R = 1,8957,86,86,86
BEGIN DESCRIPTION:
ISHMEAL BRANCH 11.0
END DESCRIPTION:
XS GIS Cut Line= 4
      2827936.58      7049063.06      2827131.89      7049339.10
      2827056.37      7049503.17      2826842.85      7049693.25
#Sta/Elev= 30
  4414.7  459.05  4484.8  456.61  4522.1  453.95  4647.7  442.10  4653.0  442.36
  4696.0  437.80  4765.2  434.61  4831.2  432.53  4849.8  431.35  4860.4  432.12
  4907.1  431.14  4976.7  430.26  4982.7  428.01  4983.3  427.21  4989.5  427.21
  4990.0  428.01  4997.8  429.93  5001.7  430.13  5017.7  430.85  5048.9  430.34
  5118.2  431.05  5232.2  432.53  5272.4  433.70  5382.0  435.02  5416.7  436.52
  5499.1  438.96  5565.5  442.47  5642.4  447.53  5675.3  448.73  5731.9  453.75
#Mann=13,-1,0
  4414.7    0.05       0  4484.8    0.08       0  4696.0    0.05       0
  4907.1    0.08       0  4982.7    0.07       0  4990.0    0.08       0
  5001.7    0.05       0  5118.2    0.08       0  5272.4    0.05       0
  5416.7    0.08       0  5499.1    0.05       0  5565.5    0.08       0
  5642.4    0.05       0
Bank Sta=4831.2,5232.2
Exp/Cntr=0.3,0.1

Type RM Length L Ch R = 1,8871,558,558,558
BEGIN DESCRIPTION:
Mapping XS 8c3ea984
END DESCRIPTION:
XS GIS Cut Line= 3
      2827907.94      7048987.54      2827361.06      7049175.04
      2826874.08      7049326.08
#Sta/Elev= 30
  4392.4  458.23  4430.1  457.78  4494.2  454.72  4535.7  450.80  4588.0  446.01
  4614.0  442.09  4631.1  441.22  4641.2  439.76  4676.6  435.18  4707.8  432.98
  4738.0  432.25  4796.4  431.03  4852.4  431.29  4913.3  429.59  4945.2  430.05
  4962.0  427.84  4962.6  427.04  4969.0  427.04  4969.6  427.84  4984.7  428.20
  4989.9  430.01  5008.3  427.86  5022.5  430.53  5062.5  431.37  5118.8  432.25
  5215.3  435.72  5249.1  436.57  5271.5  438.50  5396.6  443.81  5480.4  448.73
#Mann=12,-1,0
  4392.4    0.08       0  4430.1    0.05       0  4535.7    0.12       0
  4631.1    0.08       0  4641.2    0.05       0  4852.4    0.12       0
  4913.3    0.08       0  4962.0    0.07       0  4969.6    0.08       0
  5062.5    0.05       0  5215.3    0.08       0  5271.5    0.05       0
Bank Sta=4738,5118.8
Exp/Cntr=0.3,0.1

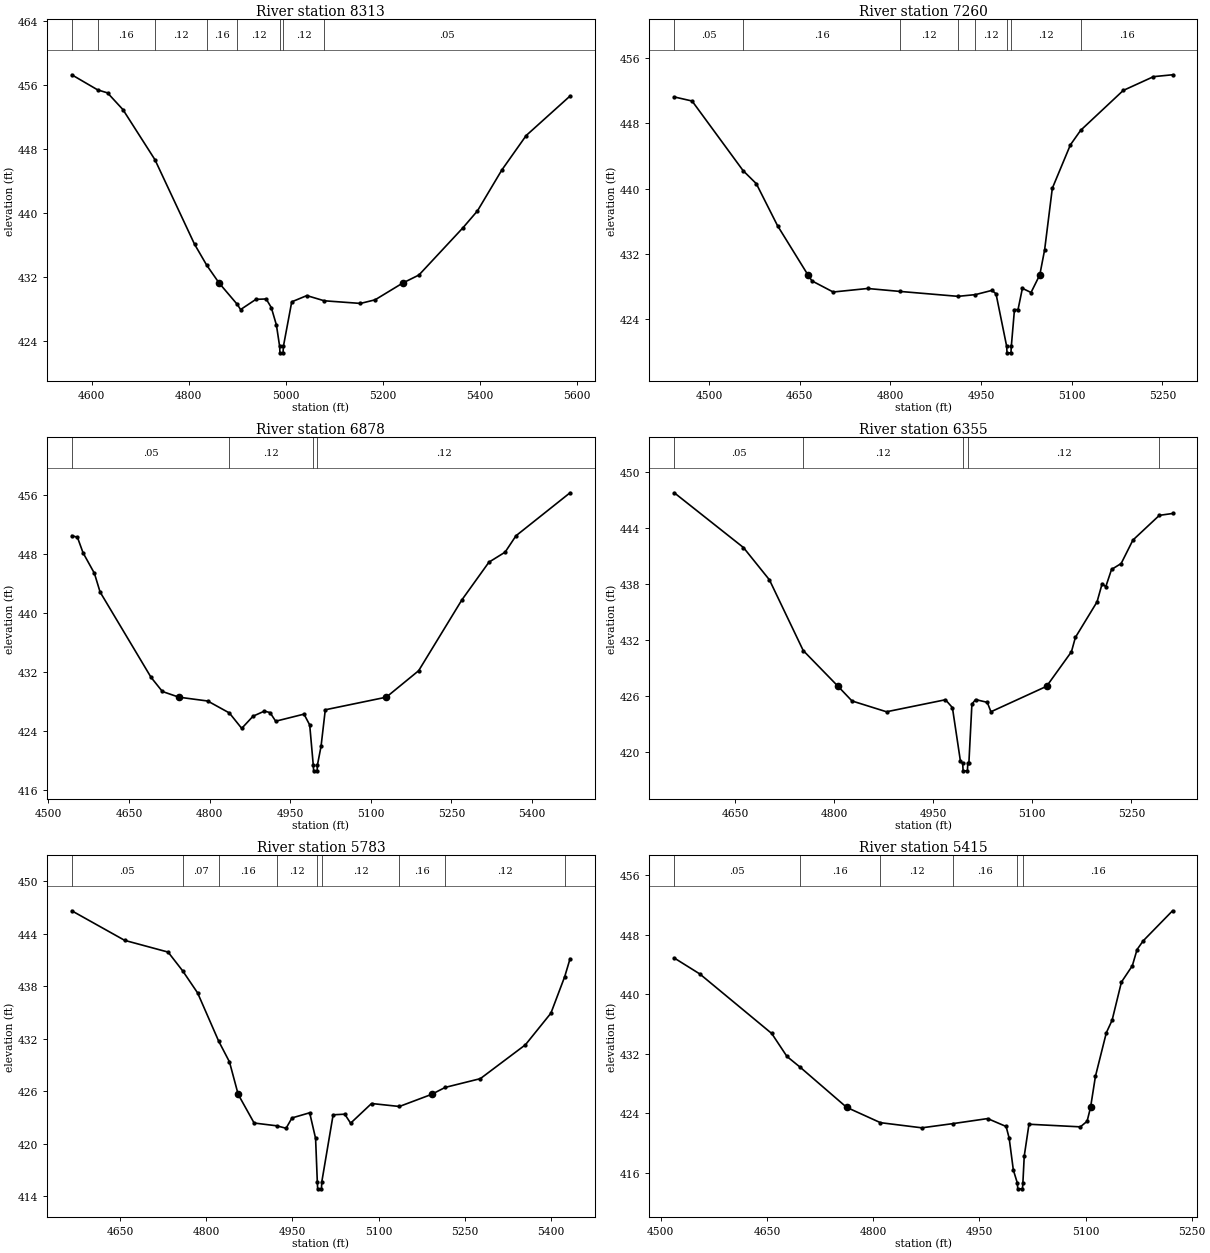
Type RM Length L Ch R = 1,8313,1053,1053,1053
BEGIN DESCRIPTION:
ISHMEAL BRANCH 10.0
END DESCRIPTION:
XS GIS Cut Line= 3
      2827924.96      7048924.99      2827475.00      7048775.00
      2826924.97      7048725.00
#Sta/Elev= 30
  4559.1  457.29  4612.4  455.40  4632.8  455.02  4664.5  452.93  4730.5  446.65
  4812.0  436.07  4837.1  433.44  4862.7  431.20  4900.2  428.52  4906.9  427.88
  4938.5  429.16  4959.6  429.21  4970.2  428.13  4980.7  425.95  4987.4  423.26
  4988.0  422.46  4994.4  422.46  4995.1  423.26  5012.3  428.85  5043.4  429.63
  5079.3  428.98  5153.9  428.65  5184.0  429.10  5240.9  431.20  5274.4  432.21
  5364.8  438.11  5394.9  440.24  5445.1  445.36  5495.3  449.68  5585.7  454.63
#Mann=8,-1,0
  4559.1    0.05       0  4612.4    0.16       0  4730.5    0.12       0
  4837.1    0.16       0  4900.2    0.12       0  4987.4    0.07       0
  4995.1    0.12       0  5079.3    0.05       0
Bank Sta=4862.7,5240.9
Exp/Cntr=0.3,0.1

Type RM Length L Ch R = 1,7260,382,382,382
BEGIN DESCRIPTION:
ISHMEAL BRANCH 9.0
END DESCRIPTION:
XS GIS Cut Line= 3
      2827968.71      7048592.59      2827546.82      7048217.58
      2827325.43      7048082.14
#Sta/Elev= 30
  4442.7  451.21  4472.2  450.71  4556.6  442.19  4578.4  440.60  4613.5  435.46
  4663.7  429.45  4670.4  428.71  4705.5  427.35  4762.4  427.78  4816.2  427.42
  4912.0  426.82  4940.7  427.03  4968.1  427.55  4974.8  427.13  4992.4  420.71
  4993.0  419.91  4999.5  419.91  5000.1  420.71  5005.3  425.20  5011.2  425.20
  5018.4  427.80  5032.7  427.29  5047.2  429.45  5055.2  432.52  5067.9  440.04
  5097.8  445.35  5114.8  447.13  5185.1  452.00  5235.2  453.69  5266.7  453.92
#Mann=8,-1,0
  4442.7    0.05       0  4556.6    0.16       0  4816.2    0.12       0
  4912.0    0.16       0  4940.7    0.12       0  4992.4    0.07       0
  5000.1    0.12       0  5114.8    0.16       0
Bank Sta=4663.7,5047.2
Exp/Cntr=0.3,0.1

Type RM Length L Ch R = 1,6878,523,523,523
BEGIN DESCRIPTION:
ISHMEAL BRANCH 8.0
END DESCRIPTION:
XS GIS Cut Line= 3
      2828224.96      7048174.99      2827775.00      7048025.00
      2827324.97      7047975.00
#Sta/Elev= 30
  4543.5  450.46  4554.0  450.25  4564.5  448.14  4585.6  445.36  4596.2  442.82
  4691.0  431.25  4712.1  429.33  4742.8  428.56  4796.4  428.04  4836.7  426.42
  4859.7  424.33  4880.8  425.98  4901.9  426.67  4912.4  426.47  4922.9  425.30
  4975.6  426.26  4986.2  424.79  4992.8  419.37  4993.5  418.57  5000.0  418.57
  5000.6  419.37  5007.3  421.89  5015.2  426.85  5128.7  428.56  5188.9  432.15
  5269.3  441.75  5319.7  446.87  5349.8  448.23  5370.0  450.45  5470.6  456.28
#Mann=4,-1,0
  4543.5    0.05       0  4836.7    0.12       0  4992.8    0.07       0
  5000.6    0.12       0
Bank Sta=4742.8,5128.7
Exp/Cntr=0.3,0.1

Type RM Length L Ch R = 1,6355,572,572,572
BEGIN DESCRIPTION:
ISHMEAL BRANCH 7.0
END DESCRIPTION:
XS GIS Cut Line= 3
      2828274.98      7047874.99      2827874.94      7047683.72
      2827590.50      7047557.77
#Sta/Elev= 30
  4557.9  447.81  4662.7  441.94  4702.0  438.48  4753.2  430.90  4805.9  427.07
  4827.0  425.50  4879.3  424.34  4968.6  425.63  4979.1  424.78  4991.2  419.06
  4994.6  418.81  4995.3  418.01  5001.8  418.01  5002.4  418.81  5004.0  418.81
  5008.6  425.15  5014.1  425.65  5031.9  425.35  5037.4  424.34  5121.7  427.07
  5159.3  430.77  5165.3  432.31  5198.1  436.12  5205.8  438.07  5211.3  437.74
  5220.0  439.59  5234.6  440.23  5252.4  442.74  5292.4  445.39  5312.4  445.59
#Mann=5,-1,0
  4557.9    0.05       0  4753.2    0.12       0  4994.6    0.07       0
  5002.4    0.12       0  5292.4    0.16       0
Bank Sta=4805.9,5121.7
Exp/Cntr=0.3,0.1

Type RM Length L Ch R = 1,5783,368,368,368
BEGIN DESCRIPTION:
ISHMEAL BRANCH 6.0
END DESCRIPTION:
XS GIS Cut Line= 3
      2828458.32      7047360.82      2828036.40      7047264.45
      2827608.38      7047194.41
#Sta/Elev= 30
  4566.3  446.63  4658.3  443.25  4733.8  441.91  4759.1  439.77  4785.1  437.25
  4821.8  431.73  4840.5  429.37  4855.7  425.65  4883.4  422.38  4922.9  422.06
  4939.0  421.78  4949.2  422.96  4980.0  423.55  4990.3  420.62  4993.3  415.66
  4993.9  414.86  5000.5  414.86  5001.1  415.66  5020.8  423.32  5041.0  423.39
  5051.2  422.36  5087.6  424.61  5136.0  424.27  5191.9  425.65  5215.7  426.45
  5276.8  427.45  5355.2  431.32  5399.5  434.93  5423.6  439.12  5432.8  441.15
#Mann=9,-1,0
  4566.3    0.05       0  4759.1    0.07       0  4821.8    0.16       0
  4922.9    0.12       0  4993.3    0.07       0  5001.1    0.12       0
  5136.0    0.16       0  5215.7    0.12       0  5423.6    0.16       0
Bank Sta=4855.7,5191.9
Exp/Cntr=0.3,0.1

Type RM Length L Ch R = 1,5415,515,515,515
BEGIN DESCRIPTION:
Mapping XS 724aa596
END DESCRIPTION:
XS GIS Cut Line= 3
      2828466.09      7047191.54      2828065.05      7046954.56
      2827862.29      7046829.78
#Sta/Elev= 30
  4519.0  444.86  4555.1  442.72  4656.7  434.73  4678.2  431.65  4696.8  430.21
  4762.5  424.82  4810.3  422.76  4868.7  422.07  4912.4  422.63  4961.7  423.31
  4987.8  422.25  4992.1  420.69  4998.0  416.41  5003.6  414.68  5004.3  413.88
  5010.9  413.88  5011.5  414.68  5013.4  418.27  5020.1  422.55  5092.7  422.20
  5102.2  422.95  5107.1  424.82  5114.0  428.99  5129.4  434.84  5137.5  436.50
  5150.7  441.63  5166.1  443.82  5172.8  446.00  5181.5  447.17  5222.9  451.20
#Mann=6,-1,0
  4519.0    0.05       0  4696.8    0.16       0  4810.3    0.12       0
  4912.4    0.16       0  5003.6    0.07       0  5011.5    0.16       0
Bank Sta=4762.5,5107.1
Exp/Cntr=0.3,0.1

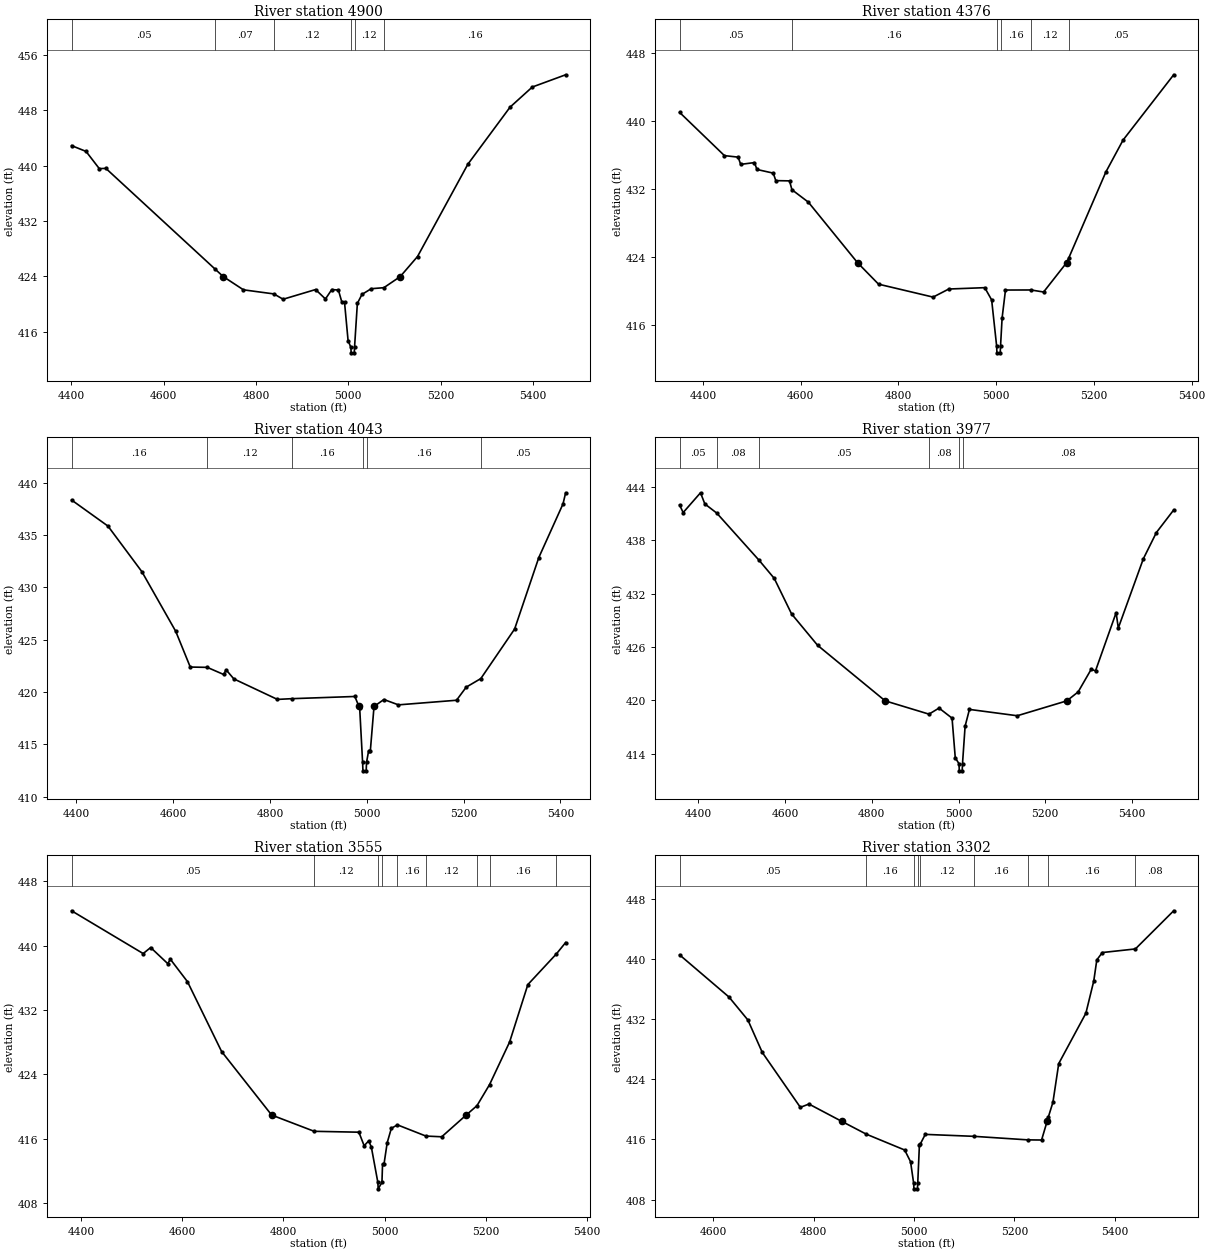
Type RM Length L Ch R = 1,4900,524,524,524
BEGIN DESCRIPTION:
ISHMEAL BRANCH 5.0
END DESCRIPTION:
XS GIS Cut Line= 3
      2828756.77      7047017.90      2828305.38      7046640.29
      2827825.04      7046675.00
#Sta/Elev= 30
  4400.6  442.90  4432.0  442.06  4460.6  439.58  4474.9  439.61  4712.2  425.02
  4729.2  423.98  4772.9  422.07  4838.8  421.48  4858.8  420.71  4929.1  422.11
  4950.5  420.75  4964.2  422.11  4978.5  422.04  4986.1  420.28  4991.8  420.28
  4999.5  414.74  5005.5  413.77  5006.2  412.97  5012.9  412.97  5013.5  413.77
  5019.6  420.11  5029.6  421.41  5049.6  422.23  5077.0  422.38  5112.4  423.98
  5149.9  426.88  5258.9  440.21  5350.4  448.46  5398.5  451.36  5470.7  453.13
#Mann=6,-1,0
  4400.6    0.05       0  4712.2    0.07       0  4838.8    0.12       0
  5005.5    0.07       0  5013.5    0.12       0  5077.0    0.16       0
Bank Sta=4729.2,5112.4
Exp/Cntr=0.3,0.1

Type RM Length L Ch R = 1,4376,333,333,333
BEGIN DESCRIPTION:
Mapping XS 7d960612
END DESCRIPTION:
XS GIS Cut Line= 3
      2828804.63      7046962.37      2828630.15      7046371.22
      2828344.83      7046098.87
#Sta/Elev= 30
  4352.3  441.02  4444.0  435.94  4472.0  435.76  4477.3  434.91  4505.4  435.12
  4510.6  434.31  4543.9  433.88  4549.1  433.00  4577.2  432.97  4582.1  431.93
  4615.7  430.47  4716.4  423.35  4759.3  420.83  4870.9  419.31  4903.0  420.26
  4976.6  420.42  4990.7  418.98  5000.9  413.56  5001.5  412.76  5008.2  412.76
  5008.9  413.56  5012.1  416.86  5019.0  420.14  5071.0  420.15  5097.0  419.91
  5144.0  423.35  5148.3  423.89  5224.4  434.02  5259.6  437.77  5363.1  445.44
#Mann=6,-1,0
  4352.3    0.05       0  4582.1    0.16       0  5000.9    0.07       0
  5008.9    0.16       0  5071.0    0.12       0  5148.3    0.05       0
Bank Sta=4716.4,5144
Exp/Cntr=0.3,0.1

Type RM Length L Ch R = 1,4043,66,66,66
BEGIN DESCRIPTION:
Mapping XS 2a3db289
END DESCRIPTION:
XS GIS Cut Line= 3
      2828804.63      7046720.15      2828815.05      7046102.99
      2828812.45      7045699.65
#Sta/Elev= 30
  4390.3  438.34  4465.5  435.85  4535.5  431.50  4605.5  425.80  4635.5  422.39
  4670.6  422.36  4704.5  421.68  4709.5  422.13  4725.5  421.26  4815.5  419.30
  4844.9  419.37  4975.5  419.58  4983.9  418.63  4985.5  418.45  4991.5  413.28
  4992.2  412.48  4998.9  412.48  4999.6  413.28  5004.0  414.41  5007.5  414.41
  5015.1  418.63  5035.5  419.29  5065.5  418.78  5185.5  419.22  5205.5  420.47
  5235.7  421.29  5305.5  426.02  5355.5  432.85  5405.5  437.97  5410.9  439.03
#Mann=6,-1,0
  4390.3    0.16       0  4670.6    0.12       0  4844.9    0.16       0
  4991.5    0.07       0  4999.6    0.16       0  5235.7    0.05       0
Bank Sta=4983.9,5015.1
Exp/Cntr=0.3,0.1

Type RM Length L Ch R = 1,3977,422,422,422
BEGIN DESCRIPTION:
Mapping XS 55479179
END DESCRIPTION:
XS GIS Cut Line= 3
      2828882.76      7046733.18      2828874.94      7046095.18
      2828908.80      7045595.18
#Sta/Elev= 30
  4356.9  441.93  4365.1  441.08  4405.1  443.30  4415.1  442.05  4442.6  441.02
  4540.5  435.71  4575.1  433.70  4615.1  429.71  4675.1  426.19  4830.9  419.96
  4931.9  418.47  4955.1  419.15  4985.1  418.02  4992.5  413.58  5001.1  412.91
  5001.8  412.11  5008.5  412.11  5009.2  412.91  5015.2  417.12  5025.2  419.00
  5135.5  418.29  5249.7  419.96  5275.8  420.96  5305.8  423.49  5315.9  423.33
  5363.4  429.85  5368.4  428.13  5426.1  435.89  5456.2  438.84  5496.1  441.37
#Mann=6,-1,0
  4356.9    0.05       0  4442.6    0.08       0  4540.5    0.05       0
  4931.9    0.08       0  5001.1    0.07       0  5009.2    0.08       0
Bank Sta=4830.9,5249.7
Exp/Cntr=0.3,0.1

Type RM Length L Ch R = 1,3555,253,253,253
BEGIN DESCRIPTION:
Mapping XS ccacaf01
END DESCRIPTION:
XS GIS Cut Line= 3
      2829322.86      7046431.12      2829153.59      7045839.97
      2828932.25      7045553.53
#Sta/Elev= 30
  4381.2  444.31  4522.8  439.00  4537.6  439.75  4571.4  437.75  4576.6  438.29
  4610.4  435.51  4677.9  426.84  4776.8  418.96  4860.9  416.94  4949.3  416.83
  4959.7  415.15  4968.8  415.76  4974.0  414.97  4986.8  410.60  4987.5  409.80
  4994.9  410.60  4996.1  412.88  4999.0  412.88  5005.3  415.53  5013.5  417.31
  5025.5  417.74  5081.8  416.35  5113.1  416.26  5161.5  418.96  5182.8  420.12
  5207.7  422.74  5247.3  428.02  5283.4  435.15  5340.0  438.97  5358.1  440.37
#Mann=9,-1,0
  4381.2    0.05       0  4860.9    0.12       0  4986.8    0.07       0
  4994.9    0.12       0  5025.5    0.16       0  5081.8    0.12       0
  5182.8    0.05       0  5207.7    0.16       0  5340.0    0.08       0
Bank Sta=4776.8,5161.5
Exp/Cntr=0.3,0.1

Type RM Length L Ch R = 1,3302,537,537,537
BEGIN DESCRIPTION:
ISHMEAL BRANCH 2.0
END DESCRIPTION:
XS GIS Cut Line= 3
      2829774.96      7045874.98      2829325.00      7045675.00
      2828875.04      7045475.02
#Sta/Elev= 30
  4532.5  440.57  4630.9  434.96  4668.6  431.90  4697.3  427.58  4773.2  420.27
  4790.3  420.71  4855.8  418.40  4904.6  416.70  4981.1  414.59  4992.8  413.04
  4998.9  410.22  4999.6  409.42  5006.5  409.42  5007.2  410.22  5010.5  415.29
  5011.9  415.34  5022.2  416.67  5119.2  416.41  5226.4  415.94  5254.0  415.92
  5265.0  418.40  5267.2  418.92  5276.6  420.94  5288.2  426.10  5342.3  432.80
  5358.0  437.09  5364.1  439.90  5375.1  440.88  5441.0  441.36  5517.3  446.44
#Mann=9,-1,0
  4532.5    0.05       0  4904.6    0.16       0  4998.9    0.07       0
  5007.2    0.16       0  5011.9    0.12       0  5119.2    0.16       0
  5226.4    0.12       0  5267.2    0.16       0  5441.0    0.08       0
Bank Sta=4855.8,5265
Exp/Cntr=0.3,0.1

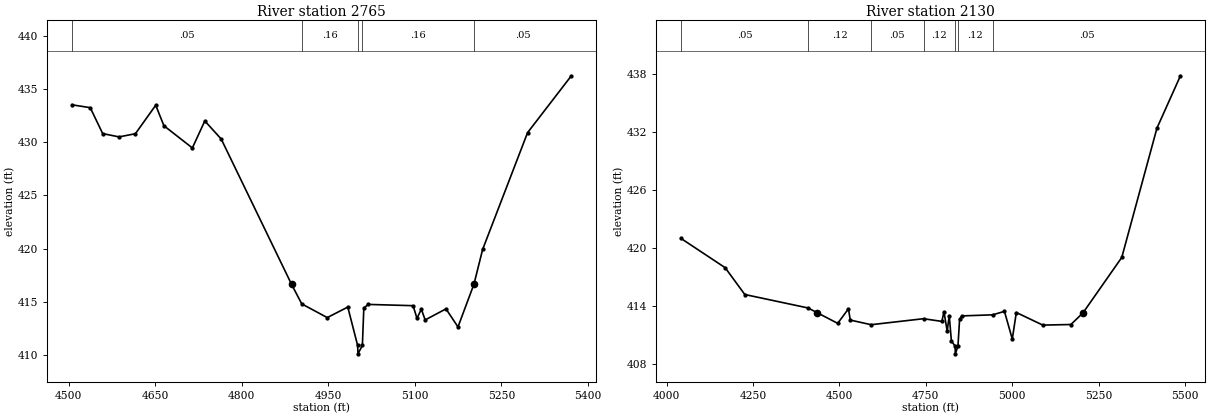
Type RM Length L Ch R = 1,2765,635,635,635
BEGIN DESCRIPTION:
Mapping XS 5225fe7e
END DESCRIPTION:
XS GIS Cut Line= 3
      2829997.33      7045668.08      2829679.63      7045319.14
      2829383.52      7045059.39
#Sta/Elev= 30
  4505.6  433.53  4537.5  433.26  4559.1  430.82  4587.5  430.51  4615.8  430.81
  4651.0  433.49  4665.2  431.56  4714.5  429.47  4736.1  432.01  4764.5  430.31
  4886.5  416.63  4904.1  414.80  4948.3  413.51  4983.9  414.50  5000.9  410.90
  5001.6  410.10  5009.2  410.90  5011.7  414.41  5019.3  414.75  5097.1  414.63
  5103.8  413.44  5111.4  414.30  5118.0  413.29  5154.1  414.33  5174.9  412.63
  5202.4  416.63  5202.6  416.66  5217.6  419.92  5295.5  430.91  5371.4  436.26
#Mann=5,-1,0
  4505.6    0.05       0  4904.1    0.16       0  5000.9    0.07       0
  5009.2    0.16       0  5202.6    0.05       0
Bank Sta=4886.5,5202.4
Exp/Cntr=0.3,0.1

Type RM Length L Ch R = 1,2130,0,0,0
BEGIN DESCRIPTION:
ISHMEAL BRANCH 1.0
END DESCRIPTION:
XS GIS Cut Line= 4
      2830341.08      7045444.12      2830165.14      7044940.13
      2829835.88      7044730.60      2829374.97      7044975.01
#Sta/Elev= 30
  4041.0  421.02  4169.1  417.99  4225.9  415.22  4409.0  413.83  4436.1  413.33
  4494.8  412.24  4525.9  413.74  4531.2  412.58  4591.5  412.10  4743.2  412.72
  4796.4  412.44  4802.3  413.45  4811.7  411.44  4817.6  413.04  4823.9  410.42
  4834.6  409.89  4835.3  409.09  4842.9  409.89  4847.6  412.66  4854.0  413.01
  4943.4  413.12  4977.4  413.48  5000.1  410.62  5011.8  413.36  5088.4  412.06
  5169.8  412.12  5204.9  413.33  5317.0  419.05  5418.9  432.42  5486.8  437.82
#Mann=7,-1,0
  4041.0    0.05       0  4409.0    0.12       0  4591.5    0.05       0
  4743.2    0.12       0  4834.6    0.03       0  4842.9    0.12       0
  4943.4    0.05       0
Bank Sta=4436.1,5204.9
Exp/Cntr=0.3,0.1

Chan Stop Cuts=-1