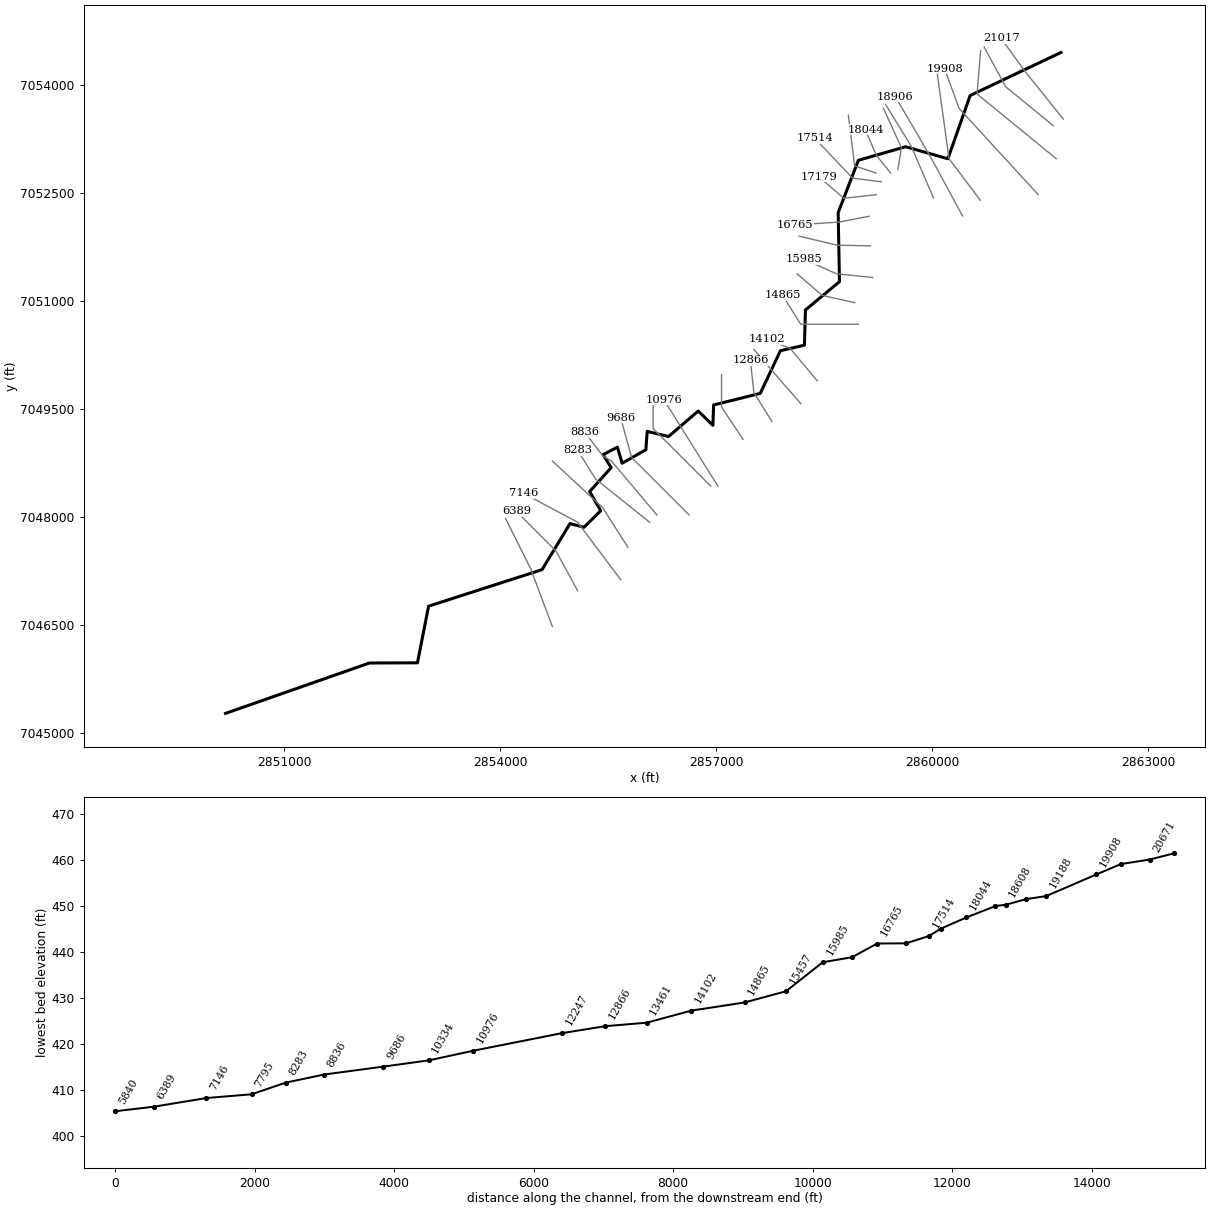
--- KINTCHLOE BRANCH.prj (project) ---

Proj Title=KINTCHLOE BRANCH Base Level Engineering
Current Plan=p01
Default Exp/Contr=0.3,0.1
English Units
Geom File=g01
Flow File=f01
Plan File=p01
BEGIN DESCRIPTION:
KINTCHLOE BRANCH
END DESCRIPTION:

--- KINTCHLOE BRANCH.p01 (plan) ---

Plan Title=Multiple Run
Short Identifier=Multiple
Geom File=g01
Flow File=f01
Subcritical Flow
K Sum by GR= 0
Std Step Tol= 0.01
Critical Tol= 0.01
Num of Std Step Trials= 20
Max Error Tol= 0.3
Flow Tol Ratio= 0.001
Split Flow NTrial= 30
Split Flow Tol= 0.02
Split Flow Ratio= 0.02
Log Output Level= 0
Friction Slope Method= 1
Unsteady Friction Slope Method= 2
Unsteady Bridges Friction Slope Method= 1
Parabolic Critical Depth
Global Vel Dist=  1 , 1 , 1
Global Log Level= 0
CheckData=True
Encroach Param= -1, 0, 0, 0
BEGIN DESCRIPTION:
Multiple Run
END DESCRIPTION:

--- KINTCHLOE BRANCH.f01 (steady flow) ---

Flow Title=Multiple
Number of Profiles=7
Profile Names=10-year,25-year,50-year,1pct_min,100-year,1pct_plu,500-year
River Rch & RM= KINTCHLOE BRANCH,Reach-1,21017
     338     437     514     302     602    1201     825
River Rch & RM= KINTCHLOE BRANCH,Reach-1,18461
     709     958    1162     700    1397    2786    2021
River Rch & RM= KINTCHLOE BRANCH,Reach-1,14102
     811    1101    1339     808    1612    3217    2344
River Rch & RM= KINTCHLOE BRANCH,Reach-1,10976
    1106    1517    1857    1127    2248    4486    3304
Boundary for River Rch & Prof#=KINTCHLOE BRANCH,Reach-1,1
Up Type=0
Dn Type=3
Dn Slope=0.005
Boundary for River Rch & Prof#=KINTCHLOE BRANCH,Reach-1,2
Up Type=0
Dn Type=3
Dn Slope=0.005
Boundary for River Rch & Prof#=KINTCHLOE BRANCH,Reach-1,3
Up Type=0
Dn Type=3
Dn Slope=0.005
Boundary for River Rch & Prof#=KINTCHLOE BRANCH,Reach-1,4
Up Type=0
Dn Type=3
Dn Slope=0.005
Boundary for River Rch & Prof#=KINTCHLOE BRANCH,Reach-1,5
Up Type=0
Dn Type=3
Dn Slope=0.005
Boundary for River Rch & Prof#=KINTCHLOE BRANCH,Reach-1,6
Up Type=0
Dn Type=3
Dn Slope=0.005
Boundary for River Rch & Prof#=KINTCHLOE BRANCH,Reach-1,7
Up Type=0
Dn Type=3
Dn Slope=0.005

--- KINTCHLOE BRANCH.g01 (geometry) ---

Geom Title=Existing Conditions

River Reach=KINTCHLOE BRANCH,Reach-1
Reach XY= 30
      2861790.59      7054450.71      2860528.99      7053852.60
      2860220.35      7052974.12      2859633.79      7053141.06
      2858976.76      7052953.00      2858695.91      7052226.56
      2858713.78      7051266.29      2858240.93      7050873.27
      2858227.14      7050384.02      2857893.58      7050307.20
      2857613.46      7049714.37      2856965.20      7049553.54
      2856955.59      7049270.71      2856751.48      7049469.02
      2856339.04      7049114.95      2856042.44      7049186.15
      2856024.27      7048931.25      2855693.98      7048743.95
      2855628.94      7048967.02      2855429.38      7048862.93
      2855541.69      7048682.90      2855243.06      7048350.52
      2855396.75      7048083.81      2855164.15      7047853.96
      2854970.19      7047905.79      2854581.63      7047265.36
      2853005.19      7046758.04      2852850.59      7045970.97
      2852182.51      7045968.16      2850184.44      7045268.50

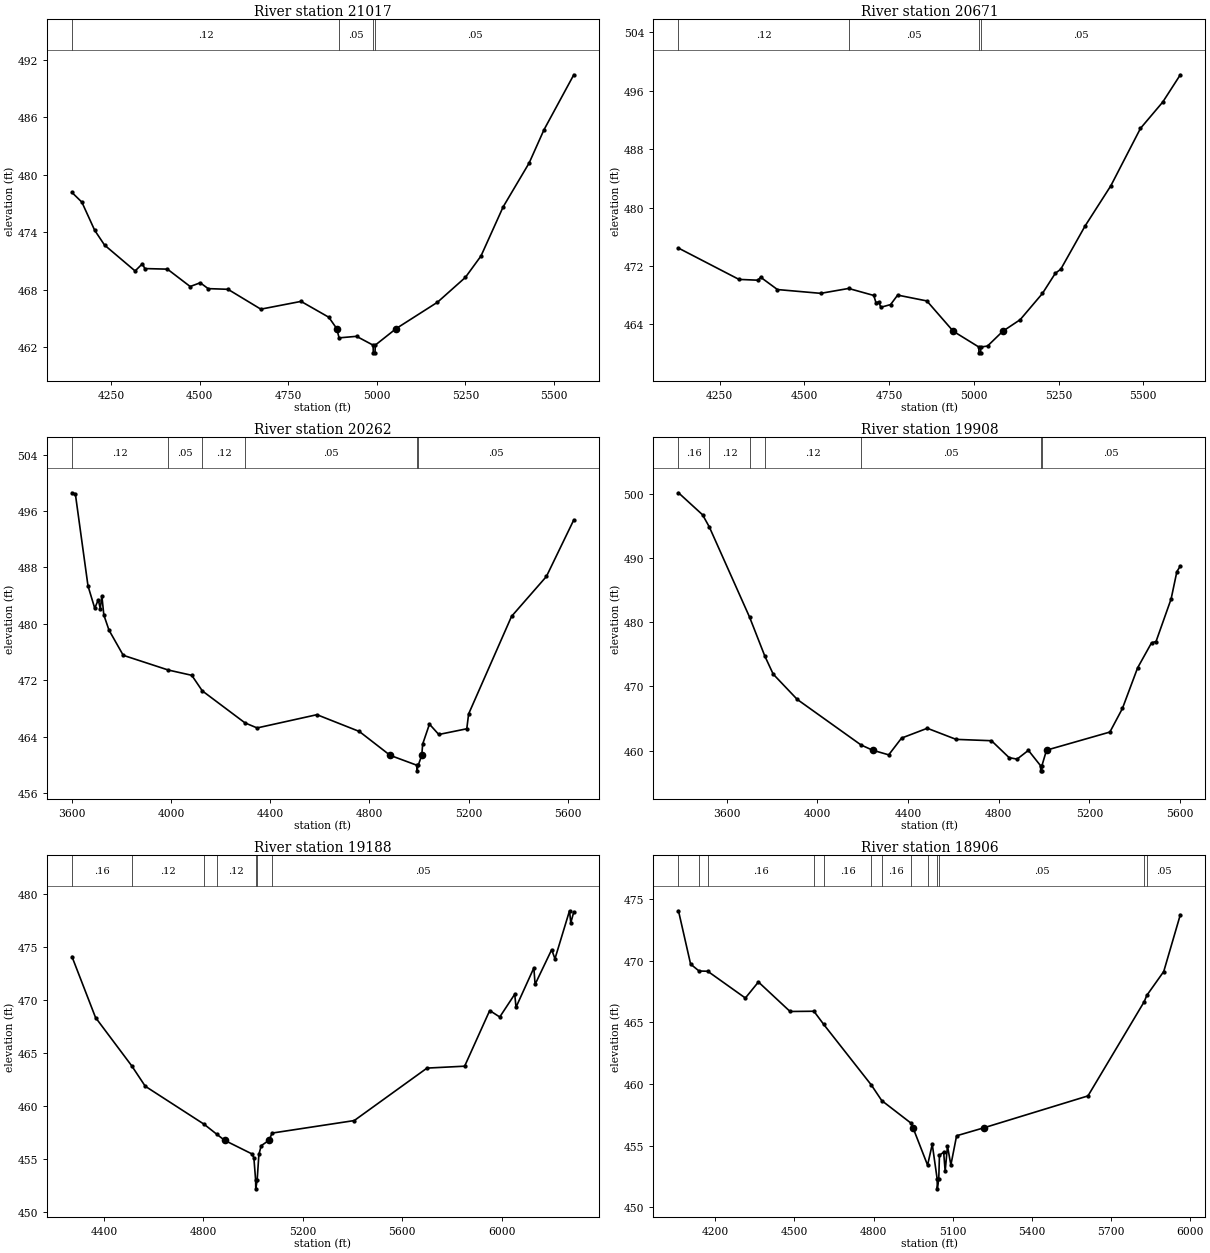
Type RM Length L Ch R = 1,21017,346,346,346
BEGIN DESCRIPTION:
KINTCHLOE BRANCH 34.0
END DESCRIPTION:
XS GIS Cut Line= 3
      2861825.01      7053524.99      2861298.51      7054178.47
      2860959.98      7054647.21
#Sta/Elev= 30
  4138.7  478.15  4166.7  477.14  4202.9  474.21  4230.7  472.67  4317.1  469.97
  4337.9  470.73  4344.3  470.22  4408.4  470.16  4472.6  468.35  4501.0  468.74
  4523.4  468.13  4579.4  468.06  4672.2  465.99  4785.7  466.80  4864.1  465.15
  4886.5  463.97  4893.2  463.00  4942.5  463.16  4989.3  462.24  4989.8  461.44
  4994.8  461.44  4995.3  462.24  5054.5  463.97  5171.0  466.71  5249.9  469.30
  5294.0  471.53  5356.6  476.65  5430.0  481.22  5471.9  484.68  5556.1  490.41
#Mann=4,-1,0
  4138.7    0.12       0  4893.2    0.05       0  4989.3    0.03       0
  4995.3    0.05       0
Bank Sta=4886.5,5054.5
Exp/Cntr=0.3,0.1

Type RM Length L Ch R = 1,20671,409,409,409
BEGIN DESCRIPTION:
KINTCHLOE BRANCH 33.0
END DESCRIPTION:
XS GIS Cut Line= 3
      2861683.95      7053433.66      2861022.47      7053975.34
      2860724.98      7054525.03
#Sta/Elev= 30
  4129.0  474.45  4307.4  470.16  4363.4  470.05  4371.3  470.46  4420.8  468.77
  4548.5  468.25  4630.8  468.92  4705.0  467.96  4711.5  466.96  4719.4  467.09
  4725.8  466.34  4754.5  466.71  4775.4  468.01  4861.5  467.21  4939.3  463.06
  5014.7  460.90  5015.2  460.10  5020.2  460.10  5020.7  460.90  5040.4  461.03
  5085.5  463.06  5136.7  464.64  5202.3  468.23  5240.4  471.00  5256.5  471.56
  5327.9  477.46  5404.0  482.98  5491.5  490.85  5557.1  494.45  5609.0  498.19
#Mann=4,-1,0
  4129.0    0.12       0  4630.8    0.05       0  5014.7    0.03       0
  5020.7    0.05       0
Bank Sta=4939.3,5085.5
Exp/Cntr=0.3,0.1

Type RM Length L Ch R = 1,20262,354,354,354
BEGIN DESCRIPTION:
KINTCHLOE BRANCH 32.0
END DESCRIPTION:
XS GIS Cut Line= 3
      2861725.04      7052974.97      2860625.00      7053875.00
      2860675.00      7054475.00
#Sta/Elev= 30
  3600.3  498.60  3614.0  498.45  3665.0  485.38  3692.2  482.21  3706.6  483.42
  3714.5  482.14  3720.9  483.98  3728.8  481.26  3749.7  479.10  3807.1  475.53
  3988.7  473.44  4083.4  472.69  4125.9  470.48  4298.3  465.93  4346.9  465.22
  4588.1  467.10  4758.9  464.72  4883.2  461.33  4990.6  459.93  4991.1  459.13
  4996.6  459.93  5010.7  461.33  5014.4  462.93  5041.7  465.76  5079.3  464.29
  5192.2  465.10  5199.7  467.21  5372.8  481.06  5513.3  486.72  5623.7  494.75
#Mann=6,-1,0
  3600.3    0.12       0  3988.7    0.05       0  4125.9    0.12       0
  4298.3    0.05       0  4990.6    0.03       0  4996.6    0.05       0
Bank Sta=4883.2,5010.7
Exp/Cntr=0.3,0.1

Type RM Length L Ch R = 1,19908,720,720,720
BEGIN DESCRIPTION:
KINTCHLOE BRANCH 31.0
END DESCRIPTION:
XS GIS Cut Line= 3
      2861474.98      7052475.02      2860375.00      7053675.00
      2860175.00      7054225.01
#Sta/Elev= 30
  3387.7  500.16  3494.0  496.73  3523.8  494.83  3701.3  480.79  3768.6  474.72
  3805.4  471.92  3911.5  467.98  4192.7  460.89  4243.4  460.08  4314.8  459.35
  4371.5  461.96  4485.0  463.49  4612.0  461.76  4768.0  461.55  4845.7  458.92
  4880.8  458.68  4930.8  460.05  4984.5  457.66  4985.0  456.86  4990.0  456.86
  4990.5  457.66  5010.7  460.08  5290.2  462.90  5345.4  466.57  5412.6  472.91
  5473.8  476.79  5493.7  477.00  5560.2  483.63  5585.5  487.87  5600.8  488.76
#Mann=7,-1,0
  3387.7    0.16       0  3523.8    0.12       0  3701.3    0.16       0
  3768.6    0.12       0  4192.7    0.05       0  4984.5    0.03       0
  4990.5    0.05       0
Bank Sta=4243.4,5010.7
Exp/Cntr=0.3,0.1

Type RM Length L Ch R = 1,19188,282,282,282
BEGIN DESCRIPTION:
Mapping XS 613f7b83
END DESCRIPTION:
XS GIS Cut Line= 3
      2860670.04      7052398.08      2860236.01      7052975.34
      2860058.06      7054260.05
#Sta/Elev= 30
  4271.0  474.06  4365.9  468.31  4511.6  463.75  4565.9  461.83  4802.3  458.25
  4854.3  457.29  4885.0  456.73  4995.6  455.44  5003.0  455.08  5010.1  452.95
  5010.6  452.15  5016.1  452.95  5023.2  455.40  5032.6  456.22  5063.8  456.73
  5076.4  457.41  5406.8  458.59  5699.6  463.54  5851.0  463.72  5951.9  468.97
  5992.3  468.36  6052.6  470.51  6057.7  469.28  6129.5  472.99  6134.5  471.44
  6201.2  474.71  6214.4  473.85  6273.0  478.38  6278.1  477.24  6290.2  478.28
#Mann=7,-1,0
  4271.0    0.16       0  4511.6    0.12       0  4802.3    0.16       0
  4854.3    0.12       0  5010.1    0.07       0  5016.1    0.12       0
  5076.4    0.05       0
Bank Sta=4885,5063.8
Exp/Cntr=0.3,0.1

Type RM Length L Ch R = 1,18906,298,298,298
BEGIN DESCRIPTION:
Mapping XS 2653e080
END DESCRIPTION:
XS GIS Cut Line= 4
      2860422.63      7052181.09      2860023.34      7052918.92
      2859817.09      7053279.94      2859489.49      7053836.34
#Sta/Elev= 30
  4061.3  474.04  4107.2  469.72  4139.2  469.16  4172.1  469.14  4314.6  466.97
  4364.0  468.27  4483.9  465.88  4574.2  465.90  4611.4  464.83  4791.7  459.92
  4831.1  458.66  4941.4  456.84  4949.6  456.45  5004.6  453.43  5022.3  455.12
  5040.9  452.31  5041.4  451.51  5046.9  452.31  5049.6  454.24  5065.5  454.47
  5071.2  452.93  5080.0  454.98  5092.8  453.44  5114.5  455.81  5216.9  456.45
  5612.0  459.04  5825.1  466.68  5834.6  467.18  5898.9  469.12  5961.7  473.72
#Mann=13,-1,0
  4061.3    0.16       0  4139.2    0.05       0  4172.1    0.16       0
  4574.2    0.08       0  4611.4    0.16       0  4791.7    0.05       0
  4831.1    0.16       0  4941.4    0.12       0  5004.6    0.05       0
  5040.9    0.07       0  5046.9    0.05       0  5825.1    0.08       0
  5834.6    0.05       0
Bank Sta=4949.6,5216.9
Exp/Cntr=0.3,0.1

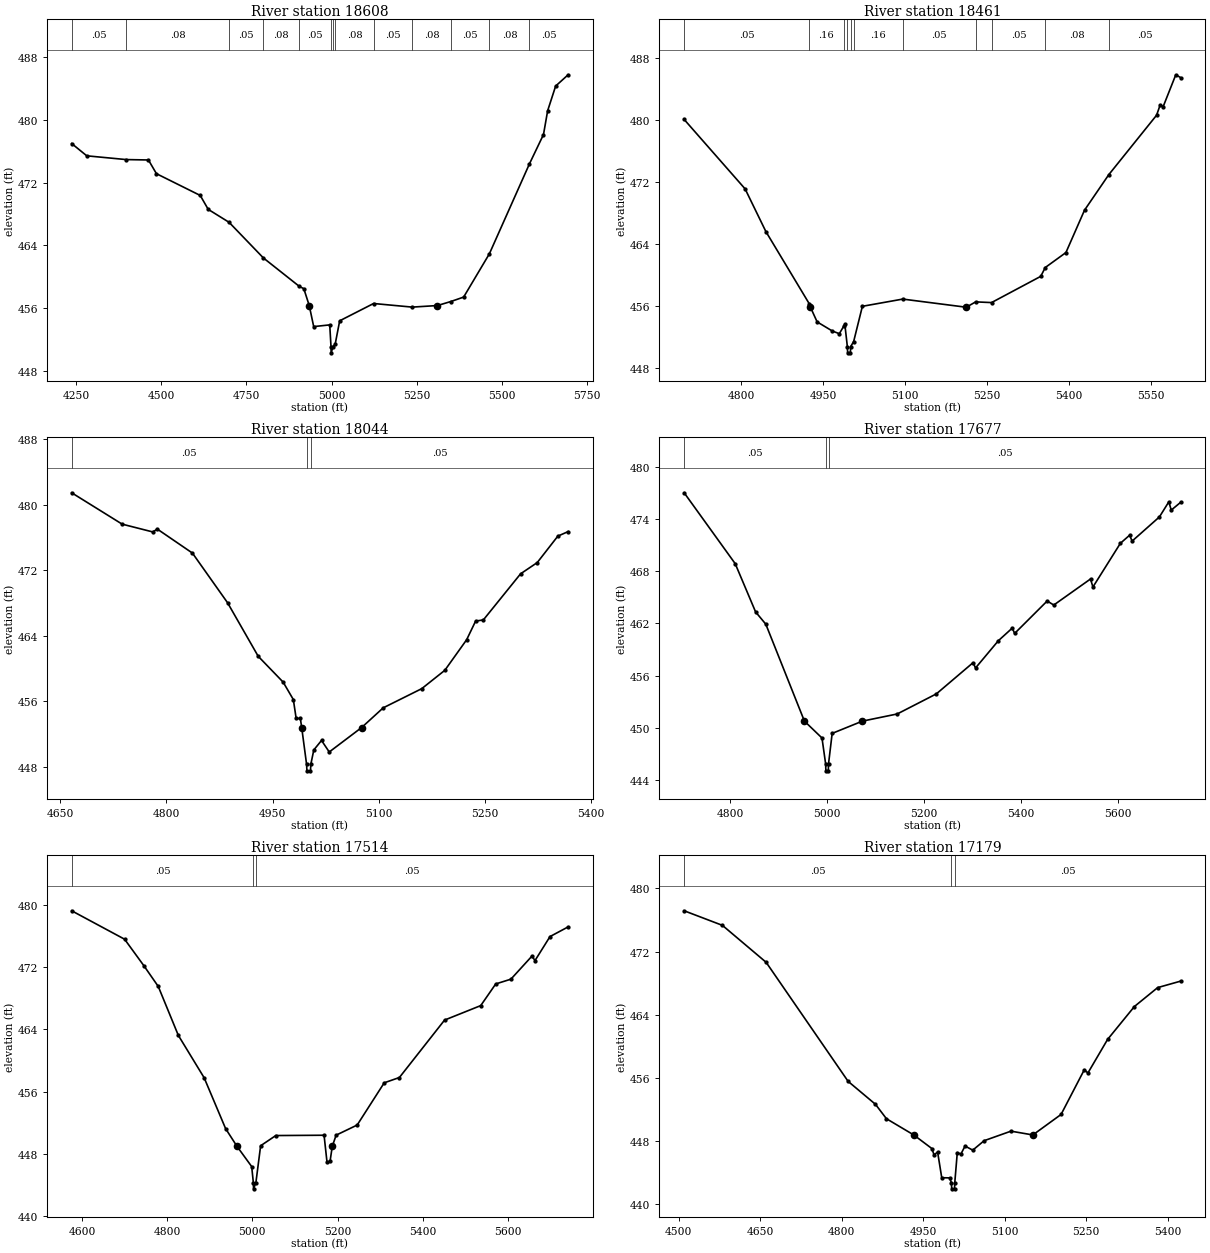
Type RM Length L Ch R = 1,18608,147,147,147
BEGIN DESCRIPTION:
Mapping XS b95d8756
END DESCRIPTION:
XS GIS Cut Line= 3
      2860019.01      7052432.77      2859710.84      7053148.96
      2859354.95      7053726.19
#Sta/Elev= 30
  4236.7  477.00  4281.0  475.43  4396.9  474.95  4462.1  474.90  4485.6  473.15
  4614.2  470.37  4637.7  468.59  4698.9  466.94  4799.6  462.39  4905.1  458.76
  4918.4  458.46  4934.3  456.31  4947.4  453.62  4994.5  453.84  4998.2  451.07
  4998.7  450.27  5004.2  451.07  5010.5  451.38  5023.7  454.36  5123.3  456.57
  5236.6  456.11  5310.7  456.31  5349.9  456.82  5387.7  457.39  5463.2  462.91
  5580.9  474.40  5622.2  478.15  5634.4  481.19  5657.9  484.34  5694.5  485.78
#Mann=13,-1,0
  4236.7    0.05       0  4396.9    0.08       0  4698.9    0.05       0
  4799.6    0.08       0  4905.1    0.05       0  4998.2    0.03       0
  5004.2    0.05       0  5010.5    0.08       0  5123.3    0.05       0
  5236.6    0.08       0  5349.9    0.05       0  5463.2    0.08       0
  5580.9    0.05       0
Bank Sta=4934.3,5310.7
Exp/Cntr=0.3,0.1

Type RM Length L Ch R = 1,18461,417,417,417
BEGIN DESCRIPTION:
KINTCHLOE BRANCH 27.0
END DESCRIPTION:
XS GIS Cut Line= 3
      2859525.00      7052824.99      2859575.00      7053125.00
      2859325.00      7053675.00
#Sta/Elev= 30
  4695.6  480.08  4807.1  471.13  4845.1  465.63  4924.3  456.34  4926.6  455.88
  4938.9  453.98  4966.8  452.80  4979.5  452.46  4987.3  453.39  4989.6  453.66
  4994.2  450.79  4994.7  449.99  4999.7  449.99  5000.2  450.79  5005.7  451.44
  5021.7  455.99  5095.6  456.92  5211.7  455.87  5229.0  456.56  5258.0  456.47
  5348.0  459.85  5356.3  460.99  5394.1  462.92  5428.1  468.38  5472.5  472.96
  5560.0  480.63  5566.6  481.97  5572.0  481.73  5595.1  485.84  5603.9  485.48
#Mann=11,-1,0
  4695.6    0.05       0  4924.3    0.16       0  4987.3    0.08       0
  4994.2    0.07       0  5000.2    0.08       0  5005.7    0.16       0
  5095.6    0.05       0  5229.0    0.08       0  5258.0    0.05       0
  5356.3    0.08       0  5472.5    0.05       0
Bank Sta=4926.6,5211.7
Exp/Cntr=0.3,0.1

Type RM Length L Ch R = 1,18044,367,367,367
BEGIN DESCRIPTION:
KINTCHLOE BRANCH 26.0
END DESCRIPTION:
XS GIS Cut Line= 3
      2859425.01      7052774.98      2859225.00      7053025.00
      2859074.99      7053375.03
#Sta/Elev= 30
  4666.3  481.45  4737.6  477.62  4780.8  476.67  4787.2  477.02  4836.8  474.09
  4886.4  468.03  4929.7  461.49  4964.9  458.34  4979.3  456.21  4983.3  453.90
  4989.2  453.90  4991.1  452.80  4998.0  448.31  4998.5  447.51  5003.5  447.51
  5004.0  448.31  5008.2  450.06  5019.1  451.22  5030.0  449.81  5075.8  452.80
  5106.2  455.20  5160.6  457.54  5193.2  459.78  5224.0  463.51  5236.7  465.79
  5247.6  465.93  5300.2  471.56  5323.7  472.93  5352.8  476.16  5367.3  476.71
#Mann=3,-1,0
  4666.3    0.05       0  4998.0    0.03       0  5004.0    0.05       0
Bank Sta=4991.1,5075.8
Exp/Cntr=0.3,0.1

Type RM Length L Ch R = 1,17677,163,163,163
BEGIN DESCRIPTION:
KINTCHLOE BRANCH 25.0
END DESCRIPTION:
XS GIS Cut Line= 3
      2859224.96      7052775.01      2858925.00      7052875.00
      2858837.52      7053578.39
#Sta/Elev= 30
  4705.2  476.99  4810.6  468.85  4852.7  463.31  4873.8  461.90  4953.5  450.77
  4989.8  448.83  4997.3  445.86  4997.8  445.06  5002.8  445.06  5003.3  445.86
  5010.8  449.36  5073.3  450.77  5145.1  451.59  5226.0  453.90  5301.7  457.48
  5306.8  456.87  5353.9  460.00  5382.6  461.45  5387.6  460.84  5454.7  464.56
  5468.4  464.10  5544.2  467.09  5549.2  466.17  5605.9  471.19  5625.0  472.12
  5630.1  471.44  5686.5  474.22  5705.9  475.95  5710.9  475.00  5730.2  475.89
#Mann=3,-1,0
  4705.2    0.05       0  4997.3    0.03       0  5003.3    0.05       0
Bank Sta=4953.5,5073.3
Exp/Cntr=0.3,0.1

Type RM Length L Ch R = 1,17514,335,335,335
BEGIN DESCRIPTION:
Mapping XS 949bb2e5
END DESCRIPTION:
XS GIS Cut Line= 3
      2859293.28      7052653.95      2858893.94      7052706.04
      2858370.15      7053260.13
#Sta/Elev= 30
  4576.0  479.20  4700.2  475.55  4745.7  472.13  4779.2  469.49  4826.4  463.20
  4886.9  457.77  4937.3  451.24  4964.2  448.95  4998.5  446.37  5002.4  444.31
  5002.9  443.51  5008.4  444.31  5019.5  449.04  5055.1  450.35  5168.4  450.39
  5175.3  446.93  5182.5  447.06  5187.6  448.95  5196.7  450.40  5246.1  451.70
  5309.6  457.12  5345.2  457.80  5451.2  465.17  5536.1  467.03  5571.3  469.81
  5606.9  470.42  5656.3  473.38  5663.5  472.81  5698.7  475.89  5741.2  477.13
#Mann=3,-1,0
  4576.0    0.05       0  5002.4    0.03       0  5008.4    0.05       0
Bank Sta=4964.2,5187.6
Exp/Cntr=0.3,0.1

Type RM Length L Ch R = 1,17179,414,414,414
BEGIN DESCRIPTION:
KINTCHLOE BRANCH 24.0
END DESCRIPTION:
XS GIS Cut Line= 3
      2859224.98      7052475.00      2858775.00      7052425.00
      2858425.02      7052724.98
#Sta/Elev= 30
  4509.9  477.17  4580.3  475.32  4660.8  470.63  4811.7  455.52  4862.0  452.61
  4882.2  450.78  4932.5  448.72  4965.9  446.99  4969.8  446.19  4976.4  446.55
  4984.0  443.29  4998.3  443.27  5001.8  442.68  5002.3  441.88  5007.5  441.88
  5008.0  442.68  5012.6  446.48  5019.2  446.29  5026.9  447.31  5041.1  446.79
  5062.0  447.99  5111.4  449.20  5151.7  448.72  5203.6  451.32  5246.4  457.00
  5253.0  456.58  5289.2  460.84  5338.6  465.02  5381.4  467.42  5423.6  468.24
#Mann=3,-1,0
  4509.9    0.05       0  5001.8    0.03       0  5008.0    0.05       0
Bank Sta=4932.5,5151.7
Exp/Cntr=0.3,0.1

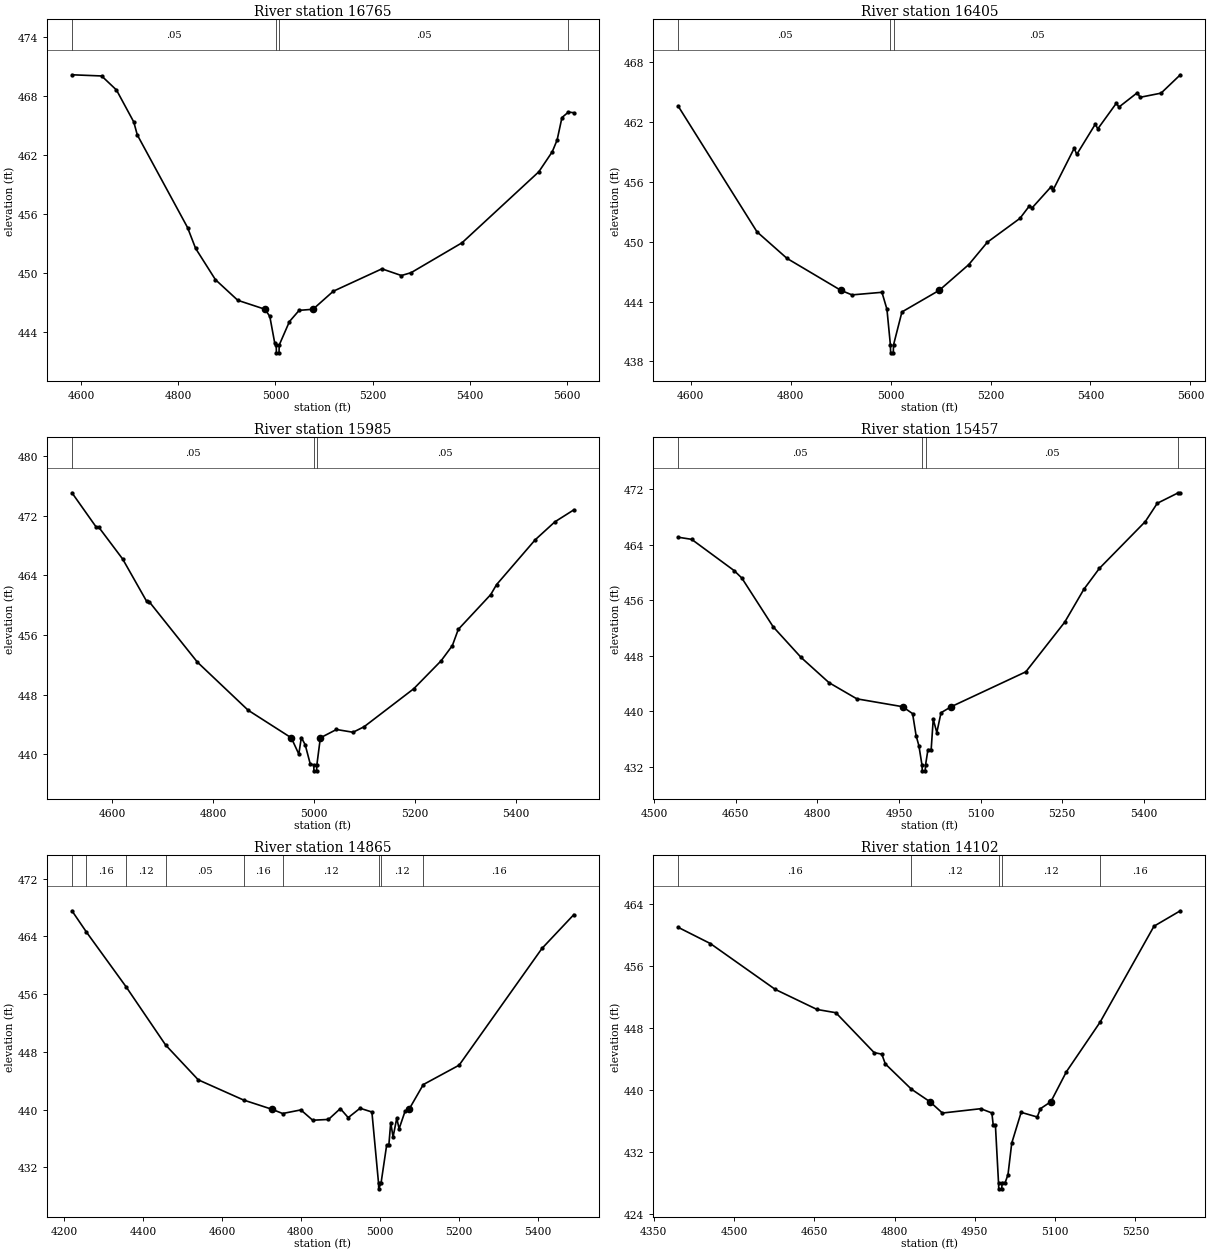
Type RM Length L Ch R = 1,16765,360,360,360
BEGIN DESCRIPTION:
KINTCHLOE BRANCH 23.0
END DESCRIPTION:
XS GIS Cut Line= 3
      2859124.99      7052175.00      2858708.23      7052094.27
      2858100.59      7052055.21
#Sta/Elev= 30
  4580.9  470.11  4642.0  469.99  4672.6  468.56  4708.2  465.31  4715.4  464.00
  4818.9  454.58  4835.5  452.46  4876.3  449.28  4922.4  447.18  4978.4  446.27
  4988.3  445.54  4998.5  442.81  5001.4  442.64  5001.9  441.84  5007.2  441.84
  5007.7  442.64  5028.7  445.02  5048.7  446.16  5077.2  446.27  5118.9  448.10
  5219.1  450.38  5259.2  449.70  5279.2  449.99  5384.1  453.03  5542.2  460.25
  5569.8  462.28  5579.8  463.47  5589.8  465.76  5603.1  466.32  5614.3  466.25
#Mann=4,-1,0
  4580.9    0.05       0  5001.4    0.03       0  5007.7    0.05       0
  5603.1    0.16       0
Bank Sta=4978.4,5077.2
Exp/Cntr=0.3,0.1

Type RM Length L Ch R = 1,16405,420,420,420
BEGIN DESCRIPTION:
Mapping XS 9141f1a3
END DESCRIPTION:
XS GIS Cut Line= 3
      2859142.26      7051764.41      2858682.19      7051773.09
      2858152.69      7051898.95
#Sta/Elev= 30
  4575.4  463.56  4732.7  450.99  4792.7  448.33  4900.4  445.13  4922.7  444.67
  4982.7  444.93  4992.7  443.23  4999.6  439.66  5000.1  438.86  5005.4  438.86
  5005.9  439.66  5022.7  442.96  5097.4  445.13  5156.5  447.71  5193.6  449.95
  5258.8  452.34  5277.9  453.60  5283.1  453.39  5320.1  455.45  5325.2  455.19
  5367.4  459.37  5372.6  458.76  5409.6  461.78  5414.7  461.32  5451.8  463.89
  5456.9  463.50  5494.0  464.95  5499.1  464.48  5541.3  464.90  5579.8  466.74
#Mann=3,-1,0
  4575.4    0.05       0  4999.6    0.03       0  5005.9    0.05       0
Bank Sta=4900.4,5097.4
Exp/Cntr=0.3,0.1

Type RM Length L Ch R = 1,15985,528,528,528
BEGIN DESCRIPTION:
KINTCHLOE BRANCH 22.0
END DESCRIPTION:
XS GIS Cut Line= 3
      2859174.96      7051325.00      2858675.00      7051375.00
      2858225.00      7051575.00
#Sta/Elev= 30
  4520.3  475.10  4568.0  470.53  4573.0  470.52  4620.8  466.21  4668.5  460.51
  4673.5  460.47  4769.0  452.36  4869.5  445.91  4955.1  442.20  4970.0  440.02
  4975.0  442.24  4982.6  441.28  4992.6  438.71  4999.5  438.57  5000.0  437.77
  5005.3  437.77  5005.8  438.57  5012.7  442.20  5044.6  443.32  5077.5  442.95
  5099.4  443.69  5197.8  448.79  5251.9  452.53  5274.4  454.59  5286.1  456.76
  5350.4  461.43  5362.0  462.77  5438.6  468.79  5477.6  471.20  5515.2  472.81
#Mann=3,-1,0
  4520.3    0.05       0  4999.5    0.03       0  5005.8    0.05       0
Bank Sta=4955.1,5012.7
Exp/Cntr=0.3,0.1

Type RM Length L Ch R = 1,15457,592,592,592
BEGIN DESCRIPTION:
KINTCHLOE BRANCH 21.0
END DESCRIPTION:
XS GIS Cut Line= 3
      2858925.00      7050975.00      2858475.00      7051075.00
      2858124.97      7051375.03
#Sta/Elev= 30
  4544.9  465.06  4569.2  464.76  4647.3  460.26  4661.4  459.19  4719.0  452.17
  4770.3  447.76  4821.5  444.14  4872.7  441.81  4956.7  440.68  4975.1  439.68
  4981.5  436.53  4986.7  435.05  4992.4  432.25  4992.9  431.45  4998.3  431.45
  4998.8  432.25  5003.3  434.50  5009.2  434.50  5013.0  438.88  5019.6  436.96
  5027.3  439.81  5046.0  440.68  5183.1  445.70  5254.5  452.84  5289.6  457.56
  5318.1  460.57  5402.6  467.32  5424.6  469.95  5463.2  471.46  5466.9  471.46
#Mann=4,-1,0
  4544.9    0.05       0  4992.4    0.03       0  4998.8    0.05       0
  5463.2    0.16       0
Bank Sta=4956.7,5046
Exp/Cntr=0.3,0.1

Type RM Length L Ch R = 1,14865,763,763,763
BEGIN DESCRIPTION:
KINTCHLOE BRANCH 20.0
END DESCRIPTION:
XS GIS Cut Line= 3
      2858975.03      7050675.00      2858175.00      7050675.00
      2857925.01      7051074.98
#Sta/Elev= 30
  4220.0  467.56  4256.7  464.61  4357.6  456.99  4457.4  448.95  4540.0  444.13
  4654.8  441.33  4727.2  440.04  4753.8  439.46  4800.0  439.96  4830.0  438.53
  4870.0  438.64  4900.0  440.14  4920.0  438.89  4950.0  440.19  4980.0  439.67
  4996.8  429.82  4997.3  429.02  5003.2  429.82  5017.5  435.12  5023.0  435.12
  5027.7  438.21  5033.6  436.20  5043.0  438.82  5048.9  437.34  5064.2  439.80
  5074.1  440.04  5110.2  443.47  5201.0  446.16  5410.9  462.34  5491.7  467.03
#Mann=9,-1,0
  4220.0    0.12       0  4256.7    0.16       0  4357.6    0.12       0
  4457.4    0.05       0  4654.8    0.16       0  4753.8    0.12       0
  4996.8    0.07       0  5003.2    0.12       0  5110.2    0.16       0
Bank Sta=4727.2,5074.1
Exp/Cntr=0.3,0.1

Type RM Length L Ch R = 1,14102,641,641,641
BEGIN DESCRIPTION:
KINTCHLOE BRANCH 19.0
END DESCRIPTION:
XS GIS Cut Line= 3
      2858404.41      7049889.42      2858026.81      7050340.80
      2857701.29      7050466.66
#Sta/Elev= 30
  4396.3  460.94  4456.1  458.86  4577.1  452.96  4655.2  450.37  4690.4  449.95
  4761.9  444.81  4776.2  444.61  4782.7  443.36  4831.4  440.10  4866.1  438.48
  4889.4  437.02  4961.0  437.58  4981.8  437.03  4984.3  435.47  4988.4  435.47
  4994.2  428.05  4994.7  427.25  5000.3  427.25  5000.8  428.05  5006.6  428.06
  5011.9  429.07  5018.9  433.14  5036.5  437.11  5066.5  436.51  5072.5  437.58
  5092.0  438.48  5121.0  442.34  5183.9  448.73  5284.6  461.10  5333.8  463.09
#Mann=5,-1,0
  4396.3    0.16       0  4831.4    0.12       0  4994.2    0.07       0
  5000.8    0.12       0  5183.9    0.16       0
Bank Sta=4866.1,5092
Exp/Cntr=0.3,0.1

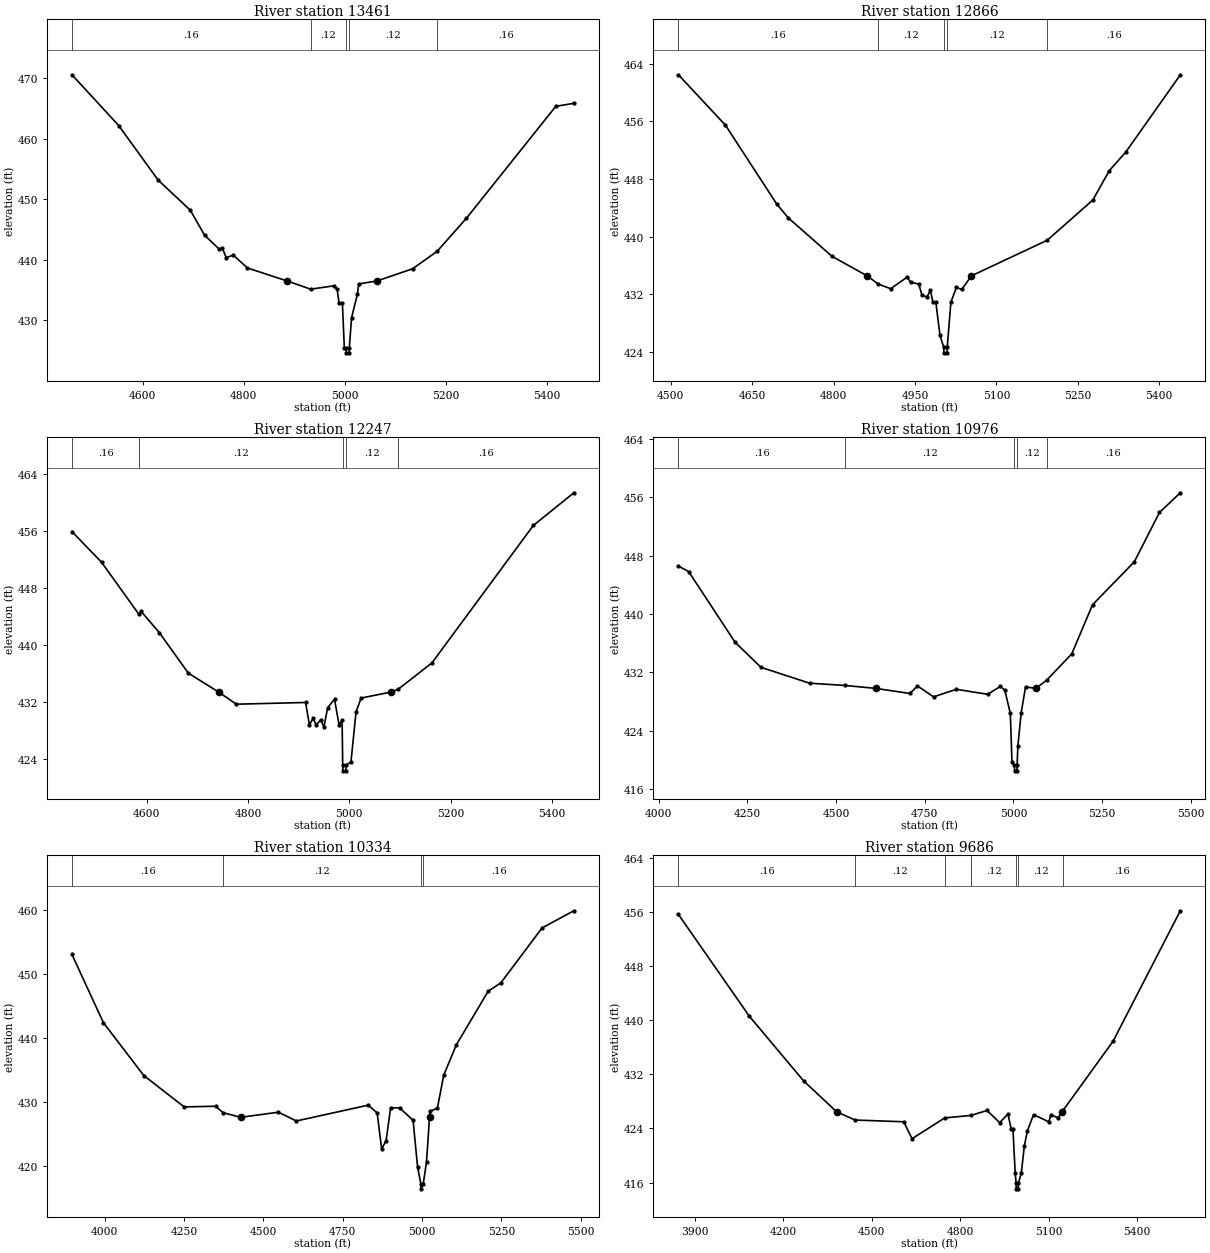
Type RM Length L Ch R = 1,13461,595,595,595
BEGIN DESCRIPTION:
KINTCHLOE BRANCH 18.0
END DESCRIPTION:
XS GIS Cut Line= 3
      2858175.00      7049575.00      2857825.00      7049975.00
      2857524.99      7050325.01
#Sta/Elev= 30
  4460.1  470.54  4552.6  462.15  4630.5  453.15  4694.1  448.17  4722.5  444.03
  4751.0  441.77  4757.7  441.87  4765.2  440.33  4779.0  440.77  4807.0  438.64
  4885.9  436.48  4932.1  435.13  4977.9  435.69  4984.5  435.17  4988.3  432.79
  4994.9  432.79  4998.7  425.49  5002.0  425.42  5002.5  424.62  5008.1  424.62
  5008.6  425.42  5013.0  430.41  5024.5  434.27  5027.3  436.01  5062.9  436.48
  5133.7  438.50  5182.3  441.39  5240.2  446.85  5416.9  465.33  5452.6  465.83
#Mann=5,-1,0
  4460.1    0.16       0  4932.1    0.12       0  5002.0    0.07       0
  5008.6    0.12       0  5182.3    0.16       0
Bank Sta=4885.9,5062.9
Exp/Cntr=0.3,0.1

Type RM Length L Ch R = 1,12866,619,619,619
BEGIN DESCRIPTION:
KINTCHLOE BRANCH 17.0
END DESCRIPTION:
XS GIS Cut Line= 3
      2857775.02      7049324.98      2857525.00      7049725.00
      2857475.00      7050175.00
#Sta/Elev= 30
  4514.3  462.45  4601.0  455.45  4695.3  444.52  4716.6  442.60  4797.3  437.25
  4861.8  434.55  4882.2  433.41  4905.2  432.76  4935.9  434.38  4941.8  433.65
  4957.1  433.41  4963.0  431.82  4972.5  431.65  4978.4  432.56  4983.1  430.87
  4988.5  430.87  4996.1  426.28  5002.9  424.66  5003.4  423.86  5009.0  423.86
  5009.5  424.66  5016.2  430.88  5026.3  432.93  5036.3  432.66  5054.1  434.55
  5193.8  439.49  5277.8  445.08  5308.0  449.15  5338.2  451.71  5438.8  462.44
#Mann=5,-1,0
  4514.3    0.16       0  4882.2    0.12       0  5002.9    0.07       0
  5009.5    0.12       0  5193.8    0.16       0
Bank Sta=4861.8,5054.1
Exp/Cntr=0.3,0.1

Type RM Length L Ch R = 1,12247,1271,1271,1271
BEGIN DESCRIPTION:
KINTCHLOE BRANCH 16.0
END DESCRIPTION:
XS GIS Cut Line= 3
      2857375.00      7049075.01      2857075.00      7049525.00
      2857075.00      7049974.97
#Sta/Elev= 30
  4452.4  455.95  4511.0  451.63  4584.8  444.31  4589.1  444.73  4625.2  441.73
  4682.2  436.07  4742.1  433.41  4776.9  431.71  4913.6  431.95  4921.1  428.83
  4928.6  429.71  4934.6  428.80  4943.7  429.51  4949.7  428.47  4957.2  431.22
  4970.7  432.40  4979.7  428.82  4985.7  429.44  4986.9  423.15  4987.4  422.35
  4993.0  422.35  4993.5  423.15  5003.2  423.60  5013.2  430.61  5023.2  432.57
  5081.9  433.41  5096.1  433.79  5163.2  437.52  5363.2  456.81  5443.2  461.40
#Mann=5,-1,0
  4452.4    0.16       0  4584.8    0.12       0  4986.9    0.07       0
  4993.5    0.12       0  5096.1    0.16       0
Bank Sta=4742.1,5081.9
Exp/Cntr=0.3,0.1

Type RM Length L Ch R = 1,10976,642,642,642
BEGIN DESCRIPTION:
KINTCHLOE BRANCH 15.0
END DESCRIPTION:
XS GIS Cut Line= 3
      2857025.02      7048424.97      2856525.00      7049225.00
      2856275.02      7049624.97
#Sta/Elev= 30
  4055.4  446.57  4084.3  445.81  4215.2  436.13  4288.3  432.70  4425.1  430.53
  4524.8  430.22  4611.5  429.82  4708.2  429.12  4729.4  430.16  4774.8  428.66
  4839.0  429.69  4927.5  429.01  4963.5  430.10  4975.8  429.54  4991.2  426.39
  4995.9  419.68  5002.7  419.33  5003.3  418.53  5009.7  418.53  5010.4  419.33
  5012.4  421.89  5021.8  426.49  5034.2  430.02  5063.2  429.82  5093.2  430.92
  5164.5  434.55  5222.9  441.26  5340.8  447.15  5411.6  453.90  5470.5  456.60
#Mann=5,-1,0
  4055.4    0.16       0  4524.8    0.12       0  5002.7    0.07       0
  5010.4    0.12       0  5093.2    0.16       0
Bank Sta=4611.5,5063.2
Exp/Cntr=0.3,0.1

Type RM Length L Ch R = 1,10334,648,648,648
BEGIN DESCRIPTION:
KINTCHLOE BRANCH 14.0
END DESCRIPTION:
XS GIS Cut Line= 3
      2856924.99      7048425.01      2856125.00      7049225.00
      2856125.00      7049675.04
#Sta/Elev= 30
  3896.7  453.03  3995.7  442.38  4123.0  434.12  4250.2  429.22  4349.2  429.32
  4372.9  428.32  4427.9  427.59  4547.2  428.39  4603.8  427.02  4830.1  429.49
  4858.4  428.29  4872.5  422.65  4886.6  423.96  4900.8  429.09  4929.1  429.05
  4971.5  427.14  4985.6  419.88  4995.9  417.22  4996.6  416.42  5003.6  417.22
  5013.9  420.62  5023.3  427.59  5024.5  428.51  5048.1  429.01  5068.1  434.18
  5108.1  438.94  5208.1  447.28  5248.1  448.59  5378.1  457.18  5478.1  459.85
#Mann=4,-1,0
  3896.7    0.16       0  4372.9    0.12       0  4995.9    0.07       0
  5003.6    0.16       0
Bank Sta=4427.9,5023.3
Exp/Cntr=0.3,0.1

Type RM Length L Ch R = 1,9686,850,850,850
BEGIN DESCRIPTION:
KINTCHLOE BRANCH 13.0
END DESCRIPTION:
XS GIS Cut Line= 3
      2856625.02      7048024.98      2855825.00      7048825.00
      2855675.00      7049375.01
#Sta/Elev= 30
  3845.0  455.62  4085.4  440.58  4269.3  431.03  4381.0  426.47  4443.6  425.24
  4608.7  424.98  4637.0  422.48  4747.8  425.55  4836.8  425.92  4891.5  426.65
  4934.0  424.85  4962.3  426.14  4972.9  423.93  4979.0  423.93  4986.8  417.39
  4989.8  415.87  4990.4  415.07  4996.9  415.07  4997.5  415.87  5007.5  417.43
  5017.9  421.45  5028.2  423.67  5049.0  426.03  5100.8  424.97  5107.7  426.02
  5131.9  425.56  5146.7  426.47  5149.0  426.66  5318.5  436.88  5546.5  456.16
#Mann=7,-1,0
  3845.0    0.16       0  4443.6    0.12       0  4747.8    0.16       0
  4836.8    0.12       0  4989.8    0.07       0  4997.5    0.12       0
  5149.0    0.16       0
Bank Sta=4381,5146.7
Exp/Cntr=0.3,0.1

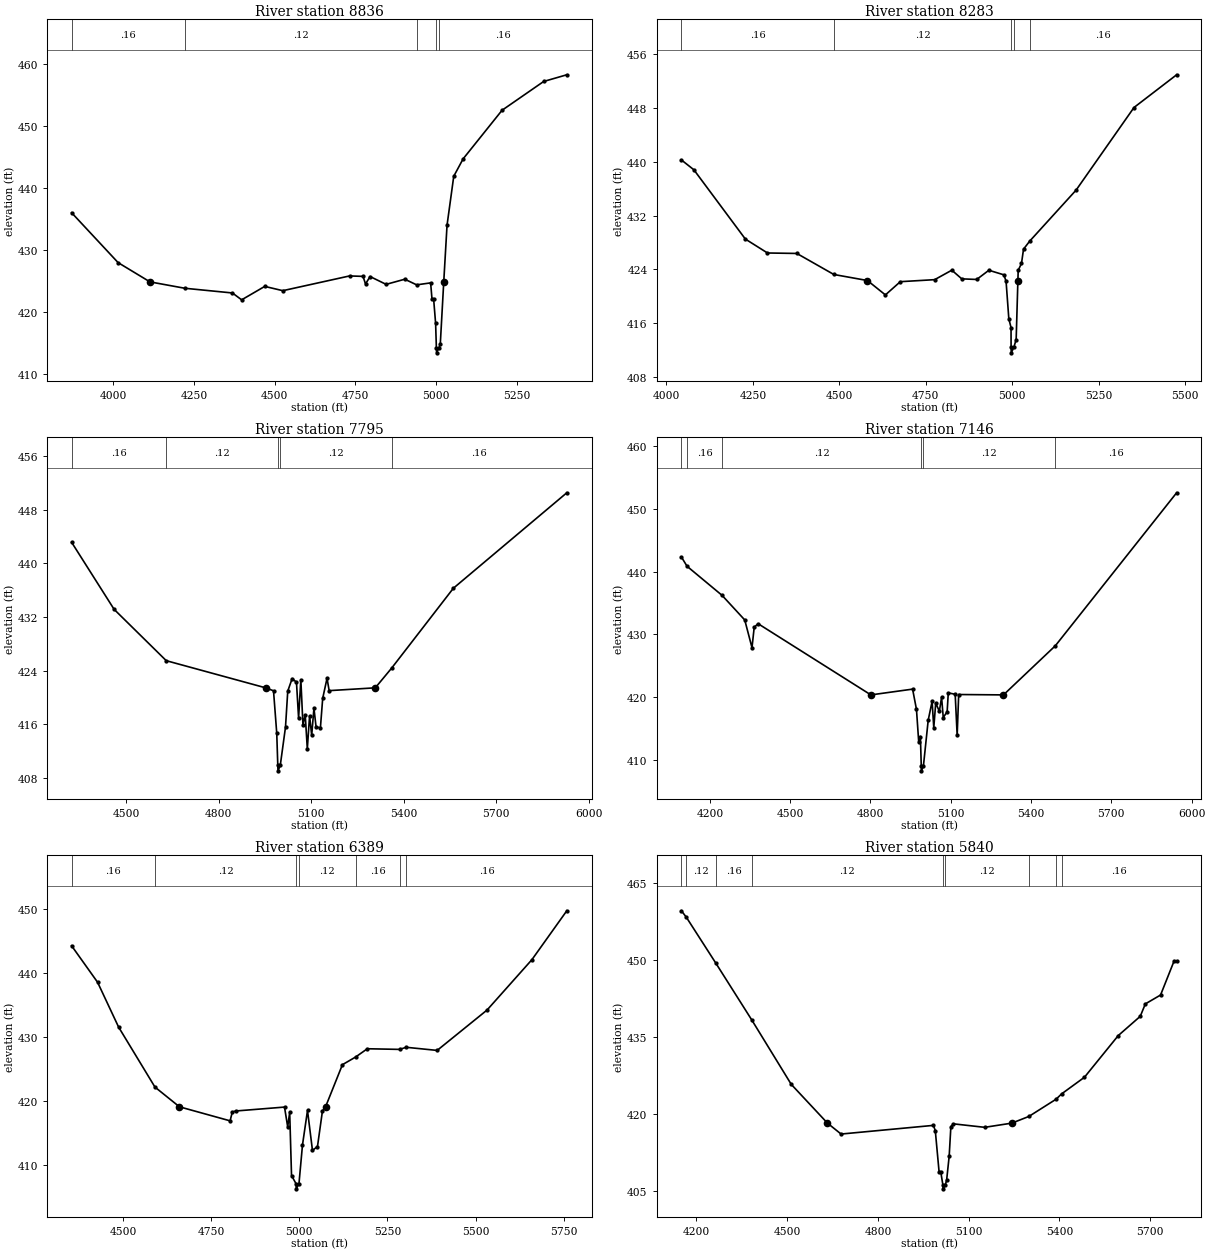
Type RM Length L Ch R = 1,8836,553,553,553
BEGIN DESCRIPTION:
KINTCHLOE BRANCH 12.0
END DESCRIPTION:
XS GIS Cut Line= 4
      2856177.34      7048024.90      2855545.38      7048774.92
      2855427.32      7048844.37      2855175.03      7049174.96
#Sta/Elev= 30
  3871.2  435.98  4015.2  427.92  4113.9  424.81  4221.8  423.78  4369.2  423.02
  4397.8  421.91  4469.3  424.08  4525.3  423.39  4732.0  425.77  4773.7  425.70
  4781.4  424.48  4795.7  425.67  4845.2  424.41  4903.0  425.24  4939.8  424.33
  4983.1  424.65  4987.4  421.97  4992.5  421.97  4998.5  418.12  5000.9  414.15
  5001.6  413.35  5008.7  414.15  5013.0  414.76  5023.7  424.81  5033.9  433.96
  5054.7  441.87  5083.7  444.68  5204.3  452.53  5333.2  457.18  5404.8  458.26
#Mann=5,-1,0
  3871.2    0.16       0  4221.8    0.12       0  4939.8    0.16       0
  5000.9    0.07       0  5008.7    0.16       0
Bank Sta=4113.9,5023.7
Exp/Cntr=0.3,0.1

Type RM Length L Ch R = 1,8283,488,488,488
BEGIN DESCRIPTION:
KINTCHLOE BRANCH 11.0
END DESCRIPTION:
XS GIS Cut Line= 3
      2856075.00      7047925.00      2855325.00      7048525.00
      2855074.99      7048925.02
#Sta/Elev= 30
  4043.3  440.28  4079.3  438.82  4228.2  428.51  4292.2  426.44  4377.1  426.37
  4484.1  423.24  4581.3  422.34  4633.2  420.20  4676.4  422.17  4775.7  422.47
  4825.3  423.88  4854.1  422.59  4897.3  422.50  4932.5  423.87  4975.8  423.19
  4982.2  422.24  4990.2  416.64  4996.6  415.34  4996.7  412.38  4997.3  411.58
  5004.5  412.38  5011.4  413.55  5016.4  422.34  5017.3  423.86  5026.8  424.88
  5032.7  427.01  5050.5  428.20  5184.8  435.80  5352.2  448.09  5475.5  452.96
#Mann=5,-1,0
  4043.3    0.16       0  4484.1    0.12       0  4996.7    0.07       0
  5004.5    0.12       0  5050.5    0.16       0
Bank Sta=4581.3,5016.4
Exp/Cntr=0.3,0.1

Type RM Length L Ch R = 1,7795,649,649,649
BEGIN DESCRIPTION:
KINTCHLOE BRANCH 10.0
END DESCRIPTION:
XS GIS Cut Line= 3
      2855774.99      7047575.01      2855425.00      7048125.00
      2854724.97      7048775.03
#Sta/Elev= 30
  4322.2  443.16  4460.2  433.15  4629.4  425.49  4951.9  421.44  4977.5  421.00
  4988.0  414.65  4991.4  409.85  4992.0  409.05  4999.4  409.85  5016.4  415.58
  5023.7  420.94  5037.9  422.82  5052.0  422.28  5058.9  416.93  5066.2  422.66
  5073.0  415.93  5080.4  417.41  5087.2  412.33  5094.6  417.27  5101.4  414.35
  5108.7  418.39  5115.6  415.61  5129.7  415.46  5137.1  419.86  5151.2  422.86
  5158.1  421.02  5307.8  421.44  5360.7  424.37  5561.2  436.30  5929.4  450.55
#Mann=5,-1,0
  4322.2    0.16       0  4629.4    0.12       0  4991.4    0.07       0
  4999.4    0.12       0  5360.7    0.16       0
Bank Sta=4951.9,5307.8
Exp/Cntr=0.3,0.1

Type RM Length L Ch R = 1,7146,757,757,757
BEGIN DESCRIPTION:
KINTCHLOE BRANCH 9.0
END DESCRIPTION:
XS GIS Cut Line= 3
      2855675.01      7047124.99      2855075.00      7047925.00
      2854325.01      7048325.00
#Sta/Elev= 30
  4093.9  442.32  4114.9  440.85  4246.0  436.20  4330.4  432.29  4357.5  427.87
  4365.8  431.14  4380.4  431.69  4801.7  420.34  4957.5  421.26  4972.0  418.02
  4980.4  412.81  4986.6  413.70  4989.9  409.03  4990.6  408.23  4998.0  409.03
  5015.8  416.30  5030.4  419.31  5036.6  415.11  5043.9  419.03  5057.5  417.73
  5065.8  419.96  5072.0  416.73  5086.6  417.66  5090.8  420.66  5116.6  420.44
  5124.0  413.89  5129.7  420.40  5297.0  420.34  5490.7  428.17  5943.9  452.57
#Mann=6,-1,0
  4093.9    0.12       0  4114.9    0.16       0  4246.0    0.12       0
  4989.9    0.07       0  4998.0    0.12       0  5490.7    0.16       0
Bank Sta=4801.7,5297
Exp/Cntr=0.3,0.1

Type RM Length L Ch R = 1,6389,549,549,549
BEGIN DESCRIPTION:
KINTCHLOE BRANCH 8.0
END DESCRIPTION:
XS GIS Cut Line= 3
      2855075.02      7046974.96      2854775.00      7047525.00
      2854224.97      7048075.03
#Sta/Elev= 30
  4354.3  444.30  4427.9  438.61  4487.7  431.59  4590.7  422.23  4660.2  419.15
  4803.8  416.96  4810.0  418.33  4819.9  418.50  4958.1  419.11  4967.1  416.03
  4972.8  418.27  4978.0  408.42  4990.8  407.14  4991.5  406.34  4999.1  407.14
  5009.1  413.20  5023.3  418.58  5037.4  412.34  5051.6  412.95  5065.7  418.51
  5074.5  419.15  5122.3  425.73  5159.5  426.92  5193.0  428.22  5284.9  428.12
  5303.0  428.45  5391.0  427.96  5532.4  434.26  5659.7  442.13  5758.7  449.77
#Mann=7,-1,0
  4354.3    0.16       0  4590.7    0.12       0  4990.8    0.07       0
  4999.1    0.12       0  5159.5    0.16       0  5284.9    0.12       0
  5303.0    0.16       0
Bank Sta=4660.2,5074.5
Exp/Cntr=0.3,0.1

Type RM Length L Ch R = 1,5840,657,657,657
BEGIN DESCRIPTION:
KINTCHLOE BRANCH 7.0
END DESCRIPTION:
XS GIS Cut Line= 3
      2854724.99      7046475.03      2854425.00      7047275.00
      2854075.00      7047975.01
#Sta/Elev= 30
  4150.6  459.56  4166.9  458.29  4264.4  449.34  4383.2  438.27  4513.7  425.72
  4633.3  418.17  4678.3  416.04  4983.6  417.73  4989.8  416.70  5002.3  408.69
  5007.8  408.69  5014.8  406.16  5015.5  405.36  5023.1  406.16  5027.3  407.06
  5035.7  411.72  5041.3  417.48  5049.7  418.03  5153.1  417.35  5242.9  418.17
  5299.1  419.47  5389.1  422.83  5407.2  423.86  5482.9  427.11  5594.7  435.24
  5667.4  438.99  5684.2  441.41  5734.5  443.14  5779.2  449.77  5787.6  449.74
#Mann=9,-1,0
  4150.6    0.16       0  4166.9    0.12       0  4264.4    0.16       0
  4383.2    0.12       0  5014.8    0.07       0  5023.1    0.12       0
  5299.1    0.16       0  5389.1    0.12       0  5407.2    0.16       0
Bank Sta=4633.3,5242.9
Exp/Cntr=0.3,0.1