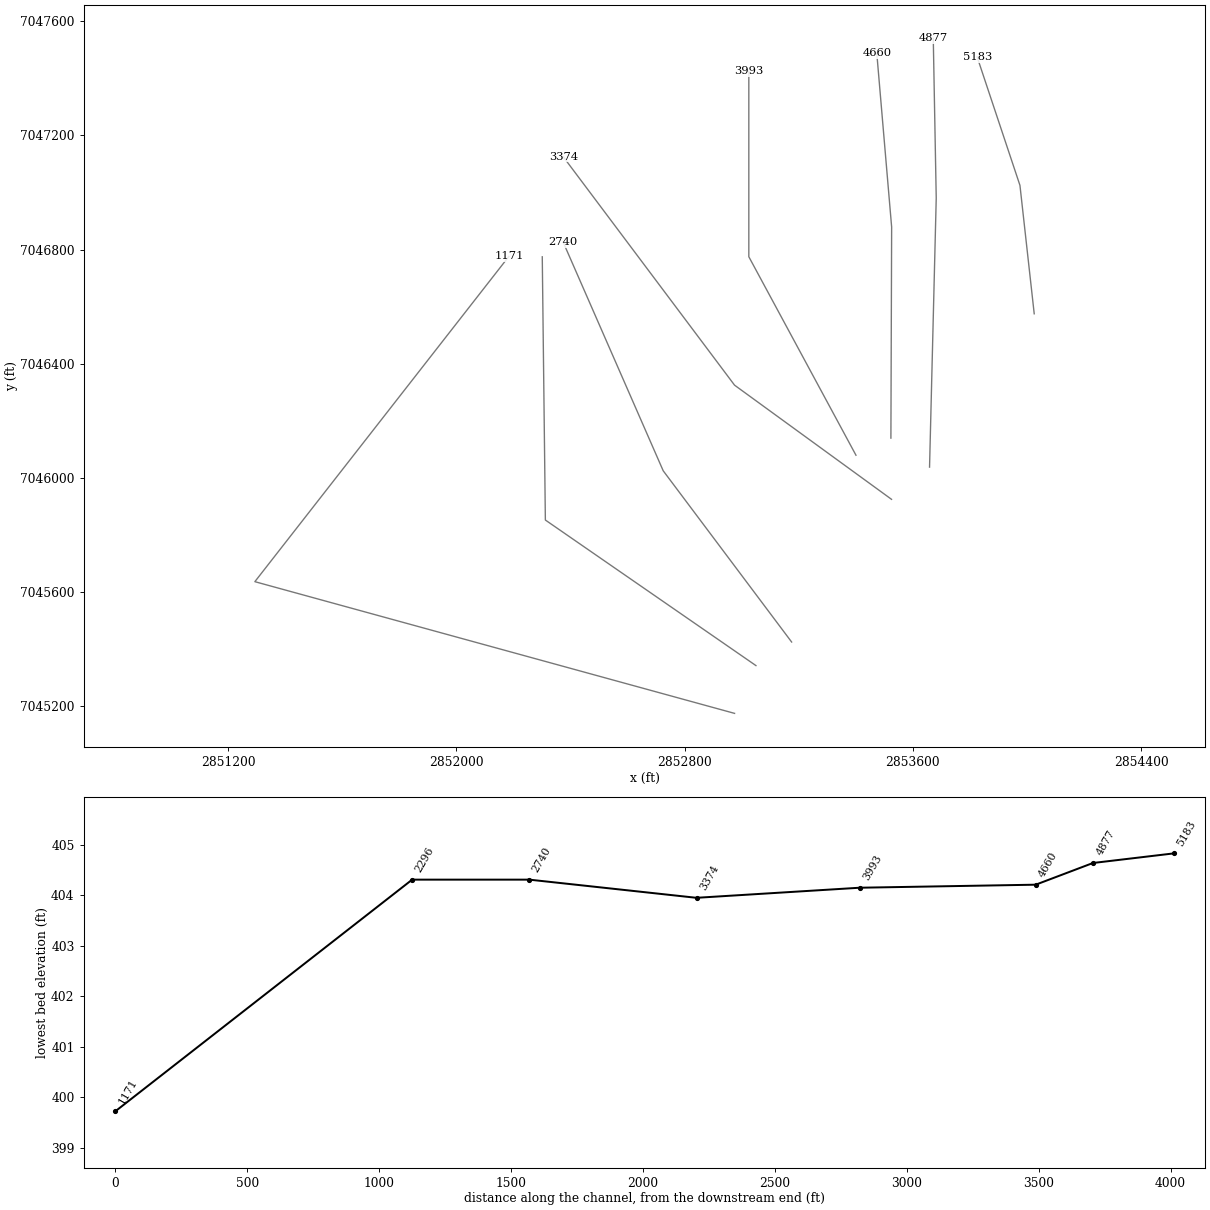
HEC-RAS study KINTCHLOE BRANCH.prj: KINTCHLOE BRANCH Base Level Engineering

--- KINTCHLOE BRANCH.g01 (geometry) --- (continued)

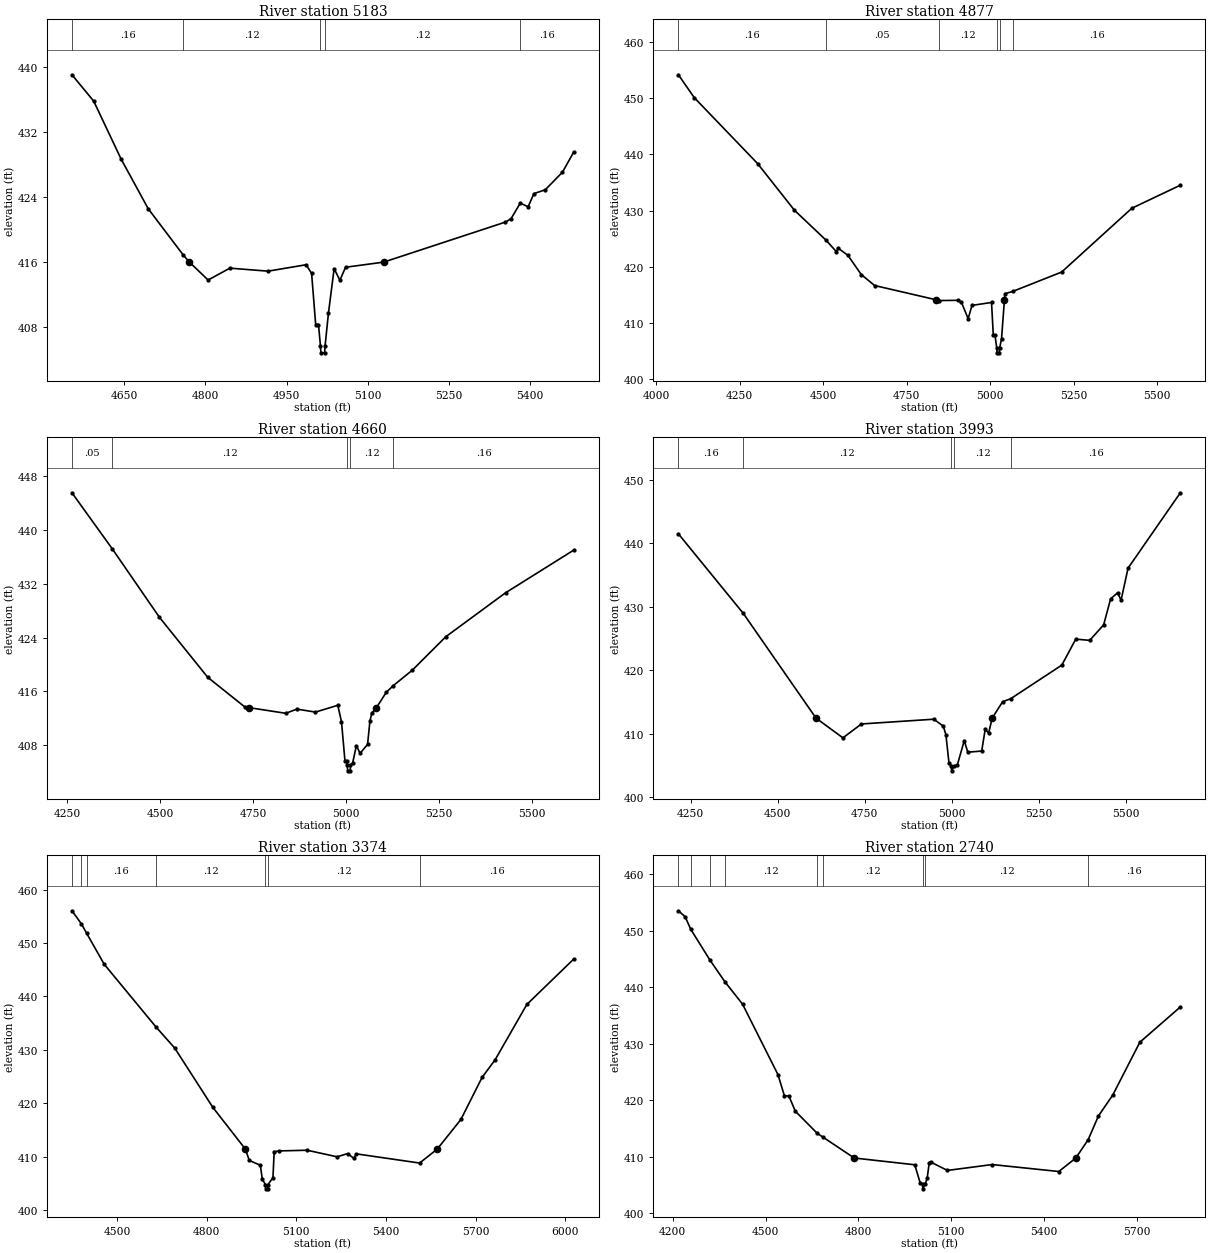
Type RM Length L Ch R = 1,5183,306,306,306
BEGIN DESCRIPTION:
KINTCHLOE BRANCH 6.0
END DESCRIPTION:
XS GIS Cut Line= 3
      2854024.99      7046575.05      2853975.00      7047025.00
      2853824.99      7047475.03
#Sta/Elev= 30
  4553.5  439.01  4593.7  435.77  4644.0  428.69  4694.3  422.55  4758.9  416.87
  4770.5  415.98  4805.0  413.78  4845.2  415.24  4915.7  414.87  4986.1  415.66
  4996.2  414.59  5003.7  408.31  5008.9  408.31  5012.6  405.63  5013.3  404.83
  5020.2  404.83  5021.0  405.63  5027.3  409.71  5037.8  415.18  5048.4  413.75
  5058.9  415.35  5129.2  415.98  5354.1  420.90  5364.6  421.32  5381.6  423.23
  5396.2  422.79  5406.8  424.40  5427.9  424.88  5459.5  427.03  5480.6  429.54
#Mann=5,-1,0
  4553.5    0.16       0  4758.9    0.12       0  5012.6    0.07       0
  5021.0    0.12       0  5381.6    0.16       0
Bank Sta=4770.5,5129.2
Exp/Cntr=0.3,0.1

Type RM Length L Ch R = 1,4877,217,217,217
BEGIN DESCRIPTION:
KINTCHLOE BRANCH 5.0
END DESCRIPTION:
XS GIS Cut Line= 3
      2853658.23      7046037.81      2853681.67      7046980.55
      2853671.26      7047540.22
#Sta/Elev= 30
  4066.8  454.20  4114.0  450.14  4304.1  438.36  4414.1  430.06  4508.6  424.73
  4539.7  422.67  4544.7  423.30  4574.2  422.03  4614.2  418.60  4654.2  416.64
  4837.4  414.11  4846.3  413.96  4904.3  414.00  4914.3  413.63  4934.3  410.74
  4945.9  413.10  5004.3  413.62  5009.6  407.82  5014.6  407.82  5020.1  405.44
  5020.8  404.64  5027.8  404.64  5028.5  405.44  5034.3  407.18  5043.0  414.11
  5044.3  415.17  5067.9  415.59  5214.3  419.04  5424.4  430.41  5569.6  434.52
#Mann=6,-1,0
  4066.8    0.16       0  4508.6    0.05       0  4846.3    0.12       0
  5020.1    0.07       0  5028.5    0.12       0  5067.9    0.16       0
Bank Sta=4837.4,5043
Exp/Cntr=0.3,0.1

Type RM Length L Ch R = 1,4660,667,667,667
BEGIN DESCRIPTION:
Mapping XS bd264dcd
END DESCRIPTION:
XS GIS Cut Line= 3
      2853522.82      7046139.45      2853525.42      7046878.99
      2853473.34      7047488.32
#Sta/Elev= 30
  4262.9  445.48  4371.7  437.14  4498.5  426.99  4628.5  418.09  4728.5  413.68
  4739.7  413.59  4838.5  412.75  4868.5  413.37  4918.5  412.93  4978.5  413.94
  4988.5  411.49  4997.9  405.63  5002.4  405.63  5004.2  405.01  5005.0  404.21
  5012.0  404.21  5012.7  405.01  5018.5  405.37  5028.5  407.95  5038.6  406.81
  5058.7  408.13  5064.9  411.54  5069.9  412.76  5082.6  413.59  5108.8  415.85
  5127.9  416.86  5178.8  419.13  5269.4  424.12  5430.0  430.63  5614.0  436.98
#Mann=5,-1,0
  4262.9    0.05       0  4371.7    0.12       0  5004.2    0.07       0
  5012.7    0.12       0  5127.9    0.16       0
Bank Sta=4739.7,5082.6
Exp/Cntr=0.3,0.1

Type RM Length L Ch R = 1,3993,619,619,619
BEGIN DESCRIPTION:
KINTCHLOE BRANCH 4.0
END DESCRIPTION:
XS GIS Cut Line= 3
      2853400.42      7046079.52      2853025.00      7046775.00
      2853025.00      7047424.96
#Sta/Elev= 30
  4215.3  441.51  4401.4  428.98  4610.2  412.46  4687.4  409.35  4740.5  411.54
  4948.1  412.29  4975.6  411.19  4982.9  409.84  4991.9  405.32  4998.5  404.95
  4999.3  404.15  5007.0  404.95  5015.6  405.05  5035.6  408.93  5045.6  407.09
  5085.6  407.27  5095.6  410.68  5105.6  410.12  5115.7  412.46  5145.6  415.04
  5169.0  415.53  5315.6  420.82  5355.6  424.92  5395.6  424.72  5435.6  427.17
  5455.6  431.28  5475.6  432.21  5485.6  431.06  5505.6  436.11  5655.6  447.99
#Mann=5,-1,0
  4215.3    0.16       0  4401.4    0.12       0  4998.5    0.07       0
  5007.0    0.12       0  5169.0    0.16       0
Bank Sta=4610.2,5115.7
Exp/Cntr=0.3,0.1

Type RM Length L Ch R = 1,3374,634,634,634
BEGIN DESCRIPTION:
KINTCHLOE BRANCH 3.0
END DESCRIPTION:
XS GIS Cut Line= 3
      2853525.04      7045924.97      2852975.00      7046325.00
      2852375.01      7047124.98
#Sta/Elev= 30
  4349.1  456.02  4380.2  453.62  4398.2  451.82  4457.0  446.01  4629.4  434.33
  4693.4  430.29  4820.9  419.19  4929.7  411.39  4942.7  409.27  4979.8  408.36
  4986.3  405.74  4996.8  404.75  4997.5  403.95  5004.5  403.95  5005.3  404.75
  5021.9  406.03  5026.1  410.90  5042.8  411.05  5136.5  411.18  5236.5  409.95
  5271.9  410.55  5292.8  409.66  5301.1  410.50  5512.9  408.78  5571.8  411.39
  5651.1  416.94  5721.9  424.81  5765.7  428.12  5871.9  438.48  6029.2  447.00
#Mann=7,-1,0
  4349.1    0.05       0  4380.2     0.1       0  4398.2    0.16       0
  4629.4    0.12       0  4996.8    0.07       0  5005.3    0.12       0
  5512.9    0.16       0
Bank Sta=4929.7,5571.8
Exp/Cntr=0.3,0.1

Type RM Length L Ch R = 1,2740,444,444,444
BEGIN DESCRIPTION:
KINTCHLOE BRANCH 2.0
END DESCRIPTION:
XS GIS Cut Line= 3
      2853174.98      7045425.03      2852725.00      7046025.00
      2852374.99      7046825.02
#Sta/Elev= 30
  4218.2  453.56  4240.0  452.50  4258.0  450.29  4320.0  444.84  4369.3  440.93
  4425.5  437.03  4540.0  424.56  4560.9  420.81  4575.5  420.75  4596.3  418.06
  4667.2  414.14  4685.1  413.49  4786.8  409.77  4982.6  408.57  5000.5  405.27
  5007.6  405.11  5008.3  404.31  5016.1  405.11  5022.7  406.16  5029.4  408.95
  5034.8  409.03  5088.2  407.57  5232.9  408.61  5448.4  407.38  5503.5  409.77
  5543.6  413.04  5576.7  417.23  5623.1  420.94  5710.4  430.27  5841.4  436.52
#Mann=9,-1,0
  4218.2     0.1       0  4258.0    0.12       0  4320.0    0.16       0
  4369.3    0.12       0  4667.2    0.16       0  4685.1    0.12       0
  5007.6    0.07       0  5016.1    0.12       0  5543.6    0.16       0
Bank Sta=4786.8,5503.5
Exp/Cntr=0.3,0.1

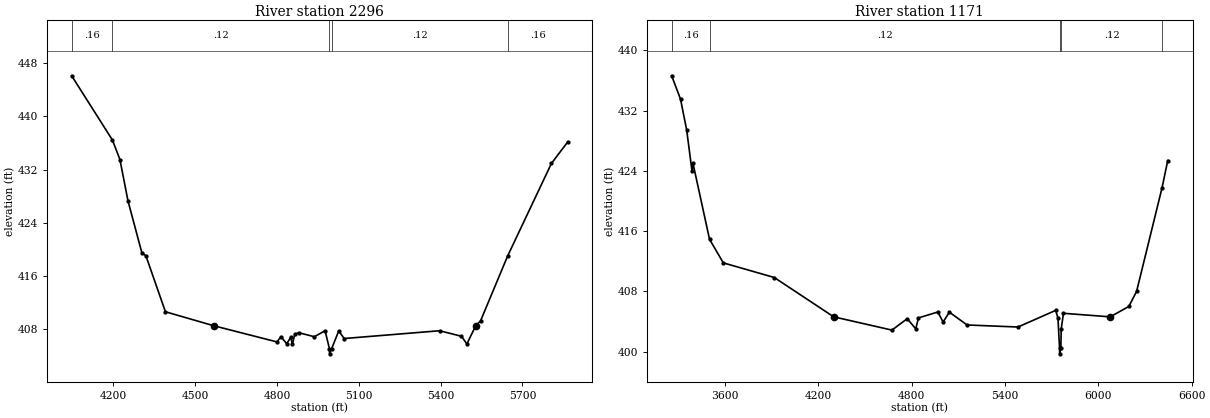
Type RM Length L Ch R = 1,2296,1125,1125,1125
BEGIN DESCRIPTION:
Mapping XS c6a3f040
END DESCRIPTION:
XS GIS Cut Line= 3
      2853049.97      7045342.43      2852312.13      7045852.41
      2852301.28      7046774.72
#Sta/Elev= 30
  4046.7  446.08  4196.2  436.43  4223.7  433.50  4253.4  427.27  4304.1  419.51
  4319.0  419.04  4390.6  410.63  4567.0  408.54  4799.5  406.10  4814.4  406.89
  4835.3  405.83  4850.2  406.79  4856.3  405.74  4865.1  407.24  4879.4  407.49
  4936.7  406.88  4976.2  407.78  4991.9  405.11  4992.7  404.31  5000.5  405.11
  5026.2  407.75  5046.2  406.61  5396.2  407.78  5476.3  406.95  5496.3  405.79
  5528.7  408.54  5546.3  409.25  5645.5  418.99  5806.3  432.91  5866.0  436.14
#Mann=5,-1,0
  4046.7    0.16       0  4196.2    0.12       0  4991.9    0.07       0
  5000.5    0.12       0  5645.5    0.16       0
Bank Sta=4567,5528.7
Exp/Cntr=0.3,0.1

Type RM Length L Ch R = 1,1171,0,0,0
BEGIN DESCRIPTION:
KINTCHLOE BRANCH 1.0
END DESCRIPTION:
XS GIS Cut Line= 3
      2852975.05      7045174.99      2851294.25      7045636.47
      2852184.27      7046776.11
#Sta/Elev= 30
  3257.0  436.62  3313.9  433.52  3353.5  429.42  3388.0  423.93  3393.1  425.09
  3500.3  414.93  3588.9  411.79  3916.8  409.85  4298.7  404.63  4673.0  402.87
  4771.1  404.38  4826.3  403.04  4843.7  404.49  4968.1  405.27  5002.2  403.94
  5042.2  405.25  5156.2  403.55  5483.6  403.28  5726.0  405.49  5740.4  404.46
  5750.6  400.52  5751.3  399.72  5759.2  400.52  5761.2  402.99  5775.7  405.10
  6075.8  404.63  6196.3  406.01  6246.0  408.01  6410.0  421.79  6446.0  425.36
#Mann=5,-1,0
  3257.0    0.16       0  3500.3    0.12       0  5750.6    0.07       0
  5759.2    0.12       0  6410.0    0.16       0
Bank Sta=4298.7,6075.8
Exp/Cntr=0.3,0.1

Chan Stop Cuts=-1