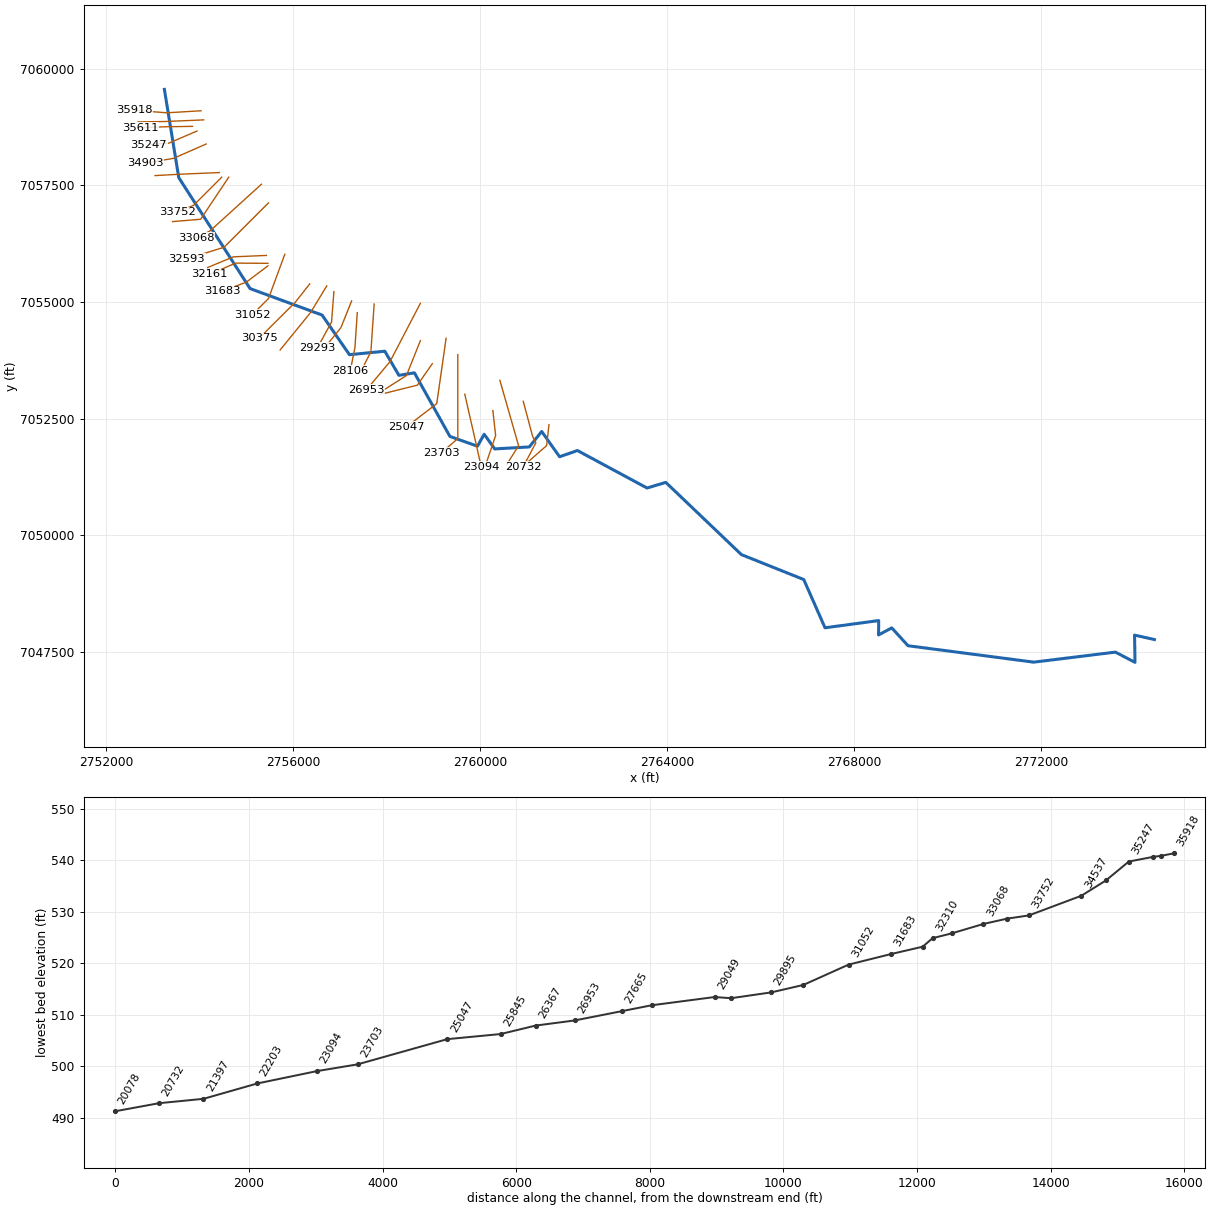
--- LAKE FORK CREEK TRIB 1.prj (project) ---

Proj Title=LAKE FORK CREEK TRIB 1 Base Level Engineering
Current Plan=p01
Default Exp/Contr=0.3,0.1
English Units
Geom File=g01
Flow File=f01
Plan File=p01
BEGIN DESCRIPTION:
LAKE FORK CREEK TRIB 1
END DESCRIPTION:

--- LAKE FORK CREEK TRIB 1.p01 (plan) ---

Plan Title=Multiple Run
Short Identifier=Multiple
Geom File=g01
Flow File=f01
Subcritical Flow
K Sum by GR= 0
Std Step Tol= 0.01
Critical Tol= 0.01
Num of Std Step Trials= 20
Max Error Tol= 0.3
Flow Tol Ratio= 0.001
Split Flow NTrial= 30
Split Flow Tol= 0.02
Split Flow Ratio= 0.02
Log Output Level= 0
Friction Slope Method= 1
Unsteady Friction Slope Method= 2
Unsteady Bridges Friction Slope Method= 1
Parabolic Critical Depth
Global Vel Dist=  1 , 1 , 1
Global Log Level= 0
CheckData=True
Encroach Param= -1, 0, 0, 0
BEGIN DESCRIPTION:
Multiple Run
END DESCRIPTION:

--- LAKE FORK CREEK TRIB 1.f01 (steady flow) ---

Flow Title=Multiple
Number of Profiles=7
Profile Names=10-year,25-year,50-year,1pct_min,100-year,1pct_plu,500-year
River Rch & RM= LAKE FORK CREEK ,Reach-1,35918
     435     562     660     385     767    1531    1035
River Rch & RM= LAKE FORK CREEK ,Reach-1,34537
     715     955    1148     684    1364    2721    1924
River Rch & RM= LAKE FORK CREEK ,Reach-1,30375
     844    1136    1372     821    1638    3269    2335
River Rch & RM= LAKE FORK CREEK ,Reach-1,25845
     981    1333    1620     975    1946    3883    2810
River Rch & RM= LAKE FORK CREEK ,Reach-1,18611
    1118    1528    1866    1128    2250    4490    3277
River Rch & RM= LAKE FORK CREEK ,Reach-1,15071
    1217    1667    2037    1232    2458    4905    3587
River Rch & RM= LAKE FORK CREEK ,Reach-1,6281
    1599    2220    2740    1672    3337    6657    4960
Boundary for River Rch & Prof#=LAKE FORK CREEK ,Reach-1,1
Up Type=0
Dn Type=3
Dn Slope=0.005
Boundary for River Rch & Prof#=LAKE FORK CREEK ,Reach-1,2
Up Type=0
Dn Type=3
Dn Slope=0.005
Boundary for River Rch & Prof#=LAKE FORK CREEK ,Reach-1,3
Up Type=0
Dn Type=3
Dn Slope=0.005
Boundary for River Rch & Prof#=LAKE FORK CREEK ,Reach-1,4
Up Type=0
Dn Type=3
Dn Slope=0.005
Boundary for River Rch & Prof#=LAKE FORK CREEK ,Reach-1,5
Up Type=0
Dn Type=3
Dn Slope=0.005
Boundary for River Rch & Prof#=LAKE FORK CREEK ,Reach-1,6
Up Type=0
Dn Type=3
Dn Slope=0.005
Boundary for River Rch & Prof#=LAKE FORK CREEK ,Reach-1,7
Up Type=0
Dn Type=3
Dn Slope=0.005

--- LAKE FORK CREEK TRIB 1.g01 (geometry) ---

Geom Title=Existing Conditions

River Reach=LAKE FORK CREEK ,Reach-1
Reach XY= 30
      2753249.03      7059557.42      2753556.79      7057666.12
      2755081.89      7055289.55      2756621.96      7054722.85
      2757207.55      7053873.69      2757964.15      7053947.58
      2758265.63      7053430.97      2758596.70      7053484.94
      2759356.13      7052122.66      2759945.44      7051912.98
      2760089.26      7052168.92      2760315.06      7051854.48
      2761054.35      7051897.37      2761319.54      7052228.15
      2761701.98      7051687.07      2762084.57      7051820.01
      2763572.66      7051017.41      2763974.03      7051137.56
      2765592.05      7049589.99      2766924.98      7049056.39
      2767379.95      7048022.64      2768528.69      7048177.22
      2768524.82      7047869.03      2768806.93      7048020.71
      2769155.71      7047638.12      2771845.49      7047286.43
      2773590.46      7047501.38      2774010.20      7047282.55
      2774000.57      7047865.84      2774425.59      7047770.71

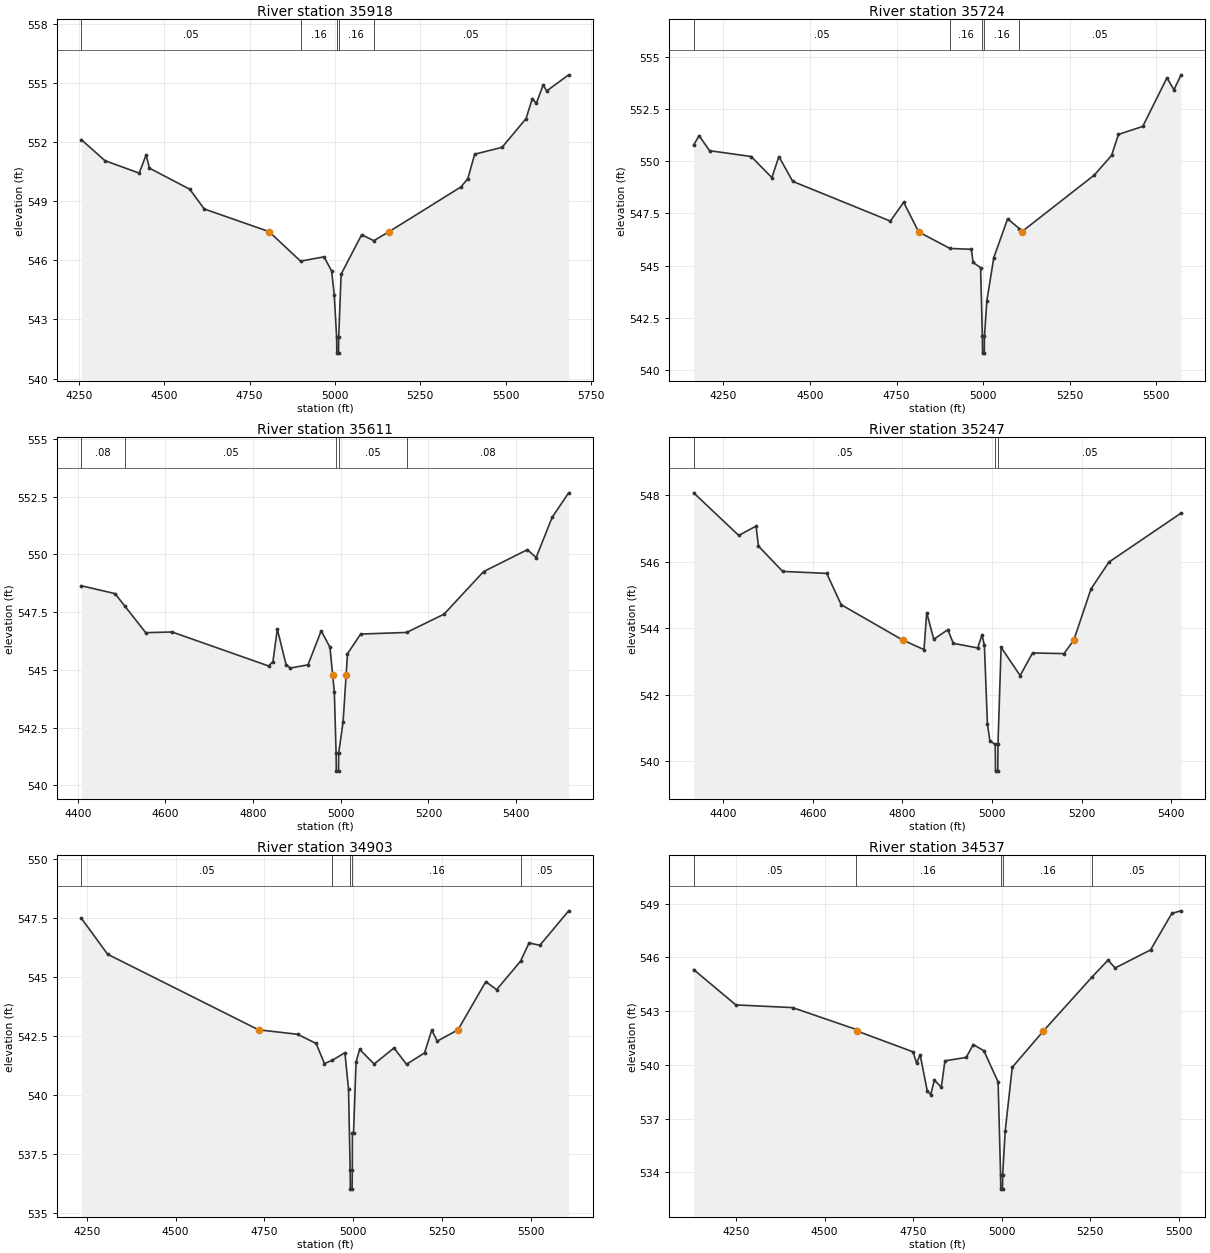
Type RM Length L Ch R = 1,35918,194,194,194
BEGIN DESCRIPTION:
LAKE FORK CREEK TRIB 1 55.0
END DESCRIPTION:
XS GIS Cut Line= 3
      2754034.30      7059099.05      2753305.13      7059055.65
      2752610.64      7059107.73
#Sta/Elev= 30
  4257.4  552.13  4326.8  551.06  4427.0  550.43  4447.0  551.35  4457.1  550.68
  4575.1  549.61  4617.3  548.61  4807.0  547.46  4899.4  545.96  4968.0  546.18
  4990.4  545.46  4998.0  544.24  5005.0  542.09  5005.5  541.29  5010.5  541.29
  5011.0  542.09  5018.1  545.30  5078.2  547.30  5113.8  547.00  5158.9  547.46
  5369.1  549.73  5389.1  550.15  5409.2  551.39  5489.4  551.74  5559.6  553.20
  5577.8  554.21  5589.7  553.97  5609.7  554.91  5619.8  554.60  5684.3  555.42
#Mann=5,-1,0
  4257.4    0.05       0  4899.4    0.16       0  5005.0    0.07       0
  5011.0    0.16       0  5113.8    0.05       0
Bank Sta=4807,5158.9
Exp/Cntr=0.3,0.1

Type RM Length L Ch R = 1,35724,113,113,113
BEGIN DESCRIPTION:
Mapping XS 6d70fc25
END DESCRIPTION:
XS GIS Cut Line= 3
      2754090.74      7058903.74      2753266.07      7058869.01
      2752684.44      7058860.33
#Sta/Elev= 30
  4164.1  550.77  4179.9  551.22  4209.9  550.50  4330.0  550.22  4390.0  549.21
  4410.1  550.22  4450.1  549.03  4731.9  547.13  4770.4  548.03  4813.7  546.61
  4904.2  545.82  4965.8  545.78  4970.8  545.15  4992.5  544.90  4997.6  541.61
  4998.1  540.81  5003.1  540.81  5003.6  541.61  5010.6  543.32  5030.6  545.38
  5070.6  547.24  5104.1  546.77  5110.6  546.61  5320.6  549.33  5370.6  550.27
  5390.6  551.28  5460.6  551.66  5530.6  553.99  5550.6  553.41  5571.2  554.13
#Mann=5,-1,0
  4164.1    0.05       0  4904.2    0.16       0  4997.6    0.07       0
  5003.6    0.16       0  5104.1    0.05       0
Bank Sta=4813.7,5110.6
Exp/Cntr=0.3,0.1

Type RM Length L Ch R = 1,35611,364,364,364
BEGIN DESCRIPTION:
Mapping XS 1c6d80ab
END DESCRIPTION:
XS GIS Cut Line= 3
      2753852.02      7058764.85      2753266.07      7058756.17
      2752740.87      7058738.81
#Sta/Elev= 30
  4408.2  548.64  4485.2  548.30  4507.5  547.76  4555.2  546.61  4615.2  546.64
  4835.3  545.17  4845.3  545.36  4855.3  546.76  4875.3  545.22  4885.3  545.08
  4925.3  545.22  4955.3  546.69  4975.3  545.98  4981.6  544.76  4985.3  544.04
  4989.3  541.42  4989.8  540.62  4994.8  540.62  4995.3  541.42  5005.3  542.75
  5012.1  544.76  5015.3  545.70  5045.3  546.55  5150.2  546.62  5235.4  547.41
  5325.5  549.25  5425.5  550.20  5445.5  549.86  5482.0  551.60  5519.7  552.66
#Mann=5,-1,0
  4408.2    0.08       0  4507.5    0.05       0  4989.3    0.03       0
  4995.3    0.05       0  5150.2    0.08       0
Bank Sta=4981.6,5012.1
Exp/Cntr=0.3,0.1

Type RM Length L Ch R = 1,35247,344,344,344
BEGIN DESCRIPTION:
Mapping XS 81a01128
END DESCRIPTION:
XS GIS Cut Line= 3
      2753947.46      7058665.01      2753339.85      7058404.60
      2752914.50      7058374.22
#Sta/Elev= 30
  4334.2  548.07  4434.8  546.79  4473.4  547.07  4478.8  546.47  4532.7  545.71
  4631.1  545.65  4663.3  544.71  4800.4  543.65  4848.2  543.36  4854.2  544.47
  4870.0  543.67  4901.3  543.96  4913.5  543.55  4967.9  543.41  4977.5  543.80
  4982.9  543.49  4989.7  541.12  4995.2  540.62  5007.2  540.51  5007.7  539.71
  5012.7  539.71  5013.2  540.51  5020.2  543.43  5062.6  542.58  5090.4  543.26
  5160.5  543.24  5182.5  543.65  5220.7  545.18  5260.8  545.99  5421.7  547.46
#Mann=3,-1,0
  4334.2    0.05       0  5007.2    0.03       0  5013.2    0.05       0
Bank Sta=4800.4,5182.5
Exp/Cntr=0.3,0.1

Type RM Length L Ch R = 1,34903,366,366,366
BEGIN DESCRIPTION:
Mapping XS 40ed148e
END DESCRIPTION:
XS GIS Cut Line= 3
      2754142.80      7058387.24      2753444.02      7058079.08
      2752845.10      7057979.26
#Sta/Elev= 30
  4234.9  547.51  4309.0  545.98  4733.4  542.78  4843.4  542.59  4895.5  542.20
  4918.8  541.35  4941.1  541.49  4976.4  541.81  4986.6  540.27  4991.2  536.83
  4991.7  536.03  4996.7  536.03  4997.2  536.83  4997.5  538.42  5000.7  538.42
  5007.8  541.42  5017.9  541.95  5058.7  541.33  5114.5  542.01  5149.7  541.32
  5200.4  541.80  5220.7  542.77  5236.1  542.30  5294.5  542.78  5372.7  544.82
  5403.1  544.48  5470.6  545.69  5494.4  546.46  5524.8  546.36  5605.8  547.82
#Mann=5,-1,0
  4234.9    0.05       0  4941.1    0.16       0  4991.2    0.07       0
  4997.2    0.16       0  5470.6    0.05       0
Bank Sta=4733.4,5294.5
Exp/Cntr=0.3,0.1

Type RM Length L Ch R = 1,34537,785,785,785
BEGIN DESCRIPTION:
Mapping XS 2dc537fa
END DESCRIPTION:
XS GIS Cut Line= 3
      2754424.01      7057775.26      2753595.06      7057740.54
      2753049.08      7057710.21
#Sta/Elev= 30
  4130.2  545.32  4249.3  543.35  4409.5  543.20  4587.8  541.99  4592.1  541.89
  4749.8  540.73  4759.8  540.10  4769.8  540.57  4789.8  538.56  4799.8  538.34
  4809.8  539.15  4829.8  538.76  4839.8  540.23  4899.9  540.42  4919.9  541.14
  4949.9  540.79  4990.0  539.05  4997.0  533.87  4997.5  533.07  5002.5  533.07
  5003.0  533.87  5010.0  536.30  5030.0  539.87  5117.7  541.89  5255.9  544.92
  5300.5  545.85  5320.5  545.41  5420.6  546.42  5480.7  548.46  5506.7  548.60
#Mann=5,-1,0
  4130.2    0.05       0  4587.8    0.16       0  4997.0    0.07       0
  5003.0    0.16       0  5255.9    0.05       0
Bank Sta=4592.1,5117.7
Exp/Cntr=0.3,0.1

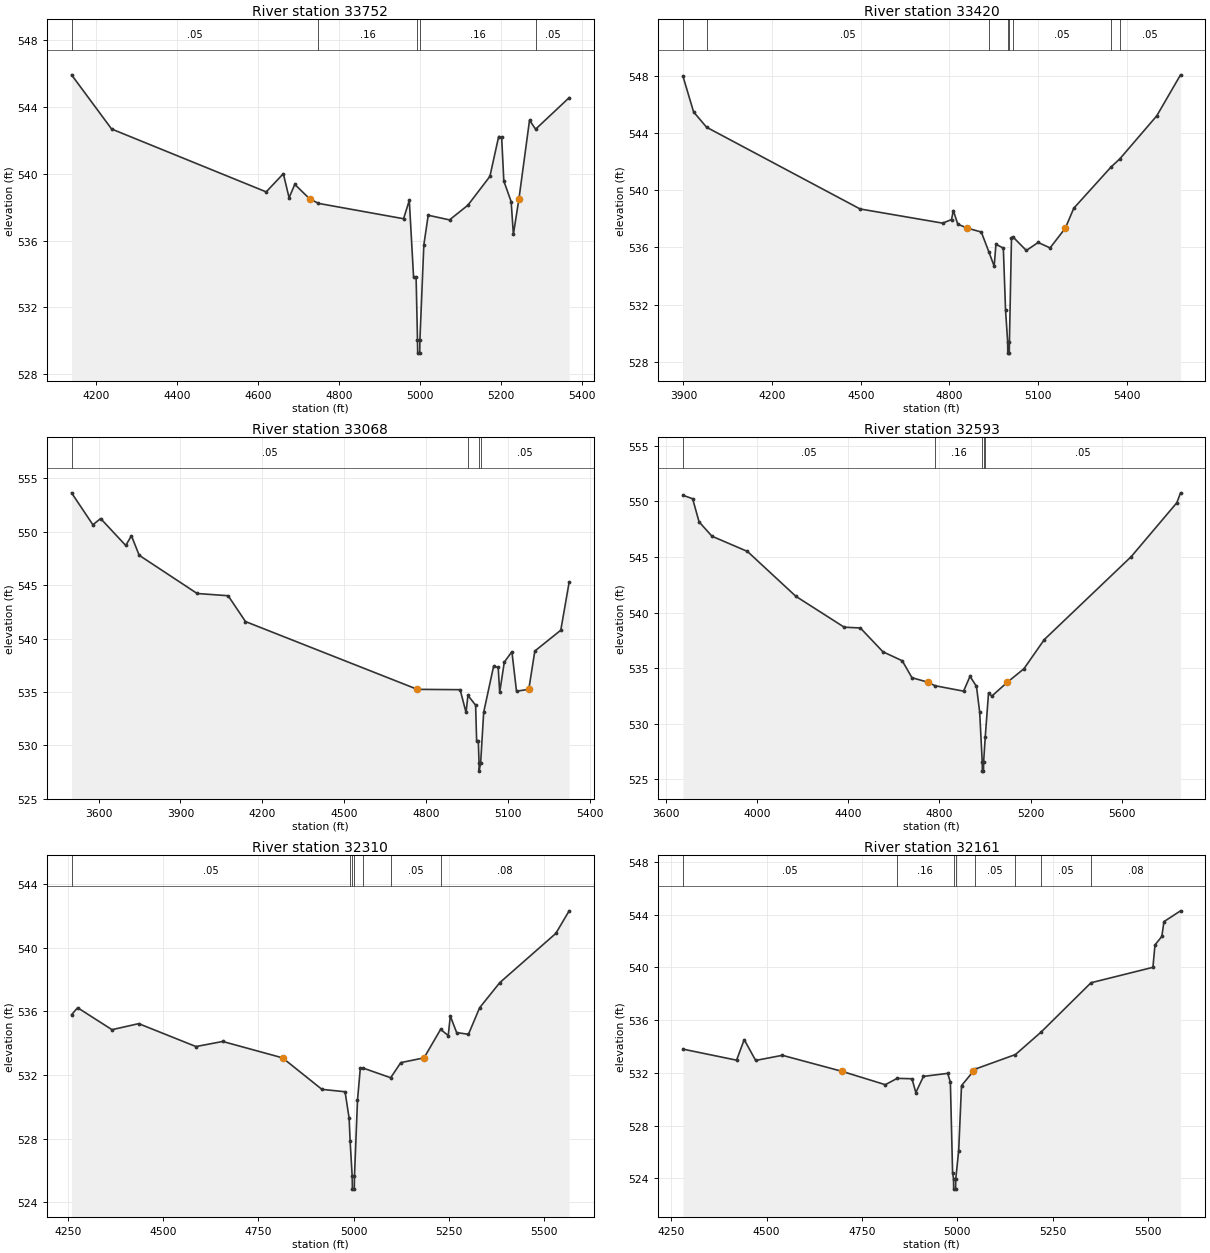
Type RM Length L Ch R = 1,33752,332,332,332
BEGIN DESCRIPTION:
LAKE FORK CREEK TRIB 1 50.0
END DESCRIPTION:
XS GIS Cut Line= 3
      2754474.98      7057674.98      2753875.00      7057075.00
      2753524.99      7056925.00
#Sta/Elev= 30
  4139.9  545.94  4238.9  542.69  4620.7  538.92  4663.1  540.01  4677.3  538.57
  4691.4  539.37  4727.8  538.51  4749.9  538.23  4960.1  537.31  4974.3  538.41
  4984.9  533.79  4991.1  533.79  4994.5  530.05  4995.0  529.25  5000.0  529.25
  5000.5  530.05  5010.2  535.74  5021.0  537.52  5073.6  537.24  5119.0  538.12
  5173.4  539.85  5195.1  542.24  5202.4  542.21  5207.8  539.57  5225.9  538.34
  5231.4  536.37  5245.2  538.51  5271.3  543.22  5286.3  542.68  5369.2  544.57
#Mann=5,-1,0
  4139.9    0.05       0  4749.9    0.16       0  4994.5    0.07       0
  5000.5    0.16       0  5286.3    0.05       0
Bank Sta=4727.8,5245.2
Exp/Cntr=0.3,0.1

Type RM Length L Ch R = 1,33420,352,352,352
BEGIN DESCRIPTION:
LAKE FORK CREEK TRIB 1 49.0
END DESCRIPTION:
XS GIS Cut Line= 3
      2754625.02      7057675.03      2754025.00      7056775.00
      2753424.98      7056725.00
#Sta/Elev= 30
  3898.3  547.96  3934.4  545.46  3978.3  544.39  4497.8  538.68  4777.2  537.69
  4807.2  537.94  4813.2  538.57  4828.3  537.62  4860.9  537.34  4907.9  537.07
  4934.0  535.66  4951.5  534.68  4957.5  536.21  4982.5  535.95  4990.0  531.61
  4997.1  529.41  4997.6  528.61  5002.6  528.61  5003.1  529.41  5010.1  536.68
  5015.0  536.73  5060.3  535.78  5100.4  536.34  5140.6  535.96  5192.3  537.34
  5220.8  538.73  5346.9  541.61  5377.1  542.19  5501.8  545.19  5582.1  548.05
#Mann=8,-1,0
  3898.3    0.08       0  3978.3    0.05       0  4934.0    0.16       0
  4997.1    0.07       0  5003.1    0.16       0  5015.0    0.05       0
  5346.9    0.16       0  5377.1    0.05       0
Bank Sta=4860.9,5192.3
Exp/Cntr=0.3,0.1

Type RM Length L Ch R = 1,33068,475,475,475
BEGIN DESCRIPTION:
LAKE FORK CREEK TRIB 1 48.0
END DESCRIPTION:
XS GIS Cut Line= 3
      2755325.02      7057525.02      2754225.00      7056525.00
      2753925.04      7056375.02
#Sta/Elev= 30
  3501.3  553.65  3579.4  550.66  3607.8  551.24  3699.7  548.72  3720.6  549.63
  3749.0  547.80  3961.2  544.22  4074.7  544.01  4138.2  541.59  4767.5  535.24
  4924.1  535.21  4945.7  533.08  4952.7  534.67  4980.8  533.76  4984.6  530.37
  4990.7  530.37  4993.3  528.38  4993.8  527.58  4999.3  528.38  5010.3  533.09
  5046.6  537.40  5063.4  537.29  5069.0  534.96  5085.8  537.79  5113.7  538.77
  5130.5  535.07  5175.5  535.24  5197.6  538.83  5292.6  540.78  5323.3  545.28
#Mann=4,-1,0
  3501.3    0.05       0  4952.7    0.16       0  4993.3    0.03       0
  4999.3    0.05       0
Bank Sta=4767.5,5175.5
Exp/Cntr=0.3,0.1

Type RM Length L Ch R = 1,32593,283,283,283
BEGIN DESCRIPTION:
LAKE FORK CREEK TRIB 1 47.0
END DESCRIPTION:
XS GIS Cut Line= 3
      2755475.03      7057125.03      2754525.00      7056175.00
      2753725.00      7055925.00
#Sta/Elev= 30
  3676.1  550.55  3718.6  550.24  3746.9  548.16  3803.4  546.87  3959.0  545.50
  4171.1  541.47  4383.2  538.69  4454.0  538.62  4553.0  536.48  4637.8  535.67
  4680.2  534.15  4750.7  533.74  4781.0  533.43  4906.5  532.94  4934.8  534.27
  4963.1  533.37  4977.2  531.05  4988.4  526.55  4988.9  525.75  4993.9  525.75
  4994.4  526.55  5001.5  528.80  5016.1  532.80  5030.1  532.49  5098.3  533.74
  5171.0  534.95  5260.6  537.58  5641.4  545.03  5841.6  549.88  5857.8  550.77
#Mann=5,-1,0
  3676.1    0.05       0  4781.0    0.16       0  4988.4    0.07       0
  4994.4    0.16       0  5001.5    0.05       0
Bank Sta=4750.7,5098.3
Exp/Cntr=0.3,0.1

Type RM Length L Ch R = 1,32310,149,149,149
BEGIN DESCRIPTION:
Mapping XS acf36fdd
END DESCRIPTION:
XS GIS Cut Line= 3
      2755430.98      7056000.09      2754723.53      7055969.71
      2754172.68      7055739.82
#Sta/Elev= 30
  4260.2  535.79  4276.2  536.23  4366.3  534.85  4436.3  535.23  4586.5  533.79
  4656.5  534.11  4813.5  533.08  4916.8  531.10  4977.5  530.95  4988.2  529.28
  4990.8  527.85  4996.2  525.63  4996.7  524.83  5001.7  524.83  5002.2  525.63
  5010.1  530.41  5017.5  532.44  5025.8  532.43  5097.1  531.83  5123.6  532.78
  5184.6  533.08  5228.1  534.87  5248.1  534.48  5253.5  535.71  5270.1  534.67
  5301.1  534.56  5330.4  536.23  5383.4  537.81  5530.2  540.90  5565.2  542.32
#Mann=7,-1,0
  4260.2    0.05       0  4990.8    0.16       0  4996.2    0.07       0
  5002.2    0.16       0  5025.8    0.08       0  5097.1    0.05       0
  5228.1    0.08       0
Bank Sta=4813.5,5184.6
Exp/Cntr=0.3,0.1

Type RM Length L Ch R = 1,32161,478,478,478
BEGIN DESCRIPTION:
Mapping XS 0b3da8be
END DESCRIPTION:
XS GIS Cut Line= 3
      2755465.70      7055830.82      2754771.27      7055835.16
      2754211.39      7055592.11
#Sta/Elev= 30
  4280.7  533.80  4421.4  532.96  4441.4  534.52  4471.4  532.94  4541.4  533.33
  4697.0  532.12  4811.4  531.10  4842.5  531.58  4881.4  531.55  4891.4  530.50
  4911.4  531.73  4975.1  531.96  4982.0  531.28  4987.8  524.42  4990.2  523.97
  4990.7  523.17  4995.7  523.17  4996.2  523.97  5003.8  526.10  5011.2  531.03
  5042.2  532.12  5045.8  532.27  5152.7  533.39  5219.7  535.09  5350.8  538.84
  5513.1  540.01  5518.5  541.71  5536.5  542.36  5542.0  543.48  5585.5  544.30
#Mann=8,-1,0
  4280.7    0.05       0  4842.5    0.16       0  4990.2    0.07       0
  4996.2    0.16       0  5045.8    0.05       0  5152.7    0.08       0
  5219.7    0.05       0  5350.8    0.08       0
Bank Sta=4697,5042.2
Exp/Cntr=0.3,0.1

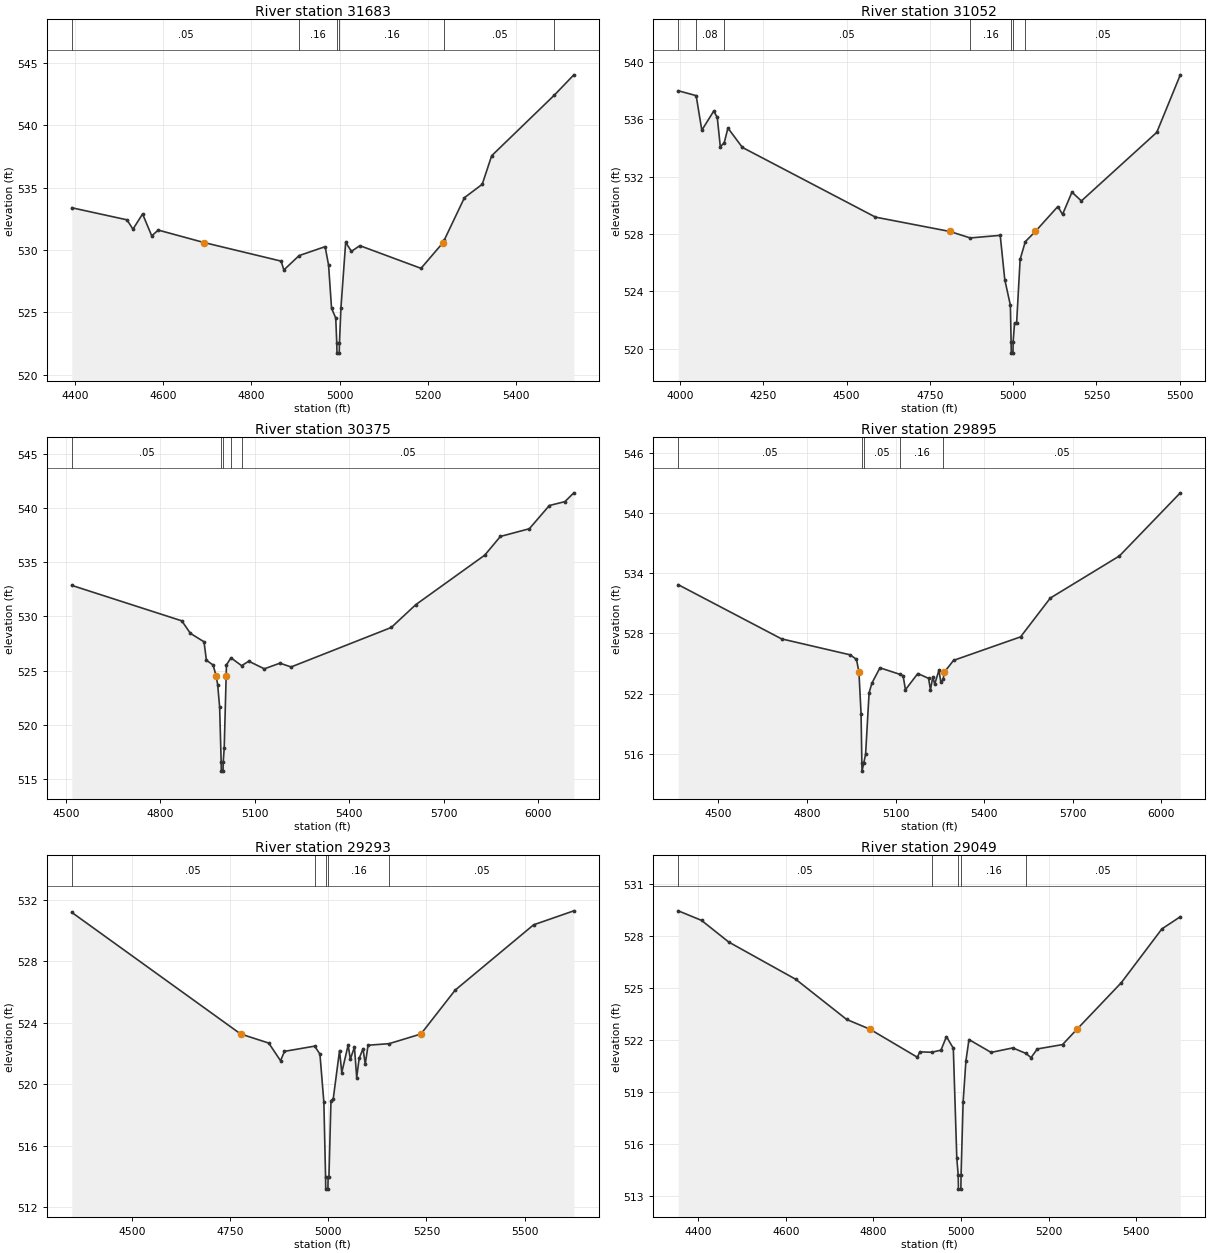
Type RM Length L Ch R = 1,31683,631,631,631
BEGIN DESCRIPTION:
Mapping XS f5b1144f
END DESCRIPTION:
XS GIS Cut Line= 3
      2755465.69      7055778.71      2755001.31      7055427.17
      2754480.46      7055231.86
#Sta/Elev= 30
  4392.6  533.39  4517.8  532.42  4531.4  531.67  4553.2  532.89  4574.0  531.13
  4588.6  531.60  4692.4  530.60  4867.4  529.11  4873.6  528.40  4908.1  529.55
  4967.2  530.27  4975.0  528.80  4981.8  525.32  4991.3  524.55  4993.6  522.53
  4994.1  521.73  4999.2  521.73  4999.7  522.53  5003.1  525.37  5013.8  530.61
  5026.9  529.89  5045.9  530.35  5184.7  528.53  5234.8  530.60  5237.7  530.82
  5283.2  534.20  5323.5  535.27  5344.9  537.56  5487.3  542.43  5531.3  544.05
#Mann=6,-1,0
  4392.6    0.05       0  4908.1    0.16       0  4993.6    0.07       0
  4999.7    0.16       0  5237.7    0.05       0  5487.3    0.08       0
Bank Sta=4692.4,5234.8
Exp/Cntr=0.3,0.1

Type RM Length L Ch R = 1,31052,677,677,677
BEGIN DESCRIPTION:
LAKE FORK CREEK TRIB 1 44.0
END DESCRIPTION:
XS GIS Cut Line= 3
      2755824.99      7056024.97      2755475.00      7055075.00
      2755124.97      7054724.97
#Sta/Elev= 30
  3994.4  537.98  4048.2  537.64  4065.2  535.23  4100.9  536.56  4111.6  536.12
  4120.7  534.08  4132.4  534.35  4143.6  535.38  4187.0  534.03  4586.6  529.17
  4810.0  528.17  4871.1  527.72  4961.1  527.90  4974.8  524.81  4991.6  523.03
  4993.8  520.49  4994.3  519.69  4999.4  519.69  4999.9  520.49  5004.1  521.77
  5010.3  521.77  5020.9  526.23  5036.4  527.46  5066.5  528.17  5134.1  529.91
  5148.2  529.36  5176.5  530.91  5204.8  530.30  5431.1  535.08  5501.8  539.09
#Mann=7,-1,0
  3994.4    0.05       0  4048.2    0.08       0  4132.4    0.05       0
  4871.1    0.16       0  4993.8    0.07       0  4999.9    0.16       0
  5036.4    0.05       0
Bank Sta=4810,5066.5
Exp/Cntr=0.3,0.1

Type RM Length L Ch R = 1,30375,480,480,480
BEGIN DESCRIPTION:
LAKE FORK CREEK TRIB 1 43.0
END DESCRIPTION:
XS GIS Cut Line= 3
      2756359.40      7055390.65      2756045.58      7054993.15
      2755275.00      7054225.00
#Sta/Elev= 30
  4519.0  532.86  4868.5  529.59  4895.7  528.44  4939.0  527.66  4946.6  525.96
  4967.8  525.52  4977.7  524.49  4982.3  523.71  4988.6  521.65  4993.5  516.54
  4994.0  515.74  4999.4  515.74  4999.9  516.54  5003.1  517.83  5009.3  524.49
  5010.3  525.54  5024.7  526.18  5058.4  525.46  5081.1  525.87  5130.6  525.17
  5180.1  525.69  5215.5  525.34  5533.7  528.98  5611.4  531.08  5830.7  535.65
  5880.2  537.37  5972.1  538.08  6035.7  540.22  6085.2  540.58  6113.5  541.39
#Mann=5,-1,0
  4519.0    0.05       0  4993.5    0.03       0  4999.9    0.05       0
  5024.7    0.16       0  5058.4    0.05       0
Bank Sta=4977.7,5009.3
Exp/Cntr=0.3,0.1

Type RM Length L Ch R = 1,29895,602,602,602
BEGIN DESCRIPTION:
LAKE FORK CREEK TRIB 1 42.0
END DESCRIPTION:
XS GIS Cut Line= 3
      2756722.65      7055347.29      2756375.00      7054775.00
      2755724.99      7053974.99
#Sta/Elev= 30
  4364.1  532.85  4713.9  527.46  4946.5  525.87  4967.8  525.42  4976.1  524.15
  4983.3  520.01  4986.0  515.10  4986.5  514.30  4992.4  515.10  4998.6  515.98
  5010.5  522.10  5020.1  523.06  5047.3  524.58  5114.7  523.93  5125.6  523.80
  5133.6  522.40  5175.4  524.01  5211.9  523.53  5218.3  522.39  5226.2  523.67
  5232.7  522.96  5247.1  524.34  5253.5  523.16  5261.3  523.42  5265.2  524.15
  5296.6  525.32  5523.6  527.66  5624.2  531.52  5858.3  535.71  6064.5  541.99
#Mann=5,-1,0
  4364.1    0.05       0  4986.0    0.03       0  4992.4    0.05       0
  5114.7    0.16       0  5261.3    0.05       0
Bank Sta=4976.1,5265.2
Exp/Cntr=0.3,0.1

Type RM Length L Ch R = 1,29293,244,244,244
BEGIN DESCRIPTION:
LAKE FORK CREEK TRIB 1 41.0
END DESCRIPTION:
XS GIS Cut Line= 3
      2756875.00      7055225.00      2756825.00      7054575.00
      2756525.01      7054025.02
#Sta/Elev= 30
  4346.8  531.17  4776.8  523.26  4848.3  522.67  4878.4  521.52  4888.4  522.13
  4965.3  522.47  4978.7  521.95  4988.7  518.82  4993.0  513.97  4993.5  513.17
  4999.0  513.17  4999.5  513.97  5001.6  513.97  5006.8  518.92  5012.5  519.03
  5028.6  522.18  5034.3  520.75  5050.5  522.54  5056.1  521.63  5066.6  522.40
  5072.3  520.42  5078.5  521.67  5088.4  522.30  5094.1  521.30  5101.2  522.53
  5154.8  522.63  5235.9  523.26  5322.9  526.11  5522.7  530.36  5625.2  531.27
#Mann=5,-1,0
  4346.8    0.05       0  4965.3    0.16       0  4993.0    0.07       0
  4999.5    0.16       0  5154.8    0.05       0
Bank Sta=4776.8,5235.9
Exp/Cntr=0.3,0.1

Type RM Length L Ch R = 1,29049,943,943,943
BEGIN DESCRIPTION:
Mapping XS 82a7db91
END DESCRIPTION:
XS GIS Cut Line= 3
      2757253.92      7055024.42      2757024.75      7054451.48
      2756691.42      7054040.03
#Sta/Elev= 30
  4354.3  529.44  4407.5  528.89  4469.7  527.64  4622.9  525.49  4738.9  523.18
  4791.9  522.62  4900.5  521.00  4905.9  521.31  4933.5  521.29  4954.3  521.41
  4966.8  522.19  4982.5  521.52  4990.5  515.17  4993.7  514.20  4994.2  513.40
  4999.7  513.40  5000.2  514.20  5004.9  518.42  5011.3  520.80  5018.3  522.02
  5068.8  521.28  5118.4  521.54  5148.5  521.22  5160.0  520.98  5174.4  521.48
  5231.9  521.73  5265.1  522.62  5366.2  525.30  5458.9  528.40  5500.9  529.10
#Mann=5,-1,0
  4354.3    0.05       0  4933.5    0.16       0  4993.7    0.07       0
  5000.2    0.16       0  5148.5    0.05       0
Bank Sta=4791.9,5265.1
Exp/Cntr=0.3,0.1

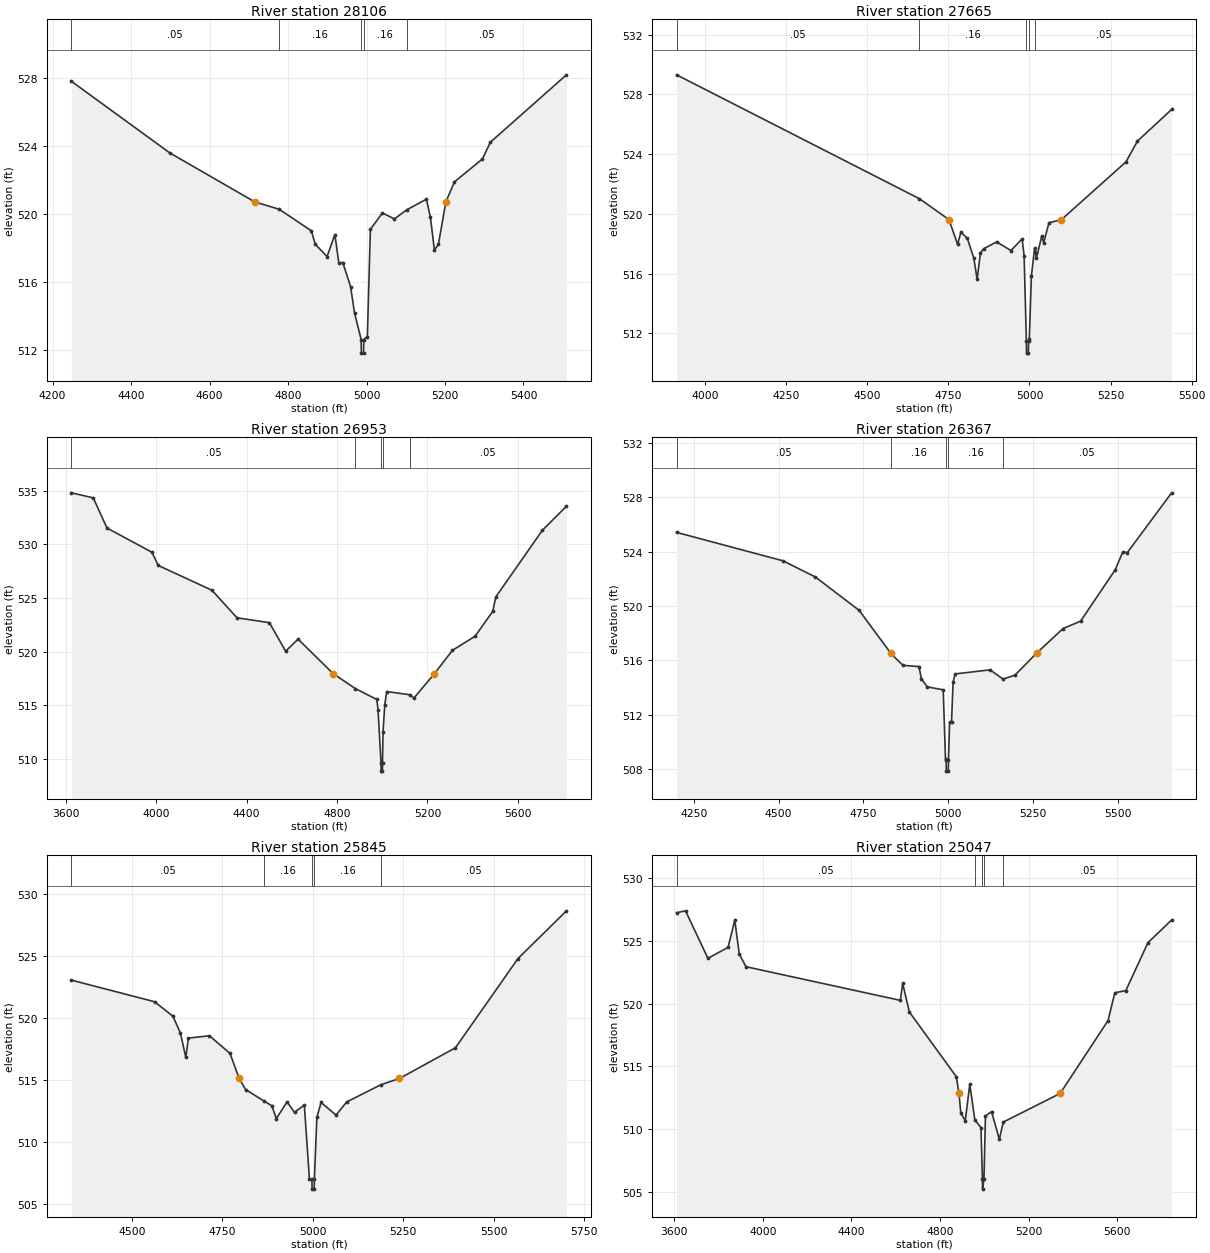
Type RM Length L Ch R = 1,28106,441,441,441
BEGIN DESCRIPTION:
LAKE FORK CREEK TRIB 1 39.0
END DESCRIPTION:
XS GIS Cut Line= 3
      2757375.00      7054775.03      2757325.00      7054025.00
      2757225.00      7053525.00
#Sta/Elev= 30
  4247.9  527.82  4498.5  523.60  4715.3  520.71  4777.3  520.28  4859.3  519.01
  4869.3  518.22  4899.4  517.49  4919.4  518.79  4929.4  517.11  4939.5  517.14
  4959.5  515.70  4969.5  514.16  4986.3  512.60  4986.8  511.80  4992.4  511.80
  4992.9  512.60  5002.1  512.77  5009.8  519.09  5040.4  520.06  5071.0  519.71
  5102.7  520.25  5152.6  520.87  5162.8  519.81  5173.0  517.87  5183.2  518.21
  5202.1  520.71  5224.0  521.89  5295.3  523.24  5315.7  524.23  5509.5  528.20
#Mann=5,-1,0
  4247.9    0.05       0  4777.3    0.16       0  4986.3    0.07       0
  4992.9    0.16       0  5102.7    0.05       0
Bank Sta=4715.3,5202.1
Exp/Cntr=0.3,0.1

Type RM Length L Ch R = 1,27665,712,712,712
BEGIN DESCRIPTION:
LAKE FORK CREEK TRIB 1 38.0
END DESCRIPTION:
XS GIS Cut Line= 3
      2757735.94      7054959.58      2757665.75      7053931.07
      2757436.86      7053491.61
#Sta/Elev= 30
  3911.8  529.31  4660.8  521.01  4751.8  519.61  4778.4  517.95  4788.4  518.77
  4808.5  518.35  4828.5  517.02  4838.5  515.61  4848.6  517.37  4858.6  517.66
  4898.7  518.12  4942.7  517.54  4977.3  518.32  4983.4  517.20  4990.4  511.47
  4990.9  510.67  4996.5  510.67  4997.0  511.47  4999.4  511.61  5005.9  515.84
  5015.8  517.71  5018.1  517.44  5021.5  517.03  5037.9  518.53  5043.6  518.06
  5060.0  519.40  5098.4  519.61  5297.5  523.48  5332.9  524.87  5438.2  526.99
#Mann=5,-1,0
  3911.8    0.05       0  4660.8    0.16       0  4990.4    0.07       0
  4997.0    0.16       0  5018.1    0.05       0
Bank Sta=4751.8,5098.4
Exp/Cntr=0.3,0.1

Type RM Length L Ch R = 1,26953,586,586,586
BEGIN DESCRIPTION:
LAKE FORK CREEK TRIB 1 37.0
END DESCRIPTION:
XS GIS Cut Line= 3
      2758724.99      7054974.97      2758075.00      7053725.00
      2757575.00      7053125.00
#Sta/Elev= 30
  3625.1  534.79  3721.7  534.32  3782.4  531.51  3981.4  529.25  4009.2  528.02
  4246.7  525.71  4357.7  523.14  4500.8  522.69  4572.7  520.03  4627.8  521.15
  4783.2  517.93  4880.9  516.55  4975.9  515.53  4981.5  514.59  4994.6  509.65
  4995.1  508.85  5000.8  508.85  5001.3  509.65  5003.6  512.51  5011.4  515.06
  5020.1  516.27  5121.0  515.97  5140.1  515.66  5230.9  517.93  5310.6  520.11
  5410.8  521.42  5488.9  523.74  5502.6  525.09  5708.9  531.31  5815.0  533.54
#Mann=5,-1,0
  3625.1    0.05       0  4880.9    0.16       0  4994.6    0.07       0
  5001.3    0.16       0  5121.0    0.05       0
Bank Sta=4783.2,5230.9
Exp/Cntr=0.3,0.1

Type RM Length L Ch R = 1,26367,522,522,522
BEGIN DESCRIPTION:
LAKE FORK CREEK TRIB 1 36.0
END DESCRIPTION:
XS GIS Cut Line= 3
      2758725.00      7054175.00      2758425.00      7053425.00
      2757874.99      7053075.00
#Sta/Elev= 30
  4199.3  525.41  4513.0  523.32  4608.6  522.13  4737.8  519.67  4830.4  516.54
  4832.9  516.45  4867.1  515.63  4914.2  515.54  4920.9  514.65  4938.4  514.05
  4985.5  513.83  4992.3  508.72  4994.2  508.65  4994.7  507.85  5000.5  507.85
  5001.0  508.65  5004.4  511.45  5010.0  511.45  5014.7  514.40  5020.6  515.00
  5123.9  515.30  5161.7  514.62  5196.7  514.90  5261.4  516.54  5339.0  518.34
  5390.6  518.88  5493.0  522.67  5515.1  523.98  5528.6  523.93  5659.0  528.32
#Mann=5,-1,0
  4199.3    0.05       0  4832.9    0.16       0  4994.2    0.07       0
  5001.0    0.16       0  5161.7    0.05       0
Bank Sta=4830.4,5261.4
Exp/Cntr=0.3,0.1

Type RM Length L Ch R = 1,25845,798,798,798
BEGIN DESCRIPTION:
LAKE FORK CREEK TRIB 1 35.0
END DESCRIPTION:
XS GIS Cut Line= 3
      2758979.98      7053680.76      2758660.27      7053220.66
      2757874.95      7053024.99
#Sta/Elev= 30
  4332.2  523.04  4562.2  521.30  4612.9  520.14  4633.8  518.78  4648.7  516.81
  4655.8  518.37  4714.2  518.56  4770.9  517.14  4796.3  515.12  4814.1  514.23
  4865.8  513.29  4886.8  512.92  4899.1  511.89  4928.8  513.24  4949.4  512.39
  4976.6  512.98  4990.7  507.02  4997.6  507.01  4998.1  506.21  5003.9  506.21
  5004.4  507.01  5011.3  511.99  5023.0  513.19  5064.3  512.17  5093.7  513.23
  5188.6  514.62  5239.8  515.12  5394.6  517.59  5567.8  524.78  5701.8  528.62
#Mann=5,-1,0
  4332.2    0.05       0  4865.8    0.16       0  4997.6    0.07       0
  5004.4    0.16       0  5188.6    0.05       0
Bank Sta=4796.3,5239.8
Exp/Cntr=0.3,0.1

Type RM Length L Ch R = 1,25047,1344,1344,1344
BEGIN DESCRIPTION:
LAKE FORK CREEK TRIB 1 34.0
END DESCRIPTION:
XS GIS Cut Line= 3
      2759275.01      7054225.04      2759075.00      7052825.00
      2758425.01      7052325.01
#Sta/Elev= 30
  3611.3  527.23  3651.7  527.38  3752.8  523.60  3843.7  524.47  3874.0  526.64
  3894.2  523.95  3924.5  522.93  4621.5  520.25  4631.6  521.61  4661.9  519.33
  4874.0  514.17  4886.0  512.84  4894.2  511.26  4914.4  510.68  4934.6  513.57
  4957.6  510.73  4985.1  510.12  4991.8  506.02  4992.3  505.22  4998.7  506.02
  5005.3  511.04  5032.8  511.39  5068.1  509.20  5086.0  510.56  5342.6  512.84
  5558.6  518.64  5589.2  520.85  5639.0  521.03  5738.7  524.84  5845.6  526.65
#Mann=5,-1,0
  3611.3    0.05       0  4957.6    0.16       0  4991.8    0.07       0
  4998.7    0.16       0  5086.0    0.05       0
Bank Sta=4886,5342.6
Exp/Cntr=0.3,0.1

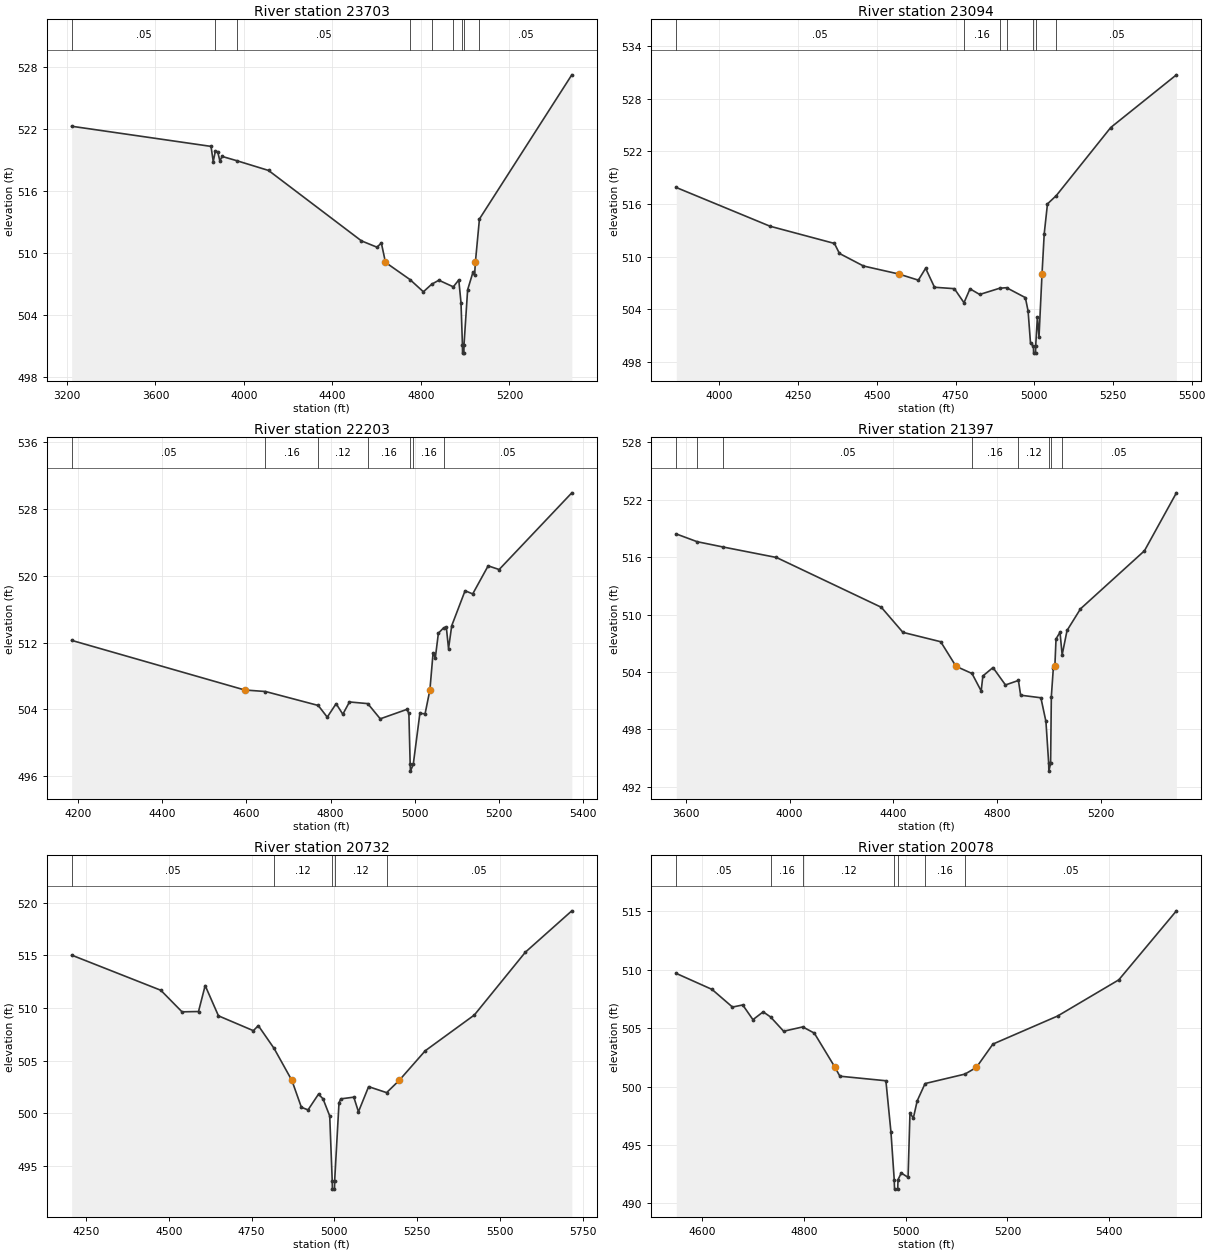
Type RM Length L Ch R = 1,23703,609,609,609
BEGIN DESCRIPTION:
LAKE FORK CREEK TRIB 1 33.0
END DESCRIPTION:
XS GIS Cut Line= 3
      2759525.00      7053875.03      2759525.00      7052075.00
      2759175.01      7051775.00
#Sta/Elev= 30
  3221.1  522.29  3851.1  520.34  3861.1  518.87  3870.3  519.85  3881.1  519.83
  3891.1  518.93  3901.1  519.37  3968.1  518.95  4111.1  518.01  4531.1  511.19
  4601.1  510.58  4621.1  510.98  4639.7  509.11  4750.7  507.44  4811.1  506.26
  4848.5  506.99  4881.1  507.38  4946.4  506.74  4971.1  507.41  4981.1  505.21
  4987.6  501.12  4988.1  500.32  4994.2  500.32  4994.7  501.12  5011.1  506.45
  5034.8  508.13  5042.5  507.84  5046.1  509.11  5064.5  513.31  5482.1  527.27
#Mann=9,-1,0
  3221.1    0.05       0  3870.3    0.08       0  3968.1    0.05       0
  4750.7    0.16       0  4848.5    0.12       0  4946.4    0.16       0
  4987.6    0.07       0  4994.7    0.16       0  5064.5    0.05       0
Bank Sta=4639.7,5046.1
Exp/Cntr=0.3,0.1

Type RM Length L Ch R = 1,23094,891,891,891
BEGIN DESCRIPTION:
LAKE FORK CREEK TRIB 1 32.0
END DESCRIPTION:
XS GIS Cut Line= 3
      2759675.00      7053025.01      2759925.00      7051925.00
      2760024.99      7051475.04
#Sta/Elev= 30
  3862.7  517.87  4160.6  513.46  4365.2  511.50  4381.1  510.36  4457.5  508.93
  4569.5  508.02  4631.8  507.32  4654.9  508.67  4683.1  506.51  4746.2  506.35
  4776.8  504.75  4795.9  506.33  4826.7  505.69  4890.2  506.40  4912.0  506.46
  4971.8  505.33  4980.5  503.79  4988.2  500.11  4997.4  499.81  4998.0  499.01
  5004.1  499.01  5004.6  499.81  5010.0  503.12  5015.1  500.83  5024.7  508.02
  5031.7  512.60  5042.0  516.00  5070.1  516.95  5243.0  524.70  5451.7  530.70
#Mann=7,-1,0
  3862.7    0.05       0  4776.8    0.16       0  4890.2    0.12       0
  4912.0    0.16       0  4997.4    0.07       0  5004.6    0.16       0
  5070.1    0.05       0
Bank Sta=4569.5,5024.7
Exp/Cntr=0.3,0.1

Type RM Length L Ch R = 1,22203,806,806,806
BEGIN DESCRIPTION:
LAKE FORK CREEK TRIB 1 31.0
END DESCRIPTION:
XS GIS Cut Line= 3
      2760275.00      7052674.99      2760334.38      7052141.07
      2760125.00      7051524.99
#Sta/Elev= 30
  4184.9  512.26  4596.0  506.32  4645.2  506.14  4770.5  504.47  4791.9  503.07
  4813.0  504.68  4828.9  503.42  4844.7  504.89  4888.2  504.69  4917.8  502.87
  4980.5  503.99  4985.8  503.55  4988.9  497.41  4989.5  496.61  4996.2  497.41
  5011.9  503.51  5024.3  503.48  5035.7  506.32  5043.3  510.76  5048.6  510.17
  5055.9  513.12  5068.3  513.76  5074.7  513.85  5080.0  511.27  5087.6  514.02
  5119.3  518.20  5137.4  517.82  5174.1  521.18  5200.2  520.74  5372.8  529.92
#Mann=7,-1,0
  4184.9    0.05       0  4645.2    0.16       0  4770.5    0.12       0
  4888.2    0.16       0  4988.9    0.07       0  4996.2    0.16       0
  5068.3    0.05       0
Bank Sta=4596,5035.7
Exp/Cntr=0.3,0.1

Type RM Length L Ch R = 1,21397,665,665,665
BEGIN DESCRIPTION:
LAKE FORK CREEK TRIB 1 30.0
END DESCRIPTION:
XS GIS Cut Line= 3
      2760424.99      7053325.02      2760825.00      7051925.00
      2760575.02      7051525.04
#Sta/Elev= 30
  3562.9  518.43  3643.3  517.62  3744.3  517.06  3949.0  515.97  4353.3  510.76
  4436.5  508.14  4582.1  507.16  4641.1  504.59  4702.7  503.84  4738.1  502.01
  4744.6  503.58  4783.6  504.46  4831.7  502.64  4881.6  503.11  4890.2  501.57
  4968.2  501.30  4987.7  498.82  4998.3  494.43  4998.9  493.63  5005.7  494.43
  5008.5  501.42  5016.3  504.45  5022.1  504.59  5026.6  507.46  5041.9  508.15
  5050.2  505.79  5069.1  508.34  5120.9  510.60  5367.4  516.67  5490.6  522.73
#Mann=8,-1,0
  3562.9    0.05       0  3643.3    0.08       0  3744.3    0.05       0
  4702.7    0.16       0  4881.6    0.12       0  4998.3    0.07       0
  5005.7    0.12       0  5050.2    0.05       0
Bank Sta=4641.1,5022.1
Exp/Cntr=0.3,0.1

Type RM Length L Ch R = 1,20732,654,654,654
BEGIN DESCRIPTION:
LAKE FORK CREEK TRIB 1 29.0
END DESCRIPTION:
XS GIS Cut Line= 4
      2760925.00      7052875.02      2761125.00      7052125.00
      2761195.00      7051985.00      2760925.01      7051475.01
#Sta/Elev= 30
  4207.0  515.02  4476.1  511.68  4540.1  509.63  4589.9  509.66  4610.0  512.13
  4650.1  509.25  4755.5  507.84  4770.4  508.32  4818.1  506.15  4871.8  503.11
  4900.4  500.56  4920.5  500.31  4952.2  501.81  4965.8  501.36  4986.0  499.73
  4993.5  493.58  4994.1  492.78  5000.4  492.78  5000.9  493.58  5014.0  500.99
  5019.6  501.36  5058.7  501.52  5072.7  500.13  5103.4  502.52  5157.7  501.95
  5195.6  503.11  5274.3  505.93  5422.6  509.33  5576.6  515.30  5716.8  519.23
#Mann=5,-1,0
  4207.0    0.05       0  4818.1    0.12       0  4993.5    0.07       0
  5000.9    0.12       0  5157.7    0.05       0
Bank Sta=4871.8,5195.6
Exp/Cntr=0.3,0.1

Type RM Length L Ch R = 1,20078,585,585,585
BEGIN DESCRIPTION:
LAKE FORK CREEK TRIB 1 28.0
END DESCRIPTION:
XS GIS Cut Line= 3
      2761475.00      7052374.96      2761425.00      7051925.00
      2761025.03      7051575.03
#Sta/Elev= 30
  4548.4  509.69  4618.8  508.32  4659.0  506.81  4679.2  506.99  4699.3  505.73
  4719.4  506.40  4734.0  505.96  4759.7  504.74  4797.3  505.11  4820.0  504.58
  4860.9  501.64  4870.3  500.89  4960.9  500.50  4970.9  496.08  4977.3  492.02
  4977.9  491.22  4984.2  491.22  4984.7  492.02  4991.1  492.60  5004.5  492.23
  5008.3  497.74  5014.9  497.30  5022.5  498.78  5038.0  500.26  5116.5  501.07
  5138.9  501.64  5171.5  503.64  5298.7  506.04  5419.2  509.14  5532.6  515.05
#Mann=7,-1,0
  4548.4    0.05       0  4734.0    0.16       0  4797.3    0.12       0
  4977.3    0.07       0  4984.7    0.12       0  5038.0    0.16       0
  5116.5    0.05       0
Bank Sta=4860.9,5138.9
Exp/Cntr=0.3,0.1