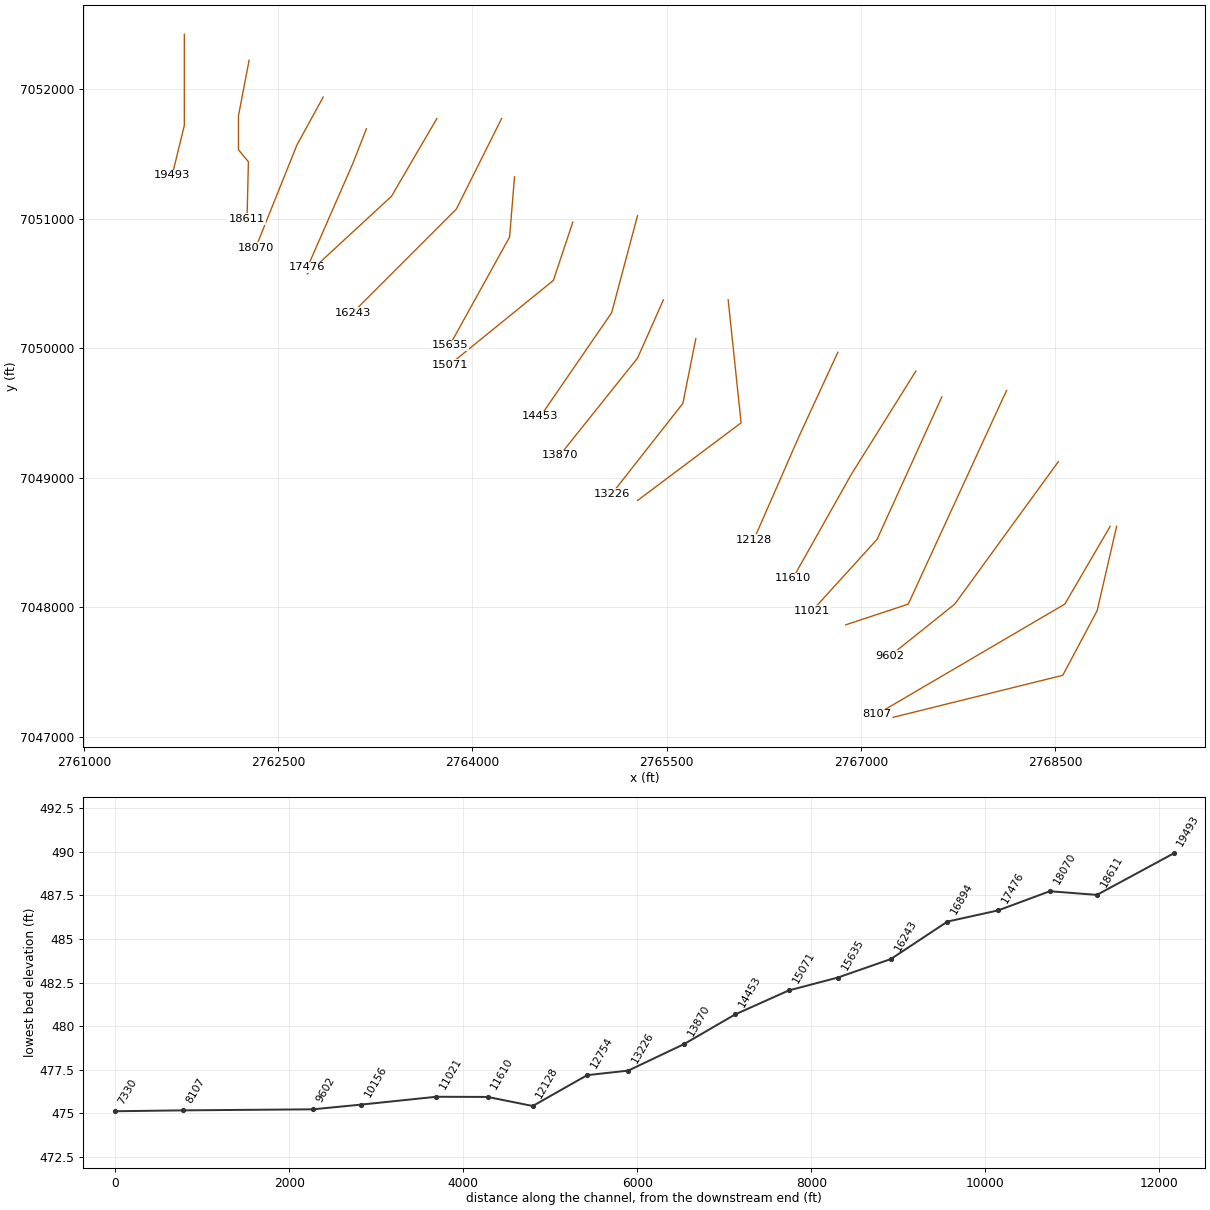
HEC-RAS study LAKE FORK CREEK TRIB 1.prj: LAKE FORK CREEK TRIB 1 Base Level Engineering

--- LAKE FORK CREEK TRIB 1.g01 (geometry) --- (continued)

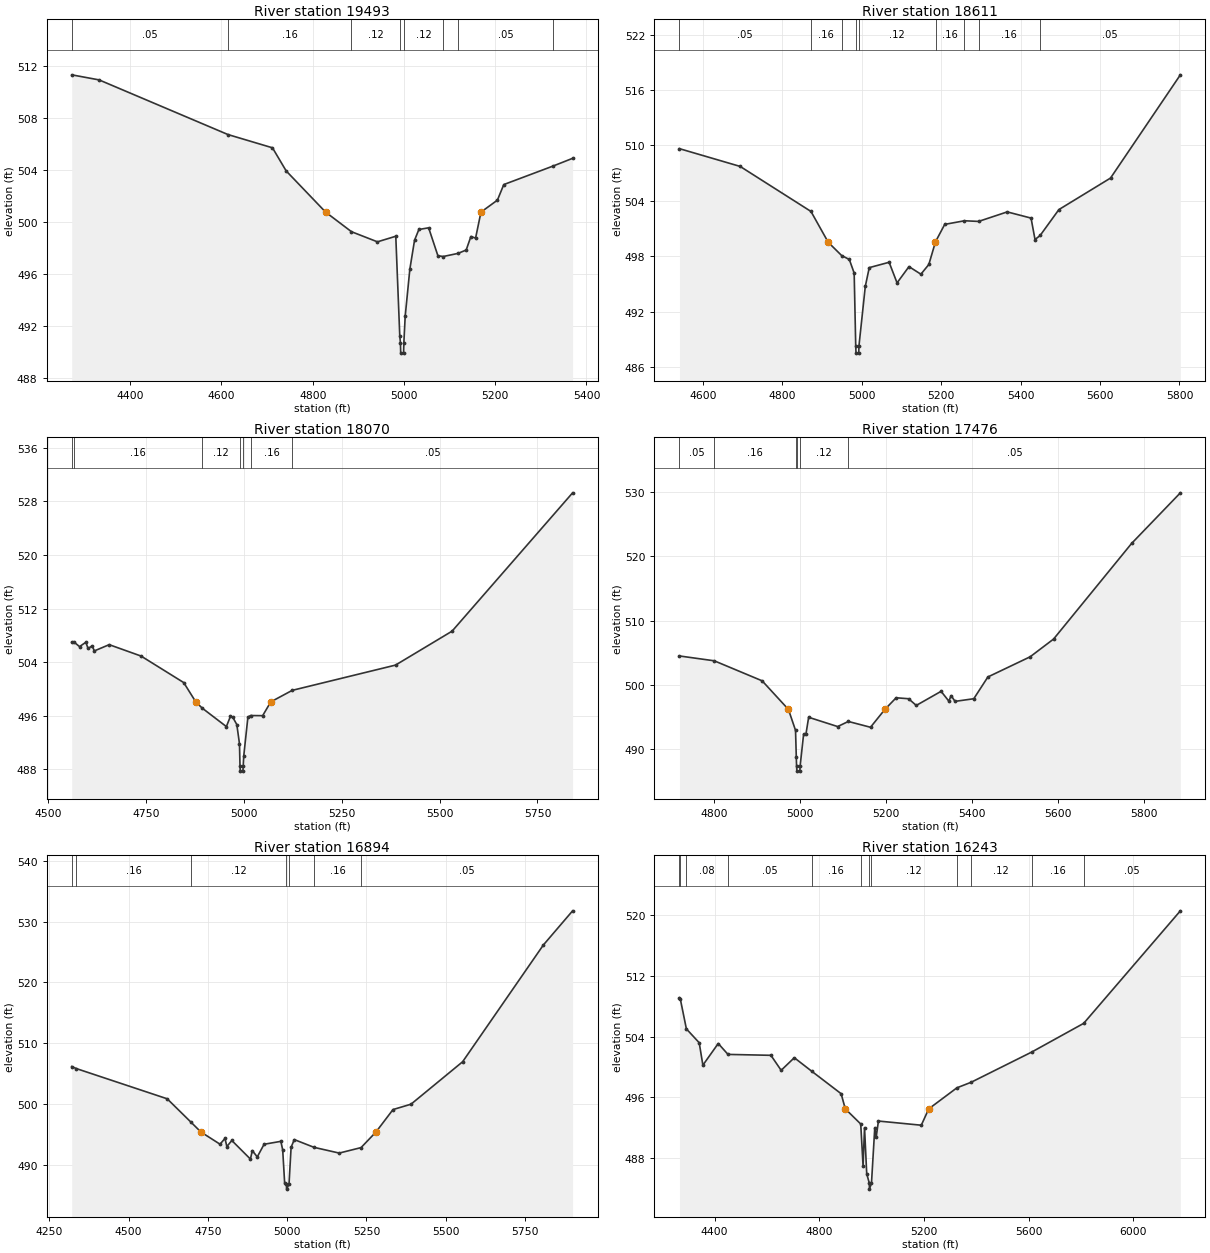
Type RM Length L Ch R = 1,19493,882,882,882
BEGIN DESCRIPTION:
LAKE FORK CREEK TRIB 1 27.0
END DESCRIPTION:
XS GIS Cut Line= 3
      2761775.00      7052424.96      2761774.75      7051722.31
      2761681.38      7051338.45
#Sta/Elev= 30
  4271.9  511.34  4331.9  510.95  4614.4  506.74  4711.9  505.72  4741.9  503.94
  4828.3  500.77  4885.0  499.26  4941.9  498.48  4982.1  498.91  4990.9  491.20
  4992.3  490.71  4992.9  489.91  4999.2  489.91  4999.8  490.71  5002.7  492.74
  5012.9  496.37  5023.2  498.60  5032.7  499.43  5054.1  499.56  5074.4  497.41
  5086.0  497.35  5118.5  497.59  5136.4  497.85  5146.7  498.89  5157.0  498.77
  5168.8  500.77  5204.8  501.69  5218.8  502.89  5327.1  504.32  5369.6  504.91
#Mann=8,-1,0
  4271.9    0.05       0  4614.4    0.16       0  4885.0    0.12       0
  4992.3    0.07       0  4999.8    0.12       0  5086.0    0.16       0
  5118.5    0.05       0  5327.1    0.16       0
Bank Sta=4828.3,5168.8
Exp/Cntr=0.3,0.1

Type RM Length L Ch R = 1,18611,541,541,541
BEGIN DESCRIPTION:
LAKE FORK CREEK TRIB 1 26.0
END DESCRIPTION:
XS GIS Cut Line= 5
      2762275.01      7052225.04      2762192.71      7051795.83
      2762192.71      7051534.81      2762269.54      7051441.06
      2762259.14      7050999.14
#Sta/Elev= 30
  4541.0  509.65  4693.8  507.73  4872.1  502.86  4915.6  499.52  4949.3  498.09
  4968.7  497.66  4980.9  496.19  4984.8  488.33  4985.5  487.53  4992.3  487.53
  4993.0  488.33  5008.9  494.75  5018.9  496.78  5068.9  497.36  5088.9  495.13
  5118.9  496.89  5148.9  496.07  5168.9  497.12  5185.3  499.52  5186.1  499.61
  5208.9  501.46  5258.7  501.85  5294.2  501.78  5366.3  502.81  5426.3  502.14
  5436.3  499.82  5449.2  500.26  5496.4  503.06  5626.4  506.47  5802.3  517.64
#Mann=9,-1,0
  4541.0    0.05       0  4872.1    0.16       0  4949.3    0.12       0
  4984.8    0.07       0  4993.0    0.12       0  5186.1    0.16       0
  5258.7    0.12       0  5294.2    0.16       0  5449.2    0.05       0
Bank Sta=4915.6,5185.3
Exp/Cntr=0.3,0.1

Type RM Length L Ch R = 1,18070,594,594,594
BEGIN DESCRIPTION:
LAKE FORK CREEK TRIB 1 25.0
END DESCRIPTION:
XS GIS Cut Line= 3
      2762847.68      7051941.09      2762644.54      7051571.27
      2762325.01      7050775.03
#Sta/Elev= 30
  4559.9  507.02  4566.8  506.96  4579.9  506.33  4596.0  506.98  4601.7  506.05
  4612.1  506.44  4617.8  505.69  4655.7  506.62  4737.1  504.92  4846.1  500.96
  4876.9  498.08  4893.5  497.14  4955.1  494.39  4965.5  495.92  4971.2  495.81
  4981.8  494.69  4988.6  491.82  4989.9  488.54  4990.6  487.74  4997.4  487.74
  4998.2  488.54  4999.4  489.95  5010.1  495.80  5016.9  496.04  5047.8  496.02
  5068.6  498.08  5123.4  499.80  5387.3  503.57  5531.9  508.64  5839.8  529.29
#Mann=7,-1,0
  4559.9    0.05       0  4566.8    0.16       0  4893.5    0.12       0
  4989.9    0.07       0  4998.2    0.12       0  5016.9    0.16       0
  5123.4    0.05       0
Bank Sta=4876.9,5068.6
Exp/Cntr=0.3,0.1

Type RM Length L Ch R = 1,17476,582,582,582
BEGIN DESCRIPTION:
LAKE FORK CREEK TRIB 1 24.0
END DESCRIPTION:
XS GIS Cut Line= 3
      2763181.01      7051696.31      2763075.00      7051425.00
      2762725.00      7050625.00
#Sta/Elev= 30
  4720.0  504.52  4800.8  503.77  4912.2  500.66  4973.3  496.22  4989.8  492.97
  4991.6  488.82  4992.2  487.44  4993.0  486.64  4999.8  486.64  5000.5  487.44
  5008.6  492.38  5014.0  492.38  5020.3  495.00  5087.7  493.56  5112.6  494.35
  5164.1  493.45  5197.5  496.22  5223.7  498.03  5252.6  497.88  5270.5  496.84
  5328.2  499.03  5346.2  497.51  5351.6  498.36  5360.6  497.47  5404.2  497.88
  5437.0  501.26  5535.2  504.39  5589.8  507.15  5771.1  521.99  5884.5  529.85
#Mann=6,-1,0
  4720.0    0.05       0  4800.8    0.16       0  4991.6    0.12       0
  4992.2    0.07       0  5000.5    0.12       0  5112.6    0.05       0
Bank Sta=4973.3,5197.5
Exp/Cntr=0.3,0.1

Type RM Length L Ch R = 1,16894,651,651,651
BEGIN DESCRIPTION:
LAKE FORK CREEK TRIB 1 23.0
END DESCRIPTION:
XS GIS Cut Line= 3
      2763724.98      7051774.97      2763375.00      7051175.00
      2762724.99      7050574.99
#Sta/Elev= 30
  4320.8  506.17  4335.4  505.83  4621.8  500.86  4696.9  497.01  4728.1  495.40
  4788.4  493.39  4804.1  494.35  4809.9  493.00  4825.6  494.00  4884.3  490.94
  4890.1  492.34  4905.8  491.30  4927.3  493.38  4980.2  493.86  4986.0  492.45
  4992.2  486.97  4997.6  486.80  4998.3  486.00  5005.9  486.80  5012.5  492.88
  5022.5  494.15  5085.0  492.87  5164.2  491.93  5233.0  492.83  5280.1  495.40
  5333.8  499.09  5390.5  499.97  5553.2  506.95  5807.8  526.16  5900.0  531.78
#Mann=7,-1,0
  4320.8    0.05       0  4335.4    0.16       0  4696.9    0.12       0
  4997.6    0.07       0  5005.9    0.12       0  5085.0    0.16       0
  5233.0    0.05       0
Bank Sta=4728.1,5280.1
Exp/Cntr=0.3,0.1

Type RM Length L Ch R = 1,16243,608,608,608
BEGIN DESCRIPTION:
LAKE FORK CREEK TRIB 1 22.0
END DESCRIPTION:
XS GIS Cut Line= 3
      2764224.99      7051774.98      2763875.00      7051075.00
      2763074.98      7050274.98
#Sta/Elev= 30
  4266.0  509.12  4269.2  508.96  4292.4  505.01  4341.4  503.18  4355.4  500.22
  4414.1  503.08  4451.4  501.64  4615.4  501.52  4654.5  499.54  4704.8  501.20
  4770.9  499.43  4883.7  496.45  4899.6  494.45  4958.6  492.45  4967.5  486.93
  4973.1  491.97  4981.5  485.87  4991.3  484.65  4992.0  483.85  4999.7  484.65
  5012.3  491.97  5017.9  490.76  5026.2  492.84  5190.0  492.29  5218.5  494.45
  5326.2  497.23  5380.4  497.96  5611.4  501.94  5810.5  505.74  6180.0  520.60
#Mann=12,-1,0
  4266.0    0.05       0  4269.2    0.16       0  4292.4    0.08       0
  4451.4    0.05       0  4770.9    0.16       0  4958.6    0.12       0
  4991.3    0.07       0  4999.7    0.12       0  5326.2    0.16       0
  5380.4    0.12       0  5611.4    0.16       0  5810.5    0.05       0
Bank Sta=4899.6,5218.5
Exp/Cntr=0.3,0.1

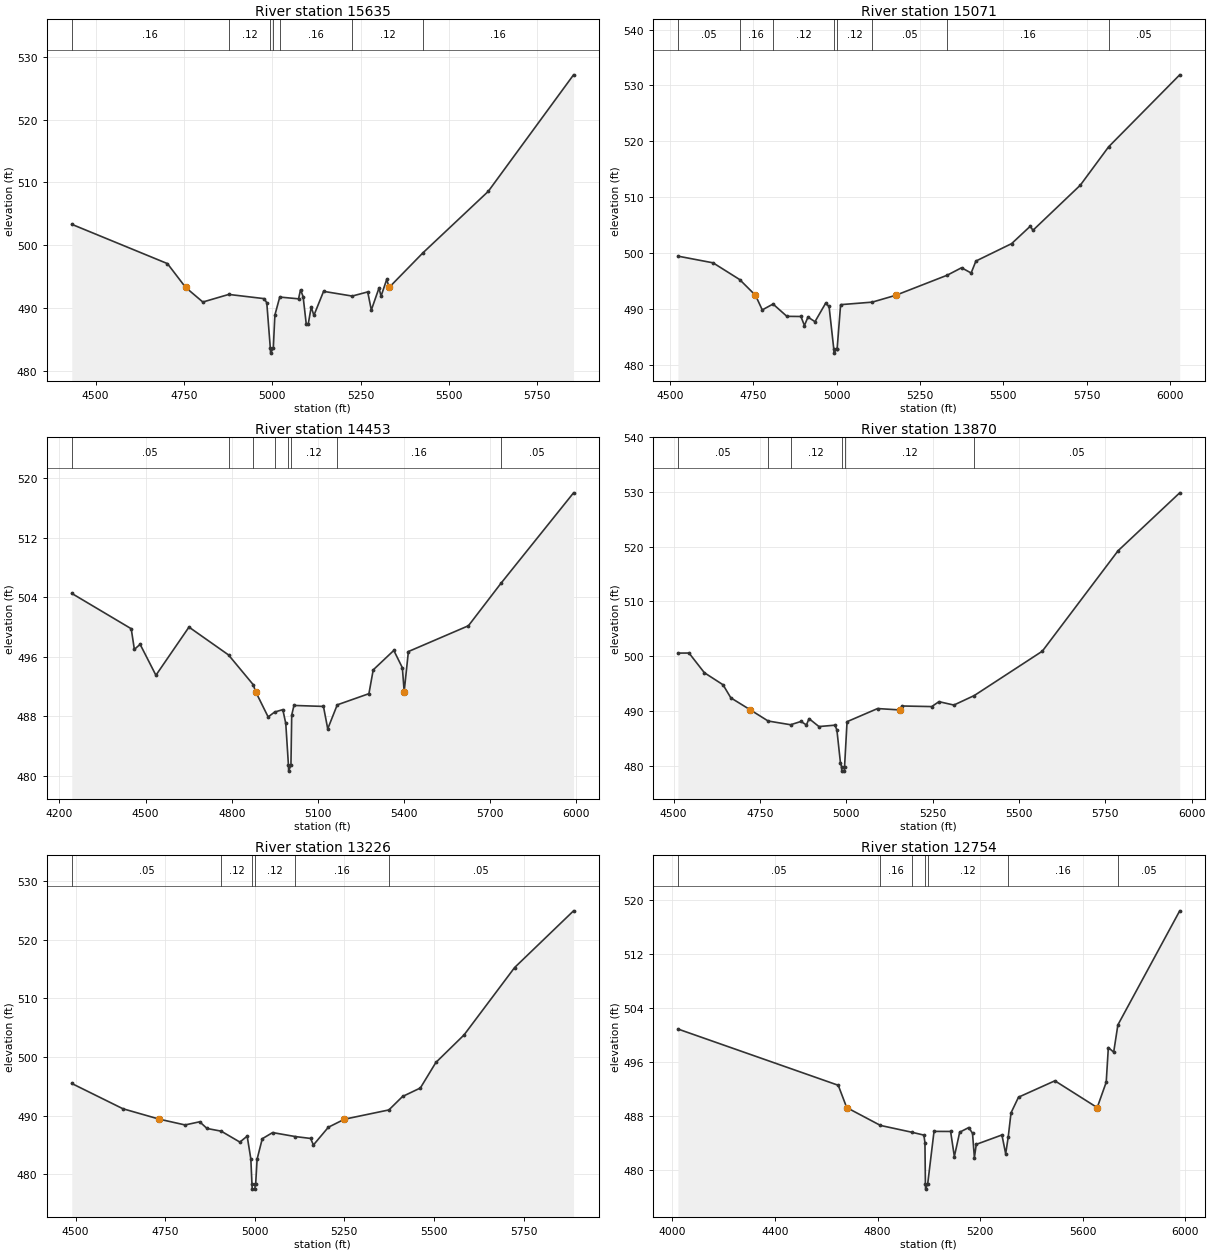
Type RM Length L Ch R = 1,15635,564,564,564
BEGIN DESCRIPTION:
LAKE FORK CREEK TRIB 1 21.0
END DESCRIPTION:
XS GIS Cut Line= 3
      2764325.00      7051324.99      2764286.88      7050859.87
      2763825.00      7050025.00
#Sta/Elev= 30
  4432.4  503.31  4703.3  497.05  4754.8  493.26  4803.6  490.93  4877.0  492.14
  4977.1  491.47  4984.6  490.81  4994.6  483.59  4995.4  482.79  5003.1  483.59
  5007.5  488.84  5021.3  491.72  5074.5  491.44  5080.2  492.88  5087.5  491.79
  5096.2  487.49  5101.9  487.40  5110.4  490.14  5118.0  488.80  5145.4  492.63
  5226.4  491.88  5270.4  492.54  5280.6  489.65  5302.4  493.17  5308.1  491.85
  5324.1  494.52  5331.1  493.26  5427.0  498.78  5611.6  508.55  5853.2  527.12
#Mann=7,-1,0
  4432.4    0.16       0  4877.0    0.12       0  4994.6    0.07       0
  5003.1    0.12       0  5021.3    0.16       0  5226.4    0.12       0
  5427.0    0.16       0
Bank Sta=4754.8,5331.1
Exp/Cntr=0.3,0.1

Type RM Length L Ch R = 1,15071,618,618,618
BEGIN DESCRIPTION:
LAKE FORK CREEK TRIB 1 20.0
END DESCRIPTION:
XS GIS Cut Line= 3
      2764775.00      7050975.00      2764625.00      7050525.00
      2763825.02      7049875.01
#Sta/Elev= 30
  4524.3  499.42  4629.7  498.22  4709.4  495.23  4757.0  492.40  4777.3  489.79
  4809.6  490.84  4851.1  488.64  4893.2  488.61  4903.8  486.99  4914.3  488.51
  4935.4  487.68  4967.0  490.95  4977.6  490.43  4991.7  482.85  4992.5  482.05
  5000.4  482.85  5001.9  482.85  5012.3  490.73  5106.9  491.18  5177.3  492.40
  5332.2  496.01  5375.0  497.34  5403.8  496.40  5418.1  498.54  5525.2  501.66
  5581.2  504.78  5589.1  504.04  5731.3  512.13  5816.2  519.00  6029.4  531.89
#Mann=8,-1,0
  4524.3    0.05       0  4709.4    0.16       0  4809.6    0.12       0
  4991.7    0.07       0  5000.4    0.12       0  5106.9    0.05       0
  5332.2    0.16       0  5816.2    0.05       0
Bank Sta=4757,5177.3
Exp/Cntr=0.3,0.1

Type RM Length L Ch R = 1,14453,583,583,583
BEGIN DESCRIPTION:
LAKE FORK CREEK TRIB 1 19.0
END DESCRIPTION:
XS GIS Cut Line= 3
      2765275.00      7051024.99      2765075.00      7050275.00
      2764525.01      7049475.02
#Sta/Elev= 30
  4243.2  504.51  4450.2  499.77  4461.2  497.00  4481.2  497.68  4536.2  493.53
  4651.3  499.99  4788.9  496.26  4875.3  492.25  4883.1  491.35  4926.9  487.94
  4949.4  488.59  4978.0  488.92  4988.3  487.06  4997.6  481.47  4998.3  480.67
  5006.3  481.47  5009.0  488.19  5016.8  489.48  5119.5  489.35  5134.4  486.34
  5167.5  489.56  5277.8  491.06  5292.7  494.25  5364.4  496.86  5394.2  494.54
  5400.5  491.35  5415.2  496.71  5624.2  500.17  5737.2  505.85  5990.2  518.00
#Mann=8,-1,0
  4243.2    0.05       0  4788.9    0.12       0  4875.3    0.16       0
  4949.4    0.12       0  4997.6    0.07       0  5006.3    0.12       0
  5167.5    0.16       0  5737.2    0.05       0
Bank Sta=4883.1,5400.5
Exp/Cntr=0.3,0.1

Type RM Length L Ch R = 1,13870,644,644,644
BEGIN DESCRIPTION:
LAKE FORK CREEK TRIB 1 18.0
END DESCRIPTION:
XS GIS Cut Line= 3
      2765475.00      7050374.99      2765275.00      7049925.00
      2764675.00      7049175.00
#Sta/Elev= 30
  4512.6  500.56  4544.7  500.57  4589.2  496.97  4643.2  494.77  4665.8  492.38
  4722.5  490.17  4773.9  488.14  4838.9  487.46  4868.9  488.06  4884.7  487.42
  4892.2  488.58  4920.9  487.13  4967.4  487.38  4972.9  486.50  4983.1  480.55
  4986.3  479.78  4987.1  478.98  4994.3  478.98  4995.1  479.78  5002.3  488.02
  5090.7  490.42  5154.8  490.17  5161.1  490.89  5247.5  490.78  5268.4  491.68
  5311.6  491.06  5370.7  492.80  5567.7  500.91  5787.0  519.27  5965.5  529.86
#Mann=6,-1,0
  4512.6    0.05       0  4773.9    0.16       0  4838.9    0.12       0
  4986.3    0.07       0  4995.1    0.12       0  5370.7    0.05       0
Bank Sta=4722.5,5154.8
Exp/Cntr=0.3,0.1

Type RM Length L Ch R = 1,13226,472,472,472
BEGIN DESCRIPTION:
LAKE FORK CREEK TRIB 1 17.0
END DESCRIPTION:
XS GIS Cut Line= 3
      2765725.01      7050075.04      2765625.00      7049575.00
      2765074.98      7048874.97
#Sta/Elev= 30
  4489.3  495.46  4632.1  491.15  4734.0  489.37  4805.5  488.39  4846.3  488.93
  4866.7  487.79  4906.3  487.33  4958.4  485.47  4978.8  486.48  4989.0  482.60
  4992.2  478.25  4993.0  477.45  5000.3  477.45  5001.1  478.25  5002.4  478.25
  5006.5  482.56  5020.9  486.04  5049.8  487.09  5113.2  486.41  5155.6  486.09
  5163.7  484.98  5205.3  488.00  5250.3  489.37  5374.2  490.95  5412.3  493.24
  5462.0  494.69  5505.3  499.04  5584.0  503.74  5725.0  515.22  5889.5  524.89
#Mann=6,-1,0
  4489.3    0.05       0  4906.3    0.12       0  4992.2    0.07       0
  5001.1    0.12       0  5113.2    0.16       0  5374.2    0.05       0
Bank Sta=4734,5250.3
Exp/Cntr=0.3,0.1

Type RM Length L Ch R = 1,12754,626,626,626
BEGIN DESCRIPTION:
LAKE FORK CREEK TRIB 1 16.0
END DESCRIPTION:
XS GIS Cut Line= 3
      2765975.00      7050374.99      2766075.00      7049425.00
      2765275.03      7048825.02
#Sta/Elev= 30
  4022.3  500.87  4647.0  492.55  4680.0  489.25  4811.5  486.61  4934.2  485.60
  4980.7  485.18  4984.8  484.07  4986.6  477.99  4987.4  477.19  4995.6  477.99
  5020.2  485.73  5084.8  485.72  5099.4  482.01  5120.2  485.61  5155.7  486.30
  5170.2  485.44  5177.5  481.84  5184.8  483.81  5284.8  485.20  5299.4  482.41
  5309.4  484.93  5320.2  488.47  5349.4  490.79  5491.1  493.21  5656.0  489.25
  5691.1  493.00  5699.4  498.13  5720.2  497.45  5736.6  501.48  5977.5  518.35
#Mann=7,-1,0
  4022.3    0.05       0  4811.5    0.16       0  4934.2    0.12       0
  4986.6    0.07       0  4995.6    0.12       0  5309.4    0.16       0
  5736.6    0.05       0
Bank Sta=4680,5656
Exp/Cntr=0.3,0.1

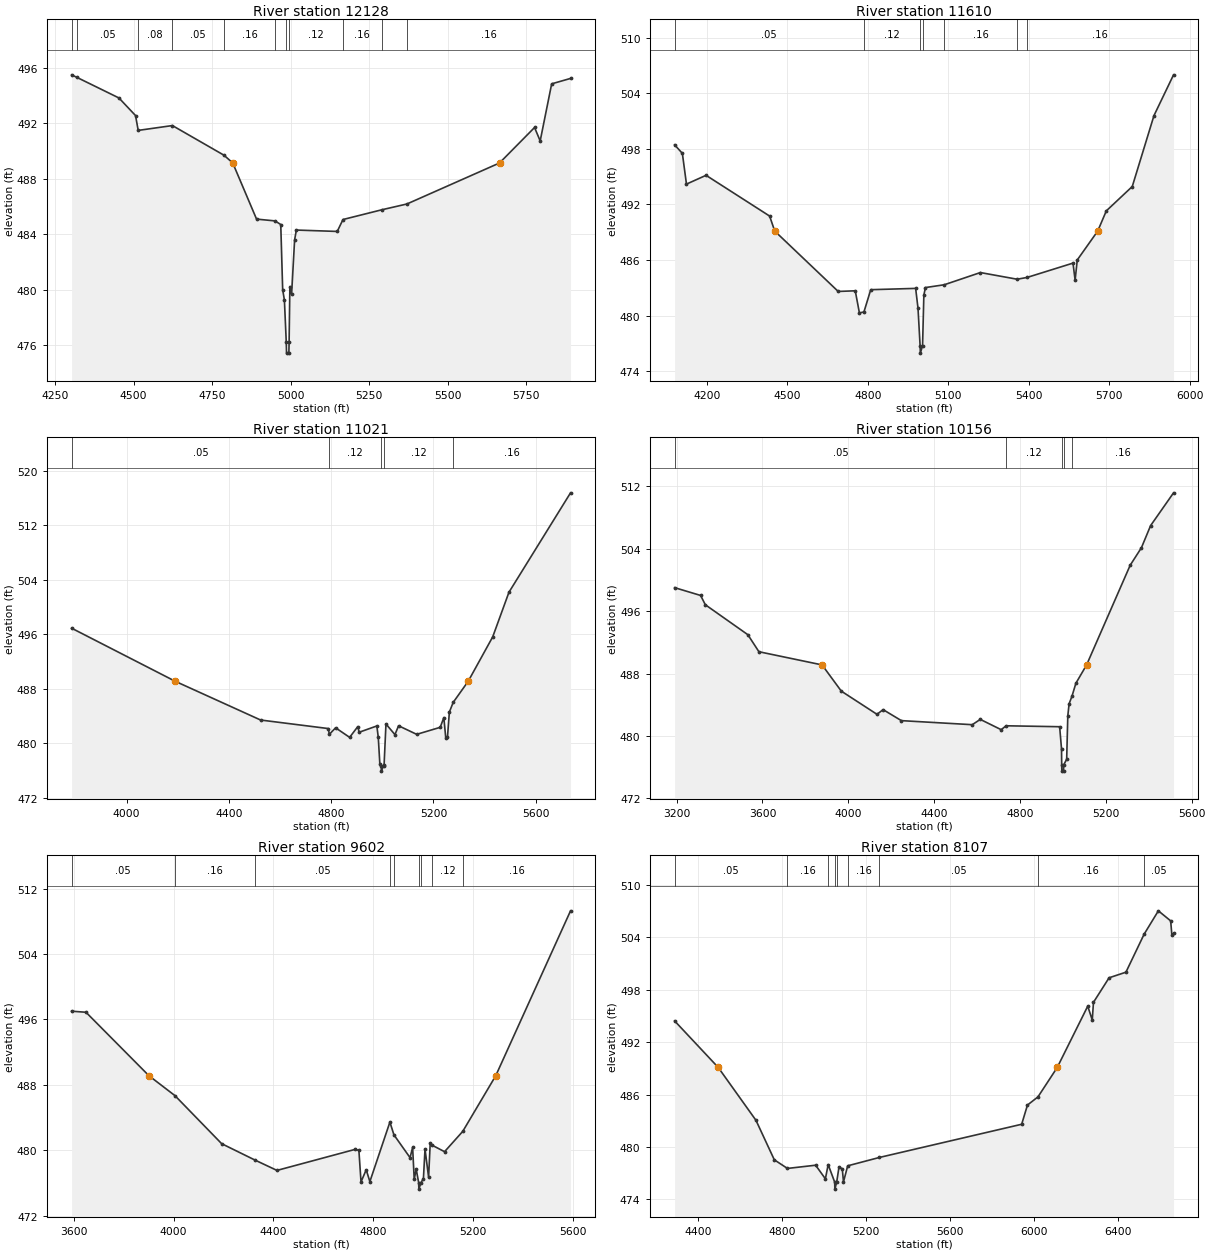
Type RM Length L Ch R = 1,12128,518,518,518
BEGIN DESCRIPTION:
LAKE FORK CREEK TRIB 1 15.0
END DESCRIPTION:
XS GIS Cut Line= 3
      2766821.89      7049969.82      2766521.88      7049319.79
      2766171.93      7048519.91
#Sta/Elev= 30
  4302.7  495.50  4319.2  495.32  4453.5  493.83  4506.3  492.56  4514.8  491.49
  4623.7  491.84  4788.0  489.70  4815.9  489.14  4891.7  485.09  4950.5  484.96
  4968.8  484.70  4974.9  480.00  4980.4  479.25  4986.3  476.22  4987.2  475.42
  4994.6  475.42  4995.4  476.22  4997.8  480.22  5003.3  479.66  5012.9  483.59
  5018.5  484.30  5148.7  484.20  5167.0  485.06  5290.1  485.76  5370.5  486.18
  5665.5  489.14  5777.1  491.70  5795.0  490.73  5831.6  494.85  5891.7  495.24
#Mann=11,-1,0
  4302.7    0.16       0  4319.2    0.05       0  4514.8    0.08       0
  4623.7    0.05       0  4788.0    0.16       0  4950.5    0.12       0
  4986.3    0.07       0  4995.4    0.12       0  5167.0    0.16       0
  5290.1    0.07       0  5370.5    0.16       0
Bank Sta=4815.9,5665.5
Exp/Cntr=0.3,0.1

Type RM Length L Ch R = 1,11610,589,589,589
BEGIN DESCRIPTION:
LAKE FORK CREEK TRIB 1 14.0
END DESCRIPTION:
XS GIS Cut Line= 3
      2767425.00      7049825.01      2766925.00      7049025.00
      2766474.99      7048224.99
#Sta/Elev= 30
  4079.0  498.43  4107.9  497.51  4123.2  494.19  4196.3  495.14  4433.4  490.74
  4452.5  489.12  4689.3  482.60  4752.9  482.67  4768.3  480.29  4785.2  480.38
  4810.7  482.79  4978.2  482.93  4987.0  480.79  4994.8  476.74  4995.7  475.94
  5004.0  476.74  5008.8  482.20  5014.7  483.02  5084.7  483.32  5219.7  484.64
  5356.8  483.92  5393.7  484.11  5565.2  485.66  5573.1  483.82  5581.1  486.00
  5657.4  489.12  5689.5  491.30  5786.3  493.93  5867.3  501.59  5940.3  505.99
#Mann=7,-1,0
  4079.0    0.05       0  4785.2    0.12       0  4994.8    0.07       0
  5004.0    0.12       0  5084.7    0.16       0  5356.8    0.12       0
  5393.7    0.16       0
Bank Sta=4452.5,5657.4
Exp/Cntr=0.3,0.1

Type RM Length L Ch R = 1,11021,865,865,865
BEGIN DESCRIPTION:
LAKE FORK CREEK TRIB 1 13.0
END DESCRIPTION:
XS GIS Cut Line= 3
      2767625.00      7049625.00      2767125.00      7048525.00
      2766625.01      7047975.01
#Sta/Elev= 30
  3784.8  496.90  4190.0  489.12  4524.1  483.44  4788.8  482.19  4792.9  481.34
  4817.4  482.30  4872.3  480.90  4904.1  482.47  4909.6  481.65  4978.8  482.57
  4984.3  480.91  4990.4  477.06  4995.6  476.75  4996.5  475.95  5004.9  476.75
  5007.0  476.79  5014.4  482.86  5049.5  481.30  5063.7  482.60  5134.7  481.34
  5226.6  482.37  5240.8  483.80  5248.2  480.86  5255.0  480.92  5262.4  484.61
  5277.5  486.03  5336.1  489.12  5432.0  495.63  5495.5  502.17  5736.4  516.74
#Mann=5,-1,0
  3784.8    0.05       0  4792.9    0.12       0  4995.6    0.07       0
  5004.9    0.12       0  5277.5    0.16       0
Bank Sta=4190,5336.1
Exp/Cntr=0.3,0.1

Type RM Length L Ch R = 1,10156,554,554,554
BEGIN DESCRIPTION:
LAKE FORK CREEK TRIB 1 12.0
END DESCRIPTION:
XS GIS Cut Line= 3
      2768125.02      7049675.04      2767365.63      7048024.65
      2766882.98      7047864.93
#Sta/Elev= 30
  3190.5  499.01  3311.6  498.01  3333.6  496.82  3531.8  492.98  3583.3  490.80
  3877.7  489.11  3967.3  485.75  4133.6  482.78  4162.1  483.38  4247.3  481.97
  4577.5  481.45  4615.0  482.13  4712.4  480.81  4735.2  481.31  4984.8  481.19
  4993.5  478.36  4994.4  476.30  4995.2  475.50  5002.8  475.50  5003.7  476.30
  5017.6  477.02  5022.8  482.58  5028.9  484.13  5042.4  485.11  5060.5  486.76
  5110.4  489.11  5313.5  501.88  5366.0  504.13  5408.7  506.96  5515.6  511.16
#Mann=5,-1,0
  3190.5    0.05       0  4735.2    0.12       0  4994.4    0.07       0
  5003.7    0.12       0  5042.4    0.16       0
Bank Sta=3877.7,5110.4
Exp/Cntr=0.3,0.1

Type RM Length L Ch R = 1,9602,1495,1495,1495
BEGIN DESCRIPTION:
LAKE FORK CREEK TRIB 1 11.0
END DESCRIPTION:
XS GIS Cut Line= 3
      2768524.99      7049124.99      2767725.00      7048025.00
      2767224.96      7047624.97
#Sta/Elev= 30
  3591.1  497.00  3648.7  496.87  3901.0  489.11  4005.4  486.67  4192.7  480.79
  4326.1  478.79  4414.5  477.52  4728.7  480.10  4743.0  479.96  4751.5  476.11
  4772.3  477.60  4787.0  476.15  4867.3  483.43  4883.5  481.87  4948.1  479.08
  4958.4  480.33  4964.8  476.44  4972.8  477.67  4982.6  476.03  4983.5  475.23
  4992.0  476.03  5001.7  476.52  5008.1  480.13  5022.5  476.69  5028.9  480.82
  5036.2  480.61  5086.5  479.81  5159.5  482.30  5291.8  489.11  5591.6  509.28
#Mann=9,-1,0
  3591.1    0.05       0  4005.4    0.16       0  4326.1    0.05       0
  4867.3    0.16       0  4883.5    0.05       0  4982.6    0.03       0
  4992.0    0.05       0  5036.2    0.12       0  5159.5    0.16       0
Bank Sta=3901,5291.8
Exp/Cntr=0.3,0.1

Type RM Length L Ch R = 1,8107,777,777,777
BEGIN DESCRIPTION:
LAKE FORK CREEK TRIB 1 10.0
END DESCRIPTION:
XS GIS Cut Line= 3
      2768924.99      7048624.98      2768575.00      7048025.00
      2767124.98      7047174.99
#Sta/Elev= 30
  4289.7  494.44  4497.3  489.11  4677.1  483.05  4764.3  478.53  4826.9  477.54
  4961.1  477.91  5007.5  476.35  5020.8  477.98  5051.8  475.97  5052.7  475.17
  5061.3  475.97  5072.3  477.70  5087.9  477.50  5093.7  476.00  5113.7  477.84
  5265.0  478.80  5942.0  482.60  5969.6  484.80  6019.7  485.74  6111.4  489.11
  6256.6  496.13  6278.1  494.54  6283.9  496.57  6358.2  499.38  6438.4  500.02
  6524.9  504.37  6592.8  507.05  6651.4  505.90  6657.2  504.26  6665.1  504.47
#Mann=9,-1,0
  4289.7    0.05       0  4826.9    0.16       0  5020.8    0.12       0
  5051.8    0.07       0  5061.3    0.12       0  5113.7    0.16       0
  5265.0    0.05       0  6019.7    0.16       0  6524.9    0.05       0
Bank Sta=4497.3,6111.4
Exp/Cntr=0.3,0.1

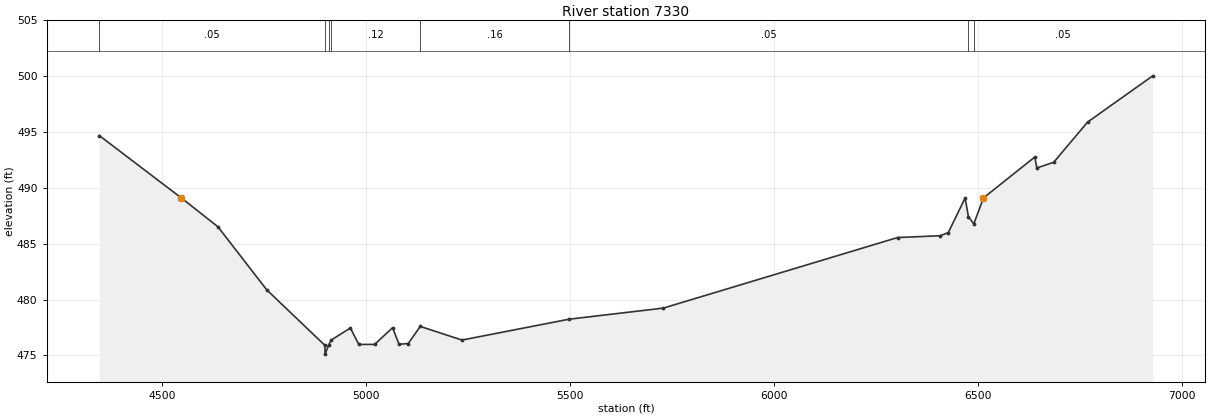
Type RM Length L Ch R = 1,7330,1049,1049,1049
BEGIN DESCRIPTION:
LAKE FORK CREEK TRIB 1 9.0
END DESCRIPTION:
XS GIS Cut Line= 4
      2768974.99      7048624.96      2768825.00      7047975.00
      2768559.42      7047475.09      2767248.61      7047150.60
#Sta/Elev= 30
  4345.3  494.69  4546.2  489.11  4636.0  486.53  4755.8  480.88  4898.1  475.92
  4899.0  475.12  4907.6  475.92  4913.5  476.37  4961.0  477.46  4981.6  475.99
  5020.5  475.99  5064.5  477.49  5080.3  476.00  5102.8  476.07  5132.4  477.60
  5234.6  476.38  5497.8  478.25  5728.4  479.24  6303.0  485.56  6407.1  485.72
  6427.2  485.99  6468.7  489.10  6476.7  487.43  6489.9  486.78  6513.7  489.11
  6639.5  492.77  6644.6  491.79  6686.0  492.30  6768.8  495.89  6928.8  500.04
#Mann=8,-1,0
  4345.3    0.05       0  4898.1    0.07       0  4907.6    0.05       0
  4913.5    0.12       0  5132.4    0.16       0  5497.8    0.05       0
  6476.7    0.16       0  6489.9    0.05       0
Bank Sta=4546.2,6513.7
Exp/Cntr=0.3,0.1