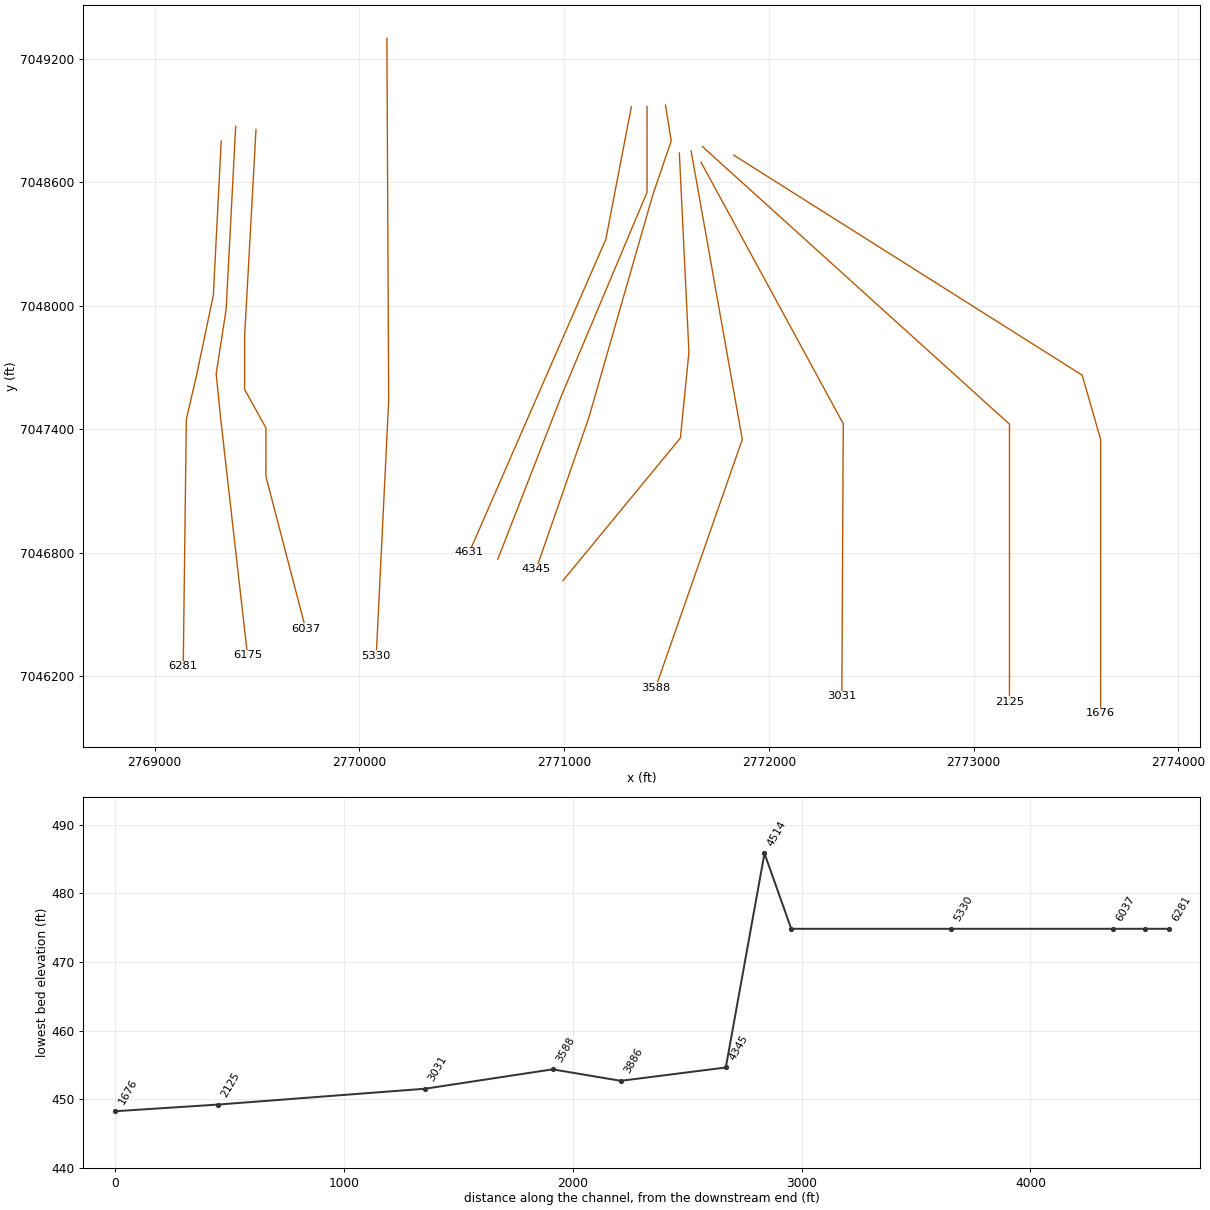
HEC-RAS study LAKE FORK CREEK TRIB 1.prj: LAKE FORK CREEK TRIB 1 Base Level Engineering

--- LAKE FORK CREEK TRIB 1.g01 (geometry) --- (continued)

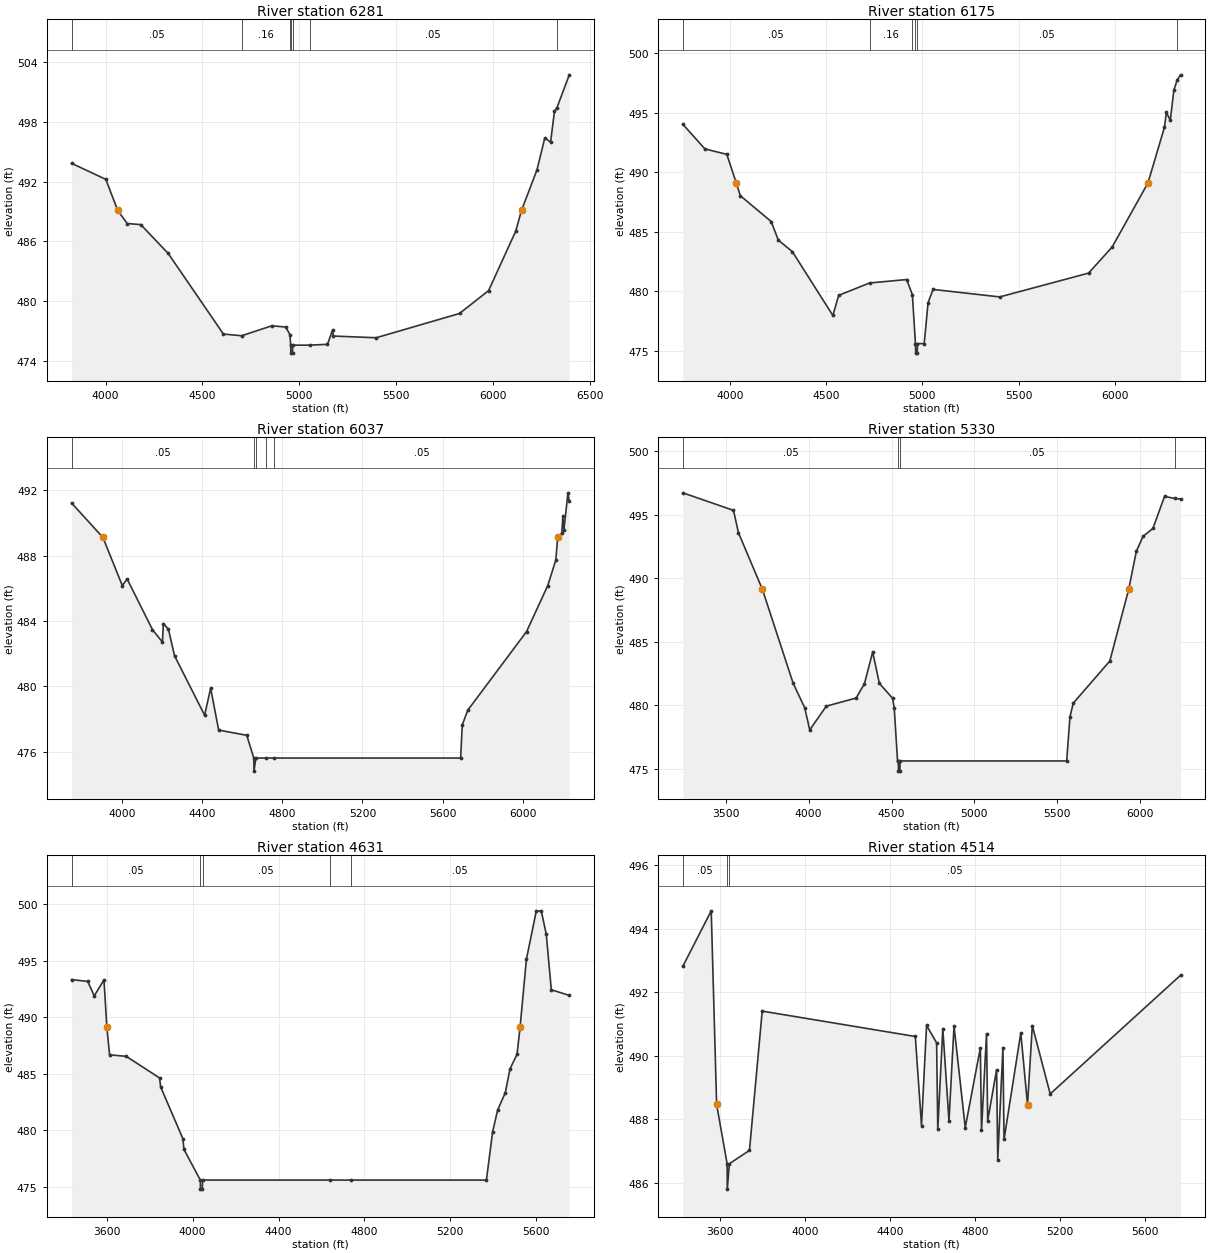
Type RM Length L Ch R = 1,6281,106,106,106
BEGIN DESCRIPTION:
Mapping XS b9e3f4a0
END DESCRIPTION:
XS GIS Cut Line= 5
      2769325.42      7048801.69      2769286.90      7048052.17
      2769203.57      7047656.34      2769154.96      7047448.01
      2769139.88      7046248.65
#Sta/Elev= 30
  3824.7  493.83  4001.6  492.22  4062.9  489.11  4111.8  487.80  4181.9  487.69
  4323.5  484.80  4608.4  476.73  4702.3  476.56  4858.5  477.56  4930.0  477.43
  4951.7  476.67  4955.5  475.62  4956.4  474.82  4964.9  474.82  4965.8  475.62
  5052.6  475.62  5145.4  475.70  5171.3  477.13  5176.4  476.53  5396.7  476.36
  5826.7  478.79  5976.7  481.08  6116.7  487.03  6146.6  489.11  6226.7  493.18
  6266.7  496.37  6296.7  495.95  6316.7  499.04  6329.2  499.38  6393.1  502.69
#Mann=7,-1,0
  3824.7    0.05       0  4702.3    0.16       0  4951.7    0.07       0
  4955.5    0.07       0  4965.8    0.07       0  5052.6    0.05       0
  6329.2    0.16       0
Bank Sta=4062.9,6146.6
Exp/Cntr=0.3,0.1

Type RM Length L Ch R = 1,6175,138,138,138
BEGIN DESCRIPTION:
Mapping XS 378769fa
END DESCRIPTION:
XS GIS Cut Line= 5
      2769396.06      7048873.25      2769349.40      7047982.73
      2769300.79      7047670.23      2769321.62      7047461.90
      2769453.57      7046302.15
#Sta/Elev= 30
  3756.2  494.04  3870.9  491.97  3984.8  491.51  4033.8  489.11  4054.9  488.04
  4215.1  485.87  4252.2  484.31  4325.2  483.34  4535.5  477.98  4565.6  479.67
  4725.7  480.71  4918.9  481.00  4948.3  479.72  4964.3  475.62  4965.2  474.82
  4973.7  474.82  4974.6  475.62  5009.7  475.62  5029.8  479.06  5055.8  480.17
  5401.9  479.54  5863.4  481.54  5985.7  483.73  6171.6  489.11  6257.4  493.79
  6267.5  495.05  6287.6  494.36  6306.0  496.88  6322.9  497.74  6340.8  498.19
#Mann=6,-1,0
  3756.2    0.05       0  4725.7    0.16       0  4948.3    0.05       0
  4964.3    0.03       0  4974.6    0.05       0  6322.9    0.16       0
Bank Sta=4033.8,6171.6
Exp/Cntr=0.3,0.1

Type RM Length L Ch R = 1,6037,707,707,707
BEGIN DESCRIPTION:
Mapping XS 85954eb2
END DESCRIPTION:
XS GIS Cut Line= 6
      2769495.23      7048857.72      2769439.68      7047850.79
      2769439.68      7047593.84      2769543.84      7047406.34
      2769543.84      7047170.23      2769737.91      7046428.62
#Sta/Elev= 30
  3749.2  491.22  3905.7  489.11  4002.3  486.17  4026.5  486.57  4152.5  483.48
  4202.4  482.71  4207.4  483.84  4232.7  483.49  4262.7  481.88  4412.9  478.24
  4443.0  479.89  4483.0  477.33  4623.3  477.01  4658.2  475.62  4659.1  474.82
  4668.5  475.62  4720.7  475.62  4756.6  475.62  5690.0  475.62  5698.0  477.64
  5725.2  478.54  6018.5  483.35  6124.3  486.16  6164.7  487.73  6173.8  489.11
  6194.2  489.36  6200.0  490.40  6205.1  489.58  6225.2  491.84  6231.8  491.31
#Mann=5,-1,0
  3749.2    0.05       0  4658.2   0.033       0  4668.5    0.05       0
  4720.7    0.16       0  4756.6    0.05       0
Bank Sta=3905.7,6173.8
Exp/Cntr=0.3,0.1

Type RM Length L Ch R = 1,5330,699,699,699
BEGIN DESCRIPTION:
Mapping XS 6cf3ffd7
END DESCRIPTION:
XS GIS Cut Line= 3
      2770134.53      7049300.86      2770143.21      7047538.74
      2770082.51      7046298.67
#Sta/Elev= 30
  3240.4  496.71  3546.3  495.33  3576.3  493.57  3720.9  489.11  3906.3  481.73
  3976.3  479.80  4006.3  478.06  4106.3  479.93  4286.3  480.57  4336.3  481.69
  4386.3  484.19  4426.3  481.73  4506.3  480.55  4516.3  479.79  4536.3  475.63
  4541.1  475.62  4542.0  474.82  4550.6  474.82  4551.5  475.62  5556.9  475.62
  5577.0  479.10  5597.0  480.17  5817.3  483.48  5931.1  489.11  5977.4  492.11
  6017.5  493.28  6077.6  493.91  6147.7  496.43  6207.8  496.27  6244.1  496.22
#Mann=4,-1,0
  3240.4    0.05       0  4541.1   0.033       0  4551.5    0.05       0
  6207.8    0.16       0
Bank Sta=3720.9,5931.1
Exp/Cntr=0.3,0.1

Type RM Length L Ch R = 1,4631,117,117,117
BEGIN DESCRIPTION:
Mapping XS 6c745db0
END DESCRIPTION:
XS GIS Cut Line= 3
      2771328.57      7048968.88      2771203.57      7048323.01
      2770536.90      7046802.17
#Sta/Elev= 30
  3435.9  493.33  3511.2  493.16  3541.7  491.89  3586.9  493.30  3600.4  489.11
  3613.0  486.68  3690.5  486.55  3845.8  484.64  3850.9  483.85  3954.4  479.28
  3959.5  478.33  4035.6  475.62  4036.5  474.82  4045.2  474.82  4046.0  475.62
  4639.0  475.62  4737.5  475.62  5368.3  475.62  5397.1  479.86  5420.5  481.80
  5456.4  483.34  5478.2  485.44  5511.0  486.73  5525.1  489.11  5554.7  495.13
  5600.5  499.37  5623.8  499.40  5647.2  497.33  5670.6  492.43  5754.3  491.93
#Mann=5,-1,0
  3435.9    0.05       0  4035.6   0.033       0  4046.0    0.05       0
  4639.0    0.07       0  4737.5    0.05       0
Bank Sta=3600.4,5525.1
Exp/Cntr=0.3,0.1

Type RM Length L Ch R = 1,4514,169,169,169
BEGIN DESCRIPTION:
Mapping XS 1030dae6
END DESCRIPTION:
XS GIS Cut Line= 4
      2771404.96      7048968.81      2771404.96      7048552.17
      2770988.29      7047566.06      2770676.28      7046768.70
#Sta/Elev= 30
  3425.7  492.82  3559.5  494.57  3584.9  488.47  3634.3  486.60  3635.2  485.80
  3644.7  486.60  3739.5  487.02  3799.5  491.41  4520.4  490.61  4549.6  487.80
  4573.3  490.96  4620.7  490.41  4626.1  487.68  4649.8  490.86  4678.9  487.95
  4702.6  490.94  4755.5  487.74  4826.6  490.25  4832.0  487.65  4855.7  490.70
  4861.1  487.96  4903.1  489.56  4908.5  486.73  4932.9  490.26  4938.2  487.37
  5017.0  490.72  5048.7  488.46  5071.3  490.95  5155.4  488.80  5769.1  492.54
#Mann=3,-1,0
  3425.7    0.05       0  3634.3    0.03       0  3644.7    0.05       0
Bank Sta=3584.9,5048.7
Exp/Cntr=0.3,0.1

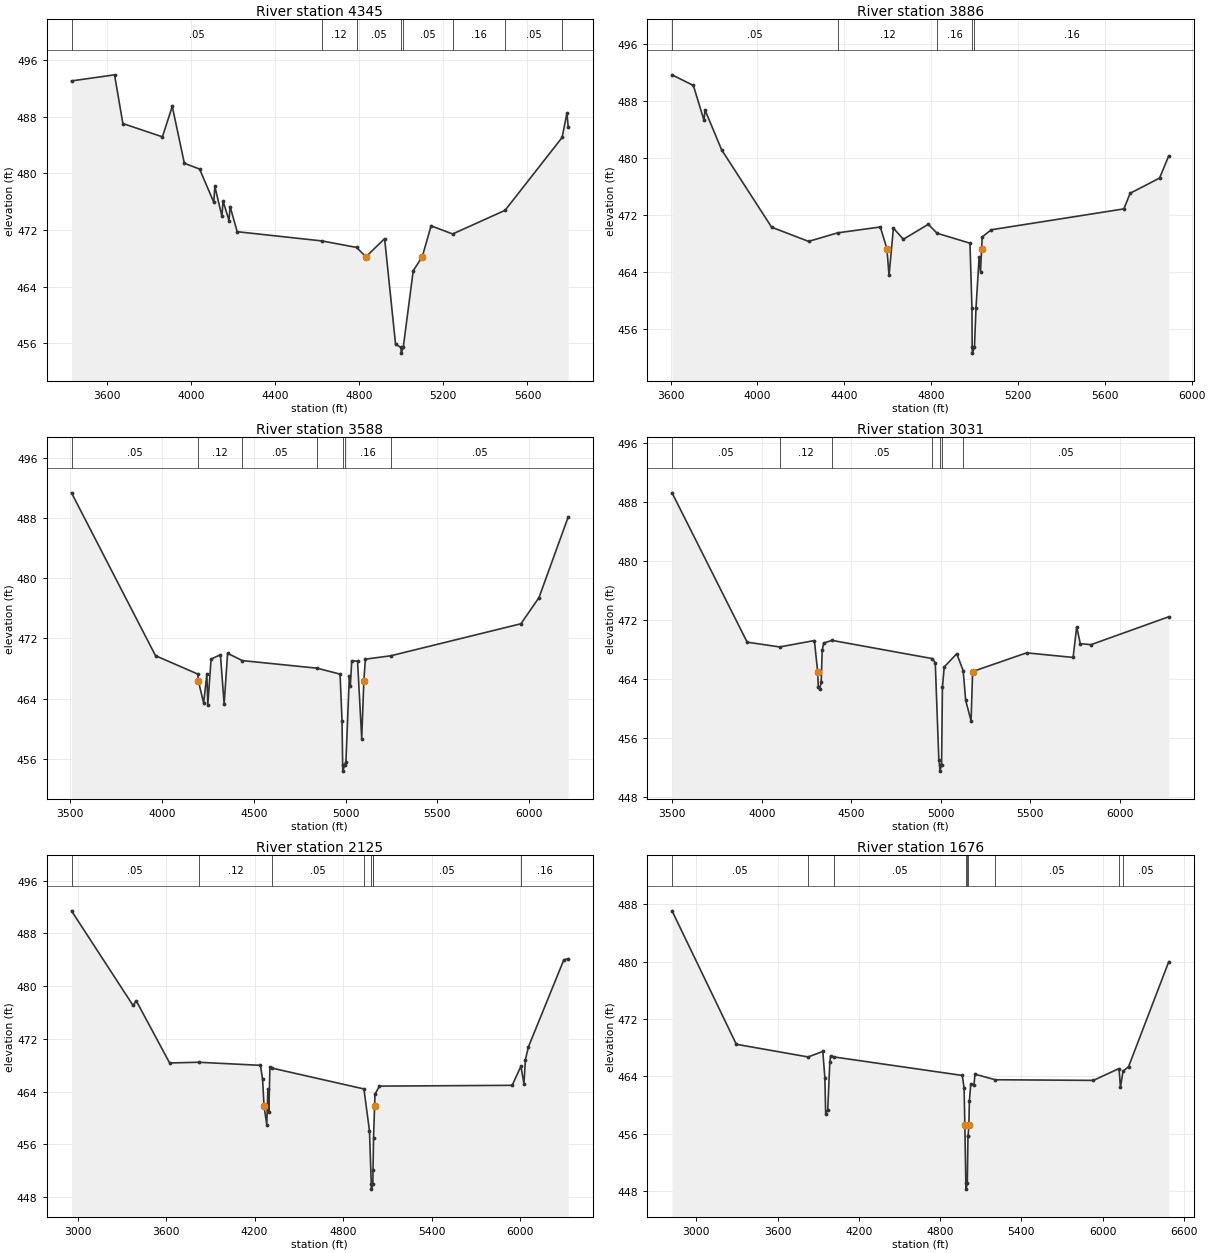
Type RM Length L Ch R = 1,4345,459,459,459
BEGIN DESCRIPTION:
Mapping XS ac026c42
END DESCRIPTION:
XS GIS Cut Line= 5
      2771495.23      7048975.83      2771523.01      7048802.17
      2771432.73      7048538.29      2771120.23      7047454.95
      2770863.50      7046719.44
#Sta/Elev= 30
  3432.4  493.07  3637.0  493.93  3676.7  487.05  3864.5  485.17  3911.4  489.47
  3968.9  481.44  4041.4  480.62  4108.7  475.94  4113.9  478.17  4147.6  473.96
  4152.8  476.11  4181.2  473.35  4186.4  475.33  4220.1  471.77  4622.6  470.47
  4787.6  469.55  4832.1  468.23  4921.0  470.79  4973.0  455.87  4999.0  455.42
  4999.9  454.62  5009.5  455.42  5057.0  466.26  5099.9  468.23  5141.9  472.60
  5244.3  471.45  5493.6  474.79  5764.8  485.08  5787.8  488.55  5793.7  486.60
#Mann=8,-1,0
  3432.4    0.05       0  4622.6    0.12       0  4787.6    0.05       0
  4999.0    0.03       0  5009.5    0.05       0  5244.3    0.16       0
  5493.6    0.05       0  5764.8    0.16       0
Bank Sta=4832.1,5099.9
Exp/Cntr=0.3,0.1

Type RM Length L Ch R = 1,3886,298,298,298
BEGIN DESCRIPTION:
Mapping XS e21adc45
END DESCRIPTION:
XS GIS Cut Line= 4
      2771562.73      7048743.13      2771609.61      7047774.33
      2771567.94      7047357.67      2770995.03      7046664.96
#Sta/Elev= 30
  3606.8  491.71  3705.0  490.22  3753.7  485.36  3758.7  486.78  3835.2  481.19
  4065.5  470.34  4235.7  468.35  4370.0  469.55  4566.0  470.37  4596.4  467.33
  4606.2  463.57  4626.3  470.21  4672.4  468.65  4787.1  470.75  4827.7  469.49
  4978.9  468.10  4988.1  458.94  4989.1  453.48  4990.0  452.68  4999.6  453.48
  5006.7  459.01  5021.0  466.10  5027.5  464.11  5032.7  467.33  5035.3  468.98
  5077.0  469.98  5687.9  472.91  5716.6  475.10  5852.1  477.23  5894.4  480.35
#Mann=5,-1,0
  3606.8    0.05       0  4370.0    0.12       0  4827.7    0.16       0
  4989.1    0.07       0  4999.6    0.16       0
Bank Sta=4596.4,5032.7
Exp/Cntr=0.3,0.1

Type RM Length L Ch R = 1,3588,557,557,557
BEGIN DESCRIPTION:
Mapping XS 4a20c8e4
END DESCRIPTION:
XS GIS Cut Line= 3
      2771620.24      7048753.54      2771870.23      7047350.79
      2771446.62      7046142.44
#Sta/Elev= 30
  3507.1  491.36  3964.7  469.70  4194.8  467.26  4198.2  466.32  4226.8  463.42
  4244.4  467.22  4249.4  463.16  4267.4  469.25  4318.2  469.83  4338.5  463.27
  4357.2  470.02  4437.5  469.05  4844.5  468.04  4969.9  467.25  4980.5  461.07
  4984.1  455.15  4985.0  454.35  4994.7  455.15  5001.7  455.59  5020.5  466.98
  5025.7  465.70  5033.5  469.03  5065.2  468.97  5087.8  458.67  5099.4  466.32
  5107.6  469.24  5246.1  469.69  5955.2  473.95  6053.5  477.44  6212.4  488.15
#Mann=7,-1,0
  3507.1    0.05       0  4194.8    0.12       0  4437.5    0.05       0
  4844.5    0.16       0  4984.1    0.07       0  4994.7    0.16       0
  5246.1    0.05       0
Bank Sta=4198.2,5099.4
Exp/Cntr=0.3,0.1

Type RM Length L Ch R = 1,3031,906,906,906
BEGIN DESCRIPTION:
Mapping XS 7645dc55
END DESCRIPTION:
XS GIS Cut Line= 3
      2771668.83      7048698.03      2772363.29      7047427.17
      2772356.34      7046100.81
#Sta/Elev= 30
  3498.6  489.25  3918.1  469.01  4100.0  468.36  4293.8  469.23  4311.9  465.03
  4315.6  462.90  4322.5  462.65  4331.7  463.55  4337.4  467.89  4345.3  468.89
  4392.3  469.25  4952.6  466.78  4969.0  466.20  4989.0  453.04  4993.7  452.33
  4994.5  451.53  5004.3  452.33  5009.0  462.89  5019.0  465.65  5089.0  467.44
  5124.9  465.16  5139.0  461.12  5169.0  458.34  5177.7  465.03  5479.0  467.56
  5739.0  466.94  5759.0  471.10  5779.0  468.81  5839.0  468.67  6273.2  472.45
#Mann=7,-1,0
  3498.6    0.05       0  4100.0    0.12       0  4392.3    0.05       0
  4952.6    0.16       0  4993.7    0.07       0  5004.3    0.16       0
  5124.9    0.05       0
Bank Sta=4311.9,5177.7
Exp/Cntr=0.3,0.1

Type RM Length L Ch R = 1,2125,449,449,449
BEGIN DESCRIPTION:
LAKE FORK CREEK TRIB 1 2.0
END DESCRIPTION:
XS GIS Cut Line= 3
      2771675.03      7048774.98      2773175.00      7047425.00
      2773175.00      7046075.01
#Sta/Elev= 30
  2958.7  491.42  3376.1  477.07  3397.8  477.78  3624.2  468.35  3819.9  468.46
  4240.1  467.99  4254.3  465.90  4264.3  461.82  4282.7  459.01  4290.2  464.34
  4296.9  460.88  4304.0  467.70  4320.5  467.56  4941.6  464.41  4979.2  458.07
  4991.4  450.02  4992.3  449.22  5002.0  450.02  5003.4  452.09  5006.7  456.98
  5014.0  461.82  5016.7  463.61  5046.7  464.84  5946.7  464.96  6006.0  467.84
  6026.7  465.23  6036.7  468.87  6056.7  470.77  6296.7  483.97  6326.7  484.17
#Mann=8,-1,0
  2958.7    0.05       0  3819.9    0.12       0  4320.5    0.05       0
  4941.6    0.16       0  4991.4    0.07       0  5002.0    0.16       0
  5003.4    0.05       0  6006.0    0.16       0
Bank Sta=4264.3,5014
Exp/Cntr=0.3,0.1

Type RM Length L Ch R = 1,1676,0,0,0
BEGIN DESCRIPTION:
Mapping XS bfa8153a
END DESCRIPTION:
XS GIS Cut Line= 4
      2771828.54      7048732.75      2773529.96      7047663.29
      2773620.23      7047350.79      2773620.23      7046018.68
#Sta/Elev= 30
  2821.4  487.10  3296.0  468.47  3826.5  466.70  3934.3  467.47  3949.6  463.83
  3955.5  458.80  3970.8  459.31  3986.1  465.93  3992.0  466.87  4017.8  466.70
  4964.5  464.12  4977.7  462.33  4983.1  457.19  4990.4  449.05  4991.3  448.25
  5001.1  449.05  5006.2  455.64  5007.4  455.73  5012.7  457.19  5016.6  460.57
  5027.0  462.97  5050.2  462.80  5058.2  464.29  5207.9  463.52  5932.1  463.43
  6121.4  465.08  6132.1  462.47  6150.8  464.71  6192.1  465.36  6488.4  479.99
#Mann=9,-1,0
  2821.4    0.05       0  3826.5    0.12       0  4017.8    0.05       0
  4990.4    0.03       0  5001.1    0.05       0  5007.4    0.16       0
  5207.9    0.05       0  6121.4    0.16       0  6150.8    0.05       0
Bank Sta=4983.1,5012.7
Exp/Cntr=0.3,0.1

Chan Stop Cuts=-1