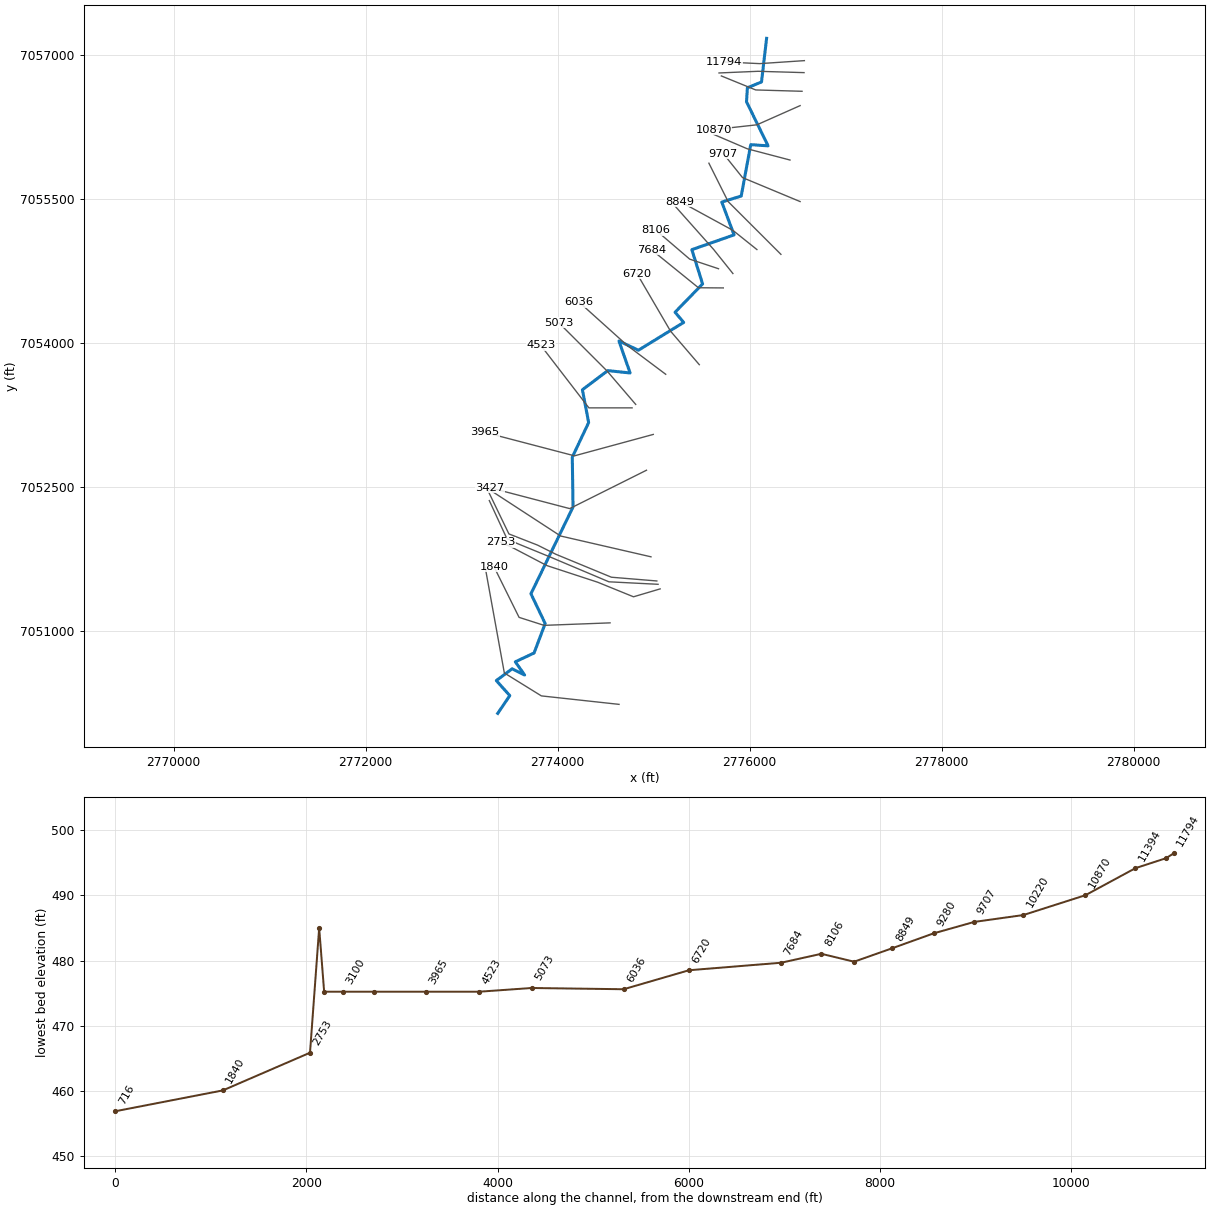
--- LAKE FORK CREEK TRIB 2.prj (project) ---

Proj Title=LAKE FORK CREEK TRIB 2 Base Level Engineering
Current Plan=p01
Default Exp/Contr=0.3,0.1
English Units
Geom File=g01
Flow File=f01
Plan File=p01
BEGIN DESCRIPTION:
LAKE FORK CREEK TRIB 2
END DESCRIPTION:

--- LAKE FORK CREEK TRIB 2.p01 (plan) ---

Plan Title=Multiple Run
Short Identifier=Multiple
Geom File=g01
Flow File=f01
Subcritical Flow
K Sum by GR= 0
Std Step Tol= 0.01
Critical Tol= 0.01
Num of Std Step Trials= 20
Max Error Tol= 0.3
Flow Tol Ratio= 0.001
Split Flow NTrial= 30
Split Flow Tol= 0.02
Split Flow Ratio= 0.02
Log Output Level= 0
Friction Slope Method= 1
Unsteady Friction Slope Method= 2
Unsteady Bridges Friction Slope Method= 1
Parabolic Critical Depth
Global Vel Dist=  1 , 1 , 1
Global Log Level= 0
CheckData=True
Encroach Param= -1, 0, 0, 0
BEGIN DESCRIPTION:
Multiple Run
END DESCRIPTION:

--- LAKE FORK CREEK TRIB 2.f01 (steady flow) ---

Flow Title=Multiple
Number of Profiles=7
Profile Names=10-year,25-year,50-year,1pct_min,100-year,1pct_plu,500-year
River Rch & RM= LAKE FORK CREEK ,Reach-1,11794
     292     370     430     248     496     989     657
River Rch & RM= LAKE FORK CREEK ,Reach-1,10870
     701     941    1135     680    1356    2706    1933
River Rch & RM= LAKE FORK CREEK ,Reach-1,6720
     736     989    1194     715    1427    2847    2036
River Rch & RM= LAKE FORK CREEK ,Reach-1,2901
     883    1203    1466     886    1767    3526    2571
Boundary for River Rch & Prof#=LAKE FORK CREEK ,Reach-1,1
Up Type=0
Dn Type=3
Dn Slope=0.005
Boundary for River Rch & Prof#=LAKE FORK CREEK ,Reach-1,2
Up Type=0
Dn Type=3
Dn Slope=0.005
Boundary for River Rch & Prof#=LAKE FORK CREEK ,Reach-1,3
Up Type=0
Dn Type=3
Dn Slope=0.005
Boundary for River Rch & Prof#=LAKE FORK CREEK ,Reach-1,4
Up Type=0
Dn Type=3
Dn Slope=0.005
Boundary for River Rch & Prof#=LAKE FORK CREEK ,Reach-1,5
Up Type=0
Dn Type=3
Dn Slope=0.005
Boundary for River Rch & Prof#=LAKE FORK CREEK ,Reach-1,6
Up Type=0
Dn Type=3
Dn Slope=0.005
Boundary for River Rch & Prof#=LAKE FORK CREEK ,Reach-1,7
Up Type=0
Dn Type=3
Dn Slope=0.005

--- LAKE FORK CREEK TRIB 2.g01 (geometry) ---

Geom Title=Existing Conditions

River Reach=LAKE FORK CREEK ,Reach-1
Reach XY= 30
      2776175.94      7057176.30      2776122.88      7056721.72
      2775975.66      7056660.55      2775966.57      7056515.88
      2776191.16      7056056.02      2776010.69      7056067.98
      2775911.62      7055532.79      2775709.11      7055469.82
      2775836.93      7055127.68      2775397.46      7054973.82
      2775509.27      7054616.27      2775222.56      7054321.81
      2775312.23      7054215.54      2774840.66      7053925.52
      2774638.08      7054021.82      2774754.32      7053688.63
      2774521.85      7053712.98      2774257.29      7053513.73
      2774322.60      7053171.67      2774152.13      7052810.80
      2774159.88      7052291.64      2773721.52      7051387.24
      2773869.70      7051077.22      2773754.22      7050770.01
      2773558.79      7050678.23      2773655.63      7050540.63
      2773525.35      7050605.12      2773360.95      7050482.65
      2773501.16      7050325.92      2773375.59      7050140.71

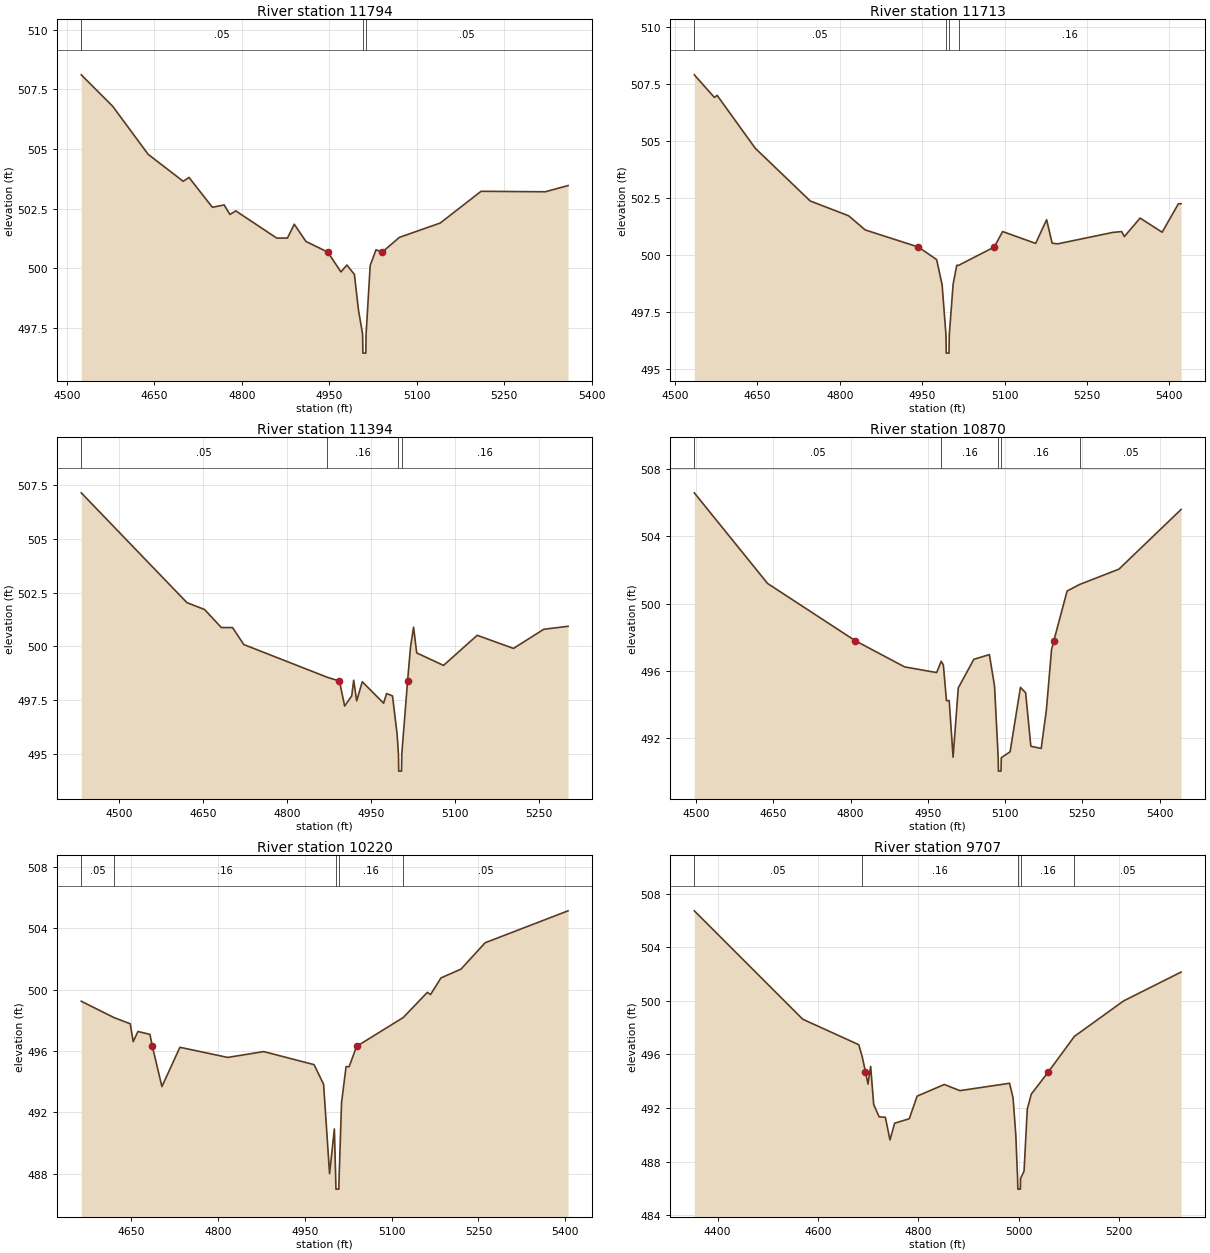
Type RM Length L Ch R = 1,11794,81,81,81
BEGIN DESCRIPTION:
LAKE FORK CREEK TRIB 2 18.0
END DESCRIPTION:
XS GIS Cut Line= 3
      2776569.43      7056943.92      2776104.13      7056912.67
      2775736.09      7056930.03
#Sta/Elev= 30
  4524.5  508.11  4578.5  506.79  4639.2  504.78  4699.3  503.65  4709.3  503.81
  4749.4  502.56  4769.5  502.66  4779.5  502.26  4789.5  502.41  4859.7  501.27
  4878.1  501.27  4889.8  501.85  4909.8  501.13  4947.4  500.68  4969.9  499.85
  4980.0  500.14  4992.9  499.75  5000.0  498.24  5007.0  497.25  5007.5  496.45
  5012.5  496.45  5013.0  497.25  5020.0  500.12  5030.0  500.78  5040.5  500.68
  5070.1  501.30  5140.1  501.90  5210.2  503.23  5320.3  503.21  5359.3  503.47
#Mann=3,-1,0
  4524.5    0.05       0  5007.0    0.04       0  5013.0    0.05       0
Bank Sta=4947.4,5040.5
Exp/Cntr=0.3,0.1

Type RM Length L Ch R = 1,11713,319,319,319
BEGIN DESCRIPTION:
Mapping XS 0c814406
END DESCRIPTION:
XS GIS Cut Line= 3
      2776565.93      7056818.92      2776086.77      7056832.81
      2775680.50      7056815.44
#Sta/Elev= 30
  4535.2  507.91  4571.8  506.92  4576.8  507.01  4646.2  504.69  4746.2  502.38
  4816.2  501.73  4846.3  501.11  4943.2  500.36  4976.3  499.81  4986.3  498.70
  4993.3  496.51  4993.8  495.71  4998.8  495.71  4999.3  496.51  5006.3  498.73
  5012.9  499.56  5016.4  499.56  5081.1  500.36  5096.4  501.04  5156.5  500.52
  5176.5  501.56  5186.5  500.53  5196.5  500.50  5296.6  501.00  5313.0  501.04
  5318.0  500.82  5346.6  501.63  5386.7  501.01  5416.4  502.26  5421.2  502.26
#Mann=4,-1,0
  4535.2    0.05       0  4993.3    0.03       0  4999.3    0.05       0
  5016.4    0.16       0
Bank Sta=4943.2,5081.1
Exp/Cntr=0.3,0.1

Type RM Length L Ch R = 1,11394,524,524,524
BEGIN DESCRIPTION:
Mapping XS 84b72b79
END DESCRIPTION:
XS GIS Cut Line= 3
      2776545.12      7056624.47      2776062.47      7056638.36
      2775704.81      7056784.20
#Sta/Elev= 30
  4432.6  507.14  4621.3  502.03  4652.8  501.71  4682.8  500.87  4702.8  500.87
  4722.8  500.08  4871.6  498.56  4893.5  498.38  4902.9  497.22  4915.5  497.69
  4919.0  498.42  4924.4  497.46  4934.3  498.35  4972.4  497.35  4977.8  497.80
  4988.3  497.69  4996.5  495.92  4998.9  494.99  4999.4  494.19  5004.4  494.19
  5004.9  494.99  5015.2  498.38  5020.5  499.97  5025.9  500.89  5031.5  499.69
  5079.4  499.11  5139.5  500.51  5204.3  499.90  5258.3  500.79  5301.7  500.93
#Mann=4,-1,0
  4432.6    0.05       0  4871.6    0.16       0  4998.9    0.07       0
  5004.9    0.16       0
Bank Sta=4893.5,5015.2
Exp/Cntr=0.3,0.1

Type RM Length L Ch R = 1,10870,650,650,650
BEGIN DESCRIPTION:
LAKE FORK CREEK TRIB 2 16.0
END DESCRIPTION:
XS GIS Cut Line= 3
      2776525.03      7056475.01      2776075.00      7056275.00
      2775625.04      7056225.00
#Sta/Elev= 30
  4496.6  506.59  4638.9  501.20  4808.9  497.80  4904.9  496.24  4967.2  495.90
  4976.0  496.57  4980.2  496.36  4986.3  494.23  4991.6  494.23  4999.1  490.87
  5009.2  494.99  5039.4  496.69  5069.6  496.97  5079.6  495.10  5086.7  490.84
  5087.2  490.04  5092.2  490.04  5092.7  490.84  5109.8  491.19  5129.9  495.02
  5140.0  494.70  5150.1  491.52  5170.2  491.39  5180.2  493.66  5190.3  497.27
  5194.8  497.80  5220.5  500.75  5244.7  501.14  5321.1  502.05  5441.8  505.60
#Mann=5,-1,0
  4496.6    0.05       0  4976.0    0.16       0  5086.7    0.07       0
  5092.7    0.16       0  5244.7    0.05       0
Bank Sta=4808.9,5194.8
Exp/Cntr=0.3,0.1

Type RM Length L Ch R = 1,10220,513,513,513
BEGIN DESCRIPTION:
LAKE FORK CREEK TRIB 2 15.0
END DESCRIPTION:
XS GIS Cut Line= 3
      2776419.71      7055907.93      2775975.00      7056025.00
      2775625.04      7056174.98
#Sta/Elev= 30
  4564.1  499.24  4620.4  498.18  4648.7  497.77  4653.8  496.61  4662.0  497.27
  4682.7  497.08  4686.9  496.30  4703.4  493.68  4734.5  496.24  4817.1  495.58
  4879.2  495.96  4966.1  495.11  4982.6  493.83  4992.9  488.01  5001.2  490.92
  5003.4  487.80  5003.9  487.00  5008.9  487.00  5009.4  487.80  5013.6  492.64
  5021.4  494.98  5026.7  494.98  5039.6  496.30  5120.2  498.18  5161.8  499.82
  5167.2  499.67  5185.3  500.76  5219.8  501.33  5261.5  503.05  5404.7  505.13
#Mann=5,-1,0
  4564.1    0.05       0  4620.4    0.16       0  5003.4    0.07       0
  5009.4    0.16       0  5120.2    0.05       0
Bank Sta=4686.9,5039.6
Exp/Cntr=0.3,0.1

Type RM Length L Ch R = 1,9707,427,427,427
BEGIN DESCRIPTION:
LAKE FORK CREEK TRIB 2 14.0
END DESCRIPTION:
XS GIS Cut Line= 3
      2776524.97      7055475.01      2775925.00      7055725.00
      2775725.02      7055974.98
#Sta/Elev= 30
  4353.5  506.72  4569.6  498.63  4681.2  496.73  4688.3  495.82  4694.6  494.71
  4699.6  493.79  4705.0  495.11  4711.0  492.27  4721.8  491.35  4734.3  491.31
  4743.5  489.62  4752.7  490.87  4781.9  491.20  4797.6  492.89  4851.8  493.76
  4882.7  493.30  4981.8  493.85  4988.8  492.76  4994.3  489.95  4997.8  486.75
  4998.3  485.95  5003.3  485.95  5003.8  486.75  5010.7  487.30  5017.1  491.92
  5025.1  493.04  5059.3  494.71  5111.0  497.35  5209.2  500.00  5323.6  502.15
#Mann=5,-1,0
  4353.5    0.05       0  4688.3    0.16       0  4997.8    0.07       0
  5003.8    0.16       0  5111.0    0.05       0
Bank Sta=4694.6,5059.3
Exp/Cntr=0.3,0.1

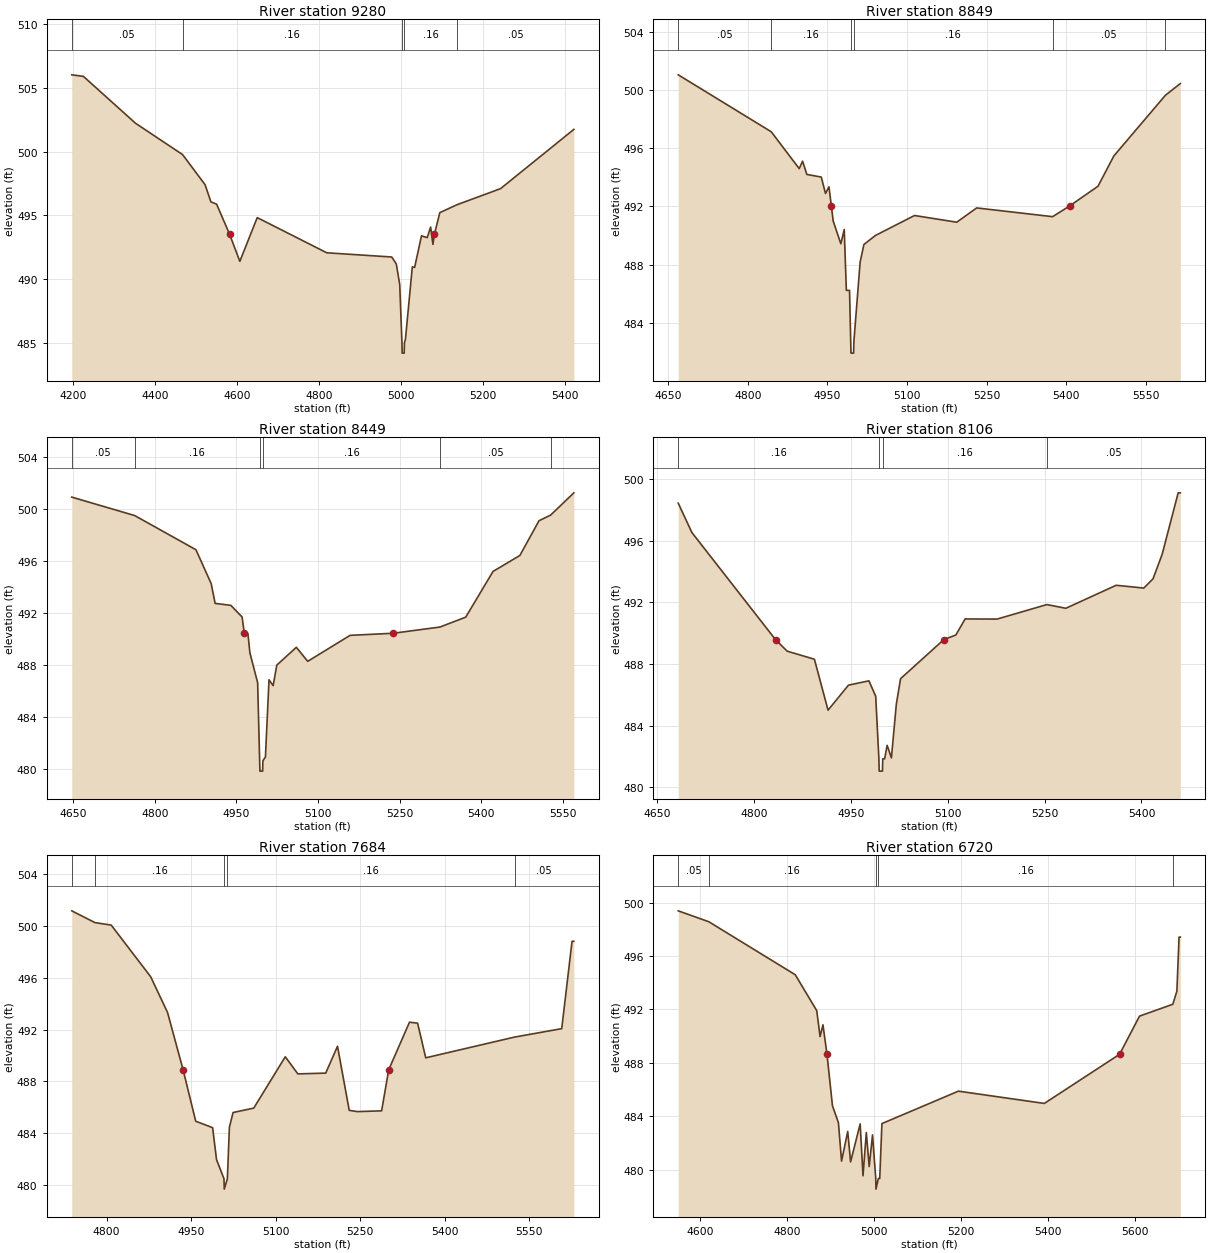
Type RM Length L Ch R = 1,9280,431,431,431
BEGIN DESCRIPTION:
LAKE FORK CREEK TRIB 2 13.0
END DESCRIPTION:
XS GIS Cut Line= 3
      2776324.99      7054925.01      2775775.00      7055475.00
      2775575.01      7055874.98
#Sta/Elev= 30
  4196.7  506.02  4225.0  505.90  4352.3  502.22  4467.2  499.76  4522.0  497.40
  4536.1  496.06  4550.2  495.87  4581.7  493.52  4606.8  491.39  4649.2  494.82
  4818.9  492.06  4977.3  491.73  4988.5  491.19  4996.9  489.56  5002.3  484.99
  5002.8  484.19  5007.8  484.19  5008.3  484.99  5010.8  485.28  5027.6  490.96
  5033.2  490.91  5050.0  493.39  5063.9  493.25  5072.3  494.08  5077.9  492.72
  5081.6  493.52  5094.7  495.21  5137.4  495.84  5242.8  497.09  5421.7  501.74
#Mann=5,-1,0
  4196.7    0.05       0  4467.2    0.16       0  5002.3    0.07       0
  5008.3    0.16       0  5137.4    0.05       0
Bank Sta=4581.7,5081.6
Exp/Cntr=0.3,0.1

Type RM Length L Ch R = 1,8849,400,400,400
BEGIN DESCRIPTION:
LAKE FORK CREEK TRIB 2 12.0
END DESCRIPTION:
XS GIS Cut Line= 3
      2776075.01      7054974.99      2775825.00      7055175.00
      2775274.97      7055475.02
#Sta/Elev= 30
  4668.7  501.03  4844.1  497.12  4896.8  494.59  4903.2  495.10  4911.2  494.19
  4938.4  494.01  4946.4  492.88  4952.9  493.34  4957.4  492.03  4960.9  490.99
  4975.3  489.43  4981.7  490.41  4985.7  486.23  4991.7  486.23  4993.9  482.72
  4994.4  481.92  4999.4  481.92  4999.9  482.72  5011.7  488.17  5018.8  489.38
  5040.6  490.00  5114.2  491.37  5193.9  490.91  5231.4  491.89  5374.6  491.29
  5406.9  492.03  5460.2  493.38  5490.1  495.46  5587.4  499.63  5615.4  500.43
#Mann=6,-1,0
  4668.7    0.05       0  4844.1    0.16       0  4993.9    0.07       0
  4999.9    0.16       0  5374.6    0.05       0  5587.4    0.16       0
Bank Sta=4957.4,5406.9
Exp/Cntr=0.3,0.1

Type RM Length L Ch R = 1,8449,343,343,343
BEGIN DESCRIPTION:
LAKE FORK CREEK TRIB 2 11.0
END DESCRIPTION:
XS GIS Cut Line= 3
      2775824.98      7054725.03      2775625.00      7054975.00
      2775225.00      7055425.00
#Sta/Elev= 30
  4647.7  500.94  4763.3  499.52  4875.8  496.89  4903.8  494.28  4911.0  492.76
  4939.8  492.61  4960.6  491.71  4964.6  490.45  4971.2  490.45  4974.9  488.95
  4989.1  486.66  4992.8  480.65  4993.3  479.85  4998.3  479.85  4998.8  480.65
  5003.4  480.94  5010.0  486.88  5017.6  486.43  5024.3  488.01  5060.2  489.38
  5081.1  488.30  5158.9  490.30  5237.9  490.46  5324.0  490.94  5371.3  491.70
  5421.5  495.22  5470.8  496.45  5505.9  499.12  5527.4  499.56  5569.9  501.27
#Mann=6,-1,0
  4647.7    0.05       0  4763.3    0.16       0  4992.8    0.07       0
  4998.8    0.16       0  5324.0    0.05       0  5527.4    0.16       0
Bank Sta=4964.6,5237.9
Exp/Cntr=0.3,0.1

Type RM Length L Ch R = 1,8106,422,422,422
BEGIN DESCRIPTION:
LAKE FORK CREEK TRIB 2 10.0
END DESCRIPTION:
XS GIS Cut Line= 3
      2775675.02      7054774.99      2775375.00      7054875.00
      2775025.02      7055174.99
#Sta/Elev= 30
  4682.9  498.42  4704.0  496.52  4833.5  489.58  4851.6  488.83  4893.7  488.31
  4914.8  485.01  4946.4  486.63  4978.1  486.91  4988.6  485.91  4993.5  481.86
  4994.0  481.06  4999.0  481.06  4999.5  481.86  5002.4  481.86  5006.3  482.73
  5012.9  481.92  5020.5  485.40  5027.1  487.05  5094.0  489.58  5112.7  489.88
  5127.0  490.92  5176.4  490.91  5253.5  491.85  5282.9  491.61  5360.8  493.10
  5403.6  492.92  5417.9  493.52  5432.1  495.12  5456.8  499.09  5460.1  499.09
#Mann=4,-1,0
  4682.9    0.16       0  4993.5    0.07       0  4999.5    0.16       0
  5253.5    0.05       0
Bank Sta=4833.5,5094
Exp/Cntr=0.3,0.1

Type RM Length L Ch R = 1,7684,964,964,964
BEGIN DESCRIPTION:
LAKE FORK CREEK TRIB 2 9.0
END DESCRIPTION:
XS GIS Cut Line= 3
      2775725.04      7054575.00      2775466.11      7054576.73
      2774975.03      7054974.97
#Sta/Elev= 30
  4738.2  501.16  4779.4  500.25  4808.2  500.06  4878.2  496.08  4908.2  493.32
  4935.8  488.90  4958.2  484.93  4988.2  484.43  4995.2  481.96  5008.4  480.49
  5008.9  479.69  5014.4  480.49  5018.0  484.46  5024.5  485.60  5061.2  485.94
  5117.2  489.90  5139.5  488.58  5189.0  488.64  5209.9  490.71  5230.7  485.77
  5245.0  485.67  5288.2  485.73  5300.8  488.90  5337.7  492.57  5352.1  492.49
  5366.5  489.82  5524.2  491.42  5607.9  492.07  5626.2  498.81  5629.4  498.81
#Mann=5,-1,0
  4738.2    0.05       0  4779.4    0.16       0  5008.4    0.07       0
  5014.4    0.16       0  5524.2    0.05       0
Bank Sta=4935.8,5300.8
Exp/Cntr=0.3,0.1

Type RM Length L Ch R = 1,6720,684,684,684
BEGIN DESCRIPTION:
LAKE FORK CREEK TRIB 2 8.0
END DESCRIPTION:
XS GIS Cut Line= 3
      2775474.97      7053775.04      2775175.00      7054125.00
      2774824.97      7054725.04
#Sta/Elev= 30
  4549.8  499.39  4620.3  498.57  4819.2  494.60  4868.6  491.91  4876.3  489.97
  4882.9  490.85  4892.2  488.64  4904.8  484.78  4918.5  483.52  4925.7  480.64
  4939.9  482.86  4946.5  480.58  4968.5  483.43  4975.1  479.54  4982.7  482.78
  4989.3  480.23  4997.0  482.60  5004.4  479.34  5004.9  478.54  5010.5  479.34
  5013.6  479.34  5018.6  483.45  5194.7  485.88  5392.4  484.96  5565.6  488.64
  5611.5  491.50  5688.2  492.39  5697.5  493.37  5702.5  497.42  5705.4  497.42
#Mann=5,-1,0
  4549.8    0.05       0  4620.3    0.16       0  5004.4    0.07       0
  5010.5    0.16       0  5688.2    0.05       0
Bank Sta=4892.2,5565.6
Exp/Cntr=0.3,0.1

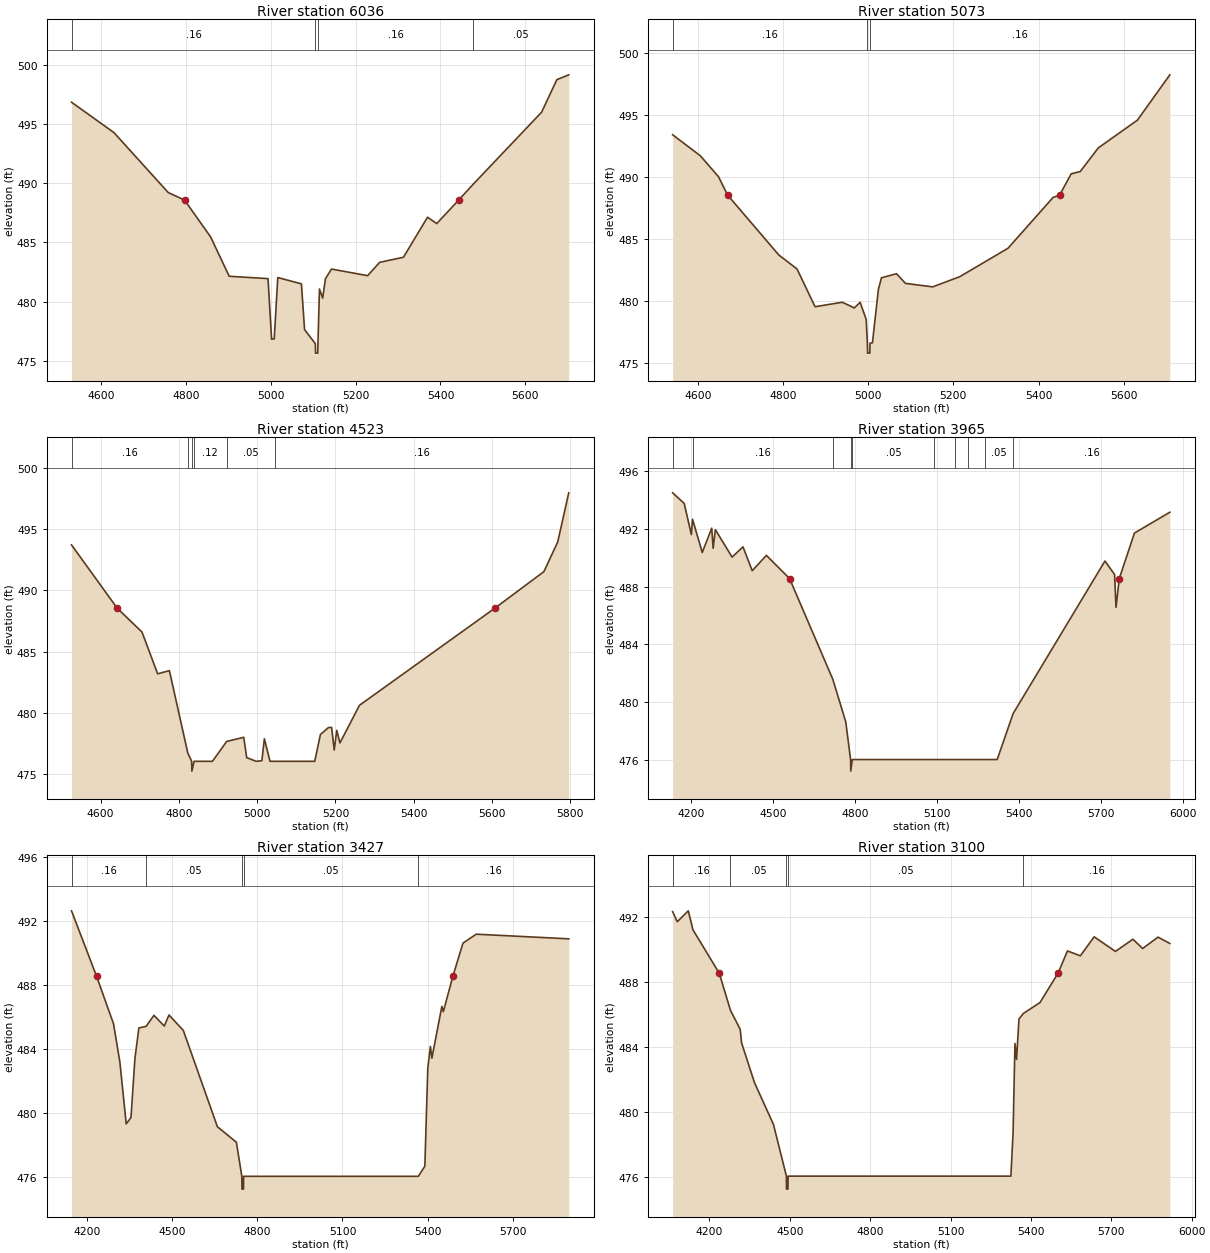
Type RM Length L Ch R = 1,6036,963,963,963
BEGIN DESCRIPTION:
LAKE FORK CREEK TRIB 2 7.0
END DESCRIPTION:
XS GIS Cut Line= 3
      2775125.00      7053675.00      2774725.00      7053975.00
      2774224.99      7054425.01
#Sta/Elev= 30
  4529.8  496.88  4629.8  494.31  4757.9  489.23  4796.4  488.59  4857.9  485.47
  4901.7  482.14  4993.3  481.94  5001.7  476.81  5007.9  476.84  5016.3  482.03
  5072.0  481.50  5079.5  477.62  5104.9  476.43  5105.4  475.63  5110.5  475.63
  5111.0  476.43  5114.6  481.06  5122.1  480.29  5128.8  481.94  5143.0  482.75
  5228.2  482.19  5256.6  483.32  5312.7  483.75  5369.5  487.14  5391.2  486.60
  5442.8  488.59  5476.6  489.91  5638.6  496.04  5674.5  498.79  5702.5  499.20
#Mann=4,-1,0
  4529.8    0.16       0  5104.9    0.07       0  5111.0    0.16       0
  5476.6    0.05       0
Bank Sta=4796.4,5442.8
Exp/Cntr=0.3,0.1

Type RM Length L Ch R = 1,5073,550,550,550
BEGIN DESCRIPTION:
LAKE FORK CREEK TRIB 2 6.0
END DESCRIPTION:
XS GIS Cut Line= 3
      2774812.52      7053361.09      2774512.50      7053711.11
      2774013.07      7054210.54
#Sta/Elev= 30
  4541.0  493.42  4605.9  491.73  4648.7  490.04  4670.2  488.55  4790.3  483.73
  4833.1  482.60  4875.4  479.56  4939.5  479.92  4967.6  479.46  4981.2  479.92
  4995.5  478.53  4998.2  476.62  4998.7  475.82  5003.9  475.82  5004.4  476.62
  5010.1  476.65  5024.2  480.98  5031.3  481.89  5066.6  482.22  5087.8  481.44
  5151.5  481.16  5215.1  481.98  5328.3  484.27  5434.3  488.37  5449.5  488.55
  5476.7  490.27  5498.0  490.46  5540.4  492.36  5632.3  494.60  5708.3  498.25
#Mann=3,-1,0
  4541.0    0.16       0  4998.2    0.07       0  5004.4    0.16       0
Bank Sta=4670.2,5449.5
Exp/Cntr=0.3,0.1

Type RM Length L Ch R = 1,4523,558,558,558
BEGIN DESCRIPTION:
LAKE FORK CREEK TRIB 2 5.0
END DESCRIPTION:
XS GIS Cut Line= 3
      2774775.05      7053325.00      2774325.00      7053325.00
      2773825.01      7053974.99
#Sta/Elev= 30
  4525.7  493.71  4642.3  488.55  4705.7  486.60  4745.7  483.19  4775.7  483.45
  4822.8  476.72  4832.6  476.05  4833.1  475.25  4838.8  476.05  4885.7  476.05
  4921.9  477.67  4965.7  478.01  4973.2  476.35  4997.5  476.05  5012.0  476.10
  5018.3  477.89  5032.8  476.05  5045.3  476.05  5147.0  476.05  5161.5  478.24
  5182.3  478.81  5190.2  478.81  5196.8  476.97  5203.2  478.58  5211.4  477.55
  5261.2  480.62  5607.3  488.55  5732.4  491.53  5767.7  493.95  5795.8  497.96
#Mann=6,-1,0
  4525.7    0.16       0  4822.8    0.12       0  4832.6   0.033       0
  4838.8    0.12       0  4921.9    0.05       0  5045.3    0.16       0
Bank Sta=4642.3,5607.3
Exp/Cntr=0.3,0.1

Type RM Length L Ch R = 1,3965,538,538,538
BEGIN DESCRIPTION:
LAKE FORK CREEK TRIB 2 4.0
END DESCRIPTION:
XS GIS Cut Line= 3
      2774995.68      7053048.10      2774175.00      7052825.00
      2773239.90      7053069.90
#Sta/Elev= 30
  4133.2  494.47  4175.4  493.74  4201.7  491.59  4205.9  492.65  4241.5  490.35
  4276.1  492.03  4281.3  490.64  4289.3  491.93  4350.5  490.03  4390.3  490.74
  4424.1  489.09  4475.9  490.15  4560.5  488.55  4718.7  481.59  4766.0  478.65
  4783.6  476.05  4784.1  475.25  4789.9  476.05  5090.2  476.05  5165.5  476.05
  5213.3  476.05  5274.5  476.05  5319.4  476.05  5377.5  479.22  5713.2  489.76
  5748.4  488.83  5753.6  486.56  5765.6  488.55  5821.0  491.69  5950.3  493.13
#Mann=10,-1,0
  4133.2    0.05       0  4205.9    0.16       0  4718.7    0.05       0
  4783.6   0.033       0  4789.9    0.05       0  5090.2    0.16       0
  5165.5    0.05       0  5213.3    0.07       0  5274.5    0.05       0
  5377.5    0.16       0
Bank Sta=4560.5,5765.6
Exp/Cntr=0.3,0.1

Type RM Length L Ch R = 1,3427,327,327,327
BEGIN DESCRIPTION:
LAKE FORK CREEK TRIB 2 3.0
END DESCRIPTION:
XS GIS Cut Line= 3
      2774924.96      7052674.98      2774125.00      7052275.00
      2773294.29      7052492.52
#Sta/Elev= 30
  4144.6  492.64  4232.9  488.55  4292.7  485.58  4315.1  483.19  4337.4  479.33
  4354.2  479.72  4368.2  483.42  4382.1  485.32  4407.5  485.42  4435.2  486.11
  4471.6  485.44  4488.3  486.13  4538.7  485.17  4658.9  479.15  4725.9  478.18
  4745.1  476.05  4745.6  475.25  4750.9  475.25  4751.4  476.05  5367.3  476.05
  5390.4  476.68  5400.8  482.81  5410.0  484.16  5415.2  483.43  5450.4  486.67
  5455.6  486.34  5489.2  488.55  5524.8  490.62  5571.6  491.18  5897.7  490.89
#Mann=5,-1,0
  4144.6    0.16       0  4407.5    0.05       0  4745.1   0.033       0
  4751.4    0.05       0  5367.3    0.16       0
Bank Sta=4232.9,5489.2
Exp/Cntr=0.3,0.1

Type RM Length L Ch R = 1,3100,199,199,199
BEGIN DESCRIPTION:
Mapping XS f2015ca5
END DESCRIPTION:
XS GIS Cut Line= 3
      2774971.92      7051772.46      2774030.12      7051989.46
      2773284.88      7052475.32
#Sta/Elev= 30
  4062.4  492.34  4079.8  491.72  4120.8  492.39  4138.4  491.22  4236.4  488.55
  4278.2  486.27  4314.7  485.09  4319.8  484.26  4367.7  481.82  4438.9  479.23
  4487.1  476.05  4487.6  475.25  4492.9  475.25  4493.4  476.05  5325.1  476.05
  5333.4  478.75  5340.3  484.22  5346.2  483.24  5355.4  485.73  5371.8  486.07
  5433.8  486.74  5501.2  488.55  5536.4  489.92  5584.6  489.62  5636.0  490.79
  5715.4  489.89  5780.8  490.64  5817.1  490.07  5874.4  490.77  5918.5  490.38
#Mann=5,-1,0
  4062.4    0.16       0  4278.2    0.05       0  4487.1   0.033       0
  4493.4    0.05       0  5371.8    0.16       0
Bank Sta=4236.4,5501.2
Exp/Cntr=0.3,0.1

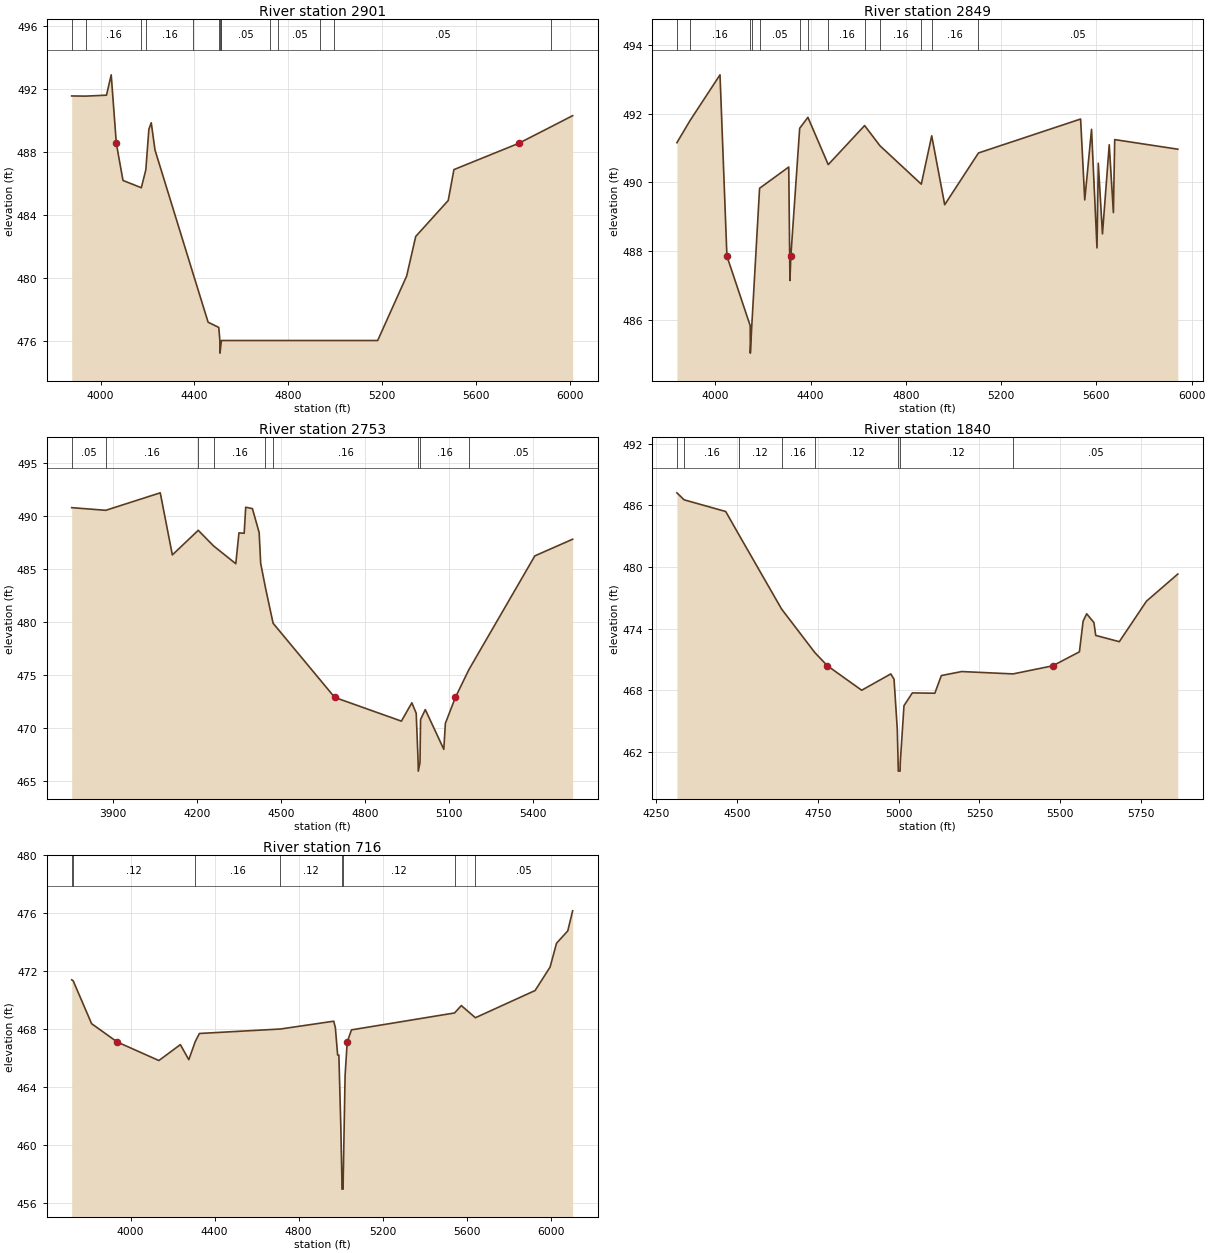
Type RM Length L Ch R = 1,2901,52,52,52
BEGIN DESCRIPTION:
Mapping XS 9bf2d1d0
END DESCRIPTION:
XS GIS Cut Line= 6
      2775032.72      7051520.71      2774559.63      7051559.77
      2773982.38      7051798.49      2773791.40      7051893.98
      2773491.92      7052011.16      2773274.58      7052461.16
#Sta/Elev= 30
  3877.0  491.56  3937.7  491.55  4025.2  491.61  4045.3  492.90  4067.1  488.55
  4095.5  486.20  4173.6  485.74  4192.7  486.87  4205.8  489.45  4215.9  489.86
  4231.9  488.13  4395.4  480.23  4458.2  477.21  4503.6  476.88  4508.2  476.05
  4508.7  475.25  4514.8  476.05  4515.1  476.05  4720.1  476.05  4757.2  476.05
  4936.6  476.05  4996.2  476.05  5180.6  476.05  5304.1  480.14  5342.7  482.65
  5481.1  484.93  5505.5  486.89  5780.6  488.55  5919.9  489.61  6011.2  490.31
#Mann=14,-1,0
  3877.0    0.05       0  3937.7    0.16       0  4173.6    0.05       0
  4192.7    0.16       0  4395.4    0.05       0  4503.6    0.16       0
  4508.2   0.033       0  4514.8    0.16       0  4515.1    0.05       0
  4720.1    0.16       0  4757.2    0.05       0  4936.6    0.16       0
  4996.2    0.05       0  5919.9    0.16       0
Bank Sta=4067.1,5780.6
Exp/Cntr=0.3,0.1

Type RM Length L Ch R = 1,2849,96,96,96
BEGIN DESCRIPTION:
Mapping XS 1b988016
END DESCRIPTION:
XS GIS Cut Line= 6
      2775045.73      7051485.99      2774533.59      7051512.03
      2773917.27      7051772.45      2773578.73      7051911.34
      2773470.22      7051963.42      2773287.92      7052358.42
#Sta/Elev= 30
  3838.8  491.16  3893.4  491.80  4019.8  493.14  4048.8  487.85  4146.6  485.82
  4147.1  485.02  4153.2  485.82  4185.9  489.83  4308.4  490.45  4313.4  487.14
  4317.2  487.85  4354.3  491.58  4388.9  491.90  4474.2  490.52  4626.9  491.66
  4691.5  491.07  4864.9  489.95  4908.7  491.36  4963.2  489.35  5104.9  490.86
  5533.8  491.85  5551.2  489.49  5579.7  491.55  5602.6  488.09  5608.1  490.56
  5625.6  488.50  5654.0  491.10  5671.5  489.12  5677.0  491.25  5942.0  490.97
#Mann=13,-1,0
  3838.8    0.05       0  3893.4    0.16       0  4146.6    0.07       0
  4153.2    0.16       0  4185.9    0.05       0  4354.3    0.16       0
  4388.9    0.05       0  4474.2    0.16       0  4626.9    0.05       0
  4691.5    0.16       0  4864.9    0.05       0  4908.7    0.16       0
  5104.9    0.05       0
Bank Sta=4048.8,4317.2
Exp/Cntr=0.3,0.1

Type RM Length L Ch R = 1,2753,913,913,913
BEGIN DESCRIPTION:
Mapping XS ba9f32b3
END DESCRIPTION:
XS GIS Cut Line= 6
      2775067.44      7051438.24      2774789.67      7051355.78
      2774416.40      7051507.69      2773886.89      7051681.30
      2773522.31      7051872.27      2773405.15      7051924.34
#Sta/Elev= 30
  3752.6  490.77  3874.3  490.52  4069.0  492.17  4112.2  486.31  4204.8  488.63
  4259.4  487.16  4338.9  485.48  4350.2  488.39  4368.9  488.35  4374.3  490.81
  4398.3  490.68  4422.4  488.42  4427.8  485.52  4444.7  483.24  4472.2  479.86
  4692.3  472.86  4930.6  470.62  4968.0  472.35  4983.6  471.36  4990.5  466.70
  4991.0  465.90  4997.1  466.70  4999.1  470.77  5016.0  471.71  5082.2  467.96
  5087.8  470.41  5123.6  472.86  5171.8  475.48  5407.5  486.22  5542.5  487.79
#Mann=9,-1,0
  3752.6    0.05       0  3874.3    0.16       0  4204.8    0.05       0
  4259.4    0.16       0  4444.7    0.05       0  4472.2    0.16       0
  4990.5    0.07       0  4997.1    0.16       0  5171.8    0.05       0
Bank Sta=4692.3,5123.6
Exp/Cntr=0.3,0.1

Type RM Length L Ch R = 1,1840,1124,1124,1124
BEGIN DESCRIPTION:
Mapping XS 5d88eec6
END DESCRIPTION:
XS GIS Cut Line= 4
      2774545.76      7051084.08      2773858.24      7051058.04
      2773597.83      7051141.37      2773337.41      7051667.41
#Sta/Elev= 30
  4314.7  487.23  4336.9  486.55  4465.6  485.41  4506.0  483.17  4638.3  475.91
  4741.3  471.66  4780.1  470.38  4885.9  468.00  4975.9  469.59  4985.9  469.07
  4995.9  464.22  4998.5  460.92  4999.0  460.12  5004.6  460.12  5005.1  460.92
  5016.6  466.49  5042.4  467.74  5112.0  467.71  5132.1  469.43  5195.1  469.82
  5353.7  469.59  5476.4  470.38  5558.9  471.74  5570.3  474.72  5581.3  475.45
  5603.8  474.59  5609.3  473.34  5682.2  472.73  5766.3  476.68  5863.1  479.32
#Mann=8,-1,0
  4314.7    0.12       0  4336.9    0.16       0  4506.0    0.12       0
  4638.3    0.16       0  4741.3    0.12       0  4998.5    0.07       0
  5005.1    0.12       0  5353.7    0.05       0
Bank Sta=4780.1,5476.4
Exp/Cntr=0.3,0.1

Type RM Length L Ch R = 1,716,0,0,0
BEGIN DESCRIPTION:
LAKE FORK CREEK TRIB 2 1.0
END DESCRIPTION:
XS GIS Cut Line= 4
      2774639.04      7050234.64      2773830.19      7050322.88
      2773444.45      7050561.72      2773245.49      7051660.71
#Sta/Elev= 30
  3720.0  471.40  3727.1  471.33  3814.6  468.37  3937.0  467.10  4134.9  465.82
  4237.1  466.92  4277.3  465.88  4308.3  467.14  4327.7  467.69  4713.7  468.00
  4967.1  468.54  4974.9  468.10  4985.7  466.20  4991.6  466.20  5000.8  461.29
  5005.8  457.73  5006.3  456.93  5011.9  456.93  5012.4  457.73  5021.2  464.78
  5031.2  467.10  5051.7  467.94  5542.4  469.11  5574.4  469.62  5641.4  468.78
  5925.6  470.66  5996.8  472.28  6027.6  473.93  6081.0  474.78  6104.2  476.17
#Mann=8,-1,0
  3720.0    0.16       0  3727.1    0.12       0  4308.3    0.16       0
  4713.7    0.12       0  5005.8    0.07       0  5012.4    0.12       0
  5542.4    0.16       0  5641.4    0.05       0
Bank Sta=3937,5031.2
Exp/Cntr=0.3,0.1

Chan Stop Cuts=-1