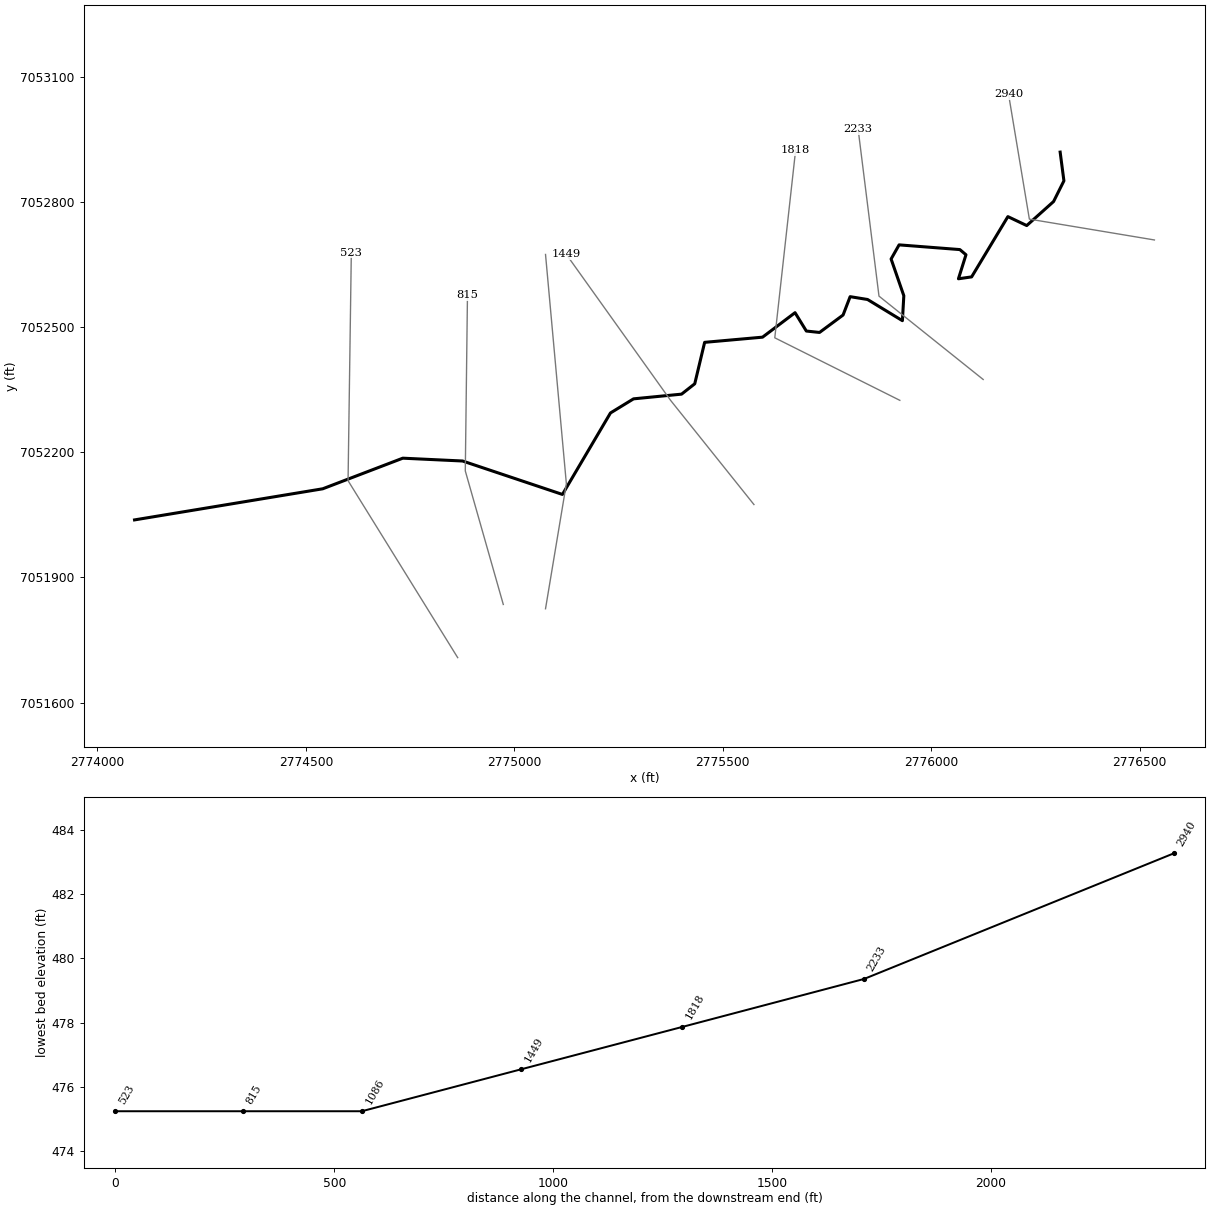
--- LAKE FORK CREEK TRIB 2_1.prj (project) ---

Proj Title=LAKE FORK CREEK TRIB 2_1 Base Level Engineering
Current Plan=p01
Default Exp/Contr=0.3,0.1
English Units
Geom File=g01
Flow File=f01
Plan File=p01
BEGIN DESCRIPTION:
LAKE FORK CREEK TRIB 2_1
END DESCRIPTION:

--- LAKE FORK CREEK TRIB 2_1.p01 (plan) ---

Plan Title=Multiple Run
Short Identifier=Multiple
Geom File=g01
Flow File=f01
Subcritical Flow
K Sum by GR= 0
Std Step Tol= 0.01
Critical Tol= 0.01
Num of Std Step Trials= 20
Max Error Tol= 0.3
Flow Tol Ratio= 0.001
Split Flow NTrial= 30
Split Flow Tol= 0.02
Split Flow Ratio= 0.02
Log Output Level= 0
Friction Slope Method= 1
Unsteady Friction Slope Method= 2
Unsteady Bridges Friction Slope Method= 1
Parabolic Critical Depth
Global Vel Dist=  1 , 1 , 1
Global Log Level= 0
CheckData=True
Encroach Param= -1, 0, 0, 0
BEGIN DESCRIPTION:
Multiple Run
END DESCRIPTION:

--- LAKE FORK CREEK TRIB 2_1.f01 (steady flow) ---

Flow Title=Multiple
Number of Profiles=7
Profile Names=10-year,25-year,50-year,1pct_min,100-year,1pct_plu,500-year
River Rch & RM= LAKE FORK CREEK ,Reach-1,2940
     200     249     287     165     329     656     431
Boundary for River Rch & Prof#=LAKE FORK CREEK ,Reach-1,1
Up Type=0
Dn Type=3
Dn Slope=0.005
Boundary for River Rch & Prof#=LAKE FORK CREEK ,Reach-1,2
Up Type=0
Dn Type=3
Dn Slope=0.005
Boundary for River Rch & Prof#=LAKE FORK CREEK ,Reach-1,3
Up Type=0
Dn Type=3
Dn Slope=0.005
Boundary for River Rch & Prof#=LAKE FORK CREEK ,Reach-1,4
Up Type=0
Dn Type=3
Dn Slope=0.005
Boundary for River Rch & Prof#=LAKE FORK CREEK ,Reach-1,5
Up Type=0
Dn Type=3
Dn Slope=0.005
Boundary for River Rch & Prof#=LAKE FORK CREEK ,Reach-1,6
Up Type=0
Dn Type=3
Dn Slope=0.005
Boundary for River Rch & Prof#=LAKE FORK CREEK ,Reach-1,7
Up Type=0
Dn Type=3
Dn Slope=0.005

--- LAKE FORK CREEK TRIB 2_1.g01 (geometry) ---

Geom Title=Existing Conditions

River Reach=LAKE FORK CREEK ,Reach-1
Reach XY= 30
      2776309.62      7052920.51      2776318.66      7052851.60
      2776293.81      7052801.89      2776229.42      7052744.28
      2776184.23      7052765.74      2776097.24      7052621.14
      2776065.61      7052616.62      2776083.69      7052674.24
      2776069.00      7052686.66      2775923.27      7052697.96
      2775904.07      7052664.07      2775934.57      7052575.96
      2775931.18      7052516.08      2775847.59      7052566.92
      2775805.79      7052573.70      2775788.84      7052529.64
      2775732.36      7052487.84      2775700.73      7052491.23
      2775673.62      7052535.29      2775595.67      7052476.55
      2775456.72      7052464.12      2775433.00      7052364.71
      2775401.36      7052339.85      2775286.14      7052328.56
      2775230.78      7052294.67      2775115.56      7052099.23
      2774876.07      7052179.44      2774732.60      7052186.22
      2774540.55      7052112.79      2774089.03      7052038.14

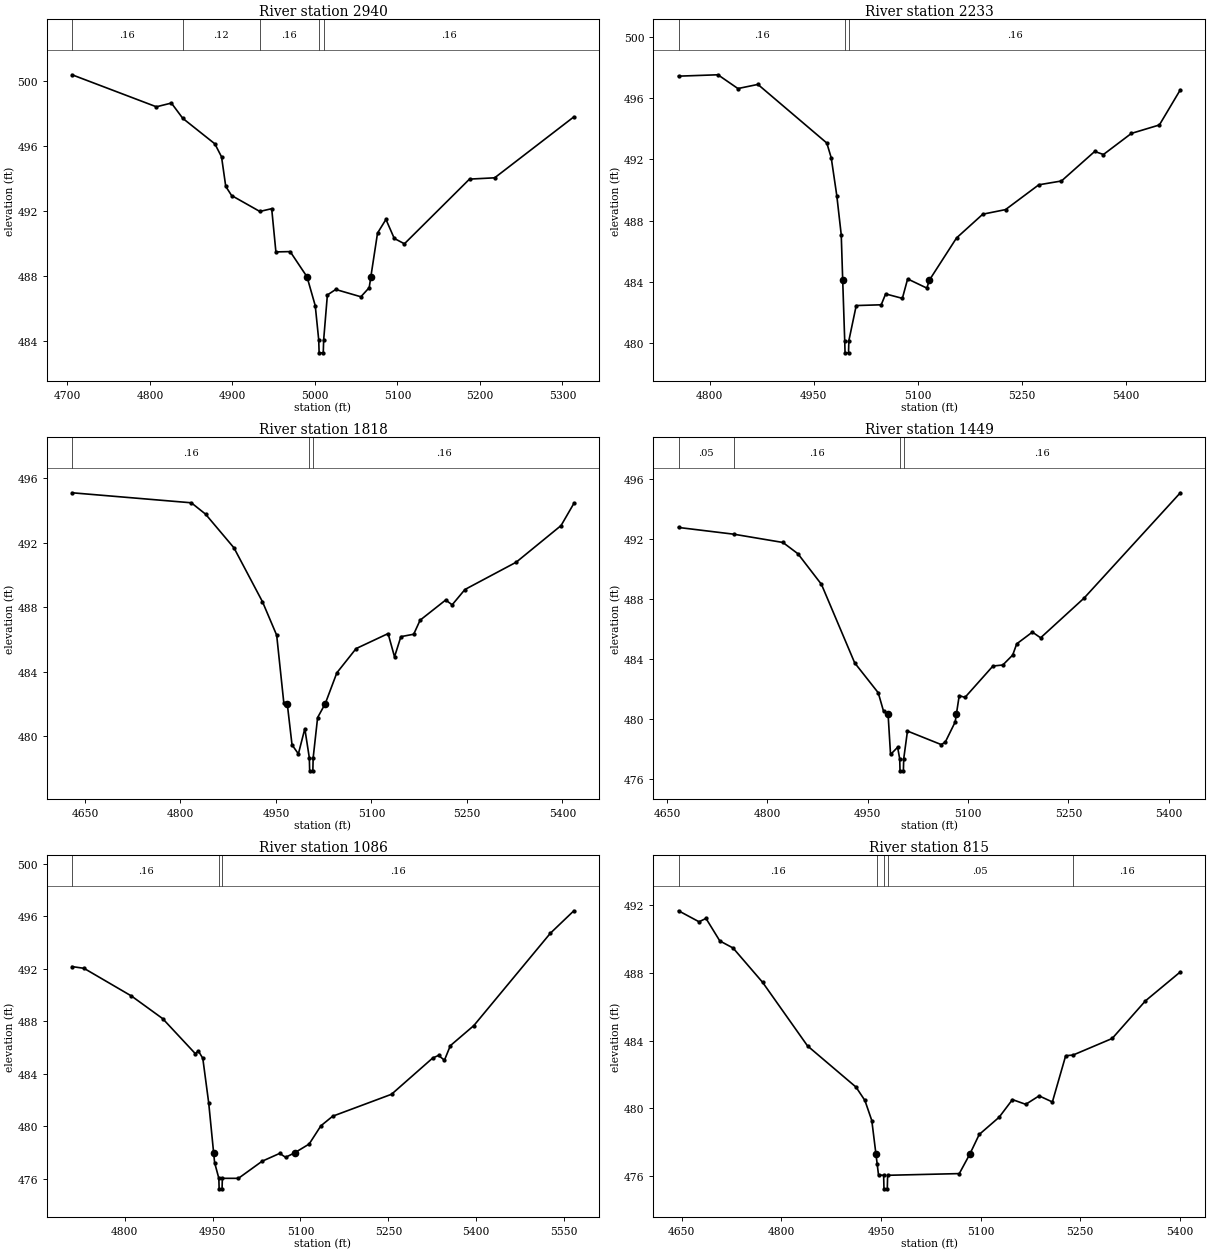
Type RM Length L Ch R = 1,2940,707,707,707
BEGIN DESCRIPTION:
LAKE FORK CREEK TRIB 2_1 6.0
END DESCRIPTION:
XS GIS Cut Line= 3
      2776535.78      7052709.72      2776235.76      7052759.72
      2776185.76      7053059.73
#Sta/Elev= 30
  4705.6  500.37  4807.8  498.40  4826.0  498.63  4839.8  497.69  4878.7  496.12
  4886.8  495.32  4891.9  493.50  4899.0  492.94  4933.2  491.96  4947.6  492.13
  4952.7  489.47  4970.0  489.49  4990.4  487.94  5000.4  486.16  5004.6  484.06
  5005.1  483.26  5010.1  483.26  5010.6  484.06  5015.1  486.82  5025.2  487.16
  5055.7  486.71  5065.8  487.27  5067.8  487.94  5075.9  490.63  5086.1  491.47
  5096.2  490.30  5108.5  489.97  5187.4  493.95  5217.9  494.03  5313.9  497.78
#Mann=5,-1,0
  4705.6    0.16       0  4839.8    0.12       0  4933.2    0.16       0
  5004.6    0.07       0  5010.6    0.16       0
Bank Sta=4990.4,5067.8
Exp/Cntr=0.3,0.1

Type RM Length L Ch R = 1,2233,415,415,415
BEGIN DESCRIPTION:
LAKE FORK CREEK TRIB 2_1 5.0
END DESCRIPTION:
XS GIS Cut Line= 3
      2776124.97      7052375.02      2775875.00      7052575.00
      2775825.00      7052974.97
#Sta/Elev= 30
  4755.1  497.44  4811.9  497.53  4840.7  496.63  4869.5  496.90  4968.8  493.07
  4975.2  492.10  4983.2  489.63  4989.6  487.07  4991.7  484.11  4994.6  480.16
  4995.1  479.36  5000.1  479.36  5000.6  480.16  5011.2  482.45  5047.2  482.50
  5053.6  483.21  5077.7  482.92  5085.3  484.19  5113.0  483.59  5116.6  484.11
  5155.8  486.87  5193.6  488.42  5226.4  488.72  5274.3  490.34  5307.0  490.59
  5354.9  492.52  5367.5  492.32  5407.8  493.70  5448.1  494.25  5478.3  496.55
#Mann=3,-1,0
  4755.1    0.16       0  4994.6    0.07       0  5000.6    0.16       0
Bank Sta=4991.7,5116.6
Exp/Cntr=0.3,0.1

Type RM Length L Ch R = 1,1818,369,369,369
BEGIN DESCRIPTION:
LAKE FORK CREEK TRIB 2_1 4.0
END DESCRIPTION:
XS GIS Cut Line= 3
      2775925.00      7052325.00      2775625.00      7052475.00
      2775675.00      7052925.02
#Sta/Elev= 30
  4629.8  495.09  4817.1  494.47  4839.4  493.77  4884.1  491.68  4928.9  488.34
  4951.2  486.27  4962.4  482.08  4967.8  482.03  4975.3  479.48  4985.3  478.92
  4995.4  480.48  5002.5  478.67  5003.0  477.87  5008.0  477.87  5008.5  478.67
  5015.5  481.17  5027.5  482.03  5045.7  483.94  5075.9  485.44  5126.2  486.37
  5136.3  484.93  5146.3  486.18  5166.4  486.33  5176.5  487.20  5216.7  488.45
  5226.8  488.15  5246.9  489.10  5327.4  490.79  5397.9  493.06  5418.0  494.43
#Mann=3,-1,0
  4629.8    0.16       0  5002.5    0.07       0  5008.5    0.16       0
Bank Sta=4967.8,5027.5
Exp/Cntr=0.3,0.1

Type RM Length L Ch R = 1,1449,363,363,363
BEGIN DESCRIPTION:
LAKE FORK CREEK TRIB 2_1 3.0
END DESCRIPTION:
XS GIS Cut Line= 3
      2775575.02      7052074.98      2775375.00      7052325.00
      2775125.00      7052675.00
#Sta/Elev= 30
  4667.1  492.76  4749.9  492.31  4823.2  491.76  4845.6  491.01  4880.8  488.97
  4930.5  483.74  4965.7  481.75  4973.7  480.51  4980.4  480.34  4984.1  477.64
  4994.7  478.12  4997.8  477.35  4998.3  476.55  5003.3  476.55  5003.8  477.35
  5009.4  479.20  5059.8  478.30  5065.9  478.46  5080.7  479.80  5082.6  480.34
  5086.8  481.56  5095.4  481.44  5137.2  483.53  5152.0  483.60  5166.7  484.26
  5172.8  485.01  5196.2  485.79  5208.5  485.41  5273.6  488.06  5417.4  495.07
#Mann=4,-1,0
  4667.1    0.05       0  4749.9    0.16       0  4997.8    0.07       0
  5003.8    0.16       0
Bank Sta=4980.4,5082.6
Exp/Cntr=0.3,0.1

Type RM Length L Ch R = 1,1086,271,271,271
BEGIN DESCRIPTION:
LAKE FORK CREEK TRIB 2_1 2.0
END DESCRIPTION:
XS GIS Cut Line= 3
      2775074.99      7051824.96      2775125.00      7052125.00
      2775075.00      7052674.96
#Sta/Elev= 30
  4710.2  492.17  4730.5  492.04  4811.6  489.93  4864.8  488.21  4920.6  485.54
  4925.7  485.75  4933.3  485.19  4943.4  481.79  4951.8  477.99  4953.5  477.24
  4960.7  476.05  4961.2  475.25  4966.2  475.25  4966.7  476.05  4994.1  476.05
  5034.5  477.35  5064.6  477.95  5074.6  477.65  5090.0  477.99  5114.8  478.66
  5134.9  480.05  5155.0  480.78  5255.4  482.45  5325.7  485.21  5335.7  485.41
  5345.7  485.04  5355.8  486.15  5395.9  487.68  5526.5  494.71  5566.6  496.42
#Mann=3,-1,0
  4710.2    0.16       0  4960.7    0.07       0  4966.7    0.16       0
Bank Sta=4951.8,5090
Exp/Cntr=0.3,0.1

Type RM Length L Ch R = 1,815,292,292,292
BEGIN DESCRIPTION:
Mapping XS 61477304
END DESCRIPTION:
XS GIS Cut Line= 3
      2774973.69      7051835.28      2774882.54      7052155.62
      2774887.75      7052577.53
#Sta/Elev= 30
  4645.5  491.67  4676.4  491.02  4686.8  491.22  4707.6  489.89  4727.6  489.47
  4771.9  487.45  4839.6  483.69  4912.5  481.26  4925.9  480.47  4936.3  479.28
  4942.5  477.31  4944.4  476.71  4946.4  476.07  4954.1  476.05  4954.6  475.25
  4959.6  475.25  4960.1  476.05  5067.9  476.15  5083.9  477.31  5097.9  478.46
  5127.9  479.48  5147.9  480.52  5167.9  480.24  5188.0  480.74  5208.0  480.38
  5228.0  483.11  5239.1  483.15  5298.0  484.13  5348.0  486.35  5400.5  488.06
#Mann=5,-1,0
  4645.5    0.16       0  4944.4    0.05       0  4954.1   0.035       0
  4960.1    0.05       0  5239.1    0.16       0
Bank Sta=4942.5,5083.9
Exp/Cntr=0.3,0.1

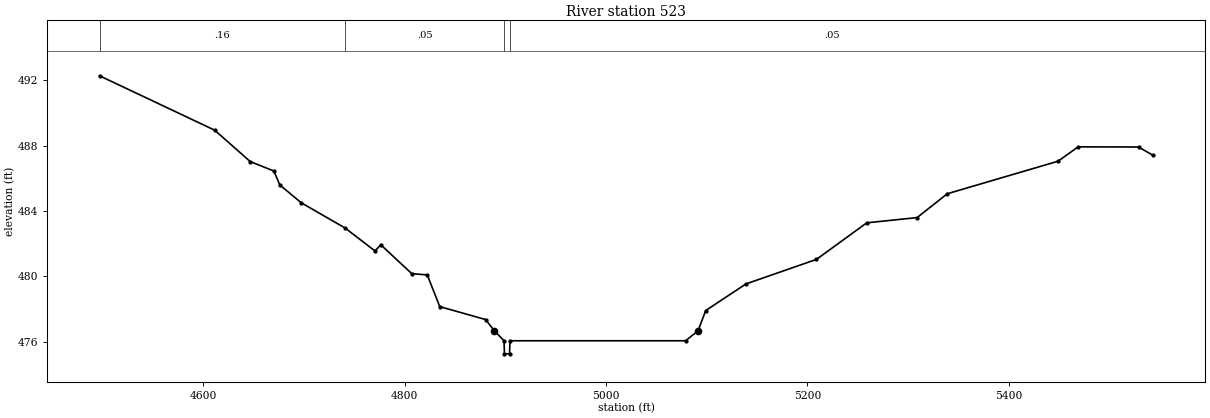
Type RM Length L Ch R = 1,523,0,0,0
BEGIN DESCRIPTION:
LAKE FORK CREEK TRIB 2_1 1.0
END DESCRIPTION:
XS GIS Cut Line= 3
      2774864.30      7051707.71      2774601.29      7052132.18
      2774609.10      7052679.08
#Sta/Elev= 30
  4496.8  492.27  4611.2  488.94  4646.5  487.02  4670.0  486.44  4675.9  485.59
  4697.1  484.50  4740.8  482.95  4770.4  481.55  4776.3  481.92  4807.0  480.16
  4822.4  480.08  4834.8  478.14  4880.3  477.35  4889.1  476.66  4898.6  476.05
  4899.1  475.25  4904.1  475.25  4904.6  476.05  5079.0  476.05  5091.4  476.66
  5099.0  477.90  5139.0  479.53  5209.0  481.03  5259.0  483.27  5309.0  483.59
  5339.0  485.05  5449.0  487.04  5469.0  487.92  5529.0  487.91  5543.1  487.41
#Mann=4,-1,0
  4496.8    0.16       0  4740.8    0.05       0  4898.6   0.033       0
  4904.6    0.05       0
Bank Sta=4889.1,5091.4
Exp/Cntr=0.3,0.1

Chan Stop Cuts=-1