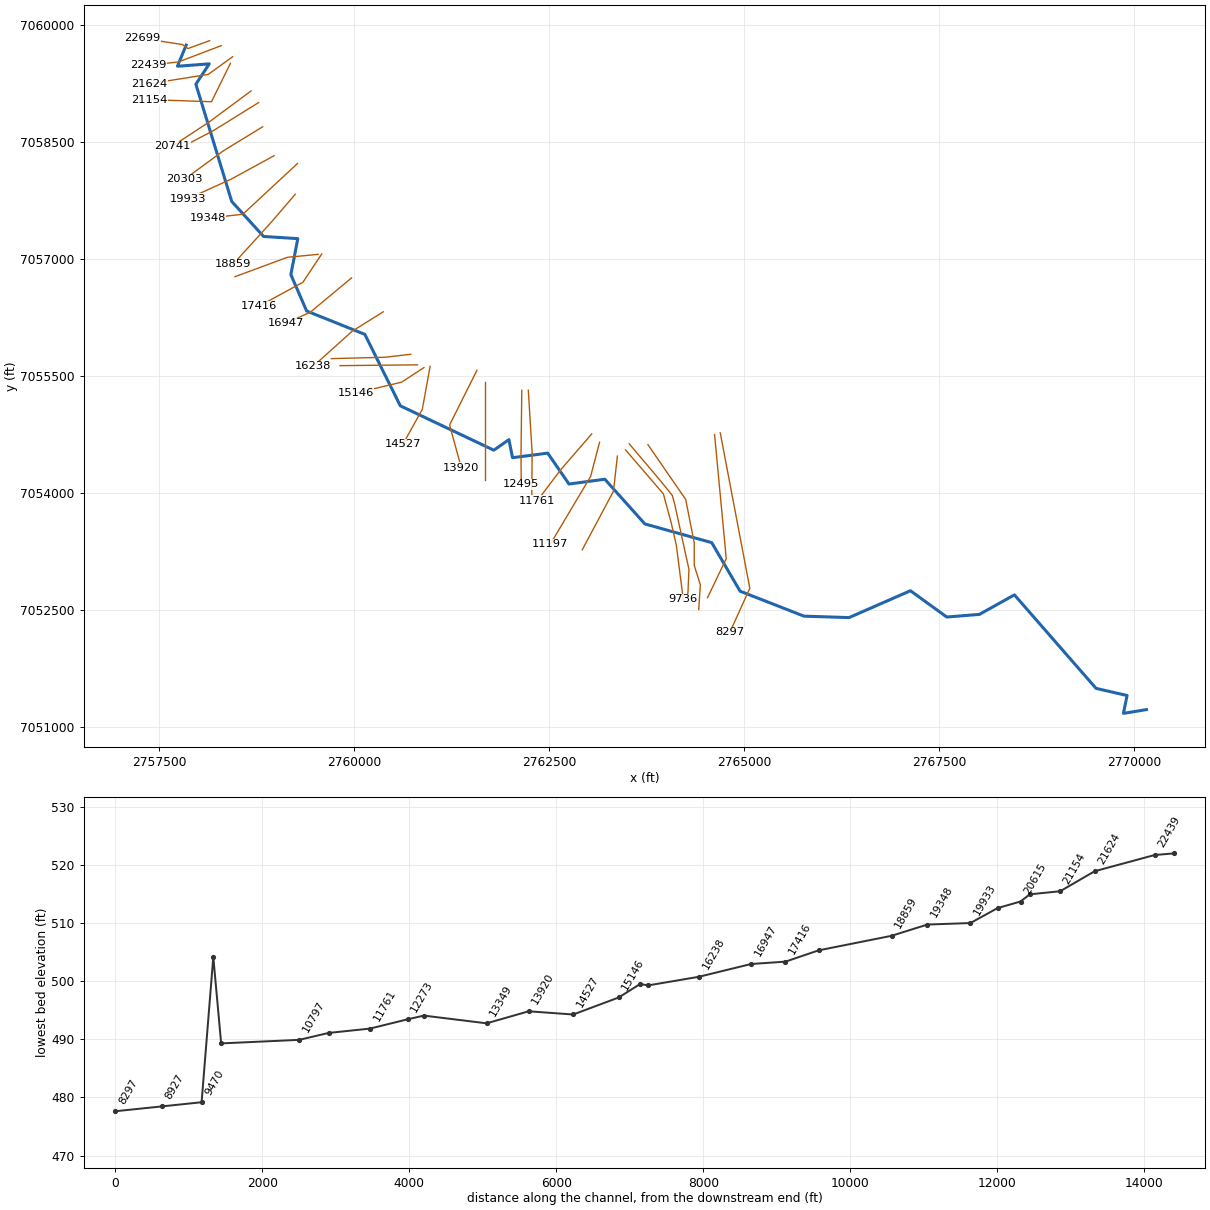
--- LAKE FORK CREEK TRIB 3.prj (project) ---

Proj Title=LAKE FORK CREEK TRIB 3 Base Level Engineering
Current Plan=p01
Default Exp/Contr=0.3,0.1
English Units
Geom File=g01
Flow File=f01
Plan File=p01
BEGIN DESCRIPTION:
LAKE FORK CREEK TRIB 3
END DESCRIPTION:

--- LAKE FORK CREEK TRIB 3.p01 (plan) ---

Plan Title=Multiple Run
Short Identifier=Multiple
Geom File=g01
Flow File=f01
Subcritical Flow
K Sum by GR= 0
Std Step Tol= 0.01
Critical Tol= 0.01
Num of Std Step Trials= 20
Max Error Tol= 0.3
Flow Tol Ratio= 0.001
Split Flow NTrial= 30
Split Flow Tol= 0.02
Split Flow Ratio= 0.02
Log Output Level= 0
Friction Slope Method= 1
Unsteady Friction Slope Method= 2
Unsteady Bridges Friction Slope Method= 1
Parabolic Critical Depth
Global Vel Dist=  1 , 1 , 1
Global Log Level= 0
CheckData=True
Encroach Param= -1, 0, 0, 0
BEGIN DESCRIPTION:
Multiple Run
END DESCRIPTION:

--- LAKE FORK CREEK TRIB 3.f01 (steady flow) ---

Flow Title=Multiple
Number of Profiles=7
Profile Names=10-year,25-year,50-year,1pct_min,100-year,1pct_plu,500-year
River Rch & RM= LAKE FORK CREEK ,Reach-1,22699
     633     838    1002     593    1184    2363    1652
River Rch & RM= LAKE FORK CREEK ,Reach-1,22439
     823    1106    1335     798    1592    3176    2260
River Rch & RM= LAKE FORK CREEK ,Reach-1,13920
     930    1257    1524     914    1824    3640    2616
River Rch & RM= LAKE FORK CREEK ,Reach-1,3725
    1055    1436    1749    1054    2103    4197    3045
Boundary for River Rch & Prof#=LAKE FORK CREEK ,Reach-1,1
Up Type=0
Dn Type=3
Dn Slope=0.005
Boundary for River Rch & Prof#=LAKE FORK CREEK ,Reach-1,2
Up Type=0
Dn Type=3
Dn Slope=0.005
Boundary for River Rch & Prof#=LAKE FORK CREEK ,Reach-1,3
Up Type=0
Dn Type=3
Dn Slope=0.005
Boundary for River Rch & Prof#=LAKE FORK CREEK ,Reach-1,4
Up Type=0
Dn Type=3
Dn Slope=0.005
Boundary for River Rch & Prof#=LAKE FORK CREEK ,Reach-1,5
Up Type=0
Dn Type=3
Dn Slope=0.005
Boundary for River Rch & Prof#=LAKE FORK CREEK ,Reach-1,6
Up Type=0
Dn Type=3
Dn Slope=0.005
Boundary for River Rch & Prof#=LAKE FORK CREEK ,Reach-1,7
Up Type=0
Dn Type=3
Dn Slope=0.005

--- LAKE FORK CREEK TRIB 3.g01 (geometry) ---

Geom Title=Existing Conditions

River Reach=LAKE FORK CREEK ,Reach-1
Reach XY= 30
      2757848.71      7059742.98      2757736.59      7059471.65
      2758144.63      7059502.51      2757973.18      7059241.90
      2758432.62      7057739.11      2758840.59      7057290.45
      2759279.42      7057262.44      2759190.27      7056801.22
      2759393.25      7056334.34      2760138.58      7056035.81
      2760592.92      7055120.28      2761791.35      7054551.07
      2761985.08      7054686.51      2762031.38      7054455.06
      2762482.29      7054513.35      2762754.89      7054117.30
      2763214.37      7054179.02      2763727.00      7053606.39
      2764584.25      7053366.36      2764947.60      7052744.27
      2765766.63      7052424.23      2766344.09      7052405.65
      2767130.71      7052750.00      2767597.02      7052412.89
      2768015.35      7052446.99      2768463.86      7052696.84
      2769509.76      7051498.53      2769908.12      7051406.95
      2769860.32      7051178.11      2770155.72      7051226.57

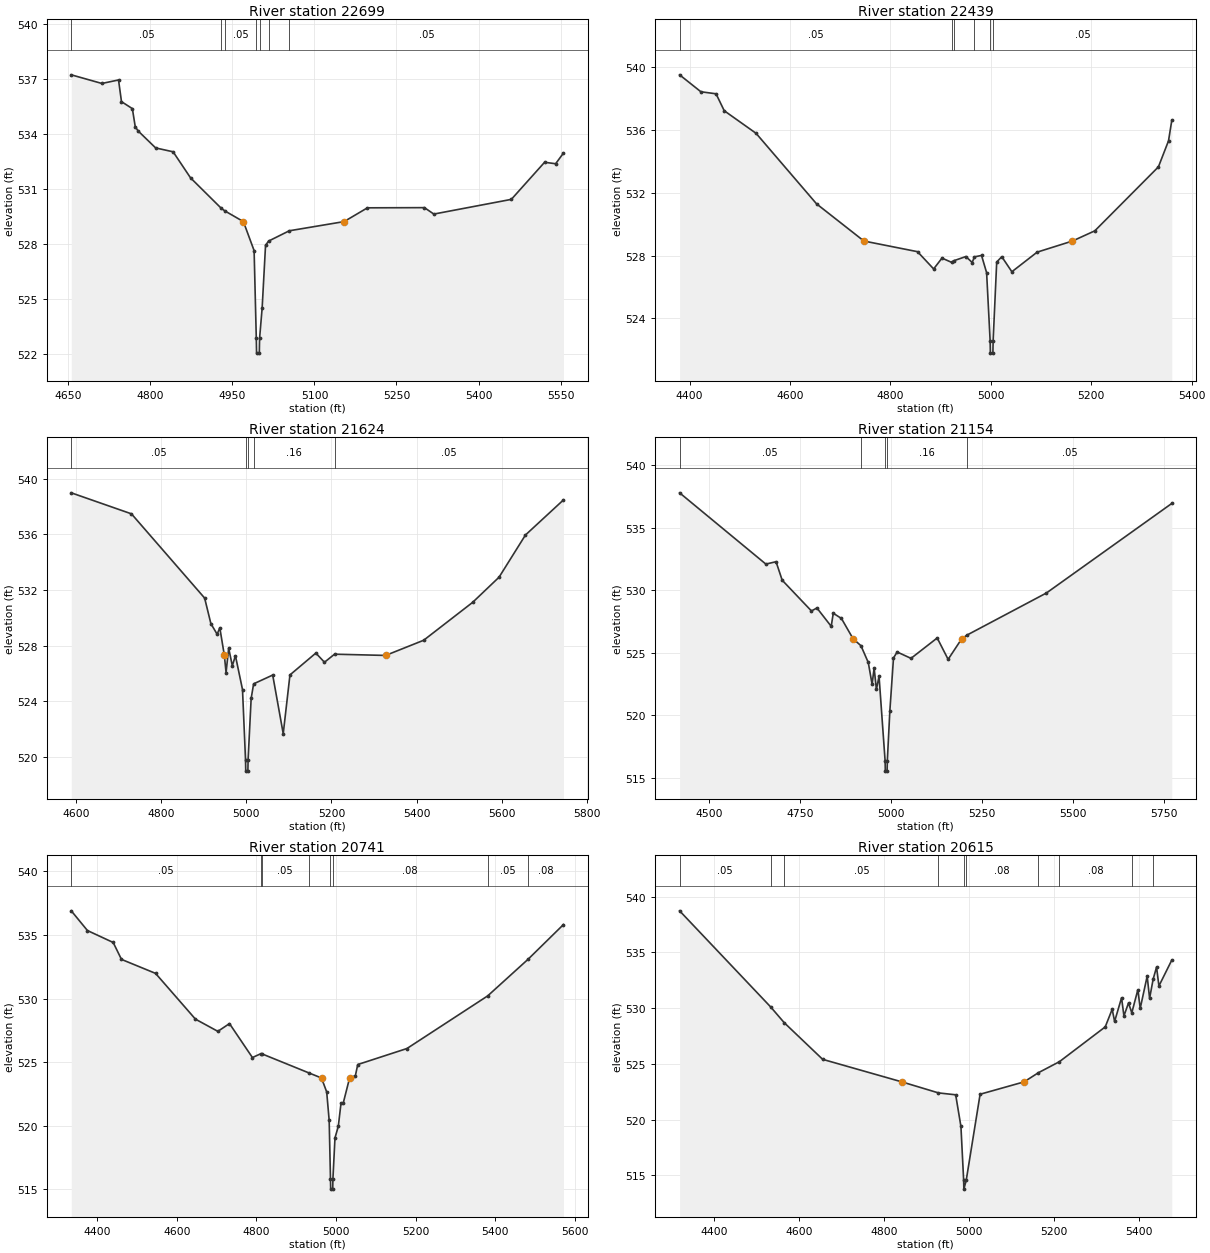
Type RM Length L Ch R = 1,22699,260,260,260
BEGIN DESCRIPTION:
LAKE FORK CREEK TRIB 3 31.0
END DESCRIPTION:
XS GIS Cut Line= 4
      2758149.99      7059800.00      2757870.94      7059698.51
      2757800.00      7059750.00      2757290.87      7059829.59
#Sta/Elev= 30
  4655.4  537.21  4711.3  536.74  4741.8  536.93  4747.2  535.75  4767.1  535.37
  4772.4  534.38  4777.8  534.15  4809.7  533.23  4841.6  533.02  4873.5  531.60
  4929.8  529.94  4936.9  529.79  4970.1  529.22  4989.7  527.64  4993.7  522.86
  4994.2  522.06  4999.2  522.06  4999.7  522.86  5004.4  524.52  5010.6  527.93
  5016.2  528.16  5054.0  528.72  5154.2  529.22  5196.9  529.97  5301.1  529.98
  5318.3  529.63  5460.0  530.43  5520.8  532.45  5541.0  532.37  5555.3  532.95
#Mann=7,-1,0
  4655.4    0.05       0  4929.8    0.16       0  4936.9    0.05       0
  4993.7    0.03       0  4999.7    0.05       0  5016.2    0.16       0
  5054.0    0.05       0
Bank Sta=4970.1,5154.2
Exp/Cntr=0.3,0.1

Type RM Length L Ch R = 1,22439,815,815,815
BEGIN DESCRIPTION:
Mapping XS a82924e8
END DESCRIPTION:
XS GIS Cut Line= 3
      2758298.07      7059735.68      2757749.41      7059527.33
      2757358.58      7059482.37
#Sta/Elev= 30
  4380.1  539.53  4422.5  538.45  4452.7  538.32  4469.0  537.24  4532.4  535.80
  4652.9  531.30  4747.2  528.93  4854.0  528.25  4886.1  527.15  4902.7  527.84
  4921.9  527.57  4926.0  527.67  4950.3  527.94  4962.9  527.56  4967.3  527.92
  4981.5  528.01  4991.6  526.91  4998.6  522.58  4999.1  521.78  5004.1  521.78
  5004.6  522.58  5011.7  527.59  5021.8  527.93  5041.9  526.97  5092.2  528.22
  5162.6  528.93  5207.1  529.58  5333.8  533.66  5353.9  535.32  5360.4  536.62
#Mann=6,-1,0
  4380.1    0.05       0  4921.9    0.16       0  4926.0     0.1       0
  4967.3    0.05       0  4998.6    0.03       0  5004.6    0.05       0
Bank Sta=4747.2,5162.6
Exp/Cntr=0.3,0.1

Type RM Length L Ch R = 1,21624,470,470,470
BEGIN DESCRIPTION:
Mapping XS c37145c9
END DESCRIPTION:
XS GIS Cut Line= 3
      2758443.82      7059593.28      2758131.36      7059367.61
      2757370.94      7059246.08
#Sta/Elev= 30
  4589.1  538.98  4730.4  537.47  4902.2  531.42  4916.9  529.58  4931.6  528.82
  4937.8  529.29  4948.5  527.30  4952.5  526.07  4958.6  527.82  4967.2  526.56
  4974.5  527.28  4991.1  524.85  4998.2  519.79  4998.7  518.99  5003.7  518.99
  5004.2  519.79  5011.4  524.21  5017.2  525.26  5062.0  525.89  5086.7  521.68
  5102.5  525.90  5163.3  527.47  5183.5  526.81  5207.2  527.39  5327.1  527.30
  5416.4  528.39  5531.3  531.11  5593.4  532.92  5655.4  535.95  5744.6  538.47
#Mann=5,-1,0
  4589.1    0.05       0  4998.2   0.035       0  5004.2    0.05       0
  5017.2    0.16       0  5207.2    0.05       0
Bank Sta=4948.5,5327.1
Exp/Cntr=0.3,0.1

Type RM Length L Ch R = 1,21154,413,413,413
BEGIN DESCRIPTION:
Mapping XS 17913f85
END DESCRIPTION:
XS GIS Cut Line= 3
      2758416.07      7059509.95      2758173.02      7059016.92
      2757370.89      7059044.70
#Sta/Elev= 30
  4419.4  537.80  4656.4  532.10  4684.4  532.29  4701.3  530.81  4781.7  528.35
  4796.7  528.59  4836.0  527.12  4841.6  528.17  4864.1  527.75  4896.0  526.13
  4917.7  525.57  4937.8  524.23  4948.3  522.49  4953.9  523.79  4960.1  522.07
  4967.4  523.13  4984.1  516.34  4984.6  515.54  4989.6  515.54  4990.1  516.34
  4997.1  520.36  5007.1  524.59  5017.1  525.07  5055.2  524.56  5127.2  526.19
  5157.2  524.48  5194.6  526.13  5209.6  526.43  5427.4  529.79  5771.7  536.95
#Mann=5,-1,0
  4419.4    0.05       0  4917.7    0.16       0  4984.1    0.07       0
  4990.1    0.16       0  5209.6    0.05       0
Bank Sta=4896,5194.6
Exp/Cntr=0.3,0.1

Type RM Length L Ch R = 1,20741,126,126,126
BEGIN DESCRIPTION:
Mapping XS 2da973ea
END DESCRIPTION:
XS GIS Cut Line= 3
      2758680.50      7059155.74      2758141.73      7058756.30
      2757668.99      7058445.78
#Sta/Elev= 30
  4334.9  536.90  4375.5  535.35  4440.2  534.41  4461.0  533.08  4546.6  531.98
  4646.8  528.38  4703.1  527.42  4732.3  528.03  4789.9  525.36  4810.9  525.66
  4813.8  525.65  4931.1  524.16  4963.5  523.75  4976.5  522.65  4982.7  520.42
  4986.0  515.81  4986.5  515.01  4991.6  515.01  4992.1  515.81  4997.3  519.04
  5005.6  519.94  5012.4  521.75  5018.3  521.81  5034.0  523.75  5048.5  523.93
  5054.5  524.81  5178.1  526.07  5380.9  530.21  5482.0  533.08  5571.2  535.82
#Mann=8,-1,0
  4334.9    0.05       0  4810.9    0.16       0  4813.8    0.05       0
  4931.1    0.08       0  4986.0    0.07       0  4992.1    0.08       0
  5380.9    0.05       0  5482.0    0.08       0
Bank Sta=4963.5,5034
Exp/Cntr=0.3,0.1

Type RM Length L Ch R = 1,20615,312,312,312
BEGIN DESCRIPTION:
LAKE FORK CREEK TRIB 3 30.0
END DESCRIPTION:
XS GIS Cut Line= 3
      2758777.98      7059007.08      2758202.10      7058649.48
      2757774.98      7058424.99
#Sta/Elev= 30
  4317.9  538.73  4532.6  530.11  4564.5  528.70  4655.2  525.41  4841.8  523.39
  4928.2  522.40  4968.8  522.23  4981.2  519.39  4987.6  514.57  4988.1  513.77
  4993.7  514.57  5026.4  522.28  5130.1  523.39  5163.8  524.21  5213.4  525.20
  5321.4  528.32  5337.8  529.90  5343.5  528.81  5359.9  530.93  5365.5  529.30
  5376.3  530.47  5384.0  529.58  5398.3  531.65  5403.9  529.98  5420.3  532.87
  5426.0  530.88  5434.5  532.62  5442.4  533.68  5448.0  531.99  5478.3  534.31
#Mann=10,-1,0
  4317.9    0.05       0  4532.6    0.08       0  4564.5    0.05       0
  4928.2    0.08       0  4987.6    0.07       0  4993.7    0.08       0
  5163.8    0.16       0  5213.4    0.08       0  5384.0    0.05       0
  5434.5    0.08       0
Bank Sta=4841.8,5130.1
Exp/Cntr=0.3,0.1

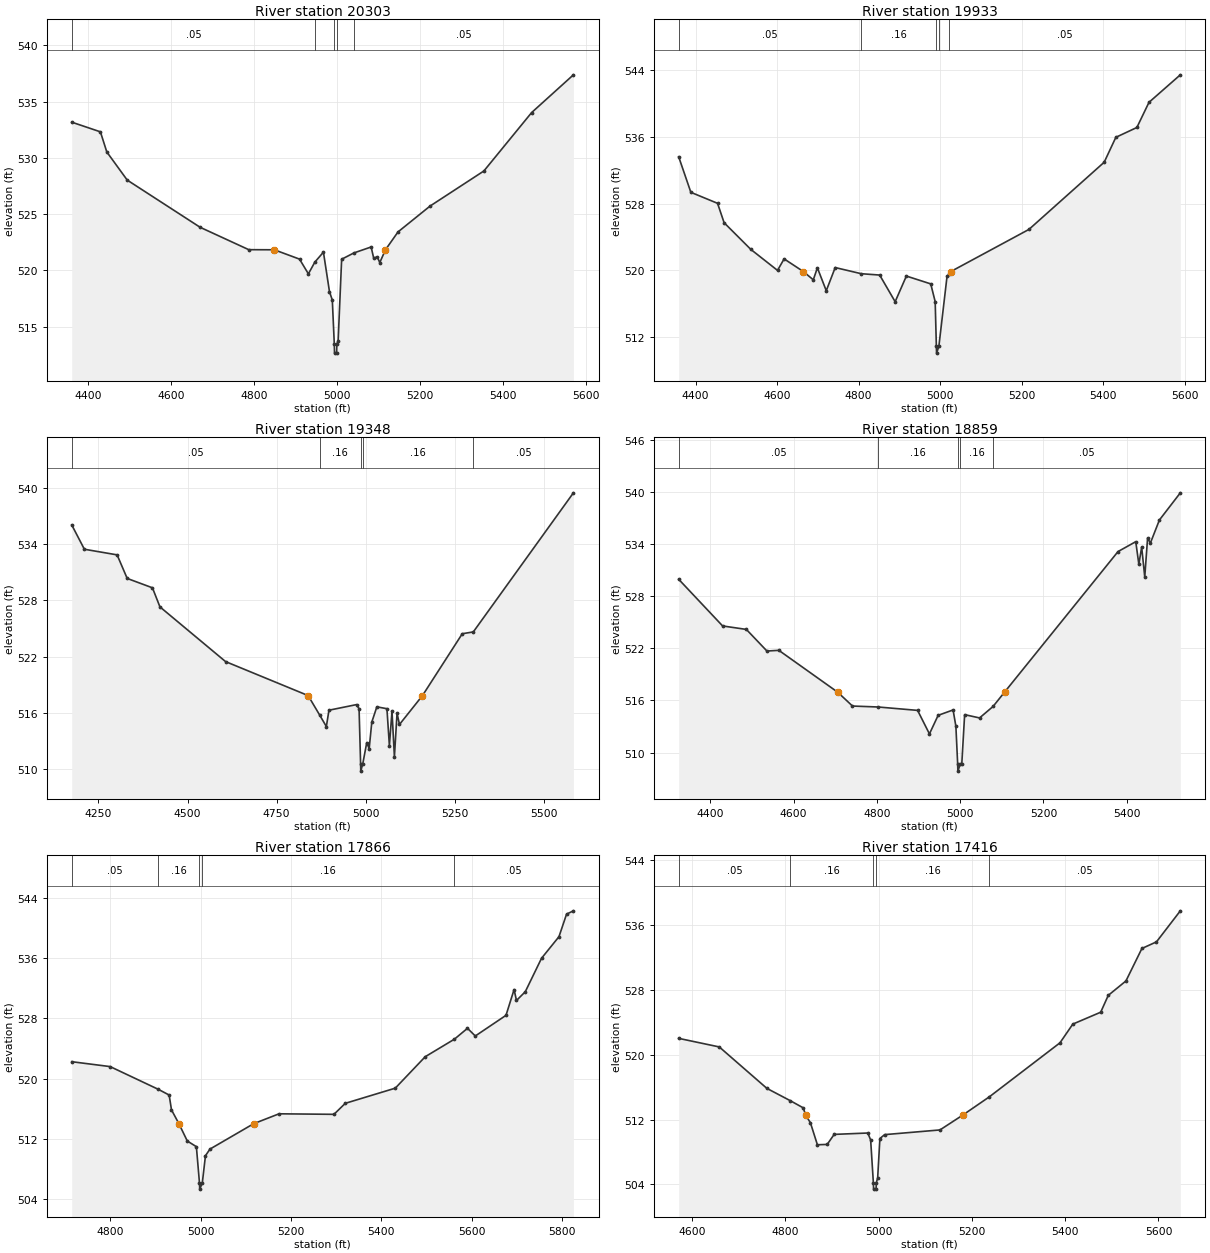
Type RM Length L Ch R = 1,20303,370,370,370
BEGIN DESCRIPTION:
Mapping XS 01c8beb7
END DESCRIPTION:
XS GIS Cut Line= 3
      2758829.11      7058695.93      2758327.50      7058389.39
      2757825.93      7058022.50
#Sta/Elev= 30
  4361.3  533.18  4430.4  532.32  4445.8  530.53  4495.0  528.03  4670.8  523.83
  4788.0  521.84  4849.6  521.83  4910.4  521.00  4931.7  519.69  4947.4  520.74
  4968.0  521.62  4982.6  518.10  4989.4  517.36  4994.2  513.44  4994.7  512.64
  4999.8  512.64  5000.3  513.44  5003.5  513.76  5011.9  520.99  5041.4  521.55
  5083.0  522.08  5089.2  521.08  5097.7  521.21  5103.8  520.69  5117.5  521.83
  5147.8  523.42  5225.1  525.72  5354.8  528.84  5469.8  534.03  5570.6  537.39
#Mann=5,-1,0
  4361.3    0.05       0  4947.4    0.16       0  4994.2    0.07       0
  5000.3    0.16       0  5041.4    0.05       0
Bank Sta=4849.6,5117.5
Exp/Cntr=0.3,0.1

Type RM Length L Ch R = 1,19933,585,585,585
BEGIN DESCRIPTION:
LAKE FORK CREEK TRIB 3 29.0
END DESCRIPTION:
XS GIS Cut Line= 3
      2758975.01      7058325.00      2758425.00      7058025.00
      2757874.96      7057774.98
#Sta/Elev= 30
  4358.7  533.63  4388.6  529.36  4454.1  528.04  4470.2  525.71  4535.7  522.51
  4601.2  519.99  4617.4  521.37  4664.6  519.85  4689.0  518.86  4699.0  520.30
  4720.8  517.55  4742.7  520.33  4806.8  519.59  4851.8  519.43  4889.8  516.23
  4917.3  519.31  4977.1  518.37  4988.0  516.24  4990.9  510.86  4991.4  510.06
  4997.0  510.86  5017.1  519.28  5023.1  519.50  5026.3  519.85  5218.1  524.91
  5402.6  532.97  5431.2  535.96  5482.8  537.14  5512.5  540.16  5589.4  543.46
#Mann=5,-1,0
  4358.7    0.05       0  4806.8    0.16       0  4990.9    0.07       0
  4997.0    0.16       0  5023.1    0.05       0
Bank Sta=4664.6,5026.3
Exp/Cntr=0.3,0.1

Type RM Length L Ch R = 1,19348,489,489,489
BEGIN DESCRIPTION:
LAKE FORK CREEK TRIB 3 28.0
END DESCRIPTION:
XS GIS Cut Line= 3
      2759274.98      7058224.98      2758575.00      7057575.00
      2758125.00      7057525.00
#Sta/Elev= 30
  4175.0  536.03  4210.4  533.44  4302.3  532.84  4330.6  530.33  4401.5  529.33
  4422.5  527.30  4606.7  521.47  4838.4  517.85  4871.2  515.75  4889.6  514.55
  4896.9  516.29  4974.6  516.89  4981.4  516.44  4985.7  510.60  4986.2  509.80
  4991.9  510.60  5002.9  512.83  5009.8  512.20  5017.1  515.02  5031.3  516.65
  5059.6  516.45  5066.5  512.52  5073.8  516.18  5080.6  511.33  5088.0  515.97
  5094.8  514.77  5159.4  517.85  5271.1  524.44  5302.0  524.63  5583.0  539.45
#Mann=5,-1,0
  4175.0    0.05       0  4871.2    0.16       0  4985.7    0.07       0
  4991.9    0.16       0  5302.0    0.05       0
Bank Sta=4838.4,5159.4
Exp/Cntr=0.3,0.1

Type RM Length L Ch R = 1,18859,993,993,993
BEGIN DESCRIPTION:
LAKE FORK CREEK TRIB 3 27.0
END DESCRIPTION:
XS GIS Cut Line= 3
      2759247.14      7057831.83      2758947.13      7057481.82
      2758447.13      7056931.82
#Sta/Elev= 30
  4324.2  529.97  4429.7  524.59  4486.7  524.19  4536.1  521.70  4564.7  521.78
  4705.9  516.96  4741.5  515.36  4803.2  515.25  4897.8  514.86  4926.2  512.15
  4947.1  514.29  4983.0  514.91  4989.7  513.03  4994.0  508.66  4994.5  507.86
  5000.2  508.66  5003.9  508.72  5010.7  514.37  5046.5  513.99  5078.9  515.31
  5106.5  516.96  5378.9  533.16  5421.5  534.30  5428.9  531.70  5435.7  533.68
  5443.1  530.23  5449.9  534.73  5456.6  534.14  5478.3  536.80  5528.5  539.93
#Mann=5,-1,0
  4324.2    0.05       0  4803.2    0.16       0  4994.0    0.07       0
  5000.2    0.16       0  5078.9    0.05       0
Bank Sta=4705.9,5106.5
Exp/Cntr=0.3,0.1

Type RM Length L Ch R = 1,17866,450,450,450
BEGIN DESCRIPTION:
LAKE FORK CREEK TRIB 3 26.0
END DESCRIPTION:
XS GIS Cut Line= 3
      2759539.72      7057061.08      2759145.73      7057023.34
      2758475.03      7056775.01
#Sta/Elev= 30
  4714.5  522.25  4799.6  521.60  4906.4  518.58  4930.2  517.83  4935.4  515.86
  4951.9  514.02  4970.4  511.73  4990.5  510.98  4997.4  506.15  4997.9  505.35
  5003.6  506.15  5010.6  509.78  5020.6  510.66  5117.1  514.02  5173.6  515.34
  5295.2  515.27  5320.3  516.73  5431.0  518.74  5497.3  522.91  5562.0  525.24
  5590.9  526.68  5608.2  525.66  5676.2  528.40  5694.1  531.82  5699.4  530.37
  5718.9  531.53  5754.9  535.97  5793.5  538.83  5810.3  541.82  5825.5  542.26
#Mann=5,-1,0
  4714.5    0.05       0  4906.4    0.16       0  4997.4    0.07       0
  5003.6    0.16       0  5562.0    0.05       0
Bank Sta=4951.9,5117.1
Exp/Cntr=0.3,0.1

Type RM Length L Ch R = 1,17416,469,469,469
BEGIN DESCRIPTION:
LAKE FORK CREEK TRIB 3 25.0
END DESCRIPTION:
XS GIS Cut Line= 3
      2759586.13      7057065.68      2759344.64      7056703.45
      2758782.65      7056396.91
#Sta/Elev= 30
  4571.4  522.03  4658.5  520.97  4760.6  515.85  4811.1  514.32  4838.7  513.44
  4843.4  512.55  4853.8  511.62  4868.8  508.89  4889.8  508.93  4904.8  510.17
  4976.9  510.34  4983.0  509.48  4988.8  504.21  4989.3  503.41  4994.6  503.41
  4995.1  504.21  4998.0  504.77  5002.8  509.66  5013.0  510.14  5131.6  510.72
  5180.4  512.55  5237.5  514.81  5388.9  521.48  5416.4  523.79  5476.2  525.26
  5492.4  527.34  5530.3  529.12  5564.5  533.13  5595.8  533.95  5646.9  537.78
#Mann=5,-1,0
  4571.4    0.05       0  4811.1    0.16       0  4988.8    0.07       0
  4995.1    0.16       0  5237.5    0.05       0
Bank Sta=4843.4,5180.4
Exp/Cntr=0.3,0.1

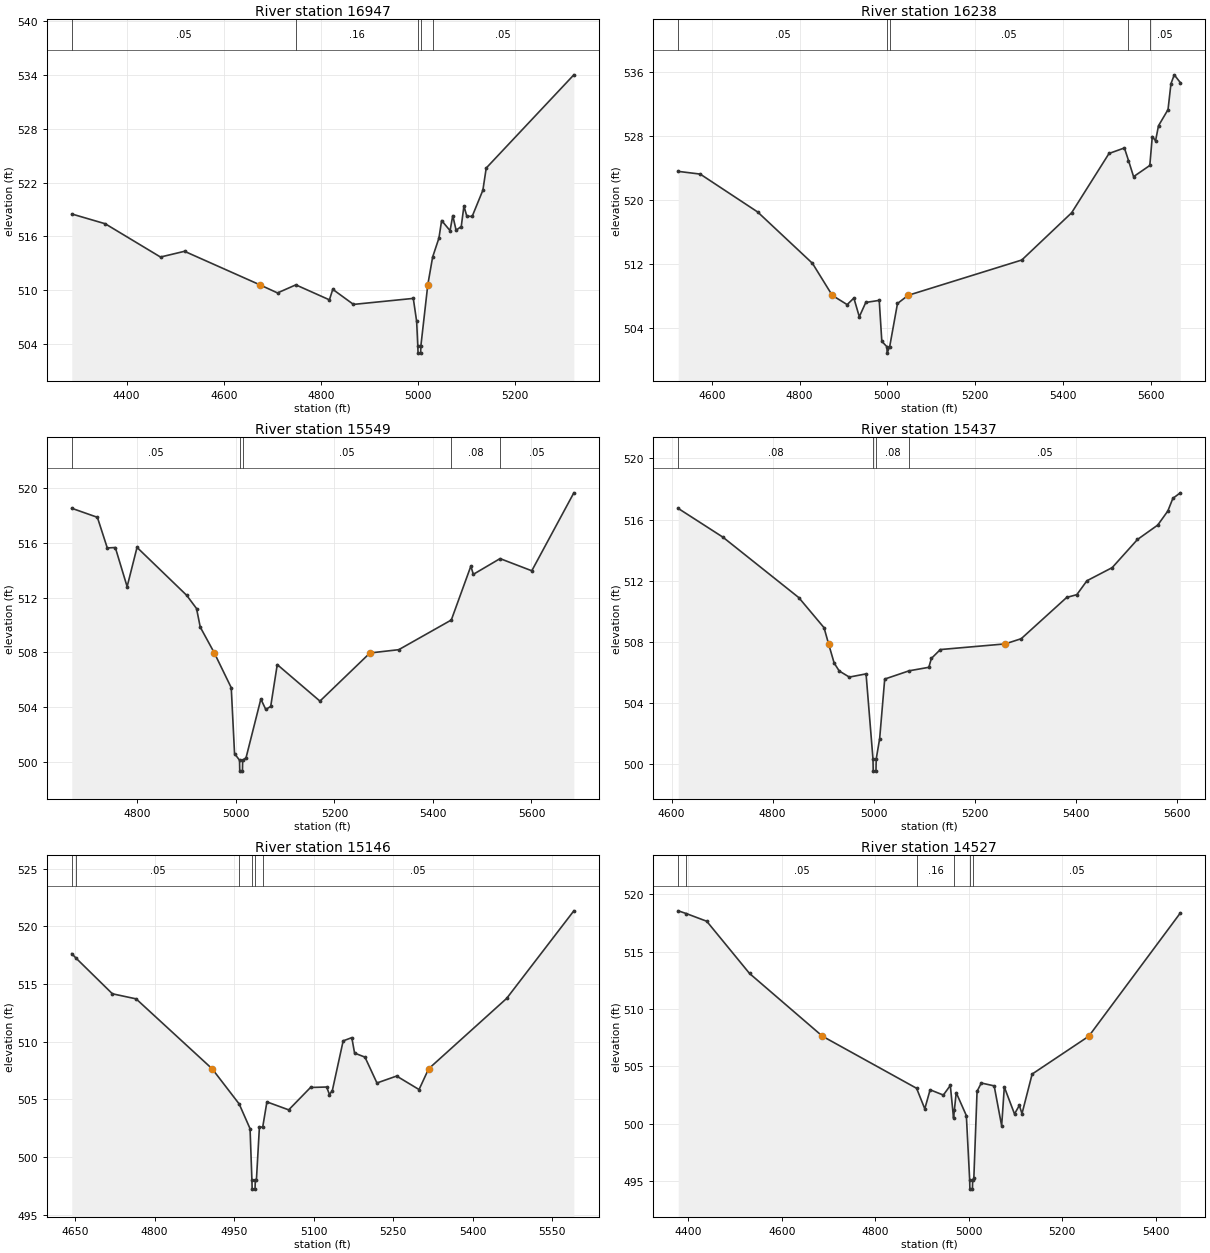
Type RM Length L Ch R = 1,16947,709,709,709
BEGIN DESCRIPTION:
LAKE FORK CREEK TRIB 3 24.0
END DESCRIPTION:
XS GIS Cut Line= 3
      2759967.92      7056758.78      2759441.88      7056321.27
      2759125.01      7056175.01
#Sta/Elev= 30
  4287.2  518.51  4356.0  517.42  4469.8  513.71  4519.2  514.35  4673.6  510.63
  4710.6  509.71  4748.3  510.61  4817.4  508.94  4824.3  510.11  4866.9  508.43
  4990.0  509.10  4996.9  506.55  4999.3  503.80  4999.8  503.00  5005.1  503.00
  5005.6  503.80  5019.9  510.63  5029.8  513.71  5042.8  515.83  5048.3  517.78
  5065.7  516.65  5071.2  518.33  5078.1  516.70  5088.7  517.11  5094.2  519.40
  5100.1  518.27  5111.1  518.23  5133.2  521.16  5140.1  523.63  5320.4  534.02
#Mann=5,-1,0
  4287.2    0.05       0  4748.3    0.16       0  4999.3    0.07       0
  5005.6    0.16       0  5029.8    0.05       0
Bank Sta=4673.6,5019.9
Exp/Cntr=0.3,0.1

Type RM Length L Ch R = 1,16238,689,689,689
BEGIN DESCRIPTION:
LAKE FORK CREEK TRIB 3 23.0
END DESCRIPTION:
XS GIS Cut Line= 3
      2760374.97      7056324.98      2759975.00      7056075.00
      2759475.03      7055625.03
#Sta/Elev= 30
  4523.4  523.54  4573.5  523.20  4704.4  518.46  4829.4  512.03  4874.4  508.03
  4908.4  506.87  4923.7  507.69  4936.1  505.35  4950.8  507.14  4981.5  507.40
  4987.4  502.28  4999.0  501.60  4999.5  500.80  5005.3  501.60  5023.1  507.01
  5047.3  508.03  5306.4  512.45  5420.0  518.36  5505.2  525.78  5540.3  526.47
  5549.6  524.90  5561.2  522.88  5598.2  524.28  5603.8  527.90  5611.3  527.37
  5618.0  529.25  5639.7  531.27  5646.4  534.51  5653.9  535.62  5667.7  534.65
#Mann=5,-1,0
  4523.4    0.05       0  4999.0    0.03       0  5005.3    0.05       0
  5549.6    0.08       0  5598.2    0.05       0
Bank Sta=4874.4,5047.3
Exp/Cntr=0.3,0.1

Type RM Length L Ch R = 1,15549,112,112,112
BEGIN DESCRIPTION:
Mapping XS 047eeaa7
END DESCRIPTION:
XS GIS Cut Line= 3
      2760726.63      7055780.31      2760396.74      7055742.11
      2759709.65      7055724.76
#Sta/Elev= 30
  4666.7  518.54  4718.7  517.88  4738.8  515.64  4755.1  515.67  4779.1  512.81
  4799.2  515.68  4899.9  512.18  4920.0  511.21  4927.6  509.85  4956.2  507.96
  4990.5  505.42  4997.2  500.60  5007.3  500.12  5007.8  499.32  5013.2  499.32
  5013.7  500.12  5020.5  500.29  5050.6  504.59  5060.6  503.83  5070.6  504.05
  5083.9  507.11  5170.6  504.44  5272.1  507.96  5330.6  508.20  5437.3  510.37
  5477.0  514.31  5482.0  513.71  5536.3  514.86  5600.7  513.97  5686.1  519.67
#Mann=5,-1,0
  4666.7    0.05       0  5007.3    0.04       0  5013.7    0.05       0
  5437.3    0.08       0  5536.3    0.05       0
Bank Sta=4956.2,5272.1
Exp/Cntr=0.3,0.1

Type RM Length L Ch R = 1,15437,291,291,291
BEGIN DESCRIPTION:
Mapping XS e10b195b
END DESCRIPTION:
XS GIS Cut Line= 3
      2760813.38      7055644.88      2760441.88      7055641.41
      2759820.34      7055634.47
#Sta/Elev= 30
  4613.2  516.73  4701.6  514.85  4851.6  510.90  4901.6  508.93  4910.6  507.87
  4921.6  506.62  4931.6  506.10  4951.6  505.70  4984.7  505.91  4998.4  500.35
  4998.9  499.55  5004.3  499.55  5004.8  500.35  5011.6  501.67  5021.6  505.57
  5069.8  506.11  5108.9  506.34  5113.9  506.92  5131.6  507.50  5259.8  507.87
  5291.6  508.21  5381.6  510.91  5401.6  511.09  5421.6  512.00  5471.6  512.86
  5521.6  514.70  5561.6  515.64  5581.6  516.56  5591.6  517.39  5606.3  517.75
#Mann=4,-1,0
  4613.2    0.08       0  4998.4    0.07       0  5004.8    0.08       0
  5069.8    0.05       0
Bank Sta=4910.6,5259.8
Exp/Cntr=0.3,0.1

Type RM Length L Ch R = 1,15146,619,619,619
BEGIN DESCRIPTION:
Mapping XS 11c0fd24
END DESCRIPTION:
XS GIS Cut Line= 3
      2760896.70      7055610.14      2760608.54      7055422.66
      2760021.73      7055283.77
#Sta/Elev= 30
  4643.7  517.64  4651.1  517.28  4720.3  514.16  4765.0  513.72  4908.4  507.66
  4959.4  504.61  4979.9  502.47  4983.4  498.03  4983.9  497.23  4989.3  497.23
  4989.8  498.03  4991.9  498.03  4997.6  502.64  5003.7  502.59  5011.7  504.79
  5052.8  504.10  5093.9  506.04  5124.4  506.08  5129.6  505.43  5135.0  505.76
  5155.5  510.08  5171.8  510.36  5177.0  509.02  5196.6  508.67  5219.2  506.43
  5256.3  507.03  5298.6  505.86  5316.7  507.66  5463.8  513.76  5590.5  521.35
#Mann=6,-1,0
  4643.7    0.08       0  4651.1    0.05       0  4959.4    0.16       0
  4983.4    0.07       0  4989.8    0.16       0  5003.7    0.05       0
Bank Sta=4908.4,5316.7
Exp/Cntr=0.3,0.1

Type RM Length L Ch R = 1,14527,607,607,607
BEGIN DESCRIPTION:
LAKE FORK CREEK TRIB 3 20.0
END DESCRIPTION:
XS GIS Cut Line= 3
      2760975.00      7055625.00      2760875.00      7055075.00
      2760625.00      7054625.00
#Sta/Elev= 30
  4378.6  518.56  4395.9  518.32  4439.6  517.65  4531.1  513.10  4687.0  507.63
  4888.4  503.09  4905.9  501.30  4917.3  502.96  4945.6  502.50  4960.5  503.34
  4967.4  500.49  4969.2  501.19  4973.1  502.71  4994.8  500.71  5001.9  495.10
  5002.4  494.30  5007.8  494.30  5008.3  495.10  5010.8  495.24  5017.7  502.83
  5026.8  503.55  5054.3  503.30  5070.3  499.82  5076.0  503.20  5097.8  500.85
  5108.1  501.60  5113.8  500.88  5135.5  504.33  5256.7  507.63  5452.4  518.37
#Mann=6,-1,0
  4378.6    0.08       0  4395.9    0.05       0  4888.4    0.16       0
  4969.2    0.05       0  5001.9    0.03       0  5008.3    0.05       0
Bank Sta=4687,5256.7
Exp/Cntr=0.3,0.1

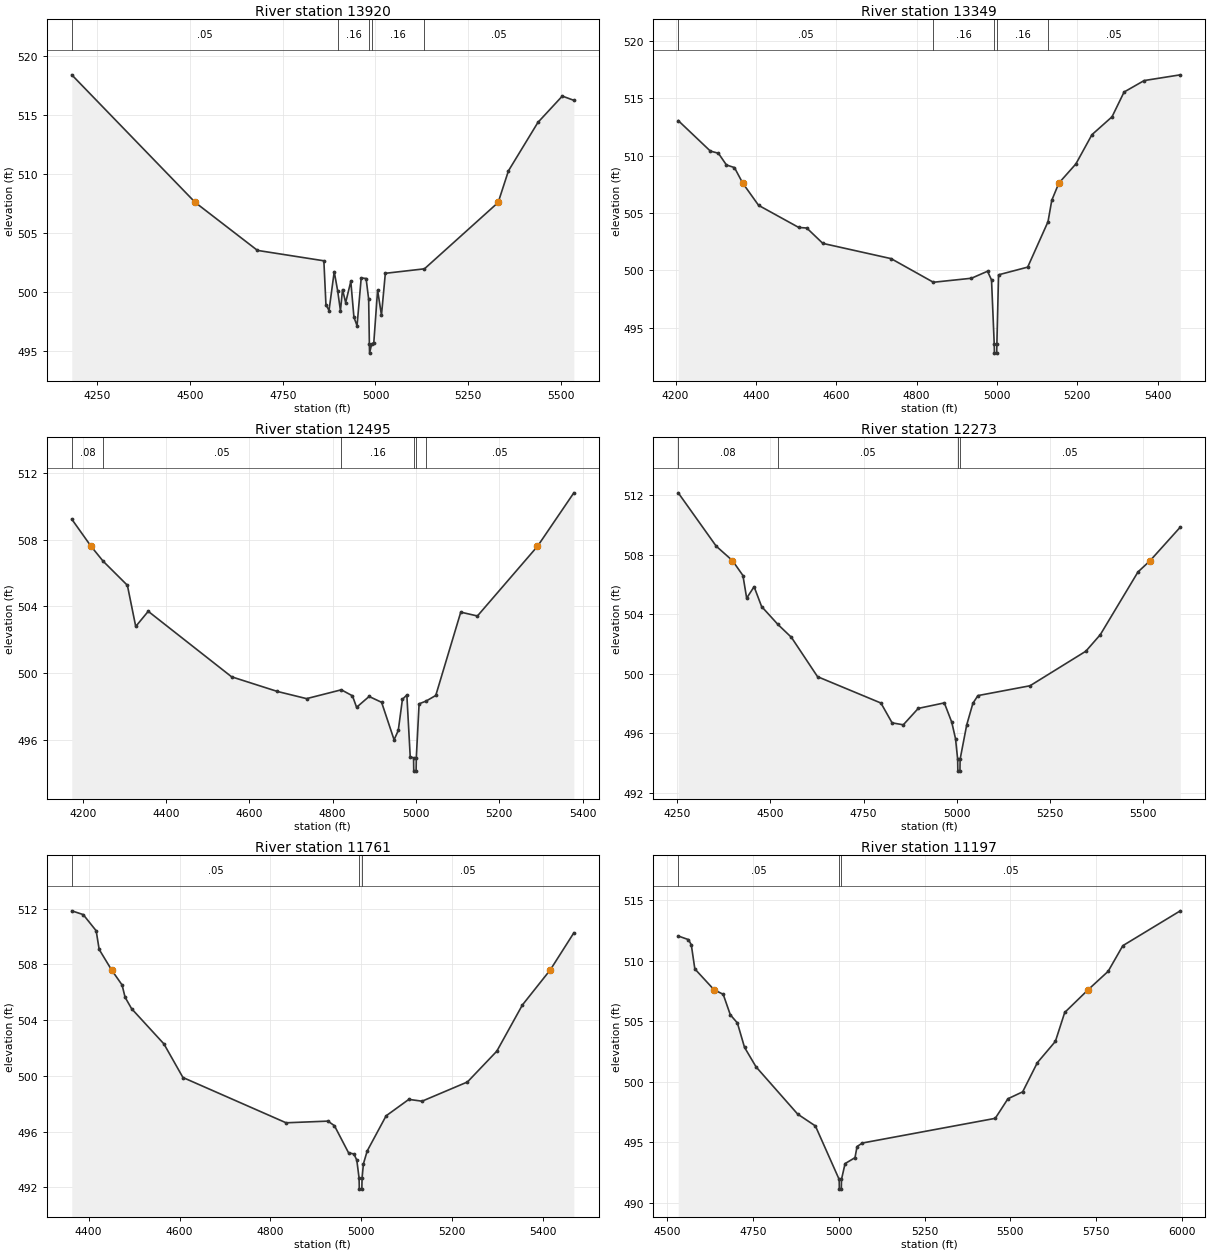
Type RM Length L Ch R = 1,13920,571,571,571
BEGIN DESCRIPTION:
LAKE FORK CREEK TRIB 3 19.0
END DESCRIPTION:
XS GIS Cut Line= 3
      2761574.98      7055574.97      2761225.00      7054875.00
      2761375.01      7054324.98
#Sta/Elev= 30
  4181.7  518.42  4514.4  507.61  4682.0  503.55  4860.9  502.67  4866.5  498.95
  4874.8  498.46  4888.8  501.75  4898.0  500.14  4905.6  498.44  4911.2  500.23
  4919.6  499.13  4933.5  500.93  4941.9  497.89  4950.3  497.17  4961.5  501.22
  4974.7  501.17  4981.6  499.41  4983.5  495.65  4984.0  494.85  4990.0  495.65
  4995.4  495.72  5005.7  500.19  5016.1  498.06  5026.5  501.61  5131.9  501.99
  5330.5  507.61  5358.2  510.29  5437.6  514.39  5503.3  516.62  5534.4  516.26
#Mann=5,-1,0
  4181.7    0.05       0  4898.0    0.16       0  4983.5    0.07       0
  4990.0    0.16       0  5131.9    0.05       0
Bank Sta=4514.4,5330.5
Exp/Cntr=0.3,0.1

Type RM Length L Ch R = 1,13349,854,854,854
BEGIN DESCRIPTION:
LAKE FORK CREEK TRIB 3 18.0
END DESCRIPTION:
XS GIS Cut Line= 3
      2761675.00      7055424.97      2761675.00      7054625.00
      2761675.00      7054174.97
#Sta/Elev= 30
  4206.6  513.06  4286.6  510.40  4306.6  510.21  4326.6  509.19  4346.6  508.96
  4367.1  507.61  4406.6  505.67  4506.6  503.74  4526.6  503.69  4566.6  502.35
  4736.6  501.02  4841.8  498.96  4936.6  499.31  4976.6  499.92  4986.6  499.16
  4993.3  493.58  4993.8  492.78  4999.4  492.78  4999.9  493.58  5004.1  499.61
  5076.6  500.28  5127.2  504.24  5136.6  506.11  5154.3  507.61  5196.6  509.28
  5236.6  511.83  5286.6  513.39  5316.6  515.55  5366.6  516.55  5456.6  517.05
#Mann=5,-1,0
  4206.6    0.05       0  4841.8    0.16       0  4993.3    0.07       0
  4999.9    0.16       0  5127.2    0.05       0
Bank Sta=4367.1,5154.3
Exp/Cntr=0.3,0.1

Type RM Length L Ch R = 1,12495,222,222,222
BEGIN DESCRIPTION:
Mapping XS 79fa61e6
END DESCRIPTION:
XS GIS Cut Line= 3
      2762150.21      7055318.53      2762139.79      7054502.52
      2762143.26      7054113.61
#Sta/Elev= 30
  4173.9  509.23  4220.2  507.60  4249.1  506.71  4307.4  505.26  4327.4  502.79
  4357.4  503.70  4557.5  499.77  4667.5  498.89  4737.5  498.46  4820.8  498.99
  4847.5  498.63  4857.5  497.94  4887.5  498.59  4917.5  498.24  4947.5  495.99
  4957.5  496.55  4967.5  498.42  4978.1  498.68  4986.2  494.97  4994.2  494.91
  4994.7  494.11  5000.3  494.11  5000.8  494.91  5007.5  498.15  5024.0  498.31
  5047.5  498.65  5107.5  503.65  5147.5  503.42  5291.6  507.60  5378.9  510.81
#Mann=6,-1,0
  4173.9    0.08       0  4249.1    0.05       0  4820.8    0.16       0
  4994.2    0.07       0  5000.8    0.16       0  5024.0    0.05       0
Bank Sta=4220.2,5291.6
Exp/Cntr=0.3,0.1

Type RM Length L Ch R = 1,12273,512,512,512
BEGIN DESCRIPTION:
Mapping XS 066eaf4b
END DESCRIPTION:
XS GIS Cut Line= 3
      2762233.54      7055318.46      2762282.15      7054526.83
      2762278.68      7053971.27
#Sta/Elev= 30
  4252.2  512.15  4354.2  508.57  4397.9  507.60  4426.0  506.60  4436.0  505.08
  4456.0  505.85  4476.1  504.52  4519.8  503.32  4556.2  502.45  4626.4  499.81
  4796.7  498.04  4826.7  496.71  4856.8  496.58  4896.9  497.68  4967.0  498.05
  4987.0  496.75  4997.1  495.64  5002.8  494.27  5003.3  493.47  5008.9  493.47
  5009.4  494.27  5027.1  496.57  5043.7  498.02  5057.2  498.54  5197.2  499.20
  5347.2  501.52  5386.0  502.63  5487.2  506.84  5519.9  507.60  5600.9  509.85
#Mann=4,-1,0
  4252.2    0.08       0  4519.8    0.05       0  5002.8    0.03       0
  5009.4    0.05       0
Bank Sta=4397.9,5519.9
Exp/Cntr=0.3,0.1

Type RM Length L Ch R = 1,11761,564,564,564
BEGIN DESCRIPTION:
LAKE FORK CREEK TRIB 3 15.0
END DESCRIPTION:
XS GIS Cut Line= 3
      2763046.07      7054759.50      2762646.74      7054297.66
      2762349.08      7053903.09
#Sta/Elev= 30
  4362.9  511.84  4388.1  511.57  4416.6  510.41  4423.2  509.07  4450.5  507.60
  4473.6  506.52  4480.2  505.64  4494.5  504.82  4565.7  502.29  4607.5  499.88
  4834.5  496.63  4926.6  496.75  4940.9  496.42  4971.9  494.48  4983.8  494.39
  4990.1  493.95  4995.1  492.67  4995.6  491.87  5001.2  491.87  5001.7  492.67
  5004.7  493.69  5013.0  494.61  5054.6  497.13  5104.6  498.31  5133.7  498.18
  5233.6  499.56  5298.2  501.77  5354.4  505.08  5415.8  507.60  5467.7  510.26
#Mann=3,-1,0
  4362.9    0.05       0  4995.1    0.03       0  5001.7    0.05       0
Bank Sta=4450.5,5415.8
Exp/Cntr=0.3,0.1

Type RM Length L Ch R = 1,11197,400,400,400
BEGIN DESCRIPTION:
Mapping XS 5f07610f
END DESCRIPTION:
XS GIS Cut Line= 3
      2763146.74      7054651.86      2763032.15      7054214.33
      2762514.70      7053345.31
#Sta/Elev= 30
  4531.7  512.04  4561.5  511.74  4569.8  511.31  4580.1  509.32  4636.0  507.60
  4662.8  507.22  4683.5  505.53  4704.2  504.85  4724.9  502.84  4758.4  501.23
  4879.9  497.32  4931.6  496.34  5000.9  491.92  5001.4  491.12  5007.1  491.12
  5007.6  491.92  5018.1  493.23  5047.0  493.72  5053.0  494.64  5068.4  494.93
  5455.9  496.97  5492.9  498.59  5535.8  499.16  5578.6  501.57  5631.2  503.33
  5658.4  505.72  5726.7  507.60  5785.0  509.12  5827.8  511.24  5995.4  514.12
#Mann=3,-1,0
  4531.7    0.05       0  5000.9    0.03       0  5007.6    0.05       0
Bank Sta=4636,5726.7
Exp/Cntr=0.3,0.1

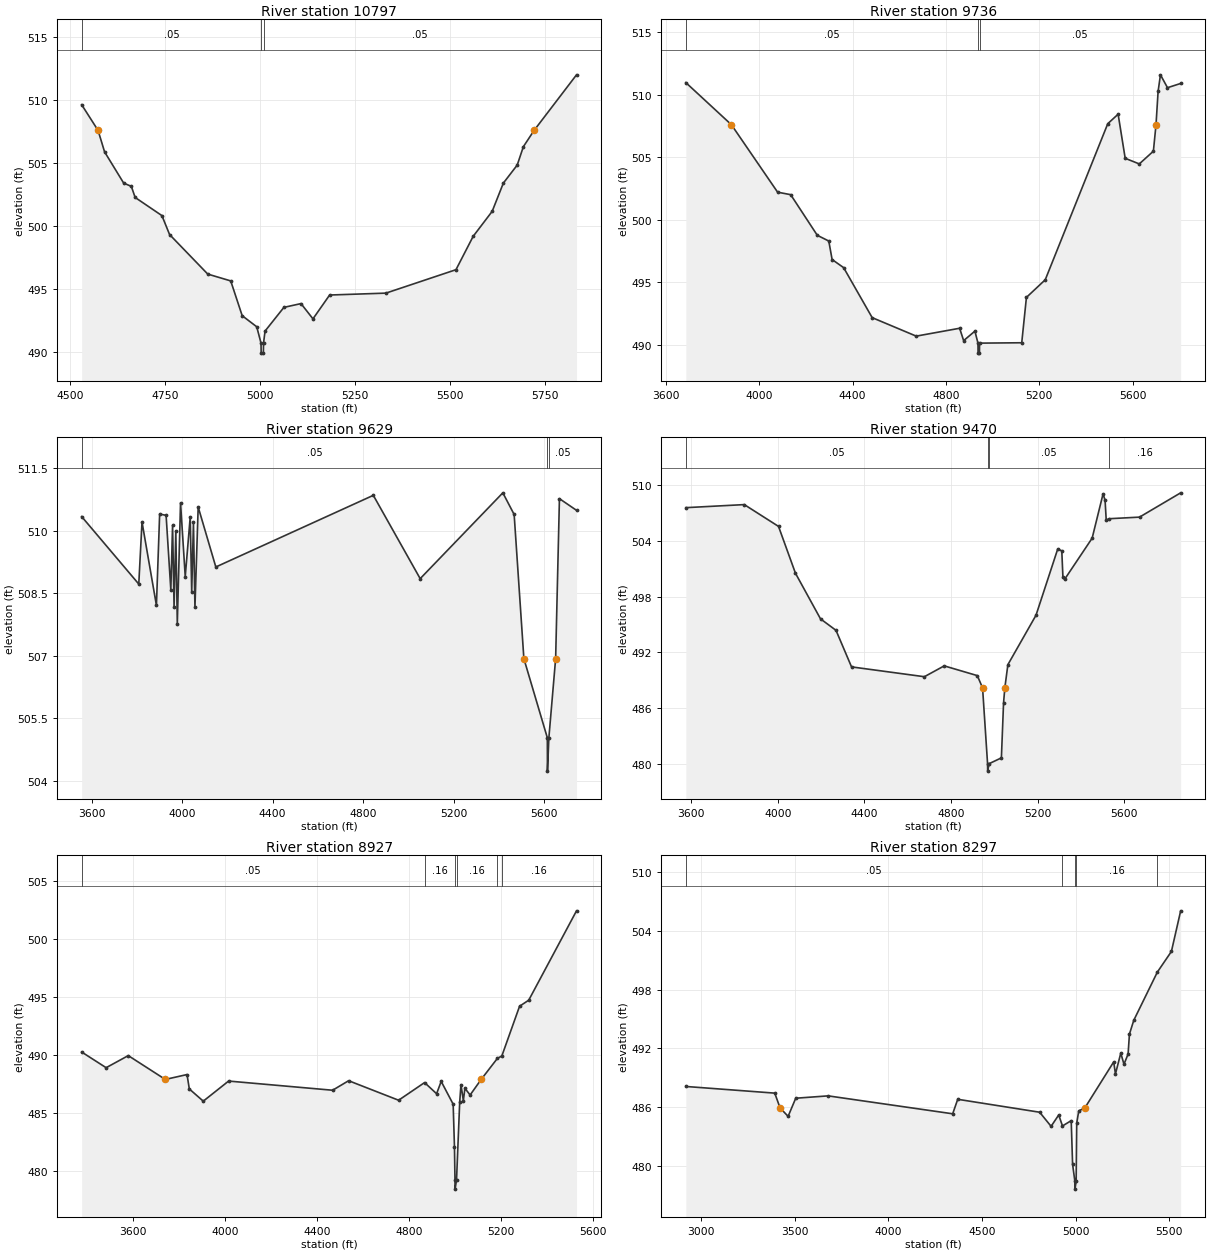
Type RM Length L Ch R = 1,10797,1061,1061,1061
BEGIN DESCRIPTION:
LAKE FORK CREEK TRIB 3 14.0
END DESCRIPTION:
XS GIS Cut Line= 3
      2763375.00      7054474.97      2763325.00      7054025.00
      2762925.02      7053275.04
#Sta/Elev= 30
  4530.1  509.64  4573.3  507.60  4590.4  505.90  4640.7  503.42  4660.9  503.16
  4670.9  502.28  4741.4  500.84  4761.5  499.34  4862.1  496.20  4922.5  495.66
  4952.7  492.90  4991.0  492.02  5002.2  490.73  5002.7  489.93  5008.4  489.93
  5008.9  490.73  5012.9  491.68  5062.5  493.56  5107.5  493.86  5139.0  492.65
  5182.9  494.54  5331.0  494.69  5515.5  496.55  5560.8  499.20  5610.8  501.18
  5640.2  503.42  5676.7  504.85  5692.9  506.31  5721.1  507.60  5832.8  512.01
#Mann=3,-1,0
  4530.1    0.05       0  5002.2    0.03       0  5008.9    0.05       0
Bank Sta=4573.3,5721.1
Exp/Cntr=0.3,0.1

Type RM Length L Ch R = 1,9736,107,107,107
BEGIN DESCRIPTION:
Mapping XS 39bf9807
END DESCRIPTION:
XS GIS Cut Line= 5
      2763480.05      7054554.63      2763964.44      7053992.11
      2764068.61      7053606.69      2764131.11      7053330.65
      2764219.52      7052638.99
#Sta/Elev= 30
  3684.5  510.97  3879.9  507.60  4078.1  502.20  4134.1  502.00  4248.2  498.75
  4297.5  498.29  4311.8  496.81  4361.2  496.16  4483.6  492.16  4672.5  490.68
  4858.6  491.31  4875.8  490.32  4924.1  491.08  4937.2  490.12  4937.7  489.32
  4943.5  489.32  4944.0  490.12  5124.9  490.15  5145.0  493.78  5225.7  495.19
  5493.8  507.68  5538.2  508.44  5568.5  504.91  5629.0  504.46  5689.4  505.48
  5700.7  507.60  5709.6  510.26  5719.7  511.59  5749.9  510.56  5806.4  510.90
#Mann=3,-1,0
  3684.5    0.05       0  4937.2    0.03       0  4944.0    0.05       0
Bank Sta=3879.9,5700.7
Exp/Cntr=0.3,0.1

Type RM Length L Ch R = 1,9629,159,159,159
BEGIN DESCRIPTION:
Mapping XS 58ed1327
END DESCRIPTION:
XS GIS Cut Line= 6
      2763526.93      7054632.75      2763927.99      7054158.77
      2764079.03      7053971.27      2764110.28      7053856.69
      2764292.57      7053023.36      2764276.96      7052669.57
#Sta/Elev= 30
  3556.0  510.34  3808.5  508.72  3822.8  510.21  3886.5  508.21  3900.8  510.40
  3929.3  510.37  3950.2  508.58  3957.9  510.13  3964.5  508.17  3972.2  510.00
  3978.8  507.77  3993.1  510.67  4013.9  508.90  4035.9  510.33  4042.5  508.53
  4050.2  510.20  4056.8  508.16  4071.1  510.57  4149.1  509.13  4845.3  510.85
  5052.5  508.85  5417.9  510.91  5467.9  510.39  5510.9  506.93  5614.6  505.03
  5615.1  504.23  5621.4  505.03  5651.3  506.93  5668.1  510.77  5743.6  510.49
#Mann=3,-1,0
  3556.0    0.05       0  5614.6    0.03       0  5621.4    0.05       0
Bank Sta=5510.9,5651.3
Exp/Cntr=0.3,0.1

Type RM Length L Ch R = 1,9470,543,543,543
BEGIN DESCRIPTION:
Mapping XS 9e2f41c8
END DESCRIPTION:
XS GIS Cut Line= 6
      2763766.51      7054622.34      2764250.90      7053919.19
      2764360.28      7053361.90      2764360.28      7053075.44
      2764438.40      7052825.44      2764417.64      7052508.87
#Sta/Elev= 30
  3574.3  507.59  3844.6  507.92  4002.8  505.57  4081.1  500.52  4196.9  495.60
  4268.6  494.36  4340.3  490.42  4677.0  489.36  4768.7  490.53  4921.6  489.48
  4946.0  488.16  4969.1  479.98  4969.6  479.18  4975.9  479.98  5033.0  480.61
  5043.0  486.53  5048.9  488.16  5063.0  490.66  5193.0  495.99  5293.5  503.14
  5312.2  502.93  5317.4  500.12  5324.9  499.85  5452.5  504.30  5503.0  509.08
  5512.3  508.38  5517.5  506.27  5532.3  506.40  5671.5  506.57  5861.7  509.19
#Mann=4,-1,0
  3574.3    0.05       0  4969.1    0.03       0  4975.9    0.05       0
  5532.3    0.16       0
Bank Sta=4946,5048.9
Exp/Cntr=0.3,0.1

Type RM Length L Ch R = 1,8927,630,630,630
BEGIN DESCRIPTION:
Mapping XS 0b36287e
END DESCRIPTION:
XS GIS Cut Line= 3
      2764620.96      7054750.97      2764770.43      7053161.38
      2764530.87      7052661.42
#Sta/Elev= 30
  3376.8  490.26  3483.2  488.91  3579.4  489.95  3740.4  487.90  3834.8  488.32
  3844.8  487.08  3905.4  486.03  4015.6  487.76  4467.6  486.97  4537.2  487.79
  4754.5  486.11  4867.4  487.63  4919.6  486.67  4939.6  487.73  4991.6  485.77
  4997.3  482.09  4999.5  479.26  5000.0  478.46  5006.3  479.26  5020.0  485.93
  5025.5  487.45  5035.9  486.08  5042.7  487.14  5065.3  486.56  5113.4  487.90
  5183.8  489.71  5203.2  489.92  5280.3  494.20  5320.1  494.72  5527.8  502.41
#Mann=6,-1,0
  3376.8    0.05       0  4867.4    0.16       0  4999.5    0.07       0
  5006.3    0.16       0  5183.8    0.05       0  5203.2    0.16       0
Bank Sta=3740.4,5113.4
Exp/Cntr=0.3,0.1

Type RM Length L Ch R = 1,8297,578,578,578
BEGIN DESCRIPTION:
Mapping XS 0a77758a
END DESCRIPTION:
XS GIS Cut Line= 3
      2764693.88      7054771.77      2765072.52      7052781.17
      2764817.59      7052219.29
#Sta/Elev= 30
  2918.4  488.11  3393.5  487.43  3421.8  485.92  3464.8  485.06  3505.5  486.91
  3678.6  487.15  4343.9  485.32  4370.8  486.80  4808.5  485.48  4869.5  484.04
  4910.3  485.20  4930.4  484.08  4977.0  484.62  4984.4  480.16  4996.6  478.43
  4997.1  477.63  5003.4  478.43  5006.4  484.37  5017.4  485.62  5049.8  485.92
  5204.0  490.62  5213.3  489.39  5241.8  491.51  5258.9  490.38  5280.9  491.42
  5288.0  493.45  5311.1  494.86  5437.3  499.79  5512.2  501.89  5561.7  506.04
#Mann=5,-1,0
  2918.4    0.05       0  4930.4    0.16       0  4996.6    0.07       0
  5003.4    0.16       0  5437.3    0.05       0
Bank Sta=3421.8,5049.8
Exp/Cntr=0.3,0.1