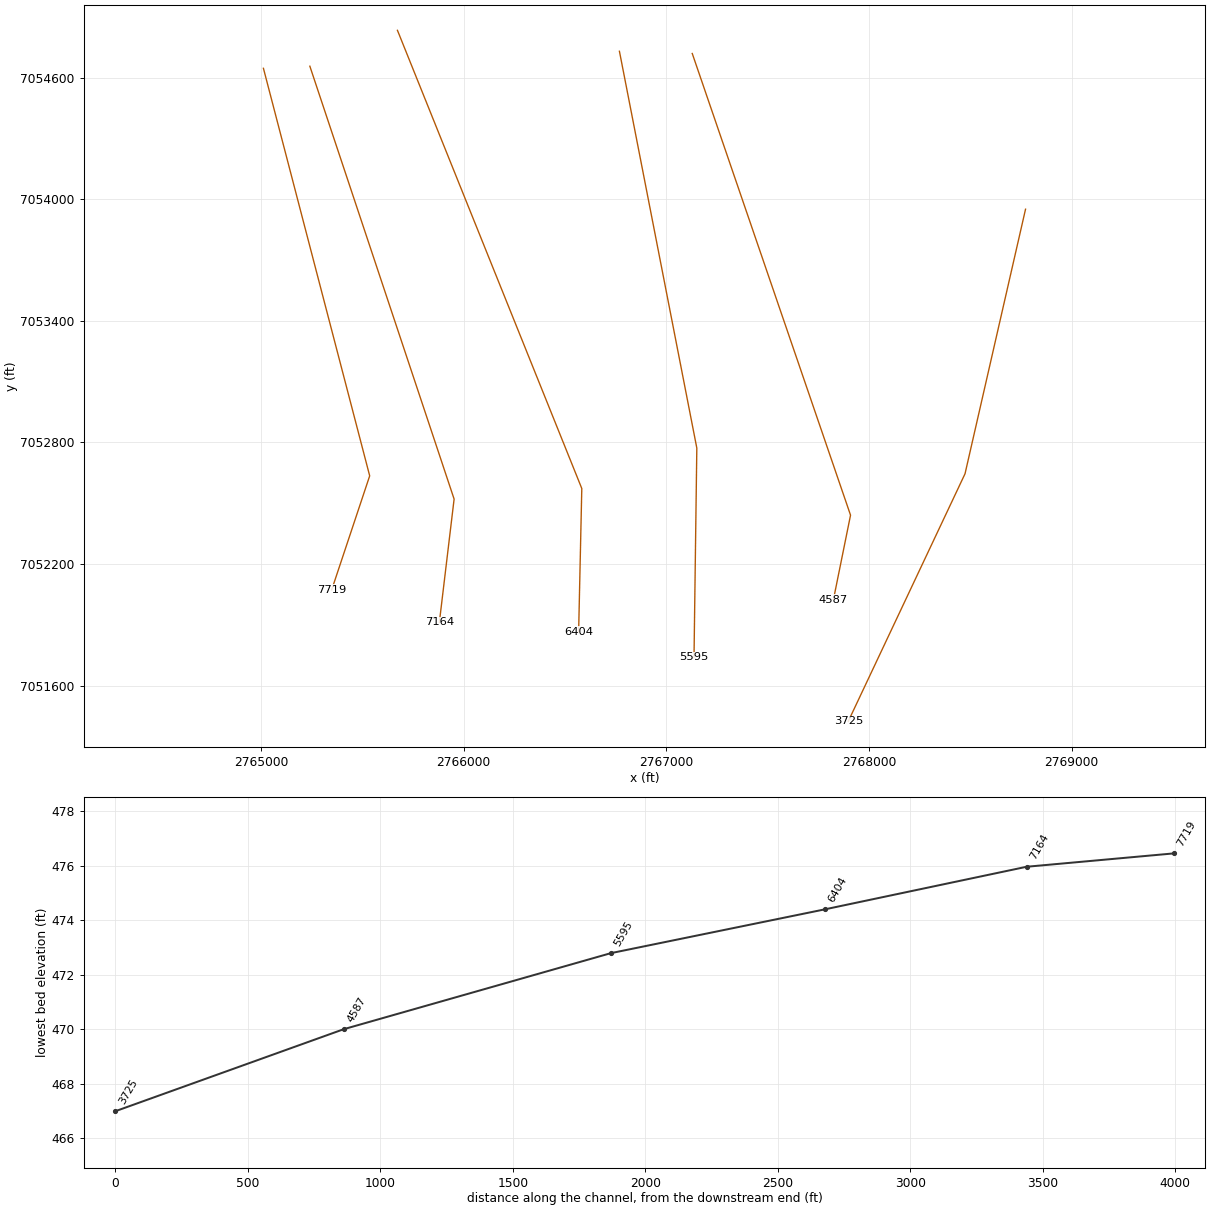
HEC-RAS study LAKE FORK CREEK TRIB 3.prj: LAKE FORK CREEK TRIB 3 Base Level Engineering

--- LAKE FORK CREEK TRIB 3.g01 (geometry) --- (continued)

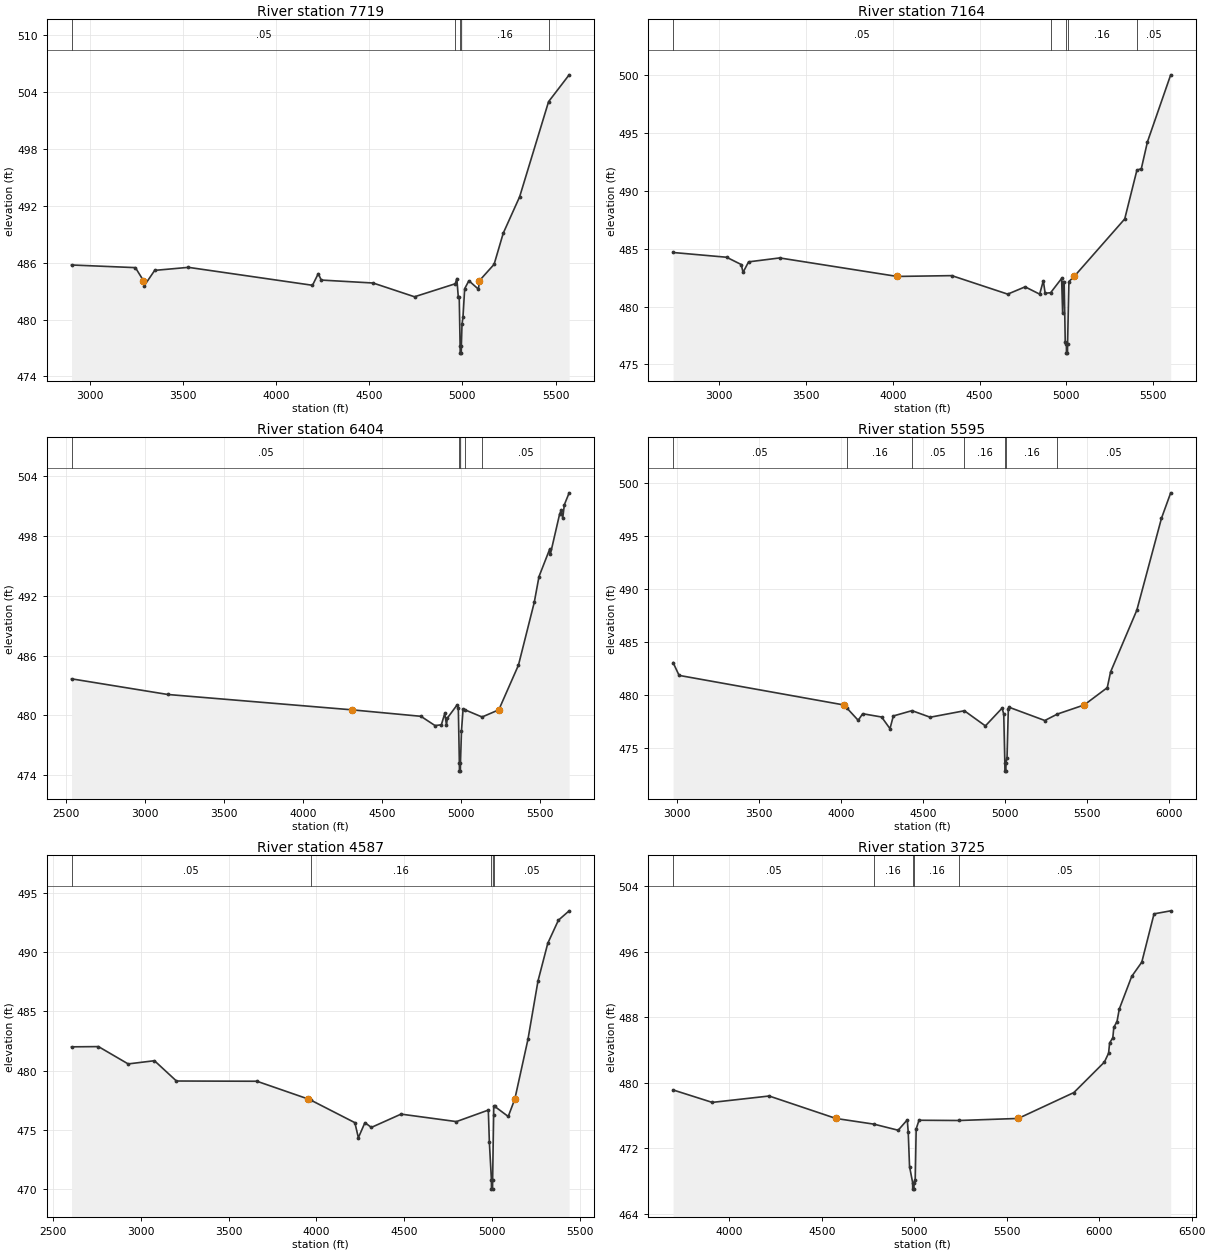
Type RM Length L Ch R = 1,7719,555,555,555
BEGIN DESCRIPTION:
Mapping XS 1b72f474
END DESCRIPTION:
XS GIS Cut Line= 3
      2765011.58      7054646.82      2765536.06      7052635.34
      2765348.55      7052072.80
#Sta/Elev= 30
  2901.5  485.75  3244.4  485.47  3287.6  484.10  3291.2  483.54  3347.8  485.18
  3529.0  485.50  4195.2  483.61  4226.2  484.84  4242.2  484.16  4520.5  483.85
  4742.9  482.40  4961.7  483.77  4970.2  484.32  4977.8  482.41  4983.0  482.41
  4987.7  477.26  4988.2  476.46  4994.0  476.46  4994.5  477.26  4997.9  479.50
  5003.2  480.25  5012.2  483.25  5034.8  484.09  5086.0  483.20  5091.6  484.10
  5170.3  485.82  5219.3  489.10  5307.4  492.94  5462.7  502.96  5573.2  505.79
#Mann=5,-1,0
  2901.5    0.05       0  4961.7    0.16       0  4987.7    0.07       0
  4994.5    0.16       0  5462.7    0.05       0
Bank Sta=3287.6,5091.6
Exp/Cntr=0.3,0.1

Type RM Length L Ch R = 1,7164,760,760,760
BEGIN DESCRIPTION:
Mapping XS 32e48e1c
END DESCRIPTION:
XS GIS Cut Line= 3
      2765240.76      7054657.18      2765952.73      7052520.75
      2765879.90      7051912.13
#Sta/Elev= 30
  2735.6  484.67  3043.6  484.26  3127.9  483.63  3138.4  482.95  3170.1  483.86
  3349.3  484.20  4025.6  482.60  4340.1  482.67  4662.1  481.07  4762.2  481.70
  4846.0  481.07  4867.1  482.22  4877.7  481.15  4909.1  481.19  4972.5  482.43
  4978.4  479.41  4983.2  482.10  4987.5  482.10  4993.3  476.95  5000.0  476.77
  5000.5  475.97  5006.3  475.97  5006.8  476.77  5014.5  482.16  5045.0  482.60
  5335.8  487.57  5405.8  491.78  5431.4  491.92  5466.7  494.24  5600.5  500.03
#Mann=5,-1,0
  2735.6    0.05       0  4909.1    0.16       0  5000.0    0.07       0
  5006.8    0.16       0  5405.8    0.05       0
Bank Sta=4025.6,5045
Exp/Cntr=0.3,0.1

Type RM Length L Ch R = 1,6404,809,809,809
BEGIN DESCRIPTION:
Mapping XS a1a8232f
END DESCRIPTION:
XS GIS Cut Line= 3
      2765673.07      7054834.23      2766582.93      7052572.84
      2766567.31      7051864.48
#Sta/Elev= 30
  2538.0  483.67  3146.1  482.10  4310.2  480.56  4746.9  479.91  4836.1  478.98
  4876.2  479.06  4897.8  480.21  4908.6  479.03  4914.0  479.73  4975.6  481.05
  4983.4  480.73  4990.0  475.21  4990.5  474.41  4996.4  474.41  4996.9  475.21
  5003.4  478.45  5013.4  480.60  5028.6  480.54  5133.5  479.84  5239.3  480.56
  5363.5  485.04  5463.5  491.34  5493.5  493.93  5560.3  496.65  5565.3  496.17
  5623.6  500.18  5633.6  500.57  5643.6  499.79  5653.6  501.13  5684.1  502.33
#Mann=5,-1,0
  2538.0    0.05       0  4990.0    0.03       0  4996.9    0.05       0
  5028.6    0.16       0  5133.5    0.05       0
Bank Sta=4310.2,5239.3
Exp/Cntr=0.3,0.1

Type RM Length L Ch R = 1,5595,1008,1008,1008
BEGIN DESCRIPTION:
Mapping XS e50849a1
END DESCRIPTION:
XS GIS Cut Line= 3
      2766768.70      7054730.81      2767150.64      7052772.49
      2767136.77      7051738.90
#Sta/Elev= 30
  2978.6  483.05  3015.1  481.84  4017.6  479.05  4038.2  478.73  4105.2  477.60
  4132.7  478.22  4247.9  477.91  4298.8  476.81  4319.2  478.01  4432.7  478.51
  4543.3  477.89  4751.5  478.50  4879.6  477.07  4981.3  478.75  4991.3  478.18
  4997.9  473.60  4998.4  472.80  5004.3  472.80  5004.8  473.60  5011.3  474.08
  5019.0  478.64  5024.0  478.83  5241.3  477.58  5318.0  478.19  5481.1  479.05
  5621.4  480.68  5641.4  482.16  5801.4  488.00  5951.4  496.68  6007.5  499.08
#Mann=7,-1,0
  2978.6    0.05       0  4038.2    0.16       0  4432.7    0.05       0
  4751.5    0.16       0  4997.9    0.07       0  5004.8    0.16       0
  5318.0    0.05       0
Bank Sta=4017.6,5481.1
Exp/Cntr=0.3,0.1

Type RM Length L Ch R = 1,4587,862,862,862
BEGIN DESCRIPTION:
LAKE FORK CREEK TRIB 3 6.0
END DESCRIPTION:
XS GIS Cut Line= 3
      2767128.07      7054719.99      2767909.32      7052441.33
      2767825.01      7052025.05
#Sta/Elev= 30
  2605.9  482.00  2759.2  482.02  2928.3  480.56  3078.0  480.83  3203.2  479.12
  3661.6  479.10  3952.3  477.61  3968.4  477.51  4219.3  475.61  4239.2  474.34
  4276.5  475.61  4313.2  475.21  4482.3  476.33  4797.6  475.70  4979.2  476.67
  4985.2  473.96  4996.8  470.81  4997.3  470.01  5003.3  470.01  5003.8  470.81
  5009.4  476.22  5010.2  476.99  5014.8  476.99  5092.6  476.13  5130.3  477.61
  5204.9  482.63  5262.1  487.55  5317.9  490.73  5378.3  492.67  5439.5  493.46
#Mann=5,-1,0
  2605.9    0.05       0  3968.4    0.16       0  4996.8    0.07       0
  5003.8    0.16       0  5009.4    0.05       0
Bank Sta=3952.3,5130.3
Exp/Cntr=0.3,0.1

Type RM Length L Ch R = 1,3725,0,0,0
BEGIN DESCRIPTION:
Mapping XS 2f2d50d9
END DESCRIPTION:
XS GIS Cut Line= 3
      2768773.04      7053951.33      2768474.43      7052645.75
      2767898.04      7051423.54
#Sta/Elev= 30
  3696.1  479.11  3907.8  477.59  4215.5  478.37  4576.3  475.63  4783.0  474.93
  4913.1  474.19  4962.4  475.46  4967.5  473.96  4974.6  469.76  4991.3  467.80
  4991.9  467.00  4998.3  467.00  4998.9  467.80  5005.3  468.14  5010.5  474.37
  5025.9  475.41  5243.2  475.38  5562.3  475.63  5863.1  478.79  6028.1  482.51
  6050.9  483.60  6056.4  484.85  6073.7  485.47  6079.2  486.76  6096.4  487.46
  6108.7  488.99  6175.8  492.97  6230.3  494.71  6296.6  500.61  6386.7  500.98
#Mann=5,-1,0
  3696.1    0.05       0  4783.0    0.16       0  4991.3    0.07       0
  4998.9    0.16       0  5243.2    0.05       0
Bank Sta=4576.3,5562.3
Exp/Cntr=0.3,0.1

Chan Stop Cuts=-1