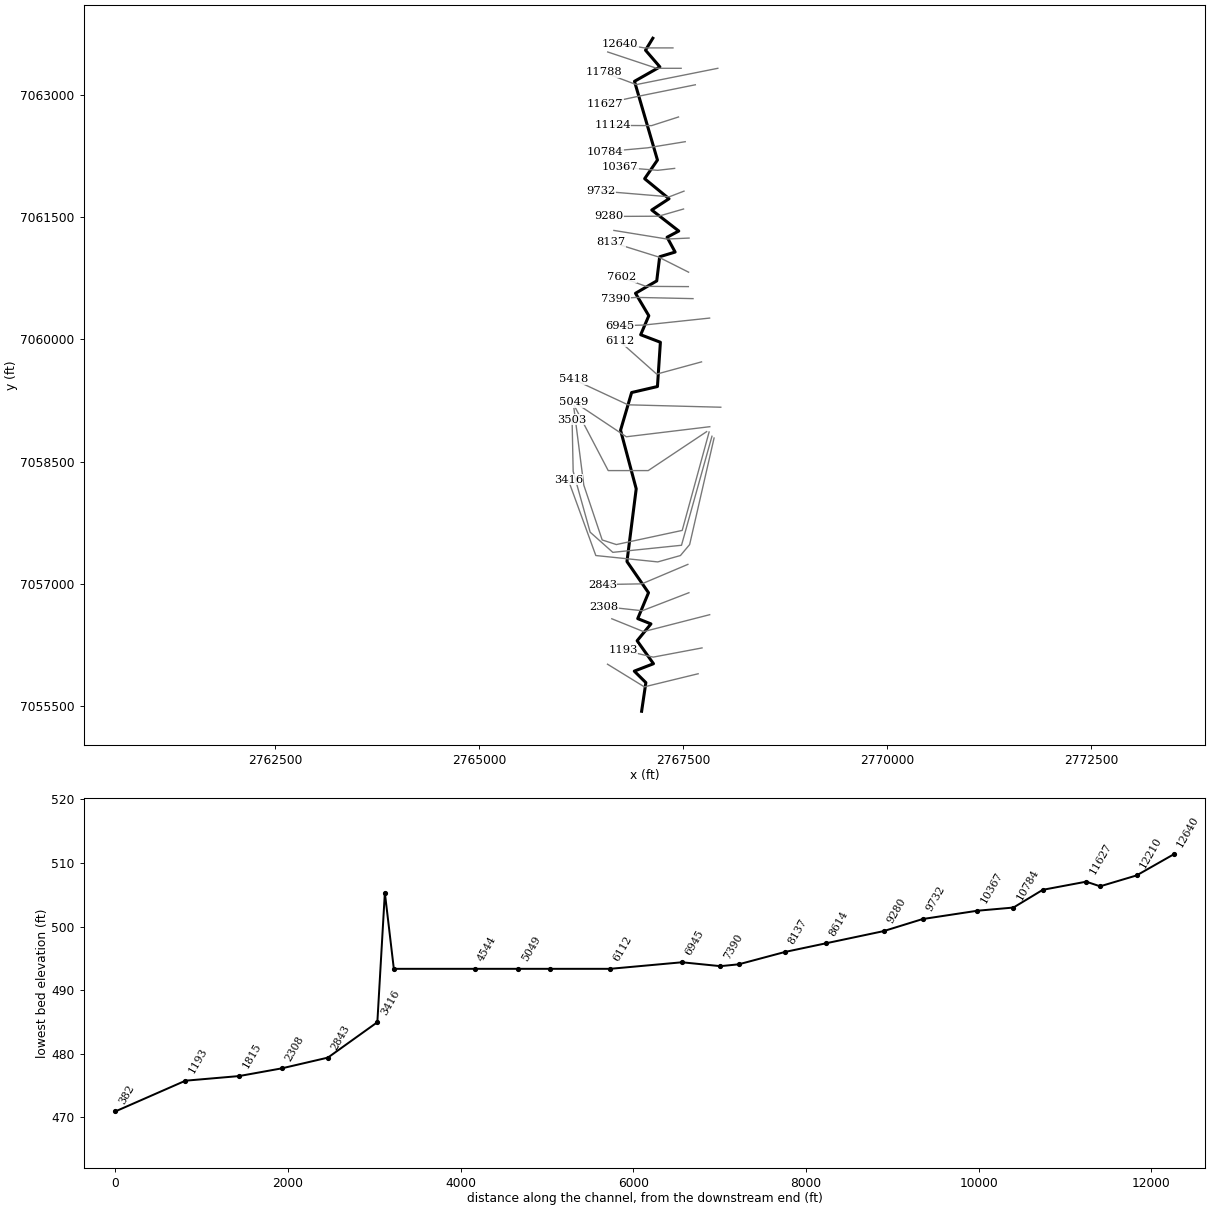
--- LAKE FORK CREEK TRIB 4.prj (project) ---

Proj Title=LAKE FORK CREEK TRIB 4 Base Level Engineering
Current Plan=p01
Default Exp/Contr=0.3,0.1
English Units
Geom File=g01
Flow File=f01
Plan File=p01
BEGIN DESCRIPTION:
LAKE FORK CREEK TRIB 4
END DESCRIPTION:

--- LAKE FORK CREEK TRIB 4.p01 (plan) ---

Plan Title=Multiple Run
Short Identifier=Multiple
Geom File=g01
Flow File=f01
Subcritical Flow
K Sum by GR= 0
Std Step Tol= 0.01
Critical Tol= 0.01
Num of Std Step Trials= 20
Max Error Tol= 0.3
Flow Tol Ratio= 0.001
Split Flow NTrial= 30
Split Flow Tol= 0.02
Split Flow Ratio= 0.02
Log Output Level= 0
Friction Slope Method= 1
Unsteady Friction Slope Method= 2
Unsteady Bridges Friction Slope Method= 1
Parabolic Critical Depth
Global Vel Dist=  1 , 1 , 1
Global Log Level= 0
CheckData=True
Encroach Param= -1, 0, 0, 0
BEGIN DESCRIPTION:
Multiple Run
END DESCRIPTION:

--- LAKE FORK CREEK TRIB 4.f01 (steady flow) ---

Flow Title=Multiple
Number of Profiles=7
Profile Names=10-year,25-year,50-year,1pct_min,100-year,1pct_plu,500-year
River Rch & RM= LAKE FORK CREEK ,Reach-1,12640
     673     896    1074     639    1275    2543    1790
River Rch & RM= LAKE FORK CREEK ,Reach-1,12210
     953    1291    1566     940    1876    3744    2690
Boundary for River Rch & Prof#=LAKE FORK CREEK ,Reach-1,1
Up Type=0
Dn Type=3
Dn Slope=0.005
Boundary for River Rch & Prof#=LAKE FORK CREEK ,Reach-1,2
Up Type=0
Dn Type=3
Dn Slope=0.005
Boundary for River Rch & Prof#=LAKE FORK CREEK ,Reach-1,3
Up Type=0
Dn Type=3
Dn Slope=0.005
Boundary for River Rch & Prof#=LAKE FORK CREEK ,Reach-1,4
Up Type=0
Dn Type=3
Dn Slope=0.005
Boundary for River Rch & Prof#=LAKE FORK CREEK ,Reach-1,5
Up Type=0
Dn Type=3
Dn Slope=0.005
Boundary for River Rch & Prof#=LAKE FORK CREEK ,Reach-1,6
Up Type=0
Dn Type=3
Dn Slope=0.005
Boundary for River Rch & Prof#=LAKE FORK CREEK ,Reach-1,7
Up Type=0
Dn Type=3
Dn Slope=0.005

--- LAKE FORK CREEK TRIB 4.g01 (geometry) ---

Geom Title=Existing Conditions

River Reach=LAKE FORK CREEK ,Reach-1
Reach XY= 30
      2767127.91      7063693.58      2767038.12      7063546.76
      2767214.42      7063342.10      2766903.06      7063165.24
      2767184.67      7062200.03      2767027.56      7061971.20
      2767326.51      7061725.51      2767114.78      7061587.26
      2767446.07      7061329.45      2767302.85      7061253.48
      2767401.24      7061071.65      2767211.93      7061014.36
      2767175.81      7060717.94      2766915.51      7060566.00
      2767078.67      7060290.75      2766979.03      7060057.85
      2767220.65      7059965.69      2767184.53      7059422.68
      2766868.19      7059349.19      2766732.43      7058887.13
      2766924.23      7058168.51      2766810.90      7057276.77
      2767074.93      7056894.42      2766942.91      7056576.83
      2767104.82      7056512.07      2766935.44      7056305.32
      2767135.96      7056023.85      2766900.57      7055932.94
      2767042.55      7055792.20      2766990.54      7055440.69

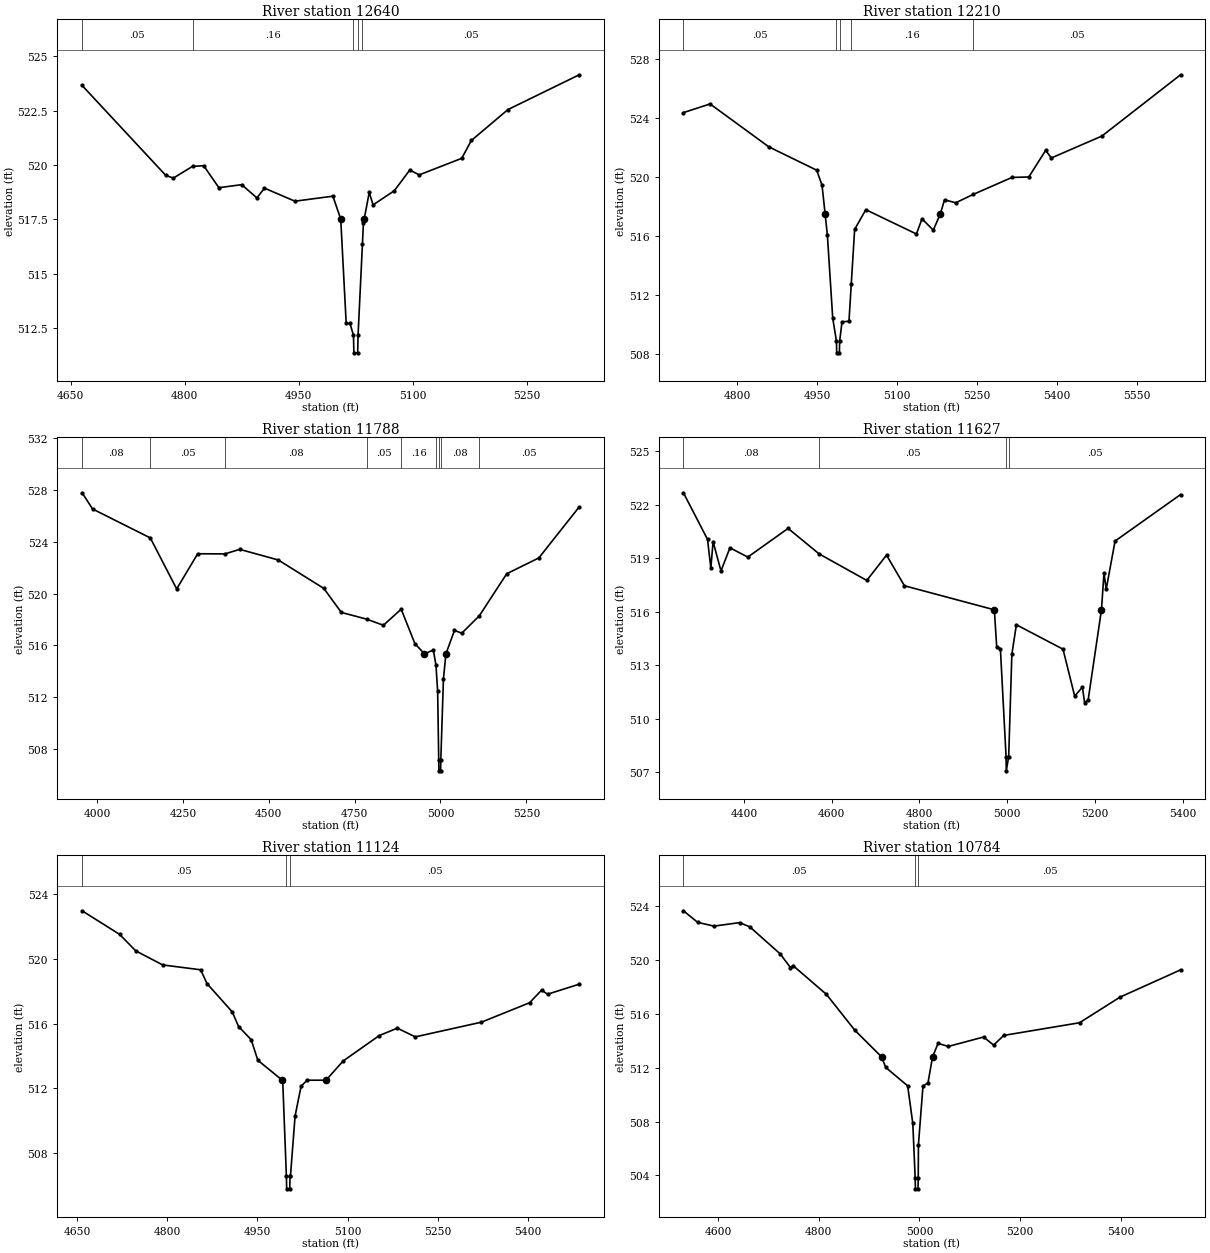
Type RM Length L Ch R = 1,12640,430,430,430
BEGIN DESCRIPTION:
LAKE FORK CREEK TRIB 4 17.0
END DESCRIPTION:
XS GIS Cut Line= 3
      2767374.96      7063575.00      2767025.00      7063575.00
      2766725.00      7063625.00
#Sta/Elev= 30
  4664.8  523.66  4774.8  519.53  4784.8  519.40  4810.1  519.94  4824.8  519.97
  4844.8  518.96  4874.8  519.10  4894.8  518.49  4904.8  518.94  4944.8  518.34
  4994.8  518.57  5005.1  517.52  5012.3  512.72  5017.3  512.72  5021.9  512.17
  5022.4  511.37  5027.4  511.37  5027.9  512.17  5033.7  516.39  5035.0  517.34
  5036.0  517.52  5042.6  518.74  5047.7  518.17  5075.6  518.82  5095.9  519.77
  5108.5  519.55  5164.3  520.31  5177.0  521.13  5225.1  522.55  5318.9  524.15
#Mann=5,-1,0
  4664.8    0.05       0  4810.1    0.16       0  5021.9    0.07       0
  5027.9    0.16       0  5033.7    0.05       0
Bank Sta=5005.1,5036
Exp/Cntr=0.3,0.1

Type RM Length L Ch R = 1,12210,422,422,422
BEGIN DESCRIPTION:
LAKE FORK CREEK TRIB 4 16.0
END DESCRIPTION:
XS GIS Cut Line= 3
      2767474.97      7063325.00      2767175.00      7063325.00
      2766575.02      7063524.99
#Sta/Elev= 30
  4699.4  524.36  4749.4  524.95  4859.4  522.04  4949.4  520.45  4959.4  519.42
  4965.1  517.50  4969.4  516.04  4979.4  510.41  4986.4  508.85  4986.9  508.05
  4991.9  508.05  4992.4  508.85  4996.9  510.16  5009.9  510.19  5014.2  512.72
  5020.5  516.43  5041.5  517.77  5136.4  516.12  5146.9  517.15  5168.0  516.38
  5181.4  517.50  5189.1  518.44  5210.2  518.24  5243.1  518.81  5315.6  519.96
  5347.2  519.99  5378.8  521.80  5389.4  521.28  5484.3  522.77  5631.8  526.93
#Mann=5,-1,0
  4699.4    0.05       0  4986.4    0.03       0  4992.4    0.05       0
  5014.2    0.16       0  5243.1    0.05       0
Bank Sta=4965.1,5181.4
Exp/Cntr=0.3,0.1

Type RM Length L Ch R = 1,11788,161,161,161
BEGIN DESCRIPTION:
LAKE FORK CREEK TRIB 4 15.0
END DESCRIPTION:
XS GIS Cut Line= 3
      2767924.96      7063324.99      2766925.00      7063125.00
      2766524.97      7063275.01
#Sta/Elev= 30
  3956.8  527.77  3987.4  526.52  4155.4  524.29  4232.1  520.36  4293.3  523.07
  4372.6  523.06  4415.7  523.41  4527.9  522.59  4660.4  520.40  4711.4  518.55
  4785.1  518.03  4833.8  517.56  4885.6  518.80  4925.6  516.14  4953.3  515.36
  4979.2  515.65  4986.8  514.49  4991.7  512.49  4994.9  507.14  4995.4  506.34
  5000.4  506.34  5000.9  507.14  5008.6  513.44  5015.9  515.36  5040.6  517.16
  5062.0  516.95  5113.1  518.29  5192.8  521.53  5286.3  522.75  5403.8  526.68
#Mann=9,-1,0
  3956.8    0.08       0  4155.4    0.05       0  4372.6    0.08       0
  4785.1    0.05       0  4885.6    0.16       0  4986.8    0.08       0
  4994.9    0.07       0  5000.9    0.08       0  5113.1    0.05       0
Bank Sta=4953.3,5015.9
Exp/Cntr=0.3,0.1

Type RM Length L Ch R = 1,11627,503,503,503
BEGIN DESCRIPTION:
Mapping XS ea22ffd8
END DESCRIPTION:
XS GIS Cut Line= 3
      2767648.88      7063122.83      2766947.71      7062981.41
      2766539.10      7062893.23
#Sta/Elev= 30
  4261.9  522.68  4316.9  520.06  4324.4  518.45  4329.5  519.94  4347.5  518.29
  4367.9  519.59  4408.7  519.07  4500.5  520.68  4571.2  519.25  4679.9  517.76
  4724.9  519.18  4765.7  517.46  4970.7  516.11  4976.0  514.04  4984.5  513.92
  4997.4  507.87  4997.9  507.07  5003.4  507.87  5010.6  513.61  5020.9  515.27
  5127.2  513.90  5153.9  511.26  5171.4  511.77  5176.5  510.89  5184.6  511.06
  5214.9  516.11  5220.6  518.17  5225.7  517.27  5245.9  519.97  5395.2  522.58
#Mann=4,-1,0
  4261.9    0.08       0  4571.2    0.05       0  4997.4    0.03       0
  5003.4    0.05       0
Bank Sta=4970.7,5214.9
Exp/Cntr=0.3,0.1

Type RM Length L Ch R = 1,11124,340,340,340
BEGIN DESCRIPTION:
Mapping XS 7194d046
END DESCRIPTION:
XS GIS Cut Line= 3
      2767442.71      7062728.05      2767112.70      7062621.98
      2766632.45      7062624.93
#Sta/Elev= 30
  4658.3  522.99  4720.7  521.53  4747.6  520.51  4792.4  519.64  4855.5  519.34
  4866.0  518.49  4908.0  516.74  4918.6  515.83  4939.5  515.02  4950.7  513.74
  4991.3  512.51  4992.0  512.48  4998.1  506.59  4998.6  505.79  5003.7  505.79
  5004.2  506.59  5004.9  506.59  5012.6  510.30  5022.6  512.14  5032.6  512.51
  5064.0  512.51  5092.6  513.70  5152.6  515.27  5182.6  515.73  5212.6  515.19
  5322.6  516.10  5402.6  517.30  5422.6  518.08  5432.6  517.83  5485.2  518.45
#Mann=3,-1,0
  4658.3    0.05       0  4998.1    0.03       0  5004.2    0.05       0
Bank Sta=4991.3,5064
Exp/Cntr=0.3,0.1

Type RM Length L Ch R = 1,10784,417,417,417
BEGIN DESCRIPTION:
LAKE FORK CREEK TRIB 4 14.0
END DESCRIPTION:
XS GIS Cut Line= 3
      2767525.04      7062425.01      2767063.20      7062349.76
      2766544.95      7062302.88
#Sta/Elev= 30
  4530.9  523.66  4559.2  522.80  4591.7  522.52  4642.4  522.78  4662.7  522.47
  4723.5  520.45  4743.6  519.44  4748.7  519.59  4815.2  517.45  4871.7  514.78
  4924.7  512.81  4933.1  512.02  4976.7  510.65  4986.9  507.86  4991.6  503.80
  4992.1  503.00  4997.2  503.00  4997.7  503.80  4998.1  506.29  5007.1  510.63
  5017.1  510.88  5026.2  512.81  5037.2  513.81  5057.3  513.58  5127.6  514.28
  5147.6  513.68  5167.7  514.40  5318.3  515.34  5398.7  517.24  5519.2  519.27
#Mann=3,-1,0
  4530.9    0.05       0  4991.6    0.03       0  4997.7    0.05       0
Bank Sta=4924.7,5026.2
Exp/Cntr=0.3,0.1

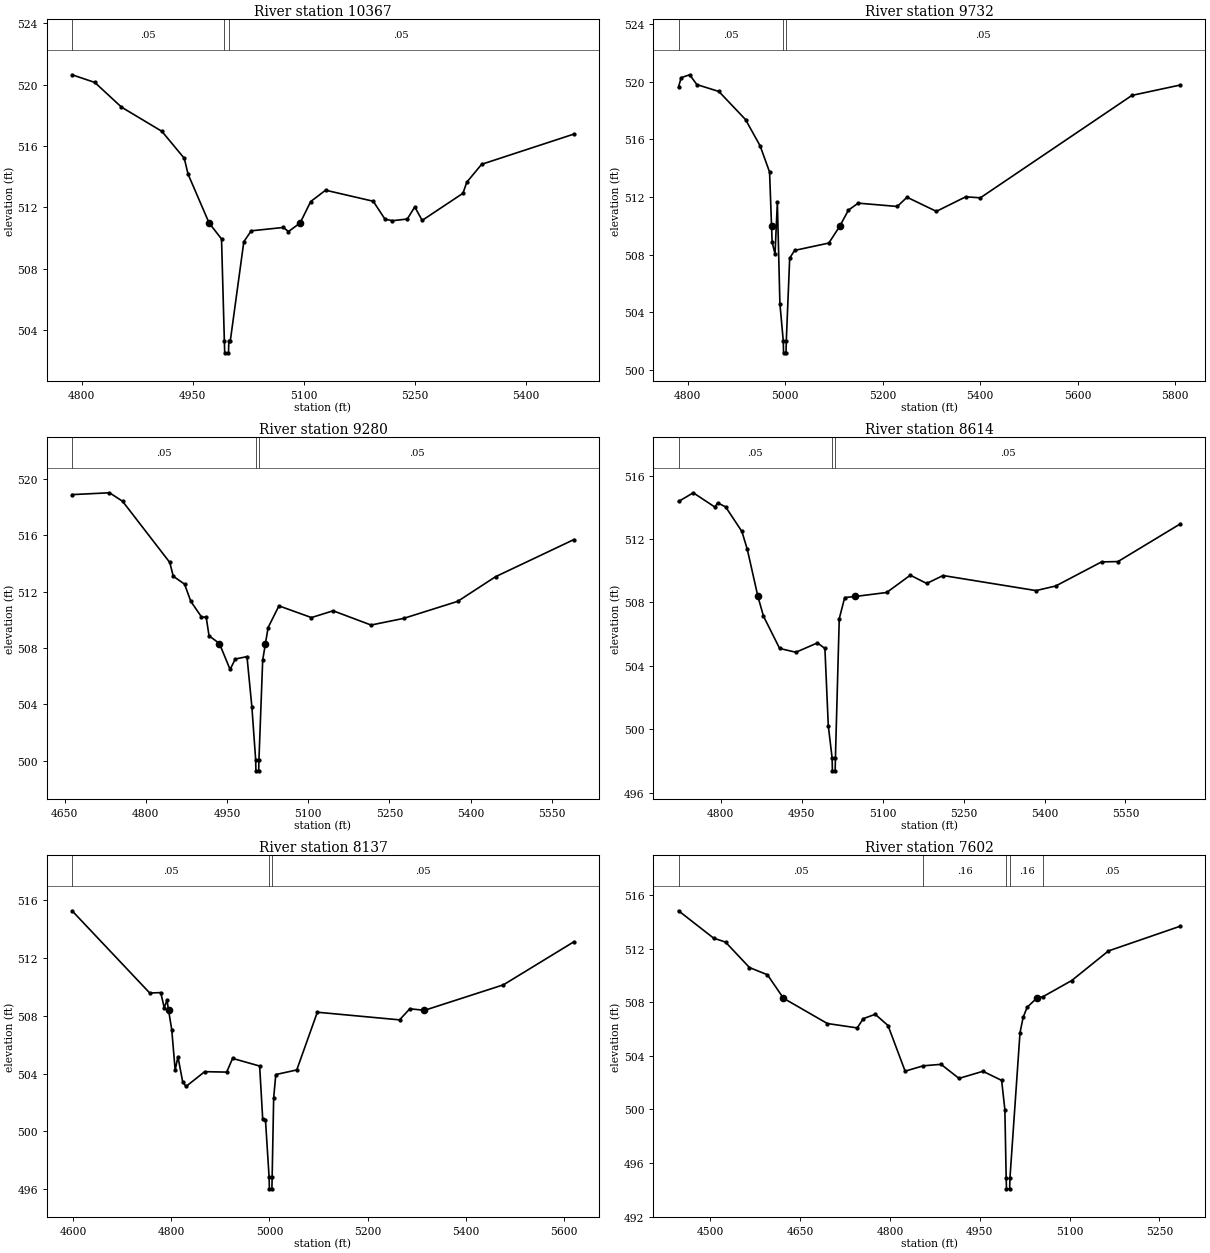
Type RM Length L Ch R = 1,10367,635,635,635
BEGIN DESCRIPTION:
Mapping XS b6eb2e48
END DESCRIPTION:
XS GIS Cut Line= 3
      2767395.51      7062097.55      2767186.35      7062073.99
      2766720.90      7062112.28
#Sta/Elev= 30
  4787.1  520.64  4817.8  520.14  4853.8  518.53  4908.4  516.95  4938.6  515.19
  4943.7  514.16  4972.1  510.97  4988.9  509.93  4992.7  503.30  4993.2  502.50
  4998.3  502.50  4998.8  503.30  5000.8  503.30  5019.0  509.75  5029.0  510.46
  5072.5  510.68  5079.2  510.41  5095.0  510.97  5109.3  512.37  5129.4  513.11
  5193.7  512.39  5209.6  511.22  5219.7  511.12  5239.7  511.23  5249.8  512.02
  5259.8  511.14  5314.9  512.91  5320.0  513.63  5340.1  514.80  5464.6  516.77
#Mann=3,-1,0
  4787.1    0.05       0  4992.7    0.03       0  4998.8    0.05       0
Bank Sta=4972.1,5095
Exp/Cntr=0.3,0.1

Type RM Length L Ch R = 1,9732,452,452,452
BEGIN DESCRIPTION:
LAKE FORK CREEK TRIB 4 13.0
END DESCRIPTION:
XS GIS Cut Line= 3
      2767510.07      7061818.68      2767329.52      7061749.24
      2766496.15      7061818.68
#Sta/Elev= 30
  4781.2  519.64  4786.6  520.29  4804.0  520.49  4818.8  519.81  4864.0  519.33
  4918.7  517.38  4948.7  515.55  4968.0  513.74  4972.1  509.96  4973.3  508.87
  4979.2  508.05  4984.0  511.65  4989.2  504.61  4996.2  501.99  4996.7  501.19
  5001.8  501.19  5002.3  501.99  5009.3  507.76  5019.3  508.30  5089.6  508.81
  5111.7  509.96  5129.7  511.09  5149.8  511.58  5230.0  511.35  5250.1  511.99
  5310.3  511.01  5370.5  512.02  5400.6  511.95  5711.7  519.06  5810.9  519.78
#Mann=3,-1,0
  4781.2    0.05       0  4996.2    0.03       0  5002.3    0.05       0
Bank Sta=4972.1,5111.7
Exp/Cntr=0.3,0.1

Type RM Length L Ch R = 1,9280,666,666,666
BEGIN DESCRIPTION:
Mapping XS 8984c086
END DESCRIPTION:
XS GIS Cut Line= 3
      2767504.55      7061599.66      2767198.14      7061511.27
      2766590.45      7061508.49
#Sta/Elev= 30
  4663.9  518.88  4733.0  519.01  4757.1  518.41  4844.3  514.07  4850.8  513.09
  4871.6  512.53  4883.2  511.31  4902.8  510.21  4911.6  510.18  4916.8  508.87
  4936.0  508.32  4955.7  506.48  4965.3  507.22  4986.9  507.39  4995.9  503.84
  5002.9  500.09  5003.4  499.29  5008.5  499.29  5009.0  500.09  5015.9  507.14
  5021.0  508.32  5025.9  509.45  5045.9  510.99  5105.9  510.16  5146.0  510.64
  5216.0  509.63  5276.0  510.10  5376.0  511.31  5446.0  513.06  5590.5  515.69
#Mann=3,-1,0
  4663.9    0.05       0  5002.9    0.03       0  5009.0    0.05       0
Bank Sta=4936,5021
Exp/Cntr=0.3,0.1

Type RM Length L Ch R = 1,8614,477,477,477
BEGIN DESCRIPTION:
Mapping XS 68b9c3aa
END DESCRIPTION:
XS GIS Cut Line= 3
      2767572.27      7061243.16      2767301.25      7061231.38
      2766650.91      7061336.79
#Sta/Elev= 30
  4721.6  514.37  4748.9  514.92  4788.9  514.02  4794.2  514.28  4808.9  514.03
  4839.0  512.48  4849.0  511.36  4868.7  508.38  4879.0  507.14  4909.0  505.10
  4939.1  504.86  4979.1  505.45  4992.9  505.10  4999.2  500.22  5006.3  498.18
  5006.8  497.38  5011.9  497.38  5012.4  498.18  5019.5  506.98  5029.6  508.31
  5049.3  508.38  5107.4  508.63  5151.2  509.72  5181.6  509.20  5211.9  509.70
  5384.2  508.75  5420.7  509.04  5505.7  510.56  5536.1  510.58  5651.7  512.96
#Mann=3,-1,0
  4721.6    0.05       0  5006.3    0.03       0  5012.4    0.05       0
Bank Sta=4868.7,5049.3
Exp/Cntr=0.3,0.1

Type RM Length L Ch R = 1,8137,535,535,535
BEGIN DESCRIPTION:
Mapping XS 02d34bb3
END DESCRIPTION:
XS GIS Cut Line= 3
      2767566.45      7060824.78      2767192.24      7061013.36
      2766615.84      7061193.73
#Sta/Elev= 30
  4597.7  515.28  4756.1  509.58  4778.5  509.61  4785.6  508.56  4791.2  509.08
  4794.5  508.38  4800.9  507.04  4807.9  504.23  4813.5  505.17  4823.3  503.41
  4830.2  503.11  4868.1  504.13  4912.9  504.10  4925.0  505.05  4980.1  504.52
  4986.4  500.82  4992.0  500.78  4999.4  496.81  4999.9  496.01  5005.1  496.01
  5005.6  496.81  5008.7  502.31  5013.0  503.93  5055.8  504.25  5097.7  508.25
  5265.3  507.72  5286.3  508.49  5316.1  508.38  5477.2  510.15  5620.7  513.13
#Mann=3,-1,0
  4597.7    0.05       0  4999.4    0.03       0  5005.6    0.05       0
Bank Sta=4794.5,5316.1
Exp/Cntr=0.3,0.1

Type RM Length L Ch R = 1,7602,212,212,212
BEGIN DESCRIPTION:
Mapping XS d301c2c0
END DESCRIPTION:
XS GIS Cut Line= 3
      2767563.49      7060648.03      2767044.93      7060650.98
      2766744.46      7060759.97
#Sta/Elev= 30
  4446.7  514.84  4505.2  512.80  4525.2  512.50  4565.2  510.60  4595.2  510.06
  4621.9  508.31  4695.2  506.42  4745.2  506.09  4755.2  506.78  4775.2  507.11
  4796.6  506.27  4825.2  502.86  4855.5  503.26  4885.2  503.37  4915.2  502.32
  4955.2  502.85  4986.4  502.17  4991.8  499.99  4994.0  494.87  4994.5  494.07
  4999.8  494.07  5000.3  494.87  5017.1  505.73  5022.4  506.89  5029.0  507.63
  5045.0  508.31  5055.7  508.43  5103.5  509.63  5164.8  511.84  5284.9  513.69
#Mann=5,-1,0
  4446.7    0.05       0  4855.5    0.16       0  4994.0    0.07       0
  5000.3    0.16       0  5055.7    0.05       0
Bank Sta=4621.9,5045
Exp/Cntr=0.3,0.1

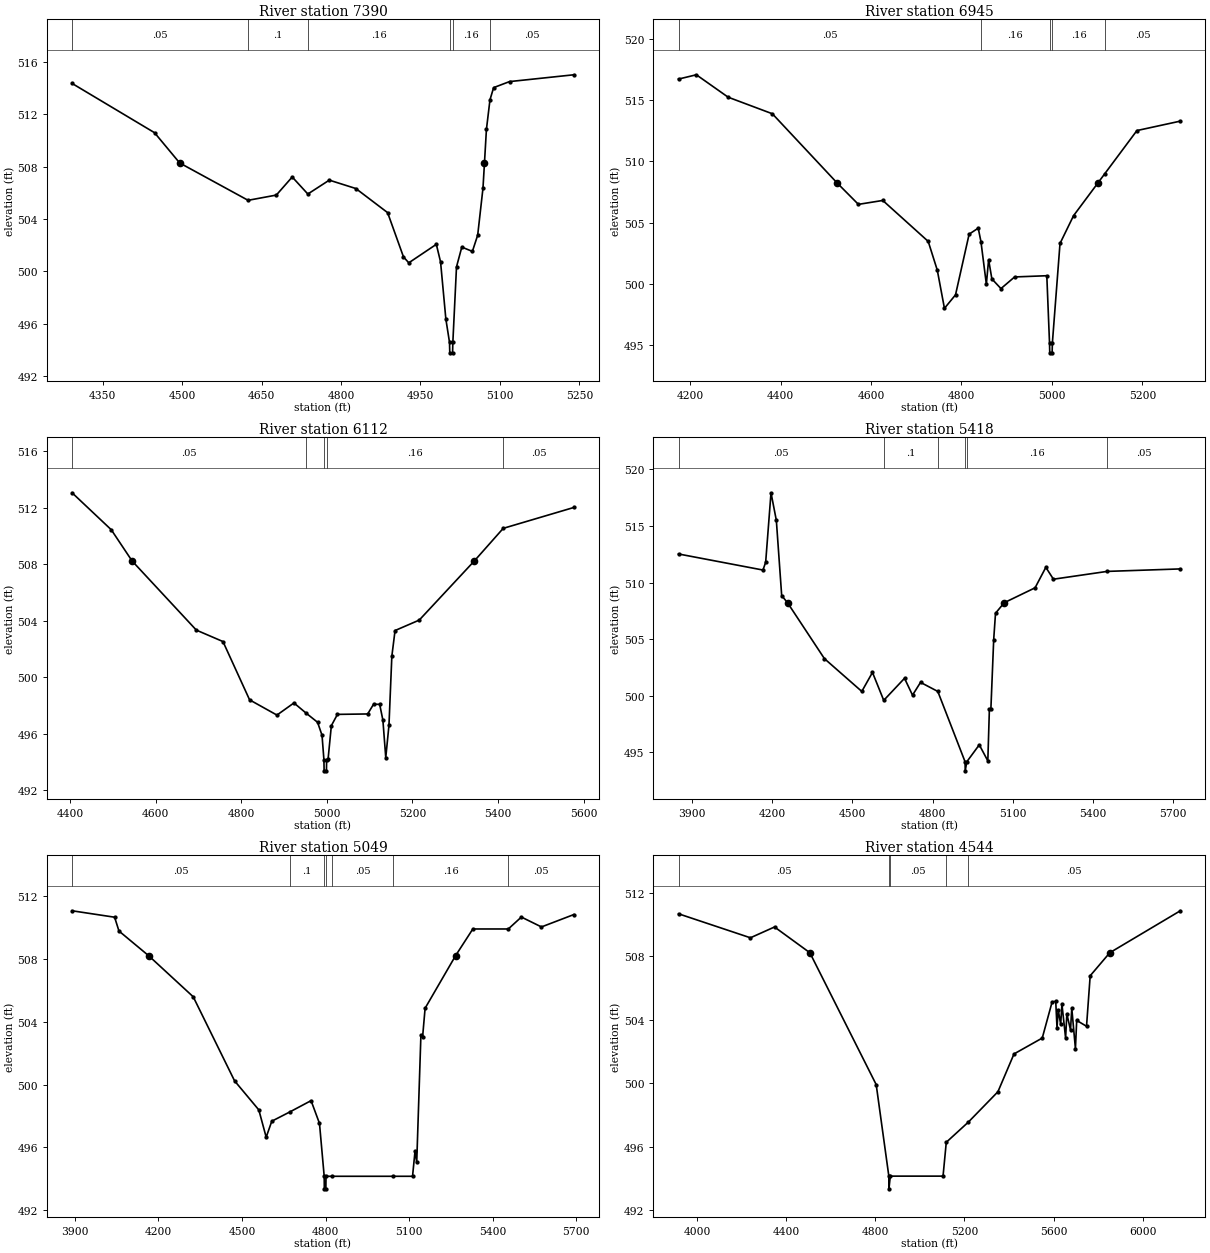
Type RM Length L Ch R = 1,7390,445,445,445
BEGIN DESCRIPTION:
Mapping XS fe7ec46d
END DESCRIPTION:
XS GIS Cut Line= 3
      2767620.63      7060500.57      2766932.98      7060515.45
      2766673.71      7060500.72
#Sta/Elev= 30
  4292.2  514.34  4447.9  510.58  4495.4  508.27  4624.6  505.42  4677.9  505.82
  4707.9  507.20  4737.4  505.90  4777.9  506.96  4828.0  506.32  4888.0  504.48
  4918.0  501.10  4928.0  500.65  4980.0  502.06  4988.0  500.72  4998.0  496.36
  5004.9  494.58  5005.4  493.78  5010.7  493.78  5011.2  494.58  5018.1  500.34
  5028.1  501.85  5048.1  501.52  5058.1  502.76  5068.1  506.35  5070.9  508.27
  5074.6  510.83  5081.3  513.09  5088.2  514.02  5118.2  514.48  5239.7  515.00
#Mann=6,-1,0
  4292.2    0.05       0  4624.6     0.1       0  4737.4    0.16       0
  5004.9    0.07       0  5011.2    0.16       0  5081.3    0.05       0
Bank Sta=4495.4,5070.9
Exp/Cntr=0.3,0.1

Type RM Length L Ch R = 1,6945,833,833,833
BEGIN DESCRIPTION:
Mapping XS 2ac61e7f
END DESCRIPTION:
XS GIS Cut Line= 3
      2767824.15      7060262.11      2767018.42      7060176.64
      2766719.00      7060167.84
#Sta/Elev= 30
  4174.2  516.72  4213.6  517.07  4284.0  515.24  4381.7  513.89  4525.1  508.24
  4572.0  506.50  4625.9  506.82  4726.4  503.48  4746.5  501.13  4762.3  498.02
  4786.8  499.12  4816.9  504.07  4837.0  504.56  4843.0  503.47  4855.0  499.99
  4860.0  501.99  4867.2  500.42  4887.3  499.63  4917.5  500.58  4988.7  500.68
  4994.7  495.19  4995.2  494.39  5000.5  494.39  5001.0  495.19  5017.9  503.31
  5047.9  505.58  5101.6  508.24  5116.5  508.98  5188.0  512.52  5284.0  513.29
#Mann=5,-1,0
  4174.2    0.05       0  4843.0    0.16       0  4994.7    0.07       0
  5001.0    0.16       0  5116.5    0.05       0
Bank Sta=4525.1,5101.6
Exp/Cntr=0.3,0.1

Type RM Length L Ch R = 1,6112,694,694,694
BEGIN DESCRIPTION:
LAKE FORK CREEK TRIB 4 9.0
END DESCRIPTION:
XS GIS Cut Line= 3
      2767725.05      7059725.01      2767175.00      7059575.00
      2766725.01      7059974.99
#Sta/Elev= 30
  4404.8  513.06  4496.4  510.44  4545.0  508.23  4695.1  503.33  4757.3  502.52
  4819.5  498.39  4883.4  497.31  4923.1  498.17  4951.5  497.45  4978.3  496.80
  4988.7  495.88  4993.1  494.16  4993.6  493.36  4999.0  493.36  4999.5  494.16
  5002.9  494.21  5010.5  496.56  5024.7  497.36  5095.4  497.39  5109.1  498.08
  5123.4  498.07  5130.9  496.95  5137.6  494.30  5145.1  496.60  5151.8  501.48
  5159.3  503.30  5215.8  504.04  5344.5  508.23  5412.0  510.54  5577.0  512.02
#Mann=5,-1,0
  4404.8    0.05       0  4951.5    0.16       0  4993.1    0.07       0
  4999.5    0.16       0  5412.0    0.05       0
Bank Sta=4545,5344.5
Exp/Cntr=0.3,0.1

Type RM Length L Ch R = 1,5418,369,369,369
BEGIN DESCRIPTION:
LAKE FORK CREEK TRIB 4 8.0
END DESCRIPTION:
XS GIS Cut Line= 3
      2767961.24      7059168.94      2766823.97      7059198.51
      2766151.31      7059511.82
#Sta/Elev= 30
  3848.6  512.53  4164.9  511.11  4175.0  511.80  4195.0  517.94  4215.0  515.50
  4235.0  508.85  4256.9  508.22  4395.0  503.28  4535.1  500.38  4575.1  502.06
  4617.3  499.59  4695.1  501.54  4725.1  500.05  4755.1  501.18  4819.8  500.38
  4922.0  494.16  4922.5  493.36  4928.4  494.16  4975.2  495.66  5007.2  494.24
  5013.1  498.84  5018.6  498.80  5029.2  504.97  5036.0  507.29  5068.5  508.22
  5184.2  509.54  5224.5  511.35  5252.9  510.30  5454.1  510.99  5728.3  511.21
#Mann=6,-1,0
  3848.6    0.05       0  4617.3     0.1       0  4819.8    0.16       0
  4922.0    0.07       0  4928.4    0.16       0  5454.1    0.05       0
Bank Sta=4256.9,5068.5
Exp/Cntr=0.3,0.1

Type RM Length L Ch R = 1,5049,505,505,505
BEGIN DESCRIPTION:
LAKE FORK CREEK TRIB 4 7.0
END DESCRIPTION:
XS GIS Cut Line= 3
      2767826.63      7058930.22      2766803.35      7058806.66
      2766162.41      7059233.92
#Sta/Elev= 30
  3890.2  511.08  4042.9  510.67  4058.5  509.79  4164.9  508.22  4325.0  505.60
  4473.5  500.24  4560.5  498.39  4586.9  496.65  4607.0  497.67  4670.6  498.25
  4748.0  498.98  4778.2  497.53  4795.1  494.16  4795.6  493.36  4801.1  493.36
  4801.6  494.16  4823.9  494.16  5042.9  494.16  5112.2  494.16  5121.2  495.77
  5127.2  495.04  5142.3  503.18  5148.3  503.04  5157.3  504.87  5266.7  508.22
  5328.6  509.92  5455.9  509.92  5502.8  510.68  5574.9  510.05  5691.2  510.84
#Mann=7,-1,0
  3890.2    0.05       0  4670.6     0.1       0  4795.1   0.033       0
  4801.6     0.1       0  4823.9    0.05       0  5042.9    0.16       0
  5455.9    0.05       0
Bank Sta=4164.9,5266.7
Exp/Cntr=0.3,0.1

Type RM Length L Ch R = 1,4544,937,937,937
BEGIN DESCRIPTION:
Mapping XS e0397ecf
END DESCRIPTION:
XS GIS Cut Line= 4
      2767787.63      7058869.48      2767071.45      7058392.03
      2766581.00      7058392.03      2766163.68      7059190.57
#Sta/Elev= 30
  3916.6  510.67  4239.2  509.16  4347.4  509.84  4506.0  508.22  4803.8  499.92
  4860.5  494.16  4861.0  493.36  4867.0  494.16  5103.8  494.16  5118.3  496.29
  5217.4  497.56  5350.1  499.47  5422.3  501.85  5549.1  502.85  5593.3  505.12
  5609.6  505.16  5615.3  503.51  5621.0  504.61  5631.8  503.71  5637.4  504.98
  5653.9  502.85  5659.5  504.37  5675.9  503.36  5681.6  504.72  5698.0  502.18
  5703.7  503.96  5747.8  503.59  5764.2  506.77  5852.2  508.22  6168.8  510.86
#Mann=5,-1,0
  3916.6    0.05       0  4860.5   0.033       0  4867.0    0.05       0
  5118.3    0.08       0  5217.4    0.05       0
Bank Sta=4506,5852.2
Exp/Cntr=0.3,0.1

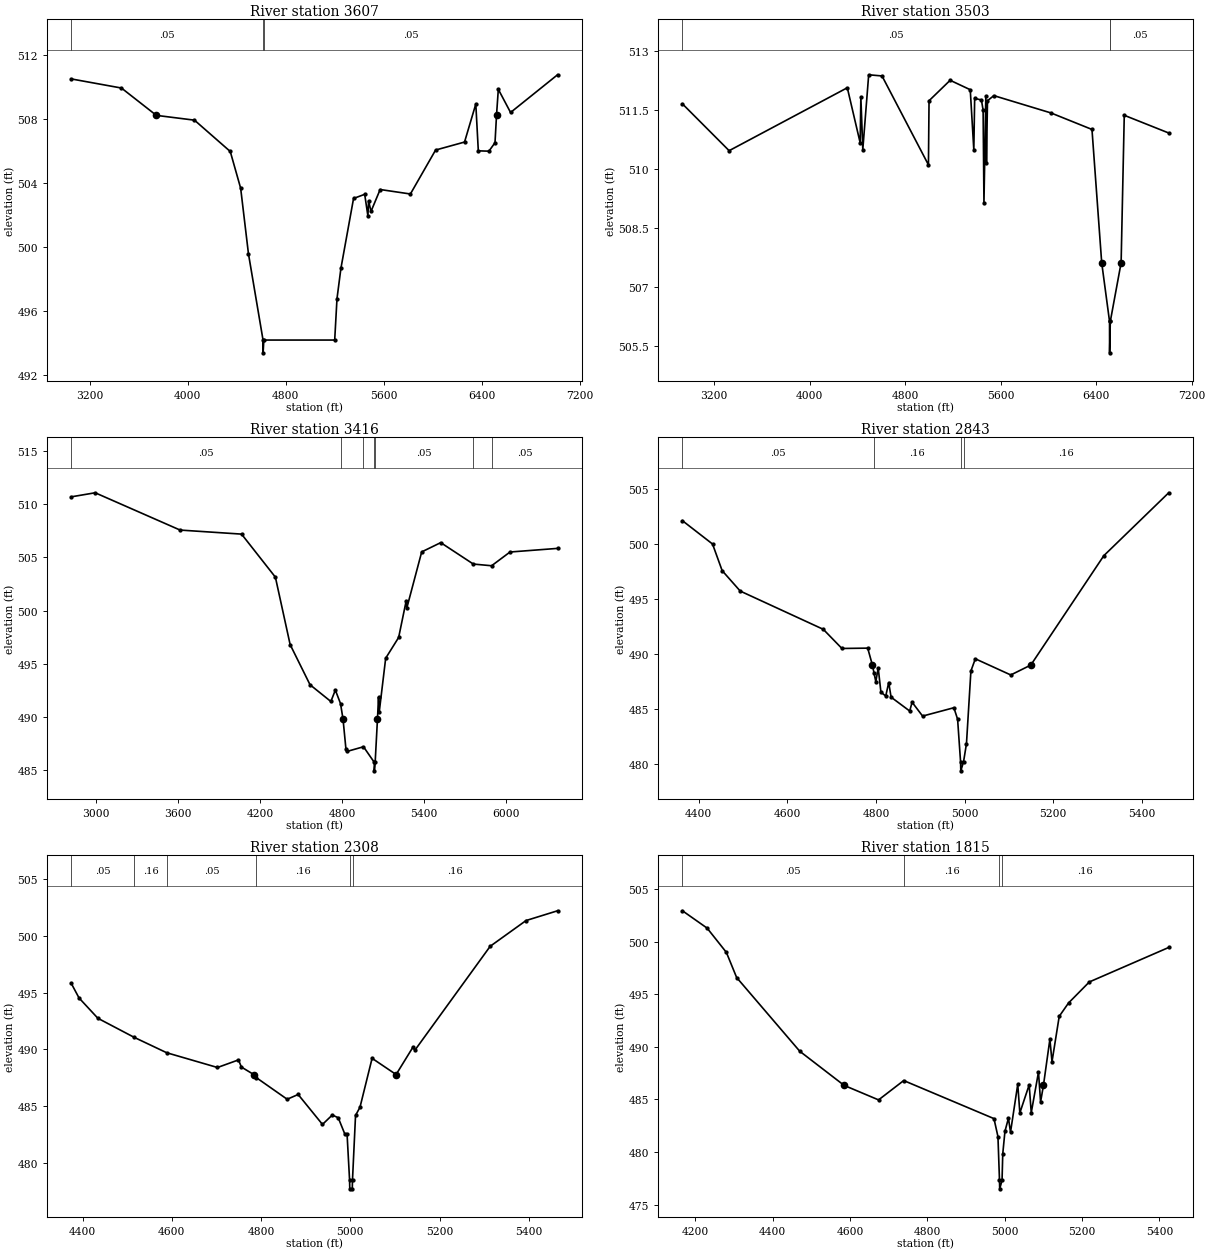
Type RM Length L Ch R = 1,3607,104,104,104
BEGIN DESCRIPTION:
Mapping XS 862dc26e
END DESCRIPTION:
XS GIS Cut Line= 6
      2767817.99      7058865.15      2767488.12      7057658.52
      2766680.82      7057484.91      2766507.21      7057541.34
      2766281.52      7058214.08      2766160.49      7059157.96
#Sta/Elev= 30
  3048.9  510.50  3458.5  509.93  3743.5  508.22  4054.7  507.92  4346.9  505.96
  4431.8  503.66  4495.4  499.56  4614.5  494.16  4615.0  493.36  4621.0  494.16
  5199.6  494.16  5218.3  496.75  5250.2  498.64  5353.5  503.02  5444.5  503.28
  5470.8  501.92  5476.1  502.87  5496.0  502.21  5570.7  503.58  5817.7  503.30
  6023.4  506.05  6259.7  506.55  6351.7  508.93  6372.2  506.00  6458.7  505.98
  6508.5  506.51  6520.8  508.22  6535.5  509.85  6635.6  508.40  7019.1  510.76
#Mann=3,-1,0
  3048.9    0.05       0  4614.5   0.033       0  4621.0    0.05       0
Bank Sta=3743.5,6520.8
Exp/Cntr=0.3,0.1

Type RM Length L Ch R = 1,3503,87,87,87
BEGIN DESCRIPTION:
Mapping XS 4fe1bac4
END DESCRIPTION:
XS GIS Cut Line= 6
      2767852.70      7058813.04      2767479.44      7057476.23
      2766637.42      7057389.43      2766359.64      7057636.82
      2766151.31      7058383.35      2766138.29      7059017.01
#Sta/Elev= 30
  2936.3  511.66  3327.2  510.47  4316.5  512.07  4424.2  510.67  4429.9  511.84
  4446.2  510.50  4495.5  512.40  4607.1  512.37  4995.8  510.11  5000.8  511.74
  5177.5  512.26  5345.8  512.02  5375.7  510.49  5382.7  511.80  5439.3  511.76
  5453.5  511.50  5460.5  509.14  5476.2  511.86  5481.5  510.16  5490.1  511.74
  5543.2  511.87  6021.4  511.43  6364.9  511.01  6446.3  507.62  6511.9  506.13
  6512.4  505.33  6518.4  506.13  6608.8  507.62  6635.2  511.37  7007.2  510.92
#Mann=3,-1,0
  2936.3    0.05       0  6511.9    0.03       0  6518.4    0.05       0
Bank Sta=6446.3,6608.8
Exp/Cntr=0.3,0.1

Type RM Length L Ch R = 1,3416,573,573,573
BEGIN DESCRIPTION:
Mapping XS 4378e920
END DESCRIPTION:
XS GIS Cut Line= 6
      2767878.75      7058791.38      2767579.26      7057484.91
      2767466.41      7057350.36      2767188.64      7057272.24
      2766429.09      7057350.36      2766091.49      7058277.78
#Sta/Elev= 30
  2820.9  510.68  2995.5  511.06  3616.6  507.56  4066.1  507.18  4313.5  503.14
  4421.4  496.81  4566.9  493.04  4719.2  491.47  4752.1  492.54  4789.9  491.27
  4808.3  489.80  4829.5  487.00  4839.5  486.79  4957.9  487.22  5036.6  485.76
  5037.1  484.96  5043.2  485.76  5060.0  489.80  5067.7  491.86  5072.7  490.45
  5120.1  495.53  5215.0  497.48  5269.5  500.88  5274.6  500.24  5383.5  505.51
  5522.7  506.38  5761.0  504.37  5894.8  504.21  6029.4  505.50  6377.0  505.84
#Mann=7,-1,0
  2820.9    0.05       0  4789.9    0.16       0  4957.9    0.05       0
  5036.6    0.03       0  5043.2    0.05       0  5761.0    0.16       0
  5894.8    0.05       0
Bank Sta=4808.3,5060
Exp/Cntr=0.3,0.1

Type RM Length L Ch R = 1,2843,535,535,535
BEGIN DESCRIPTION:
Mapping XS 809fa0af
END DESCRIPTION:
XS GIS Cut Line= 3
      2767557.55      7057241.85      2766993.32      7057003.14
      2766508.64      7056994.49
#Sta/Elev= 30
  4363.1  502.14  4431.0  500.02  4452.7  497.60  4493.5  495.74  4681.0  492.26
  4723.0  490.52  4781.2  490.55  4791.8  489.01  4795.6  488.26  4799.5  487.50
  4804.9  488.75  4811.0  486.55  4821.9  486.19  4828.6  487.42  4834.0  486.09
  4876.0  484.83  4881.4  485.63  4905.1  484.37  4975.7  485.13  4984.1  484.08
  4990.8  480.19  4991.3  479.39  4997.4  480.19  5004.1  481.86  5014.1  488.47
  5024.1  489.58  5104.1  488.11  5149.3  489.01  5314.1  498.96  5460.5  504.68
#Mann=4,-1,0
  4363.1    0.05       0  4795.6    0.16       0  4990.8    0.07       0
  4997.4    0.16       0
Bank Sta=4791.8,5149.3
Exp/Cntr=0.3,0.1

Type RM Length L Ch R = 1,2308,493,493,493
BEGIN DESCRIPTION:
LAKE FORK CREEK TRIB 4 3.0
END DESCRIPTION:
XS GIS Cut Line= 3
      2767570.57      7056894.63      2766997.66      7056673.28
      2766524.96      7056725.00
#Sta/Elev= 30
  4374.6  495.81  4392.0  494.53  4434.2  492.74  4515.5  491.06  4588.5  489.70
  4702.2  488.40  4749.3  489.07  4755.8  488.44  4783.5  487.78  4789.1  487.51
  4858.4  485.60  4883.0  486.02  4937.5  483.38  4959.5  484.21  4972.8  483.97
  4987.5  482.54  4992.6  482.54  4998.2  478.50  4998.7  477.70  5004.3  477.70
  5004.8  478.50  5011.6  484.17  5021.6  484.90  5048.7  489.21  5102.5  487.78
  5139.9  490.17  5144.9  489.94  5313.4  499.09  5393.8  501.36  5464.3  502.22
#Mann=6,-1,0
  4374.6    0.05       0  4515.5    0.16       0  4588.5    0.05       0
  4789.1    0.16       0  4998.2    0.07       0  5004.8    0.16       0
Bank Sta=4783.5,5102.5
Exp/Cntr=0.3,0.1

Type RM Length L Ch R = 1,1815,622,622,622
BEGIN DESCRIPTION:
LAKE FORK CREEK TRIB 4 2.0
END DESCRIPTION:
XS GIS Cut Line= 3
      2767825.02      7056625.01      2767015.03      7056417.20
      2766624.96      7056575.01
#Sta/Elev= 30
  4166.9  502.94  4230.7  501.29  4280.5  498.98  4307.0  496.59  4470.1  489.58
  4584.9  486.33  4673.9  484.95  4738.9  486.79  4972.2  483.17  4982.5  481.46
  4986.5  477.29  4987.0  476.49  4993.1  477.29  4994.9  479.81  5000.6  481.96
  5009.6  483.21  5015.0  481.88  5033.7  486.44  5039.1  483.71  5063.2  486.38
  5068.6  483.73  5087.3  487.60  5092.7  484.75  5100.1  486.33  5116.8  490.73
  5122.2  488.58  5140.9  492.90  5165.0  494.17  5218.7  496.17  5423.9  499.45
#Mann=4,-1,0
  4166.9    0.05       0  4738.9    0.16       0  4986.5    0.07       0
  4993.1    0.16       0
Bank Sta=4584.9,5100.1
Exp/Cntr=0.3,0.1

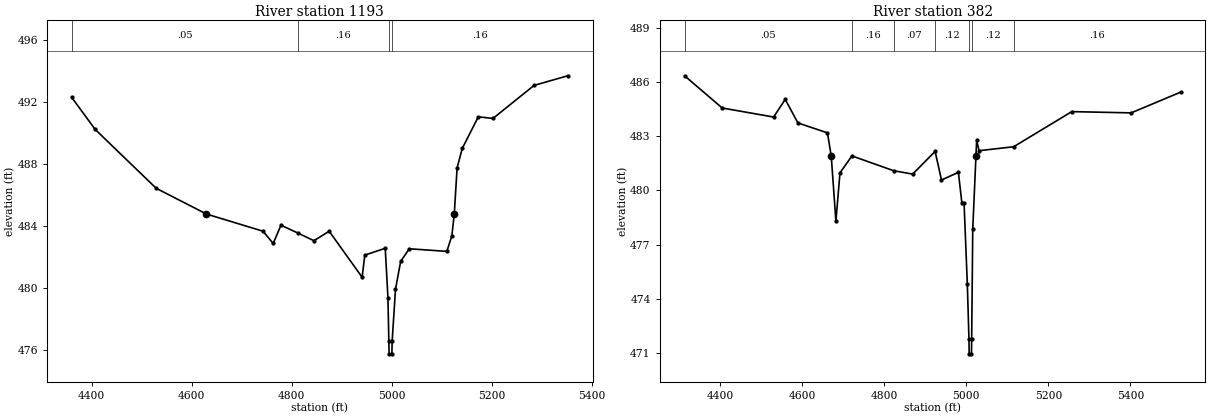
Type RM Length L Ch R = 1,1193,811,811,811
BEGIN DESCRIPTION:
Mapping XS 6ad63d33
END DESCRIPTION:
XS GIS Cut Line= 3
      2767731.15      7056217.55      2767132.21      7056104.70
      2766759.44      7056191.40
#Sta/Elev= 30
  4359.9  492.31  4406.9  490.24  4529.0  486.44  4629.5  484.78  4742.7  483.67
  4763.0  482.88  4778.5  484.06  4812.0  483.56  4844.4  483.06  4875.0  483.67
  4940.9  480.70  4946.2  482.13  4987.1  482.57  4992.5  479.39  4994.3  476.56
  4994.8  475.76  5000.4  475.76  5000.9  476.56  5007.6  479.92  5017.9  481.72
  5035.1  482.54  5110.3  482.37  5120.3  483.37  5125.2  484.78  5130.8  487.75
  5141.1  489.01  5173.2  491.05  5202.7  490.95  5284.8  493.08  5352.1  493.70
#Mann=4,-1,0
  4359.9    0.05       0  4812.0    0.16       0  4994.3    0.07       0
  5000.9    0.16       0
Bank Sta=4629.5,5125.2
Exp/Cntr=0.3,0.1

Type RM Length L Ch R = 1,382,0,0,0
BEGIN DESCRIPTION:
LAKE FORK CREEK TRIB 4 1.0
END DESCRIPTION:
XS GIS Cut Line= 3
      2767683.45      7055900.72      2767023.71      7055740.12
      2766572.34      7056017.89
#Sta/Elev= 30
  4313.3  486.37  4405.2  484.58  4530.4  484.08  4558.7  485.06  4589.6  483.75
  4661.6  483.20  4670.9  481.90  4682.2  478.29  4692.1  480.98  4721.3  481.92
  4822.7  481.10  4869.3  480.91  4924.0  482.17  4939.5  480.58  4980.7  481.01
  4989.1  479.33  4994.5  479.33  5002.5  474.80  5006.5  471.73  5007.0  470.93
  5012.6  470.93  5013.1  471.73  5015.7  477.86  5023.5  481.90  5025.2  482.78
  5031.1  482.21  5115.5  482.43  5257.1  484.38  5401.8  484.31  5522.3  485.46
#Mann=7,-1,0
  4313.3    0.05       0  4721.3    0.16       0  4822.7    0.07       0
  4924.0    0.12       0  5006.5    0.07       0  5013.1    0.12       0
  5115.5    0.16       0
Bank Sta=4670.9,5023.5
Exp/Cntr=0.3,0.1

Chan Stop Cuts=-1