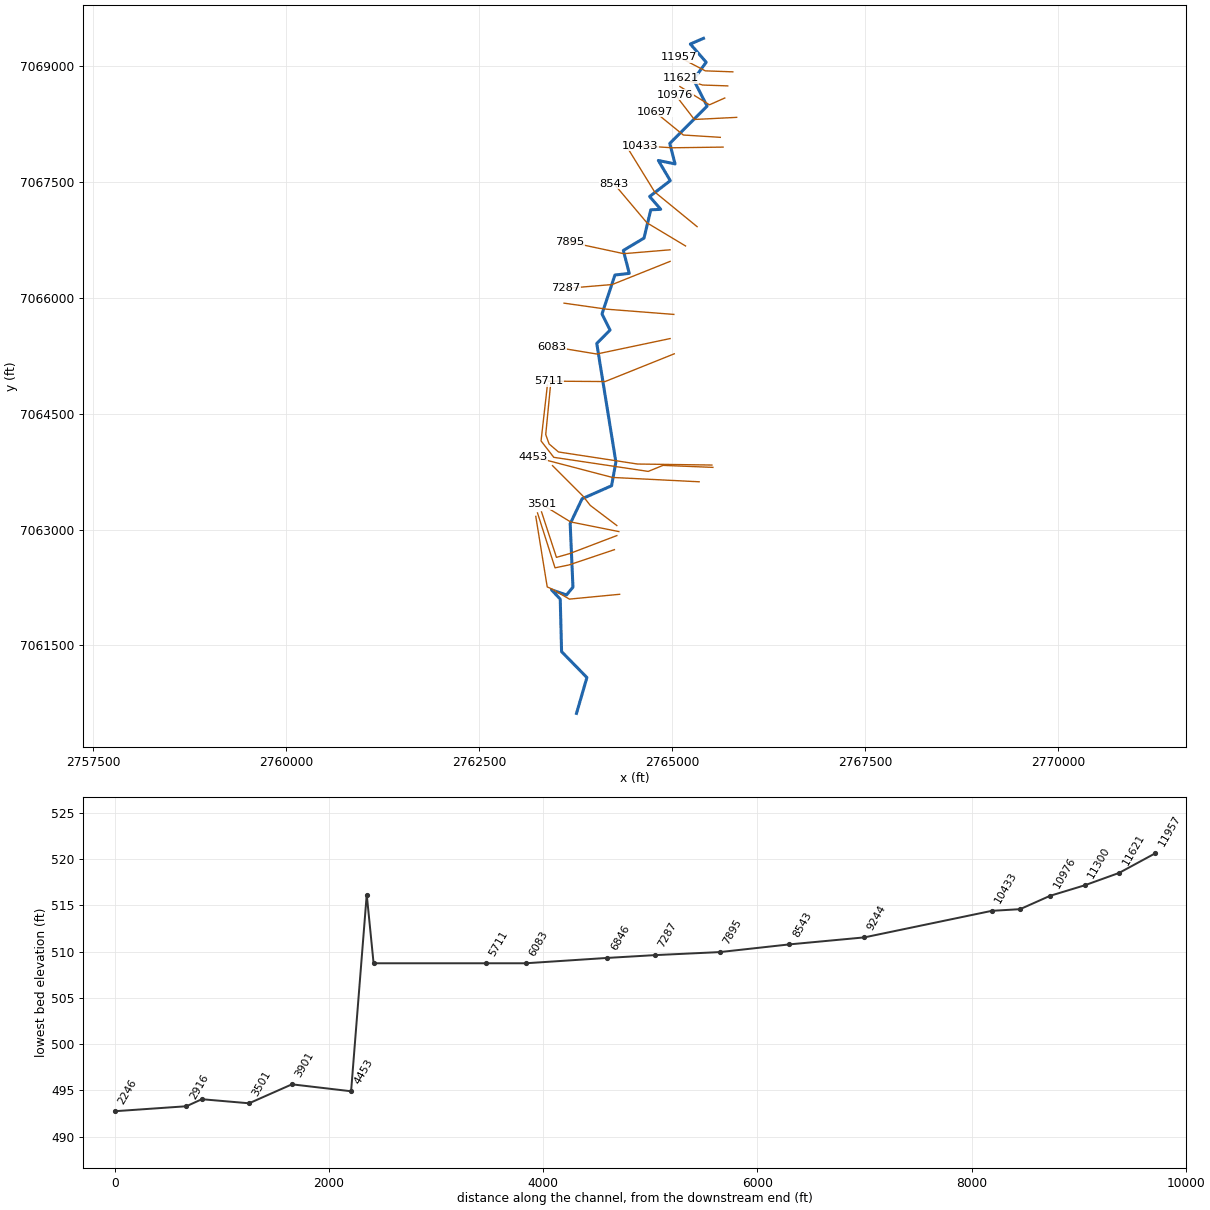
--- LAKE FORK CREEK TRIB 5.prj (project) ---

Proj Title=LAKE FORK CREEK TRIB 5 Base Level Engineering
Current Plan=p01
Default Exp/Contr=0.3,0.1
English Units
Geom File=g01
Flow File=f01
Plan File=p01
BEGIN DESCRIPTION:
LAKE FORK CREEK TRIB 5
END DESCRIPTION:

--- LAKE FORK CREEK TRIB 5.p01 (plan) ---

Plan Title=Multiple Run
Short Identifier=Multiple
Geom File=g01
Flow File=f01
Subcritical Flow
K Sum by GR= 0
Std Step Tol= 0.01
Critical Tol= 0.01
Num of Std Step Trials= 20
Max Error Tol= 0.3
Flow Tol Ratio= 0.001
Split Flow NTrial= 30
Split Flow Tol= 0.02
Split Flow Ratio= 0.02
Log Output Level= 0
Friction Slope Method= 1
Unsteady Friction Slope Method= 2
Unsteady Bridges Friction Slope Method= 1
Parabolic Critical Depth
Global Vel Dist=  1 , 1 , 1
Global Log Level= 0
CheckData=True
Encroach Param= -1, 0, 0, 0
BEGIN DESCRIPTION:
Multiple Run
END DESCRIPTION:

--- LAKE FORK CREEK TRIB 5.f01 (steady flow) ---

Flow Title=Multiple
Number of Profiles=7
Profile Names=10-year,25-year,50-year,1pct_min,100-year,1pct_plu,500-year
River Rch & RM= LAKE FORK CREEK ,Reach-1,11957
     636     842    1006     596    1188    2371    1656
River Rch & RM= LAKE FORK CREEK ,Reach-1,11621
     980    1327    1610     966    1927    3845    2760
Boundary for River Rch & Prof#=LAKE FORK CREEK ,Reach-1,1
Up Type=0
Dn Type=3
Dn Slope=0.005
Boundary for River Rch & Prof#=LAKE FORK CREEK ,Reach-1,2
Up Type=0
Dn Type=3
Dn Slope=0.005
Boundary for River Rch & Prof#=LAKE FORK CREEK ,Reach-1,3
Up Type=0
Dn Type=3
Dn Slope=0.005
Boundary for River Rch & Prof#=LAKE FORK CREEK ,Reach-1,4
Up Type=0
Dn Type=3
Dn Slope=0.005
Boundary for River Rch & Prof#=LAKE FORK CREEK ,Reach-1,5
Up Type=0
Dn Type=3
Dn Slope=0.005
Boundary for River Rch & Prof#=LAKE FORK CREEK ,Reach-1,6
Up Type=0
Dn Type=3
Dn Slope=0.005
Boundary for River Rch & Prof#=LAKE FORK CREEK ,Reach-1,7
Up Type=0
Dn Type=3
Dn Slope=0.005

--- LAKE FORK CREEK TRIB 5.g01 (geometry) ---

Geom Title=Existing Conditions

River Reach=LAKE FORK CREEK ,Reach-1
Reach XY= 30
      2765407.73      7069364.75      2765237.59      7069291.02
      2765442.82      7069055.17      2765278.02      7068830.54
      2765454.69      7068486.06      2764970.96      7068003.39
      2765039.67      7067737.77      2764822.91      7067782.36
      2764977.74      7067521.01      2764710.19      7067315.39
      2764853.87      7067149.41      2764725.05      7067143.21
      2764637.11      7066776.57      2764369.56      7066616.78
      2764446.35      7066319.51      2764260.55      7066298.45
      2764093.33      7065794.31      2764197.38      7065584.98
      2764025.21      7065411.57      2764272.94      7063875.63
      2764217.20      7063568.44      2763835.69      7063399.98
      2763680.86      7063076.69      2763716.78      7062254.22
      2763633.79      7062153.89      2763439.32      7062219.54
      2763552.04      7062099.39      2763569.38      7061419.36
      2763897.63      7061083.69      2763762.71      7060619.34

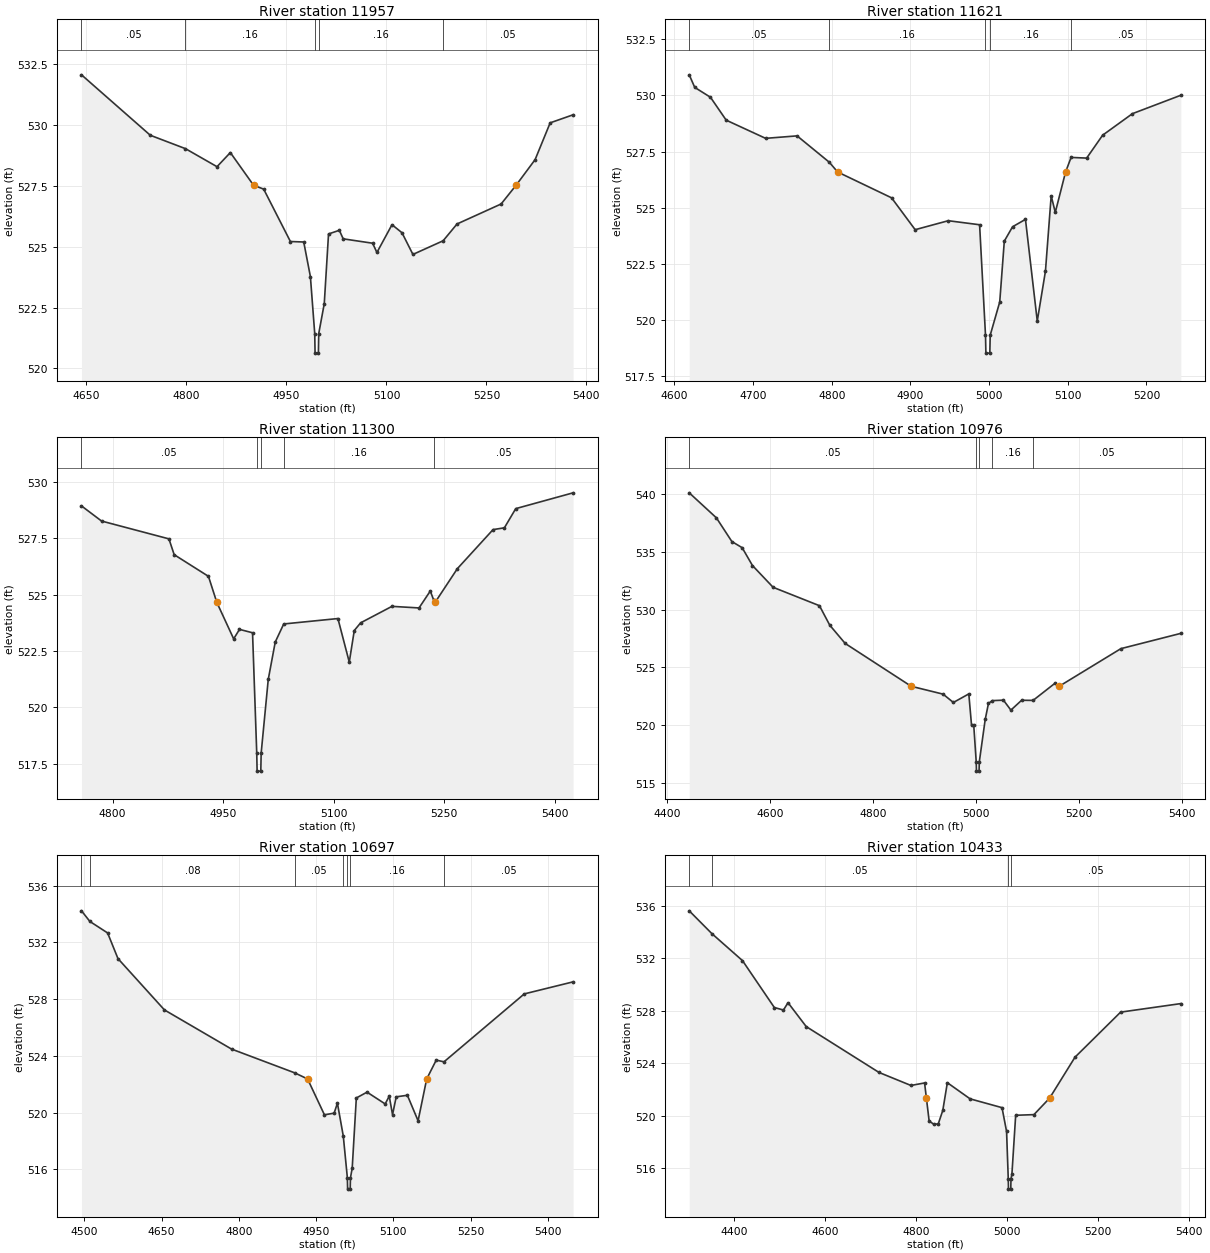
Type RM Length L Ch R = 1,11957,336,336,336
BEGIN DESCRIPTION:
LAKE FORK CREEK TRIB 5 13.0
END DESCRIPTION:
XS GIS Cut Line= 3
      2765788.16      7068930.52      2765430.90      7068943.54
      2765094.52      7069120.31
#Sta/Elev= 30
  4642.5  532.05  4745.7  529.57  4798.5  529.02  4845.8  528.28  4865.8  528.86
  4900.6  527.52  4915.8  527.36  4955.9  525.21  4975.9  525.19  4985.9  523.77
  4992.4  521.43  4992.9  520.63  4997.9  520.63  4998.4  521.43  5006.7  522.66
  5013.1  525.52  5029.3  525.67  5035.1  525.32  5079.2  525.14  5085.7  524.76
  5108.3  525.90  5123.3  525.57  5139.7  524.68  5185.0  525.24  5205.9  525.93
  5272.0  526.75  5294.5  527.52  5323.0  528.57  5345.6  530.08  5380.0  530.41
#Mann=5,-1,0
  4642.5    0.05       0  4798.5    0.16       0  4992.4    0.07       0
  4998.4    0.16       0  5185.0    0.05       0
Bank Sta=4900.6,5294.5
Exp/Cntr=0.3,0.1

Type RM Length L Ch R = 1,11621,321,321,321
BEGIN DESCRIPTION:
Mapping XS 53938a1c
END DESCRIPTION:
XS GIS Cut Line= 3
      2765722.01      7068748.72      2765396.99      7068759.74
      2765110.55      7068847.88
#Sta/Elev= 30
  4618.9  530.92  4625.9  530.36  4645.9  529.92  4665.9  528.90  4716.0  528.09
  4756.0  528.20  4796.8  527.03  4807.6  526.59  4876.1  525.44  4906.1  524.02
  4948.2  524.42  4988.0  524.24  4995.5  519.32  4996.0  518.52  5001.0  518.52
  5001.5  519.32  5013.6  520.80  5019.4  523.51  5029.9  524.15  5046.3  524.48
  5061.3  519.95  5071.7  522.17  5079.0  525.53  5084.2  524.79  5097.3  526.59
  5104.3  527.24  5124.1  527.21  5144.4  528.23  5182.3  529.19  5243.8  530.01
#Mann=5,-1,0
  4618.9    0.05       0  4796.8    0.16       0  4995.5    0.07       0
  5001.5    0.16       0  5104.3    0.05       0
Bank Sta=4807.6,5097.3
Exp/Cntr=0.3,0.1

Type RM Length L Ch R = 1,11300,324,324,324
BEGIN DESCRIPTION:
Mapping XS 6743f20f
END DESCRIPTION:
XS GIS Cut Line= 3
      2765683.42      7068591.69      2765485.14      7068503.56
      2765102.62      7068740.23
#Sta/Elev= 30
  4757.9  528.93  4785.1  528.26  4876.5  527.47  4883.6  526.77  4930.1  525.81
  4941.4  524.66  4964.3  523.04  4972.2  523.46  4989.9  523.31  4995.6  517.98
  4996.1  517.18  5001.1  517.18  5001.6  517.98  5011.2  521.24  5020.7  522.90
  5032.2  523.70  5105.7  523.94  5121.1  522.01  5127.9  523.41  5136.5  523.75
  5179.0  524.48  5215.7  524.41  5231.0  525.16  5235.7  524.75  5237.6  524.66
  5267.7  526.15  5316.1  527.88  5331.5  527.96  5346.9  528.81  5424.7  529.51
#Mann=5,-1,0
  4757.9    0.05       0  4995.6    0.03       0  5001.6    0.05       0
  5032.2    0.16       0  5235.7    0.05       0
Bank Sta=4941.4,5237.6
Exp/Cntr=0.3,0.1

Type RM Length L Ch R = 1,10976,279,279,279
BEGIN DESCRIPTION:
Mapping XS 85a43378
END DESCRIPTION:
XS GIS Cut Line= 3
      2765837.75      7068341.04      2765289.56      7068313.50
      2765041.64      7068635.80
#Sta/Elev= 30
  4443.2  540.08  4496.0  537.92  4526.1  535.87  4546.1  535.34  4566.1  533.80
  4606.2  531.92  4696.3  530.33  4716.3  528.65  4746.3  527.07  4874.6  523.37
  4936.6  522.69  4956.6  521.97  4986.6  522.71  4991.9  520.00  4996.2  520.00
  5001.0  516.84  5001.5  516.04  5006.5  516.04  5007.0  516.84  5018.5  520.51
  5024.8  521.89  5032.4  522.13  5053.9  522.17  5068.4  521.31  5089.2  522.16
  5111.5  522.15  5153.5  523.61  5162.3  523.37  5282.2  526.62  5398.7  527.94
#Mann=5,-1,0
  4443.2    0.05       0  5001.0    0.03       0  5007.0    0.05       0
  5032.4    0.16       0  5111.5    0.05       0
Bank Sta=4874.6,5162.3
Exp/Cntr=0.3,0.1

Type RM Length L Ch R = 1,10697,264,264,264
BEGIN DESCRIPTION:
Mapping XS 020c1cf8
END DESCRIPTION:
XS GIS Cut Line= 3
      2765625.64      7068082.11      2765146.32      7068112.41
      2764778.60      7068411.53
#Sta/Elev= 30
  4494.5  534.23  4510.8  533.48  4545.2  532.67  4565.3  530.86  4655.5  527.24
  4785.7  524.48  4908.5  522.80  4933.4  522.37  4966.1  519.84  4984.9  519.96
  4991.3  520.66  5002.7  518.34  5010.6  515.40  5011.1  514.60  5016.1  514.60
  5016.6  515.40  5020.0  516.08  5028.0  521.03  5048.8  521.44  5084.0  520.61
  5091.9  521.16  5098.3  519.85  5105.4  521.11  5127.1  521.22  5147.9  519.42
  5164.6  522.37  5183.1  523.70  5198.2  523.58  5354.0  528.37  5448.8  529.22
#Mann=7,-1,0
  4494.5    0.05       0  4510.8    0.08       0  4908.5    0.05       0
  5002.7    0.16       0  5010.6    0.03       0  5016.6    0.16       0
  5198.2    0.05       0
Bank Sta=4933.4,5164.6
Exp/Cntr=0.3,0.1

Type RM Length L Ch R = 1,10433,1189,1189,1189
BEGIN DESCRIPTION:
LAKE FORK CREEK TRIB 5 12.0
END DESCRIPTION:
XS GIS Cut Line= 3
      2765661.97      7067955.59      2765006.55      7067946.91
      2764582.94      7067973.20
#Sta/Elev= 30
  4302.3  535.60  4351.9  533.87  4419.3  531.81  4489.3  528.24  4509.3  528.05
  4519.3  528.61  4559.3  526.79  4719.2  523.30  4789.3  522.31  4819.3  522.50
  4823.3  521.34  4829.3  519.61  4839.3  519.36  4849.3  519.38  4859.3  520.41
  4869.3  522.52  4919.3  521.29  4989.4  520.62  4999.4  518.81  5003.1  515.22
  5003.6  514.42  5008.6  514.42  5009.1  515.22  5011.1  515.54  5019.4  520.04
  5059.5  520.09  5093.8  521.34  5149.7  524.46  5249.9  527.89  5382.2  528.54
#Mann=4,-1,0
  4302.3    0.08       0  4351.9    0.05       0  5003.1    0.04       0
  5009.1    0.05       0
Bank Sta=4823.3,5093.8
Exp/Cntr=0.3,0.1

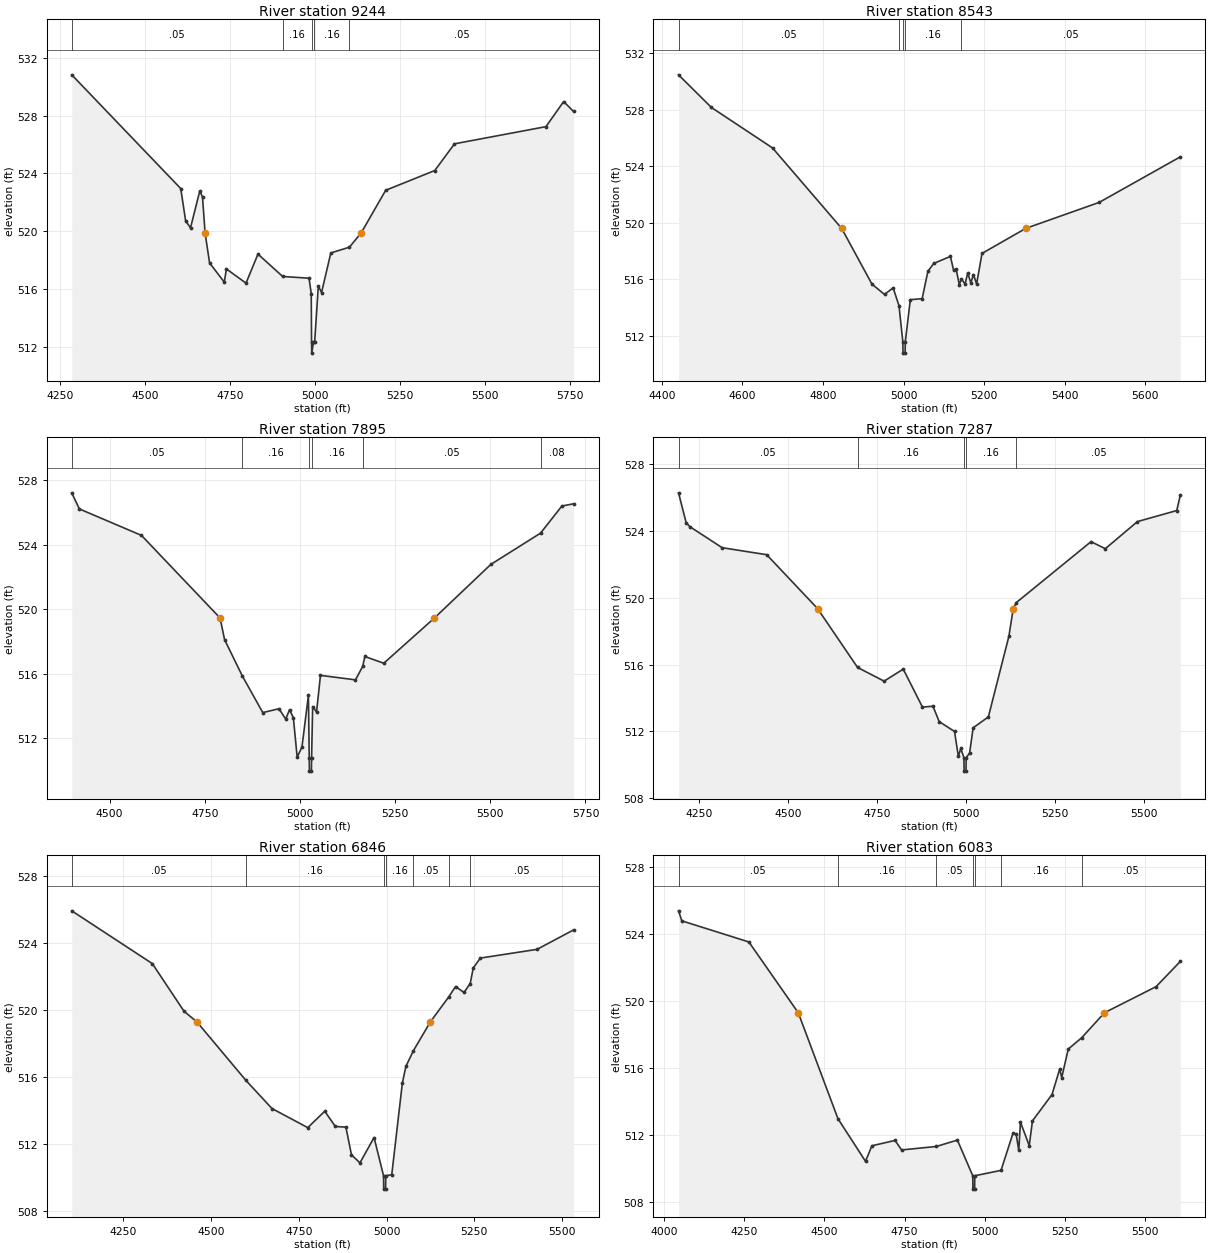
Type RM Length L Ch R = 1,9244,701,701,701
BEGIN DESCRIPTION:
LAKE FORK CREEK TRIB 5 11.0
END DESCRIPTION:
XS GIS Cut Line= 3
      2765324.98      7066925.02      2764775.00      7067375.00
      2764375.01      7068024.98
#Sta/Elev= 30
  4285.6  530.83  4605.7  522.95  4620.1  520.71  4634.4  520.23  4661.7  522.79
  4669.6  522.37  4677.2  519.87  4690.4  517.80  4733.5  516.47  4739.9  517.38
  4797.4  516.40  4832.5  518.41  4905.1  516.86  4982.6  516.74  4989.0  515.67
  4989.9  512.35  4990.4  511.55  4996.0  512.35  4999.1  512.35  5009.8  516.20
  5019.3  515.75  5046.5  518.49  5101.1  518.89  5135.4  519.87  5207.6  522.83
  5351.8  524.20  5409.7  526.05  5678.3  527.24  5730.4  528.98  5759.4  528.29
#Mann=5,-1,0
  4285.6    0.05       0  4905.1    0.16       0  4989.9    0.07       0
  4996.0    0.16       0  5101.1    0.05       0
Bank Sta=4677.2,5135.4
Exp/Cntr=0.3,0.1

Type RM Length L Ch R = 1,8543,648,648,648
BEGIN DESCRIPTION:
LAKE FORK CREEK TRIB 5 10.0
END DESCRIPTION:
XS GIS Cut Line= 3
      2765175.02      7066674.99      2764675.00      7066975.00
      2764248.03      7067481.28
#Sta/Elev= 30
  4441.6  530.47  4523.3  528.16  4674.9  525.30  4846.5  519.61  4921.7  515.67
  4952.8  514.94  4974.2  515.41  4988.7  514.15  4998.3  511.59  4998.8  510.79
  5003.9  510.79  5004.4  511.59  5016.9  514.57  5046.2  514.64  5060.5  516.57
  5074.8  517.13  5116.4  517.63  5124.2  516.66  5130.7  516.72  5138.5  515.62
  5143.5  516.04  5152.8  515.68  5159.3  516.46  5167.1  515.76  5173.6  516.34
  5181.4  515.68  5194.8  517.84  5303.3  519.61  5485.7  521.45  5687.0  524.67
#Mann=5,-1,0
  4441.6    0.05       0  4988.7    0.16       0  4998.3    0.07       0
  5004.4    0.16       0  5143.5    0.05       0
Bank Sta=4846.5,5303.3
Exp/Cntr=0.3,0.1

Type RM Length L Ch R = 1,7895,608,608,608
BEGIN DESCRIPTION:
LAKE FORK CREEK TRIB 5 9.0
END DESCRIPTION:
XS GIS Cut Line= 3
      2764974.96      7066625.00      2764375.00      7066575.00
      2763675.03      7066724.99
#Sta/Elev= 30
  4400.8  527.22  4420.8  526.22  4583.9  524.58  4790.3  519.46  4802.1  518.12
  4848.6  515.87  4902.5  513.59  4945.1  513.83  4962.7  513.19  4972.7  513.76
  4982.8  513.28  4992.8  510.83  5005.4  511.45  5022.4  514.67  5024.5  510.76
  5025.0  509.96  5030.2  509.96  5030.7  510.76  5033.5  513.96  5043.7  513.63
  5054.0  515.90  5146.0  515.62  5164.8  516.45  5170.7  517.07  5220.2  516.65
  5353.4  519.46  5501.4  522.78  5632.0  524.72  5688.0  526.40  5718.7  526.54
#Mann=6,-1,0
  4400.8    0.05       0  4848.6    0.16       0  5024.5    0.07       0
  5030.7    0.16       0  5164.8    0.05       0  5632.0    0.08       0
Bank Sta=4790.3,5353.4
Exp/Cntr=0.3,0.1

Type RM Length L Ch R = 1,7287,441,441,441
BEGIN DESCRIPTION:
LAKE FORK CREEK TRIB 5 8.0
END DESCRIPTION:
XS GIS Cut Line= 3
      2764975.01      7066475.00      2764225.00      7066175.00
      2763624.96      7066125.00
#Sta/Elev= 30
  4191.4  526.27  4212.9  524.48  4223.7  524.24  4313.9  522.99  4439.1  522.57
  4582.0  519.35  4694.4  515.83  4769.0  515.01  4822.8  515.73  4876.7  513.46
  4906.3  513.51  4923.8  512.59  4966.9  512.00  4977.6  510.51  4984.4  510.99
  4993.3  510.43  4993.8  509.63  4999.1  509.63  4999.6  510.43  5009.2  510.71
  5019.2  512.22  5061.9  512.87  5119.6  517.69  5131.8  519.35  5140.6  519.71
  5350.4  523.35  5390.5  522.93  5480.8  524.55  5591.2  525.21  5601.3  526.13
#Mann=5,-1,0
  4191.4    0.05       0  4694.4    0.16       0  4993.3    0.07       0
  4999.6    0.16       0  5140.6    0.05       0
Bank Sta=4582,5131.8
Exp/Cntr=0.3,0.1

Type RM Length L Ch R = 1,6846,763,763,763
BEGIN DESCRIPTION:
Mapping XS a90f7f48
END DESCRIPTION:
XS GIS Cut Line= 3
      2765023.87      7065788.05      2764154.12      7065855.76
      2763602.00      7065933.89
#Sta/Elev= 30
  4102.7  525.94  4332.3  522.79  4422.5  519.95  4459.8  519.30  4598.6  515.83
  4673.3  514.14  4775.3  513.00  4823.7  513.98  4853.8  513.07  4883.9  513.03
  4899.9  511.37  4924.0  510.90  4964.2  512.41  4991.2  510.13  4991.7  509.33
  4997.0  509.33  4997.5  510.13  5014.6  510.19  5044.9  515.67  5055.0  516.66
  5076.3  517.59  5124.3  519.30  5176.9  520.80  5196.4  521.42  5220.5  521.07
  5238.2  521.60  5246.9  522.53  5267.1  523.12  5428.6  523.64  5532.7  524.80
#Mann=7,-1,0
  4102.7    0.05       0  4598.6    0.16       0  4991.2    0.07       0
  4997.5    0.16       0  5076.3    0.05       0  5176.9    0.08       0
  5238.2    0.05       0
Bank Sta=4459.8,5124.3
Exp/Cntr=0.3,0.1

Type RM Length L Ch R = 1,6083,372,372,372
BEGIN DESCRIPTION:
LAKE FORK CREEK TRIB 5 6.0
END DESCRIPTION:
XS GIS Cut Line= 3
      2764975.04      7065475.01      2764025.00      7065275.00
      2763440.56      7065371.39
#Sta/Elev= 30
  4045.8  525.38  4056.1  524.78  4264.9  523.52  4418.8  519.29  4542.4  512.96
  4628.3  510.41  4648.1  511.34  4720.3  511.66  4740.7  511.09  4849.0  511.30
  4914.5  511.68  4962.4  509.55  4962.9  508.75  4968.2  508.75  4968.7  509.55
  5050.4  509.87  5087.6  512.08  5097.7  512.03  5105.8  511.06  5110.9  512.76
  5138.3  511.35  5148.4  512.83  5209.2  514.40  5233.2  515.92  5239.6  515.42
  5259.9  517.12  5301.4  517.79  5372.7  519.29  5533.6  520.85  5609.0  522.36
#Mann=7,-1,0
  4045.8    0.05       0  4542.4    0.16       0  4849.0    0.05       0
  4962.4   0.035       0  4968.7    0.05       0  5050.4    0.16       0
  5301.4    0.05       0
Bank Sta=4418.8,5372.7
Exp/Cntr=0.3,0.1

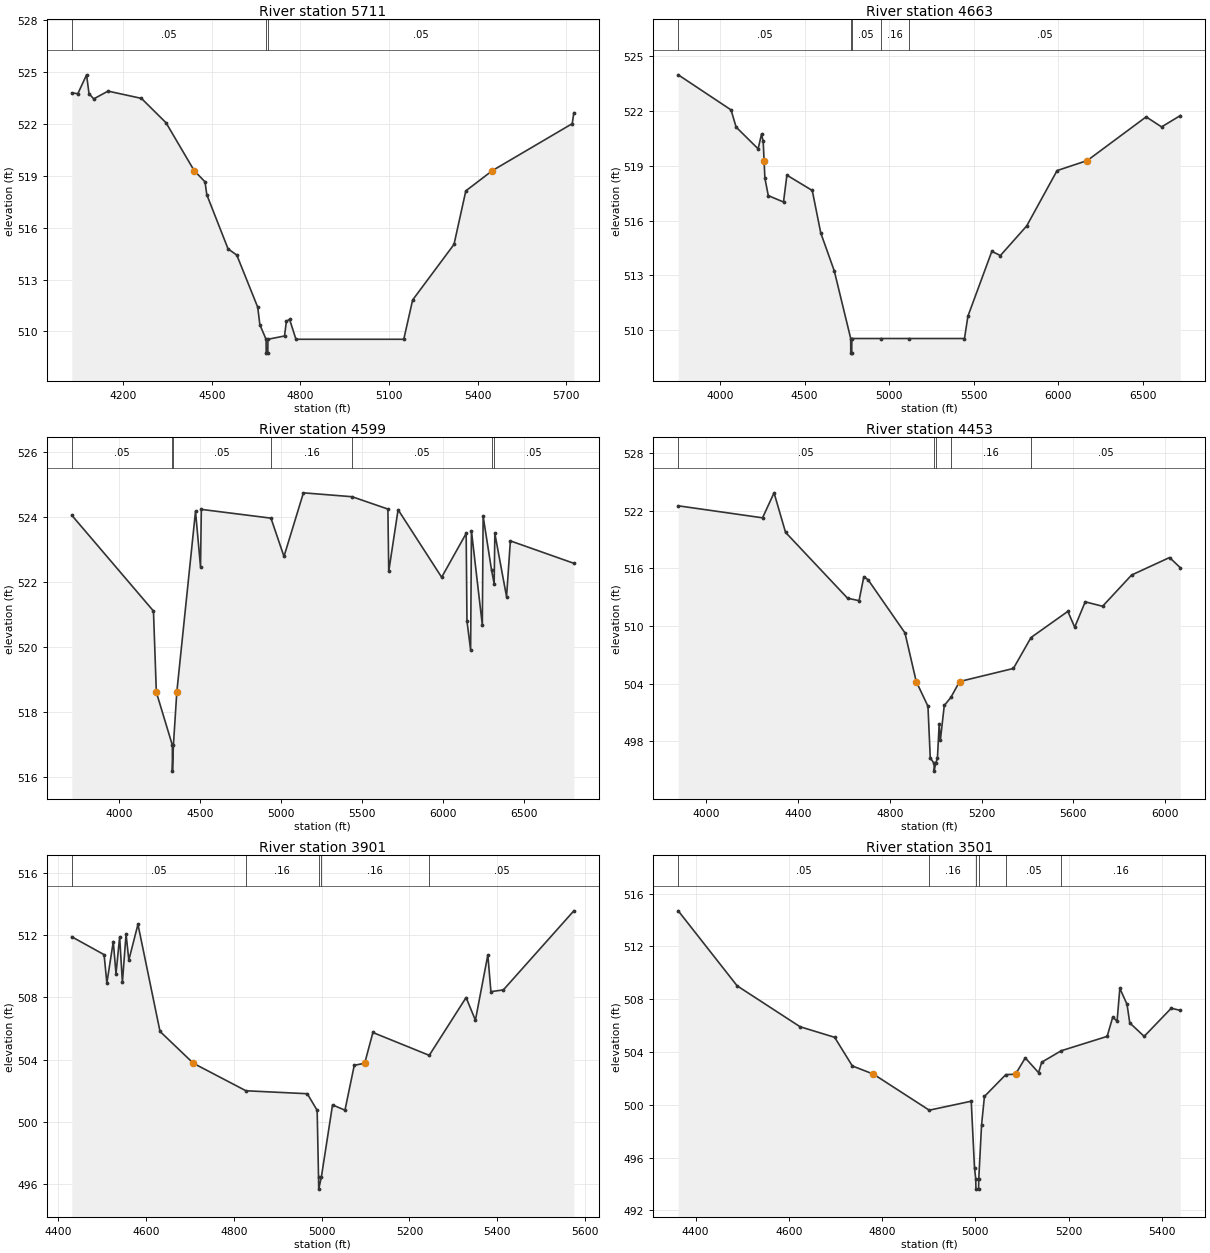
Type RM Length L Ch R = 1,5711,1048,1048,1048
BEGIN DESCRIPTION:
Mapping XS 06373f7f
END DESCRIPTION:
XS GIS Cut Line= 3
      2765029.09      7065277.62      2764133.29      7064918.26
      2763399.50      7064923.46
#Sta/Elev= 30
  4026.2  523.78  4046.7  523.73  4076.3  524.82  4084.5  523.74  4100.5  523.43
  4148.9  523.88  4261.9  523.46  4345.3  522.05  4440.4  519.29  4477.1  518.64
  4483.1  517.90  4555.1  514.77  4584.7  514.41  4655.5  511.40  4662.7  510.39
  4683.7  509.55  4684.2  508.75  4689.6  508.75  4690.1  509.55  4746.1  509.74
  4752.5  510.59  4763.3  510.70  4784.8  509.55  5149.7  509.55  5179.7  511.82
  5319.7  515.03  5359.7  518.12  5449.6  519.29  5719.7  522.00  5725.2  522.63
#Mann=3,-1,0
  4026.2    0.05       0  4683.7   0.033       0  4690.1    0.05       0
Bank Sta=4440.4,5449.6
Exp/Cntr=0.3,0.1

Type RM Length L Ch R = 1,4663,64,64,64
BEGIN DESCRIPTION:
Mapping XS d6a76498
END DESCRIPTION:
XS GIS Cut Line= 6
      2765516.93      7063836.66      2764553.43      7063849.68
      2763529.12      7064005.93      2763407.59      7064110.10
      2763364.19      7064231.63      2763429.29      7064904.35
#Sta/Elev= 30
  3753.5  523.98  4065.5  522.06  4095.5  521.12  4225.5  519.93  4245.5  520.73
  4255.5  520.34  4260.7  519.29  4265.5  518.33  4285.5  517.37  4375.5  517.02
  4395.5  518.49  4545.5  517.65  4595.5  515.33  4675.5  513.25  4772.6  509.55
  4773.1  508.75  4778.7  508.75  4779.2  509.55  4949.8  509.55  5116.8  509.55
  5444.9  509.55  5465.1  510.77  5606.5  514.32  5657.0  514.09  5812.4  515.71
  5992.0  518.74  6170.6  519.29  6518.4  521.68  6609.5  521.13  6720.2  521.75
#Mann=5,-1,0
  3753.5    0.05       0  4772.6    0.07       0  4779.2    0.05       0
  4949.8    0.16       0  5116.8    0.05       0
Bank Sta=4260.7,6170.6
Exp/Cntr=0.3,0.1

Type RM Length L Ch R = 1,4599,146,146,146
BEGIN DESCRIPTION:
Mapping XS 3ee7e3e3
END DESCRIPTION:
XS GIS Cut Line= 6
      2765530.02      7063806.28      2764883.29      7063832.32
      2764692.31      7063754.20      2763468.36      7063936.49
      2763303.43      7064149.16      2763385.90      7064874.04
#Sta/Elev= 30
  3704.8  524.06  4210.2  521.11  4228.0  518.61  4327.0  516.98  4327.5  516.18
  4333.6  516.98  4354.5  518.61  4470.3  524.18  4501.3  522.47  4506.3  524.24
  4937.1  523.97  5017.6  522.79  5137.9  524.75  5439.1  524.63  5660.5  524.25
  5665.6  522.33  5723.5  524.23  5993.0  522.15  6144.6  523.50  6149.6  520.80
  6172.2  519.91  6177.2  523.58  6244.6  520.68  6249.6  524.03  6302.0  522.36
  6317.8  521.95  6322.0  523.50  6394.5  521.55  6418.1  523.27  6810.7  522.58
#Mann=7,-1,0
  3704.8    0.05       0  4327.0    0.07       0  4333.6    0.05       0
  4937.1    0.16       0  5439.1    0.05       0  6302.0    0.08       0
  6317.8    0.05       0
Bank Sta=4228,4354.5
Exp/Cntr=0.3,0.1

Type RM Length L Ch R = 1,4453,552,552,552
BEGIN DESCRIPTION:
LAKE FORK CREEK TRIB 5 4.0
END DESCRIPTION:
XS GIS Cut Line= 3
      2765352.09      7063619.65      2764227.90      7063676.07
      2763199.61      7063945.08
#Sta/Elev= 30
  3877.6  522.51  4245.1  521.26  4295.2  523.86  4345.3  519.75  4615.6  512.90
  4665.7  512.64  4686.6  515.14  4705.7  514.80  4865.9  509.29  4915.0  504.23
  4966.1  501.66  4976.1  496.30  4992.8  495.71  4993.3  494.91  4999.4  495.71
  5007.3  496.23  5015.0  499.77  5020.2  498.14  5037.2  501.74  5065.8  502.57
  5104.0  504.23  5338.5  505.59  5415.4  508.81  5575.9  511.53  5605.7  509.88
  5651.6  512.52  5727.3  512.06  5853.8  515.31  6019.2  517.13  6066.1  516.07
#Mann=5,-1,0
  3877.6    0.05       0  4992.8    0.03       0  4999.4    0.05       0
  5065.8    0.16       0  5415.4    0.05       0
Bank Sta=4915,5104
Exp/Cntr=0.3,0.1

Type RM Length L Ch R = 1,3901,400,400,400
BEGIN DESCRIPTION:
Mapping XS d5749893
END DESCRIPTION:
XS GIS Cut Line= 4
      2764285.16      7063052.84      2763941.45      7063313.23
      2763847.70      7063433.02      2763451.87      7063828.84
#Sta/Elev= 30
  4431.1  511.90  4504.7  510.75  4511.0  508.92  4525.6  511.59  4531.8  509.52
  4540.1  511.89  4546.4  508.96  4554.7  512.07  4561.0  510.40  4581.8  512.70
  4632.0  505.81  4707.9  503.76  4827.7  501.99  4967.3  501.80  4989.8  500.73
  4992.9  496.46  4993.4  495.66  4999.5  496.46  5024.8  501.08  5053.1  500.74
  5074.3  503.63  5098.0  503.76  5116.7  505.74  5245.0  504.27  5328.9  507.99
  5350.1  506.53  5378.4  510.73  5385.4  508.37  5413.7  508.48  5574.2  513.57
#Mann=5,-1,0
  4431.1    0.05       0  4827.7    0.16       0  4992.9    0.07       0
  4999.5    0.16       0  5245.0    0.05       0
Bank Sta=4707.9,5098
Exp/Cntr=0.3,0.1

Type RM Length L Ch R = 1,3501,441,441,441
BEGIN DESCRIPTION:
Mapping XS 6263f101
END DESCRIPTION:
XS GIS Cut Line= 3
      2764311.19      7062974.69      2763686.24      7063099.68
      2763311.25      7063328.84
#Sta/Elev= 30
  4362.7  514.69  4489.0  509.01  4624.0  505.91  4698.1  505.11  4736.1  502.94
  4781.4  502.32  4901.0  499.59  4991.1  500.27  4998.1  495.20  5000.7  494.41
  5001.2  493.61  5006.8  493.61  5007.3  494.41  5013.2  498.46  5019.4  500.63
  5065.1  502.28  5086.1  502.32  5107.0  503.55  5135.6  502.43  5142.1  503.22
  5184.0  504.09  5282.6  505.18  5294.5  506.63  5303.9  506.34  5309.8  508.82
  5325.2  507.61  5331.1  506.20  5362.0  505.18  5420.0  507.31  5439.5  507.15
#Mann=6,-1,0
  4362.7    0.05       0  4901.0    0.16       0  5000.7    0.07       0
  5007.3    0.16       0  5065.1    0.05       0  5184.0    0.16       0
Bank Sta=4781.4,5086.1
Exp/Cntr=0.3,0.1

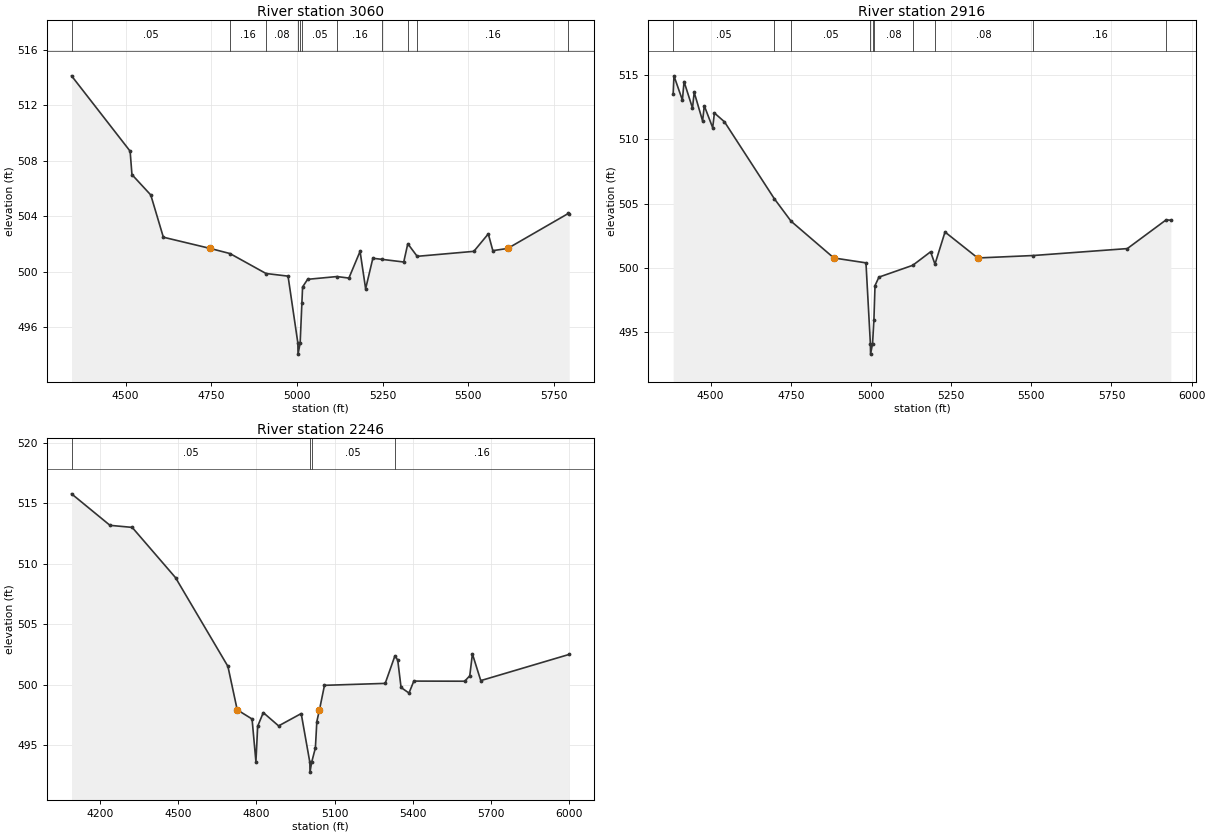
Type RM Length L Ch R = 1,3060,144,144,144
BEGIN DESCRIPTION:
Mapping XS ca8b0a14
END DESCRIPTION:
XS GIS Cut Line= 4
      2764285.19      7062922.60      2763670.61      7062688.23
      2763502.85      7062640.51      2763309.84      7063229.32
#Sta/Elev= 30
  4342.3  514.14  4513.2  508.70  4518.5  507.01  4573.4  505.54  4610.1  502.49
  4746.7  501.68  4804.5  501.31  4909.6  499.87  4973.9  499.68  5002.5  494.85
  5003.0  494.05  5009.2  494.85  5014.3  497.76  5016.3  498.90  5031.0  499.45
  5116.6  499.65  5151.4  499.54  5184.0  501.47  5200.2  498.77  5221.3  500.97
  5248.5  500.89  5311.4  500.70  5323.2  502.02  5350.6  501.11  5515.9  501.47
  5558.0  502.73  5571.3  501.52  5614.7  501.68  5791.9  504.21  5794.1  504.18
#Mann=11,-1,0
  4342.3    0.05       0  4804.5    0.16       0  4909.6    0.08       0
  5002.5    0.07       0  5009.2    0.08       0  5014.3    0.05       0
  5116.6    0.16       0  5248.5    0.05       0  5323.2    0.08       0
  5350.6    0.16       0  5791.9    0.12       0
Bank Sta=4746.7,5614.7
Exp/Cntr=0.3,0.1

Type RM Length L Ch R = 1,2916,670,670,670
BEGIN DESCRIPTION:
Mapping XS ca2be80b
END DESCRIPTION:
XS GIS Cut Line= 4
      2764253.91      7062740.30      2763665.41      7062542.39
      2763484.60      7062504.76      2763257.62      7063215.84
#Sta/Elev= 30
  4383.0  513.51  4385.5  514.94  4411.8  513.05  4417.0  514.49  4443.3  512.43
  4448.6  513.66  4474.8  511.43  4480.1  512.61  4506.3  510.90  4511.6  512.05
  4543.1  511.36  4698.2  505.39  4750.7  503.63  4884.2  500.77  4984.3  500.39
  4998.1  494.09  4998.6  493.29  5004.8  494.09  5009.1  495.96  5012.5  498.62
  5024.7  499.28  5130.2  500.20  5185.8  501.25  5199.5  500.29  5230.8  502.79
  5332.8  500.77  5505.3  500.96  5799.3  501.50  5920.1  503.73  5935.0  503.71
#Mann=10,-1,0
  4383.0    0.05       0  4698.2    0.08       0  4750.7    0.05       0
  4998.1    0.04       0  5004.8    0.05       0  5009.1    0.08       0
  5130.2    0.05       0  5199.5    0.08       0  5505.3    0.16       0
  5920.1    0.12       0
Bank Sta=4884.2,5332.8
Exp/Cntr=0.3,0.1

Type RM Length L Ch R = 1,2246,0,0,0
BEGIN DESCRIPTION:
Mapping XS 783747c7
END DESCRIPTION:
XS GIS Cut Line= 5
      2764321.70      7062162.19      2763670.61      7062099.68
      2763446.66      7062229.89      2763383.29      7062257.77
      2763235.23      7063171.28
#Sta/Elev= 30
  4091.7  515.80  4239.1  513.19  4324.2  513.02  4490.2  508.86  4691.1  501.51
  4726.8  497.91  4783.7  497.15  4798.5  493.62  4805.2  496.55  4826.7  497.68
  4885.5  496.58  4972.1  497.60  5005.3  493.55  5005.8  492.75  5012.0  493.55
  5026.5  494.76  5032.0  496.94  5042.1  497.91  5061.3  499.94  5294.1  500.10
  5331.5  502.39  5342.2  502.02  5354.9  499.76  5385.3  499.30  5403.8  500.29
  5598.9  500.28  5618.3  500.73  5628.4  502.54  5660.5  500.33  5999.5  502.50
#Mann=4,-1,0
  4091.7    0.05       0  5005.3    0.03       0  5012.0    0.05       0
  5331.5    0.16       0
Bank Sta=4726.8,5042.1
Exp/Cntr=0.3,0.1

Chan Stop Cuts=-1