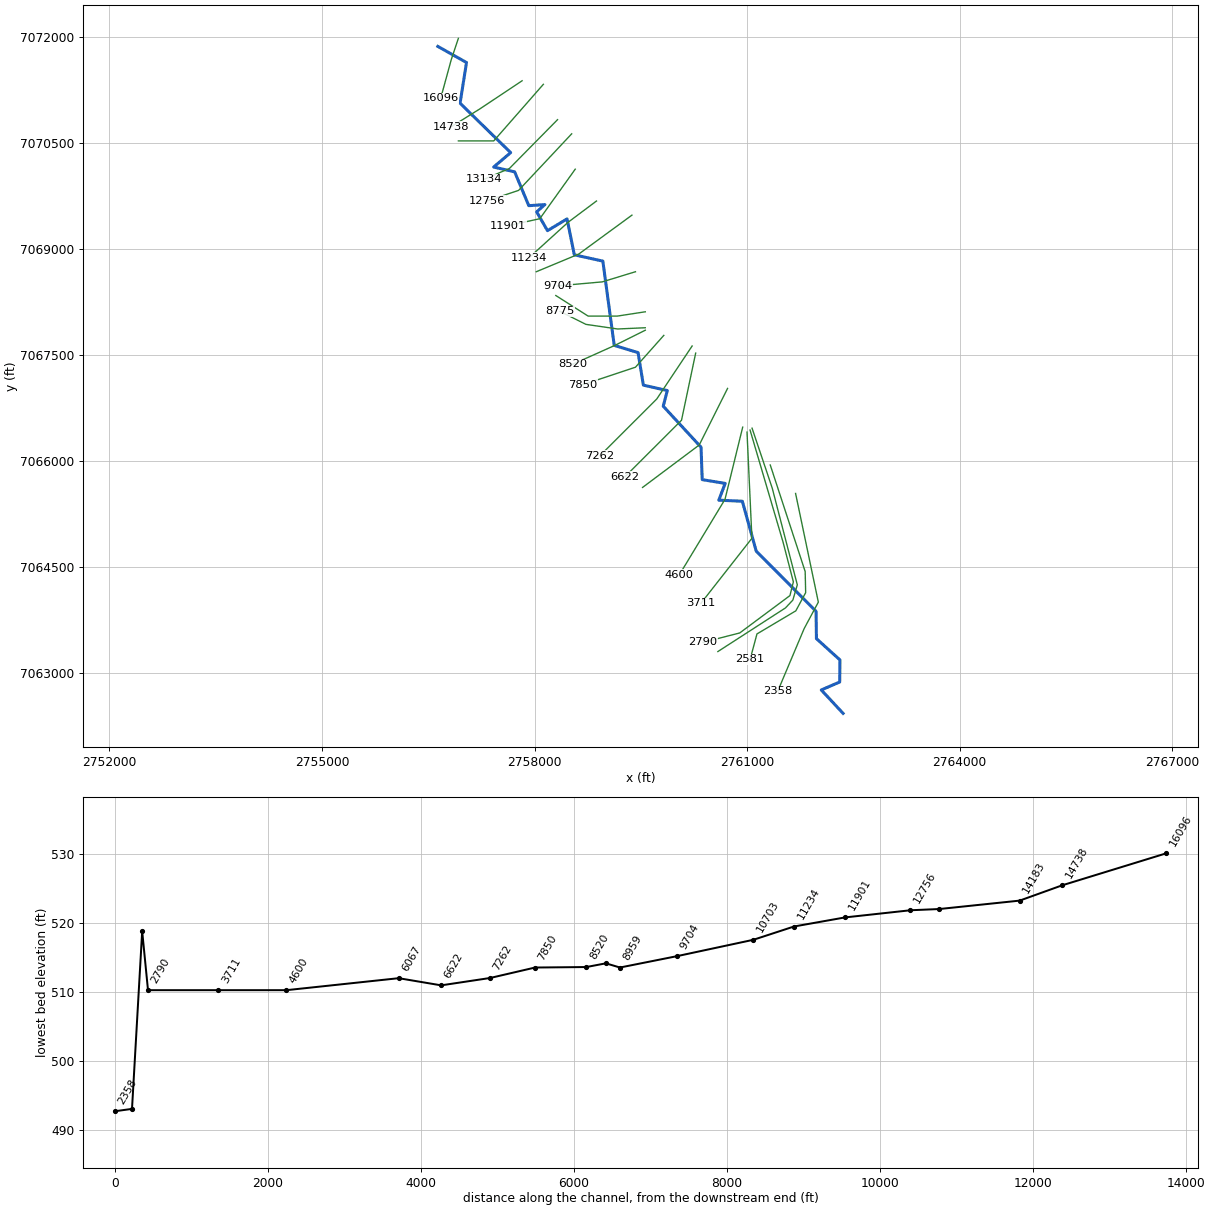
--- LAKE FORK CREEK TRIB 6.prj (project) ---

Proj Title=LAKE FORK CREEK TRIB 6 Base Level Engineering
Current Plan=p01
Default Exp/Contr=0.3,0.1
English Units
Geom File=g01
Flow File=f01
Plan File=p01
BEGIN DESCRIPTION:
LAKE FORK CREEK TRIB 6
END DESCRIPTION:

--- LAKE FORK CREEK TRIB 6.p01 (plan) ---

Plan Title=Multiple Run
Short Identifier=Multiple
Geom File=g01
Flow File=f01
Subcritical Flow
K Sum by GR= 0
Std Step Tol= 0.01
Critical Tol= 0.01
Num of Std Step Trials= 20
Max Error Tol= 0.3
Flow Tol Ratio= 0.001
Split Flow NTrial= 30
Split Flow Tol= 0.02
Split Flow Ratio= 0.02
Log Output Level= 0
Friction Slope Method= 1
Unsteady Friction Slope Method= 2
Unsteady Bridges Friction Slope Method= 1
Parabolic Critical Depth
Global Vel Dist=  1 , 1 , 1
Global Log Level= 0
CheckData=True
Encroach Param= -1, 0, 0, 0
BEGIN DESCRIPTION:
Multiple Run
END DESCRIPTION:

--- LAKE FORK CREEK TRIB 6.f01 (steady flow) ---

Flow Title=Multiple
Program Version=5.07
Number of Profiles= 7
Profile Names=10-year,25-year,50-year,1pct_min,100-year,1pct_plu,500-year
River Rch & RM=LAKE FORK CREEK,Reach-1         ,16096
     851    1145    1383     827    1650    3292    2344
River Rch & RM=LAKE FORK CREEK,Reach-1         ,8520
    1259    1726    2112    1277    2548    5084    3706
River Rch & RM=LAKE FORK CREEK,Reach-1         ,4600
    1473    2034    2500    1518    3030    6045    4444
Boundary for River Rch & Prof#=LAKE FORK CREEK,Reach-1         , 1
Up Type= 0
Dn Type= 3
Dn Slope=0.005
Boundary for River Rch & Prof#=LAKE FORK CREEK,Reach-1         , 2
Up Type= 0
Dn Type= 3
Dn Slope=0.005
Boundary for River Rch & Prof#=LAKE FORK CREEK,Reach-1         , 3
Up Type= 0
Dn Type= 3
Dn Slope=0.005
Boundary for River Rch & Prof#=LAKE FORK CREEK,Reach-1         , 4
Up Type= 0
Dn Type= 3
Dn Slope=0.005
Boundary for River Rch & Prof#=LAKE FORK CREEK,Reach-1         , 5
Up Type= 0
Dn Type= 3
Dn Slope=0.005
Boundary for River Rch & Prof#=LAKE FORK CREEK,Reach-1         , 6
Up Type= 0
Dn Type= 3
Dn Slope=0.005
Boundary for River Rch & Prof#=LAKE FORK CREEK,Reach-1         , 7
Up Type= 0
Dn Type= 3
Dn Slope=0.005
DSS Import GetInterval= 0
DSS Import GetPeak= 0
DSS Import FillOption= 0

--- LAKE FORK CREEK TRIB 6.g01 (geometry) ---

Geom Title=Existing Conditions

River Reach=LAKE FORK CREEK ,Reach-1
Reach XY= 30
      2756635.59      7071860.71      2757039.94      7071632.86
      2756949.28      7071057.92      2757663.12      7070358.92
      2757423.32      7070154.79      2757719.35      7070087.51
      2757919.56      7069608.94      2758146.91      7069624.42
      2758030.34      7069522.05      2758183.28      7069255.76
      2758459.42      7069422.00      2758562.02      7068913.98
      2758964.58      7068825.06      2759125.33      7067633.45
      2759461.58      7067531.69      2759536.79      7067071.56
      2759874.51      7066994.88      2759817.00      7066773.66
      2760350.86      7066194.08      2760367.08      7065735.43
      2760691.53      7065682.34      2760601.57      7065444.90
      2760933.39      7065430.15      2761129.54      7064725.21
      2761974.58      7063872.80      2761979.51      7063487.33
      2762311.47      7063186.01      2762308.20      7062874.27
      2762047.96      7062761.94      2762355.59      7062430.71

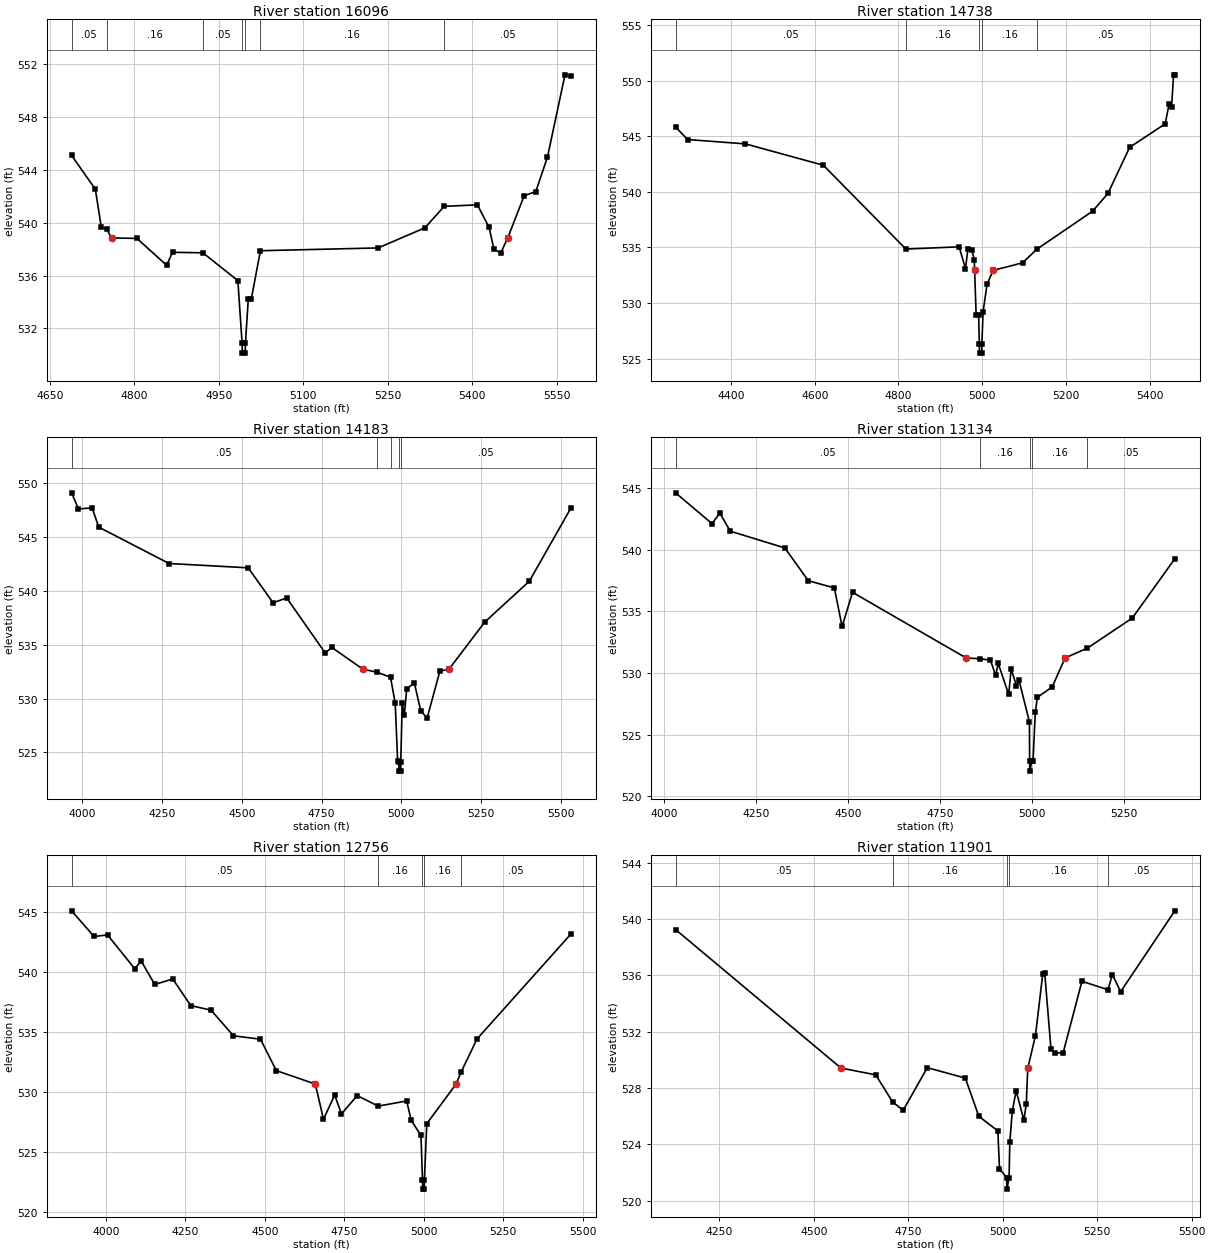
Type RM Length L Ch R = 1,16096,1358,1358,1358
BEGIN DESCRIPTION:
LAKE FORK CREEK TRIB 6 24.0
END DESCRIPTION:
XS GIS Cut Line= 3
      2756924.99      7071974.96      2756825.00      7071675.00
      2756674.99      7071124.98
#Sta/Elev= 30
  4688.8  545.09  4730.9  542.53  4741.5  539.65  4751.0  539.51  4759.8  538.85
  4804.7  538.81  4857.4  536.78  4868.0  537.76  4921.8  537.72  4983.9  535.62
  4991.4  530.93  4991.9  530.13  4996.9  530.13  4997.4  530.93  5002.4  534.19
  5007.6  534.19  5024.0  537.88  5233.0  538.09  5315.9  539.61  5350.3  541.24
  5409.2  541.35  5430.0  539.64  5438.6  537.98  5450.7  537.72  5463.1  538.85
  5492.2  542.04  5512.9  542.36  5533.6  544.97  5564.7  551.19  5575.1  551.10
#Mann=7,-1,0
  4688.8    0.05       0  4751.0    0.16       0  4921.8    0.05       0
  4991.4   0.035       0  4997.4    0.05       0  5024.0    0.16       0
  5350.3    0.05       0
Bank Sta=4759.8,5463.1
Exp/Cntr=0.3,0.1

Type RM Length L Ch R = 1,14738,555,555,555
BEGIN DESCRIPTION:
LAKE FORK CREEK TRIB 6 22.0
END DESCRIPTION:
XS GIS Cut Line= 3
      2757824.99      7071375.00      2757225.00      7070975.00
      2756825.00      7070725.00
#Sta/Elev= 30
  4267.5  545.83  4296.0  544.70  4434.3  544.31  4620.5  542.39  4817.8  534.85
  4945.0  535.05  4960.1  533.09  4966.1  534.90  4975.1  534.80  4981.1  533.91
  4982.0  532.93  4985.6  528.93  4991.6  528.93  4993.2  526.29  4993.7  525.49
  4998.8  525.49  4999.3  526.29  5002.2  529.21  5011.6  531.67  5026.0  532.93
  5096.5  533.61  5130.8  534.84  5264.0  538.26  5300.5  539.85  5352.4  544.00
  5437.3  546.11  5446.7  547.92  5452.6  547.67  5457.4  550.52  5460.3  550.52
#Mann=5,-1,0
  4267.5    0.05       0  4817.8    0.16       0  4993.2    0.07       0
  4999.3    0.16       0  5130.8    0.05       0
Bank Sta=4982,5026
Exp/Cntr=0.3,0.1

Type RM Length L Ch R = 1,14183,1049,1049,1049
BEGIN DESCRIPTION:
LAKE FORK CREEK TRIB 6 21.0
END DESCRIPTION:
XS GIS Cut Line= 3
      2758125.03      7071325.04      2757425.00      7070525.00
      2756924.96      7070525.00
#Sta/Elev= 30
  3967.5  549.06  3988.9  547.57  4031.6  547.66  4052.5  545.88  4272.7  542.51
  4520.4  542.11  4598.2  538.87  4640.9  539.32  4761.5  534.22  4782.4  534.73
  4879.2  532.72  4923.4  532.44  4966.0  531.97  4980.7  529.55  4988.3  524.20
  4991.9  524.07  4992.4  523.27  4997.5  523.27  4998.0  524.07  5002.6  529.61
  5009.2  528.44  5016.8  530.91  5040.6  531.43  5060.6  528.87  5080.6  528.19
  5120.6  532.54  5149.2  532.72  5260.6  537.07  5400.6  540.87  5530.6  547.64
#Mann=5,-1,0
  3967.5    0.05       0  4923.4    0.16       0  4966.0    0.05       0
  4991.9    0.03       0  4998.0    0.05       0
Bank Sta=4879.2,5149.2
Exp/Cntr=0.3,0.1

Type RM Length L Ch R = 1,13134,378,378,378
BEGIN DESCRIPTION:
LAKE FORK CREEK TRIB 6 20.0
END DESCRIPTION:
XS GIS Cut Line= 3
      2758325.02      7070825.02      2757645.87      7070134.97
      2757288.61      7069982.09
#Sta/Elev= 30
  4030.6  544.62  4129.6  542.12  4150.9  542.98  4179.1  541.51  4327.6  540.15
  4391.3  537.49  4462.0  536.91  4483.2  533.78  4511.5  536.55  4820.1  531.23
  4859.2  531.16  4886.3  531.05  4900.5  529.82  4907.5  530.78  4935.8  528.27
  4942.8  530.33  4956.9  528.98  4964.0  529.42  4992.3  526.03  4992.8  522.85
  4993.3  522.05  4998.9  522.85  5002.0  522.85  5008.3  526.85  5013.8  528.03
  5054.1  528.88  5089.3  531.23  5149.4  532.02  5271.7  534.46  5387.4  539.27
#Mann=5,-1,0
  4030.6    0.05       0  4859.2    0.16       0  4992.8    0.07       0
  4998.9    0.16       0  5149.4    0.05       0
Bank Sta=4820.1,5089.3
Exp/Cntr=0.3,0.1

Type RM Length L Ch R = 1,12756,855,855,855
BEGIN DESCRIPTION:
LAKE FORK CREEK TRIB 6 19.0
END DESCRIPTION:
XS GIS Cut Line= 3
      2758525.03      7070625.03      2757775.00      7069825.00
      2757324.97      7069674.99
#Sta/Elev= 30
  3891.9  545.07  3962.5  542.93  4005.0  543.06  4090.0  540.26  4111.3  540.86
  4153.5  538.93  4210.2  539.39  4266.8  537.17  4330.6  536.79  4401.2  534.65
  4486.2  534.37  4536.0  531.75  4658.8  530.63  4684.5  527.69  4719.6  529.72
  4741.1  528.14  4790.5  529.67  4856.8  528.79  4946.3  529.22  4960.4  527.61
  4991.2  526.35  4996.0  522.67  4996.5  521.87  5001.6  521.87  5002.1  522.67
  5009.6  527.33  5101.7  530.63  5118.3  531.67  5167.7  534.39  5462.9  543.13
#Mann=5,-1,0
  3891.9    0.05       0  4856.8    0.16       0  4996.0    0.07       0
  5002.1    0.16       0  5118.3    0.05       0
Bank Sta=4658.8,5101.7
Exp/Cntr=0.3,0.1

Type RM Length L Ch R = 1,11901,667,667,667
BEGIN DESCRIPTION:
LAKE FORK CREEK TRIB 6 18.0
END DESCRIPTION:
XS GIS Cut Line= 3
      2758575.00      7070125.00      2758075.00      7069425.00
      2757625.01      7069325.00
#Sta/Elev= 30
  4134.3  539.25  4572.1  529.42  4664.0  528.94  4708.6  527.02  4736.5  526.42
  4800.4  529.45  4901.1  528.71  4936.8  526.00  4987.2  524.96  4991.5  522.29
  5010.6  521.63  5011.1  520.83  5016.8  521.63  5018.9  524.20  5025.3  526.34
  5035.5  527.81  5056.0  525.73  5062.4  526.87  5066.3  529.41  5086.7  531.72
  5105.9  536.09  5111.1  536.19  5127.7  530.80  5137.9  530.51  5159.7  530.48
  5209.7  535.58  5278.5  534.98  5290.3  536.06  5312.1  534.84  5455.5  540.58
#Mann=5,-1,0
  4134.3    0.05       0  4708.6    0.16       0  5010.6    0.07       0
  5016.8    0.16       0  5278.5    0.05       0
Bank Sta=4572.1,5066.3
Exp/Cntr=0.3,0.1

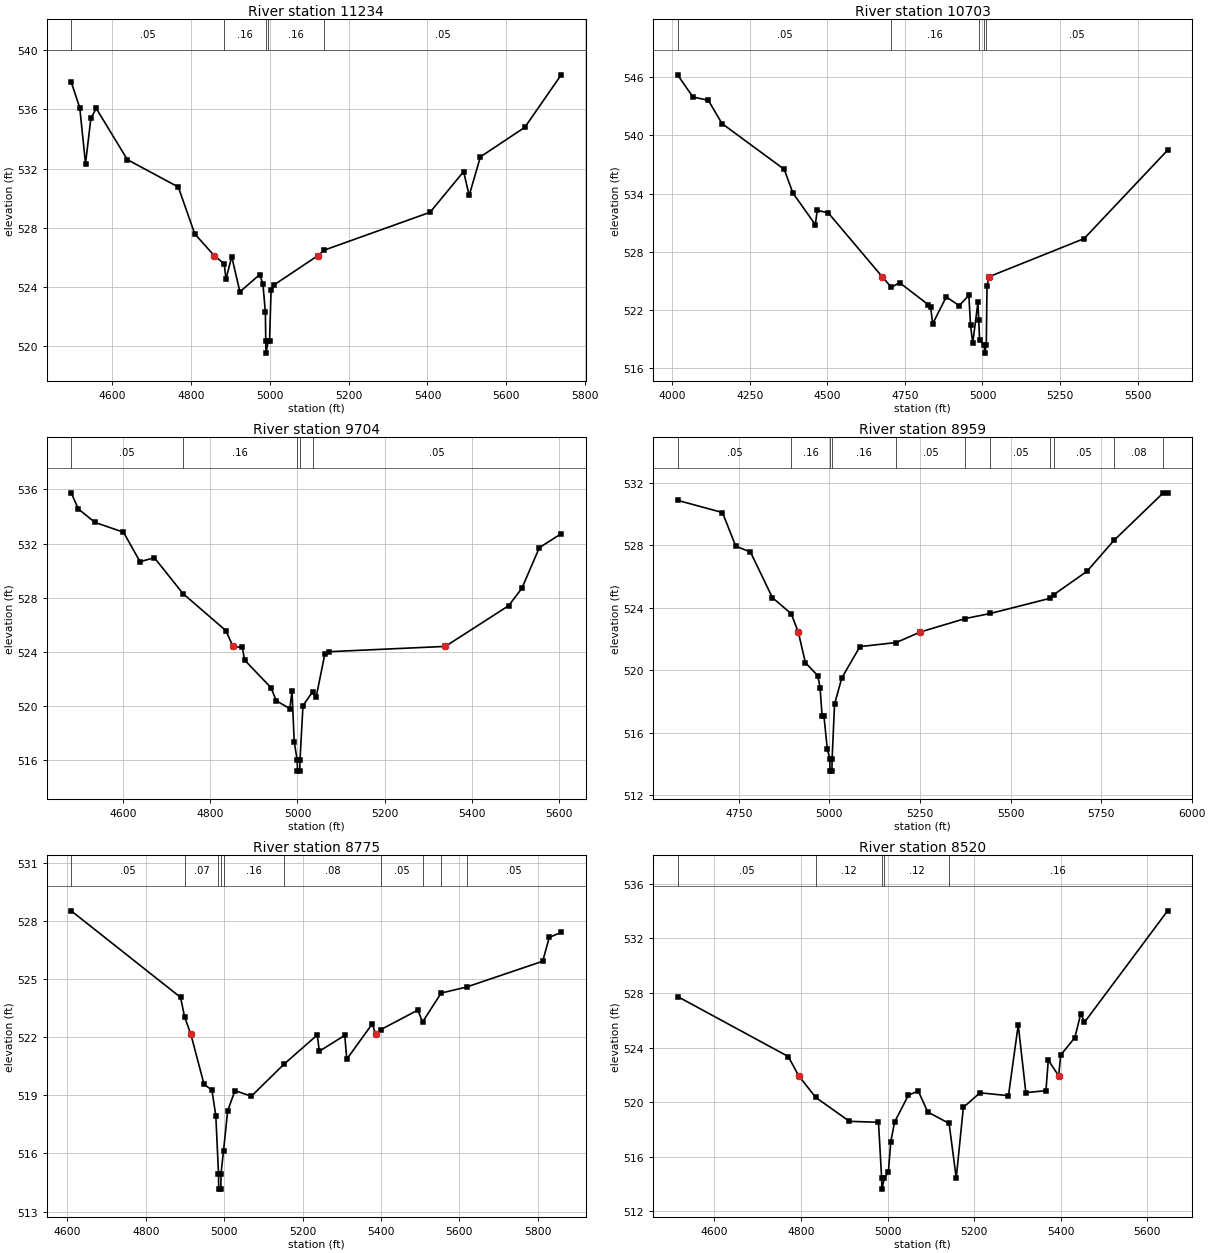
Type RM Length L Ch R = 1,11234,531,531,531
BEGIN DESCRIPTION:
LAKE FORK CREEK TRIB 6 17.0
END DESCRIPTION:
XS GIS Cut Line= 3
      2758874.98      7069674.98      2758475.00      7069375.00
      2757924.98      7068874.98
#Sta/Elev= 30
  4496.1  537.86  4517.9  536.11  4532.5  532.33  4546.1  535.39  4559.6  536.07
  4638.8  532.60  4767.9  530.75  4809.6  527.58  4859.5  526.09  4884.4  525.56
  4888.8  524.51  4903.4  526.04  4924.2  523.66  4974.2  524.82  4982.5  524.22
  4988.8  522.27  4989.8  520.31  4990.3  519.51  4996.1  520.31  4999.4  520.31
  5003.2  523.75  5009.9  524.11  5121.2  526.09  5138.4  526.48  5406.6  529.04
  5491.7  531.79  5505.9  530.18  5534.3  532.79  5647.1  534.79  5739.4  538.34
#Mann=5,-1,0
  4496.1    0.05       0  4884.4    0.16       0  4989.8    0.07       0
  4996.1    0.16       0  5138.4    0.05       0
Bank Sta=4859.5,5121.2
Exp/Cntr=0.3,0.1

Type RM Length L Ch R = 1,10703,999,999,999
BEGIN DESCRIPTION:
LAKE FORK CREEK TRIB 6 16.0
END DESCRIPTION:
XS GIS Cut Line= 3
      2759375.02      7069475.01      2758625.00      7068925.00
      2758024.97      7068674.99
#Sta/Elev= 30
  4016.9  546.21  4066.5  543.93  4116.1  543.59  4160.1  541.20  4360.8  536.49
  4388.9  534.04  4461.1  530.80  4467.3  532.27  4502.8  532.01  4676.7  525.44
  4706.5  524.35  4732.8  524.83  4824.7  522.58  4833.1  522.32  4839.3  520.59
  4883.3  523.36  4925.0  522.47  4956.2  523.52  4961.6  520.44  4968.6  518.60
  4985.4  522.79  4988.0  520.94  4990.8  518.94  5006.1  518.38  5006.6  517.58
  5012.4  518.38  5014.7  524.53  5021.3  525.44  5327.8  529.36  5597.0  538.46
#Mann=5,-1,0
  4016.9    0.05       0  4706.5    0.16       0  4988.0    0.05       0
  5006.1    0.03       0  5012.4    0.05       0
Bank Sta=4676.7,5021.3
Exp/Cntr=0.3,0.1

Type RM Length L Ch R = 1,9704,745,745,745
BEGIN DESCRIPTION:
LAKE FORK CREEK TRIB 6 15.0
END DESCRIPTION:
XS GIS Cut Line= 3
      2759425.05      7068675.01      2758955.90      7068531.41
      2758325.05      7068475.00
#Sta/Elev= 30
  4481.0  535.75  4497.4  534.56  4535.4  533.57  4601.0  532.84  4639.0  530.66
  4671.7  530.96  4737.5  528.31  4835.6  525.58  4852.2  524.41  4873.6  524.33
  4878.8  523.40  4939.1  521.37  4951.7  520.39  4982.5  519.82  4987.5  521.11
  4992.6  517.35  4999.5  516.00  5000.0  515.20  5005.3  515.20  5005.8  516.00
  5012.7  520.04  5035.0  521.07  5042.8  520.65  5062.9  523.86  5072.9  524.02
  5339.2  524.41  5484.6  527.42  5514.7  528.70  5554.8  531.70  5605.0  532.73
#Mann=5,-1,0
  4481.0    0.05       0  4737.5    0.16       0  4999.5    0.07       0
  5005.8    0.16       0  5035.0    0.05       0
Bank Sta=4852.2,5339.2
Exp/Cntr=0.3,0.1

Type RM Length L Ch R = 1,8959,184,184,184
BEGIN DESCRIPTION:
LAKE FORK CREEK TRIB 6 14.0
END DESCRIPTION:
XS GIS Cut Line= 4
      2759563.77      7068108.68      2759168.79      7068047.92
      2758756.46      7068047.92      2758300.69      7068338.74
#Sta/Elev= 30
  4581.0  530.86  4705.0  530.08  4741.6  527.93  4782.1  527.56  4842.8  524.64
  4894.8  523.61  4914.2  522.44  4933.9  520.48  4968.1  519.65  4974.3  518.89
  4980.0  517.07  4985.0  517.07  4994.4  514.95  5001.2  514.35  5001.7  513.55
  5007.1  513.55  5007.6  514.35  5014.4  517.84  5034.4  519.51  5084.4  521.51
  5184.6  521.77  5250.6  522.44  5374.6  523.30  5444.7  523.63  5609.5  524.60
  5620.0  524.84  5710.9  526.32  5786.0  528.31  5921.7  531.34  5933.6  531.32
#Mann=11,-1,0
  4581.0    0.05       0  4894.8    0.16       0  5001.2    0.07       0
  5007.6    0.16       0  5184.6    0.05       0  5374.6    0.08       0
  5444.7    0.05       0  5609.5    0.08       0  5620.0    0.05       0
  5786.0    0.08       0  5921.7    0.05       0
Bank Sta=4914.2,5250.6
Exp/Cntr=0.3,0.1

Type RM Length L Ch R = 1,8775,255,255,255
BEGIN DESCRIPTION:
LAKE FORK CREEK TRIB 6 13.0
END DESCRIPTION:
XS GIS Cut Line= 4
      2759563.73      7067882.98      2759173.13      7067865.62
      2758726.08      7067930.73      2758361.47      7068113.03
#Sta/Elev= 30
  4609.5  528.51  4888.5  524.05  4899.2  523.02  4914.8  522.15  4948.6  519.56
  4968.6  519.27  4978.6  517.94  4985.4  514.96  4985.9  514.16  4991.3  514.16
  4991.8  514.96  4998.2  516.12  5008.7  518.19  5027.4  519.24  5069.3  518.95
  5151.9  520.59  5237.5  522.11  5242.6  521.27  5307.6  522.09  5312.7  520.86
  5377.7  522.68  5386.3  522.15  5400.0  522.39  5494.0  523.39  5506.1  522.78
  5553.6  524.27  5618.2  524.58  5812.6  525.91  5829.4  527.14  5859.9  527.40
#Mann=10,-1,0
  4609.5    0.05       0  4899.2    0.07       0  4985.4    0.07       0
  4991.8    0.07       0  4998.2    0.16       0  5151.9    0.08       0
  5400.0    0.05       0  5506.1    0.16       0  5553.6    0.08       0
  5618.2    0.05       0
Bank Sta=4914.8,5386.3
Exp/Cntr=0.3,0.1

Type RM Length L Ch R = 1,8520,670,670,670
BEGIN DESCRIPTION:
double Mapping XS eea633d4
END DESCRIPTION:
XS GIS Cut Line= 3
      2759563.74      7067848.26      2759138.41      7067635.59
      2758539.69      7067366.60
#Sta/Elev= 30
  4515.0  527.74  4770.7  523.34  4794.8  521.93  4834.2  520.34  4912.0  518.59
  4979.1  518.52  4986.4  514.42  4986.9  513.62  4992.8  514.42  5002.0  514.88
  5007.4  517.07  5016.2  518.53  5048.3  520.51  5071.0  520.81  5092.9  519.27
  5142.2  518.44  5158.7  514.43  5175.1  519.61  5213.5  520.68  5279.3  520.47
  5301.9  525.66  5319.5  520.69  5365.9  520.84  5371.3  523.08  5395.3  521.93
  5400.0  523.45  5432.8  524.73  5446.3  526.49  5454.7  525.84  5646.9  534.02
#Mann=5,-1,0
  4515.0    0.05       0  4834.2    0.12       0  4986.4    0.07       0
  4992.8    0.12       0  5142.2    0.16       0
Bank Sta=4794.8,5395.3
Exp/Cntr=0.3,0.1

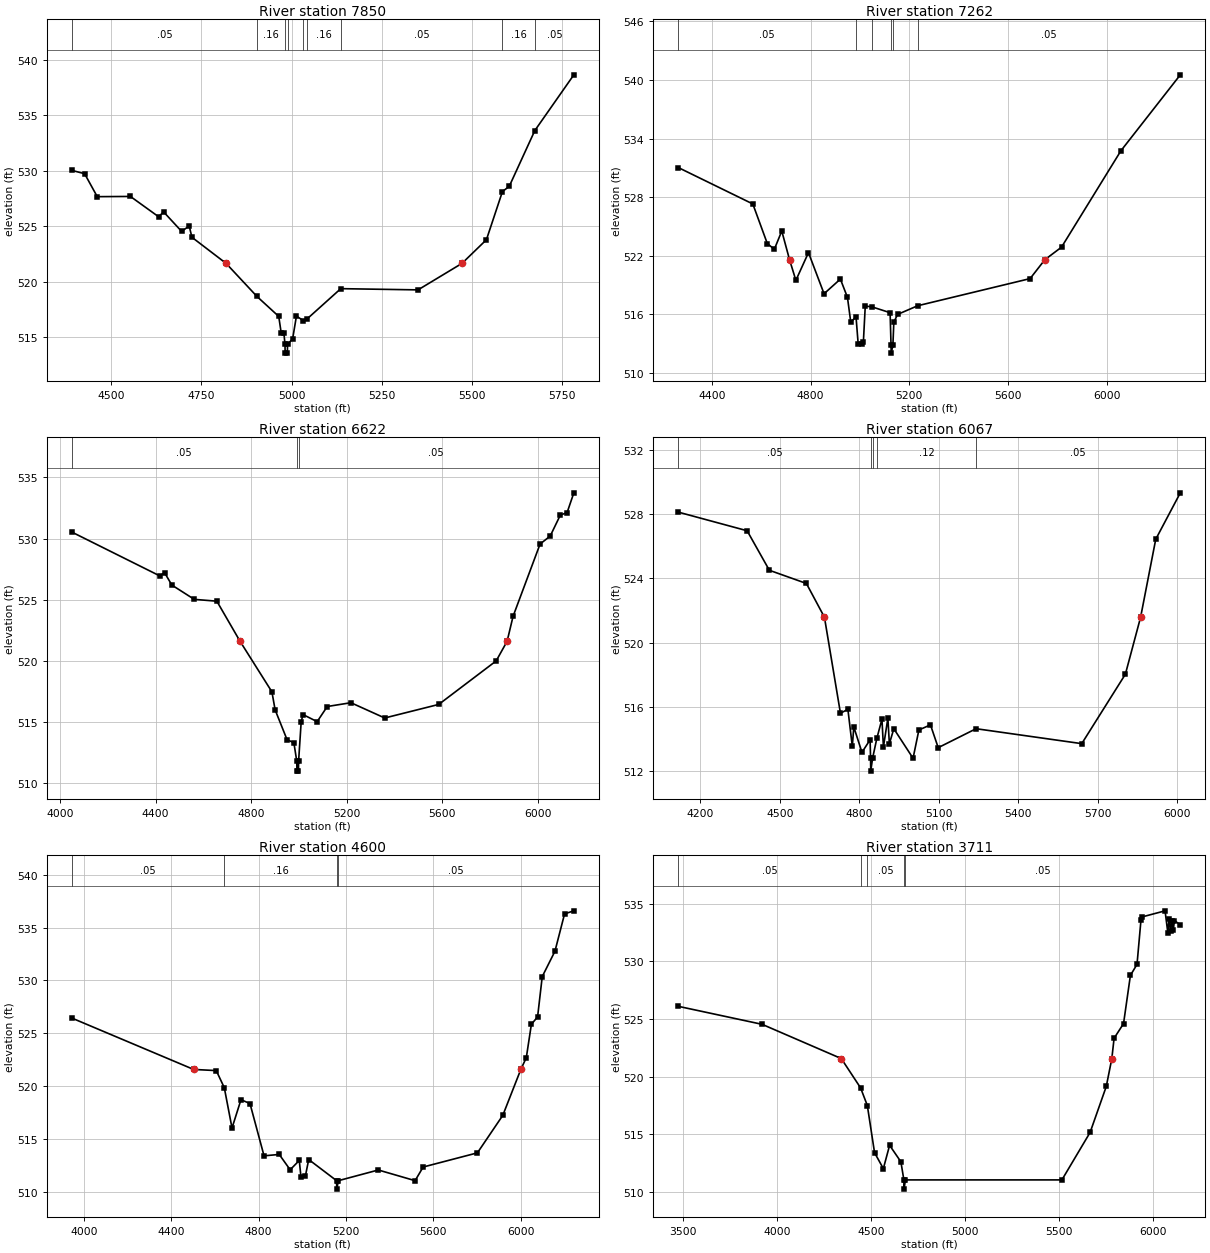
Type RM Length L Ch R = 1,7850,588,588,588
BEGIN DESCRIPTION:
LAKE FORK CREEK TRIB 6 12.0
END DESCRIPTION:
XS GIS Cut Line= 3
      2759825.02      7067775.02      2759425.00      7067325.00
      2758674.97      7067074.99
#Sta/Elev= 30
  4390.3  530.02  4425.9  529.72  4461.0  527.65  4553.0  527.67  4631.2  525.84
  4645.0  526.28  4695.1  524.52  4716.0  525.01  4723.6  523.99  4818.3  521.64
  4903.9  518.66  4964.4  516.86  4971.1  515.40  4978.6  515.40  4981.7  514.35
  4982.2  513.55  4988.3  513.55  4988.9  514.35  5002.9  514.83  5013.5  516.89
  5032.9  516.47  5043.3  516.64  5136.5  519.36  5350.8  519.25  5472.8  521.64
  5540.5  523.77  5584.9  528.11  5603.8  528.58  5674.8  533.61  5783.0  538.63
#Mann=9,-1,0
  4390.3    0.05       0  4903.9    0.16       0  4981.7    0.07       0
  4988.9    0.16       0  5032.9    0.12       0  5043.3    0.16       0
  5136.5    0.05       0  5584.9    0.16       0  5674.8    0.05       0
Bank Sta=4818.3,5472.8
Exp/Cntr=0.3,0.1

Type RM Length L Ch R = 1,7262,640,640,640
BEGIN DESCRIPTION:
LAKE FORK CREEK TRIB 6 11.0
END DESCRIPTION:
XS GIS Cut Line= 3
      2760225.01      7067625.02      2759725.00      7066875.00
      2758924.99      7066074.99
#Sta/Elev= 30
  4264.3  531.03  4566.3  527.30  4624.9  523.25  4653.4  522.66  4683.5  524.53
  4715.0  521.59  4740.6  519.48  4791.6  522.32  4854.7  518.11  4920.8  519.61
  4949.4  517.74  4962.9  515.19  4984.1  515.76  4992.9  512.95  5008.0  512.98
  5014.0  513.22  5021.5  516.84  5046.9  516.78  5122.1  516.17  5125.9  512.83
  5126.5  512.03  5133.4  512.83  5137.2  515.19  5152.2  515.99  5233.7  516.88
  5689.0  519.66  5748.5  521.59  5816.2  522.88  6056.7  532.75  6297.1  540.52
#Mann=6,-1,0
  4264.3    0.05       0  4984.1    0.16       0  5046.9    0.12       0
  5125.9    0.07       0  5133.4    0.12       0  5233.7    0.05       0
Bank Sta=4715,5748.5
Exp/Cntr=0.3,0.1

Type RM Length L Ch R = 1,6622,555,555,555
BEGIN DESCRIPTION:
LAKE FORK CREEK TRIB 6 10.0
END DESCRIPTION:
XS GIS Cut Line= 3
      2760275.00      7067525.02      2760075.00      7066575.00
      2759275.01      7065775.01
#Sta/Elev= 30
  4048.9  530.53  4417.5  526.94  4437.3  527.21  4467.9  526.19  4561.8  525.02
  4656.3  524.87  4753.4  521.59  4886.9  517.45  4900.3  515.98  4950.1  513.54
  4978.9  513.28  4991.1  511.76  4991.6  510.96  4998.0  510.96  4998.6  511.76
  5009.5  515.01  5017.2  515.59  5076.3  515.01  5118.7  516.25  5217.7  516.56
  5359.2  515.31  5585.4  516.42  5825.8  519.98  5871.7  521.59  5896.6  523.63
  6009.7  529.55  6052.1  530.20  6094.5  531.92  6122.8  532.12  6151.1  533.74
#Mann=3,-1,0
  4048.9    0.05       0  4991.1    0.03       0  4998.6    0.05       0
Bank Sta=4753.4,5871.7
Exp/Cntr=0.3,0.1

Type RM Length L Ch R = 1,6067,1467,1467,1467
BEGIN DESCRIPTION:
LAKE FORK CREEK TRIB 6 9.0
END DESCRIPTION:
XS GIS Cut Line= 3
      2760725.00      7067025.00      2760325.00      7066225.00
      2759525.02      7065625.01
#Sta/Elev= 30
  4117.2  528.12  4377.1  526.96  4461.0  524.50  4600.7  523.68  4668.8  521.58
  4729.3  515.60  4757.3  515.85  4774.0  513.54  4779.6  514.75  4810.4  513.17
  4841.1  513.95  4842.9  512.80  4843.5  512.00  4850.5  512.80  4866.6  514.04
  4885.8  515.23  4891.4  513.50  4908.2  515.30  4913.8  513.70  4930.6  514.64
  5003.2  512.80  5025.2  514.56  5068.9  514.88  5098.1  513.46  5241.0  514.64
  5639.7  513.71  5804.3  518.03  5861.8  521.58  5918.9  526.43  6011.6  529.32
#Mann=5,-1,0
  4117.2    0.05       0  4842.9    0.07       0  4850.5    0.05       0
  4866.6    0.12       0  5241.0    0.05       0
Bank Sta=4668.8,5861.8
Exp/Cntr=0.3,0.1

Type RM Length L Ch R = 1,4600,889,889,889
BEGIN DESCRIPTION:
Mapping XS 27554ad1
END DESCRIPTION:
XS GIS Cut Line= 3
      2760938.75      7066477.59      2760688.75      7065456.77
      2760043.70      7064388.62
#Sta/Elev= 30
  3944.5  526.44  4502.4  521.58  4606.1  521.47  4642.9  519.85  4678.2  516.04
  4719.3  518.72  4760.5  518.35  4824.8  513.41  4894.4  513.54  4944.4  512.09
  4986.1  512.97  4993.8  511.45  5013.8  511.46  5029.3  513.06  5157.0  511.06
  5157.7  510.26  5165.2  511.06  5348.0  512.07  5516.4  511.06  5553.3  512.35
  5801.7  513.69  5918.1  517.24  6000.5  521.58  6025.6  522.69  6048.9  525.85
  6077.3  526.55  6098.6  530.36  6156.8  532.76  6200.8  536.29  6243.3  536.58
#Mann=4,-1,0
  3944.5    0.05       0  4642.9    0.16       0  5157.0    0.07       0
  5165.2    0.05       0
Bank Sta=4502.4,6000.5
Exp/Cntr=0.3,0.1

Type RM Length L Ch R = 1,3711,921,921,921
BEGIN DESCRIPTION:
Mapping XS 68f99be4
END DESCRIPTION:
XS GIS Cut Line= 3
      2760999.52      7066408.15      2761068.96      7064906.42
      2760349.21      7063987.22
#Sta/Elev= 30
  3474.3  526.11  3920.3  524.55  4341.7  521.58  4444.3  519.04  4480.2  517.51
  4518.6  513.42  4565.4  512.04  4598.7  514.06  4658.7  512.63  4674.6  511.06
  4675.3  510.26  4682.8  511.06  5515.2  511.06  5665.3  515.18  5751.2  519.16
  5780.8  521.58  5792.8  523.34  5843.1  524.61  5879.6  528.79  5914.8  529.75
  5935.7  533.57  5943.8  533.87  6064.0  534.39  6078.5  532.51  6084.9  533.64
  6093.0  532.62  6099.3  533.55  6107.4  532.69  6113.8  533.55  6145.1  533.17
#Mann=5,-1,0
  3474.3    0.05       0  4444.3    0.16       0  4480.2    0.05       0
  4674.6   0.033       0  4682.8    0.05       0
Bank Sta=4341.7,5780.8
Exp/Cntr=0.3,0.1

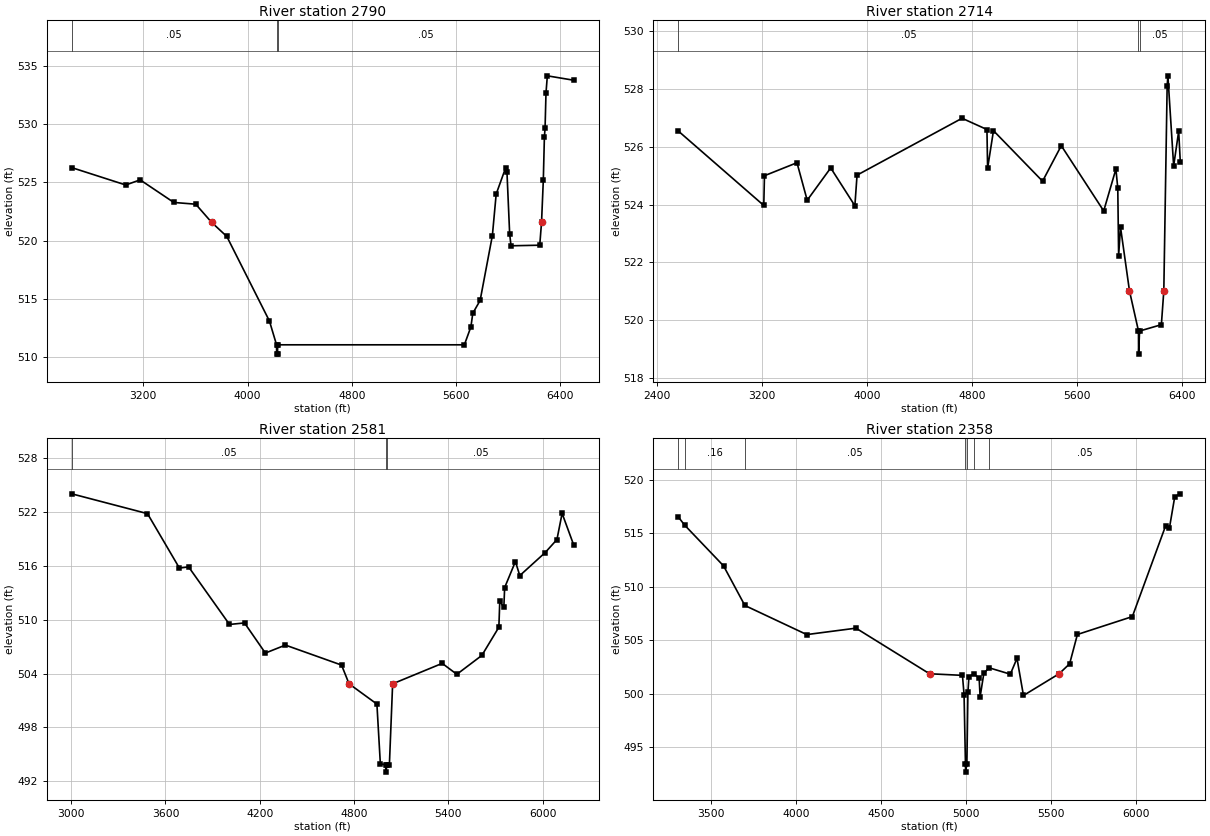
Type RM Length L Ch R = 1,2790,76,76,76
BEGIN DESCRIPTION:
Mapping XS e5235aee
END DESCRIPTION:
XS GIS Cut Line= 6
      2761042.92      7066435.95      2761508.20      7064852.60
      2761654.03      7064290.10      2761605.42      7064095.66
      2760897.09      7063567.88      2760378.11      7063434.60
#Sta/Elev= 30
  2651.5  526.27  3065.5  524.78  3176.0  525.22  3434.2  523.28  3602.5  523.13
  3723.4  521.58  3840.7  520.36  4167.7  513.10  4222.2  511.06  4222.9  510.26
  4229.8  510.26  4230.5  511.06  5662.8  511.06  5712.9  512.60  5727.5  513.77
  5783.7  514.87  5877.6  520.44  5906.8  524.00  5979.2  526.25  5989.5  525.88
  6010.1  520.60  6020.5  519.56  6241.0  519.61  6254.7  521.58  6268.3  525.18
  6276.6  528.88  6281.8  529.68  6288.9  532.69  6299.2  534.15  6502.5  533.77
#Mann=3,-1,0
  2651.5    0.05       0  4222.2    0.03       0  4230.5    0.05       0
Bank Sta=3723.4,6254.7
Exp/Cntr=0.3,0.1

Type RM Length L Ch R = 1,2714,133,133,133
BEGIN DESCRIPTION:
Mapping XS e9aebac4
END DESCRIPTION:
XS GIS Cut Line= 6
      2761070.71      7066463.67      2761355.42      7065616.49
      2761709.59      7064248.44      2761647.09      7064033.16
      2761542.92      7063922.05      2760588.30      7063304.56
#Sta/Elev= 30
  2562.0  526.55  3214.2  523.97  3219.5  525.00  3467.4  525.45  3545.3  524.15
  3724.5  525.27  3908.8  523.96  3925.4  525.02  4726.1  526.99  4915.8  526.60
  4920.9  525.26  4965.6  526.56  5339.9  524.81  5482.6  526.04  5806.1  523.78
  5899.1  525.23  5913.4  524.57  5919.9  522.23  5934.2  523.22  6002.6  521.01
  6071.3  519.62  6072.0  518.82  6079.6  519.62  6245.8  519.84  6264.4  521.01
  6289.8  528.10  6295.4  528.46  6339.4  525.34  6377.8  526.54  6390.2  525.47
#Mann=3,-1,0
  2562.0    0.05       0  6071.3    0.03       0  6079.6    0.05       0
Bank Sta=6002.6,6264.4
Exp/Cntr=0.3,0.1

Type RM Length L Ch R = 1,2581,223,223,223
BEGIN DESCRIPTION:
Mapping XS d3fb9547
END DESCRIPTION:
XS GIS Cut Line= 6
      2761327.64      7065942.89      2761820.70      7064435.94
      2761827.64      7064137.33      2761688.75      7063880.38
      2761140.14      7063553.99      2761042.91      7063192.85
#Sta/Elev= 30
  3004.1  524.05  3485.9  521.84  3689.0  515.77  3747.5  515.90  4007.6  509.48
  4103.2  509.65  4235.9  506.29  4363.4  507.18  4720.6  504.95  4768.5  502.86
  4945.6  500.60  4967.5  493.95  5001.6  493.81  5002.3  493.01  5009.9  493.81
  5025.1  493.86  5045.7  502.86  5361.1  505.14  5454.2  503.92  5613.5  506.03
  5721.6  509.17  5727.4  512.07  5753.3  511.39  5758.4  513.59  5827.0  516.50
  5854.7  514.93  6016.4  517.50  6091.1  518.95  6124.0  521.87  6198.7  518.30
#Mann=3,-1,0
  3004.1    0.05       0  5001.6    0.03       0  5009.9    0.05       0
Bank Sta=4768.5,5045.7
Exp/Cntr=0.3,0.1

Type RM Length L Ch R = 1,2358,0,0,0
BEGIN DESCRIPTION:
Mapping XS c7b1ecac
END DESCRIPTION:
XS GIS Cut Line= 4
      2761685.27      7065540.14      2762006.46      7064003.65
      2761806.81      7063630.38      2761433.54      7062744.96
#Sta/Elev= 30
  3306.8  516.52  3344.2  515.75  3573.4  511.94  3698.7  508.24  4063.0  505.52
  4352.6  506.12  4785.2  501.86  4978.9  501.71  4988.4  499.92  4996.6  493.47
  4997.4  492.67  5005.0  493.47  5011.1  500.14  5017.1  501.57  5045.9  501.87
  5077.2  501.44  5082.9  499.71  5104.8  501.90  5135.3  502.42  5260.6  501.82
  5299.8  503.30  5337.9  499.83  5547.6  501.86  5609.5  502.79  5655.2  505.53
  5978.5  507.20  6173.8  515.66  6196.8  515.49  6228.1  518.41  6260.7  518.67
#Mann=7,-1,0
  3306.8    0.05       0  3344.2    0.16       0  3698.7    0.05       0
  4996.6    0.03       0  5005.0    0.05       0  5045.9    0.16       0
  5135.3    0.05       0
Bank Sta=4785.2,5547.6
Exp/Cntr=0.3,0.1

Chan Stop Cuts=-1