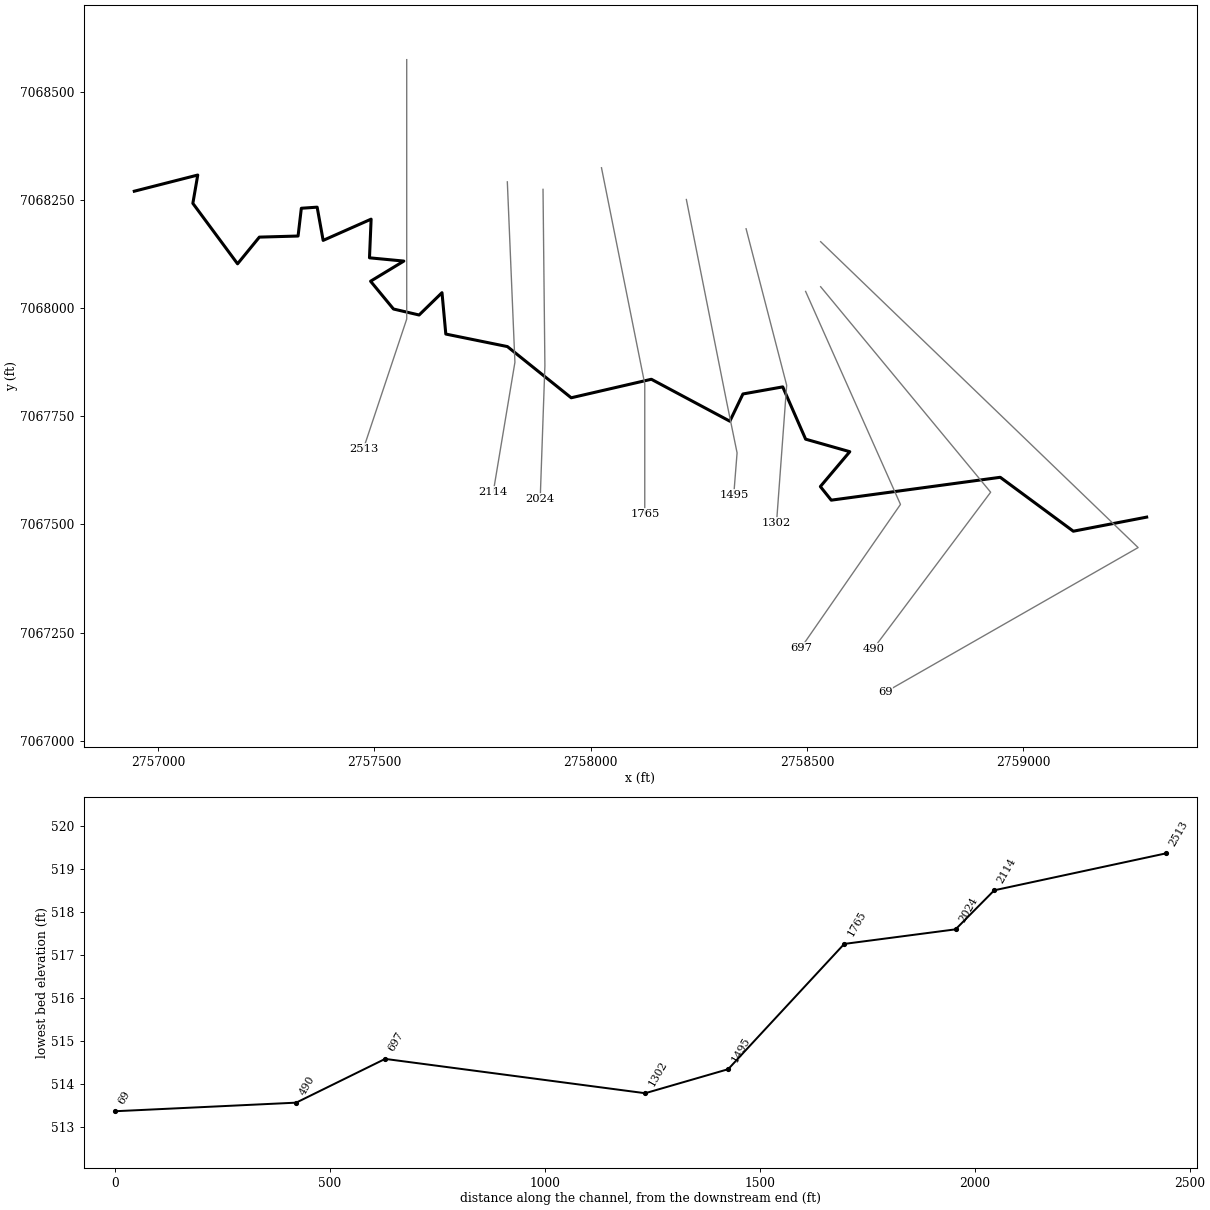
--- LAKE FORK CREEK TRIB 6_2.prj (project) ---

Proj Title=LAKE FORK CREEK TRIB 6_2 Base Level Engineering
Current Plan=p01
Default Exp/Contr=0.3,0.1
English Units
Geom File=g01
Flow File=f01
Plan File=p01
BEGIN DESCRIPTION:
LAKE FORK CREEK TRIB 6_2
END DESCRIPTION:

--- LAKE FORK CREEK TRIB 6_2.p01 (plan) ---

Plan Title=Multiple Run
Short Identifier=Multiple
Geom File=g01
Flow File=f01
Subcritical Flow
K Sum by GR= 0
Std Step Tol= 0.01
Critical Tol= 0.01
Num of Std Step Trials= 20
Max Error Tol= 0.3
Flow Tol Ratio= 0.001
Split Flow NTrial= 30
Split Flow Tol= 0.02
Split Flow Ratio= 0.02
Log Output Level= 0
Friction Slope Method= 1
Unsteady Friction Slope Method= 2
Unsteady Bridges Friction Slope Method= 1
Parabolic Critical Depth
Global Vel Dist=  1 , 1 , 1
Global Log Level= 0
CheckData=True
Encroach Param= -1, 0, 0, 0
BEGIN DESCRIPTION:
Multiple Run
END DESCRIPTION:

--- LAKE FORK CREEK TRIB 6_2.f01 (steady flow) ---

Flow Title=Multiple
Number of Profiles=7
Profile Names=10-year,25-year,50-year,1pct_min,100-year,1pct_plu,500-year
River Rch & RM= LAKE FORK CREEK ,Reach-1,2513
     606     805     966     575    1146    2287    1612
Boundary for River Rch & Prof#=LAKE FORK CREEK ,Reach-1,1
Up Type=0
Dn Type=3
Dn Slope=0.005
Boundary for River Rch & Prof#=LAKE FORK CREEK ,Reach-1,2
Up Type=0
Dn Type=3
Dn Slope=0.005
Boundary for River Rch & Prof#=LAKE FORK CREEK ,Reach-1,3
Up Type=0
Dn Type=3
Dn Slope=0.005
Boundary for River Rch & Prof#=LAKE FORK CREEK ,Reach-1,4
Up Type=0
Dn Type=3
Dn Slope=0.005
Boundary for River Rch & Prof#=LAKE FORK CREEK ,Reach-1,5
Up Type=0
Dn Type=3
Dn Slope=0.005
Boundary for River Rch & Prof#=LAKE FORK CREEK ,Reach-1,6
Up Type=0
Dn Type=3
Dn Slope=0.005
Boundary for River Rch & Prof#=LAKE FORK CREEK ,Reach-1,7
Up Type=0
Dn Type=3
Dn Slope=0.005

--- LAKE FORK CREEK TRIB 6_2.g01 (geometry) ---

Geom Title=Existing Conditions

River Reach=LAKE FORK CREEK ,Reach-1
Reach XY= 30
      2756945.59      7068270.71      2757092.23      7068308.12
      2757080.90      7068242.63      2757184.18      7068102.81
      2757234.57      7068164.53      2757324.00      7068167.05
      2757331.55      7068231.29      2757368.08      7068233.81
      2757381.94      7068156.97      2757492.78      7068206.10
      2757489.00      7068116.67      2757568.36      7068109.11
      2757491.52      7068062.51      2757544.42      7067998.27
      2757603.63      7067984.41      2757656.53      7068036.05
      2757665.34      7067940.33      2757807.68      7067911.36
      2757955.05      7067792.95      2758140.21      7067835.78
      2758321.59      7067738.79      2758351.82      7067801.77
      2758443.77      7067818.15      2758496.67      7067697.23
      2758598.70      7067668.26      2758530.68      7067587.64
      2758555.87      7067556.15      2758946.34      7067609.05
      2759115.13      7067484.36      2759284.61      7067516.94

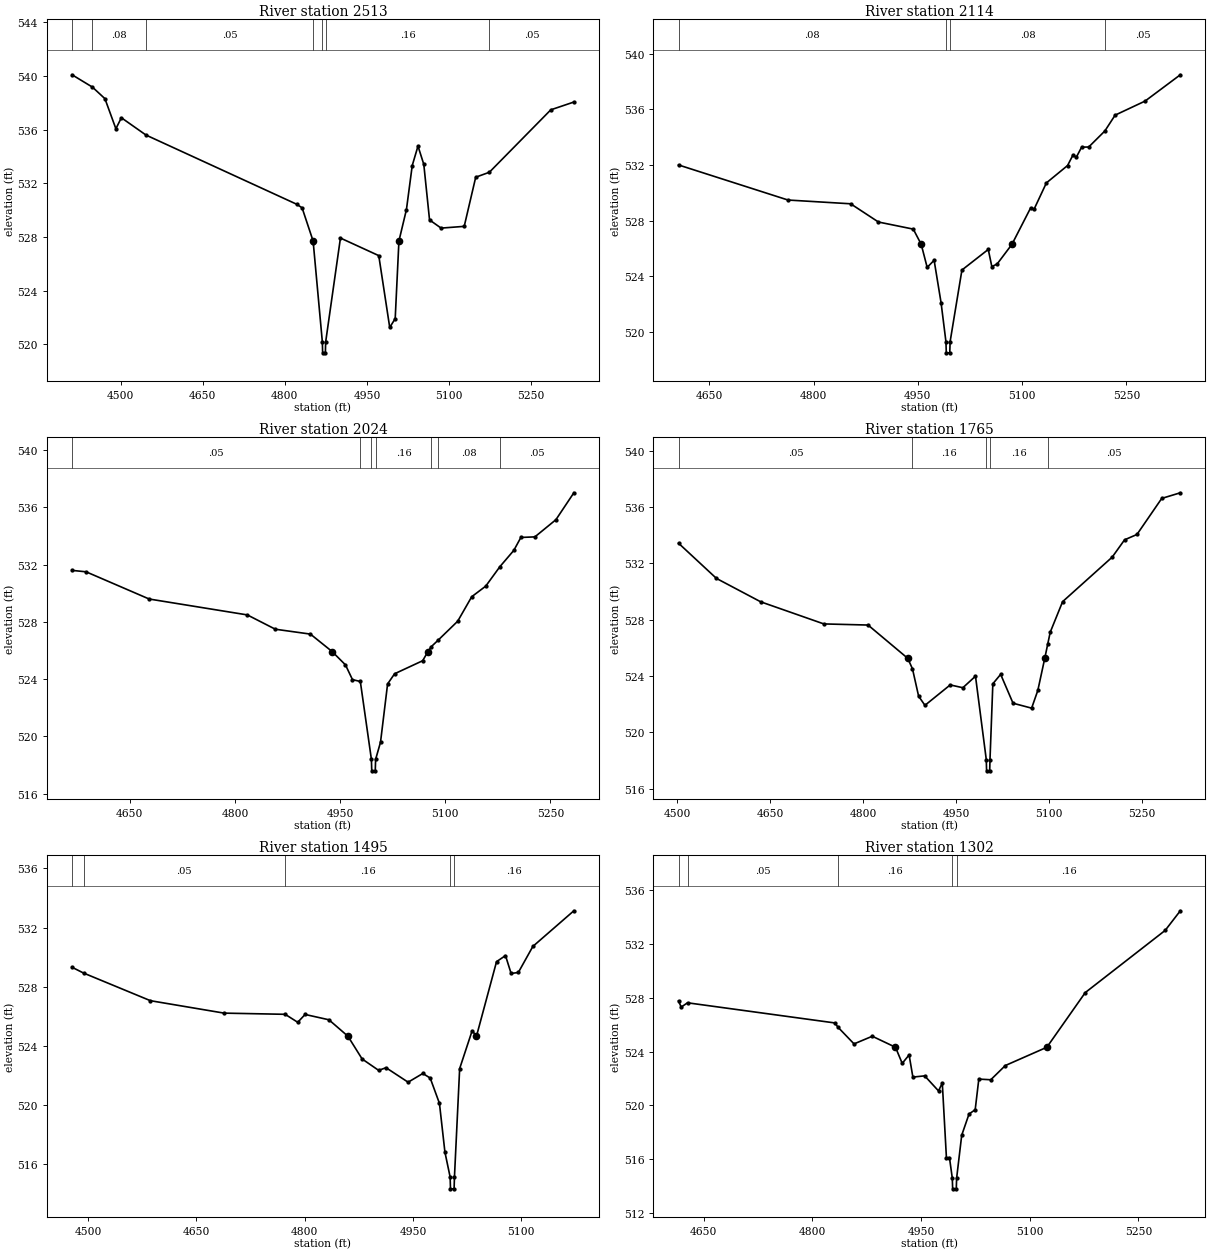
Type RM Length L Ch R = 1,2513,399,399,399
BEGIN DESCRIPTION:
LAKE FORK CREEK TRIB 6_2 4.0
END DESCRIPTION:
XS GIS Cut Line= 3
      2757575.00      7068575.01      2757575.00      7067975.00
      2757475.01      7067675.03
#Sta/Elev= 30
  4411.5  540.08  4448.7  539.16  4471.5  538.30  4491.5  536.06  4501.5  536.88
  4546.5  535.59  4821.5  530.44  4831.5  530.17  4851.6  527.70  4851.9  527.57
  4868.5  520.17  4869.0  519.37  4874.0  519.37  4874.5  520.17  4901.5  527.92
  4971.5  526.61  4991.5  521.26  5001.5  521.92  5008.3  527.70  5022.0  530.04
  5032.6  533.32  5043.1  534.77  5053.7  533.41  5064.2  529.27  5085.3  528.66
  5127.5  528.79  5148.5  532.45  5173.4  532.82  5285.6  537.47  5327.7  538.05
#Mann=7,-1,0
  4411.5    0.05       0  4448.7    0.08       0  4546.5    0.05       0
  4851.9    0.16       0  4868.5    0.07       0  4874.5    0.16       0
  5173.4    0.05       0
Bank Sta=4851.6,5008.3
Exp/Cntr=0.3,0.1

Type RM Length L Ch R = 1,2114,90,90,90
BEGIN DESCRIPTION:
LAKE FORK CREEK TRIB 6_2 3.0
END DESCRIPTION:
XS GIS Cut Line= 3
      2757807.47      7068292.36      2757825.00      7067875.00
      2757774.99      7067574.97
#Sta/Elev= 30
  4605.7  532.01  4763.2  529.49  4853.3  529.22  4893.3  527.91  4943.4  527.40
  4954.8  526.31  4963.4  524.65  4973.4  525.16  4983.4  522.11  4990.4  519.31
  4990.9  518.51  4995.9  518.51  4996.4  519.31  5013.4  524.46  5051.3  525.94
  5056.4  524.71  5064.0  524.89  5085.4  526.31  5112.1  528.91  5117.2  528.83
  5134.9  530.72  5165.4  531.97  5173.0  532.71  5178.0  532.57  5185.6  533.29
  5195.8  533.30  5219.0  534.45  5233.8  535.59  5276.9  536.60  5327.6  538.49
#Mann=4,-1,0
  4605.7    0.08       0  4990.4    0.07       0  4996.4    0.08       0
  5219.0    0.05       0
Bank Sta=4954.8,5085.4
Exp/Cntr=0.3,0.1

Type RM Length L Ch R = 1,2024,259,259,259
BEGIN DESCRIPTION:
Mapping XS 5900319c
END DESCRIPTION:
XS GIS Cut Line= 3
      2757889.93      7068275.00      2757894.27      7067867.02
      2757883.44      7067559.42
#Sta/Elev= 30
  4567.6  531.60  4587.6  531.50  4677.6  529.60  4817.6  528.49  4857.6  527.49
  4907.6  527.15  4938.6  525.93  4957.6  525.00  4967.6  523.97  4978.8  523.84
  4994.6  518.40  4995.1  517.60  5000.1  517.60  5000.6  518.40  5007.6  519.60
  5017.7  523.67  5027.7  524.38  5067.7  525.29  5075.3  525.93  5080.0  526.27
  5090.3  526.75  5117.7  528.05  5137.7  529.76  5157.7  530.50  5177.9  531.86
  5197.8  533.00  5207.8  533.90  5227.8  533.94  5257.8  535.14  5283.4  537.02
#Mann=7,-1,0
  4567.6    0.05       0  4978.8    0.16       0  4994.6    0.07       0
  5000.6    0.16       0  5080.0    0.05       0  5090.3    0.08       0
  5177.9    0.05       0
Bank Sta=4938.6,5075.3
Exp/Cntr=0.3,0.1

Type RM Length L Ch R = 1,1765,270,270,270
BEGIN DESCRIPTION:
LAKE FORK CREEK TRIB 6_2 2.0
END DESCRIPTION:
XS GIS Cut Line= 3
      2758025.00      7068324.99      2758125.00      7067825.00
      2758125.00      7067524.99
#Sta/Elev= 30
  4502.3  533.42  4563.5  530.92  4634.9  529.26  4736.8  527.69  4808.2  527.61
  4872.2  525.25  4879.9  524.50  4889.8  522.56  4900.0  521.91  4940.8  523.36
  4961.2  523.16  4981.6  523.98  4999.0  518.06  4999.5  517.26  5004.5  517.26
  5005.0  518.06  5009.6  523.44  5022.2  524.11  5042.2  522.06  5072.2  521.71
  5082.2  522.97  5093.4  525.25  5098.1  526.24  5102.2  527.10  5122.2  529.27
  5202.2  532.43  5222.2  533.66  5242.2  534.04  5282.2  536.60  5312.2  537.00
#Mann=5,-1,0
  4502.3    0.05       0  4879.9    0.16       0  4999.0    0.07       0
  5005.0    0.16       0  5098.1    0.05       0
Bank Sta=4872.2,5093.4
Exp/Cntr=0.3,0.1

Type RM Length L Ch R = 1,1495,193,193,193
BEGIN DESCRIPTION:
Mapping XS a5383fea
END DESCRIPTION:
XS GIS Cut Line= 4
      2758221.10      7068251.55      2758314.84      7067780.22
      2758338.28      7067665.63      2758330.60      7067568.36
#Sta/Elev= 30
  4477.7  529.32  4493.6  528.93  4586.3  527.06  4688.3  526.22  4772.9  526.14
  4790.3  525.60  4800.5  526.13  4833.5  525.77  4859.8  524.66  4879.5  523.12
  4902.4  522.35  4912.6  522.53  4943.2  521.55  4963.6  522.14  4973.8  521.83
  4986.6  520.12  4994.2  516.82  5001.4  515.14  5001.9  514.34  5006.9  514.34
  5007.4  515.14  5014.6  522.47  5031.9  525.03  5037.9  524.66  5065.7  529.70
  5078.1  530.11  5085.9  528.90  5095.9  528.97  5116.0  530.73  5172.8  533.14
#Mann=5,-1,0
  4477.7    0.08       0  4493.6    0.05       0  4772.9    0.16       0
  5001.4    0.07       0  5007.4    0.16       0
Bank Sta=4859.8,5037.9
Exp/Cntr=0.3,0.1

Type RM Length L Ch R = 1,1302,605,605,605
BEGIN DESCRIPTION:
Mapping XS fe87ff76
END DESCRIPTION:
XS GIS Cut Line= 3
      2758359.12      7068183.85      2758452.87      7067821.88
      2758429.43      7067504.16
#Sta/Elev= 30
  4615.4  527.76  4619.1  527.31  4627.8  527.63  4831.1  526.13  4835.5  525.81
  4857.6  524.57  4882.8  525.14  4914.8  524.32  4924.1  523.12  4933.6  523.75
  4938.8  522.10  4955.1  522.19  4974.2  521.07  4979.4  521.66  4985.1  516.10
  4989.3  516.10  4993.2  514.58  4993.7  513.78  4998.7  513.78  4999.2  514.58
  5006.2  517.77  5016.3  519.35  5024.8  519.67  5029.8  521.95  5046.3  521.90
  5066.4  522.96  5123.7  524.32  5176.7  528.39  5287.0  533.02  5307.9  534.48
#Mann=5,-1,0
  4615.4    0.08       0  4627.8    0.05       0  4835.5    0.16       0
  4993.2    0.07       0  4999.2    0.16       0
Bank Sta=4914.8,5123.7
Exp/Cntr=0.3,0.1

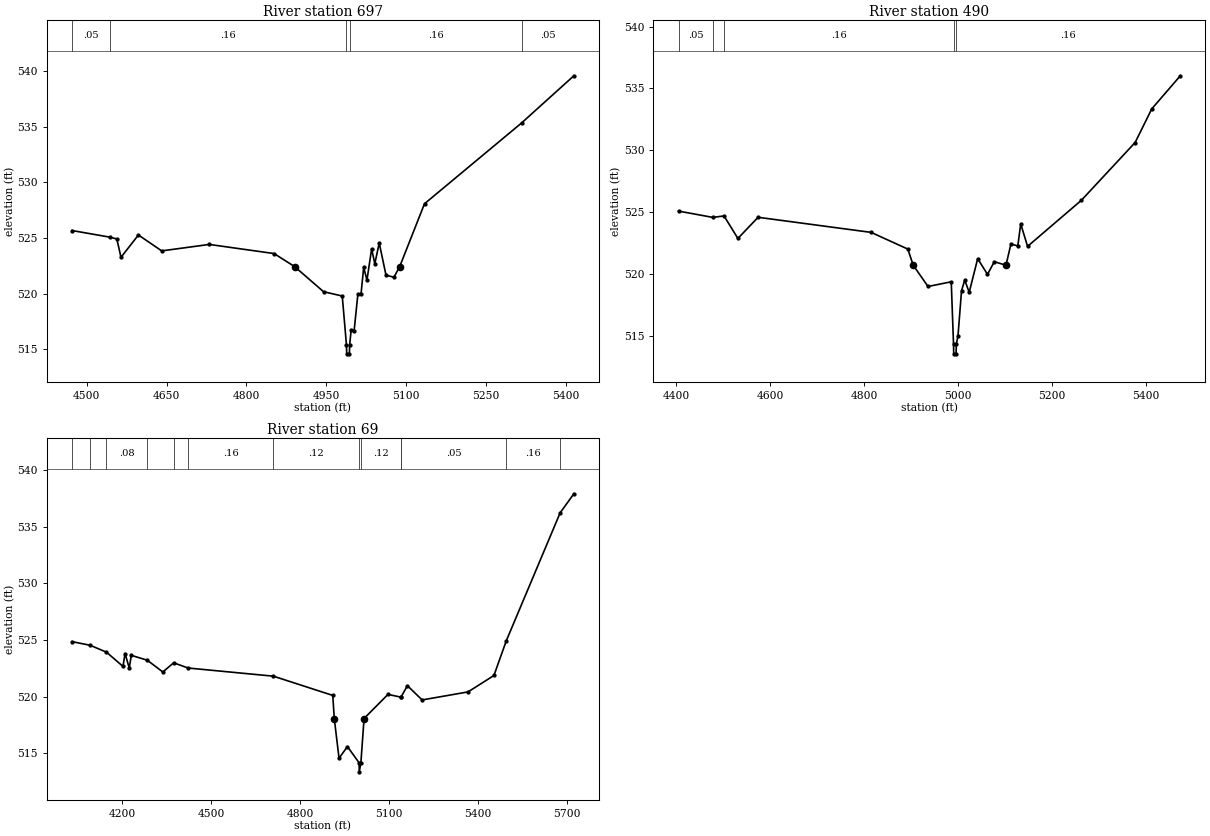
Type RM Length L Ch R = 1,697,207,207,207
BEGIN DESCRIPTION:
Mapping XS dcc3610f
END DESCRIPTION:
XS GIS Cut Line= 3
      2758496.63      7068038.93      2758715.80      7067546.33
      2758485.76      7067214.29
#Sta/Elev= 30
  4472.3  525.67  4544.0  525.07  4556.5  524.91  4564.2  523.26  4597.0  525.27
  4640.8  523.84  4730.2  524.42  4851.9  523.60  4890.5  522.43  4944.9  520.17
  4980.1  519.78  4988.0  515.38  4988.5  514.58  4993.5  514.58  4994.0  515.38
  4996.8  516.71  5002.3  516.60  5009.4  519.92  5015.3  519.92  5020.4  522.37
  5026.5  521.20  5035.3  524.01  5041.3  522.69  5049.6  524.55  5062.3  521.66
  5077.2  521.47  5088.1  522.43  5134.7  528.08  5317.0  535.34  5415.4  539.59
#Mann=5,-1,0
  4472.3    0.05       0  4544.0    0.16       0  4988.0    0.07       0
  4994.0    0.16       0  5317.0    0.05       0
Bank Sta=4890.5,5088.1
Exp/Cntr=0.3,0.1

Type RM Length L Ch R = 1,490,421,421,421
BEGIN DESCRIPTION:
Mapping XS 8c3015be
END DESCRIPTION:
XS GIS Cut Line= 3
      2758531.35      7068049.79      2758924.14      7067574.54
      2758652.90      7067212.17
#Sta/Elev= 30
  4404.4  525.09  4477.6  524.58  4501.3  524.70  4530.9  522.88  4573.9  524.59
  4814.8  523.37  4893.0  522.02  4904.4  520.72  4936.0  519.00  4985.5  519.38
  4990.3  514.36  4990.8  513.56  4995.8  513.56  4996.3  514.36  4999.8  514.98
  5007.4  518.66  5014.2  519.51  5023.8  518.53  5041.8  521.25  5062.7  519.98
  5077.3  521.00  5102.1  520.72  5112.7  522.44  5127.3  522.27  5133.5  524.06
  5148.1  522.24  5262.7  525.96  5377.3  530.63  5412.8  533.35  5473.6  536.02
#Mann=5,-1,0
  4404.4    0.05       0  4477.6    0.08       0  4501.3    0.16       0
  4990.3    0.07       0  4996.3    0.16       0
Bank Sta=4904.4,5102.1
Exp/Cntr=0.3,0.1

Type RM Length L Ch R = 1,69,0,0,0
BEGIN DESCRIPTION:
LAKE FORK CREEK TRIB 6_2 1.0
END DESCRIPTION:
XS GIS Cut Line= 3
      2758531.37      7068153.94      2759264.85      7067446.51
      2758681.09      7067112.31
#Sta/Elev= 30
  4031.0  524.86  4091.8  524.54  4147.0  523.93  4202.7  522.67  4209.6  523.81
  4223.8  522.53  4230.7  523.65  4284.5  523.22  4337.0  522.18  4373.5  522.99
  4422.1  522.53  4709.6  521.81  4909.9  520.11  4915.0  518.07  4931.0  514.56
  4959.3  515.59  4998.7  514.16  4999.2  513.36  5004.7  514.16  5015.4  518.07
  5096.0  520.20  5139.1  519.96  5140.5  519.99  5161.6  520.97  5211.2  519.71
  5365.9  520.42  5453.2  521.87  5495.0  524.94  5676.5  536.24  5722.7  537.92
#Mann=13,-1,0
  4031.0    0.08       0  4091.8    0.05       0  4147.0    0.08       0
  4284.5    0.05       0  4373.5    0.08       0  4422.1    0.16       0
  4709.6    0.12       0  4998.7    0.07       0  5004.7    0.12       0
  5139.1    0.07       0  5140.5    0.05       0  5495.0    0.16       0
  5676.5    0.05       0
Bank Sta=4915,5015.4
Exp/Cntr=0.3,0.1

Chan Stop Cuts=-1