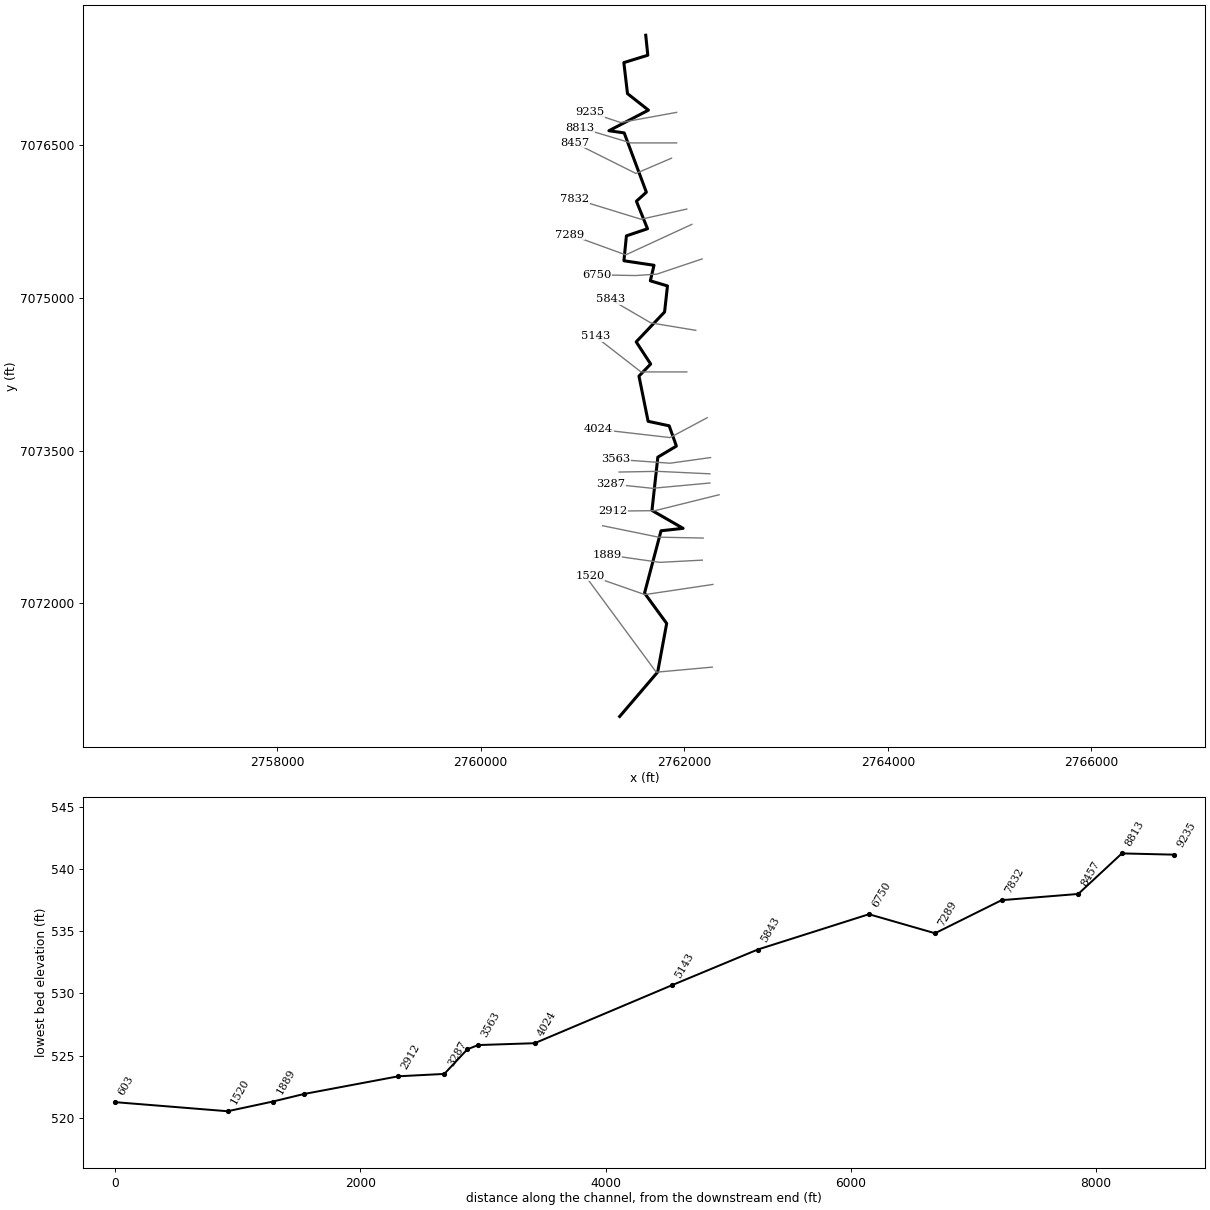
--- LAKE FORK CREEK TRIB 8.prj (project) ---

Proj Title=LAKE FORK CREEK TRIB 8 Base Level Engineering
Current Plan=p01
Default Exp/Contr=0.3,0.1
English Units
Geom File=g01
Flow File=f01
Plan File=p01
BEGIN DESCRIPTION:
LAKE FORK CREEK TRIB 8
END DESCRIPTION:

--- LAKE FORK CREEK TRIB 8.p01 (plan) ---

Plan Title=Multiple Run
Short Identifier=Multiple
Geom File=g01
Flow File=f01
Subcritical Flow
K Sum by GR= 0
Std Step Tol= 0.01
Critical Tol= 0.01
Num of Std Step Trials= 20
Max Error Tol= 0.3
Flow Tol Ratio= 0.001
Split Flow NTrial= 30
Split Flow Tol= 0.02
Split Flow Ratio= 0.02
Log Output Level= 0
Friction Slope Method= 1
Unsteady Friction Slope Method= 2
Unsteady Bridges Friction Slope Method= 1
Parabolic Critical Depth
Global Vel Dist=  1 , 1 , 1
Global Log Level= 0
CheckData=True
Encroach Param= -1, 0, 0, 0
BEGIN DESCRIPTION:
Multiple Run
END DESCRIPTION:

--- LAKE FORK CREEK TRIB 8.f01 (steady flow) ---

Flow Title=Multiple
Number of Profiles=7
Profile Names=10-year,25-year,50-year,1pct_min,100-year,1pct_plu,500-year
River Rch & RM= LAKE FORK CREEK ,Reach-1,9235
     652     865    1035     614    1224    2443    1711
River Rch & RM= LAKE FORK CREEK ,Reach-1,8813
     798    1068    1285     765    1527    3047    2154
Boundary for River Rch & Prof#=LAKE FORK CREEK ,Reach-1,1
Up Type=0
Dn Type=3
Dn Slope=0.005
Boundary for River Rch & Prof#=LAKE FORK CREEK ,Reach-1,2
Up Type=0
Dn Type=3
Dn Slope=0.005
Boundary for River Rch & Prof#=LAKE FORK CREEK ,Reach-1,3
Up Type=0
Dn Type=3
Dn Slope=0.005
Boundary for River Rch & Prof#=LAKE FORK CREEK ,Reach-1,4
Up Type=0
Dn Type=3
Dn Slope=0.005
Boundary for River Rch & Prof#=LAKE FORK CREEK ,Reach-1,5
Up Type=0
Dn Type=3
Dn Slope=0.005
Boundary for River Rch & Prof#=LAKE FORK CREEK ,Reach-1,6
Up Type=0
Dn Type=3
Dn Slope=0.005
Boundary for River Rch & Prof#=LAKE FORK CREEK ,Reach-1,7
Up Type=0
Dn Type=3
Dn Slope=0.005

--- LAKE FORK CREEK TRIB 8.g01 (geometry) ---

Geom Title=Existing Conditions

River Reach=LAKE FORK CREEK ,Reach-1
Reach XY= 30
      2761621.51      7077582.79      2761641.81      7077386.49
      2761406.44      7077313.89      2761442.30      7077009.16
      2761648.31      7076846.97      2761259.87      7076644.60
      2761409.76      7076623.34      2761627.65      7076040.78
      2761529.83      7075952.08      2761638.93      7075681.65
      2761431.76      7075611.80      2761407.31      7075367.10
      2761702.69      7075322.78      2761666.68      7075170.20
      2761835.12      7075119.86      2761806.54      7074863.87
      2761527.80      7074570.53      2761670.09      7074352.52
      2761555.04      7074233.96      2761644.84      7073789.88
      2761851.79      7073745.69      2761922.65      7073546.45
      2761740.24      7073437.71      2761682.72      7072914.36
      2761988.59      7072738.27      2761771.81      7072714.42
      2761609.76      7072101.97      2761827.24      7071803.82
      2761738.84      7071326.77      2761365.58      7070890.13

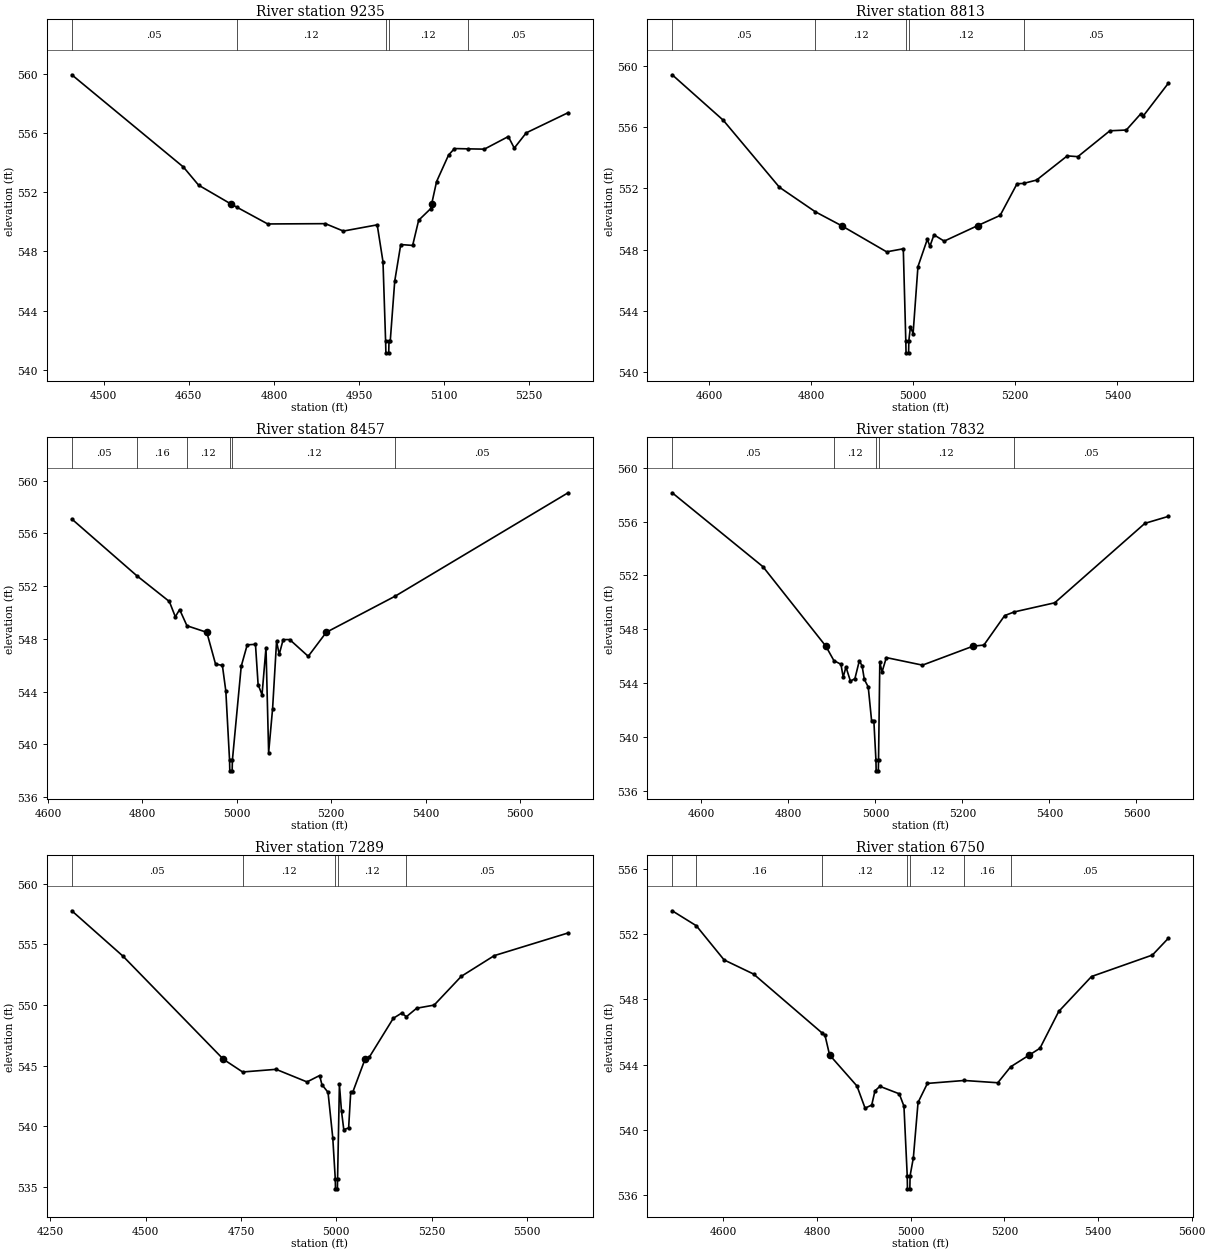
Type RM Length L Ch R = 1,9235,422,422,422
BEGIN DESCRIPTION:
LAKE FORK CREEK TRIB 8 14.0
END DESCRIPTION:
XS GIS Cut Line= 3
      2761924.95      7076824.99      2761375.00      7076725.00
      2761075.00      7076825.00
#Sta/Elev= 30
  4443.6  559.92  4640.5  553.69  4667.2  552.47  4723.7  551.21  4734.3  550.99
  4789.1  549.85  4890.8  549.87  4922.5  549.37  4982.2  549.79  4992.4  547.30
  4997.0  541.95  4997.5  541.15  5002.5  541.15  5003.0  541.95  5005.2  541.95
  5013.1  545.99  5023.7  548.46  5044.7  548.40  5055.3  550.10  5076.4  550.88
  5078.3  551.21  5086.9  552.71  5108.0  554.50  5118.5  554.94  5141.9  554.92
  5171.2  554.90  5213.4  555.75  5223.9  554.97  5245.0  556.00  5318.8  557.36
#Mann=5,-1,0
  4443.6    0.05       0  4734.3    0.12       0  4997.0    0.07       0
  5003.0    0.12       0  5141.9    0.05       0
Bank Sta=4723.7,5078.3
Exp/Cntr=0.3,0.1

Type RM Length L Ch R = 1,8813,356,356,356
BEGIN DESCRIPTION:
LAKE FORK CREEK TRIB 8 13.0
END DESCRIPTION:
XS GIS Cut Line= 3
      2761925.02      7076525.00      2761475.00      7076525.00
      2760975.03      7076674.99
#Sta/Elev= 30
  4528.1  559.42  4628.1  556.45  4738.1  552.07  4808.3  550.47  4859.7  549.56
  4948.1  547.85  4980.7  548.05  4985.6  542.05  4986.1  541.25  4991.1  541.25
  4991.6  542.05  4994.7  542.96  4999.9  542.51  5009.4  546.88  5027.7  548.66
  5032.9  548.22  5040.8  548.96  5060.8  548.55  5126.2  549.56  5170.4  550.23
  5203.5  552.30  5216.2  552.32  5241.7  552.54  5301.8  554.12  5322.6  554.07
  5385.3  555.76  5417.5  555.81  5445.3  556.85  5450.5  556.72  5500.1  558.88
#Mann=5,-1,0
  4528.1    0.05       0  4808.3    0.12       0  4985.6    0.07       0
  4991.6    0.12       0  5216.2    0.05       0
Bank Sta=4859.7,5126.2
Exp/Cntr=0.3,0.1

Type RM Length L Ch R = 1,8457,625,625,625
BEGIN DESCRIPTION:
LAKE FORK CREEK TRIB 8 12.0
END DESCRIPTION:
XS GIS Cut Line= 3
      2761874.99      7076375.00      2761525.00      7076225.00
      2760925.00      7076525.00
#Sta/Elev= 30
  4650.4  557.10  4787.7  552.81  4857.1  550.84  4869.8  549.68  4878.9  550.23
  4894.4  549.00  4936.5  548.50  4955.0  546.09  4969.5  545.99  4976.8  544.04
  4984.7  538.79  4985.2  537.99  4990.2  537.99  4990.7  538.79  5009.4  545.92
  5022.1  547.55  5039.6  547.59  5045.2  544.54  5053.5  543.76  5061.9  547.34
  5067.5  539.37  5075.9  542.72  5084.3  547.82  5089.9  546.83  5098.3  547.95
  5112.2  547.95  5151.4  546.68  5189.6  548.50  5335.9  551.25  5702.0  559.09
#Mann=6,-1,0
  4650.4    0.05       0  4787.7    0.16       0  4894.4    0.12       0
  4984.7    0.07       0  4990.7    0.12       0  5335.9    0.05       0
Bank Sta=4936.5,5189.6
Exp/Cntr=0.3,0.1

Type RM Length L Ch R = 1,7832,543,543,543
BEGIN DESCRIPTION:
LAKE FORK CREEK TRIB 8 11.0
END DESCRIPTION:
XS GIS Cut Line= 3
      2762024.98      7075875.00      2761575.00      7075775.00
      2760925.03      7075974.99
#Sta/Elev= 30
  4532.7  558.14  4741.4  552.65  4885.9  546.75  4904.4  545.68  4920.7  545.40
  4925.8  544.45  4932.2  545.20  4942.4  544.16  4952.7  544.33  4962.9  545.66
  4969.3  545.29  4974.4  544.28  4983.4  543.72  4991.1  541.22  4996.3  541.22
  5001.1  538.29  5001.6  537.49  5006.6  537.49  5007.1  538.29  5010.0  545.55
  5015.2  544.84  5025.0  545.90  5108.1  545.34  5224.5  546.75  5249.3  546.83
  5297.1  549.02  5318.9  549.29  5412.2  549.97  5619.5  555.87  5673.7  556.39
#Mann=5,-1,0
  4532.7    0.05       0  4904.4    0.12       0  5001.1    0.07       0
  5007.1    0.12       0  5318.9    0.05       0
Bank Sta=4885.9,5224.5
Exp/Cntr=0.3,0.1

Type RM Length L Ch R = 1,7289,539,539,539
BEGIN DESCRIPTION:
LAKE FORK CREEK TRIB 8 10.0
END DESCRIPTION:
XS GIS Cut Line= 3
      2762074.97      7075724.99      2761425.00      7075425.00
      2760875.00      7075625.00
#Sta/Elev= 30
  4306.5  557.77  4440.9  554.02  4703.9  545.52  4754.4  544.47  4842.0  544.69
  4923.2  543.65  4956.3  544.18  4962.2  543.43  4978.3  542.79  4990.7  539.04
  4997.3  535.63  4997.8  534.83  5002.8  534.83  5003.3  535.63  5008.1  543.44
  5013.6  541.23  5019.6  539.71  5032.3  539.86  5037.7  542.78  5043.6  542.85
  5075.2  545.52  5086.2  545.68  5149.4  548.90  5171.3  549.33  5183.7  549.03
  5210.6  549.73  5256.5  549.99  5327.6  552.36  5414.1  554.07  5607.6  555.94
#Mann=5,-1,0
  4306.5    0.05       0  4754.4    0.12       0  4997.3    0.07       0
  5003.3    0.12       0  5183.7    0.05       0
Bank Sta=4703.9,5075.2
Exp/Cntr=0.3,0.1

Type RM Length L Ch R = 1,6750,907,907,907
BEGIN DESCRIPTION:
Mapping XS 95b862ff
END DESCRIPTION:
XS GIS Cut Line= 4
      2762175.35      7075385.15      2761730.94      7075235.85
      2761522.61      7075221.97      2761140.68      7075228.91
#Sta/Elev= 30
  4490.9  553.45  4542.4  552.53  4601.7  550.43  4664.7  549.56  4810.5  545.95
  4817.1  545.80  4826.9  544.59  4885.4  542.68  4902.7  541.32  4916.9  541.51
  4923.8  542.38  4934.3  542.66  4975.7  542.20  4985.7  541.44  4992.7  537.16
  4993.2  536.36  4998.3  536.36  4998.8  537.16  5005.8  538.27  5015.8  541.67
  5035.8  542.84  5114.4  543.02  5186.1  542.88  5213.5  543.86  5253.6  544.59
  5276.1  545.00  5316.1  547.26  5386.2  549.41  5516.2  550.73  5550.5  551.77
#Mann=7,-1,0
  4490.9    0.05       0  4542.4    0.16       0  4810.5    0.12       0
  4992.7    0.07       0  4998.8    0.12       0  5114.4    0.16       0
  5213.5    0.05       0
Bank Sta=4826.9,5253.6
Exp/Cntr=0.3,0.1

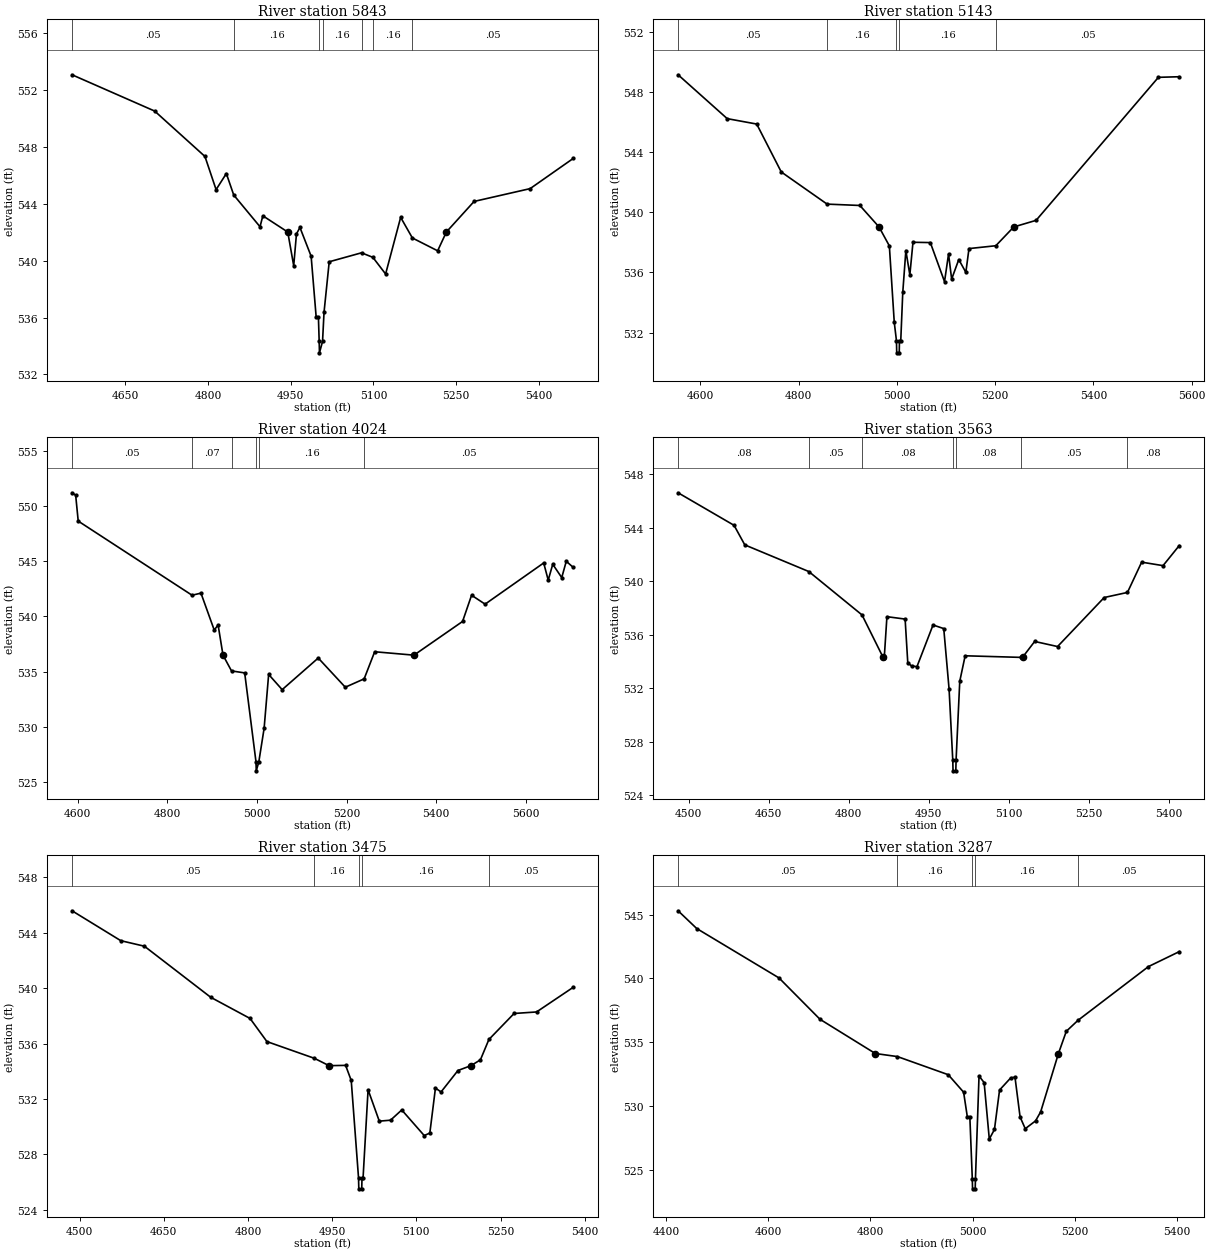
Type RM Length L Ch R = 1,5843,700,700,700
BEGIN DESCRIPTION:
Mapping XS fa7b2de0
END DESCRIPTION:
XS GIS Cut Line= 3
      2762112.84      7074683.78      2761671.91      7074756.69
      2761272.56      7074989.35
#Sta/Elev= 30
  4553.3  553.06  4703.2  550.51  4794.4  547.32  4814.6  544.99  4833.2  546.12
  4846.6  544.61  4894.3  542.38  4899.4  543.15  4944.6  542.01  4955.4  539.64
  4960.4  541.88  4966.7  542.33  4987.0  540.31  4996.1  536.05  5000.2  536.05
  5001.6  534.32  5002.1  533.52  5007.7  534.32  5010.4  536.37  5019.8  539.92
  5078.4  540.55  5099.0  540.23  5122.1  539.06  5149.4  543.04  5170.7  541.59
  5216.5  540.69  5232.3  542.01  5282.6  544.16  5384.3  545.06  5462.4  547.18
#Mann=7,-1,0
  4553.3    0.05       0  4846.6    0.16       0  5001.6    0.07       0
  5007.7    0.16       0  5078.4    0.12       0  5099.0    0.16       0
  5170.7    0.05       0
Bank Sta=4944.6,5232.3
Exp/Cntr=0.3,0.1

Type RM Length L Ch R = 1,5143,1119,1119,1119
BEGIN DESCRIPTION:
LAKE FORK CREEK TRIB 8 7.0
END DESCRIPTION:
XS GIS Cut Line= 3
      2762025.01      7074275.00      2761575.00      7074275.00
      2761125.00      7074625.00
#Sta/Elev= 30
  4554.8  549.16  4654.8  546.24  4714.8  545.88  4764.8  542.69  4858.1  540.55
  4924.8  540.46  4963.8  539.03  4984.8  537.77  4994.8  532.68  4999.3  531.45
  4999.8  530.65  5004.9  530.65  5005.4  531.45  5008.0  531.45  5012.1  534.67
  5018.4  537.46  5026.5  535.84  5032.9  538.01  5068.2  537.99  5097.1  535.39
  5105.3  537.23  5111.6  535.56  5126.1  536.86  5140.5  536.01  5146.9  537.59
  5201.5  537.78  5238.0  539.03  5283.5  539.47  5532.4  548.99  5574.9  549.03
#Mann=5,-1,0
  4554.8    0.05       0  4858.1    0.16       0  4999.3    0.07       0
  5005.4    0.16       0  5201.5    0.05       0
Bank Sta=4963.8,5238
Exp/Cntr=0.3,0.1

Type RM Length L Ch R = 1,4024,461,461,461
BEGIN DESCRIPTION:
LAKE FORK CREEK TRIB 8 6.0
END DESCRIPTION:
XS GIS Cut Line= 3
      2762224.98      7073824.99      2761859.82      7073630.06
      2761159.57      7073710.66
#Sta/Elev= 30
  4587.3  551.23  4595.4  551.01  4601.1  548.66  4855.2  541.93  4875.1  542.12
  4904.7  538.77  4913.4  539.23  4924.3  536.49  4943.3  535.06  4972.7  534.88
  4998.0  526.79  4998.5  525.99  5004.2  526.79  5016.1  529.85  5026.2  534.74
  5056.4  533.36  5136.9  536.23  5197.3  533.58  5239.4  534.34  5262.9  536.80
  5350.6  536.49  5459.1  539.55  5479.2  541.93  5509.4  541.12  5640.2  544.86
  5650.3  543.30  5660.4  544.74  5680.5  543.53  5690.6  545.01  5706.1  544.46
#Mann=6,-1,0
  4587.3    0.05       0  4855.2    0.07       0  4943.3    0.16       0
  4998.0    0.07       0  5004.2    0.16       0  5239.4    0.05       0
Bank Sta=4924.3,5350.6
Exp/Cntr=0.3,0.1

Type RM Length L Ch R = 1,3563,88,88,88
BEGIN DESCRIPTION:
Mapping XS 713ada8a
END DESCRIPTION:
XS GIS Cut Line= 3
      2762258.76      7073433.78      2761859.41      7073378.22
      2761324.67      7073416.41
#Sta/Elev= 30
  4480.4  546.60  4585.3  544.17  4605.4  542.71  4725.4  540.72  4825.1  537.48
  4863.9  534.37  4866.7  534.23  4871.8  537.35  4905.9  537.17  4910.9  533.89
  4918.1  533.67  4928.1  533.62  4958.2  536.73  4978.3  536.46  4988.3  531.94
  4995.2  526.64  4995.7  525.84  5000.9  525.84  5001.4  526.64  5008.3  532.53
  5018.4  534.43  5123.6  534.31  5127.0  534.37  5148.7  535.50  5191.6  535.12
  5279.0  538.78  5322.6  539.16  5349.2  541.42  5389.3  541.16  5419.7  542.66
#Mann=7,-1,0
  4480.4    0.08       0  4725.4    0.05       0  4825.1    0.08       0
  4995.2    0.07       0  5001.4    0.08       0  5123.6    0.05       0
  5322.6    0.08       0
Bank Sta=4863.9,5127
Exp/Cntr=0.3,0.1

Type RM Length L Ch R = 1,3475,188,188,188
BEGIN DESCRIPTION:
Mapping XS c2521d54
END DESCRIPTION:
XS GIS Cut Line= 3
      2762251.75      7073274.05      2761737.88      7073298.35
      2761359.69      7073291.41
#Sta/Elev= 30
  4486.7  545.59  4573.5  543.43  4615.6  543.03  4733.7  539.34  4803.8  537.81
  4833.8  536.14  4918.4  534.93  4944.5  534.40  4974.0  534.42  4984.0  533.33
  4997.0  526.30  4997.5  525.50  5002.7  525.50  5003.2  526.30  5005.1  526.30
  5014.0  532.66  5034.0  530.39  5054.0  530.46  5074.0  531.20  5114.0  529.35
  5124.0  529.53  5134.0  532.78  5144.0  532.50  5174.1  534.05  5197.2  534.40
  5214.1  534.82  5229.2  536.29  5274.1  538.17  5314.1  538.28  5379.4  540.06
#Mann=5,-1,0
  4486.7    0.05       0  4918.4    0.16       0  4997.0    0.07       0
  5003.2    0.16       0  5229.2    0.05       0
Bank Sta=4944.5,5197.2
Exp/Cntr=0.3,0.1

Type RM Length L Ch R = 1,3287,375,375,375
BEGIN DESCRIPTION:
LAKE FORK CREEK TRIB 8 5.0
END DESCRIPTION:
XS GIS Cut Line= 3
      2762251.78      7073183.77      2761685.80      7073131.69
      2761275.05      7073174.99
#Sta/Elev= 30
  4423.3  545.30  4459.8  543.91  4620.9  540.04  4701.2  536.80  4809.5  534.12
  4852.8  533.88  4952.3  532.46  4982.4  531.09  4989.6  529.18  4994.6  529.18
  4999.4  524.32  4999.9  523.52  5005.1  523.52  5005.6  524.32  5012.6  532.36
  5022.6  531.84  5032.7  527.42  5042.8  528.17  5052.8  531.26  5074.4  532.20
  5083.0  532.27  5093.0  529.15  5103.1  528.23  5123.2  528.84  5133.3  529.55
  5168.1  534.12  5183.5  535.86  5206.4  536.72  5344.4  540.93  5404.7  542.10
#Mann=5,-1,0
  4423.3    0.05       0  4852.8    0.16       0  4999.4    0.07       0
  5005.6    0.16       0  5206.4    0.05       0
Bank Sta=4809.5,5168.1
Exp/Cntr=0.3,0.1

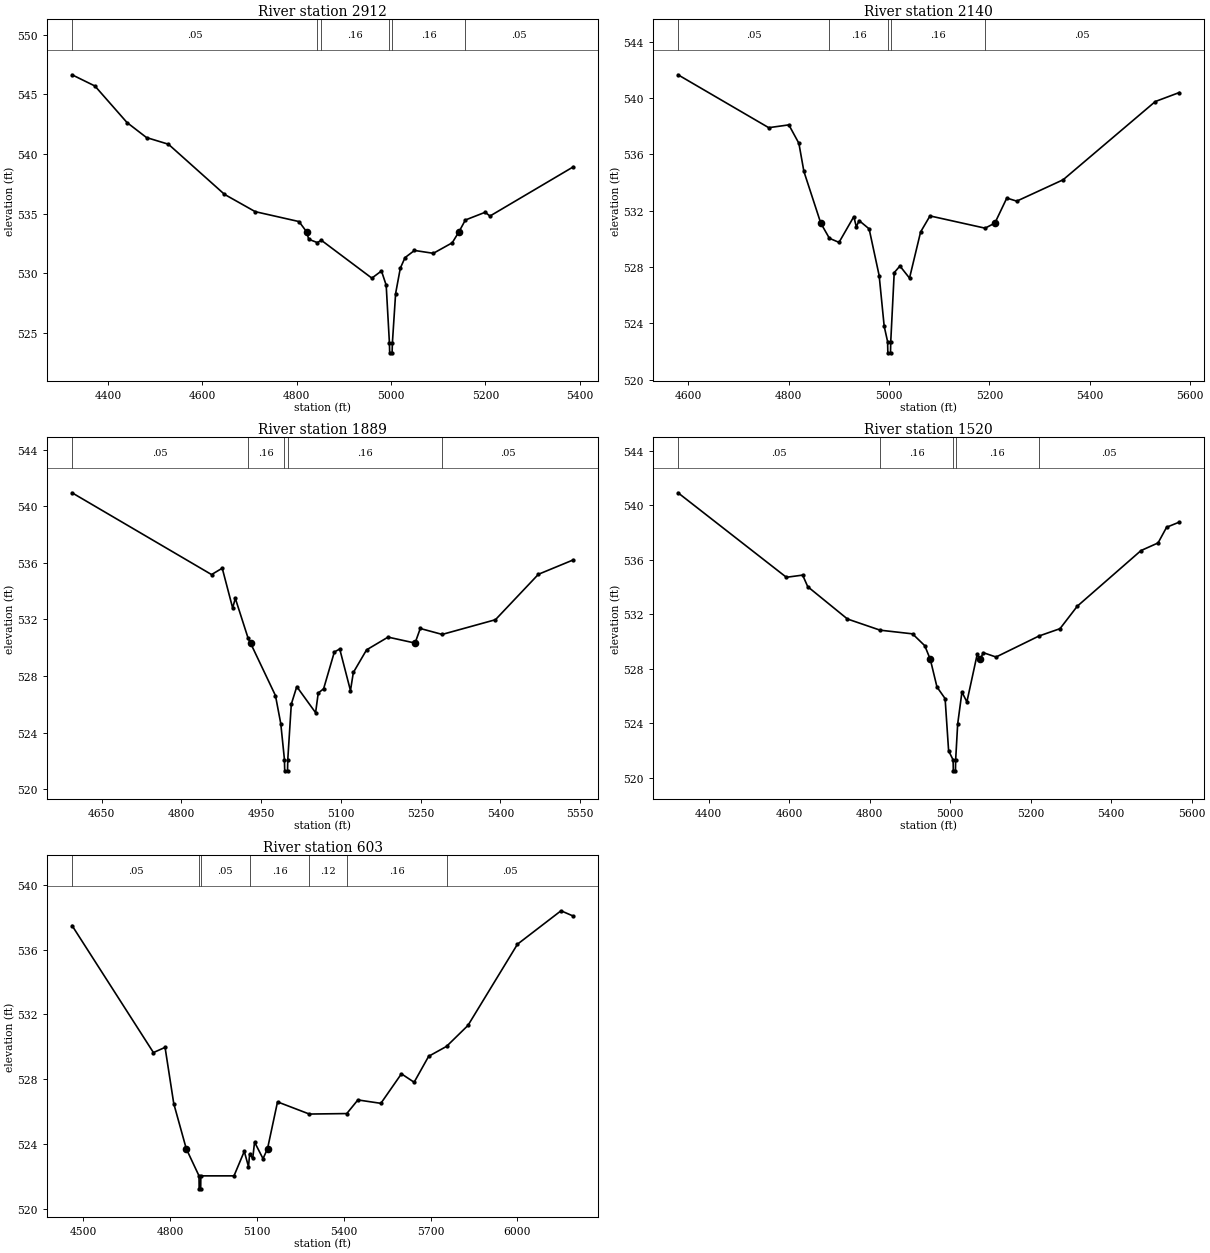
Type RM Length L Ch R = 1,2912,772,772,772
BEGIN DESCRIPTION:
Mapping XS e9f98969
END DESCRIPTION:
XS GIS Cut Line= 3
      2762342.09      7073068.33      2761712.71      7072912.07
      2761298.03      7072907.75
#Sta/Elev= 30
  4323.5  546.63  4372.0  545.69  4440.0  542.63  4481.4  541.37  4527.9  540.81
  4646.8  536.61  4712.0  535.16  4804.8  534.33  4821.0  533.47  4825.4  532.85
  4843.5  532.57  4852.3  532.76  4959.3  529.59  4979.7  530.19  4989.7  529.00
  4996.6  524.13  4997.1  523.33  5002.3  523.33  5002.8  524.13  5009.7  528.30
  5019.7  530.43  5029.7  531.31  5049.7  531.91  5089.7  531.67  5129.7  532.55
  5144.0  533.47  5157.6  534.46  5199.7  535.11  5209.7  534.79  5386.7  538.92
#Mann=6,-1,0
  4323.5    0.05       0  4843.5    0.12       0  4852.3    0.16       0
  4996.6    0.07       0  5002.8    0.16       0  5157.6    0.05       0
Bank Sta=4821,5144
Exp/Cntr=0.3,0.1

Type RM Length L Ch R = 1,2140,251,251,251
BEGIN DESCRIPTION:
Mapping XS ccd44601
END DESCRIPTION:
XS GIS Cut Line= 3
      2762185.81      7072642.97      2761747.43      7072651.65
      2761198.09      7072764.12
#Sta/Elev= 30
  4579.5  541.66  4760.3  537.90  4800.4  538.10  4820.4  536.79  4830.4  534.79
  4864.0  531.12  4881.2  530.04  4900.4  529.75  4929.9  531.58  4934.9  530.85
  4940.4  531.30  4960.4  530.71  4980.4  527.39  4990.4  523.79  4997.2  522.70
  4997.7  521.90  5003.0  521.90  5003.5  522.70  5010.4  527.60  5021.8  528.07
  5040.9  527.21  5063.0  530.49  5081.7  531.63  5191.5  530.76  5211.0  531.12
  5234.8  532.90  5254.6  532.68  5347.1  534.20  5530.8  539.76  5578.7  540.40
#Mann=5,-1,0
  4579.5    0.05       0  4881.2    0.16       0  4997.2    0.07       0
  5003.5    0.16       0  5191.5    0.05       0
Bank Sta=4864,5211
Exp/Cntr=0.3,0.1

Type RM Length L Ch R = 1,1889,369,369,369
BEGIN DESCRIPTION:
Mapping XS 5af5de30
END DESCRIPTION:
XS GIS Cut Line= 3
      2762177.08      7072425.96      2761760.45      7072404.26
      2761239.84      7072478.01
#Sta/Elev= 30
  4594.4  540.95  4856.8  535.17  4876.9  535.62  4896.5  532.81  4901.5  533.49
  4925.5  530.68  4930.1  530.33  4977.0  526.62  4987.0  524.64  4993.9  522.10
  4994.4  521.30  4999.7  521.30  5000.2  522.10  5006.8  526.01  5017.1  527.25
  5052.5  525.41  5057.5  526.80  5067.6  527.10  5087.8  529.70  5097.9  529.91
  5118.1  526.97  5123.5  528.25  5148.4  529.85  5188.8  530.75  5239.6  530.33
  5249.4  531.36  5290.6  530.94  5390.8  531.98  5471.6  535.19  5537.4  536.21
#Mann=5,-1,0
  4594.4    0.05       0  4925.5    0.16       0  4993.9    0.07       0
  5000.2    0.16       0  5290.6    0.05       0
Bank Sta=4930.1,5239.6
Exp/Cntr=0.3,0.1

Type RM Length L Ch R = 1,1520,917,917,917
BEGIN DESCRIPTION:
LAKE FORK CREEK TRIB 8 2.0
END DESCRIPTION:
XS GIS Cut Line= 3
      2762281.24      7072187.24      2761612.88      7072087.42
      2761075.02      7072274.99
#Sta/Elev= 30
  4324.1  540.92  4593.3  534.72  4633.7  534.88  4646.4  534.03  4745.0  531.66
  4826.1  530.84  4906.7  530.57  4937.1  529.70  4950.9  528.69  4967.4  526.67
  4987.6  525.82  4996.3  521.99  5007.5  521.32  5008.0  520.52  5013.3  520.52
  5013.8  521.32  5018.8  523.95  5029.4  526.30  5041.7  525.58  5067.5  529.09
  5074.6  528.69  5082.4  529.19  5114.1  528.87  5220.6  530.41  5273.0  530.95
  5316.0  532.60  5474.2  536.68  5516.6  537.24  5537.8  538.39  5569.5  538.77
#Mann=5,-1,0
  4324.1    0.05       0  4826.1    0.16       0  5007.5    0.07       0
  5013.8    0.16       0  5220.6    0.05       0
Bank Sta=4950.9,5074.6
Exp/Cntr=0.3,0.1

Type RM Length L Ch R = 1,603,0,0,0
BEGIN DESCRIPTION:
LAKE FORK CREEK TRIB 8 1.0
END DESCRIPTION:
XS GIS Cut Line= 3
      2762275.03      7071375.00      2761725.00      7071325.00
      2761025.02      7072274.97
#Sta/Elev= 30
  4461.2  537.48  4742.4  529.65  4782.6  529.97  4812.7  526.50  4855.9  523.72
  4899.9  522.05  4900.4  521.25  4905.7  521.25  4906.2  522.05  5020.8  522.05
  5056.3  523.56  5070.9  522.62  5074.9  523.39  5085.6  523.13  5091.8  524.13
  5121.1  523.11  5136.6  523.72  5171.2  526.61  5281.1  525.86  5410.5  525.89
  5448.9  526.73  5528.3  526.52  5599.3  528.34  5643.2  527.82  5693.4  529.42
  5755.1  530.03  5829.1  531.32  6000.3  536.33  6150.7  538.39  6193.5  538.06
#Mann=7,-1,0
  4461.2    0.05       0  4899.9   0.035       0  4906.2    0.05       0
  5074.9    0.16       0  5281.1    0.12       0  5410.5    0.16       0
  5755.1    0.05       0
Bank Sta=4855.9,5136.6
Exp/Cntr=0.3,0.1

Chan Stop Cuts=-1