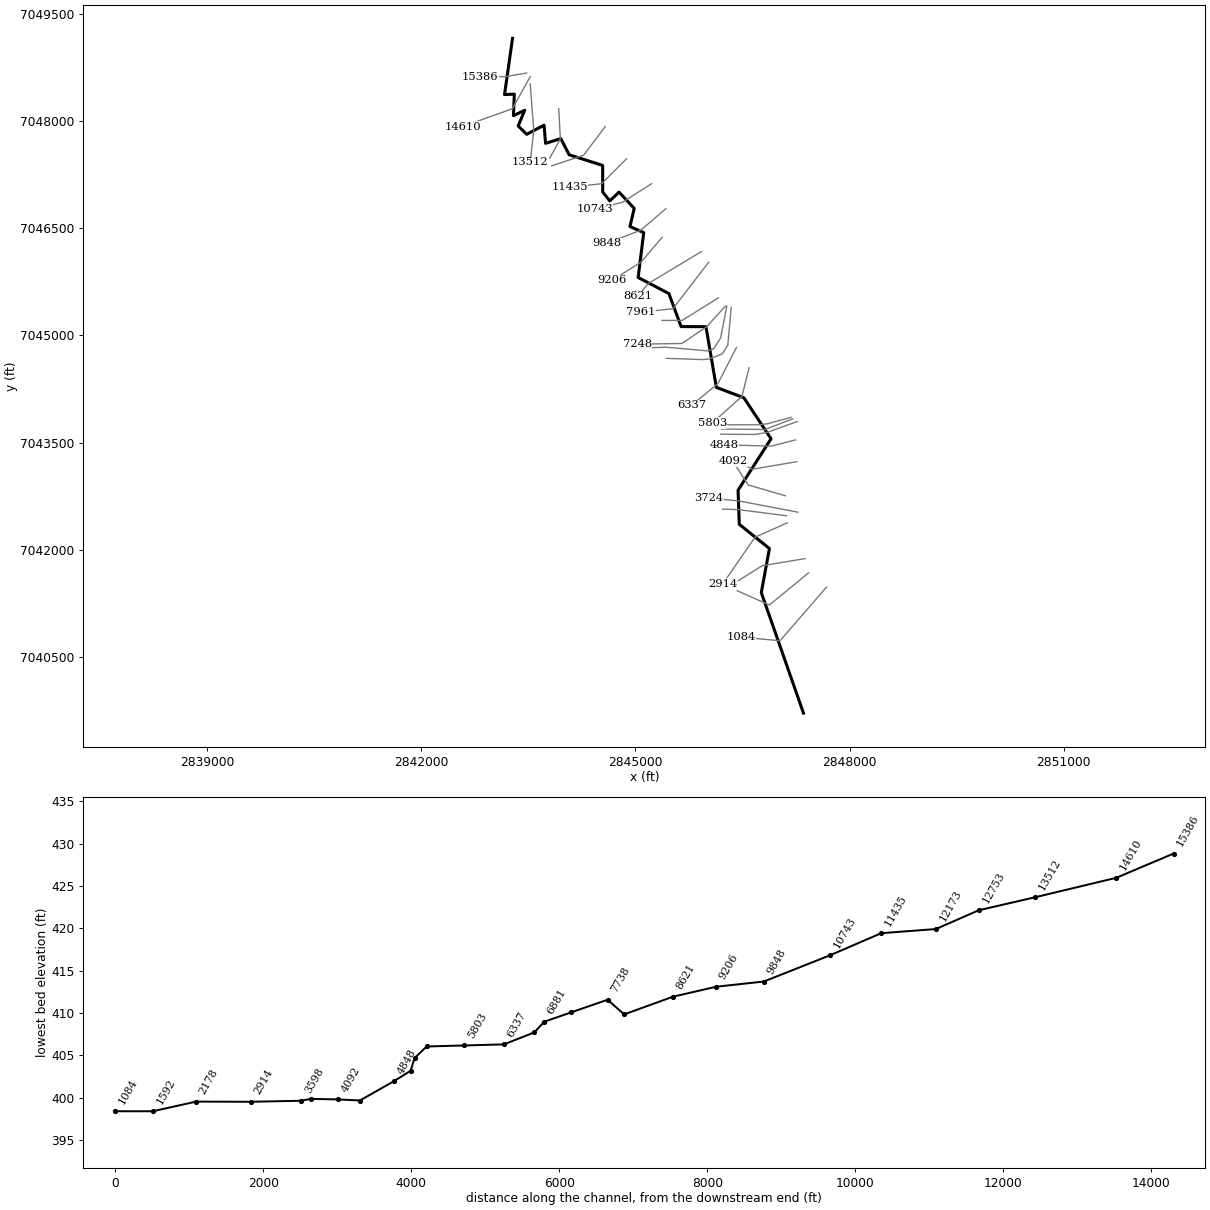
--- LINN BRANCH.prj (project) ---

Proj Title=LINN BRANCH Base Level Engineering
Current Plan=p01
Default Exp/Contr=0.3,0.1
English Units
Geom File=g01
Flow File=f01
Plan File=p01
BEGIN DESCRIPTION:
LINN BRANCH
END DESCRIPTION:

--- LINN BRANCH.p01 (plan) ---

Plan Title=Multiple Run
Short Identifier=Multiple
Geom File=g01
Flow File=f01
Subcritical Flow
K Sum by GR= 0
Std Step Tol= 0.01
Critical Tol= 0.01
Num of Std Step Trials= 20
Max Error Tol= 0.3
Flow Tol Ratio= 0.001
Split Flow NTrial= 30
Split Flow Tol= 0.02
Split Flow Ratio= 0.02
Log Output Level= 0
Friction Slope Method= 1
Unsteady Friction Slope Method= 2
Unsteady Bridges Friction Slope Method= 1
Parabolic Critical Depth
Global Vel Dist=  1 , 1 , 1
Global Log Level= 0
CheckData=True
Encroach Param= -1, 0, 0, 0
BEGIN DESCRIPTION:
Multiple Run
END DESCRIPTION:

--- LINN BRANCH.f01 (steady flow) ---

Flow Title=Multiple
Number of Profiles=7
Profile Names=10-year,25-year,50-year,1pct_min,100-year,1pct_plu,500-year
River Rch & RM= LINN BRANCH,Reach-1,15386
     530     703     841     501     999    1993    1410
River Rch & RM= LINN BRANCH,Reach-1,14610
     726     975    1178     706    1409    2810    2019
River Rch & RM= LINN BRANCH,Reach-1,6747
     901    1221    1484     894    1784    3560    2584
Boundary for River Rch & Prof#=LINN BRANCH,Reach-1,1
Up Type=0
Dn Type=3
Dn Slope=0.005
Boundary for River Rch & Prof#=LINN BRANCH,Reach-1,2
Up Type=0
Dn Type=3
Dn Slope=0.005
Boundary for River Rch & Prof#=LINN BRANCH,Reach-1,3
Up Type=0
Dn Type=3
Dn Slope=0.005
Boundary for River Rch & Prof#=LINN BRANCH,Reach-1,4
Up Type=0
Dn Type=3
Dn Slope=0.005
Boundary for River Rch & Prof#=LINN BRANCH,Reach-1,5
Up Type=0
Dn Type=3
Dn Slope=0.005
Boundary for River Rch & Prof#=LINN BRANCH,Reach-1,6
Up Type=0
Dn Type=3
Dn Slope=0.005
Boundary for River Rch & Prof#=LINN BRANCH,Reach-1,7
Up Type=0
Dn Type=3
Dn Slope=0.005

--- LINN BRANCH.g01 (geometry) ---

Geom Title=Existing Conditions

River Reach=LINN BRANCH,Reach-1
Reach XY= 30
      2843277.50      7049161.50      2843165.33      7048373.76
      2843302.42      7048379.33      2843290.06      7048078.19
      2843448.54      7048154.05      2843356.57      7047935.15
      2843475.73      7047817.25      2843718.78      7047945.21
      2843740.68      7047690.74      2843954.38      7047756.95
      2844071.09      7047530.32      2844539.88      7047381.54
      2844540.99      7047008.26      2844640.13      7046884.33
      2844769.07      7047007.82      2844982.04      7046779.36
      2844922.43      7046525.42      2845115.32      7046440.33
      2845037.23      7045811.82      2845468.11      7045586.66
      2845638.78      7045124.49      2845987.26      7045122.65
      2846132.61      7044273.06      2846517.97      7044127.71
      2846898.82      7043553.05      2846436.84      7042833.04
      2846453.74      7042355.29      2846876.28      7042016.13
      2846762.48      7041398.66      2847353.21      7039710.68

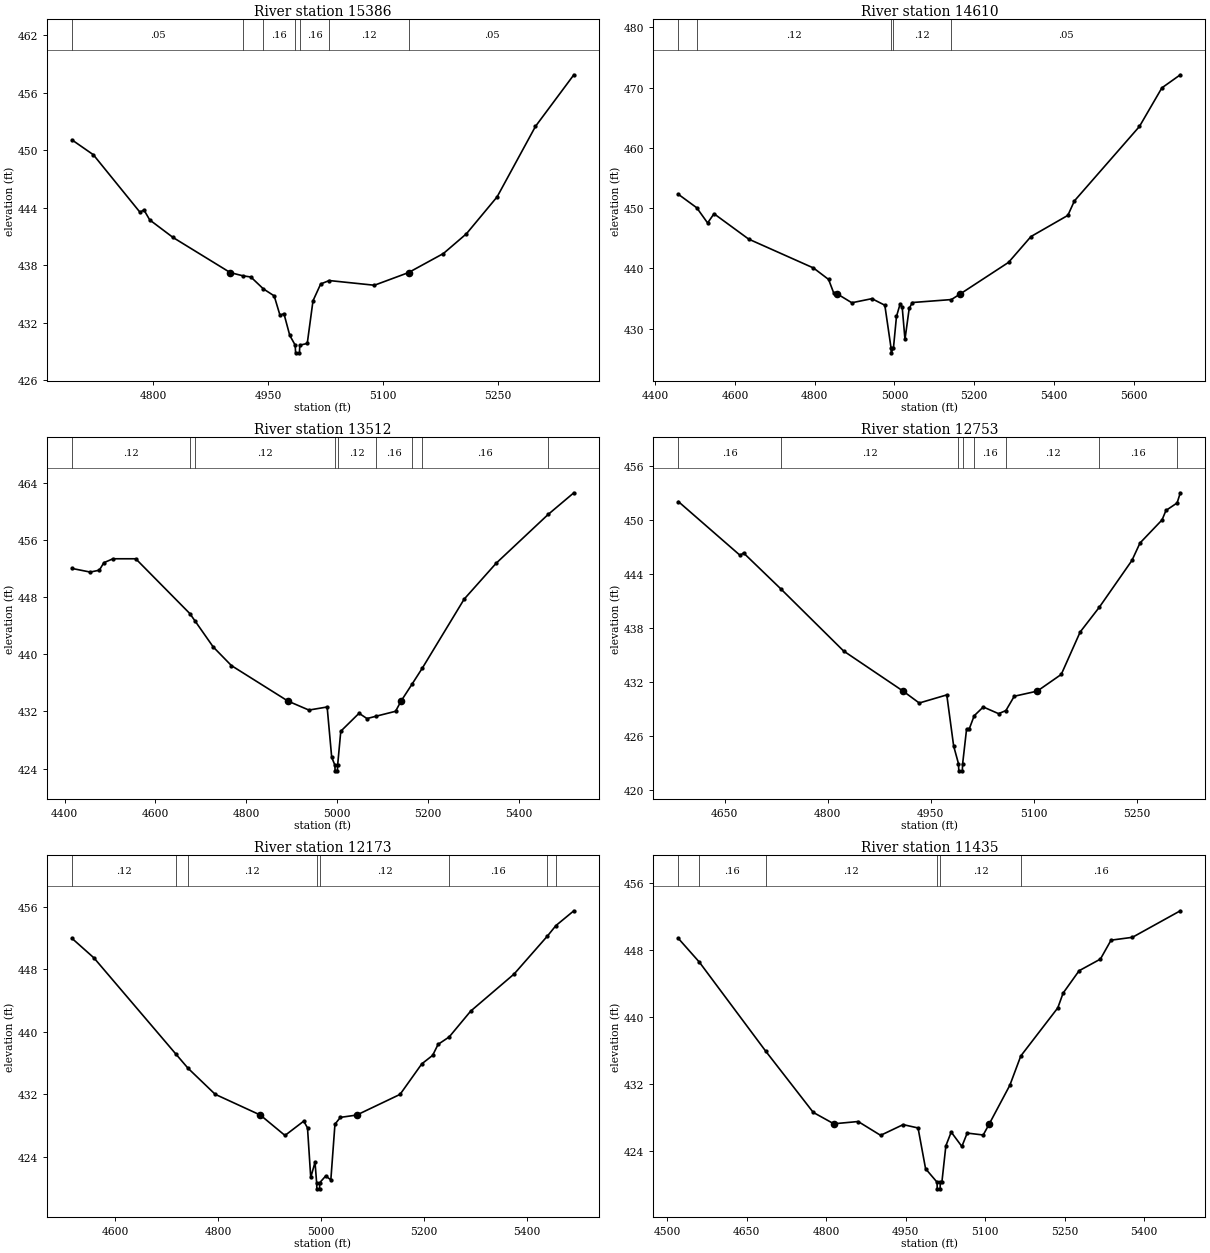
Type RM Length L Ch R = 1,15386,776,776,776
BEGIN DESCRIPTION:
LINN BRANCH 22.0
END DESCRIPTION:
XS GIS Cut Line= 3
      2843475.02      7048675.00      2843175.00      7048625.00
      2842824.96      7048625.00
#Sta/Elev= 30
  4694.3  451.06  4722.2  449.51  4783.0  443.51  4788.1  443.76  4795.7  442.71
  4826.1  440.88  4900.6  437.22  4917.3  436.88  4927.5  436.76  4943.8  435.52
  4957.9  434.79  4965.5  432.76  4970.6  432.94  4978.2  430.67  4985.3  429.65
  4985.8  428.85  4990.8  428.85  4991.3  429.65  5001.0  429.83  5008.5  434.28
  5018.5  436.03  5029.6  436.39  5088.5  435.90  5133.0  437.22  5133.9  437.26
  5178.5  439.21  5208.5  441.27  5248.5  445.12  5298.5  452.47  5348.5  457.85
#Mann=7,-1,0
  4694.3    0.05       0  4917.3    0.12       0  4943.8    0.16       0
  4985.3    0.07       0  4991.3    0.16       0  5029.6    0.12       0
  5133.9    0.05       0
Bank Sta=4900.6,5133
Exp/Cntr=0.3,0.1

Type RM Length L Ch R = 1,14610,1098,1098,1098
BEGIN DESCRIPTION:
LINN BRANCH 21.0
END DESCRIPTION:
XS GIS Cut Line= 3
      2843525.00      7048624.99      2843275.00      7048175.00
      2842574.98      7047924.99
#Sta/Elev= 30
  4458.4  452.28  4504.4  450.05  4531.6  447.53  4547.6  449.06  4634.6  444.85
  4797.0  440.06  4834.8  438.16  4847.3  435.98  4856.5  435.76  4893.1  434.29
  4943.4  434.97  4975.8  433.88  4991.4  426.78  4991.9  425.98  4997.4  426.78
  5005.0  432.01  5014.1  434.09  5019.4  433.52  5026.3  428.21  5036.9  433.35
  5044.9  434.33  5142.6  434.82  5165.0  435.76  5285.9  440.99  5342.2  445.28
  5434.6  448.79  5451.0  451.19  5614.0  463.54  5670.3  469.95  5716.5  472.12
#Mann=5,-1,0
  4458.4    0.05       0  4504.4    0.12       0  4991.4    0.07       0
  4997.4    0.12       0  5142.6    0.05       0
Bank Sta=4856.5,5165
Exp/Cntr=0.3,0.1

Type RM Length L Ch R = 1,13512,759,759,759
BEGIN DESCRIPTION:
LINN BRANCH 20.0
END DESCRIPTION:
XS GIS Cut Line= 3
      2843525.00      7048525.00      2843575.00      7047875.00
      2843525.00      7047424.99
#Sta/Elev= 30
  4416.2  451.99  4456.3  451.48  4476.4  451.74  4486.4  452.79  4506.5  453.34
  4556.6  453.34  4675.6  445.68  4687.7  444.59  4727.1  441.01  4767.2  438.40
  4891.8  433.43  4937.7  432.18  4977.9  432.61  4987.9  425.58  4994.9  424.48
  4995.4  423.68  5000.5  423.68  5001.0  424.48  5007.9  429.22  5048.1  431.73
  5065.6  430.99  5085.6  431.32  5128.5  432.01  5140.5  433.43  5164.8  435.81
  5187.5  438.06  5279.4  447.69  5349.8  452.71  5464.5  459.55  5520.9  462.57
#Mann=9,-1,0
  4416.2    0.12       0  4675.6    0.16       0  4687.7    0.12       0
  4994.9    0.07       0  5001.0    0.12       0  5085.6    0.16       0
  5164.8    0.12       0  5187.5    0.16       0  5464.5    0.12       0
Bank Sta=4891.8,5140.5
Exp/Cntr=0.3,0.1

Type RM Length L Ch R = 1,12753,580,580,580
BEGIN DESCRIPTION:
LINN BRANCH 19.0
END DESCRIPTION:
XS GIS Cut Line= 3
      2843925.00      7048175.04      2843947.41      7047752.46
      2843799.03      7047483.32
#Sta/Elev= 30
  4582.9  452.00  4672.7  446.04  4677.7  446.31  4731.6  442.35  4823.3  435.44
  4909.9  430.99  4933.4  429.67  4973.5  430.57  4983.5  424.90  4990.5  422.95
  4991.0  422.15  4996.1  422.15  4996.6  422.95  5002.3  426.78  5006.1  426.78
  5013.4  428.26  5026.6  429.23  5048.9  428.49  5059.5  428.83  5071.7  430.42
  5105.2  430.99  5140.1  432.84  5167.6  437.54  5195.5  440.29  5243.0  445.48
  5254.7  447.41  5286.8  449.97  5292.5  451.02  5308.7  451.85  5313.4  452.98
#Mann=8,-1,0
  4582.9    0.16       0  4731.6    0.12       0  4990.5    0.07       0
  4996.6    0.12       0  5013.4    0.16       0  5059.5    0.12       0
  5195.5    0.16       0  5308.7    0.12       0
Bank Sta=4909.9,5105.2
Exp/Cntr=0.3,0.1

Type RM Length L Ch R = 1,12173,738,738,738
BEGIN DESCRIPTION:
LINN BRANCH 18.0
END DESCRIPTION:
XS GIS Cut Line= 3
      2844575.01      7047925.01      2844275.00      7047525.00
      2843824.95      7047374.98
#Sta/Elev= 30
  4516.4  451.94  4559.1  449.44  4718.2  437.15  4741.6  435.35  4794.5  432.01
  4882.1  429.36  4930.0  426.75  4966.4  428.58  4973.7  427.72  4980.0  421.38
  4988.3  423.33  4991.4  420.73  4991.9  419.93  4997.1  419.93  4997.6  420.73
  5009.1  421.58  5019.0  421.07  5027.0  428.19  5037.5  429.06  5069.3  429.36
  5153.4  432.00  5195.6  435.90  5216.7  436.99  5227.2  438.39  5248.8  439.34
  5290.5  442.64  5374.8  447.38  5439.2  452.21  5456.0  453.57  5490.8  455.46
#Mann=8,-1,0
  4516.4    0.12       0  4718.2    0.16       0  4741.6    0.12       0
  4991.4    0.07       0  4997.6    0.12       0  5248.8    0.16       0
  5439.2    0.12       0  5456.0    0.16       0
Bank Sta=4882.1,5069.3
Exp/Cntr=0.3,0.1

Type RM Length L Ch R = 1,11435,692,692,692
BEGIN DESCRIPTION:
LINN BRANCH 17.0
END DESCRIPTION:
XS GIS Cut Line= 3
      2844875.00      7047475.00      2844525.00      7047125.00
      2844075.05      7047075.01
#Sta/Elev= 30
  4520.9  449.34  4560.4  446.52  4685.4  435.91  4775.5  428.57  4814.3  427.21
  4860.3  427.48  4902.7  425.83  4945.2  427.11  4973.4  426.71  4987.6  421.84
  5009.2  420.24  5009.7  419.44  5015.0  419.44  5015.5  420.24  5018.4  420.24
  5025.9  424.58  5036.0  426.22  5056.1  424.50  5066.2  426.10  5096.4  425.87
  5108.0  427.21  5146.7  431.81  5167.4  435.31  5237.2  441.05  5247.3  442.82
  5277.5  445.49  5317.7  446.88  5337.8  449.14  5378.1  449.48  5468.6  452.65
#Mann=6,-1,0
  4520.9    0.12       0  4560.4    0.16       0  4685.4    0.12       0
  5009.2    0.07       0  5015.5    0.12       0  5167.4    0.16       0
Bank Sta=4814.3,5108
Exp/Cntr=0.3,0.1

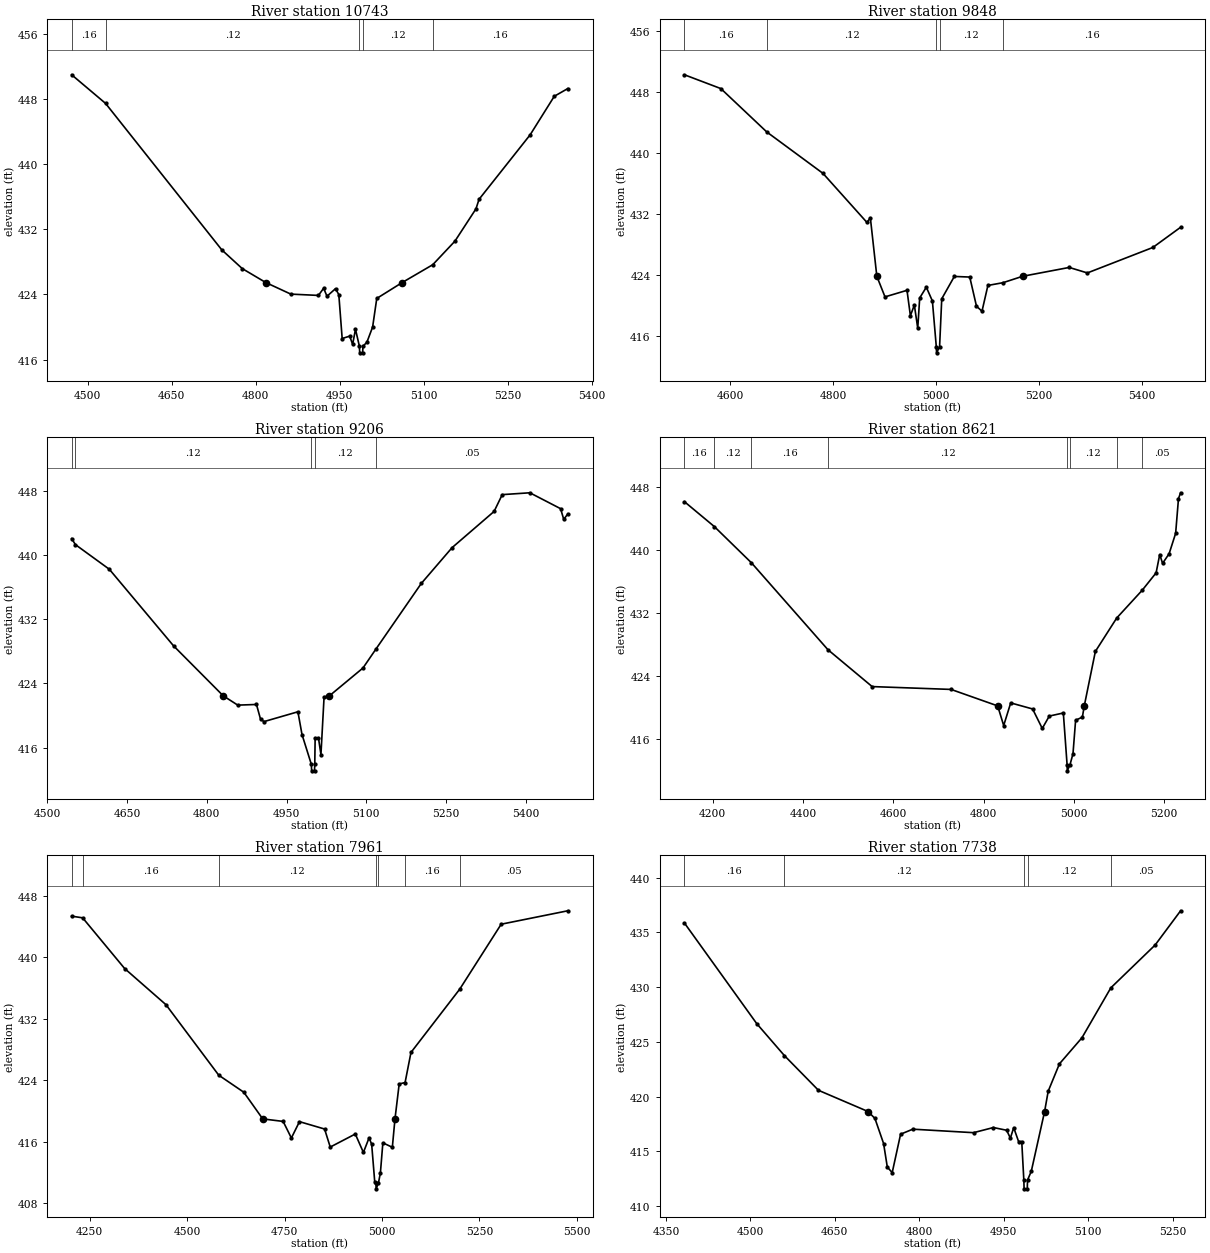
Type RM Length L Ch R = 1,10743,895,895,895
BEGIN DESCRIPTION:
LINN BRANCH 16.0
END DESCRIPTION:
XS GIS Cut Line= 3
      2845225.02      7047125.01      2844815.46      7046863.58
      2844424.97      7046774.99
#Sta/Elev= 30
  4471.3  450.97  4531.8  447.46  4739.5  429.47  4775.9  427.18  4818.1  425.46
  4862.8  424.04  4912.1  423.88  4921.4  424.76  4927.4  423.78  4942.6  424.71
  4948.5  423.98  4954.5  418.59  4967.9  418.88  4973.2  417.88  4978.3  419.72
  4985.3  417.63  4985.8  416.83  4991.1  416.83  4991.6  417.63  4998.7  418.14
  5008.9  420.00  5016.3  423.51  5061.7  425.46  5116.3  427.65  5155.9  430.54
  5193.5  434.51  5199.0  435.68  5290.3  443.60  5333.4  448.33  5357.6  449.28
#Mann=5,-1,0
  4471.3    0.16       0  4531.8    0.12       0  4985.3    0.07       0
  4991.6    0.12       0  5116.3    0.16       0
Bank Sta=4818.1,5061.7
Exp/Cntr=0.3,0.1

Type RM Length L Ch R = 1,9848,642,642,642
BEGIN DESCRIPTION:
LINN BRANCH 15.0
END DESCRIPTION:
XS GIS Cut Line= 3
      2845425.02      7046775.02      2845075.00      7046475.00
      2844604.65      7046293.11
#Sta/Elev= 30
  4510.7  450.20  4581.5  448.39  4670.9  442.70  4780.2  437.27  4865.8  430.83
  4872.4  431.45  4885.0  423.77  4900.9  421.07  4943.7  421.93  4950.3  418.60
  4958.0  420.00  4964.6  416.95  4968.4  420.93  4981.3  422.34  4993.1  420.53
  5000.7  414.53  5001.2  413.73  5007.1  414.53  5011.3  420.82  5035.8  423.75
  5065.8  423.67  5078.9  419.84  5089.6  419.19  5101.1  422.57  5130.4  422.93
  5168.6  423.77  5259.3  424.93  5294.6  424.21  5422.0  427.55  5476.0  430.20
#Mann=5,-1,0
  4510.7    0.16       0  4670.9    0.12       0  5000.7    0.07       0
  5007.1    0.12       0  5130.4    0.16       0
Bank Sta=4885,5168.6
Exp/Cntr=0.3,0.1

Type RM Length L Ch R = 1,9206,585,585,585
BEGIN DESCRIPTION:
LINN BRANCH 14.0
END DESCRIPTION:
XS GIS Cut Line= 3
      2845374.99      7046374.98      2845075.00      7046025.00
      2844674.96      7045774.98
#Sta/Elev= 30
  4546.1  442.03  4553.1  441.28  4616.9  438.21  4737.6  428.68  4831.0  422.46
  4858.3  421.30  4893.5  421.38  4901.1  419.56  4907.7  419.25  4971.4  420.47
  4979.1  417.64  4996.7  413.92  4997.2  413.12  5002.6  413.12  5003.1  413.92
  5003.8  417.23  5010.0  417.23  5014.7  415.15  5020.6  422.33  5030.7  422.46
  5093.7  425.92  5118.2  428.29  5203.4  436.45  5261.2  440.90  5340.2  445.41
  5355.5  447.50  5407.4  447.73  5465.2  445.75  5471.1  444.42  5478.8  445.10
#Mann=5,-1,0
  4546.1    0.16       0  4553.1    0.12       0  4996.7    0.07       0
  5003.1    0.12       0  5118.2    0.05       0
Bank Sta=4831,5030.7
Exp/Cntr=0.3,0.1

Type RM Length L Ch R = 1,8621,660,660,660
BEGIN DESCRIPTION:
LINN BRANCH 13.0
END DESCRIPTION:
XS GIS Cut Line= 3
      2845925.01      7046175.01      2845175.00      7045725.00
      2845035.16      7045548.80
#Sta/Elev= 30
  4137.2  446.09  4203.5  442.93  4285.8  438.33  4455.2  427.31  4553.2  422.63
  4728.1  422.27  4831.4  420.18  4844.7  417.69  4860.3  420.56  4908.8  419.79
  4930.2  417.32  4945.8  418.89  4976.9  419.28  4985.2  412.74  4985.7  411.94
  4991.8  412.74  4998.3  414.11  5004.1  418.36  5019.1  418.76  5023.3  420.18
  5047.9  427.09  5095.2  431.33  5151.8  434.86  5182.5  437.06  5190.5  439.38
  5196.9  438.27  5211.3  439.48  5225.8  442.08  5232.1  446.49  5236.8  447.22
#Mann=8,-1,0
  4137.2    0.16       0  4203.5    0.12       0  4285.8    0.16       0
  4455.2    0.12       0  4985.2    0.07       0  4991.8    0.12       0
  5095.2    0.16       0  5151.8    0.05       0
Bank Sta=4831.4,5023.3
Exp/Cntr=0.3,0.1

Type RM Length L Ch R = 1,7961,223,223,223
BEGIN DESCRIPTION:
LINN BRANCH 12.0
END DESCRIPTION:
XS GIS Cut Line= 3
      2846024.99      7046024.99      2845525.00      7045375.00
      2845075.02      7045325.00
#Sta/Elev= 30
  4203.9  445.36  4232.1  445.14  4339.8  438.54  4445.8  433.83  4581.2  424.65
  4645.5  422.43  4694.0  418.96  4746.4  418.63  4767.5  416.47  4788.3  418.60
  4852.7  417.64  4867.2  415.29  4931.5  416.99  4952.3  414.59  4966.9  416.50
  4973.5  415.65  4981.4  410.73  4984.4  410.65  4984.9  409.85  4991.0  410.65
  4995.9  411.93  5002.2  415.84  5026.5  415.26  5033.3  418.96  5044.1  423.51
  5059.2  423.69  5074.3  427.61  5199.5  435.86  5305.7  444.31  5476.7  446.06
#Mann=7,-1,0
  4203.9    0.12       0  4232.1    0.16       0  4581.2    0.12       0
  4984.4    0.07       0  4991.0    0.12       0  5059.2    0.16       0
  5199.5    0.05       0
Bank Sta=4694,5033.3
Exp/Cntr=0.3,0.1

Type RM Length L Ch R = 1,7738,490,490,490
BEGIN DESCRIPTION:
Mapping XS dc59699b
END DESCRIPTION:
XS GIS Cut Line= 3
      2846160.94      7045526.77      2845654.00      7045210.80
      2845369.65      7045210.80
#Sta/Elev= 30
  4382.7  435.86  4511.2  426.67  4560.2  423.76  4620.9  420.58  4709.1  418.64
  4721.2  418.01  4736.6  415.72  4743.2  413.57  4751.9  413.06  4766.8  416.57
  4788.5  417.03  4896.4  416.71  4931.7  417.18  4955.3  416.93  4961.9  416.21
  4967.8  417.17  4976.5  415.90  4982.1  415.90  4985.8  412.38  4986.3  411.58
  4991.9  411.58  4992.4  412.38  4999.1  413.19  5022.7  418.64  5029.1  420.50
  5049.1  423.00  5089.1  425.38  5140.4  429.94  5219.1  433.85  5264.4  436.98
#Mann=5,-1,0
  4382.7    0.16       0  4560.2    0.12       0  4985.8    0.07       0
  4992.4    0.12       0  5140.4    0.05       0
Bank Sta=4709.1,5022.7
Exp/Cntr=0.3,0.1

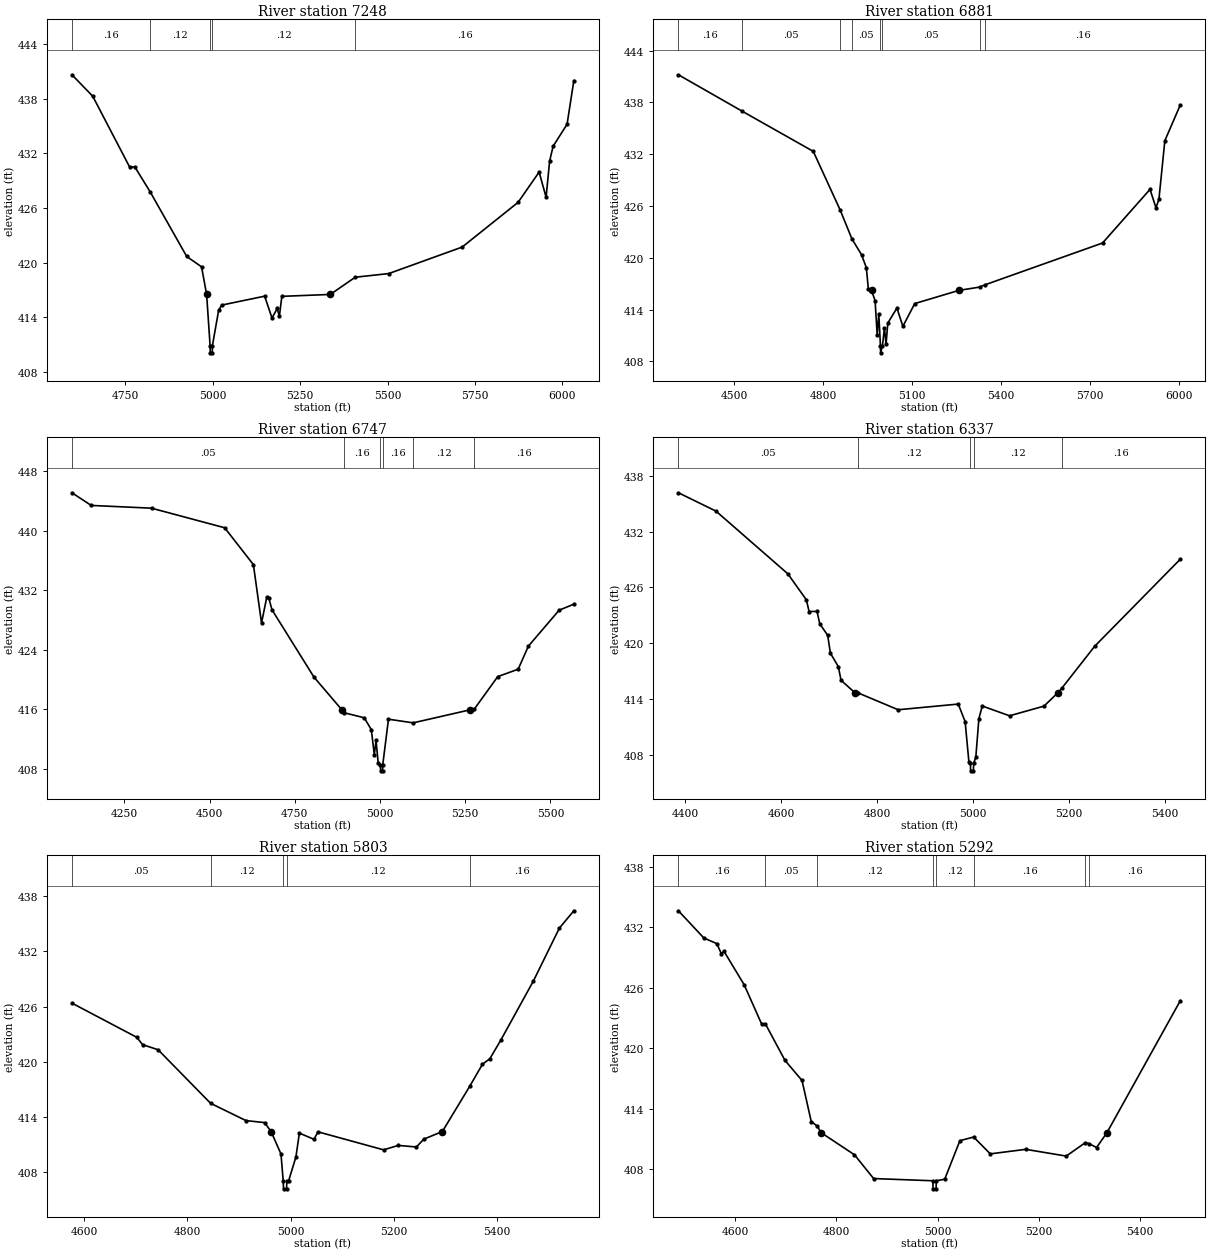
Type RM Length L Ch R = 1,7248,367,367,367
BEGIN DESCRIPTION:
Mapping XS 53217728
END DESCRIPTION:
XS GIS Cut Line= 4
      2846261.66      7045412.21      2845990.81      7045117.05
      2845650.53      7044887.88      2845025.56      7044877.47
#Sta/Elev= 30
  4597.1  440.62  4656.5  438.27  4762.6  430.46  4776.8  430.52  4821.3  427.74
  4925.4  420.68  4967.9  419.54  4982.4  416.51  4992.3  410.90  4992.8  410.10
  4998.5  410.10  4999.0  410.90  5016.8  414.77  5025.5  415.34  5148.4  416.32
  5169.4  413.92  5184.4  414.97  5190.5  414.11  5197.6  416.30  5336.2  416.51
  5407.6  418.40  5503.5  418.80  5713.5  421.71  5873.5  426.62  5933.6  429.94
  5953.6  427.18  5963.6  431.13  5973.6  432.77  6013.6  435.19  6033.0  439.98
#Mann=5,-1,0
  4597.1    0.16       0  4821.3    0.12       0  4992.3    0.07       0
  4999.0    0.12       0  5407.6    0.16       0
Bank Sta=4982.4,5336.2
Exp/Cntr=0.3,0.1

Type RM Length L Ch R = 1,6881,134,134,134
BEGIN DESCRIPTION:
Mapping XS 76f4c120
END DESCRIPTION:
XS GIS Cut Line= 6
      2846279.00      7045408.70      2846192.20      7044964.27
      2846094.97      7044814.96      2846015.11      7044783.71
      2845428.31      7044835.80      2845042.88      7044821.91
#Sta/Elev= 30
  4311.4  441.21  4527.3  436.97  4766.2  432.33  4856.8  425.54  4896.6  422.18
  4928.8  420.36  4945.1  418.85  4951.9  416.36  4962.6  416.22  4974.6  415.03
  4981.7  411.07  4987.1  413.49  4992.7  409.78  4993.2  408.98  4999.4  409.78
  5006.2  411.88  5011.5  409.95  5017.5  412.43  5048.3  414.17  5068.3  412.05
  5108.3  414.69  5257.5  416.22  5326.9  416.60  5344.8  416.86  5741.6  421.71
  5901.7  427.93  5921.7  425.80  5931.7  426.76  5951.7  433.57  6003.9  437.72
#Mann=8,-1,0
  4311.4    0.16       0  4527.3    0.05       0  4856.8    0.12       0
  4896.6    0.05       0  4992.7    0.04       0  4999.4    0.05       0
  5326.9    0.12       0  5344.8    0.16       0
Bank Sta=4962.6,5257.5
Exp/Cntr=0.3,0.1

Type RM Length L Ch R = 1,6747,410,410,410
BEGIN DESCRIPTION:
Mapping XS b28e867b
END DESCRIPTION:
XS GIS Cut Line= 6
      2846341.50      7045391.33      2846292.89      7044863.58
      2846216.50      7044742.05      2846035.95      7044672.60
      2845942.20      7044662.19      2845431.80      7044679.55
#Sta/Elev= 30
  4096.5  445.09  4153.1  443.39  4329.9  443.02  4544.3  440.39  4628.6  435.44
  4652.5  427.59  4667.8  431.04  4673.7  430.95  4683.1  429.37  4806.4  420.31
  4888.2  415.92  4894.8  415.53  4953.8  414.85  4974.5  413.25  4983.3  409.88
  4988.3  411.80  4994.6  408.79  5001.3  408.52  5001.8  407.72  5007.5  407.72
  5008.0  408.52  5024.8  414.66  5097.3  414.17  5264.0  415.92  5276.9  416.04
  5345.2  420.38  5405.2  421.38  5435.2  424.48  5525.3  429.31  5568.5  430.12
#Mann=6,-1,0
  4096.5    0.05       0  4894.8    0.16       0  5001.3    0.07       0
  5008.0    0.16       0  5097.3    0.12       0  5276.9    0.16       0
Bank Sta=4888.2,5264
Exp/Cntr=0.3,0.1

Type RM Length L Ch R = 1,6337,534,534,534
BEGIN DESCRIPTION:
Mapping XS 59224e15
END DESCRIPTION:
XS GIS Cut Line= 3
      2846414.40      7044832.30      2846154.00      7044325.38
      2845785.98      7044023.32
#Sta/Elev= 30
  4385.8  436.17  4464.1  434.20  4613.8  427.47  4652.5  424.67  4658.1  423.42
  4674.7  423.43  4680.3  422.11  4696.9  420.86  4702.5  418.95  4719.1  417.50
  4724.7  416.03  4753.5  414.71  4759.3  414.70  4843.7  412.87  4969.0  413.48
  4983.3  411.60  4991.2  407.27  4994.3  407.11  4994.8  406.31  5000.6  406.31
  5001.1  407.11  5005.6  407.78  5012.0  411.92  5019.1  413.27  5075.9  412.22
  5147.7  413.26  5176.9  414.71  5184.8  415.18  5253.2  419.68  5431.8  429.04
#Mann=5,-1,0
  4385.8    0.05       0  4759.3    0.12       0  4994.3    0.07       0
  5001.1    0.12       0  5184.8    0.16       0
Bank Sta=4753.5,5176.9
Exp/Cntr=0.3,0.1

Type RM Length L Ch R = 1,5803,511,511,511
BEGIN DESCRIPTION:
LINN BRANCH 8.0
END DESCRIPTION:
XS GIS Cut Line= 3
      2846591.51      7044547.64      2846490.81      7044144.83
      2846074.99      7043774.99
#Sta/Elev= 30
  4576.6  426.37  4702.2  422.65  4713.3  421.86  4743.4  421.30  4845.0  415.48
  4913.5  413.60  4949.6  413.38  4962.1  412.41  4981.3  409.97  4985.7  406.98
  4986.2  406.18  4992.1  406.18  4992.6  406.98  4996.0  407.04  5010.2  409.64
  5016.9  412.24  5045.3  411.56  5052.8  412.38  5179.9  410.42  5208.4  410.90
  5243.5  410.73  5257.7  411.58  5293.7  412.41  5346.5  417.31  5371.4  419.73
  5385.6  420.32  5406.6  422.32  5470.1  428.79  5520.3  434.53  5548.3  436.41
#Mann=5,-1,0
  4576.6    0.05       0  4845.0    0.12       0  4985.7    0.07       0
  4992.6    0.12       0  5346.5    0.16       0
Bank Sta=4962.1,5293.7
Exp/Cntr=0.3,0.1

Type RM Length L Ch R = 1,5292,163,163,163
BEGIN DESCRIPTION:
Mapping XS cdbbfb6a
END DESCRIPTION:
XS GIS Cut Line= 4
      2847178.27      7043853.15      2846844.97      7043762.88
      2846726.92      7043748.99      2846199.60      7043748.99
#Sta/Elev= 30
  4488.0  433.65  4538.2  430.95  4563.9  430.39  4572.8  429.39  4578.0  429.63
  4617.9  426.31  4652.5  422.40  4660.0  422.41  4698.6  418.80  4732.2  416.81
  4750.4  412.74  4761.9  412.30  4770.0  411.63  4835.8  409.44  4873.6  407.08
  4990.6  406.86  4991.1  406.06  4997.0  406.06  4997.5  406.86  5014.1  407.02
  5044.1  410.84  5071.2  411.20  5104.1  409.53  5174.1  409.98  5254.1  409.31
  5292.1  410.65  5298.8  410.55  5314.1  410.16  5334.5  411.63  5479.5  424.73
#Mann=8,-1,0
  4488.0    0.16       0  4660.0    0.05       0  4761.9    0.12       0
  4990.6    0.07       0  4997.5    0.12       0  5071.2    0.16       0
  5292.1    0.12       0  5298.8    0.16       0
Bank Sta=4770,5334.5
Exp/Cntr=0.3,0.1

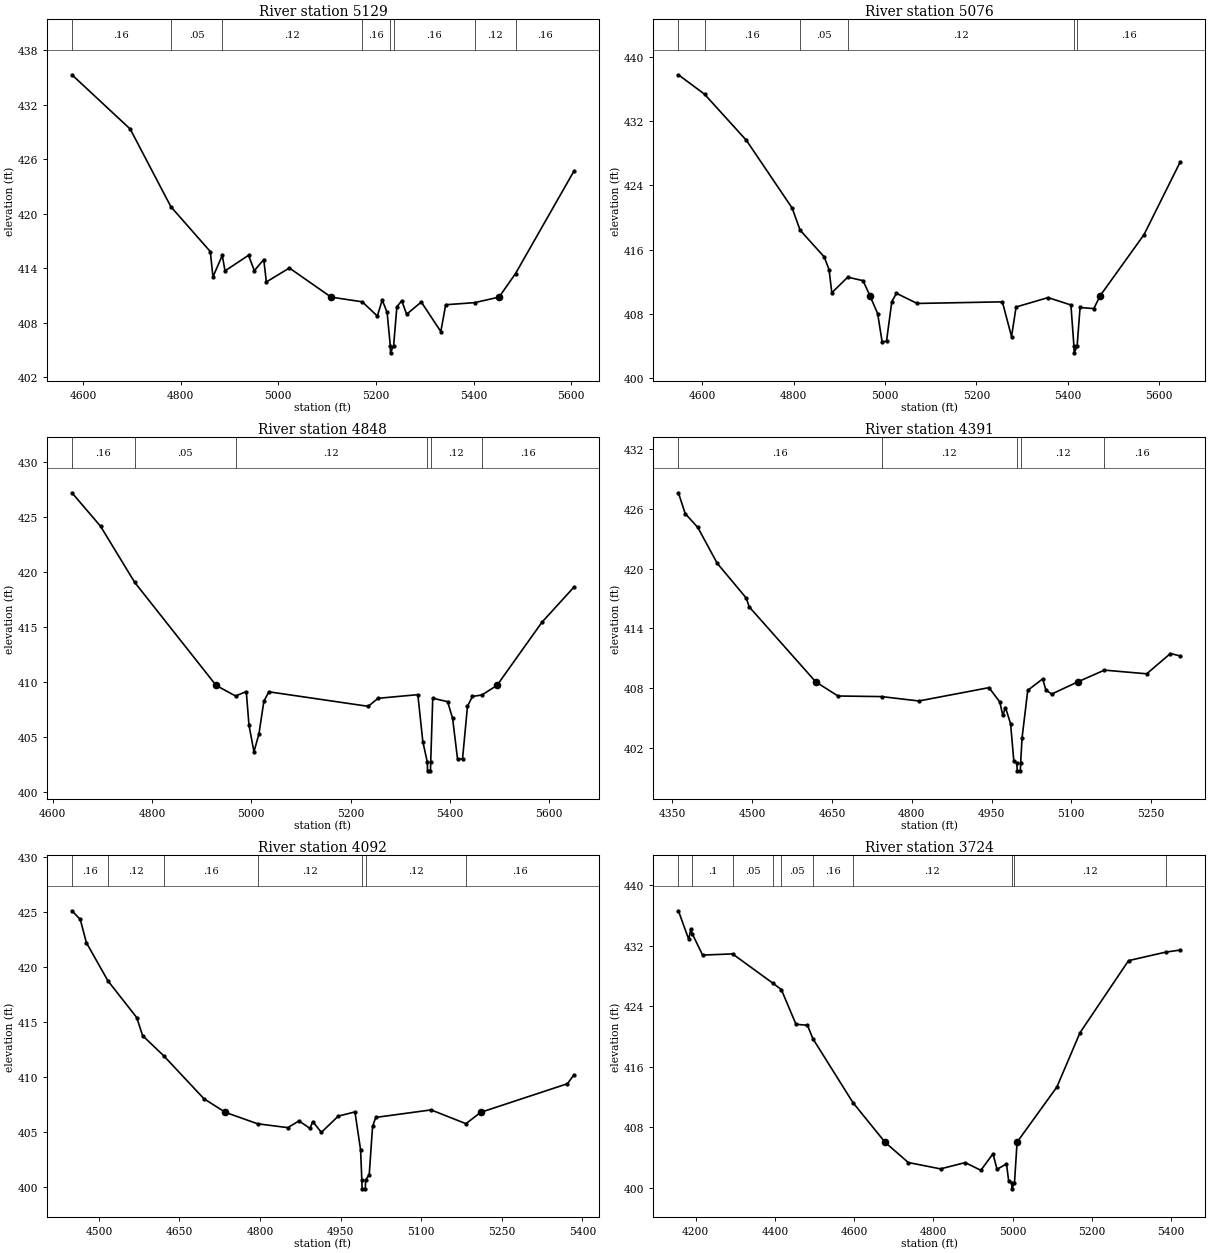
Type RM Length L Ch R = 1,5129,53,53,53
BEGIN DESCRIPTION:
LINN BRANCH 7.0
END DESCRIPTION:
XS GIS Cut Line= 3
      2847202.57      7043832.31      2846813.72      7043683.02
      2846202.58      7043689.96
#Sta/Elev= 30
  4577.5  435.32  4696.8  429.34  4780.1  420.78  4860.8  415.84  4866.2  413.05
  4885.3  415.42  4890.9  413.71  4939.1  415.43  4950.9  413.73  4970.2  414.96
  4975.6  412.49  5022.7  414.03  5108.1  410.82  5172.1  410.30  5202.8  408.73
  5212.8  410.50  5222.8  409.14  5229.3  405.48  5229.8  404.68  5236.2  405.48
  5242.8  409.76  5252.8  410.42  5262.8  408.93  5292.8  410.28  5332.8  407.02
  5342.8  409.98  5401.8  410.21  5452.0  410.82  5485.8  413.42  5605.2  424.69
#Mann=8,-1,0
  4577.5    0.16       0  4780.1    0.05       0  4885.3    0.12       0
  5172.1    0.16       0  5229.3    0.07       0  5236.2    0.16       0
  5401.8    0.12       0  5485.8    0.16       0
Bank Sta=5108.1,5452
Exp/Cntr=0.3,0.1

Type RM Length L Ch R = 1,5076,228,228,228
BEGIN DESCRIPTION:
Mapping XS efd6b5c9
END DESCRIPTION:
XS GIS Cut Line= 4
      2847265.11      7043794.13      2846841.50      7043641.35
      2846667.89      7043613.58      2846195.64      7043617.05
#Sta/Elev= 30
  4547.8  437.76  4605.1  435.34  4696.7  429.60  4796.8  421.18  4814.0  418.45
  4866.8  415.12  4877.5  413.53  4883.5  410.66  4918.4  412.60  4951.9  412.16
  4966.7  410.31  4983.8  408.08  4993.6  404.56  5003.2  404.63  5014.8  409.56
  5025.0  410.59  5070.2  409.33  5256.8  409.53  5276.8  405.21  5286.8  408.89
  5356.8  410.06  5406.8  409.14  5413.4  403.99  5413.9  403.19  5420.3  403.99
  5426.8  408.83  5456.8  408.69  5471.0  410.31  5566.8  417.89  5646.2  426.95
#Mann=6,-1,0
  4547.8    0.05       0  4605.1    0.16       0  4814.0    0.05       0
  4918.4    0.12       0  5413.4    0.07       0  5420.3    0.16       0
Bank Sta=4966.7,5471
Exp/Cntr=0.3,0.1

Type RM Length L Ch R = 1,4848,457,457,457
BEGIN DESCRIPTION:
Mapping XS 6128f8f5
END DESCRIPTION:
XS GIS Cut Line= 3
      2847240.84      7043537.19      2846900.53      7043450.38
      2846240.77      7043467.74
#Sta/Elev= 30
  4638.6  427.21  4696.2  424.17  4764.9  419.08  4929.1  409.71  4968.2  408.75
  4989.8  409.15  4995.3  406.09  5005.3  403.68  5015.3  405.30  5025.3  408.28
  5035.4  409.13  5235.4  407.81  5255.4  408.54  5335.5  408.87  5345.5  404.61
  5354.5  402.75  5355.0  401.95  5360.9  401.95  5361.4  402.75  5365.5  408.55
  5395.5  408.23  5405.5  406.71  5415.5  403.02  5425.5  403.03  5435.5  407.82
  5445.5  408.71  5464.5  408.84  5494.9  409.71  5585.5  415.45  5649.8  418.63
#Mann=6,-1,0
  4638.6    0.16       0  4764.9    0.05       0  4968.2    0.12       0
  5354.5    0.07       0  5361.4    0.12       0  5464.5    0.16       0
Bank Sta=4929.1,5494.9
Exp/Cntr=0.3,0.1

Type RM Length L Ch R = 1,4391,299,299,299
BEGIN DESCRIPTION:
LINN BRANCH 6.0
END DESCRIPTION:
XS GIS Cut Line= 3
      2847260.84      7043232.40      2846638.22      7043126.48
      2846358.35      7043265.13
#Sta/Elev= 30
  4361.2  427.62  4373.9  425.53  4397.6  424.14  4434.1  420.54  4488.8  417.04
  4494.3  416.16  4619.5  408.62  4661.3  407.20  4743.4  407.14  4813.4  406.70
  4945.3  408.04  4965.6  406.60  4971.2  405.27  4976.3  406.04  4985.9  404.41
  4991.9  400.71  4997.8  400.48  4998.3  399.68  5004.3  399.68  5004.8  400.48
  5007.5  403.01  5018.2  407.77  5046.2  408.92  5052.2  407.82  5063.0  407.39
  5112.2  408.62  5162.4  409.80  5241.9  409.43  5286.5  411.47  5305.1  411.22
#Mann=5,-1,0
  4361.2    0.16       0  4743.4    0.12       0  4997.8    0.07       0
  5004.8    0.12       0  5162.4    0.16       0
Bank Sta=4619.5,5112.2
Exp/Cntr=0.3,0.1

Type RM Length L Ch R = 1,4092,368,368,368
BEGIN DESCRIPTION:
Mapping XS 13f85451
END DESCRIPTION:
XS GIS Cut Line= 3
      2847100.72      7042754.43      2846578.80      7042906.87
      2846366.94      7043235.00
#Sta/Elev= 30
  4449.8  425.07  4465.3  424.28  4476.6  422.18  4516.7  418.71  4570.4  415.37
  4581.3  413.73  4620.6  411.90  4695.4  408.00  4735.3  406.76  4795.4  405.72
  4851.6  405.37  4872.5  405.98  4892.9  405.30  4898.1  405.92  4914.1  404.94
  4945.4  406.41  4976.6  406.80  4987.1  403.35  4989.4  400.61  4989.9  399.81
  4995.9  399.81  4996.4  400.61  5003.2  401.10  5009.4  405.49  5015.4  406.30
  5118.3  406.98  5183.2  405.73  5210.7  406.76  5372.2  409.36  5384.1  410.16
#Mann=7,-1,0
  4449.8    0.16       0  4516.7    0.12       0  4620.6    0.16       0
  4795.4    0.12       0  4989.4    0.07       0  4996.4    0.12       0
  5183.2    0.16       0
Bank Sta=4735.3,5210.7
Exp/Cntr=0.3,0.1

Type RM Length L Ch R = 1,3724,126,126,126
BEGIN DESCRIPTION:
LINN BRANCH 5.0
END DESCRIPTION:
XS GIS Cut Line= 3
      2847274.99      7042525.00      2846452.20      7042682.10
      2846025.00      7042725.00
#Sta/Elev= 30
  4156.1  436.64  4182.1  432.86  4187.2  434.19  4191.5  433.55  4217.2  430.78
  4292.8  430.94  4394.1  427.08  4415.9  426.22  4452.9  421.63  4481.9  421.50
  4495.3  419.75  4596.6  411.28  4677.9  406.02  4736.4  403.35  4817.7  402.51
  4880.0  403.34  4919.6  402.32  4950.2  404.51  4960.4  402.45  4984.2  403.17
  4989.8  400.93  4997.5  400.67  4998.0  399.87  5004.5  400.67  5011.0  406.04
  5111.5  413.34  5169.9  420.52  5292.4  430.05  5386.0  431.17  5423.1  431.45
#Mann=10,-1,0
  4156.1    0.05       0  4191.5     0.1       0  4292.8    0.05       0
  4394.1    0.08       0  4415.9    0.05       0  4495.3    0.16       0
  4596.6    0.12       0  4997.5    0.07       0  5004.5    0.12       0
  5386.0    0.05       0
Bank Sta=4677.9,5011
Exp/Cntr=0.3,0.1

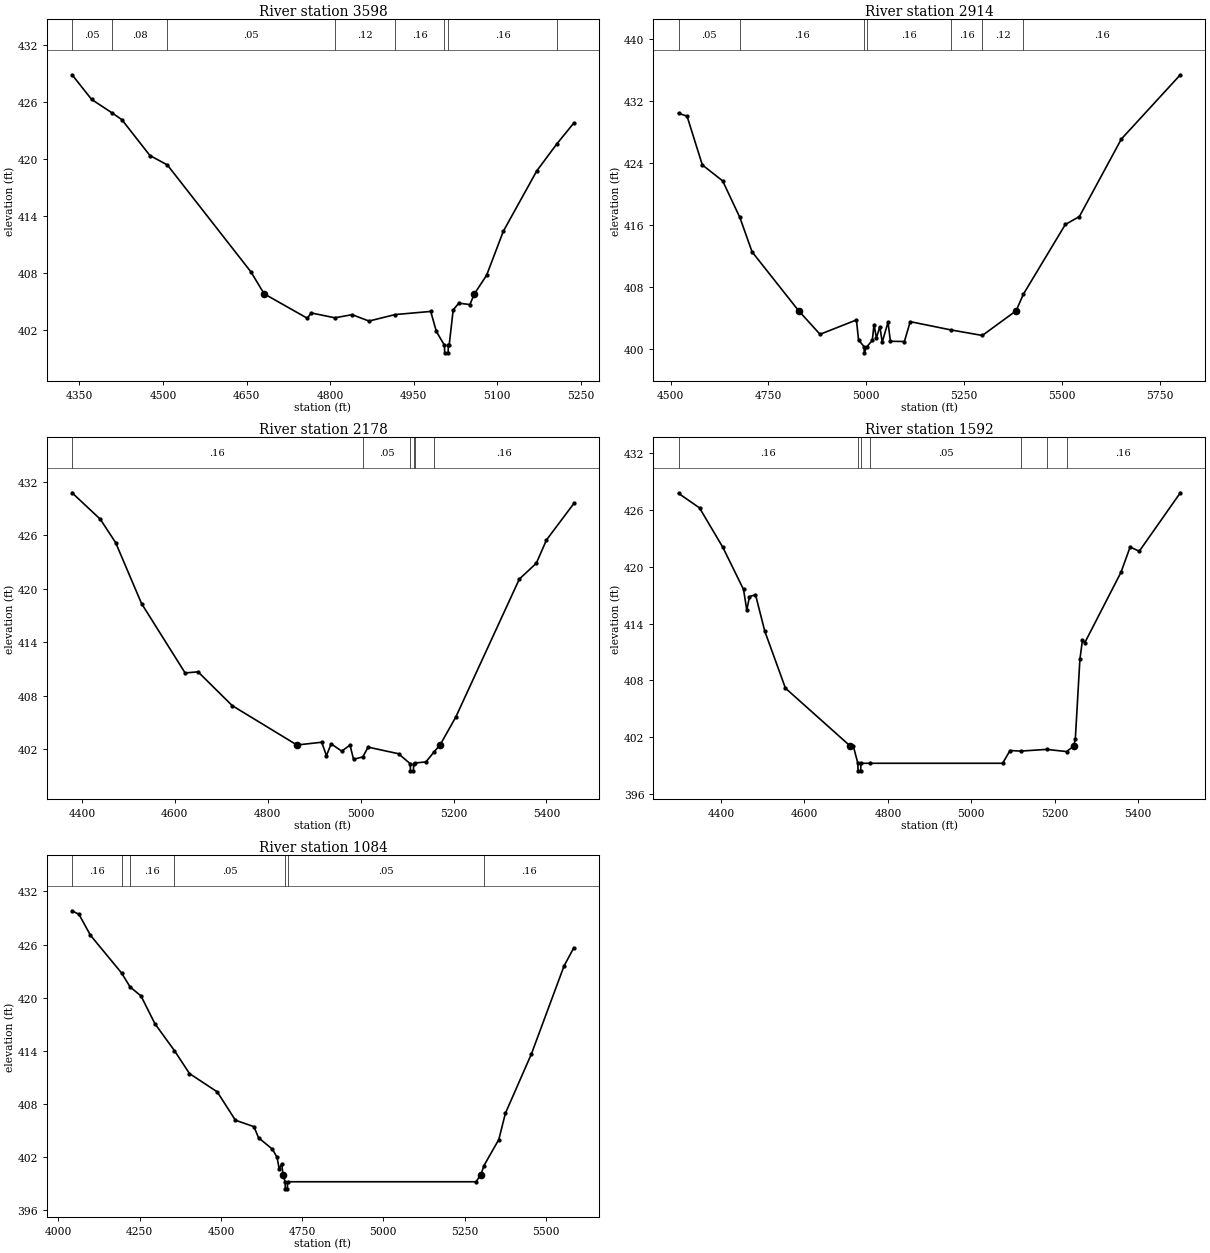
Type RM Length L Ch R = 1,3598,684,684,684
BEGIN DESCRIPTION:
Mapping XS d1607937
END DESCRIPTION:
XS GIS Cut Line= 3
      2847113.58      7042475.42      2846444.45      7042560.67
      2846218.52      7042568.37
#Sta/Elev= 30
  4336.9  428.86  4372.0  426.27  4407.8  424.89  4426.2  424.15  4476.6  420.38
  4507.9  419.39  4658.1  408.14  4681.6  405.85  4758.9  403.29  4766.3  403.84
  4808.4  403.33  4839.5  403.66  4869.8  402.99  4916.8  403.67  4980.6  404.00
  4990.7  401.90  5005.2  400.45  5005.7  399.65  5011.8  399.65  5012.3  400.45
  5013.7  400.45  5020.9  404.15  5030.9  404.87  5050.9  404.72  5059.0  405.85
  5080.9  407.80  5110.9  412.42  5171.0  418.77  5207.1  421.61  5237.5  423.80
#Mann=8,-1,0
  4336.9    0.05       0  4407.8    0.08       0  4507.9    0.05       0
  4808.4    0.12       0  4916.8    0.16       0  5005.2    0.07       0
  5012.3    0.16       0  5207.1    0.08       0
Bank Sta=4681.6,5059
Exp/Cntr=0.3,0.1

Type RM Length L Ch R = 1,2914,736,736,736
BEGIN DESCRIPTION:
LINN BRANCH 4.0
END DESCRIPTION:
XS GIS Cut Line= 3
      2847124.96      7042374.98      2846675.00      7042175.00
      2846224.98      7041524.97
#Sta/Elev= 30
  4520.1  430.42  4541.9  430.04  4580.9  423.76  4632.9  421.70  4676.9  416.98
  4708.1  412.55  4827.3  404.95  4881.9  401.92  4974.9  403.77  4980.4  401.19
  4994.4  400.33  4995.0  399.53  5001.8  400.33  5015.5  401.13  5019.9  403.17
  5026.0  401.44  5034.8  402.92  5040.9  400.91  5055.7  403.48  5061.8  401.02
  5097.6  400.99  5112.5  403.55  5216.0  402.49  5296.9  401.77  5383.2  404.95
  5401.6  407.07  5509.1  416.08  5545.0  417.10  5652.4  427.10  5803.1  435.38
#Mann=7,-1,0
  4520.1    0.05       0  4676.9    0.16       0  4994.4    0.07       0
  5001.8    0.16       0  5216.0    0.16       0  5296.9    0.12       0
  5401.6    0.16       0
Bank Sta=4827.3,5383.2
Exp/Cntr=0.3,0.1

Type RM Length L Ch R = 1,2178,586,586,586
BEGIN DESCRIPTION:
LINN BRANCH 3.0
END DESCRIPTION:
XS GIS Cut Line= 3
      2847375.02      7041875.00      2846775.00      7041775.00
      2846374.99      7041525.00
#Sta/Elev= 30
  4379.0  430.76  4439.8  427.79  4472.8  425.16  4528.6  418.32  4622.3  410.54
  4650.2  410.66  4723.7  406.87  4863.0  402.45  4916.3  402.76  4926.5  401.25
  4936.6  402.58  4959.4  401.76  4977.2  402.44  4984.8  400.85  5004.7  401.11
  5016.2  402.21  5081.6  401.47  5106.8  400.35  5107.4  399.55  5113.7  399.55
  5114.2  400.35  5116.7  400.43  5140.6  400.55  5158.8  401.72  5171.0  402.45
  5204.9  405.59  5341.7  421.08  5378.2  422.85  5400.0  425.46  5459.0  429.56
#Mann=6,-1,0
  4379.0    0.16       0  5004.7    0.05       0  5106.8    0.07       0
  5114.2    0.05       0  5116.7    0.07       0  5158.8    0.16       0
Bank Sta=4863,5171
Exp/Cntr=0.3,0.1

Type RM Length L Ch R = 1,1592,508,508,508
BEGIN DESCRIPTION:
LINN BRANCH 2.0
END DESCRIPTION:
XS GIS Cut Line= 3
      2847425.02      7041675.01      2846875.00      7041225.00
      2846425.00      7041425.00
#Sta/Elev= 30
  4298.0  427.78  4348.3  426.24  4404.3  422.06  4453.8  417.61  4461.7  415.43
  4468.1  416.84  4482.5  417.06  4504.8  413.19  4554.3  407.16  4710.0  401.02
  4717.2  401.01  4727.9  399.21  4728.4  398.41  4734.7  398.41  4735.3  399.21
  4758.0  399.21  5075.0  399.21  5092.8  400.56  5118.6  400.50  5180.6  400.68
  5228.2  400.45  5245.5  401.02  5249.4  401.83  5260.3  410.21  5266.5  412.26
  5272.0  411.97  5358.8  419.42  5380.7  422.10  5402.6  421.65  5501.1  427.84
#Mann=7,-1,0
  4298.0    0.16       0  4727.9    0.03       0  4735.3    0.16       0
  4758.0    0.05       0  5118.6    0.16       0  5180.6    0.12       0
  5228.2    0.16       0
Bank Sta=4710,5245.5
Exp/Cntr=0.3,0.1

Type RM Length L Ch R = 1,1084,0,0,0
BEGIN DESCRIPTION:
LINN BRANCH 1.0
END DESCRIPTION:
XS GIS Cut Line= 3
      2847675.01      7041475.01      2847025.00      7040725.00
      2846474.95      7040775.00
#Sta/Elev= 30
  4041.8  429.81  4063.2  429.40  4098.3  427.05  4194.3  422.78  4220.4  421.21
  4254.1  420.19  4296.8  417.06  4356.9  414.02  4403.2  411.43  4488.7  409.36
  4544.7  406.16  4601.7  405.43  4615.9  404.18  4658.7  402.88  4672.9  401.96
  4679.5  400.66  4687.2  401.24  4691.2  400.01  4697.7  399.21  4698.3  398.41
  4704.6  398.41  4705.2  399.21  5285.3  399.21  5300.5  400.01  5309.9  401.04
  5355.6  403.98  5375.7  406.93  5456.0  413.65  5556.4  423.58  5586.6  425.64
#Mann=7,-1,0
  4041.8    0.16       0  4194.3    0.05       0  4220.4    0.16       0
  4356.9    0.05       0  4697.7   0.033       0  4705.2    0.05       0
  5309.9    0.16       0
Bank Sta=4691.2,5300.5
Exp/Cntr=0.3,0.1

Chan Stop Cuts=-1