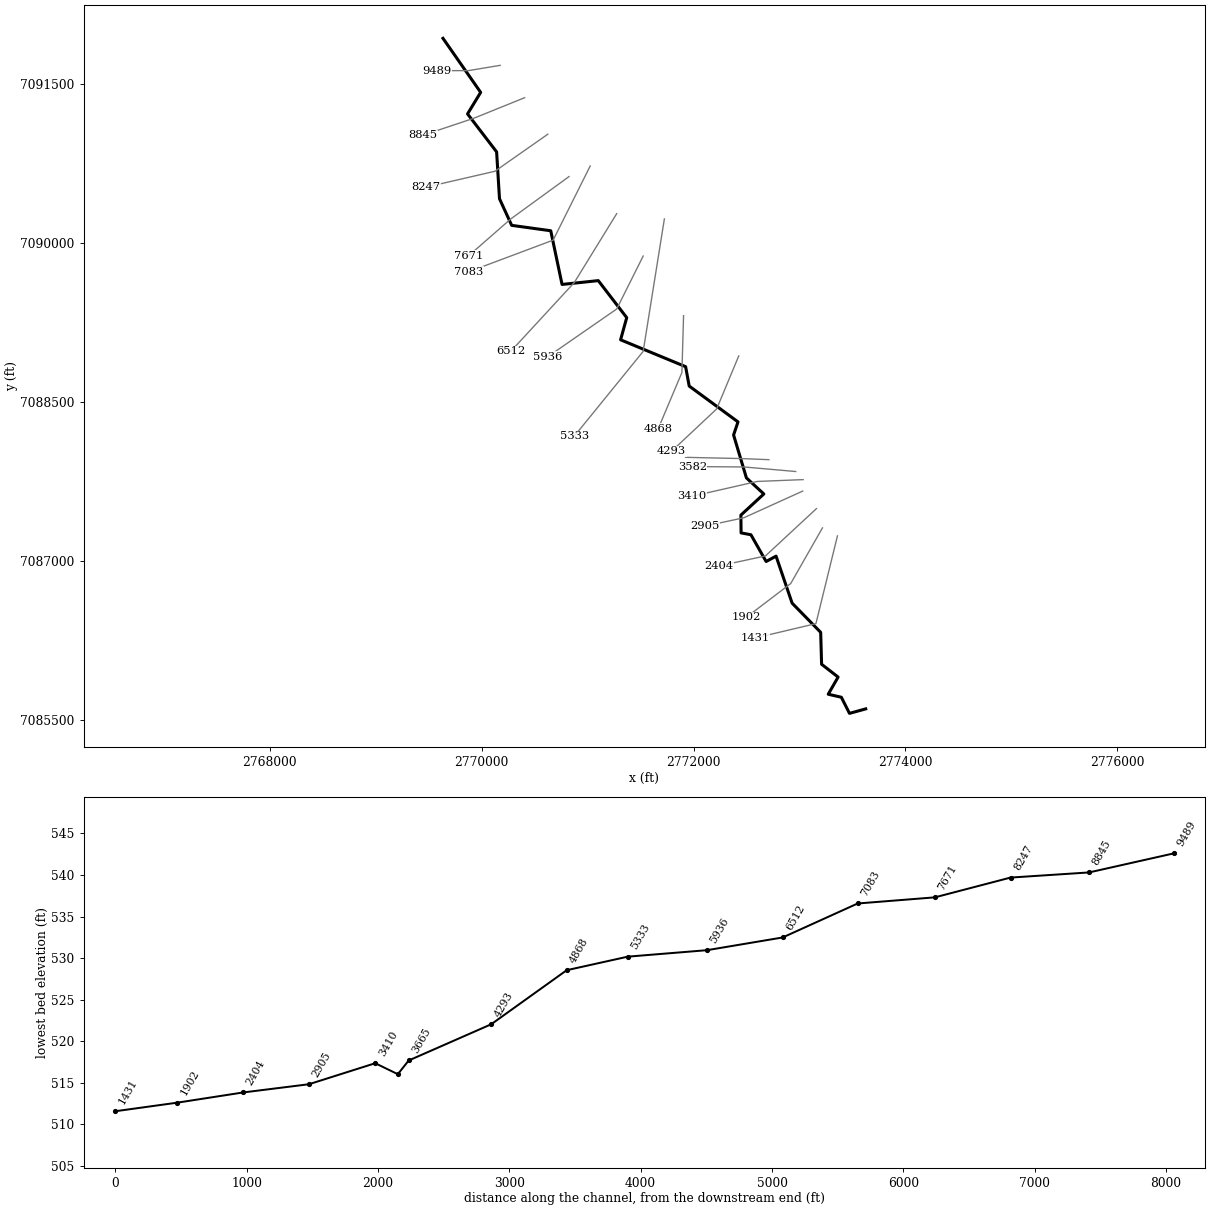
--- MIDDLE FORK TURKEY CREEK TRIB 3.prj (project) ---

Proj Title=MIDDLE FORK TURKEY CREEK TRIB 3 Base Level Engineering
Current Plan=p01
Default Exp/Contr=0.3,0.1
English Units
Geom File=g01
Flow File=f01
Plan File=p01
BEGIN DESCRIPTION:
MIDDLE FORK TURKEY CREEK TRIB 3
END DESCRIPTION:

--- MIDDLE FORK TURKEY CREEK TRIB 3.p01 (plan) ---

Plan Title=Multiple Run
Short Identifier=Multiple
Geom File=g01
Flow File=f01
Subcritical Flow
K Sum by GR= 0
Std Step Tol= 0.01
Critical Tol= 0.01
Num of Std Step Trials= 20
Max Error Tol= 0.3
Flow Tol Ratio= 0.001
Split Flow NTrial= 30
Split Flow Tol= 0.02
Split Flow Ratio= 0.02
Log Output Level= 0
Friction Slope Method= 1
Unsteady Friction Slope Method= 2
Unsteady Bridges Friction Slope Method= 1
Parabolic Critical Depth
Global Vel Dist=  1 , 1 , 1
Global Log Level= 0
CheckData=True
Encroach Param= -1, 0, 0, 0
BEGIN DESCRIPTION:
Multiple Run
END DESCRIPTION:

--- MIDDLE FORK TURKEY CREEK TRIB 3.f01 (steady flow) ---

Flow Title=Multiple
Number of Profiles=7
Profile Names=10-year,25-year,50-year,1pct_min,100-year,1pct_plu,500-year
River Rch & RM= MIDDLE FORK TURK,Reach-1,9489
     714     954    1147     683    1363    2720    1924
River Rch & RM= MIDDLE FORK TURK,Reach-1,8247
    1020    1389    1693    1021    2037    4064    2944
Boundary for River Rch & Prof#=MIDDLE FORK TURK,Reach-1,1
Up Type=0
Dn Type=3
Dn Slope=0.005
Boundary for River Rch & Prof#=MIDDLE FORK TURK,Reach-1,2
Up Type=0
Dn Type=3
Dn Slope=0.005
Boundary for River Rch & Prof#=MIDDLE FORK TURK,Reach-1,3
Up Type=0
Dn Type=3
Dn Slope=0.005
Boundary for River Rch & Prof#=MIDDLE FORK TURK,Reach-1,4
Up Type=0
Dn Type=3
Dn Slope=0.005
Boundary for River Rch & Prof#=MIDDLE FORK TURK,Reach-1,5
Up Type=0
Dn Type=3
Dn Slope=0.005
Boundary for River Rch & Prof#=MIDDLE FORK TURK,Reach-1,6
Up Type=0
Dn Type=3
Dn Slope=0.005
Boundary for River Rch & Prof#=MIDDLE FORK TURK,Reach-1,7
Up Type=0
Dn Type=3
Dn Slope=0.005

--- MIDDLE FORK TURKEY CREEK TRIB 3.g01 (geometry) ---

Geom Title=Existing Conditions

River Reach=MIDDLE FORK TURK,Reach-1
Reach XY= 30
      2769635.32      7091929.88      2769991.04      7091419.77
      2769867.15      7091216.55      2770141.60      7090858.12
      2770168.81      7090416.10      2770283.75      7090164.66
      2770652.50      7090113.62      2770759.32      7089606.97
      2771101.20      7089642.96      2771369.58      7089293.44
      2771311.83      7089084.39      2771925.59      7088830.71
      2771959.37      7088647.72      2772419.99      7088309.52
      2772378.32      7088185.82      2772499.42      7087780.87
      2772663.77      7087629.19      2772447.42      7087429.78
      2772449.06      7087261.71      2772541.94      7087244.29
      2772685.51      7086991.65      2772779.26      7087042.33
      2772930.96      7086598.43      2773200.38      7086323.29
      2773209.07      7086021.85      2773364.87      7085900.95
      2773271.67      7085738.93      2773395.37      7085710.55
      2773472.36      7085558.24      2773625.59      7085600.71

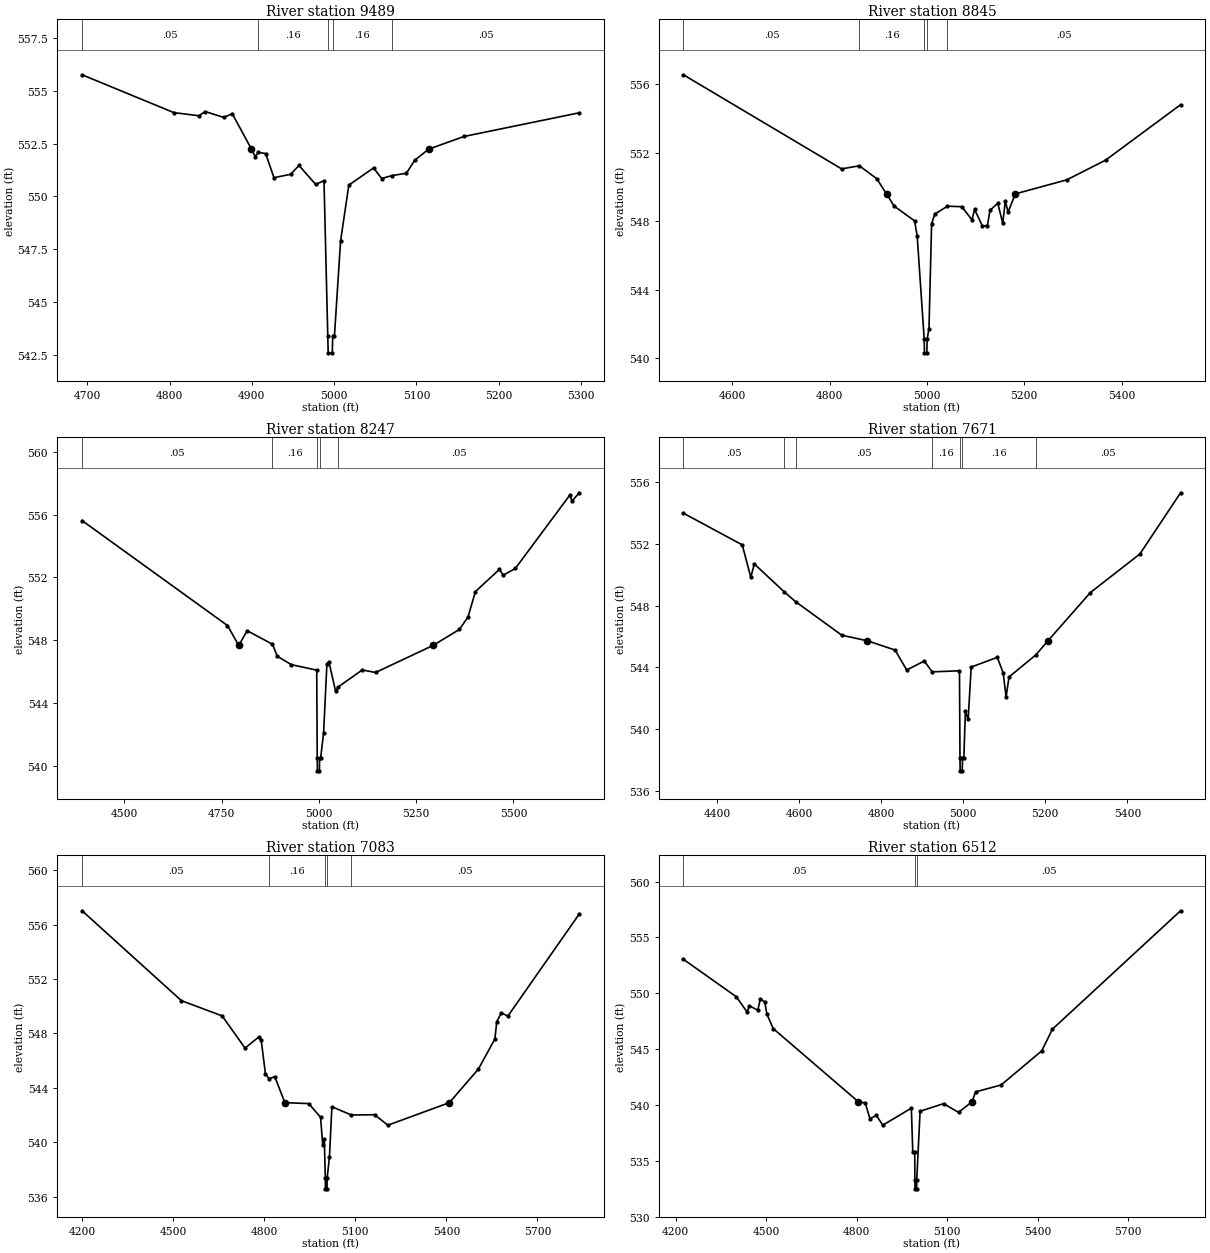
Type RM Length L Ch R = 1,9489,644,644,644
BEGIN DESCRIPTION:
MIDDLE FORK TURKEY CREEK TRIB 3 12.0
END DESCRIPTION:
XS GIS Cut Line= 3
      2770175.02      7091675.00      2769875.00      7091625.00
      2769574.96      7091625.00
#Sta/Elev= 30
  4693.7  555.76  4805.2  553.97  4835.7  553.82  4843.3  554.02  4866.1  553.74
  4876.2  553.92  4899.6  552.24  4904.1  551.89  4907.9  552.09  4916.8  552.03
  4926.9  550.89  4947.2  551.05  4957.3  551.47  4977.6  550.57  4987.7  550.75
  4992.3  543.40  4992.8  542.60  4997.8  542.60  4998.3  543.40  5000.4  543.40
  5007.9  547.91  5017.9  550.54  5047.9  551.35  5057.9  550.85  5070.3  550.99
  5087.9  551.10  5097.9  551.71  5114.9  552.24  5157.9  552.84  5297.9  553.96
#Mann=5,-1,0
  4693.7    0.05       0  4907.9    0.16       0  4992.3    0.07       0
  4998.3    0.16       0  5070.3    0.05       0
Bank Sta=4899.6,5114.9
Exp/Cntr=0.3,0.1

Type RM Length L Ch R = 1,8845,598,598,598
BEGIN DESCRIPTION:
MIDDLE FORK TURKEY CREEK TRIB 3 11.0
END DESCRIPTION:
XS GIS Cut Line= 3
      2770406.19      7091369.55      2769925.00      7091175.00
      2769448.96      7091015.75
#Sta/Elev= 30
  4499.9  556.56  4824.8  551.06  4861.2  551.24  4896.9  550.49  4917.0  549.60
  4932.6  548.89  4974.7  548.02  4980.0  547.13  4994.4  541.11  4994.9  540.31
  4999.9  540.31  5000.4  541.11  5004.2  541.71  5009.6  547.86  5016.2  548.42
  5042.1  548.88  5071.7  548.85  5092.6  548.08  5097.9  548.69  5113.8  547.73
  5124.2  547.75  5129.5  548.64  5145.5  549.05  5155.8  547.88  5161.0  549.20
  5166.6  548.52  5181.5  549.60  5287.3  550.42  5366.9  551.57  5520.9  554.81
#Mann=5,-1,0
  4499.9    0.05       0  4861.2    0.16       0  4994.4    0.07       0
  5000.4    0.16       0  5042.1    0.05       0
Bank Sta=4917,5181.5
Exp/Cntr=0.3,0.1

Type RM Length L Ch R = 1,8247,576,576,576
BEGIN DESCRIPTION:
MIDDLE FORK TURKEY CREEK TRIB 3 10.0
END DESCRIPTION:
XS GIS Cut Line= 3
      2770625.00      7091025.00      2770125.00      7090675.00
      2769475.01      7090525.00
#Sta/Elev= 30
  4391.7  555.62  4765.3  548.94  4794.3  547.67  4815.9  548.61  4880.8  547.75
  4893.5  546.98  4929.2  546.45  4994.6  546.10  4995.9  540.49  4996.4  539.69
  5001.5  539.69  5002.0  540.49  5004.6  540.49  5012.3  542.11  5020.8  546.51
  5026.0  546.62  5043.1  544.76  5050.3  545.04  5111.5  546.11  5145.7  545.95
  5293.3  547.67  5361.2  548.69  5383.5  549.49  5402.3  551.10  5463.9  552.51
  5474.1  552.15  5504.9  552.57  5645.2  557.25  5650.3  556.85  5669.1  557.39
#Mann=5,-1,0
  4391.7    0.05       0  4880.8    0.16       0  4995.9    0.07       0
  5002.0    0.16       0  5050.3    0.05       0
Bank Sta=4794.3,5293.3
Exp/Cntr=0.3,0.1

Type RM Length L Ch R = 1,7671,588,588,588
BEGIN DESCRIPTION:
MIDDLE FORK TURKEY CREEK TRIB 3 9.0
END DESCRIPTION:
XS GIS Cut Line= 3
      2770825.02      7090625.01      2770275.00      7090225.00
      2769875.00      7089875.00
#Sta/Elev= 30
  4318.1  553.97  4461.5  551.92  4482.3  549.82  4490.8  550.69  4563.1  548.90
  4591.4  548.25  4704.1  546.08  4766.3  545.72  4834.0  545.12  4862.2  543.83
  4905.1  544.41  4924.4  543.71  4990.9  543.78  4992.1  538.11  4992.6  537.31
  4997.7  537.31  4998.2  538.11  5001.5  538.11  5005.3  541.16  5012.0  540.64
  5019.5  544.02  5083.1  544.65  5097.4  543.64  5104.5  542.09  5111.6  543.38
  5177.1  544.81  5206.5  545.72  5310.0  548.84  5430.5  551.33  5529.7  555.29
#Mann=7,-1,0
  4318.1    0.05       0  4563.1    0.16       0  4591.4    0.05       0
  4924.4    0.16       0  4992.1    0.07       0  4998.2    0.16       0
  5177.1    0.05       0
Bank Sta=4766.3,5206.5
Exp/Cntr=0.3,0.1

Type RM Length L Ch R = 1,7083,571,571,571
BEGIN DESCRIPTION:
MIDDLE FORK TURKEY CREEK TRIB 3 8.0
END DESCRIPTION:
XS GIS Cut Line= 3
      2771024.99      7090724.97      2770675.00      7090025.00
      2769874.99      7089725.00
#Sta/Elev= 30
  4200.4  557.02  4527.4  550.41  4661.6  549.29  4737.0  546.92  4781.7  547.73
  4790.1  547.53  4804.1  545.03  4816.1  544.67  4834.9  544.82  4868.1  542.91
  4946.7  542.84  4985.7  541.83  4992.8  539.78  4998.1  540.21  5001.3  537.37
  5001.8  536.57  5006.9  536.57  5007.4  537.37  5015.0  538.93  5023.0  542.61
  5087.0  542.00  5163.7  542.02  5207.3  541.25  5409.9  542.91  5505.4  545.38
  5559.7  547.59  5565.9  548.87  5581.1  549.52  5602.4  549.27  5837.4  556.78
#Mann=5,-1,0
  4200.4    0.05       0  4816.1    0.16       0  5001.3    0.07       0
  5007.4    0.16       0  5087.0    0.05       0
Bank Sta=4868.1,5409.9
Exp/Cntr=0.3,0.1

Type RM Length L Ch R = 1,6512,576,576,576
BEGIN DESCRIPTION:
MIDDLE FORK TURKEY CREEK TRIB 3 7.0
END DESCRIPTION:
XS GIS Cut Line= 3
      2771274.97      7090274.96      2770875.00      7089625.00
      2770274.97      7088974.97
#Sta/Elev= 30
  4225.6  553.04  4401.3  549.68  4436.9  548.31  4443.9  548.89  4472.1  548.48
  4480.6  549.51  4495.6  549.20  4501.8  548.16  4523.1  546.84  4805.1  540.29
  4828.4  540.17  4843.8  538.76  4865.1  539.06  4886.4  538.18  4981.1  539.71
  4985.8  535.77  4992.2  535.77  4992.8  533.28  4993.3  532.48  4998.5  532.48
  4999.0  533.28  5010.0  539.43  5087.7  540.11  5137.6  539.33  5182.7  540.29
  5193.8  541.16  5278.8  541.79  5413.2  544.84  5448.9  546.79  5873.4  557.39
#Mann=3,-1,0
  4225.6    0.05       0  4992.8    0.03       0  4999.0    0.05       0
Bank Sta=4805.1,5182.7
Exp/Cntr=0.3,0.1

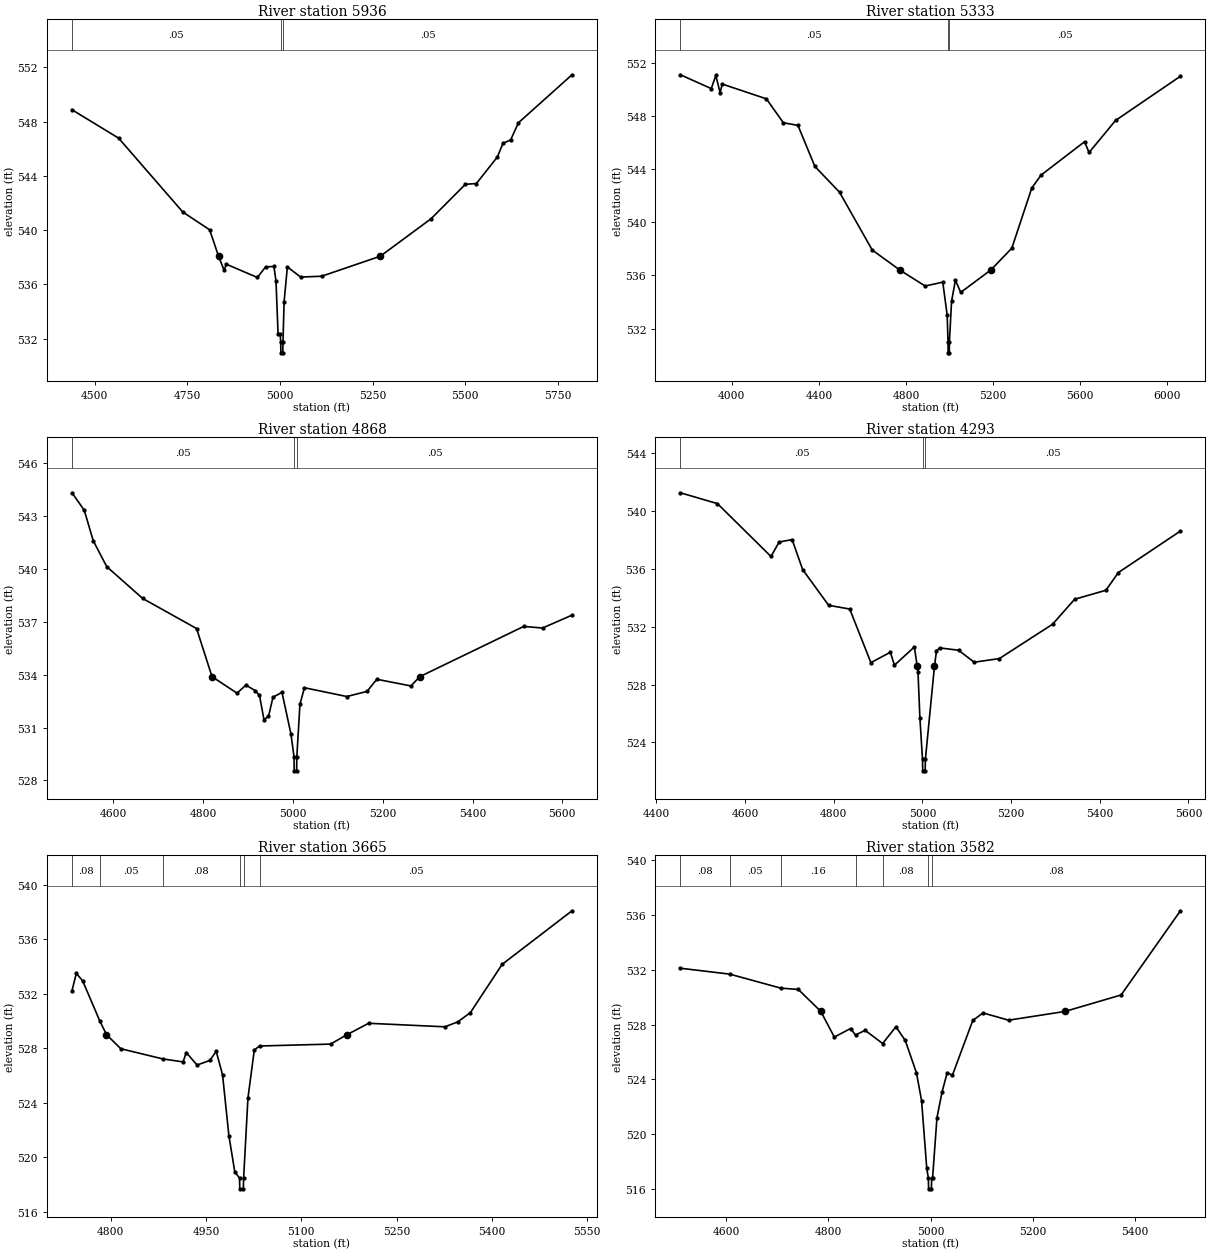
Type RM Length L Ch R = 1,5936,603,603,603
BEGIN DESCRIPTION:
MIDDLE FORK TURKEY CREEK TRIB 3 6.0
END DESCRIPTION:
XS GIS Cut Line= 3
      2771524.98      7089874.96      2771275.00      7089375.00
      2770625.04      7088925.03
#Sta/Elev= 30
  4438.8  548.88  4564.5  546.79  4737.8  541.34  4810.5  540.02  4834.3  538.08
  4849.6  537.03  4855.2  537.49  4939.1  536.51  4961.4  537.29  4983.8  537.32
  4989.4  536.25  4995.0  532.34  5000.8  532.34  5002.1  531.75  5002.6  530.95
  5007.8  530.95  5008.3  531.75  5011.3  534.72  5020.1  537.29  5055.9  536.54
  5112.6  536.60  5271.1  538.08  5407.9  540.84  5500.5  543.38  5530.2  543.44
  5587.0  545.40  5601.9  546.40  5622.8  546.66  5643.7  547.92  5788.3  551.46
#Mann=3,-1,0
  4438.8    0.05       0  5002.1    0.03       0  5008.3    0.05       0
Bank Sta=4834.3,5271.1
Exp/Cntr=0.3,0.1

Type RM Length L Ch R = 1,5333,465,465,465
BEGIN DESCRIPTION:
MIDDLE FORK TURKEY CREEK TRIB 3 5.0
END DESCRIPTION:
XS GIS Cut Line= 3
      2771725.00      7090224.97      2771525.00      7088975.00
      2770875.03      7088175.04
#Sta/Elev= 30
  3764.0  551.10  3905.8  550.06  3926.6  551.05  3946.3  549.76  3956.4  550.40
  4158.9  549.29  4236.8  547.49  4303.9  547.29  4381.7  544.20  4495.0  542.26
  4645.0  537.91  4772.1  536.40  4888.1  535.20  4969.1  535.49  4989.4  533.00
  4993.2  530.97  4993.7  530.17  4999.0  530.17  4999.5  530.97  5009.6  534.06
  5027.3  535.64  5051.4  534.72  5189.5  536.40  5286.3  538.05  5377.8  542.57
  5420.6  543.55  5620.3  546.06  5641.1  545.25  5762.6  547.66  6060.6  550.99
#Mann=3,-1,0
  3764.0    0.05       0  4993.2    0.03       0  4999.5    0.05       0
Bank Sta=4772.1,5189.5
Exp/Cntr=0.3,0.1

Type RM Length L Ch R = 1,4868,575,575,575
BEGIN DESCRIPTION:
MIDDLE FORK TURKEY CREEK TRIB 3 4.0
END DESCRIPTION:
XS GIS Cut Line= 3
      2771906.22      7089312.27      2771890.60      7088775.81
      2771666.64      7088244.57
#Sta/Elev= 30
  4508.3  544.33  4535.6  543.34  4555.6  541.61  4585.6  540.14  4665.6  538.33
  4785.7  536.62  4820.0  533.89  4875.7  532.95  4895.7  533.41  4915.7  533.10
  4925.7  532.83  4935.7  531.45  4945.8  531.63  4955.8  532.72  4975.8  533.00
  4995.8  530.63  5002.6  529.34  5003.1  528.54  5008.4  528.54  5008.9  529.34
  5015.8  532.32  5025.8  533.26  5120.1  532.76  5165.2  533.05  5186.9  533.74
  5262.9  533.36  5282.8  533.89  5513.9  536.74  5555.9  536.65  5621.5  537.38
#Mann=3,-1,0
  4508.3    0.05       0  5002.6    0.03       0  5008.9    0.05       0
Bank Sta=4820,5282.8
Exp/Cntr=0.3,0.1

Type RM Length L Ch R = 1,4293,628,628,628
BEGIN DESCRIPTION:
MIDDLE FORK TURKEY CREEK TRIB 3 3.0
END DESCRIPTION:
XS GIS Cut Line= 3
      2772427.07      7088932.10      2772218.72      7088432.06
      2771791.62      7088031.00
#Sta/Elev= 30
  4454.3  541.28  4537.8  540.53  4658.6  536.87  4677.0  537.87  4706.2  538.04
  4730.1  535.96  4788.6  533.49  4836.2  533.23  4883.9  529.52  4927.8  530.24
  4937.0  529.34  4982.0  530.61  4988.2  529.29  4990.1  528.88  4994.4  525.70
  5000.3  522.83  5000.8  522.03  5006.3  522.03  5006.8  522.83  5027.3  529.29
  5031.8  530.33  5039.1  530.54  5081.6  530.38  5116.8  529.55  5173.5  529.80
  5293.6  532.18  5343.4  533.91  5413.8  534.53  5442.1  535.76  5581.9  538.63
#Mann=3,-1,0
  4454.3    0.05       0  5000.3    0.03       0  5006.8    0.05       0
Bank Sta=4988.2,5027.3
Exp/Cntr=0.3,0.1

Type RM Length L Ch R = 1,3665,83,83,83
BEGIN DESCRIPTION:
MIDDLE FORK TURKEY CREEK TRIB 3 2.0
END DESCRIPTION:
XS GIS Cut Line= 3
      2772711.78      7087952.89      2772451.36      7087963.31
      2771925.02      7087975.00
#Sta/Elev= 30
  4739.1  532.23  4745.9  533.51  4755.9  532.96  4782.9  530.01  4793.4  529.01
  4815.9  527.97  4882.1  527.22  4914.0  527.00  4919.0  527.69  4936.0  526.77
  4956.1  527.11  4966.1  527.78  4976.1  526.06  4986.1  521.58  4995.4  518.91
  5002.8  518.47  5003.3  517.67  5008.8  517.67  5009.3  518.47  5016.1  524.35
  5026.1  527.88  5034.4  528.17  5146.1  528.31  5172.3  529.01  5206.1  529.84
  5326.2  529.58  5346.2  529.94  5366.2  530.62  5416.2  534.17  5526.2  538.11
#Mann=6,-1,0
  4739.1    0.08       0  4782.9    0.05       0  4882.1    0.08       0
  5002.8    0.07       0  5009.3    0.08       0  5034.4    0.05       0
Bank Sta=4793.4,5172.3
Exp/Cntr=0.3,0.1

Type RM Length L Ch R = 1,3582,172,172,172
BEGIN DESCRIPTION:
Mapping XS 541fa9af
END DESCRIPTION:
XS GIS Cut Line= 3
      2772964.71      7087841.08      2772477.30      7087884.08
      2771989.12      7087887.94
#Sta/Elev= 30
  4510.7  532.11  4607.1  531.68  4706.8  530.66  4741.3  530.56  4785.2  528.96
  4811.6  527.09  4843.3  527.71  4853.1  527.24  4871.8  527.58  4906.1  526.62
  4932.0  527.84  4950.3  526.84  4972.2  524.48  4982.2  522.45  4992.3  517.52
  4995.4  516.82  4995.9  516.02  5001.4  516.02  5001.9  516.82  5003.7  516.82
  5012.3  521.22  5022.3  523.09  5032.3  524.50  5042.3  524.29  5082.3  528.30
  5102.3  528.85  5152.3  528.32  5262.7  528.96  5372.3  530.16  5488.2  536.30
#Mann=7,-1,0
  4510.7    0.08       0  4607.1    0.05       0  4706.8    0.16       0
  4853.1    0.05       0  4906.1    0.08       0  4995.4    0.07       0
  5001.9    0.08       0
Bank Sta=4785.2,5262.7
Exp/Cntr=0.3,0.1

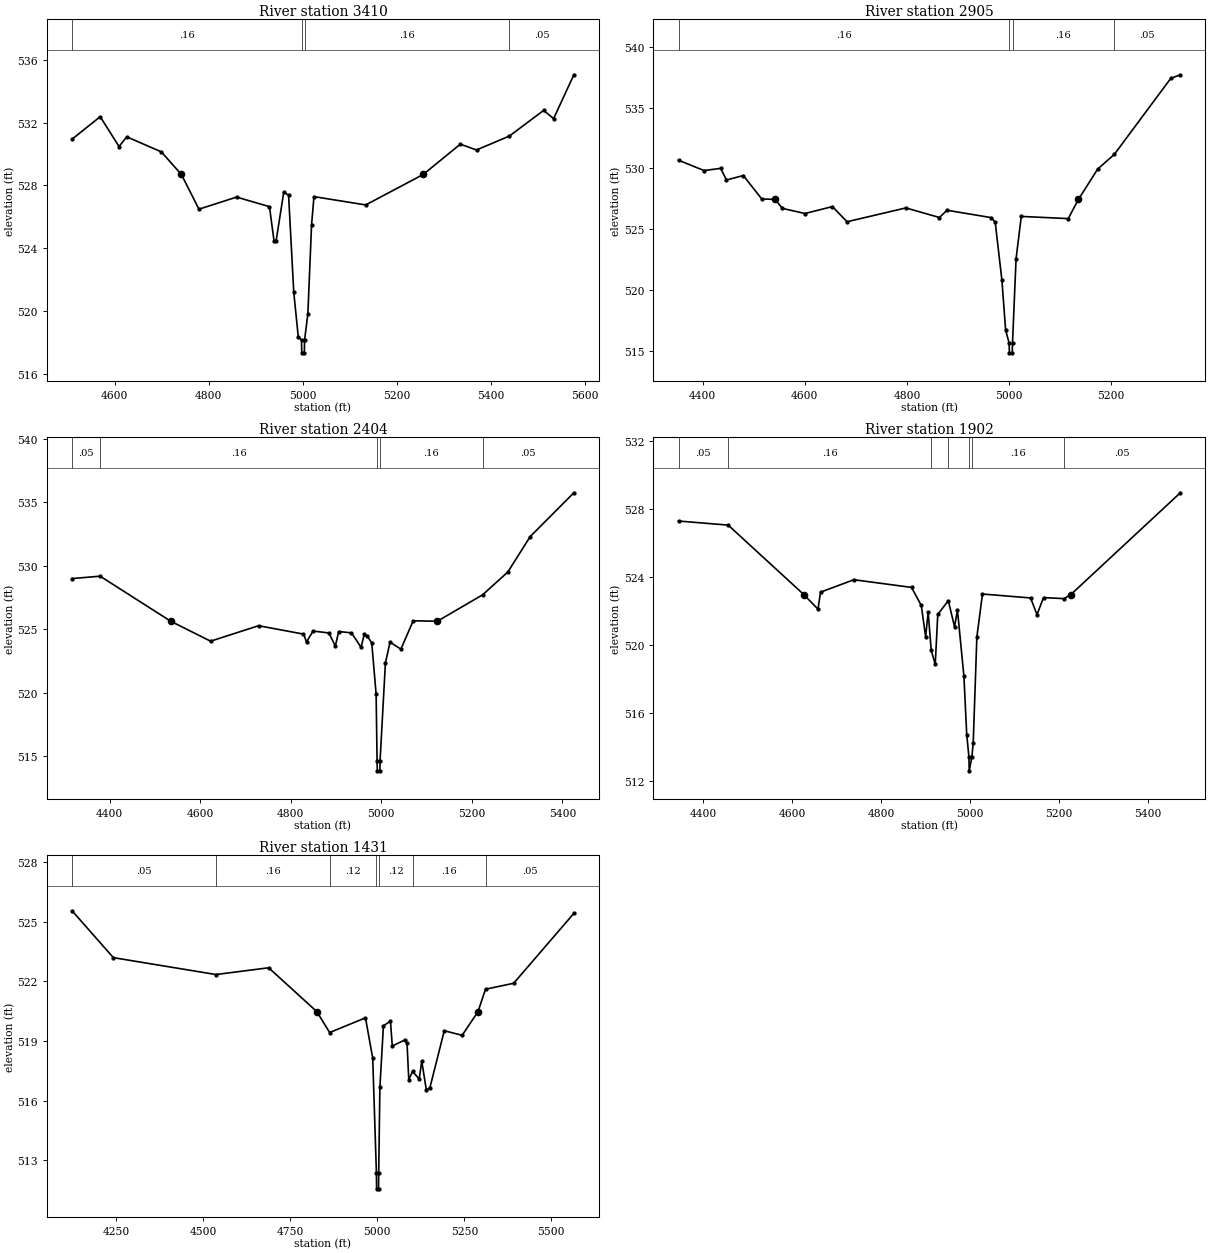
Type RM Length L Ch R = 1,3410,505,505,505
BEGIN DESCRIPTION:
Mapping XS eef700a7
END DESCRIPTION:
XS GIS Cut Line= 3
      2773034.88      7087764.70      2772600.84      7087747.34
      2771982.93      7087606.69
#Sta/Elev= 30
  4508.9  530.95  4568.8  532.38  4608.9  530.48  4625.2  531.10  4698.9  530.14
  4741.6  528.70  4779.0  526.49  4859.1  527.26  4929.1  526.65  4938.7  524.48
  4943.3  524.48  4959.5  527.58  4969.8  527.37  4980.8  521.19  4990.3  518.38
  4997.3  518.14  4997.8  517.34  5003.3  517.34  5003.8  518.14  5010.8  519.83
  5018.7  525.49  5023.8  527.29  5133.9  526.76  5256.3  528.70  5335.3  530.63
  5369.8  530.26  5439.9  531.15  5512.6  532.78  5533.9  532.26  5577.0  535.05
#Mann=4,-1,0
  4508.9    0.16       0  4997.3    0.07       0  5003.8    0.16       0
  5439.9    0.05       0
Bank Sta=4741.6,5256.3
Exp/Cntr=0.3,0.1

Type RM Length L Ch R = 1,2905,501,501,501
BEGIN DESCRIPTION:
Mapping XS b609c327
END DESCRIPTION:
XS GIS Cut Line= 3
      2773030.56      7087656.21      2772474.97      7087404.46
      2772110.41      7087326.34
#Sta/Elev= 30
  4352.7  530.68  4402.7  529.83  4435.3  530.01  4446.6  529.05  4479.6  529.42
  4515.6  527.49  4542.0  527.45  4556.2  526.71  4600.3  526.29  4654.1  526.86
  4682.7  525.61  4797.9  526.75  4863.8  525.96  4878.4  526.56  4965.2  525.95
  4972.9  525.58  4986.1  520.78  4993.3  516.69  5000.2  515.61  5000.7  514.81
  5006.3  514.81  5006.8  515.61  5013.8  522.57  5024.0  526.05  5116.0  525.87
  5135.9  527.45  5173.6  529.95  5206.2  531.16  5316.7  537.42  5335.5  537.72
#Mann=4,-1,0
  4352.7    0.16       0  5000.2    0.07       0  5006.8    0.16       0
  5206.2    0.05       0
Bank Sta=4542,5135.9
Exp/Cntr=0.3,0.1

Type RM Length L Ch R = 1,2404,502,502,502
BEGIN DESCRIPTION:
Mapping XS 8e671c6c
END DESCRIPTION:
XS GIS Cut Line= 3
      2773160.74      7087491.27      2772678.96      7087044.21
      2772238.15      7086949.14
#Sta/Elev= 30
  4317.2  528.99  4379.1  529.18  4535.3  525.62  4623.1  524.05  4729.1  525.27
  4828.3  524.61  4835.1  523.99  4849.3  524.85  4884.5  524.70  4898.6  523.66
  4906.0  524.81  4934.3  524.71  4955.3  523.57  4962.7  524.59  4969.5  524.43
  4979.0  523.92  4988.7  519.87  4990.8  514.62  4991.3  513.82  4996.9  513.82
  4997.4  514.62  5009.2  522.32  5019.4  523.98  5043.4  523.42  5070.6  525.66
  5123.7  525.62  5223.9  527.71  5279.6  529.51  5328.9  532.30  5425.4  535.76
#Mann=5,-1,0
  4317.2    0.05       0  4379.1    0.16       0  4990.8    0.07       0
  4997.4    0.16       0  5223.9    0.05       0
Bank Sta=4535.3,5123.7
Exp/Cntr=0.3,0.1

Type RM Length L Ch R = 1,1902,471,471,471
BEGIN DESCRIPTION:
Mapping XS 0960d5d0
END DESCRIPTION:
XS GIS Cut Line= 3
      2773217.18      7087309.01      2772917.68      7086783.80
      2772500.98      7086466.93
#Sta/Elev= 30
  4344.3  527.27  4455.9  527.03  4625.9  522.95  4657.8  522.09  4663.5  523.09
  4738.5  523.82  4868.1  523.37  4890.0  522.31  4899.8  520.48  4905.5  521.91
  4912.4  519.67  4921.4  518.85  4927.1  521.78  4950.8  522.59  4964.8  521.06
  4971.4  522.03  4985.9  518.14  4992.2  514.72  4997.2  513.39  4997.7  512.59
  5003.8  513.39  5006.8  514.25  5015.0  520.46  5027.6  522.98  5135.7  522.75
  5150.2  521.77  5164.8  522.77  5210.9  522.71  5226.3  522.95  5472.4  528.93
#Mann=7,-1,0
  4344.3    0.05       0  4455.9    0.16       0  4912.4    0.12       0
  4950.8    0.16       0  4997.2    0.07       0  5003.8    0.16       0
  5210.9    0.05       0
Bank Sta=4625.9,5226.3
Exp/Cntr=0.3,0.1

Type RM Length L Ch R = 1,1431,0,0,0
BEGIN DESCRIPTION:
MIDDLE FORK TURKEY CREEK TRIB 3 1.0
END DESCRIPTION:
XS GIS Cut Line= 3
      2773358.66      7087233.47      2773155.53      7086405.33
      2772582.80      7086269.95
#Sta/Elev= 30
  4123.4  525.56  4242.0  523.20  4536.5  522.35  4688.1  522.69  4826.5  520.48
  4863.2  519.43  4966.1  520.17  4986.9  518.14  4997.5  512.36  4998.0  511.56
  5003.6  511.56  5004.1  512.36  5007.5  516.69  5017.7  519.77  5037.9  520.00
  5043.1  518.75  5079.4  519.06  5085.4  518.89  5090.5  517.06  5101.3  517.47
  5120.5  517.09  5127.7  517.99  5141.0  516.53  5151.3  516.66  5192.4  519.52
  5243.8  519.29  5289.2  520.48  5310.9  521.61  5391.7  521.91  5564.6  525.43
#Mann=7,-1,0
  4123.4    0.05       0  4536.5    0.16       0  4863.2    0.12       0
  4997.5    0.07       0  5004.1    0.12       0  5101.3    0.16       0
  5310.9    0.05       0
Bank Sta=4826.5,5289.2
Exp/Cntr=0.3,0.1

Chan Stop Cuts=-1