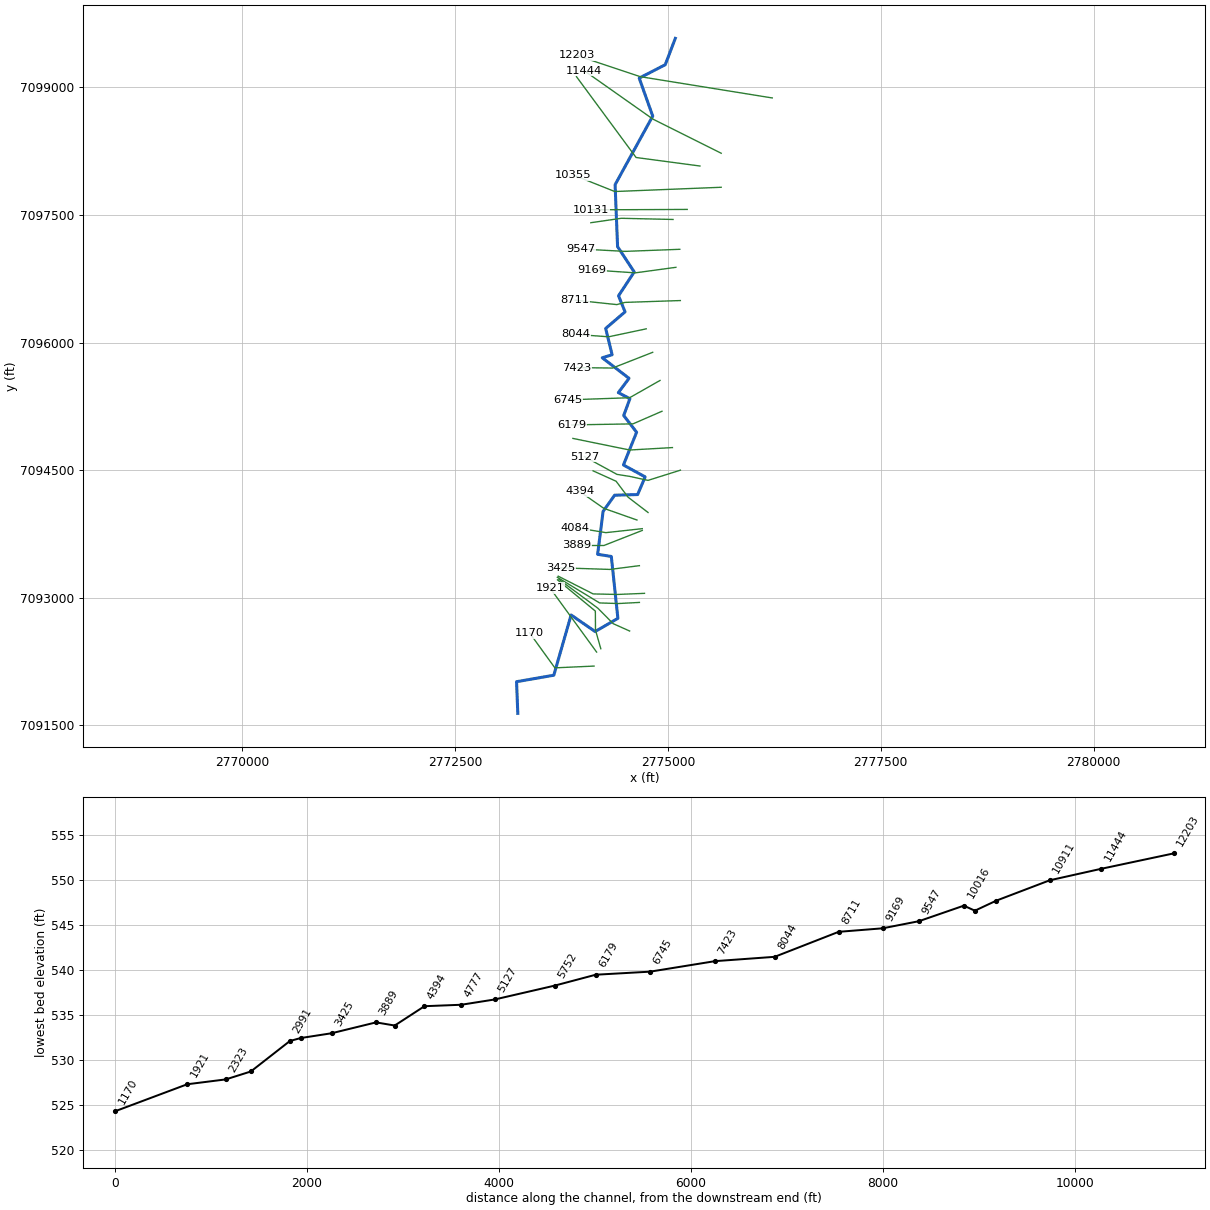
--- MIDDLE FORK TURKEY CREEK TRIB 4.prj (project) ---

Proj Title=MIDDLE FORK TURKEY CREEK TRIB 4 Base Level Engineering
Current Plan=p01
Default Exp/Contr=0.3,0.1
English Units
Geom File=g01
Flow File=f01
Plan File=p01
BEGIN DESCRIPTION:
MIDDLE FORK TURKEY CREEK TRIB 4
END DESCRIPTION:

--- MIDDLE FORK TURKEY CREEK TRIB 4.p01 (plan) ---

Plan Title=Multiple Run
Short Identifier=Multiple
Geom File=g01
Flow File=f01
Subcritical Flow
K Sum by GR= 0
Std Step Tol= 0.01
Critical Tol= 0.01
Num of Std Step Trials= 20
Max Error Tol= 0.3
Flow Tol Ratio= 0.001
Split Flow NTrial= 30
Split Flow Tol= 0.02
Split Flow Ratio= 0.02
Log Output Level= 0
Friction Slope Method= 1
Unsteady Friction Slope Method= 2
Unsteady Bridges Friction Slope Method= 1
Parabolic Critical Depth
Global Vel Dist=  1 , 1 , 1
Global Log Level= 0
CheckData=True
Encroach Param= -1, 0, 0, 0
BEGIN DESCRIPTION:
Multiple Run
END DESCRIPTION:

--- MIDDLE FORK TURKEY CREEK TRIB 4.f01 (steady flow) ---

Flow Title=Multiple
Number of Profiles=7
Profile Names=10-year,25-year,50-year,1pct_min,100-year,1pct_plu,500-year
River Rch & RM= MIDDLE FORK TURK,Reach-1,12203
     994    1356    1653     998    1990    3972    2882
River Rch & RM= MIDDLE FORK TURK,Reach-1,8044
    1204    1653    2024    1225    2445    4878    3565
Boundary for River Rch & Prof#=MIDDLE FORK TURK,Reach-1,1
Up Type=0
Dn Type=3
Dn Slope=0.005
Boundary for River Rch & Prof#=MIDDLE FORK TURK,Reach-1,2
Up Type=0
Dn Type=3
Dn Slope=0.005
Boundary for River Rch & Prof#=MIDDLE FORK TURK,Reach-1,3
Up Type=0
Dn Type=3
Dn Slope=0.005
Boundary for River Rch & Prof#=MIDDLE FORK TURK,Reach-1,4
Up Type=0
Dn Type=3
Dn Slope=0.005
Boundary for River Rch & Prof#=MIDDLE FORK TURK,Reach-1,5
Up Type=0
Dn Type=3
Dn Slope=0.005
Boundary for River Rch & Prof#=MIDDLE FORK TURK,Reach-1,6
Up Type=0
Dn Type=3
Dn Slope=0.005
Boundary for River Rch & Prof#=MIDDLE FORK TURK,Reach-1,7
Up Type=0
Dn Type=3
Dn Slope=0.005

--- MIDDLE FORK TURKEY CREEK TRIB 4.g01 (geometry) ---

Geom Title=Existing Conditions

River Reach=MIDDLE FORK TURK,Reach-1
Reach XY= 30
      2775086.26      7099575.77      2774967.63      7099265.51
      2774662.06      7099107.89      2774820.65      7098661.86
      2774378.49      7097855.13      2774407.74      7097126.99
      2774603.29      7096829.46      2774418.80      7096549.51
      2774495.59      7096360.71      2774268.06      7096165.45
      2774343.46      7095856.41      2774227.68      7095820.82
      2774542.14      7095579.34      2774416.66      7095411.19
      2774552.22      7095339.56      2774479.63      7095142.00
      2774631.31      7094945.54      2774476.63      7094560.53
      2774731.69      7094420.35      2774643.07      7094212.95
      2774373.43      7094205.49      2774237.58      7094014.88
      2774173.39      7093510.58      2774334.05      7093485.27
      2774411.41      7092757.97      2774144.13      7092602.59
      2773861.80      7092797.47      2773658.71      7092089.26
      2773221.01      7092013.01      2773235.59      7091640.71

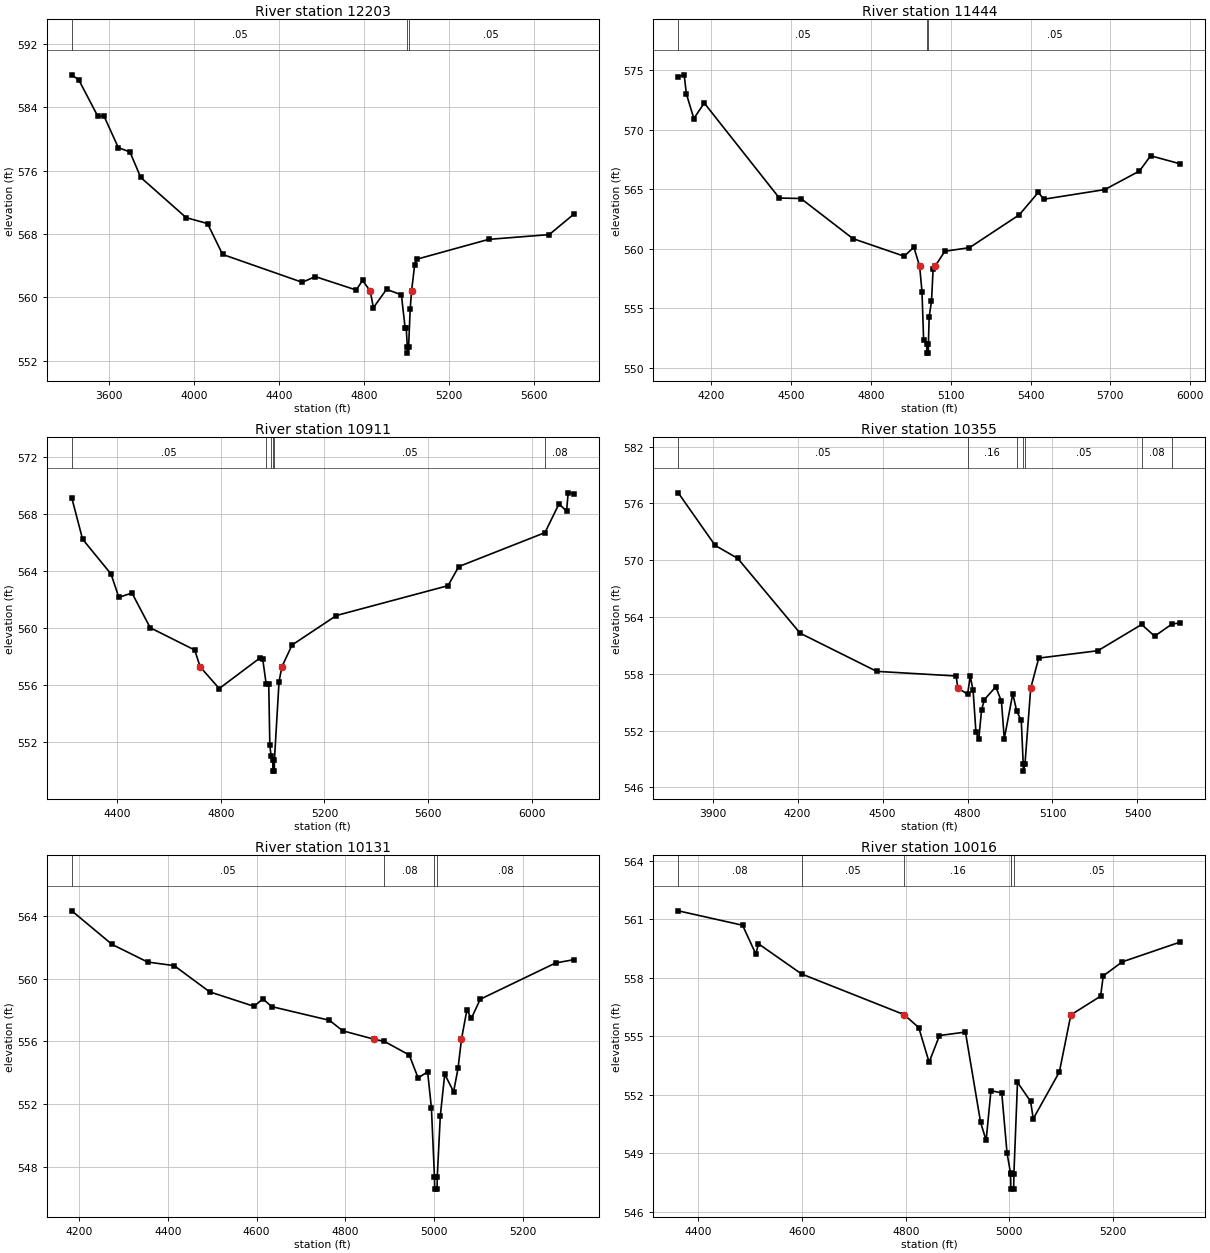
Type RM Length L Ch R = 1,12203,759,759,759
BEGIN DESCRIPTION:
MIDDLE FORK TURKEY CREEK TRIB 4 8.0
END DESCRIPTION:
XS GIS Cut Line= 3
      2776225.01      7098875.00      2774675.00      7099125.00
      2773925.01      7099375.00
#Sta/Elev= 30
  3426.4  588.10  3459.8  587.44  3548.0  582.91  3578.4  582.87  3645.2  578.91
  3699.9  578.36  3750.6  575.15  3964.3  570.07  4064.6  569.33  4135.5  565.43
  4510.2  561.91  4571.0  562.63  4763.5  560.94  4793.9  562.15  4829.8  560.79
  4844.5  558.70  4906.3  561.02  4976.2  560.33  4993.9  556.10  4999.1  556.10
  5003.9  553.77  5004.4  552.97  5010.1  553.77  5017.5  558.52  5023.9  560.79
  5038.6  564.11  5049.2  564.83  5386.5  567.33  5671.1  567.93  5787.0  570.51
#Mann=3,-1,0
  3426.4    0.05       0  5003.9    0.03       0  5010.1    0.05       0
Bank Sta=4829.8,5023.9
Exp/Cntr=0.3,0.1

Type RM Length L Ch R = 1,11444,533,533,533
BEGIN DESCRIPTION:
MIDDLE FORK TURKEY CREEK TRIB 4 7.0
END DESCRIPTION:
XS GIS Cut Line= 3
      2775624.98      7098225.01      2774825.00      7098625.00
      2774012.90      7099197.30
#Sta/Elev= 30
  4075.4  574.47  4097.7  574.63  4106.1  573.02  4134.1  570.96  4173.2  572.26
  4455.5  564.28  4536.6  564.24  4732.2  560.87  4925.1  559.39  4961.4  560.15
  4983.1  558.55  4992.0  556.42  4998.1  552.34  5009.8  552.05  5010.3  551.25
  5015.6  551.25  5016.1  552.05  5019.0  554.32  5027.7  555.61  5033.8  558.30
  5041.0  558.55  5078.2  559.81  5170.6  560.11  5357.8  562.87  5429.2  564.75
  5450.1  564.18  5679.4  564.99  5809.8  566.55  5851.6  567.83  5963.3  567.15
#Mann=3,-1,0
  4075.4    0.05       0  5009.8    0.03       0  5016.1    0.05       0
Bank Sta=4983.1,5041
Exp/Cntr=0.3,0.1

Type RM Length L Ch R = 1,10911,556,556,556
BEGIN DESCRIPTION:
MIDDLE FORK TURKEY CREEK TRIB 4 6.0
END DESCRIPTION:
XS GIS Cut Line= 3
      2775375.05      7098074.99      2774625.00      7098175.00
      2773925.02      7099124.98
#Sta/Elev= 30
  4225.5  569.14  4267.2  566.24  4376.9  563.80  4407.1  562.16  4457.6  562.47
  4528.2  560.03  4699.7  558.47  4720.7  557.29  4794.3  555.77  4951.9  557.92
  4962.0  557.84  4975.3  556.10  4985.3  556.07  4989.5  551.81  4994.5  551.01
  5000.9  550.78  5001.4  549.98  5006.8  549.98  5007.3  550.78  5025.0  556.25
  5035.9  557.29  5075.1  558.82  5246.4  560.89  5676.7  562.98  5718.4  564.32
  6050.8  566.70  6104.8  568.71  6134.1  568.21  6140.3  569.49  6162.2  569.44
#Mann=6,-1,0
  4225.5    0.05       0  4975.3    0.16       0  4994.5    0.05       0
  5000.9    0.03       0  5007.3    0.05       0  6050.8    0.08       0
Bank Sta=4720.7,5035.9
Exp/Cntr=0.3,0.1

Type RM Length L Ch R = 1,10355,224,224,224
BEGIN DESCRIPTION:
MIDDLE FORK TURKEY CREEK TRIB 4 5.0
END DESCRIPTION:
XS GIS Cut Line= 3
      2775624.96      7097825.00      2774375.00      7097775.00
      2773890.74      7097968.10
#Sta/Elev= 30
  3778.9  577.12  3909.0  571.57  3989.0  570.19  4209.2  562.29  4479.4  558.26
  4759.6  557.77  4766.1  556.49  4800.3  555.85  4809.7  557.72  4819.7  556.28
  4829.7  551.86  4839.7  551.08  4849.7  554.20  4859.7  555.28  4899.8  556.63
  4919.8  555.09  4929.8  551.14  4959.8  555.90  4973.8  554.05  4989.8  553.07
  4996.6  548.52  4997.1  547.72  5003.0  548.52  5023.2  556.49  5051.4  559.66
  5260.3  560.44  5414.7  563.21  5460.5  561.98  5522.4  563.27  5551.2  563.37
#Mann=7,-1,0
  3778.9    0.05       0  4800.3    0.16       0  4973.8    0.05       0
  4996.6    0.03       0  5003.0    0.05       0  5414.7    0.08       0
  5522.4    0.05       0
Bank Sta=4766.1,5023.2
Exp/Cntr=0.3,0.1

Type RM Length L Ch R = 1,10131,115,115,115
BEGIN DESCRIPTION:
Mapping XS 9f996ef8
END DESCRIPTION:
XS GIS Cut Line= 3
      2775225.90      7097564.62      2774427.24      7097561.15
      2774093.91      7097561.15
#Sta/Elev= 30
  4183.2  564.32  4274.1  562.18  4354.1  561.06  4414.1  560.83  4494.1  559.16
  4594.1  558.24  4614.1  558.71  4634.1  558.22  4764.1  557.35  4794.1  556.68
  4865.6  556.14  4887.8  556.01  4944.1  555.14  4964.1  553.68  4985.5  554.07
  4994.1  551.77  5000.9  547.40  5001.4  546.60  5006.8  546.60  5007.3  547.40
  5014.1  551.26  5024.1  553.92  5044.1  552.80  5054.1  554.29  5061.8  556.14
  5074.1  558.01  5084.1  557.47  5104.1  558.69  5274.1  561.00  5315.2  561.21
#Mann=4,-1,0
  4183.2    0.05       0  4887.8    0.08       0  5000.9    0.07       0
  5007.3    0.08       0
Bank Sta=4865.6,5061.8
Exp/Cntr=0.3,0.1

Type RM Length L Ch R = 1,10016,469,469,469
BEGIN DESCRIPTION:
Mapping XS f53f72c5
END DESCRIPTION:
XS GIS Cut Line= 3
      2775059.22      7097446.56      2774451.55      7097460.45
      2774093.95      7097408.37
#Sta/Elev= 30
  4360.9  561.44  4485.1  560.70  4510.7  559.22  4515.7  559.75  4599.0  558.20
  4797.3  556.11  4797.4  556.10  4825.2  555.45  4845.2  553.67  4865.2  555.04
  4915.3  555.22  4944.6  550.58  4955.3  549.66  4964.5  552.21  4985.4  552.10
  4995.6  549.01  5002.3  547.99  5002.5  547.96  5003.0  547.16  5008.4  547.16
  5008.9  547.96  5015.8  552.64  5041.1  551.66  5046.2  550.77  5096.6  553.17
  5118.8  556.10  5176.2  557.06  5181.3  558.10  5217.9  558.82  5330.1  559.84
#Mann=6,-1,0
  4360.9    0.08       0  4599.0    0.05       0  4797.3    0.16       0
  5002.3    0.05       0  5002.5    0.07       0  5008.9    0.05       0
Bank Sta=4797.4,5118.8
Exp/Cntr=0.3,0.1

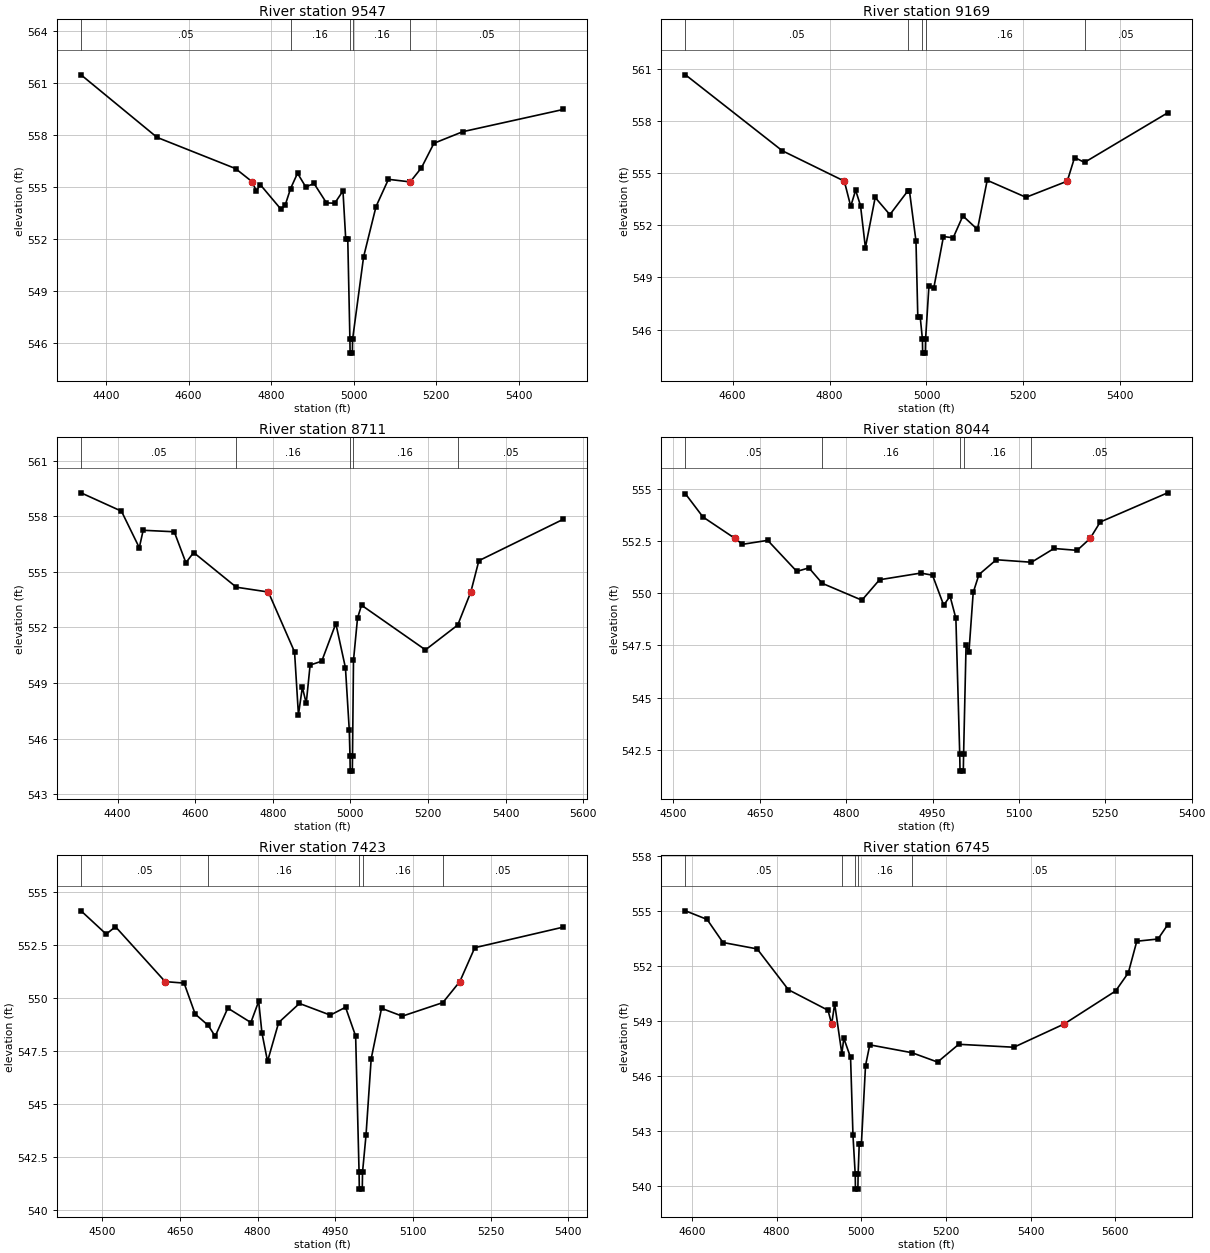
Type RM Length L Ch R = 1,9547,378,378,378
BEGIN DESCRIPTION:
Mapping XS 1e4a228e
END DESCRIPTION:
XS GIS Cut Line= 3
      2775139.03      7097095.87      2774496.68      7097071.56
      2773972.42      7097099.34
#Sta/Elev= 30
  4339.4  561.49  4523.6  557.88  4713.7  556.08  4753.9  555.32  4763.9  554.79
  4773.7  555.15  4823.8  553.73  4833.8  553.96  4846.9  554.92  4863.8  555.81
  4883.8  555.02  4903.8  555.22  4933.9  554.10  4953.9  554.08  4973.9  554.79
  4980.5  552.04  4985.5  552.04  4990.7  546.23  4991.2  545.43  4996.7  545.43
  4997.2  546.23  5023.9  550.99  5054.0  553.89  5084.0  555.46  5137.0  555.31
  5137.4  555.33  5164.1  556.13  5194.2  557.54  5264.3  558.21  5507.2  559.49
#Mann=5,-1,0
  4339.4    0.05       0  4846.9    0.16       0  4990.7    0.07       0
  4997.2    0.16       0  5137.0    0.05       0
Bank Sta=4753.9,5137.4
Exp/Cntr=0.3,0.1

Type RM Length L Ch R = 1,9169,458,458,458
BEGIN DESCRIPTION:
Mapping XS 732bf219
END DESCRIPTION:
XS GIS Cut Line= 3
      2775093.01      7096884.06      2774615.61      7096818.96
      2774103.41      7096853.68
#Sta/Elev= 30
  4502.6  560.66  4702.4  556.29  4830.5  554.54  4843.7  553.09  4853.8  554.02
  4863.9  553.13  4874.0  550.71  4894.2  553.60  4924.5  552.61  4961.9  553.99
  4964.9  553.98  4978.4  551.09  4982.2  546.70  4987.2  546.70  4991.7  545.44
  4992.2  544.64  4997.7  544.64  4998.2  545.44  5005.1  548.48  5015.1  548.38
  5035.1  551.35  5055.2  551.28  5075.2  552.54  5105.3  551.76  5125.4  554.59
  5205.5  553.61  5290.7  554.54  5305.8  555.90  5326.3  555.62  5497.8  558.47
#Mann=5,-1,0
  4502.6    0.05       0  4961.9    0.16       0  4991.7    0.07       0
  4998.2    0.16       0  5326.3    0.05       0
Bank Sta=4830.5,5290.7
Exp/Cntr=0.3,0.1

Type RM Length L Ch R = 1,8711,667,667,667
BEGIN DESCRIPTION:
Mapping XS f88f0a23
END DESCRIPTION:
XS GIS Cut Line= 4
      2775145.14      7096493.44      2774494.08      7096471.74
      2774398.59      7096445.70      2773909.04      7096497.68
#Sta/Elev= 30
  4305.6  559.26  4409.8  558.27  4455.8  556.30  4465.8  557.24  4545.9  557.16
  4575.9  555.49  4595.9  556.04  4705.9  554.17  4788.5  553.91  4856.0  550.68
  4866.0  547.29  4876.1  548.77  4886.1  547.91  4896.1  549.97  4926.1  550.18
  4962.4  552.21  4987.2  549.82  4997.0  546.48  4998.9  545.05  4999.4  544.25
  5004.9  544.25  5005.4  545.05  5007.9  550.22  5018.3  552.50  5028.6  553.20
  5193.4  550.79  5276.6  552.13  5310.3  553.91  5331.1  555.60  5548.3  557.83
#Mann=5,-1,0
  4305.6    0.05       0  4705.9    0.16       0  4998.9    0.07       0
  5005.4    0.16       0  5276.6    0.05       0
Bank Sta=4788.5,5310.3
Exp/Cntr=0.3,0.1

Type RM Length L Ch R = 1,8044,621,621,621
BEGIN DESCRIPTION:
Mapping XS e31b1fb5
END DESCRIPTION:
XS GIS Cut Line= 3
      2774744.71      7096160.97      2774302.02      7096067.22
      2773918.29      7096095.74
#Sta/Elev= 30
  4520.9  554.77  4551.3  553.66  4607.0  552.63  4619.9  552.35  4663.7  552.54
  4714.2  551.05  4735.3  551.22  4758.3  550.48  4827.3  549.67  4857.9  550.65
  4929.5  550.97  4949.9  550.87  4969.3  549.43  4980.4  549.86  4990.5  548.80
  4997.2  542.27  4997.7  541.47  5003.4  541.47  5003.9  542.27  5008.2  547.53
  5013.2  547.19  5020.6  550.04  5030.6  550.90  5060.7  551.61  5121.8  551.49
  5160.9  552.15  5201.1  552.06  5223.6  552.63  5241.2  553.42  5358.2  554.82
#Mann=5,-1,0
  4520.9    0.05       0  4758.3    0.16       0  4997.2    0.07       0
  5003.9    0.16       0  5121.8    0.05       0
Bank Sta=4607,5223.6
Exp/Cntr=0.3,0.1

Type RM Length L Ch R = 1,7423,678,678,678
BEGIN DESCRIPTION:
Mapping XS c26c75c9
END DESCRIPTION:
XS GIS Cut Line= 3
      2774820.22      7095884.92      2774348.90      7095700.04
      2773924.42      7095705.24
#Sta/Elev= 30
  4459.0  554.12  4507.6  553.02  4525.5  553.37  4621.4  550.78  4658.0  550.71
  4679.4  549.25  4704.8  548.71  4718.0  548.20  4742.4  549.53  4786.9  548.85
  4802.0  549.85  4808.3  548.36  4819.1  547.02  4840.6  548.85  4880.7  549.75
  4940.3  549.20  4969.7  549.57  4989.2  548.21  4995.8  541.79  4996.3  540.99
  5002.0  540.99  5002.5  541.79  5009.2  543.53  5019.2  547.14  5039.2  549.52
  5079.2  549.15  5157.5  549.79  5190.3  550.78  5219.2  552.38  5389.8  553.35
#Mann=5,-1,0
  4459.0    0.05       0  4704.8    0.16       0  4995.8    0.07       0
  5002.5    0.16       0  5157.5    0.05       0
Bank Sta=4621.4,5190.3
Exp/Cntr=0.3,0.1

Type RM Length L Ch R = 1,6745,566,566,566
BEGIN DESCRIPTION:
Mapping XS 35ad4e05
END DESCRIPTION:
XS GIS Cut Line= 3
      2774906.20      7095554.21      2774549.42      7095351.08
      2773822.30      7095325.99
#Sta/Elev= 30
  4585.1  555.02  4636.1  554.55  4673.6  553.29  4754.3  552.94  4828.1  550.71
  4921.5  549.59  4930.2  548.84  4937.3  549.94  4954.2  547.22  4958.9  548.06
  4974.8  547.01  4980.5  542.75  4985.8  540.62  4986.3  539.82  4992.1  539.82
  4992.6  540.62  4995.3  542.31  5000.4  542.31  5010.1  546.56  5020.1  547.70
  5119.8  547.27  5180.2  546.76  5230.2  547.73  5360.3  547.57  5479.1  548.84
  5600.4  550.64  5630.4  551.63  5650.5  553.36  5700.5  553.48  5723.2  554.25
#Mann=5,-1,0
  4585.1    0.05       0  4954.2    0.16       0  4985.8    0.07       0
  4992.6    0.16       0  5119.8    0.05       0
Bank Sta=4930.2,5479.1
Exp/Cntr=0.3,0.1

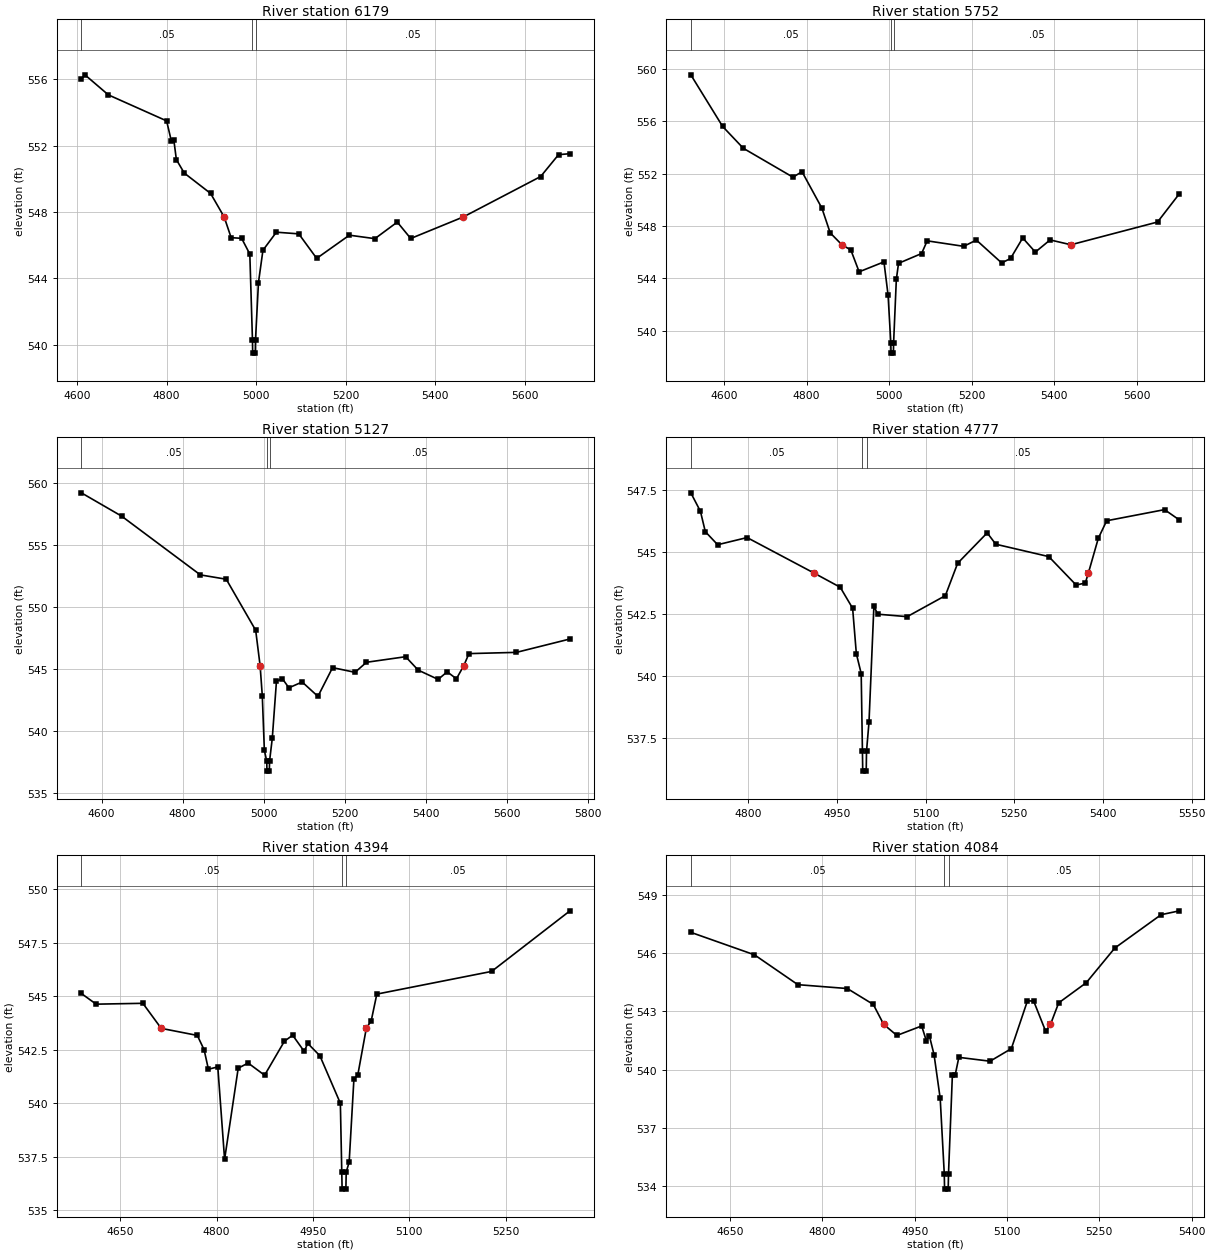
Type RM Length L Ch R = 1,6179,427,427,427
BEGIN DESCRIPTION:
Mapping XS 40ef954f
END DESCRIPTION:
XS GIS Cut Line= 3
      2774929.59      7095192.21      2774588.48      7095043.79
      2773869.49      7095031.66
#Sta/Elev= 30
  4609.7  556.01  4617.7  556.28  4670.0  555.07  4800.1  553.50  4810.6  552.29
  4816.1  552.37  4821.9  551.16  4839.5  550.35  4898.3  549.12  4928.6  547.70
  4944.2  546.45  4967.6  546.41  4985.9  545.46  4991.8  540.28  4992.3  539.48
  4998.1  539.48  4998.6  540.28  5005.2  543.74  5015.2  545.69  5045.2  546.78
  5095.2  546.68  5135.2  545.20  5208.2  546.60  5265.2  546.39  5315.2  547.39
  5345.2  546.40  5462.6  547.70  5635.3  550.14  5675.3  551.46  5700.8  551.52
#Mann=3,-1,0
  4609.7    0.05       0  4991.8    0.03       0  4998.6    0.05       0
Bank Sta=4928.6,5462.6
Exp/Cntr=0.3,0.1

Type RM Length L Ch R = 1,5752,625,625,625
BEGIN DESCRIPTION:
Mapping XS 2a541776
END DESCRIPTION:
XS GIS Cut Line= 3
      2775052.01      7094765.14      2774549.42      7094736.49
      2773883.12      7094872.79
#Sta/Elev= 30
  4519.5  559.56  4596.6  555.61  4646.7  553.94  4766.9  551.73  4788.8  552.15
  4837.0  549.36  4857.1  547.47  4885.4  546.56  4907.1  546.16  4927.2  544.49
  4987.3  545.25  4997.3  542.71  5003.9  539.07  5004.4  538.27  5010.2  538.27
  5010.7  539.07  5017.3  543.91  5022.6  545.14  5078.5  545.89  5092.0  546.86
  5180.5  546.44  5211.1  546.92  5272.4  545.17  5293.9  545.51  5323.4  547.08
  5354.0  546.00  5389.7  546.93  5440.2  546.56  5650.0  548.30  5703.0  550.47
#Mann=3,-1,0
  4519.5    0.05       0  5003.9    0.03       0  5010.7    0.05       0
Bank Sta=4885.4,5440.2
Exp/Cntr=0.3,0.1

Type RM Length L Ch R = 1,5127,350,350,350
BEGIN DESCRIPTION:
Mapping XS dd0fc7ce
END DESCRIPTION:
XS GIS Cut Line= 5
      2775145.78      7094499.52      2774765.56      7094379.72
      2774549.42      7094426.60      2774400.98      7094450.04
      2774019.07      7094657.88
#Sta/Elev= 30
  4550.2  559.18  4649.5  557.30  4843.7  552.56  4907.5  552.21  4980.1  548.09
  4991.0  545.24  4996.4  542.81  5001.5  538.40  5007.4  537.53  5007.9  536.73
  5013.8  536.73  5014.3  537.53  5021.0  539.37  5031.3  543.97  5045.6  544.20
  5062.0  543.45  5094.7  543.92  5133.6  542.76  5169.7  545.08  5225.1  544.70
  5253.2  545.51  5349.9  545.96  5380.7  544.88  5430.0  544.13  5452.3  544.74
  5475.1  544.18  5493.3  545.24  5506.0  546.21  5623.1  546.31  5755.1  547.39
#Mann=3,-1,0
  4550.2    0.05       0  5007.4    0.03       0  5014.3    0.05       0
Bank Sta=4991,5493.3
Exp/Cntr=0.3,0.1

Type RM Length L Ch R = 1,4777,383,383,383
BEGIN DESCRIPTION:
Mapping XS 59576dd9
END DESCRIPTION:
XS GIS Cut Line= 4
      2774765.60      7094002.09      2774531.19      7094181.81
      2774390.56      7094369.31      2774119.88      7094491.64
#Sta/Elev= 30
  4702.7  547.40  4719.0  546.65  4727.2  545.83  4748.1  545.30  4797.9  545.59
  4910.7  544.16  4955.5  543.58  4976.5  542.73  4982.8  540.89  4991.0  540.09
  4993.1  536.94  4993.6  536.14  4999.5  536.14  5000.0  536.94  5004.2  538.12
  5012.5  542.82  5018.8  542.49  5068.8  542.39  5133.4  543.24  5154.2  544.55
  5204.2  545.78  5218.8  545.32  5308.4  544.82  5354.7  543.67  5370.2  543.75
  5375.5  544.16  5392.2  545.56  5406.4  546.27  5504.3  546.72  5529.5  546.30
#Mann=3,-1,0
  4702.7    0.05       0  4993.1    0.03       0  5000.0    0.05       0
Bank Sta=4910.7,5375.5
Exp/Cntr=0.3,0.1

Type RM Length L Ch R = 1,4394,310,310,310
BEGIN DESCRIPTION:
Mapping XS 6de67377
END DESCRIPTION:
XS GIS Cut Line= 3
      2774635.32      7093913.59      2774244.73      7094051.60
      2773960.67      7094250.44
#Sta/Elev= 30
  4589.4  545.12  4612.4  544.62  4685.2  544.66  4713.8  543.49  4770.0  543.16
  4780.6  542.49  4787.3  541.58  4801.9  541.69  4812.5  537.37  4833.7  541.63
  4849.2  541.87  4874.8  541.30  4905.7  542.89  4918.5  543.17  4936.6  542.41
  4941.9  542.79  4960.9  542.21  4992.8  539.99  4995.0  536.78  4995.5  535.98
  5001.4  535.98  5001.9  536.78  5006.5  537.24  5013.9  541.12  5020.0  541.32
  5033.2  543.49  5040.9  543.85  5049.6  545.09  5228.4  546.15  5350.4  548.98
#Mann=3,-1,0
  4589.4    0.05       0  4995.0    0.03       0  5001.9    0.05       0
Bank Sta=4713.8,5033.2
Exp/Cntr=0.3,0.1

Type RM Length L Ch R = 1,4084,195,195,195
BEGIN DESCRIPTION:
Mapping XS 3068275f
END DESCRIPTION:
XS GIS Cut Line= 3
      2774697.82      7093812.01      2774270.77      7093765.14
      2773911.44      7093825.03
#Sta/Elev= 30
  4586.3  547.08  4689.7  545.92  4760.2  544.38  4840.6  544.18  4882.8  543.36
  4899.7  542.33  4921.1  541.76  4961.4  542.25  4968.9  541.49  4973.9  541.74
  4981.5  540.77  4991.5  538.51  4998.1  534.63  4998.6  533.83  5004.5  533.83
  5005.0  534.63  5011.3  539.73  5015.9  539.73  5021.8  540.63  5072.5  540.43
  5107.1  541.08  5133.3  543.55  5143.4  543.53  5162.9  541.97  5170.7  542.33
  5184.0  543.44  5228.8  544.48  5275.2  546.27  5350.4  547.99  5380.2  548.19
#Mann=3,-1,0
  4586.3    0.05       0  4998.1    0.03       0  5005.0    0.05       0
Bank Sta=4899.7,5170.7
Exp/Cntr=0.3,0.1

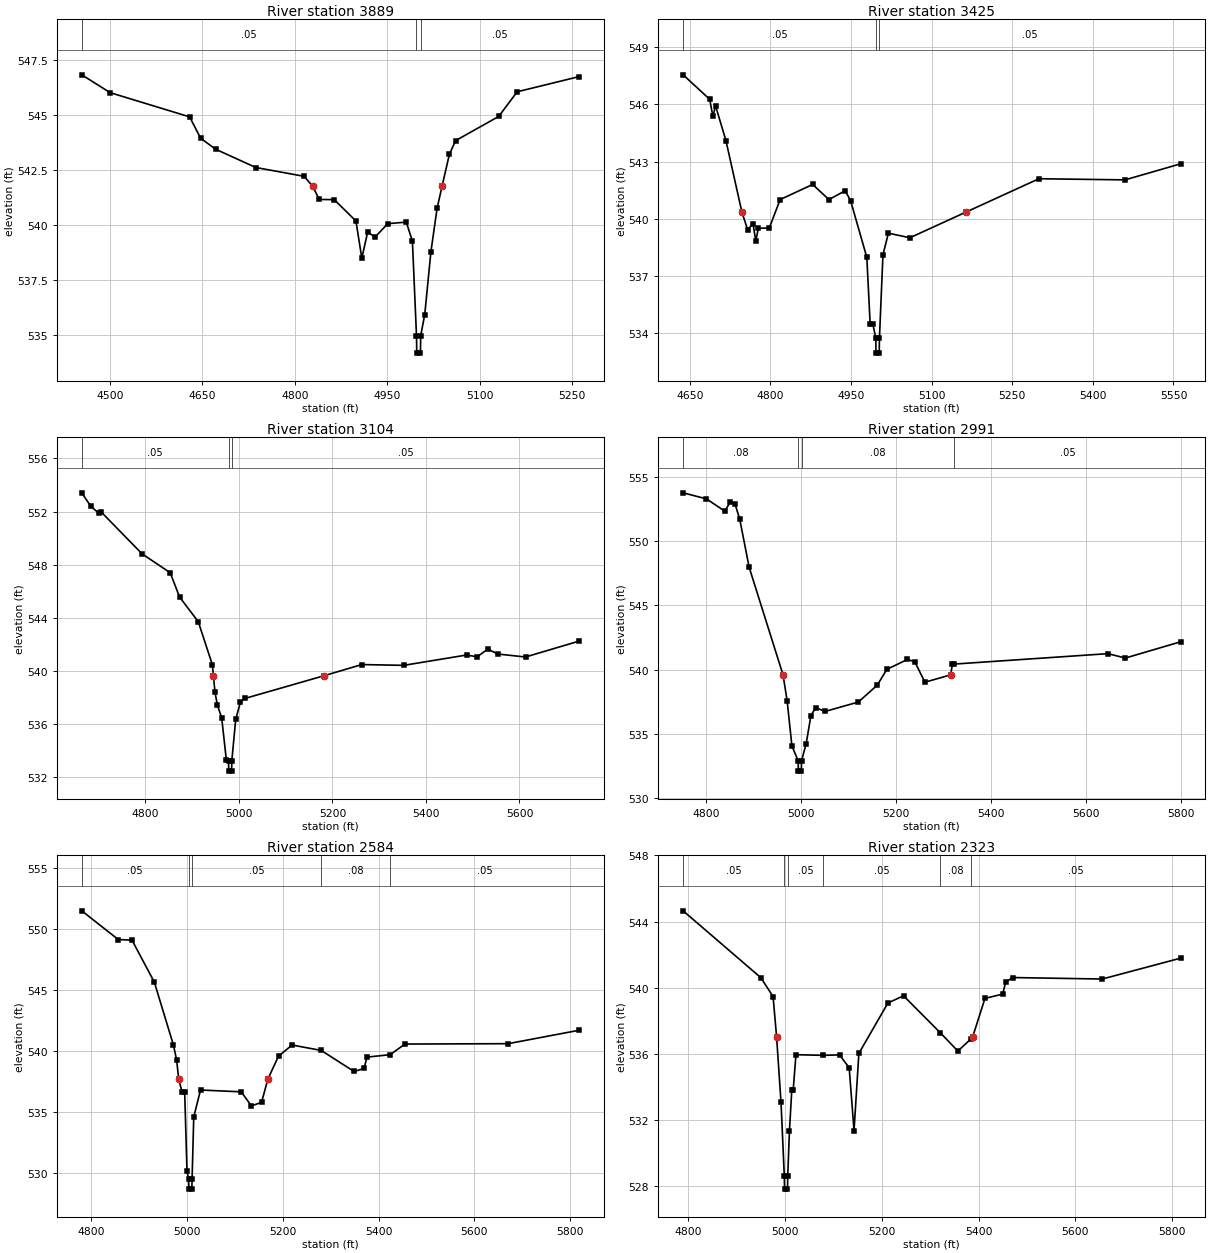
Type RM Length L Ch R = 1,3889,464,464,464
BEGIN DESCRIPTION:
Mapping XS 5f1f0232
END DESCRIPTION:
XS GIS Cut Line= 3
      2774697.85      7093791.18      2774247.34      7093614.10
      2773924.40      7093614.10
#Sta/Elev= 30
  4454.3  546.82  4500.3  546.01  4629.3  544.91  4647.1  543.94  4671.5  543.44
  4736.7  542.61  4815.1  542.21  4829.0  541.75  4839.5  541.16  4863.9  541.15
  4899.1  540.18  4908.6  538.49  4918.1  539.68  4930.1  539.45  4950.7  540.06
  4980.7  540.13  4990.7  539.27  4997.3  534.98  4997.8  534.18  5003.7  534.18
  5004.2  534.98  5010.7  535.93  5020.7  538.78  5030.7  540.75  5038.7  541.75
  5050.7  543.21  5060.7  543.83  5130.7  544.93  5160.7  546.05  5261.3  546.74
#Mann=3,-1,0
  4454.3    0.05       0  4997.3    0.03       0  5004.2    0.05       0
Bank Sta=4829,5038.7
Exp/Cntr=0.3,0.1

Type RM Length L Ch R = 1,3425,321,321,321
BEGIN DESCRIPTION:
Mapping XS d200417e
END DESCRIPTION:
XS GIS Cut Line= 3
      2774664.02      7093377.12      2774317.65      7093332.85
      2773741.64      7093351.61
#Sta/Elev= 30
  4637.7  547.54  4687.1  546.26  4693.0  545.38  4698.1  545.91  4717.4  544.09
  4747.0  540.36  4757.7  539.43  4767.7  539.75  4772.8  538.85  4777.8  539.51
  4798.0  539.52  4818.2  541.01  4878.7  541.80  4908.9  541.01  4939.2  541.47
  4949.2  540.96  4979.5  537.98  4985.7  534.49  4990.7  534.49  4996.1  533.77
  4996.6  532.97  5002.5  532.97  5003.0  533.77  5009.5  538.12  5019.6  539.25
  5059.6  539.01  5164.5  540.36  5299.7  542.10  5459.8  542.04  5563.2  542.88
#Mann=3,-1,0
  4637.7    0.05       0  4996.1    0.03       0  5003.0    0.05       0
Bank Sta=4747,5164.5
Exp/Cntr=0.3,0.1

Type RM Length L Ch R = 1,3104,113,113,113
BEGIN DESCRIPTION:
Mapping XS 11fac539
END DESCRIPTION:
XS GIS Cut Line= 4
      2774723.93      7093051.60      2774403.59      7093038.58
      2774120.88      7093044.86      2773710.42      7093253.44
#Sta/Elev= 30
  4664.0  553.41  4682.9  552.41  4700.7  551.86  4705.7  551.96  4793.0  548.81
  4853.1  547.39  4873.1  545.56  4913.1  543.70  4943.2  540.46  4945.5  539.63
  4948.9  538.38  4953.9  537.43  4963.2  536.45  4973.2  533.27  4977.8  533.24
  4978.3  532.44  4984.4  532.44  4984.9  533.24  4993.2  536.34  5003.2  537.63
  5013.2  537.92  5182.3  539.63  5262.8  540.47  5352.5  540.41  5487.1  541.19
  5509.5  541.05  5532.0  541.63  5554.4  541.26  5613.0  541.04  5727.8  542.24
#Mann=3,-1,0
  4664.0    0.05       0  4977.8    0.03       0  4984.9    0.05       0
Bank Sta=4945.5,5182.3
Exp/Cntr=0.3,0.1

Type RM Length L Ch R = 1,2991,407,407,407
BEGIN DESCRIPTION:
Mapping XS ee6c5aa7
END DESCRIPTION:
XS GIS Cut Line= 4
      2774664.01      7092944.83      2774416.61      7092931.81
      2774196.61      7092938.83      2773700.27      7093240.15
#Sta/Elev= 30
  4751.4  553.74  4800.5  553.27  4839.4  552.31  4850.5  553.02  4860.6  552.89
  4870.6  551.71  4890.6  547.95  4962.0  539.59  4970.7  537.56  4980.7  534.07
  4993.9  532.91  4994.4  532.11  5000.5  532.11  5001.0  532.91  5010.8  534.25
  5020.8  536.43  5030.8  537.04  5050.8  536.75  5120.8  537.48  5160.8  538.80
  5180.8  540.02  5224.3  540.79  5239.7  540.61  5261.1  539.02  5315.1  539.59
  5319.2  540.43  5322.8  540.43  5646.8  541.24  5683.6  540.90  5799.9  542.16
#Mann=4,-1,0
  4751.4    0.08       0  4993.9    0.07       0  5001.0    0.08       0
  5322.8    0.05       0
Bank Sta=4962,5315.1
Exp/Cntr=0.3,0.1

Type RM Length L Ch R = 1,2584,261,261,261
BEGIN DESCRIPTION:
Mapping XS d8db32e8
END DESCRIPTION:
XS GIS Cut Line= 4
      2774549.37      7092608.91      2774356.71      7092694.83
      2774176.68      7092876.41      2773718.57      7093216.66
#Sta/Elev= 30
  4781.2  551.49  4857.3  549.14  4886.0  549.09  4932.5  545.65  4972.1  540.54
  4979.0  539.29  4983.2  537.75  4990.4  536.63  4995.8  536.63  5000.6  530.19
  5004.1  529.52  5004.6  528.72  5010.7  528.72  5011.2  529.52  5014.7  534.63
  5028.8  536.83  5113.7  536.68  5134.9  535.53  5156.1  535.82  5169.4  537.74
  5191.5  539.60  5219.7  540.51  5280.3  540.07  5348.9  538.35  5369.8  538.59
  5376.0  539.52  5424.1  539.72  5455.3  540.59  5670.2  540.62  5818.5  541.72
#Mann=5,-1,0
  4781.2    0.05       0  5004.1    0.03       0  5011.2    0.05       0
  5280.3    0.08       0  5424.1    0.05       0
Bank Sta=4983.2,5169.4
Exp/Cntr=0.3,0.1

Type RM Length L Ch R = 1,2323,402,402,402
BEGIN DESCRIPTION:
Mapping XS 8bb25020
END DESCRIPTION:
XS GIS Cut Line= 4
      2774210.88      7092400.53      2774148.38      7092619.31
      2774146.60      7092842.94      2773702.09      7093210.55
#Sta/Elev= 30
  4789.4  544.65  4950.1  540.61  4975.3  539.47  4982.6  537.02  4991.7  533.08
  4998.5  528.64  4999.0  527.84  5005.1  527.84  5005.6  528.64  5009.1  531.34
  5014.0  533.84  5016.9  533.84  5022.6  535.96  5079.3  535.92  5112.6  535.95
  5132.6  535.17  5142.6  531.37  5152.6  536.04  5212.6  539.08  5244.9  539.52
  5321.0  537.28  5357.2  536.18  5383.7  536.90  5387.6  537.02  5413.2  539.36
  5449.7  539.62  5456.2  540.36  5470.5  540.62  5655.5  540.53  5817.4  541.79
#Mann=6,-1,0
  4789.4    0.05       0  4998.5    0.07       0  5005.6    0.05       0
  5079.3    0.05       0  5321.0    0.08       0  5383.7    0.05       0
Bank Sta=4982.6,5387.6
Exp/Cntr=0.3,0.1

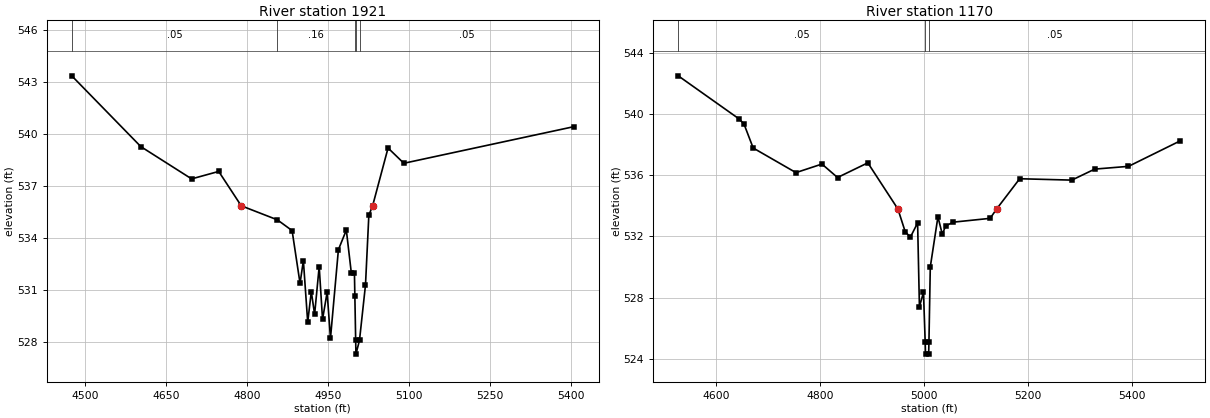
Type RM Length L Ch R = 1,1921,751,751,751
BEGIN DESCRIPTION:
Mapping XS 9b40e89d
END DESCRIPTION:
XS GIS Cut Line= 3
      2774161.42      7092361.47      2773856.45      7092780.60
      2773614.24      7093113.96
#Sta/Elev= 30
  4474.6  543.34  4602.6  539.26  4696.7  537.40  4746.9  537.83  4788.6  535.85
  4855.6  535.04  4882.9  534.42  4897.6  531.38  4903.8  532.69  4911.8  529.14
  4918.5  530.90  4924.6  529.59  4933.1  532.35  4939.3  529.30  4947.8  530.87
  4954.0  528.21  4968.7  533.32  4983.4  534.45  4992.6  531.99  4998.4  531.99
  4999.2  530.64  5000.7  528.10  5001.2  527.30  5007.8  528.10  5018.9  531.29
  5025.1  535.30  5032.2  535.86  5060.7  539.18  5090.0  538.30  5405.0  540.41
#Mann=5,-1,0
  4474.6    0.05       0  4855.6    0.16       0  4999.2    0.05       0
  5000.7    0.03       0  5007.8    0.05       0
Bank Sta=4788.6,5032.2
Exp/Cntr=0.3,0.1

Type RM Length L Ch R = 1,1170,0,0,0
BEGIN DESCRIPTION:
MIDDLE FORK TURKEY CREEK TRIB 4 2.0
END DESCRIPTION:
XS GIS Cut Line= 3
      2774131.22      7092196.65      2773671.12      7092175.82
      2773374.92      7092585.48
#Sta/Elev= 30
  4526.7  542.50  4643.0  539.70  4653.1  539.36  4670.9  537.78  4753.2  536.17
  4803.2  536.73  4833.2  535.85  4891.5  536.81  4949.4  533.79  4963.4  532.31
  4973.4  531.95  4987.3  532.88  4990.8  527.40  4998.6  528.34  5001.9  525.10
  5002.5  524.30  5008.6  524.30  5009.1  525.10  5011.7  530.00  5026.4  533.28
  5034.9  532.13  5041.1  532.68  5055.8  532.93  5126.9  533.18  5139.3  533.79
  5183.7  535.77  5284.0  535.68  5328.1  536.40  5393.1  536.58  5492.8  538.25
#Mann=3,-1,0
  4526.7    0.05       0  5001.9    0.03       0  5009.1    0.05       0
Bank Sta=4949.4,5139.3
Exp/Cntr=0.3,0.1

Chan Stop Cuts=-1