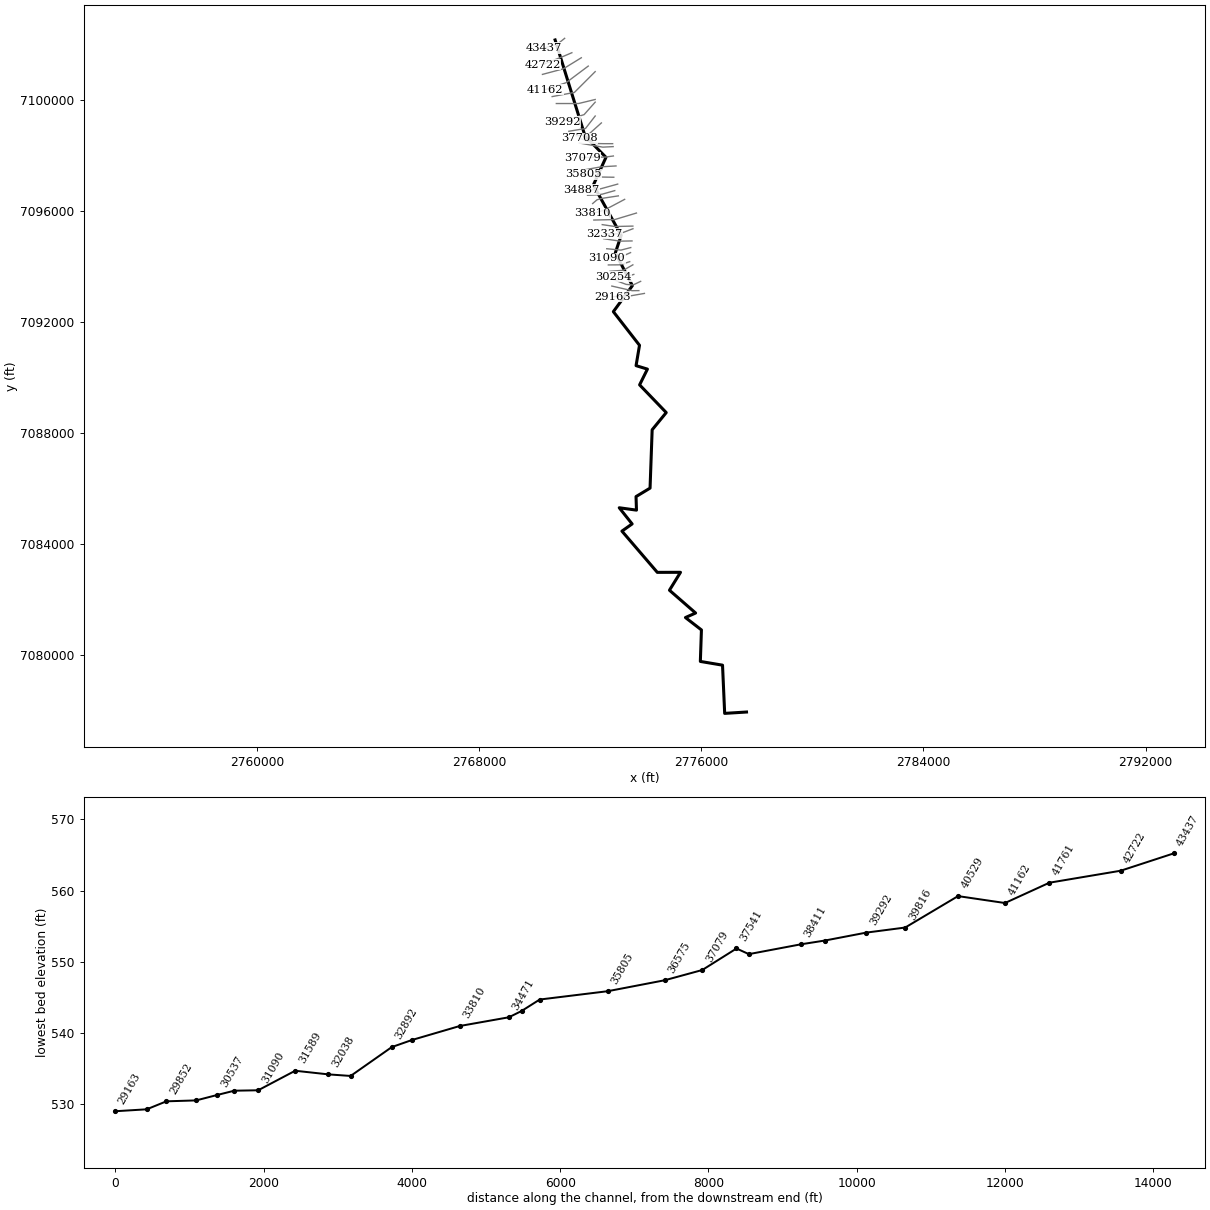
--- MIDDLE FORK TURKEY CREEK.prj (project) ---

Proj Title=MIDDLE FORK TURKEY CREEK Base Level Engineering
Current Plan=p01
Default Exp/Contr=0.3,0.1
English Units
Geom File=g01
Flow File=f01
Plan File=p01
BEGIN DESCRIPTION:
MIDDLE FORK TURKEY CREEK
END DESCRIPTION:

--- MIDDLE FORK TURKEY CREEK.p01 (plan) ---

Plan Title=Multiple Run
Short Identifier=Multiple
Geom File=g01
Flow File=f01
Subcritical Flow
K Sum by GR= 0
Std Step Tol= 0.01
Critical Tol= 0.01
Num of Std Step Trials= 20
Max Error Tol= 0.3
Flow Tol Ratio= 0.001
Split Flow NTrial= 30
Split Flow Tol= 0.02
Split Flow Ratio= 0.02
Log Output Level= 0
Friction Slope Method= 1
Unsteady Friction Slope Method= 2
Unsteady Bridges Friction Slope Method= 1
Parabolic Critical Depth
Global Vel Dist=  1 , 1 , 1
Global Log Level= 0
CheckData=True
Encroach Param= -1, 0, 0, 0
BEGIN DESCRIPTION:
Multiple Run
END DESCRIPTION:

--- MIDDLE FORK TURKEY CREEK.f01 (steady flow) ---

Flow Title=Multiple
Program Version=5.07
Number of Profiles= 7
Profile Names=10-year,25-year,50-year,1pct_min,100-year,1pct_plu,500-year
River Rch & RM=MIDDLE FORK TURK,Reach-1         ,43437
     700     935    1124     670    1337    2667    1887
River Rch & RM=MIDDLE FORK TURK,Reach-1         ,42722
     895    1208    1462     876    1748    3488    2495
River Rch & RM=MIDDLE FORK TURK,Reach-1         ,37708
    1177    1607    1960    1182    2359    4706    3411
River Rch & RM=MIDDLE FORK TURK,Reach-1         ,28788
    2048    2864    3548    2168    4327    8633    6432
River Rch & RM=MIDDLE FORK TURK,Reach-1         ,16362
    2656    3755    4687    2885    5755   11484    8674
River Rch & RM=MIDDLE FORK TURK,Reach-1         ,8156
    2649    3732    4646    2851    5689   11352    8528
Boundary for River Rch & Prof#=MIDDLE FORK TURK,Reach-1         , 1
Up Type= 0
Dn Type= 3
Dn Slope=0.00166
Boundary for River Rch & Prof#=MIDDLE FORK TURK,Reach-1         , 2
Up Type= 0
Dn Type= 3
Dn Slope=0.00166
Boundary for River Rch & Prof#=MIDDLE FORK TURK,Reach-1         , 3
Up Type= 0
Dn Type= 3
Dn Slope=0.00166
Boundary for River Rch & Prof#=MIDDLE FORK TURK,Reach-1         , 4
Up Type= 0
Dn Type= 3
Dn Slope=0.00166
Boundary for River Rch & Prof#=MIDDLE FORK TURK,Reach-1         , 5
Up Type= 0
Dn Type= 3
Dn Slope=0.00166
Boundary for River Rch & Prof#=MIDDLE FORK TURK,Reach-1         , 6
Up Type= 0
Dn Type= 3
Dn Slope=0.00166
Boundary for River Rch & Prof#=MIDDLE FORK TURK,Reach-1         , 7
Up Type= 0
Dn Type= 3
Dn Slope=0.00166
DSS Import GetInterval= 0
DSS Import GetPeak= 0
DSS Import FillOption= 0

--- MIDDLE FORK TURKEY CREEK.g01 (geometry) ---

Geom Title=Existing Conditions

River Reach=MIDDLE FORK TURK,Reach-1
Reach XY= 30
      2770730.99      7102166.54      2771809.13      7098702.02
      2772562.97      7097935.23      2772108.79      7096937.99
      2773111.25      7095123.56      2772900.17      7094492.05
      2773514.74      7093310.07      2772829.03      7092372.28
      2773770.95      7091160.36      2773647.24      7090426.30
      2774056.34      7090301.23      2773774.47      7089733.89
      2774734.09      7088734.94      2774226.75      7088114.25
      2774151.21      7086011.74      2773645.89      7085706.34
      2773661.86      7085218.38      2773041.36      7085303.67
      2773505.11      7084720.78      2773138.04      7084461.75
      2774412.62      7082975.16      2775248.18      7082976.90
      2774850.13      7082331.11      2775792.30      7081509.43
      2775425.75      7081346.36      2776001.93      7080900.22
      2775962.80      7079764.44      2776761.79      7079629.81
      2776839.19      7077892.02      2777625.59      7077940.71

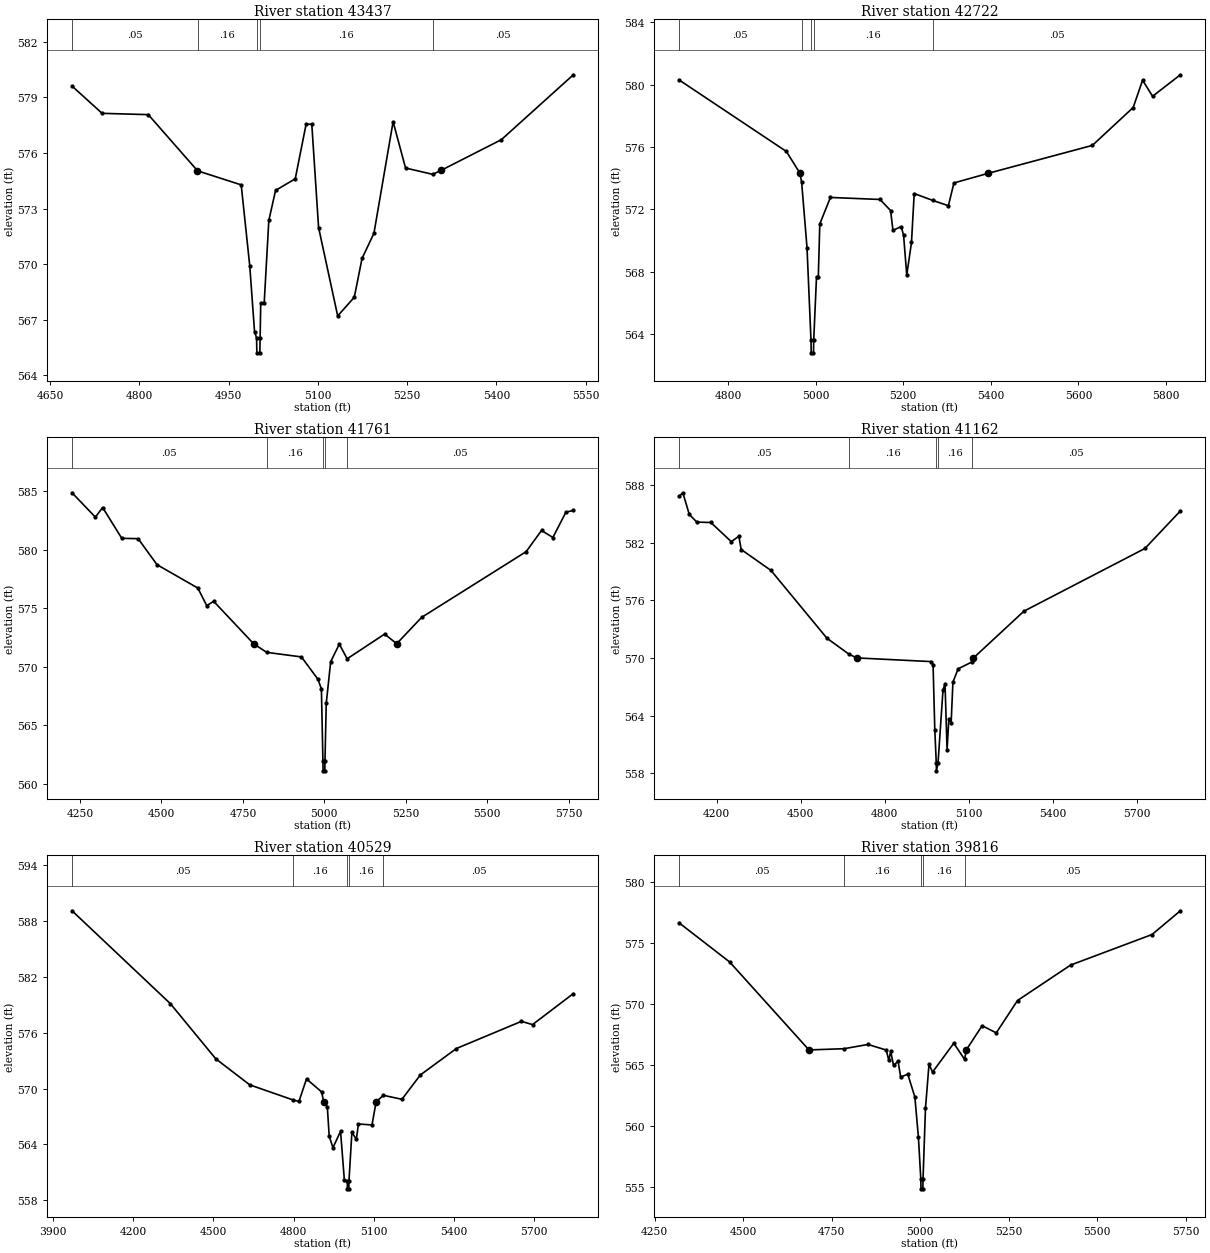
Type RM Length L Ch R = 1,43437,715,715,715
BEGIN DESCRIPTION:
MIDDLE FORK TURKEY CREEK 46.0
END DESCRIPTION:
XS GIS Cut Line= 3
      2771075.03      7102225.02      2770825.00      7102025.00
      2770325.01      7101875.00
#Sta/Elev= 30
  4687.0  579.61  4737.5  578.14  4815.1  578.07  4897.6  575.05  4897.8  575.04
  4971.2  574.28  4985.6  569.90  4993.6  566.37  4997.0  566.02  4997.5  565.22
  5002.5  565.22  5003.0  566.02  5004.0  567.90  5009.8  567.90  5017.6  572.36
  5028.9  573.98  5062.0  574.61  5080.3  577.56  5089.8  577.55  5101.2  571.98
  5133.3  567.21  5161.2  568.22  5174.2  570.31  5194.2  571.67  5226.4  577.69
  5247.3  575.19  5292.9  574.85  5306.8  575.06  5408.3  576.72  5529.2  580.22
#Mann=5,-1,0
  4687.0    0.05       0  4897.8    0.16       0  4997.0    0.07       0
  5003.0    0.16       0  5292.9    0.05       0
Bank Sta=4897.6,5306.8
Exp/Cntr=0.3,0.1

Type RM Length L Ch R = 1,42722,961,961,961
BEGIN DESCRIPTION:
MIDDLE FORK TURKEY CREEK 45.0
END DESCRIPTION:
XS GIS Cut Line= 3
      2771334.73      7101706.71      2771042.58      7101581.50
      2770274.97      7101274.99
#Sta/Elev= 30
  4688.3  580.30  4933.3  575.71  4964.2  574.32  4968.1  573.74  4980.4  569.54
  4989.5  563.59  4990.0  562.79  4995.2  562.79  4995.7  563.59  5002.1  567.68
  5006.2  567.68  5009.6  571.06  5033.8  572.76  5147.0  572.63  5171.2  571.92
  5176.6  570.65  5195.5  570.89  5200.9  570.32  5208.1  567.78  5218.9  569.87
  5225.1  573.01  5267.3  572.57  5303.2  572.23  5315.8  573.69  5394.3  574.31
  5631.9  576.10  5725.0  578.53  5746.5  580.28  5769.3  579.25  5832.7  580.63
#Mann=5,-1,0
  4688.3    0.05       0  4968.1    0.16       0  4989.5    0.07       0
  4995.7    0.16       0  5267.3    0.05       0
Bank Sta=4964.2,5394.3
Exp/Cntr=0.3,0.1

Type RM Length L Ch R = 1,41761,599,599,599
BEGIN DESCRIPTION:
MIDDLE FORK TURKEY CREEK 44.0
END DESCRIPTION:
XS GIS Cut Line= 3
      2771675.03      7101525.02      2771025.00      7101125.00
      2770274.96      7100924.99
#Sta/Elev= 30
  4225.3  584.86  4296.9  582.78  4319.3  583.60  4378.0  580.97  4428.3  580.94
  4486.2  578.72  4611.7  576.72  4638.9  575.22  4660.2  575.59  4782.8  571.97
  4823.0  571.23  4929.8  570.84  4980.8  568.92  4991.1  568.09  4995.8  561.91
  4996.3  561.11  5001.5  561.11  5002.0  561.91  5006.0  566.88  5019.6  570.43
  5046.1  571.93  5070.2  570.68  5185.2  572.79  5222.4  571.97  5299.0  574.22
  5619.9  579.83  5667.1  581.64  5702.0  581.04  5742.1  583.21  5764.8  583.35
#Mann=5,-1,0
  4225.3    0.05       0  4823.0    0.16       0  4995.8    0.07       0
  5002.0    0.16       0  5070.2    0.05       0
Bank Sta=4782.8,5222.4
Exp/Cntr=0.3,0.1

Type RM Length L Ch R = 1,41162,633,633,633
BEGIN DESCRIPTION:
MIDDLE FORK TURKEY CREEK 43.0
END DESCRIPTION:
XS GIS Cut Line= 3
      2771925.03      7101225.02      2771125.00      7100625.00
      2770375.01      7100375.00
#Sta/Elev= 30
  4065.8  586.81  4079.4  587.17  4102.3  584.92  4129.4  584.12  4179.4  584.08
  4252.3  582.09  4279.4  582.65  4287.7  581.27  4394.0  579.10  4594.0  572.05
  4672.1  570.40  4700.5  570.00  4965.8  569.62  4973.1  569.27  4979.4  562.46
  4984.6  559.06  4985.1  558.26  4990.8  559.06  5008.5  566.64  5015.8  567.33
  5023.1  560.45  5029.4  563.61  5037.7  563.26  5044.0  567.48  5062.7  568.87
  5110.6  569.56  5117.5  570.00  5297.7  574.86  5729.9  581.38  5856.4  585.28
#Mann=5,-1,0
  4065.8    0.05       0  4672.1    0.16       0  4984.6    0.07       0
  4990.8    0.16       0  5110.6    0.05       0
Bank Sta=4700.5,5117.5
Exp/Cntr=0.3,0.1

Type RM Length L Ch R = 1,40529,713,713,713
BEGIN DESCRIPTION:
MIDDLE FORK TURKEY CREEK 42.0
END DESCRIPTION:
XS GIS Cut Line= 3
      2772175.01      7101025.01      2771425.00      7100275.00
      2770625.02      7100125.00
#Sta/Elev= 30
  3971.7  589.08  4339.4  579.11  4509.1  573.19  4636.4  570.39  4799.5  568.76
  4820.2  568.61  4848.5  571.03  4905.1  569.63  4912.4  568.59  4926.3  568.04
  4933.4  564.87  4947.5  563.65  4975.8  565.41  4990.0  560.19  5000.9  560.03
  5001.4  559.23  5006.7  559.23  5007.2  560.03  5018.2  565.30  5034.9  564.55
  5042.6  566.19  5093.4  566.09  5108.9  568.59  5136.3  569.27  5205.3  568.84
  5274.0  571.45  5408.8  574.29  5652.2  577.21  5693.7  576.86  5846.3  580.19
#Mann=5,-1,0
  3971.7    0.05       0  4799.5    0.16       0  5000.9    0.07       0
  5007.2    0.16       0  5136.3    0.05       0
Bank Sta=4912.4,5108.9
Exp/Cntr=0.3,0.1

Type RM Length L Ch R = 1,39816,524,524,524
BEGIN DESCRIPTION:
MIDDLE FORK TURKEY CREEK 41.0
END DESCRIPTION:
XS GIS Cut Line= 3
      2772173.72      7100020.25      2771575.00      7099875.00
      2770774.99      7099875.00
#Sta/Elev= 30
  4319.2  576.67  4461.9  573.46  4686.2  566.23  4785.2  566.33  4853.0  566.68
  4904.4  566.22  4911.8  565.37  4917.0  566.12  4925.0  564.96  4937.8  565.30
  4945.3  564.00  4965.3  564.24  4985.3  562.36  4995.3  559.08  5002.1  555.62
  5002.6  554.82  5007.9  554.82  5008.4  555.62  5015.3  561.44  5025.3  565.05
  5035.3  564.41  5095.3  566.78  5125.9  565.45  5130.6  566.23  5175.3  568.22
  5215.3  567.63  5275.3  570.29  5425.3  573.20  5655.3  575.71  5735.3  577.66
#Mann=5,-1,0
  4319.2    0.05       0  4785.2    0.16       0  5002.1    0.07       0
  5008.4    0.16       0  5125.9    0.05       0
Bank Sta=4686.2,5130.6
Exp/Cntr=0.3,0.1

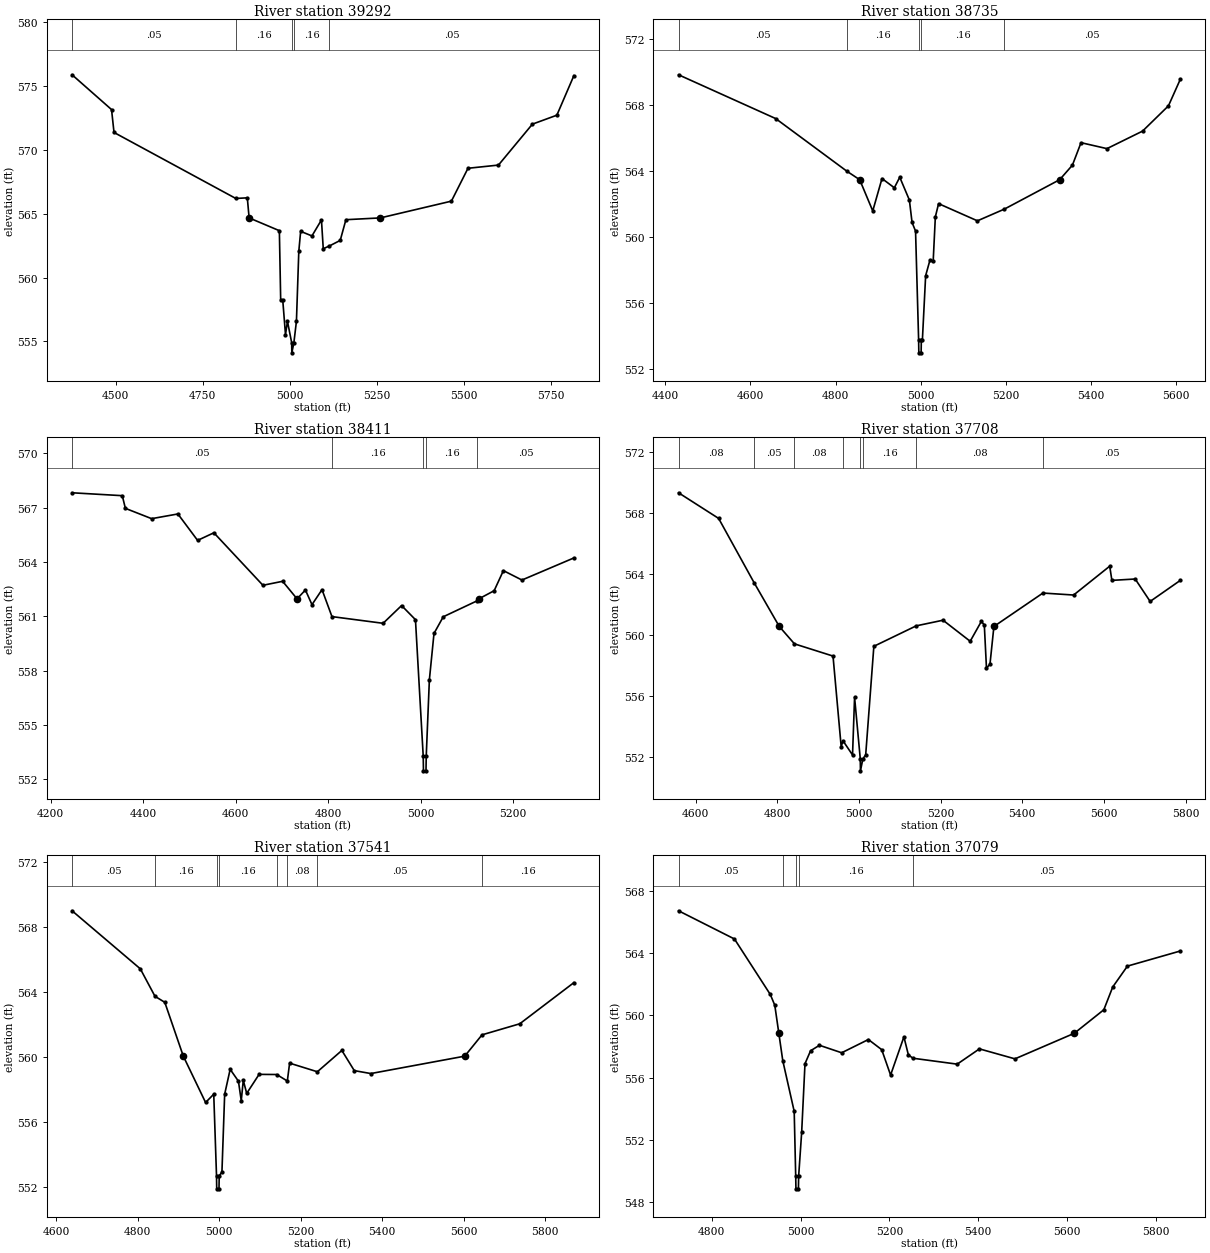
Type RM Length L Ch R = 1,39292,557,557,557
BEGIN DESCRIPTION:
MIDDLE FORK TURKEY CREEK 40.0
END DESCRIPTION:
XS GIS Cut Line= 3
      2772175.01      7099925.02      2771775.00      7099475.00
      2770974.96      7099224.99
#Sta/Elev= 30
  4375.0  575.85  4488.3  573.13  4495.4  571.34  4845.0  566.18  4878.0  566.23
  4883.2  564.66  4970.0  563.66  4973.8  558.24  4979.7  558.24  4987.6  555.54
  4993.3  556.57  5005.3  554.91  5005.8  554.11  5011.7  554.91  5019.0  556.58
  5025.8  562.05  5031.1  563.61  5063.5  563.25  5090.8  564.50  5096.0  562.25
  5113.8  562.47  5144.7  562.90  5161.0  564.52  5260.0  564.66  5463.8  565.97
  5511.4  568.54  5598.9  568.79  5696.3  571.99  5766.5  572.69  5815.3  575.78
#Mann=5,-1,0
  4375.0    0.05       0  4845.0    0.16       0  5005.3    0.07       0
  5011.7    0.16       0  5113.8    0.05       0
Bank Sta=4883.2,5260
Exp/Cntr=0.3,0.1

Type RM Length L Ch R = 1,38735,324,324,324
BEGIN DESCRIPTION:
MIDDLE FORK TURKEY CREEK 39.0
END DESCRIPTION:
XS GIS Cut Line= 3
      2772175.02      7099425.03      2771825.00      7098975.00
      2771225.00      7098875.00
#Sta/Elev= 30
  4431.2  569.83  4659.3  567.18  4826.7  563.99  4856.6  563.48  4887.3  561.59
  4909.0  563.55  4938.0  562.99  4950.7  563.63  4973.3  562.25  4979.6  560.89
  4987.8  560.37  4995.0  553.80  4995.5  553.00  5000.9  553.00  5001.4  553.80
  5003.9  553.80  5011.5  557.67  5021.6  558.61  5029.2  558.54  5034.3  561.23
  5041.9  562.03  5133.1  560.99  5196.4  561.70  5326.3  563.48  5356.2  564.36
  5376.4  565.72  5437.3  565.36  5520.9  566.42  5581.7  567.95  5609.6  569.56
#Mann=5,-1,0
  4431.2    0.05       0  4826.7    0.16       0  4995.0    0.07       0
  5001.4    0.16       0  5196.4    0.05       0
Bank Sta=4856.6,5326.3
Exp/Cntr=0.3,0.1

Type RM Length L Ch R = 1,38411,703,703,703
BEGIN DESCRIPTION:
MIDDLE FORK TURKEY CREEK 38.0
END DESCRIPTION:
XS GIS Cut Line= 3
      2772397.28      7099175.73      2771903.96      7098731.74
      2771482.78      7098712.76
#Sta/Elev= 30
  4246.1  567.83  4354.7  567.67  4361.4  566.97  4418.2  566.40  4475.0  566.66
  4517.6  565.20  4552.8  565.62  4658.9  562.72  4701.5  562.94  4732.7  561.97
  4750.8  562.46  4765.0  561.65  4786.7  562.48  4808.2  560.99  4918.8  560.62
  4958.8  561.60  4988.8  560.82  5005.6  553.27  5006.1  552.47  5011.6  552.47
  5012.1  553.27  5018.9  557.50  5028.9  560.06  5048.9  560.98  5122.0  561.86
  5125.9  561.97  5159.0  562.42  5179.0  563.53  5219.1  563.01  5331.4  564.23
#Mann=5,-1,0
  4246.1    0.05       0  4808.2    0.16       0  5005.6    0.07       0
  5012.1    0.16       0  5122.0    0.05       0
Bank Sta=4732.7,5125.9
Exp/Cntr=0.3,0.1

Type RM Length L Ch R = 1,37708,167,167,167
BEGIN DESCRIPTION:
Mapping XS bf4ebd4f
END DESCRIPTION:
XS GIS Cut Line= 5
      2772803.24      7098428.17      2772476.95      7098428.17
      2772264.45      7098431.96      2772078.51      7098462.32
      2771604.22      7098625.47
#Sta/Elev= 30
  4558.4  569.31  4656.6  567.63  4743.2  563.43  4805.1  560.55  4842.3  559.41
  4936.7  558.61  4956.7  552.67  4961.1  553.06  4984.5  552.13  4989.5  555.91
  5003.4  551.89  5003.9  551.09  5010.0  551.89  5016.7  552.13  5036.7  559.25
  5140.4  560.59  5206.1  560.96  5272.6  559.58  5299.9  560.88  5307.2  560.65
  5312.5  557.81  5321.1  558.09  5330.7  560.55  5450.7  562.74  5525.9  562.61
  5614.3  564.50  5619.6  563.57  5676.7  563.66  5713.3  562.19  5787.2  563.57
#Mann=8,-1,0
  4558.4    0.08       0  4743.2    0.05       0  4842.3    0.08       0
  4961.1    0.16       0  5003.4    0.07       0  5010.0    0.16       0
  5140.4    0.08       0  5450.7    0.05       0
Bank Sta=4805.1,5330.7
Exp/Cntr=0.3,0.1

Type RM Length L Ch R = 1,37541,462,462,462
BEGIN DESCRIPTION:
MIDDLE FORK TURKEY CREEK 37.0
END DESCRIPTION:
XS GIS Cut Line= 3
      2772822.30      7098321.92      2772446.59      7098302.94
      2771604.18      7098450.93
#Sta/Elev= 30
  4639.0  568.98  4806.5  565.41  4842.5  563.72  4866.6  563.35  4912.0  560.04
  4966.7  557.19  4986.7  557.70  4993.5  552.68  4994.0  551.88  4999.6  551.88
  5000.1  552.68  5006.8  552.91  5013.5  557.70  5027.0  559.23  5047.3  558.50
  5054.2  557.30  5059.2  558.55  5067.6  557.75  5098.0  558.92  5141.3  558.91
  5167.3  558.51  5172.9  559.61  5241.0  559.08  5301.1  560.39  5331.6  559.15
  5372.2  558.97  5602.7  560.04  5645.1  561.35  5737.7  562.03  5870.5  564.56
#Mann=8,-1,0
  4639.0    0.05       0  4842.5    0.16       0  4993.5    0.07       0
  5000.1    0.16       0  5141.3    0.05       0  5167.3    0.08       0
  5241.0    0.05       0  5645.1    0.16       0
Bank Sta=4912,5602.7
Exp/Cntr=0.3,0.1

Type RM Length L Ch R = 1,37079,504,504,504
BEGIN DESCRIPTION:
MIDDLE FORK TURKEY CREEK 36.0
END DESCRIPTION:
XS GIS Cut Line= 3
      2772829.80      7097984.19      2772545.25      7097946.25
      2771702.83      7097927.28
#Sta/Elev= 30
  4725.2  566.70  4851.1  564.89  4931.8  561.33  4941.9  560.64  4951.0  558.84
  4959.9  557.08  4985.6  553.83  4989.0  549.66  4989.5  548.86  4995.1  548.86
  4995.6  549.66  5002.4  552.48  5009.9  556.89  5022.5  557.72  5042.5  558.07
  5092.5  557.59  5152.6  558.44  5182.6  557.79  5202.6  556.16  5232.6  558.61
  5242.6  557.46  5252.8  557.24  5352.6  556.86  5402.6  557.84  5482.6  557.20
  5616.2  558.84  5682.7  560.35  5702.7  561.81  5735.8  563.15  5854.9  564.12
#Mann=5,-1,0
  4725.2    0.05       0  4959.9    0.16       0  4989.0    0.07       0
  4995.6    0.16       0  5252.8    0.05       0
Bank Sta=4951,5616.2
Exp/Cntr=0.3,0.1

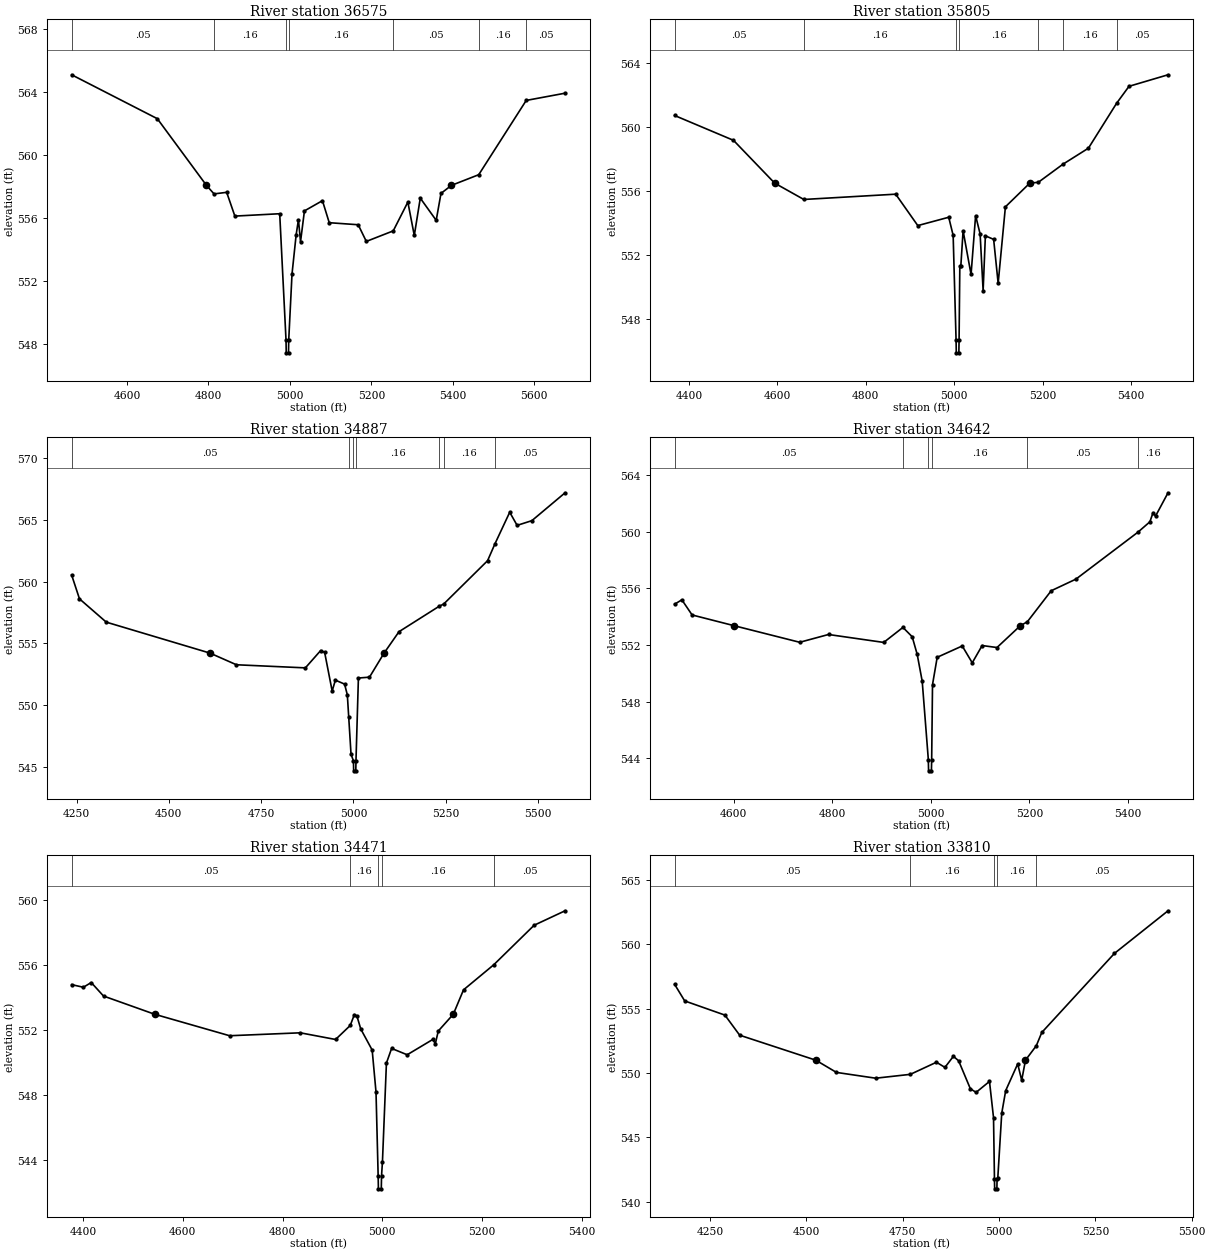
Type RM Length L Ch R = 1,36575,770,770,770
BEGIN DESCRIPTION:
MIDDLE FORK TURKEY CREEK 35.0
END DESCRIPTION:
XS GIS Cut Line= 3
      2772925.00      7097625.00      2772392.47      7097594.21
      2771725.05      7097475.01
#Sta/Elev= 30
  4464.1  565.10  4674.4  562.31  4795.1  558.07  4813.7  557.53  4844.7  557.63
  4864.8  556.12  4974.9  556.27  4990.4  548.23  4990.9  547.43  4996.5  547.43
  4997.0  548.23  5005.1  552.44  5015.3  554.94  5020.9  555.89  5026.0  554.49
  5035.6  556.45  5079.8  557.10  5096.5  555.70  5167.6  555.57  5187.5  554.51
  5253.6  555.18  5289.5  557.01  5305.3  554.89  5320.0  557.26  5359.1  555.85
  5370.8  557.56  5396.3  558.07  5463.5  558.75  5580.1  563.47  5675.5  563.93
#Mann=7,-1,0
  4464.1    0.05       0  4813.7    0.16       0  4990.4    0.07       0
  4997.0    0.16       0  5253.6    0.05       0  5463.5    0.16       0
  5580.1    0.05       0
Bank Sta=4795.1,5396.3
Exp/Cntr=0.3,0.1

Type RM Length L Ch R = 1,35805,918,918,918
BEGIN DESCRIPTION:
Mapping XS 7db01d9d
END DESCRIPTION:
XS GIS Cut Line= 3
      2772845.03      7097217.68      2772199.94      7097229.06
      2771738.52      7097323.62
#Sta/Elev= 30
  4367.5  560.70  4500.7  559.15  4593.8  556.48  4659.8  555.46  4867.6  555.79
  4917.6  553.83  4987.6  554.35  4997.6  553.22  5004.2  546.69  5004.7  545.89
  5010.5  545.89  5011.0  546.69  5012.7  551.32  5015.0  551.32  5020.1  553.51
  5038.1  550.78  5048.4  554.45  5058.6  553.31  5065.4  549.77  5070.5  553.19
  5089.2  552.97  5099.4  550.23  5115.8  555.00  5171.0  556.48  5190.2  556.53
  5246.0  557.66  5303.6  558.66  5367.3  561.46  5395.4  562.52  5483.7  563.24
#Mann=7,-1,0
  4367.5    0.05       0  4659.8    0.16       0  5004.2    0.07       0
  5011.0    0.16       0  5190.2    0.05       0  5246.0    0.16       0
  5367.3    0.05       0
Bank Sta=4593.8,5171
Exp/Cntr=0.3,0.1

Type RM Length L Ch R = 1,34887,245,245,245
BEGIN DESCRIPTION:
MIDDLE FORK TURKEY CREEK 34.0
END DESCRIPTION:
XS GIS Cut Line= 3
      2772985.45      7096971.04      2772275.00      7096775.00
      2771675.00      7096775.00
#Sta/Elev= 30
  4236.6  560.52  4257.8  558.60  4330.4  556.72  4611.6  554.22  4683.1  553.28
  4869.9  553.03  4911.4  554.43  4922.1  554.28  4942.5  551.16  4951.2  552.04
  4976.1  551.72  4983.6  550.85  4987.4  549.03  4993.6  546.06  5000.2  545.52
  5000.7  544.72  5006.5  544.72  5007.0  545.52  5013.6  552.21  5043.6  552.28
  5083.1  554.22  5123.6  555.95  5232.9  558.01  5244.6  558.18  5363.6  561.68
  5383.7  563.05  5423.6  565.59  5443.6  564.53  5483.6  564.91  5573.6  567.16
#Mann=7,-1,0
  4236.6    0.05       0  4987.4    0.16       0  5000.2    0.07       0
  5007.0    0.16       0  5232.9    0.05       0  5244.6    0.16       0
  5383.7    0.05       0
Bank Sta=4611.6,5083.1
Exp/Cntr=0.3,0.1

Type RM Length L Ch R = 1,34642,171,171,171
BEGIN DESCRIPTION:
Mapping XS a7fb8fe5
END DESCRIPTION:
XS GIS Cut Line= 4
      2772879.16      7096735.76      2772439.00      7096610.54
      2772287.21      7096583.98      2771898.22      7096568.87
#Sta/Elev= 30
  4480.1  554.88  4494.8  555.19  4515.6  554.12  4601.0  553.36  4733.9  552.19
  4792.3  552.74  4904.3  552.18  4943.3  553.24  4962.1  552.58  4972.2  551.34
  4982.4  549.44  4994.8  543.91  4995.3  543.11  5001.1  543.11  5001.6  543.91
  5003.3  549.20  5012.8  551.13  5063.6  551.93  5083.9  550.74  5104.0  551.96
  5134.1  551.82  5181.4  553.36  5195.7  553.64  5244.1  555.83  5294.2  556.65
  5419.8  559.96  5444.3  560.70  5450.7  561.35  5455.7  561.10  5481.1  562.75
#Mann=6,-1,0
  4480.1    0.05       0  4943.3    0.16       0  4994.8    0.07       0
  5001.6    0.16       0  5195.7    0.05       0  5419.8    0.16       0
Bank Sta=4601,5181.4
Exp/Cntr=0.3,0.1

Type RM Length L Ch R = 1,34471,661,661,661
BEGIN DESCRIPTION:
Mapping XS 6732c10e
END DESCRIPTION:
XS GIS Cut Line= 4
      2773008.21      7096546.04      2772412.44      7096454.96
      2772241.68      7096405.63      2772082.87      7096269.51
#Sta/Elev= 30
  4377.0  554.78  4400.5  554.62  4416.3  554.91  4440.9  554.08  4543.5  552.96
  4693.8  551.64  4835.5  551.82  4906.3  551.41  4935.7  552.27  4944.0  552.94
  4949.1  552.85  4956.9  552.05  4979.7  550.76  4987.4  548.18  4991.7  543.03
  4992.2  542.23  4998.0  542.23  4998.5  543.03  5000.3  543.88  5008.3  549.96
  5018.7  550.86  5049.9  550.47  5101.2  551.41  5106.4  551.15  5112.3  551.93
  5142.4  552.96  5162.9  554.46  5223.5  556.00  5304.5  558.43  5366.6  559.32
#Mann=5,-1,0
  4377.0    0.05       0  4935.7    0.16       0  4991.7    0.07       0
  4998.5    0.16       0  5223.5    0.05       0
Bank Sta=4543.5,5142.4
Exp/Cntr=0.3,0.1

Type RM Length L Ch R = 1,33810,644,644,644
BEGIN DESCRIPTION:
MIDDLE FORK TURKEY CREEK 33.0
END DESCRIPTION:
XS GIS Cut Line= 3
      2773235.91      7096420.83      2772499.71      7096029.96
      2772068.60      7095912.73
#Sta/Elev= 30
  4158.4  556.89  4184.6  555.60  4288.9  554.50  4327.2  552.94  4524.7  551.00
  4578.3  550.05  4680.2  549.60  4770.1  549.90  4837.8  550.84  4859.8  550.44
  4881.8  551.30  4895.4  550.95  4925.8  548.78  4940.7  548.50  4975.4  549.35
  4985.9  546.54  4988.3  541.81  4988.8  541.01  4994.6  541.01  4995.1  541.81
  4997.0  541.86  5007.2  546.88  5017.5  548.64  5048.6  550.71  5059.0  549.44
  5068.8  551.00  5096.9  552.12  5111.1  553.15  5299.6  559.29  5438.7  562.60
#Mann=5,-1,0
  4158.4    0.05       0  4770.1    0.16       0  4988.3    0.07       0
  4995.1    0.16       0  5096.9    0.05       0
Bank Sta=4524.7,5068.8
Exp/Cntr=0.3,0.1

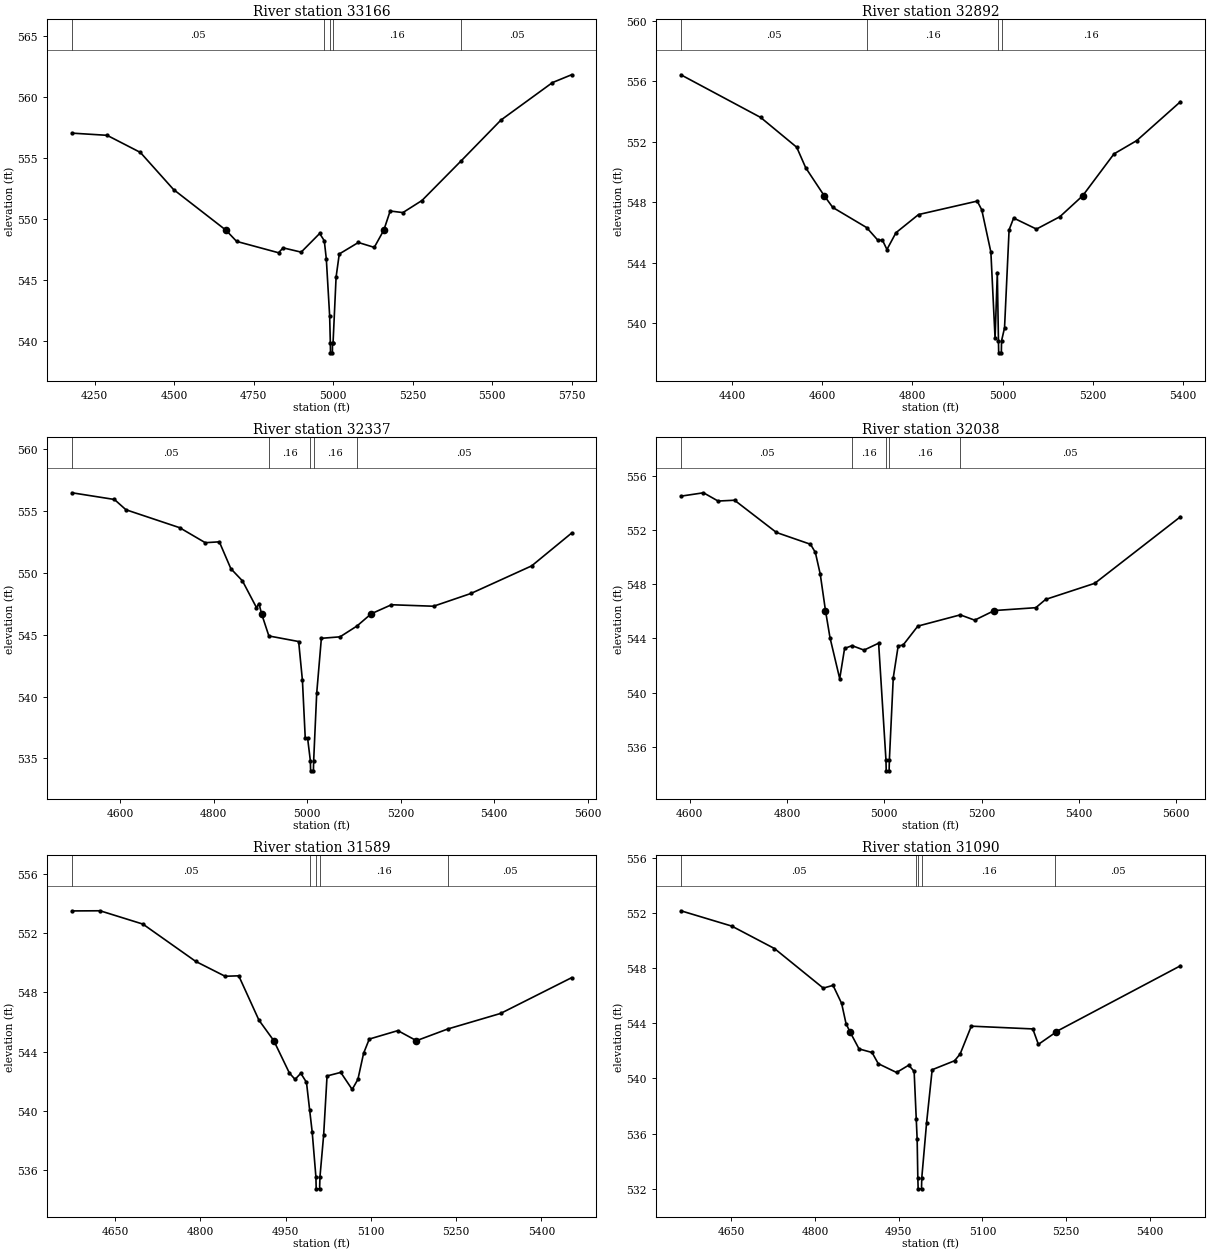
Type RM Length L Ch R = 1,33166,274,274,274
BEGIN DESCRIPTION:
MIDDLE FORK TURKEY CREEK 32.0
END DESCRIPTION:
XS GIS Cut Line= 3
      2773660.84      7095927.50      2772879.18      7095692.24
      2772124.97      7095675.00
#Sta/Elev= 30
  4178.6  557.05  4289.1  556.87  4393.6  555.47  4498.0  552.43  4662.7  549.10
  4696.4  548.18  4828.1  547.25  4842.6  547.65  4899.3  547.30  4957.5  548.83
  4972.0  548.23  4978.4  546.73  4988.8  542.09  4991.0  539.85  4991.5  539.05
  4997.4  539.05  4997.9  539.85  4999.5  539.85  5009.1  545.26  5019.1  547.15
  5079.1  548.09  5129.1  547.69  5159.1  549.10  5179.1  550.67  5219.1  550.54
  5279.1  551.53  5403.1  554.80  5527.4  558.12  5689.3  561.19  5749.3  561.83
#Mann=5,-1,0
  4178.6    0.05       0  4972.0    0.16       0  4991.0    0.07       0
  4997.9    0.16       0  5403.1    0.05       0
Bank Sta=4662.7,5159.1
Exp/Cntr=0.3,0.1

Type RM Length L Ch R = 1,32892,555,555,555
BEGIN DESCRIPTION:
Mapping XS a9215352
END DESCRIPTION:
XS GIS Cut Line= 3
      2773531.84      7095456.98      2772886.76      7095441.80
      2772429.16      7095509.87
#Sta/Elev= 30
  4286.7  556.43  4463.6  553.61  4543.6  551.64  4563.6  550.28  4604.7  548.43
  4623.6  547.66  4698.7  546.33  4723.7  545.49  4733.7  545.50  4743.7  544.88
  4763.7  545.99  4813.7  547.19  4943.9  548.08  4954.0  547.50  4974.2  544.71
  4983.5  539.01  4988.5  543.36  4991.0  538.85  4991.5  538.05  4997.4  538.05
  4997.9  538.85  5004.5  539.70  5014.6  546.18  5024.7  546.96  5075.3  546.23
  5127.3  547.05  5177.7  548.43  5247.2  551.20  5297.7  552.08  5394.6  554.65
#Mann=4,-1,0
  4286.7    0.05       0  4698.7    0.16       0  4991.0    0.07       0
  4997.9    0.16       0
Bank Sta=4604.7,5177.7
Exp/Cntr=0.3,0.1

Type RM Length L Ch R = 1,32337,299,299,299
BEGIN DESCRIPTION:
Mapping XS b285923b
END DESCRIPTION:
XS GIS Cut Line= 3
      2773535.65      7095362.11      2773068.91      7095183.76
      2772499.82      7095176.18
#Sta/Elev= 30
  4496.7  556.45  4587.5  555.91  4612.2  555.08  4727.2  553.63  4781.9  552.42
  4812.0  552.49  4836.7  550.32  4861.4  549.34  4891.5  547.18  4896.8  547.51
  4902.4  546.68  4918.0  544.89  4981.7  544.44  4989.8  541.30  4995.8  536.66
  5000.8  536.66  5006.8  534.80  5007.3  534.00  5013.3  534.00  5013.8  534.80
  5020.3  540.25  5030.3  544.70  5070.3  544.82  5106.4  545.69  5136.9  546.68
  5180.3  547.41  5270.3  547.29  5350.3  548.32  5480.3  550.55  5565.5  553.19
#Mann=5,-1,0
  4496.7    0.05       0  4918.0    0.16       0  5006.8    0.07       0
  5013.8    0.16       0  5106.4    0.05       0
Bank Sta=4902.4,5136.9
Exp/Cntr=0.3,0.1

Type RM Length L Ch R = 1,32038,449,449,449
BEGIN DESCRIPTION:
Mapping XS b93b1847
END DESCRIPTION:
XS GIS Cut Line= 3
      2773501.51      7094921.93      2773072.70      7094914.34
      2772480.77      7095001.62
#Sta/Elev= 30
  4581.8  554.49  4628.3  554.74  4658.3  554.13  4692.2  554.19  4778.3  551.81
  4848.3  550.94  4858.3  550.34  4868.4  548.73  4879.1  546.05  4888.4  544.05
  4908.4  541.02  4918.4  543.25  4933.7  543.46  4958.4  543.13  4988.4  543.64
  5003.5  535.02  5004.0  534.22  5010.0  534.22  5010.5  535.02  5018.5  541.09
  5028.6  543.44  5038.7  543.50  5069.0  544.90  5156.3  545.73  5185.9  545.34
  5226.4  546.05  5311.6  546.26  5331.8  546.87  5432.9  548.06  5609.0  552.97
#Mann=5,-1,0
  4581.8    0.05       0  4933.7    0.16       0  5003.5    0.07       0
  5010.5    0.16       0  5156.3    0.05       0
Bank Sta=4879.1,5226.4
Exp/Cntr=0.3,0.1

Type RM Length L Ch R = 1,31589,499,499,499
BEGIN DESCRIPTION:
Mapping XS 40c9a0aa
END DESCRIPTION:
XS GIS Cut Line= 3
      2773455.96      7094682.87      2773103.06      7094591.80
      2772590.79      7094641.13
#Sta/Elev= 30
  4573.8  553.49  4623.3  553.50  4698.7  552.60  4791.7  550.08  4843.3  549.08
  4867.3  549.11  4902.8  546.12  4929.0  544.73  4956.4  542.55  4966.4  542.12
  4976.5  542.53  4986.5  541.92  4992.0  540.08  4996.6  538.55  5003.1  535.53
  5003.6  534.73  5009.6  534.73  5010.2  535.53  5016.7  538.35  5022.7  542.35
  5046.8  542.59  5066.9  541.44  5077.0  542.12  5087.0  543.88  5097.0  544.84
  5147.3  545.41  5180.0  544.73  5235.1  545.52  5328.1  546.57  5452.9  548.98
#Mann=5,-1,0
  4573.8    0.05       0  4992.0    0.16       0  5003.1    0.07       0
  5010.2    0.16       0  5235.1    0.05       0
Bank Sta=4929,5180
Exp/Cntr=0.3,0.1

Type RM Length L Ch R = 1,31090,322,322,322
BEGIN DESCRIPTION:
Mapping XS 4d29e396
END DESCRIPTION:
XS GIS Cut Line= 3
      2773448.34      7094500.72      2773053.73      7094326.18
      2772590.78      7094303.41
#Sta/Elev= 30
  4559.8  552.16  4650.9  551.05  4727.5  549.42  4814.9  546.55  4832.4  546.75
  4847.8  545.44  4855.7  543.97  4862.6  543.39  4879.0  542.14  4902.3  541.88
  4913.4  541.07  4946.2  540.43  4968.0  540.96  4977.7  540.51  4981.5  537.05
  4983.1  535.59  4984.3  532.79  4984.9  531.99  4990.9  531.99  4991.4  532.79
  5000.0  536.78  5010.0  540.63  5050.1  541.28  5060.1  541.77  5080.1  543.79
  5190.3  543.59  5200.3  542.47  5230.5  543.32  5232.0  543.39  5454.8  548.17
#Mann=5,-1,0
  4559.8    0.05       0  4981.5    0.16       0  4984.3    0.07       0
  4991.4    0.16       0  5230.5    0.05       0
Bank Sta=4862.6,5232
Exp/Cntr=0.3,0.1

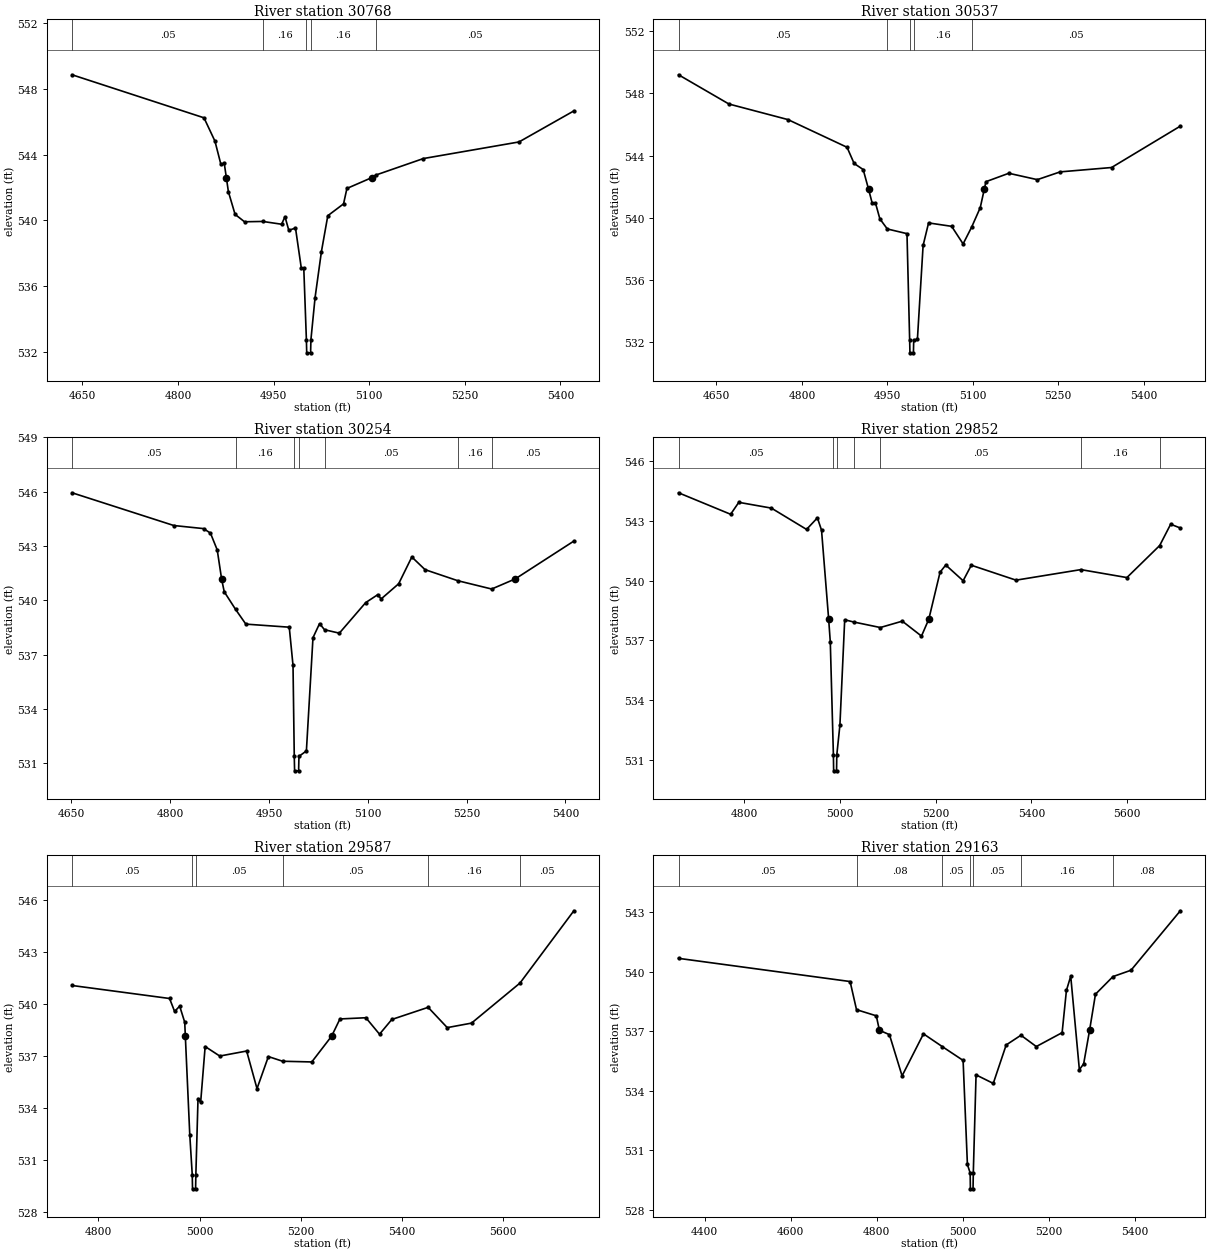
Type RM Length L Ch R = 1,30768,231,231,231
BEGIN DESCRIPTION:
Mapping XS 38b2c8a7
END DESCRIPTION:
XS GIS Cut Line= 3
      2773417.97      7094174.38      2773072.70      7094060.55
      2772648.87      7094056.77
#Sta/Elev= 30
  4633.7  548.86  4840.7  546.24  4857.9  544.82  4867.2  543.41  4872.5  543.47
  4875.8  542.60  4879.0  541.74  4889.5  540.36  4904.3  539.91  4932.9  539.93
  4962.5  539.76  4967.8  540.22  4973.8  539.39  4984.3  539.53  4993.4  537.09
  4997.3  537.09  5001.4  532.73  5001.9  531.93  5008.0  531.93  5008.5  532.73
  5015.0  535.29  5025.0  538.10  5035.0  540.28  5059.7  541.00  5065.0  541.94
  5104.2  542.60  5110.0  542.75  5185.0  543.76  5335.0  544.77  5421.1  546.66
#Mann=5,-1,0
  4633.7    0.05       0  4932.9    0.16       0  5001.4    0.07       0
  5008.5    0.16       0  5110.0    0.05       0
Bank Sta=4875.8,5104.2
Exp/Cntr=0.3,0.1

Type RM Length L Ch R = 1,30537,283,283,283
BEGIN DESCRIPTION:
Mapping XS 3e16f62a
END DESCRIPTION:
XS GIS Cut Line= 3
      2773531.83      7094060.54      2773186.54      7093863.23
      2772704.63      7093829.08
#Sta/Elev= 30
  4583.4  549.20  4671.9  547.32  4775.5  546.32  4879.2  544.54  4891.6  543.50
  4907.5  543.11  4917.1  541.83  4923.3  540.95  4929.1  540.96  4936.8  539.94
  4949.9  539.29  4984.4  538.99  4989.1  532.13  4989.6  531.33  4995.7  531.33
  4996.2  532.13  5002.7  532.20  5012.7  538.23  5022.3  539.68  5062.8  539.46
  5082.9  538.33  5097.9  539.41  5113.0  540.66  5120.0  541.83  5123.0  542.33
  5163.1  542.87  5213.2  542.46  5253.3  542.96  5343.5  543.24  5464.2  545.90
#Mann=5,-1,0
  4583.4    0.05       0  4949.9    0.16       0  4989.1    0.07       0
  4996.2    0.16       0  5097.9    0.05       0
Bank Sta=4917.1,5120
Exp/Cntr=0.3,0.1

Type RM Length L Ch R = 1,30254,402,402,402
BEGIN DESCRIPTION:
Mapping XS 2394cee2
END DESCRIPTION:
XS GIS Cut Line= 3
      2773566.00      7093715.24      2773239.66      7093616.58
      2772819.24      7093627.95
#Sta/Elev= 30
  4651.2  545.94  4805.6  544.13  4850.7  543.96  4861.2  543.71  4871.5  542.78
  4878.1  541.18  4882.1  540.47  4899.4  539.49  4914.9  538.68  4980.8  538.51
  4986.5  536.40  4988.4  531.37  4988.9  530.57  4995.0  530.57  4995.5  531.37
  5006.8  531.67  5016.8  537.93  5026.8  538.71  5034.3  538.37  5056.8  538.18
  5096.8  539.87  5115.2  540.31  5120.2  540.07  5146.8  540.91  5166.8  542.39
  5186.9  541.69  5236.5  541.08  5288.0  540.62  5323.8  541.18  5412.7  543.27
#Mann=7,-1,0
  4651.2    0.05       0  4899.4    0.16       0  4988.4    0.07       0
  4995.5    0.16       0  5034.3    0.05       0  5236.5    0.16       0
  5288.0    0.05       0
Bank Sta=4878.1,5323.8
Exp/Cntr=0.3,0.1

Type RM Length L Ch R = 1,29852,265,265,265
BEGIN DESCRIPTION:
Mapping XS a58ed83d
END DESCRIPTION:
XS GIS Cut Line= 4
      2773812.65      7093464.80      2773543.23      7093335.78
      2773292.79      7093354.75      2772826.03      7093529.31
#Sta/Elev= 30
  4663.0  544.41  4771.8  543.33  4788.9  543.93  4856.9  543.64  4930.4  542.57
  4953.1  543.15  4961.7  542.53  4976.6  538.06  4980.0  536.92  4986.5  531.24
  4987.0  530.44  4993.1  530.44  4993.6  531.24  5000.1  532.74  5010.1  538.03
  5028.5  537.92  5084.5  537.64  5130.4  537.96  5170.5  537.21  5185.8  538.06
  5209.3  540.42  5221.2  540.78  5257.5  539.99  5274.6  540.77  5368.0  540.02
  5503.4  540.55  5599.6  540.15  5668.1  541.76  5691.0  542.83  5711.2  542.64
#Mann=7,-1,0
  4663.0    0.05       0  4986.5    0.03       0  4993.6    0.05       0
  5028.5    0.16       0  5084.5    0.05       0  5503.4    0.16       0
  5668.1    0.05       0
Bank Sta=4976.6,5185.8
Exp/Cntr=0.3,0.1

Type RM Length L Ch R = 1,29587,424,424,424
BEGIN DESCRIPTION:
Mapping XS cc3aae53
END DESCRIPTION:
XS GIS Cut Line= 3
      2773747.85      7093131.32      2773503.08      7093128.72
      2772773.87      7093295.39
#Sta/Elev= 30
  4747.8  541.05  4940.7  540.30  4950.7  539.55  4960.7  539.86  4970.7  538.93
  4971.9  538.13  4980.7  532.43  4985.6  530.12  4986.1  529.32  4992.2  529.32
  4992.7  530.12  4997.0  534.53  5002.2  534.31  5011.1  537.53  5040.0  536.98
  5093.2  537.27  5113.7  535.10  5136.2  536.95  5164.4  536.68  5222.1  536.64
  5261.4  538.13  5277.8  539.12  5329.1  539.19  5356.1  538.24  5380.4  539.09
  5452.3  539.79  5490.1  538.62  5538.1  538.88  5634.0  541.19  5740.6  545.36
#Mann=6,-1,0
  4747.8    0.05       0  4985.6    0.07       0  4992.7    0.05       0
  5164.4    0.05       0  5452.3    0.16       0  5634.0    0.05       0
Bank Sta=4971.9,5261.4
Exp/Cntr=0.3,0.1

Type RM Length L Ch R = 1,29163,101,101,101
BEGIN DESCRIPTION:
Mapping XS efd4797d
END DESCRIPTION:
XS GIS Cut Line= 3
      2773947.81      7093029.89      2773384.16      7092931.67
      2772790.46      7092914.31
#Sta/Elev= 30
  4339.1  540.68  4737.8  539.51  4752.7  538.09  4798.7  537.78  4805.9  537.05
  4829.2  536.83  4858.6  534.75  4908.3  536.87  4952.5  536.22  5000.4  535.53
  5010.4  530.28  5016.8  529.85  5017.3  529.05  5023.5  529.05  5024.1  529.85
  5030.5  534.80  5070.5  534.37  5100.5  536.31  5134.8  536.80  5170.5  536.23
  5230.5  536.93  5240.5  539.06  5250.5  539.78  5270.6  535.06  5280.6  535.36
  5294.3  537.05  5308.0  538.87  5348.7  539.76  5390.6  540.08  5505.2  543.08
#Mann=7,-1,0
  4339.1    0.05       0  4752.7    0.08       0  4952.5    0.05       0
  5016.8    0.04       0  5024.1    0.05       0  5134.8    0.16       0
  5348.7    0.08       0
Bank Sta=4805.9,5294.3
Exp/Cntr=0.3,0.1