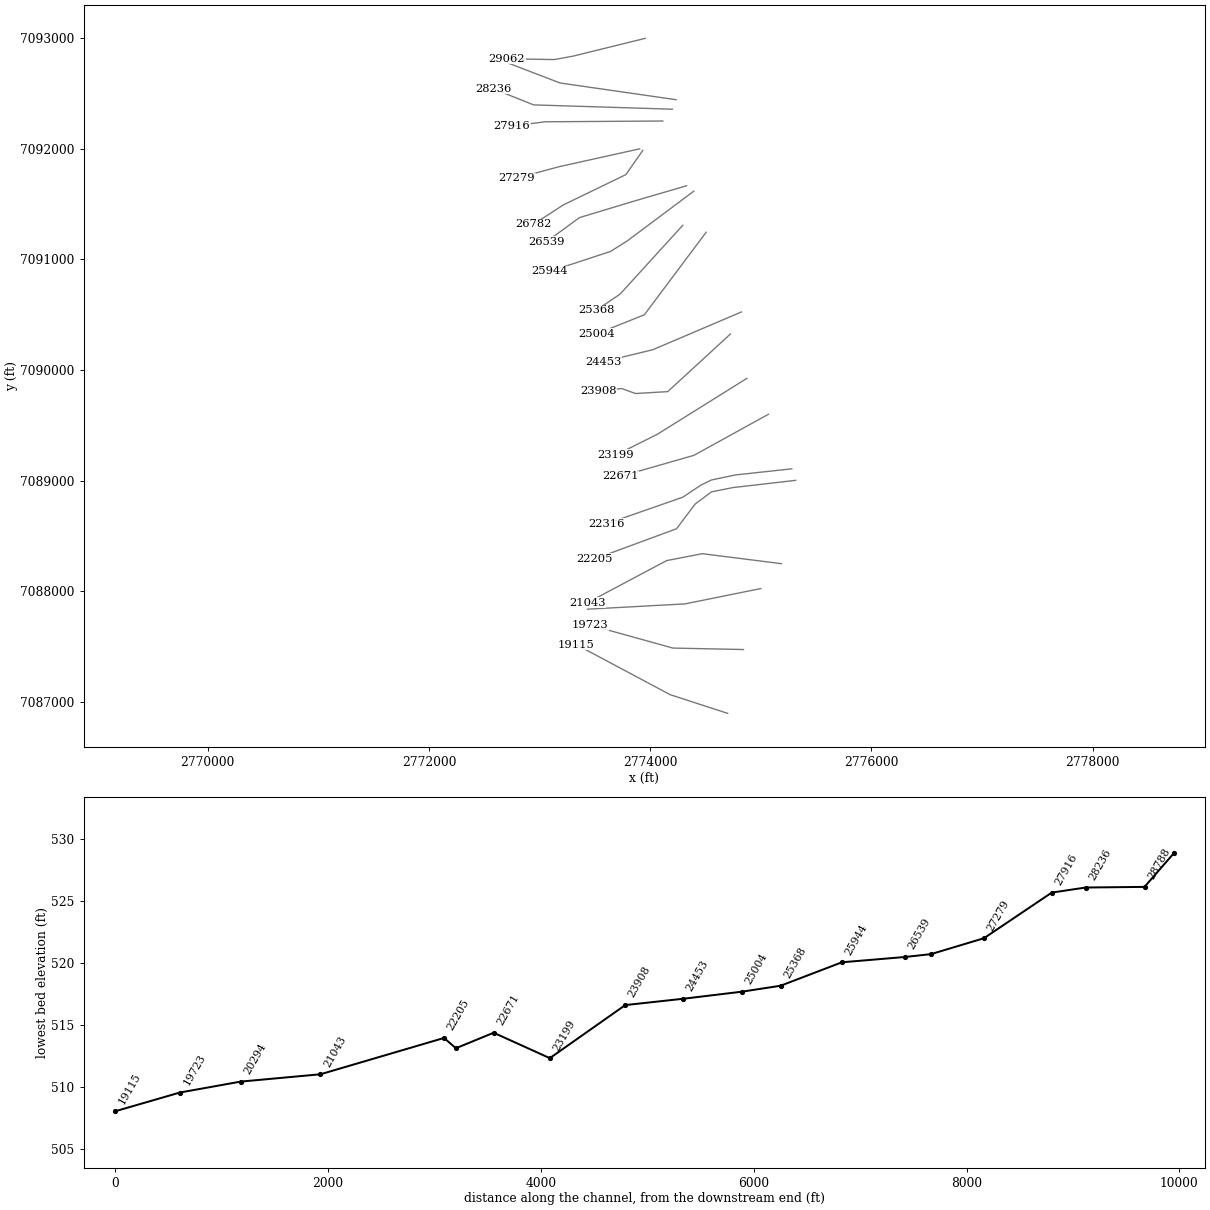
HEC-RAS study MIDDLE FORK TURKEY CREEK.prj: MIDDLE FORK TURKEY CREEK Base Level Engineering

--- MIDDLE FORK TURKEY CREEK.g01 (geometry) --- (continued)

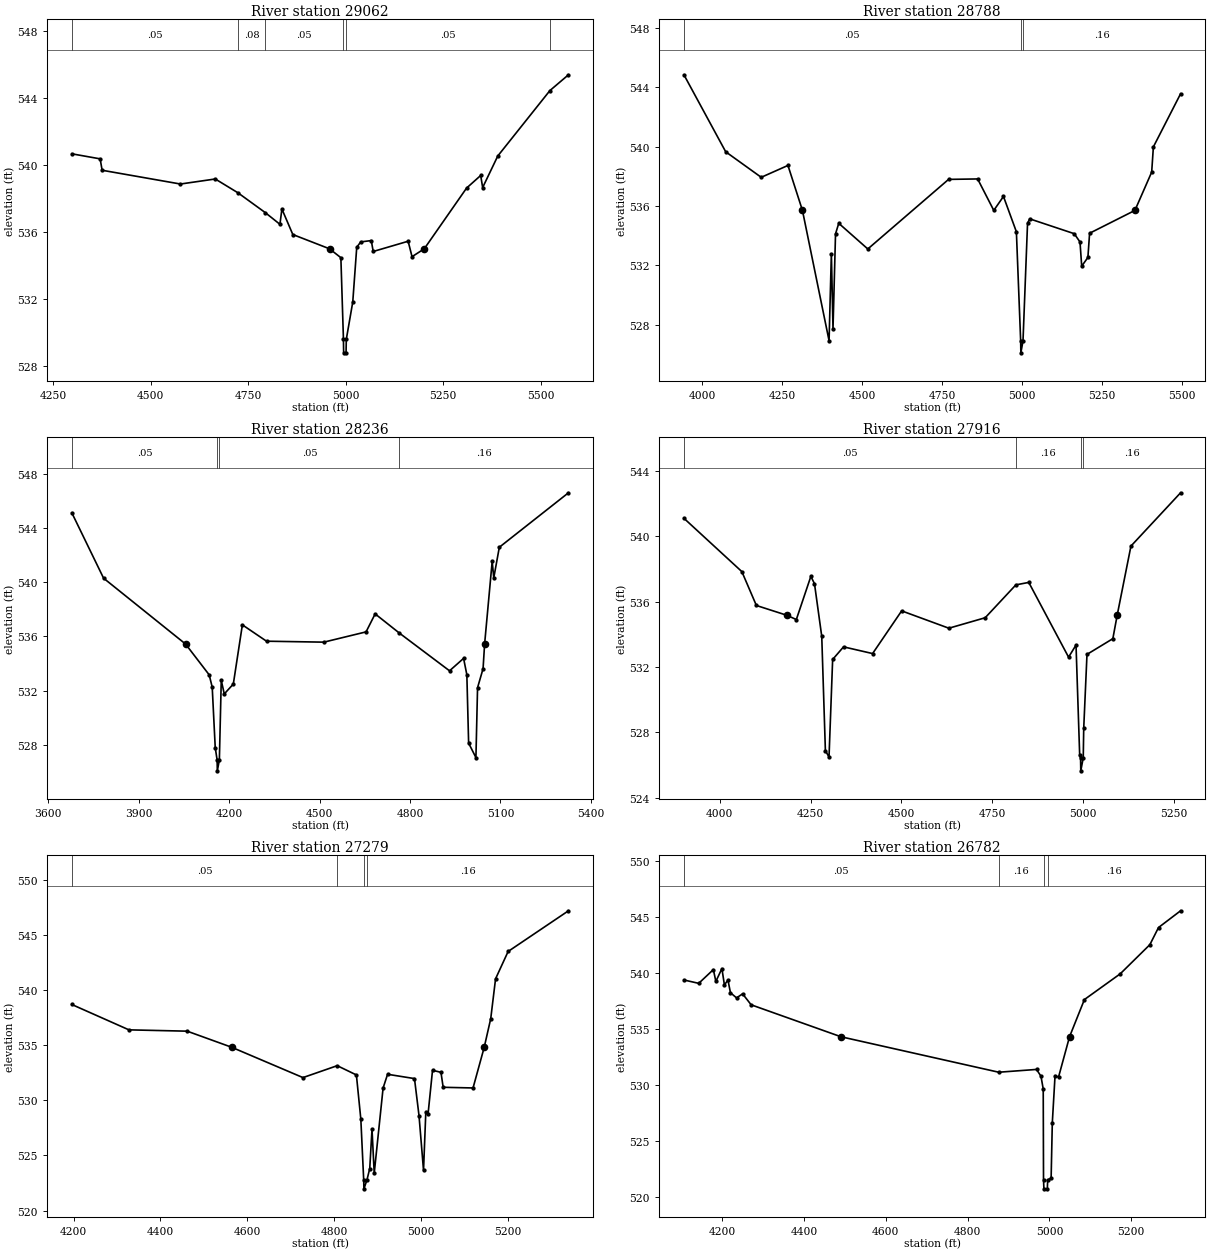
Type RM Length L Ch R = 1,29062,274,274,274
BEGIN DESCRIPTION:
Mapping XS 57d8e6dc
END DESCRIPTION:
XS GIS Cut Line= 4
      2773955.59      7092998.63      2773304.30      7092837.92
      2773134.16      7092806.67      2772703.63      7092813.61
#Sta/Elev= 30
  4297.2  540.67  4369.9  540.37  4375.0  539.69  4575.9  538.87  4665.3  539.17
  4723.3  538.35  4793.4  537.17  4831.2  536.47  4836.3  537.38  4864.3  535.86
  4958.5  535.01  4987.6  534.48  4994.2  529.61  4994.7  528.81  5000.9  528.81
  5001.5  529.61  5018.1  531.84  5028.3  535.10  5038.5  535.42  5065.6  535.50
  5070.6  534.85  5160.2  535.46  5170.2  534.54  5201.6  535.01  5310.2  538.63
  5346.4  539.38  5351.4  538.66  5390.2  540.54  5524.0  544.44  5571.6  545.38
#Mann=6,-1,0
  4297.2    0.05       0  4723.3    0.08       0  4793.4    0.05       0
  4994.2    0.03       0  5001.5    0.05       0  5524.0    0.16       0
Bank Sta=4958.5,5201.6
Exp/Cntr=0.3,0.1

Type RM Length L Ch R = 1,28788,552,552,552
BEGIN DESCRIPTION:
double Mapping XS 056db94b
END DESCRIPTION:
XS GIS Cut Line= 3
      2774234.32      7092443.95      2773186.24      7092594.86
      2772724.42      7092771.95
#Sta/Elev= 30
  3942.5  544.85  4073.2  539.66  4184.3  537.94  4267.9  538.74  4313.2  535.71
  4396.5  526.93  4403.7  532.79  4408.8  527.74  4416.7  534.13  4426.8  534.84
  4517.7  533.11  4770.3  537.80  4861.2  537.83  4911.7  535.71  4942.0  536.65
  4982.4  534.27  4995.8  526.91  4996.4  526.11  5003.1  526.91  5017.3  534.84
  5024.1  535.14  5163.4  534.14  5181.4  533.58  5186.7  531.95  5206.1  532.54
  5211.4  534.17  5353.2  535.71  5405.6  538.29  5410.9  539.99  5496.0  543.57
#Mann=3,-1,0
  3942.5    0.05       0  4995.8    0.03       0  5003.1    0.16       0
Bank Sta=4313.2,5353.2
Exp/Cntr=0.3,0.1

Type RM Length L Ch R = 1,28236,320,320,320
BEGIN DESCRIPTION:
double Mapping XS 12debd0b
END DESCRIPTION:
XS GIS Cut Line= 3
      2774200.37      7092358.02      2772946.66      7092396.95
      2772582.06      7092542.78
#Sta/Elev= 30
  3678.6  545.15  3784.0  540.31  4055.8  535.44  4134.2  533.16  4144.2  532.25
  4154.2  527.78  4160.5  526.86  4161.1  526.06  4167.9  526.86  4174.2  532.75
  4184.2  531.75  4214.2  532.48  4244.2  536.86  4324.3  535.65  4514.4  535.58
  4654.4  536.34  4684.5  537.67  4764.9  536.25  4931.2  533.46  4977.8  534.38
  4988.6  533.17  4994.5  528.11  5018.7  527.04  5024.1  532.21  5042.4  533.62
  5047.5  535.44  5072.6  541.55  5077.9  540.34  5096.3  542.60  5325.6  546.63
#Mann=4,-1,0
  3678.6    0.05       0  4160.5    0.07       0  4167.9    0.05       0
  4764.9    0.16       0
Bank Sta=4055.8,5047.5
Exp/Cntr=0.3,0.1

Type RM Length L Ch R = 1,27916,637,637,637
BEGIN DESCRIPTION:
double Mapping XS 94a2de18
END DESCRIPTION:
XS GIS Cut Line= 3
      2774114.46      7092251.25      2773050.82      7092244.17
      2772749.38      7092206.05
#Sta/Elev= 30
  3901.1  541.09  4060.6  537.83  4100.6  535.76  4184.6  535.16  4210.6  534.90
  4250.6  537.54  4260.6  537.09  4280.6  533.87  4290.6  526.89  4300.6  526.49
  4310.6  532.46  4340.6  533.23  4420.6  532.82  4500.6  535.43  4630.6  534.37
  4730.6  535.01  4815.1  537.02  4850.6  537.17  4960.2  532.60  4980.7  533.34
  4990.8  526.59  4993.2  526.45  4993.8  525.65  5000.6  526.45  5001.9  528.25
  5010.9  532.77  5082.1  533.73  5094.0  535.16  5131.9  539.39  5268.6  542.65
#Mann=4,-1,0
  3901.1    0.05       0  4815.1    0.16       0  4993.2    0.07       0
  5000.6    0.16       0
Bank Sta=4184.6,5094
Exp/Cntr=0.3,0.1

Type RM Length L Ch R = 1,27279,497,497,497
BEGIN DESCRIPTION:
MIDDLE FORK TURKEY CREEK 24.0
END DESCRIPTION:
XS GIS Cut Line= 3
      2773904.08      7091999.37      2773179.30      7091838.79
      2772793.06      7091734.63
#Sta/Elev= 30
  4196.1  538.69  4327.5  536.39  4461.5  536.27  4563.9  534.81  4727.8  532.06
  4806.6  533.14  4850.7  532.30  4860.9  528.29  4867.5  522.77  4868.0  521.97
  4874.9  522.77  4881.4  523.81  4886.6  527.37  4891.7  523.39  4912.1  531.11
  4922.4  532.36  4984.3  531.97  4994.7  528.62  5005.1  523.65  5010.4  528.97
  5015.6  528.79  5025.8  532.72  5045.2  532.54  5050.3  531.18  5119.0  531.12
  5144.7  534.81  5159.7  537.41  5170.8  541.02  5199.7  543.50  5338.5  547.19
#Mann=4,-1,0
  4196.1    0.05       0  4806.6    0.16       0  4867.5    0.07       0
  4874.9    0.16       0
Bank Sta=4563.9,5144.7
Exp/Cntr=0.3,0.1

Type RM Length L Ch R = 1,26782,243,243,243
BEGIN DESCRIPTION:
Mapping XS a774eb9a
END DESCRIPTION:
XS GIS Cut Line= 4
      2773933.65      7091985.51      2773780.86      7091766.74
      2773214.89      7091492.43      2772947.50      7091318.80
#Sta/Elev= 30
  4106.2  539.37  4142.4  539.07  4178.2  540.30  4184.3  539.24  4199.1  540.39
  4205.2  538.93  4213.9  539.36  4220.0  538.23  4234.9  537.77  4249.7  538.13
  4270.6  537.15  4490.5  534.29  4876.1  531.12  4968.5  531.37  4979.4  530.76
  4984.9  529.62  4985.6  521.49  4986.6  520.69  4994.9  520.69  4995.8  521.49
  5004.2  521.64  5007.1  526.60  5013.8  530.82  5022.3  530.68  5049.2  534.29
  5085.6  537.62  5173.2  539.92  5245.7  542.53  5266.8  544.06  5320.8  545.56
#Mann=4,-1,0
  4106.2    0.05       0  4876.1    0.16       0  4985.6    0.07       0
  4995.8    0.16       0
Bank Sta=4490.5,5049.2
Exp/Cntr=0.3,0.1

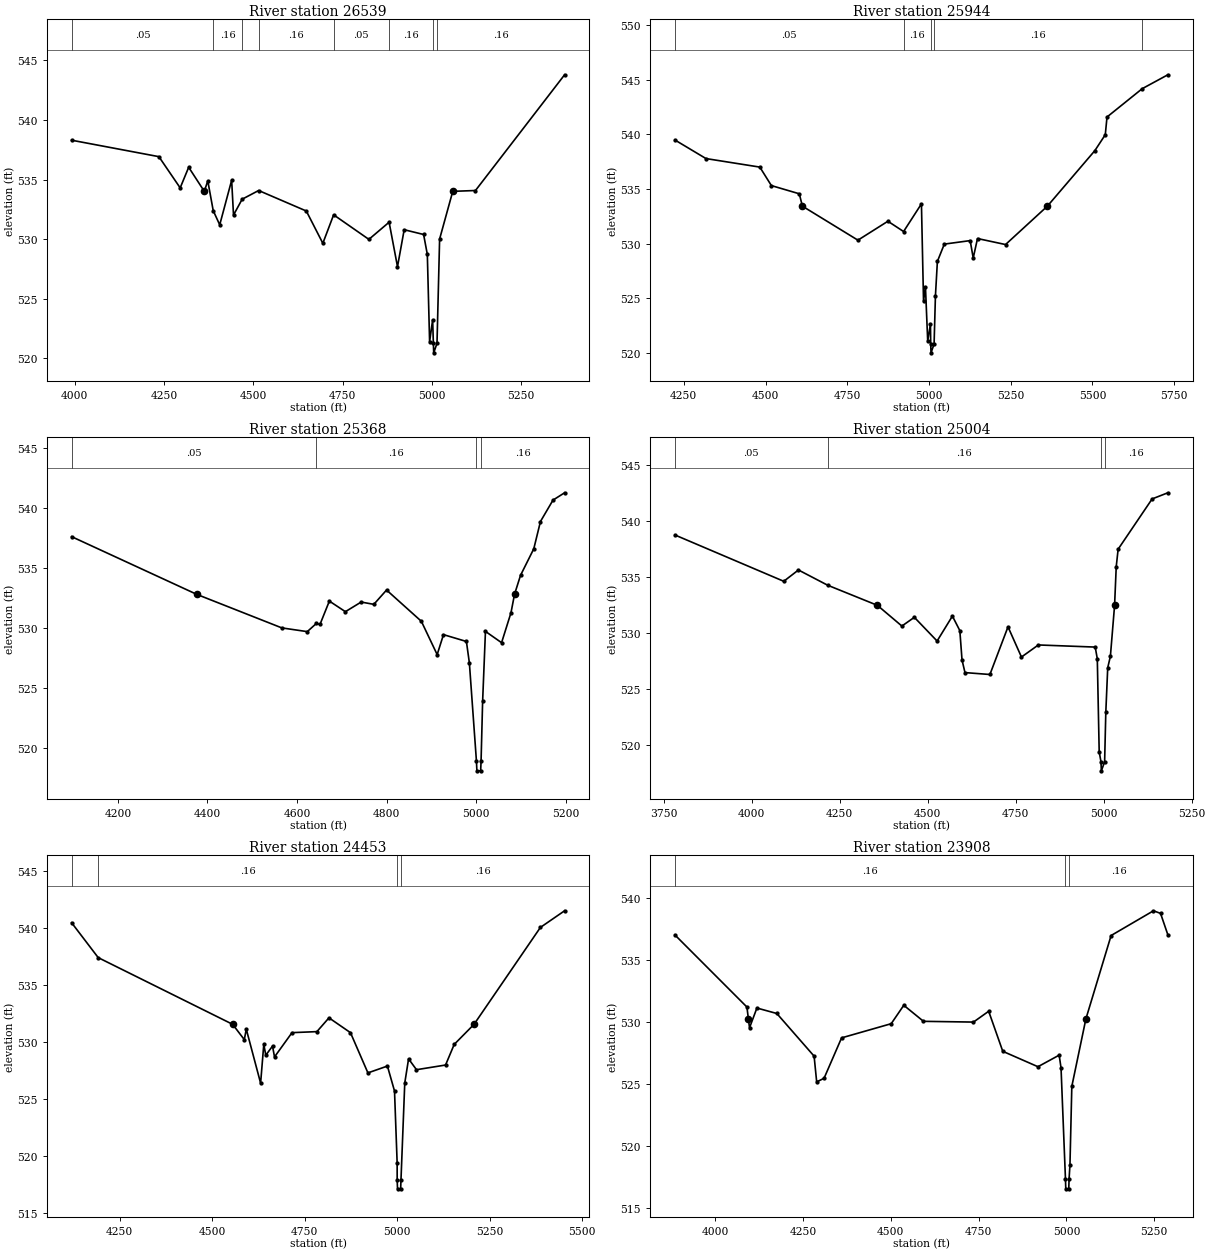
Type RM Length L Ch R = 1,26539,595,595,595
BEGIN DESCRIPTION:
Mapping XS a949206c
END DESCRIPTION:
XS GIS Cut Line= 4
      2774329.50      7091666.05      2773843.36      7091523.68
      2773360.72      7091377.85      2773062.76      7091159.58
#Sta/Elev= 30
  3991.4  538.30  4235.7  536.92  4295.3  534.30  4319.1  536.03  4362.8  534.01
  4372.6  534.89  4387.8  532.39  4406.0  531.20  4439.4  534.94  4444.6  532.02
  4468.8  533.35  4515.0  534.08  4648.4  532.36  4694.7  529.65  4724.9  532.04
  4823.6  529.98  4880.2  531.42  4903.7  527.69  4922.4  530.79  4976.8  530.39
  4987.2  528.72  4993.6  521.39  5002.1  523.24  5004.1  521.26  5005.1  520.46
  5014.3  521.26  5021.6  530.01  5058.4  534.01  5122.0  534.08  5371.5  543.79
#Mann=8,-1,0
  3991.4    0.05       0  4387.8    0.16       0  4468.8    0.05       0
  4515.0    0.16       0  4724.9    0.05       0  4880.2    0.16       0
  5004.1    0.07       0  5014.3    0.16       0
Bank Sta=4362.8,5058.4
Exp/Cntr=0.3,0.1

Type RM Length L Ch R = 1,25944,576,576,576
BEGIN DESCRIPTION:
Mapping XS 66af1615
END DESCRIPTION:
XS GIS Cut Line= 4
      2774395.45      7091617.44      2773791.28      7091166.04
      2773641.97      7091072.29      2773093.40      7090891.75
#Sta/Elev= 30
  4222.7  539.49  4317.8  537.79  4482.5  537.01  4517.9  535.32  4603.3  534.57
  4612.7  533.44  4782.6  530.33  4874.3  532.06  4922.3  531.12  4976.9  533.65
  4983.3  524.76  4989.2  526.05  4996.1  521.10  5004.5  522.67  5005.3  520.83
  5006.2  520.03  5015.6  520.83  5019.7  525.23  5025.7  528.39  5046.9  529.97
  5126.0  530.29  5135.3  528.70  5148.4  530.48  5234.2  529.93  5362.2  533.44
  5507.5  538.52  5539.3  539.97  5544.6  541.59  5652.3  544.18  5730.7  545.45
#Mann=5,-1,0
  4222.7    0.05       0  4922.3    0.16       0  5005.3    0.07       0
  5015.6    0.16       0  5652.3    0.05       0
Bank Sta=4612.7,5362.2
Exp/Cntr=0.3,0.1

Type RM Length L Ch R = 1,25368,364,364,364
BEGIN DESCRIPTION:
Mapping XS 9cf190f2
END DESCRIPTION:
XS GIS Cut Line= 3
      2774294.75      7091308.40      2773728.78      7090686.88
      2773513.52      7090541.06
#Sta/Elev= 30
  4096.7  537.62  4376.1  532.82  4566.0  530.03  4622.8  529.72  4643.1  530.40
  4651.2  530.32  4672.1  532.26  4707.9  531.38  4743.1  532.18  4771.4  531.99
  4799.8  533.18  4877.5  530.58  4912.8  527.81  4926.9  529.47  4978.1  528.90
  4984.7  527.12  5000.5  518.94  5001.5  518.14  5009.9  518.14  5010.8  518.94
  5014.3  523.93  5020.6  529.74  5056.6  528.80  5077.6  531.29  5085.5  532.82
  5098.9  534.40  5128.5  536.61  5143.4  538.88  5171.4  540.66  5197.3  541.27
#Mann=4,-1,0
  4096.7    0.05       0  4643.1    0.16       0  5000.5    0.07       0
  5010.8    0.16       0
Bank Sta=4376.1,5085.5
Exp/Cntr=0.3,0.1

Type RM Length L Ch R = 1,25004,551,551,551
BEGIN DESCRIPTION:
Mapping XS e3da9da3
END DESCRIPTION:
XS GIS Cut Line= 3
      2774506.53      7091245.88      2773947.53      7090499.38
      2773513.47      7090325.75
#Sta/Elev= 30
  3782.1  538.74  4091.3  534.60  4133.0  535.61  4215.9  534.25  4357.3  532.45
  4426.8  530.60  4462.2  531.38  4526.8  529.26  4570.3  531.49  4591.4  530.19
  4597.6  527.57  4606.0  526.44  4676.8  526.27  4728.2  530.53  4766.4  527.83
  4814.4  528.91  4975.9  528.72  4981.8  527.68  4987.2  519.36  4992.3  518.46
  4993.3  517.66  5002.6  518.46  5006.0  522.91  5011.4  526.87  5019.0  527.90
  5030.9  532.45  5035.6  535.91  5041.0  537.47  5137.5  541.96  5182.2  542.51
#Mann=4,-1,0
  3782.1    0.05       0  4215.9    0.16       0  4992.3    0.07       0
  5002.6    0.16       0
Bank Sta=4357.3,5030.9
Exp/Cntr=0.3,0.1

Type RM Length L Ch R = 1,24453,545,545,545
BEGIN DESCRIPTION:
MIDDLE FORK TURKEY CREEK 20.0
END DESCRIPTION:
XS GIS Cut Line= 3
      2774824.97      7090524.99      2774023.91      7090183.40
      2773574.96      7090074.99
#Sta/Elev= 30
  4120.3  540.43  4192.2  537.37  4555.6  531.52  4587.1  530.18  4592.5  531.09
  4631.2  526.36  4639.8  529.77  4645.2  528.81  4663.4  529.61  4668.8  528.66
  4716.1  530.79  4783.4  530.88  4816.0  532.09  4874.1  530.79  4921.3  527.26
  4974.0  527.86  4993.2  525.67  5000.3  519.38  5000.4  517.89  5001.3  517.09
  5009.8  517.09  5010.7  517.89  5020.9  526.37  5031.2  528.49  5052.6  527.54
  5131.2  527.95  5154.6  529.76  5208.2  531.52  5387.6  540.02  5453.0  541.48
#Mann=4,-1,0
  4120.3    0.05       0  4192.2    0.16       0  5000.4    0.07       0
  5010.7    0.16       0
Bank Sta=4555.6,5208.2
Exp/Cntr=0.3,0.1

Type RM Length L Ch R = 1,23908,709,709,709
BEGIN DESCRIPTION:
MIDDLE FORK TURKEY CREEK 19.0
END DESCRIPTION:
XS GIS Cut Line= 5
      2774725.02      7090325.02      2774159.33      7089804.93
      2773867.66      7089787.57      2773742.66      7089832.71
      2773534.32      7089811.87
#Sta/Elev= 30
  3885.8  537.00  4090.8  531.20  4095.0  530.24  4098.2  529.53  4119.2  531.12
  4175.9  530.68  4282.0  527.25  4289.3  525.18  4310.3  525.47  4360.2  528.72
  4501.4  529.86  4537.2  531.34  4593.3  530.05  4735.5  529.99  4778.8  530.86
  4818.9  527.64  4919.0  526.40  4979.4  527.33  4984.7  526.31  4997.3  517.38
  4998.2  516.58  5006.7  516.58  5007.6  517.38  5010.1  518.50  5015.4  524.82
  5055.4  530.24  5127.2  536.95  5247.8  538.94  5267.9  538.73  5288.7  537.01
#Mann=3,-1,0
  3885.8    0.16       0  4997.3    0.07       0  5007.6    0.16       0
Bank Sta=4095,5055.4
Exp/Cntr=0.3,0.1

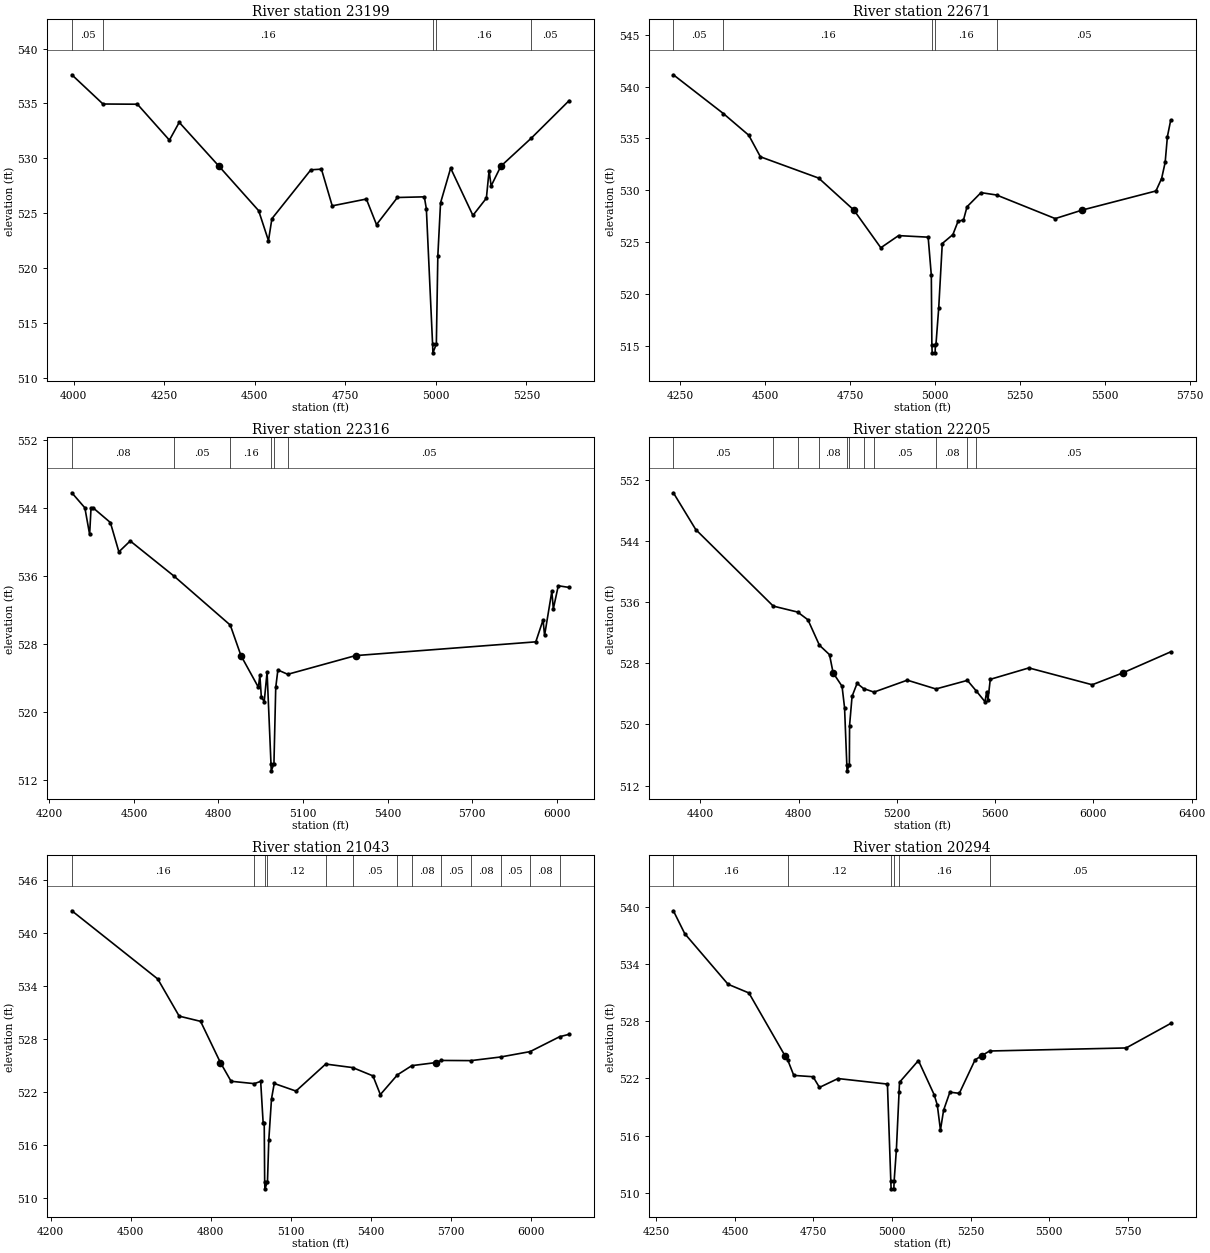
Type RM Length L Ch R = 1,23199,528,528,528
BEGIN DESCRIPTION:
MIDDLE FORK TURKEY CREEK 18.0
END DESCRIPTION:
XS GIS Cut Line= 3
      2774875.01      7089925.00      2774065.58      7089419.51
      2773690.55      7089232.00
#Sta/Elev= 30
  3994.5  537.61  4080.5  534.95  4175.6  534.93  4264.0  531.66  4291.1  533.28
  4400.8  529.29  4510.5  525.24  4537.6  522.51  4547.1  524.51  4654.7  528.96
  4683.9  529.02  4713.7  525.68  4808.0  526.30  4836.0  523.97  4893.8  526.44
  4968.1  526.50  4973.7  525.41  4990.9  513.10  4991.8  512.30  5001.3  513.10
  5005.4  521.12  5012.9  525.95  5040.8  529.11  5102.3  524.81  5139.5  526.38
  5147.0  528.89  5152.6  527.49  5179.5  529.29  5263.8  531.85  5368.1  535.26
#Mann=5,-1,0
  3994.5    0.05       0  4080.5    0.16       0  4990.9    0.07       0
  5001.3    0.16       0  5263.8    0.05       0
Bank Sta=4400.8,5179.5
Exp/Cntr=0.3,0.1

Type RM Length L Ch R = 1,22671,355,355,355
BEGIN DESCRIPTION:
Mapping XS 773315d1
END DESCRIPTION:
XS GIS Cut Line= 3
      2775069.07      7089600.08      2774395.44      7089228.54
      2773729.43      7089037.76
#Sta/Elev= 30
  4230.4  541.13  4377.6  537.39  4452.0  535.31  4486.3  533.23  4657.6  531.18
  4761.1  528.10  4840.3  524.47  4892.4  525.64  4979.5  525.49  4988.8  521.82
  4990.4  515.15  4991.3  514.35  4999.9  514.35  5000.8  515.15  5002.5  515.19
  5010.6  518.70  5021.0  524.88  5052.2  525.74  5067.4  527.02  5083.4  527.15
  5093.8  528.42  5134.9  529.78  5180.7  529.55  5353.1  527.28  5432.4  528.10
  5649.2  529.94  5665.9  531.14  5676.3  532.69  5682.9  535.18  5692.5  536.74
#Mann=5,-1,0
  4230.4    0.05       0  4377.6    0.16       0  4990.4    0.07       0
  5000.8    0.16       0  5180.7    0.05       0
Bank Sta=4761.1,5432.4
Exp/Cntr=0.3,0.1

Type RM Length L Ch R = 1,22316,111,111,111
BEGIN DESCRIPTION:
Mapping XS 9ca26b10
END DESCRIPTION:
XS GIS Cut Line= 6
      2775280.90      7089107.02      2774770.44      7089051.46
      2774555.16      7089006.32      2774461.41      7088961.18
      2774294.75      7088850.07      2773608.61      7088610.96
#Sta/Elev= 30
  4279.8  545.82  4326.0  544.05  4342.9  540.92  4347.9  544.05  4356.2  544.02
  4416.5  542.32  4446.7  538.87  4486.9  540.15  4642.5  536.01  4841.9  530.25
  4879.8  526.66  4941.7  522.93  4946.8  524.34  4952.1  521.80  4962.3  521.24
  4972.5  524.73  4986.4  513.90  4987.2  513.10  4996.8  513.90  5003.2  522.91
  5010.8  524.97  5045.8  524.46  5286.3  526.66  5925.9  528.28  5951.7  530.86
  5957.0  529.03  5982.8  534.22  5988.1  532.17  6005.7  534.88  6044.2  534.68
#Mann=6,-1,0
  4279.8    0.08       0  4642.5    0.05       0  4841.9    0.16       0
  4986.4    0.07       0  4996.8    0.16       0  5045.8    0.05       0
Bank Sta=4879.8,5286.3
Exp/Cntr=0.3,0.1

Type RM Length L Ch R = 1,22205,1162,1162,1162
BEGIN DESCRIPTION:
Mapping XS 6343cb0a
END DESCRIPTION:
XS GIS Cut Line= 6
      2775315.60      7089002.85      2774746.14      7088936.88
      2774555.16      7088898.68      2774405.86      7088787.57
      2774239.19      7088565.35      2773496.11      7088291.03
#Sta/Elev= 30
  4290.1  550.27  4381.3  545.46  4696.7  535.46  4795.9  534.68  4837.8  533.67
  4884.5  530.35  4925.7  529.11  4940.3  526.74  4976.7  524.98  4986.9  522.18
  4996.1  514.73  4997.0  513.93  5006.5  514.73  5007.3  519.85  5017.5  523.67
  5037.9  525.36  5064.4  524.68  5106.7  524.22  5242.2  525.78  5358.7  524.63
  5486.8  525.75  5522.7  524.38  5558.6  522.96  5565.2  524.26  5570.6  523.19
  5580.0  525.89  5737.2  527.38  5995.0  525.18  6120.1  526.74  6314.3  529.48
#Mann=11,-1,0
  4290.1    0.05       0  4696.7    0.16       0  4795.9    0.05       0
  4884.5    0.08       0  4996.1    0.07       0  5006.5    0.08       0
  5064.4    0.12       0  5106.7    0.05       0  5358.7    0.08       0
  5486.8    0.12       0  5522.7    0.05       0
Bank Sta=4940.3,6120.1
Exp/Cntr=0.3,0.1

Type RM Length L Ch R = 1,21043,749,749,749
BEGIN DESCRIPTION:
Mapping XS e15ed0bb
END DESCRIPTION:
XS GIS Cut Line= 4
      2775187.13      7088249.37      2774471.83      7088339.65
      2774148.91      7088277.15      2773430.17      7087895.21
#Sta/Elev= 30
  4279.1  542.51  4601.1  534.78  4681.4  530.57  4761.6  529.98  4835.9  525.31
  4875.9  523.19  4963.1  522.92  4986.8  523.18  4996.0  518.50  5000.1  518.50
  5001.8  511.80  5002.7  511.00  5012.3  511.80  5017.2  516.51  5027.4  521.20
  5037.6  522.94  5119.1  522.08  5230.5  525.14  5331.7  524.74  5407.6  523.80
  5435.3  521.68  5499.4  523.92  5553.3  524.96  5643.9  525.31  5664.1  525.55
  5774.9  525.53  5885.7  525.94  5996.5  526.55  6107.3  528.24  6142.9  528.51
#Mann=13,-1,0
  4279.1    0.16       0  4963.1    0.12       0  5001.8    0.07       0
  5012.3    0.12       0  5230.5    0.16       0  5331.7    0.05       0
  5499.4    0.16       0  5553.3    0.08       0  5664.1    0.05       0
  5774.9    0.08       0  5885.7    0.05       0  5996.5    0.08       0
  6107.3    0.05       0
Bank Sta=4835.9,5643.9
Exp/Cntr=0.3,0.1

Type RM Length L Ch R = 1,20294,571,571,571
BEGIN DESCRIPTION:
Mapping XS a73d69e0
END DESCRIPTION:
XS GIS Cut Line= 3
      2775000.52      7088024.56      2774314.71      7087885.66
      2773433.63      7087837.92
#Sta/Elev= 30
  4304.2  539.58  4340.4  537.18  4478.2  531.87  4544.5  530.96  4659.3  524.37
  4668.0  523.93  4687.3  522.31  4748.6  522.17  4769.0  521.05  4828.0  521.98
  4985.2  521.40  4996.0  511.21  4996.9  510.41  5005.6  510.41  5006.5  511.21
  5013.7  514.52  5022.3  520.60  5023.7  521.59  5083.8  523.87  5133.8  520.29
  5143.8  519.21  5153.9  516.58  5163.9  518.66  5183.9  520.55  5213.9  520.43
  5264.0  523.94  5284.8  524.37  5310.2  524.87  5744.7  525.19  5886.3  527.76
#Mann=6,-1,0
  4304.2    0.16       0  4668.0    0.12       0  4996.0    0.07       0
  5006.5    0.12       0  5022.3    0.16       0  5310.2    0.05       0
Bank Sta=4659.3,5284.8
Exp/Cntr=0.3,0.1

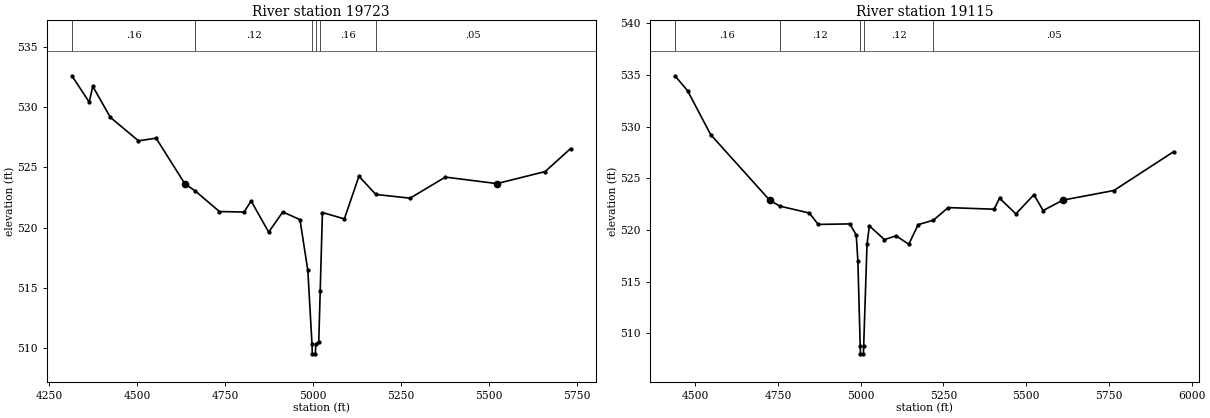
Type RM Length L Ch R = 1,19723,608,608,608
BEGIN DESCRIPTION:
Mapping XS 56b747e1
END DESCRIPTION:
XS GIS Cut Line= 3
      2774844.20      7087473.33      2774206.21      7087486.36
      2773455.30      7087694.70
#Sta/Elev= 30
  4314.2  532.61  4363.4  530.42  4373.4  531.74  4423.4  529.16  4503.4  527.21
  4553.5  527.43  4634.9  523.66  4665.1  523.04  4733.5  521.34  4803.5  521.30
  4823.5  522.22  4873.5  519.63  4913.5  521.31  4962.4  520.67  4984.7  516.45
  4996.6  510.33  4997.4  509.53  5006.2  509.53  5007.1  510.33  5015.8  510.54
  5019.9  514.77  5026.2  521.26  5088.5  520.73  5130.0  524.27  5178.2  522.76
  5275.3  522.45  5375.6  524.20  5522.1  523.66  5659.3  524.66  5731.6  526.57
#Mann=6,-1,0
  4314.2    0.16       0  4665.1    0.12       0  4996.6    0.07       0
  5007.1    0.12       0  5019.9    0.16       0  5178.2    0.05       0
Bank Sta=4634.9,5522.1
Exp/Cntr=0.3,0.1

Type RM Length L Ch R = 1,19115,614,614,614
BEGIN DESCRIPTION:
Mapping XS 897f869a
END DESCRIPTION:
XS GIS Cut Line= 3
      2774701.03      7086896.07      2774180.16      7087065.35
      2773333.79      7087516.75
#Sta/Elev= 30
  4438.8  534.92  4476.7  533.48  4546.8  529.22  4724.8  522.89  4755.6  522.31
  4844.9  521.64  4871.6  520.54  4967.4  520.59  4986.5  519.51  4991.5  516.98
  4998.4  508.82  4999.2  508.02  5008.1  508.02  5009.0  508.82  5019.1  518.65
  5026.3  520.40  5071.7  519.07  5107.0  519.44  5145.2  518.62  5173.7  520.52
  5219.7  520.95  5264.3  522.17  5403.1  522.01  5419.4  523.08  5468.9  521.56
  5523.5  523.42  5551.1  521.88  5610.7  522.89  5765.0  523.82  5945.7  527.58
#Mann=5,-1,0
  4438.8    0.16       0  4755.6    0.12       0  4998.4    0.07       0
  5009.0    0.12       0  5219.7    0.05       0
Bank Sta=4724.8,5610.7
Exp/Cntr=0.3,0.1