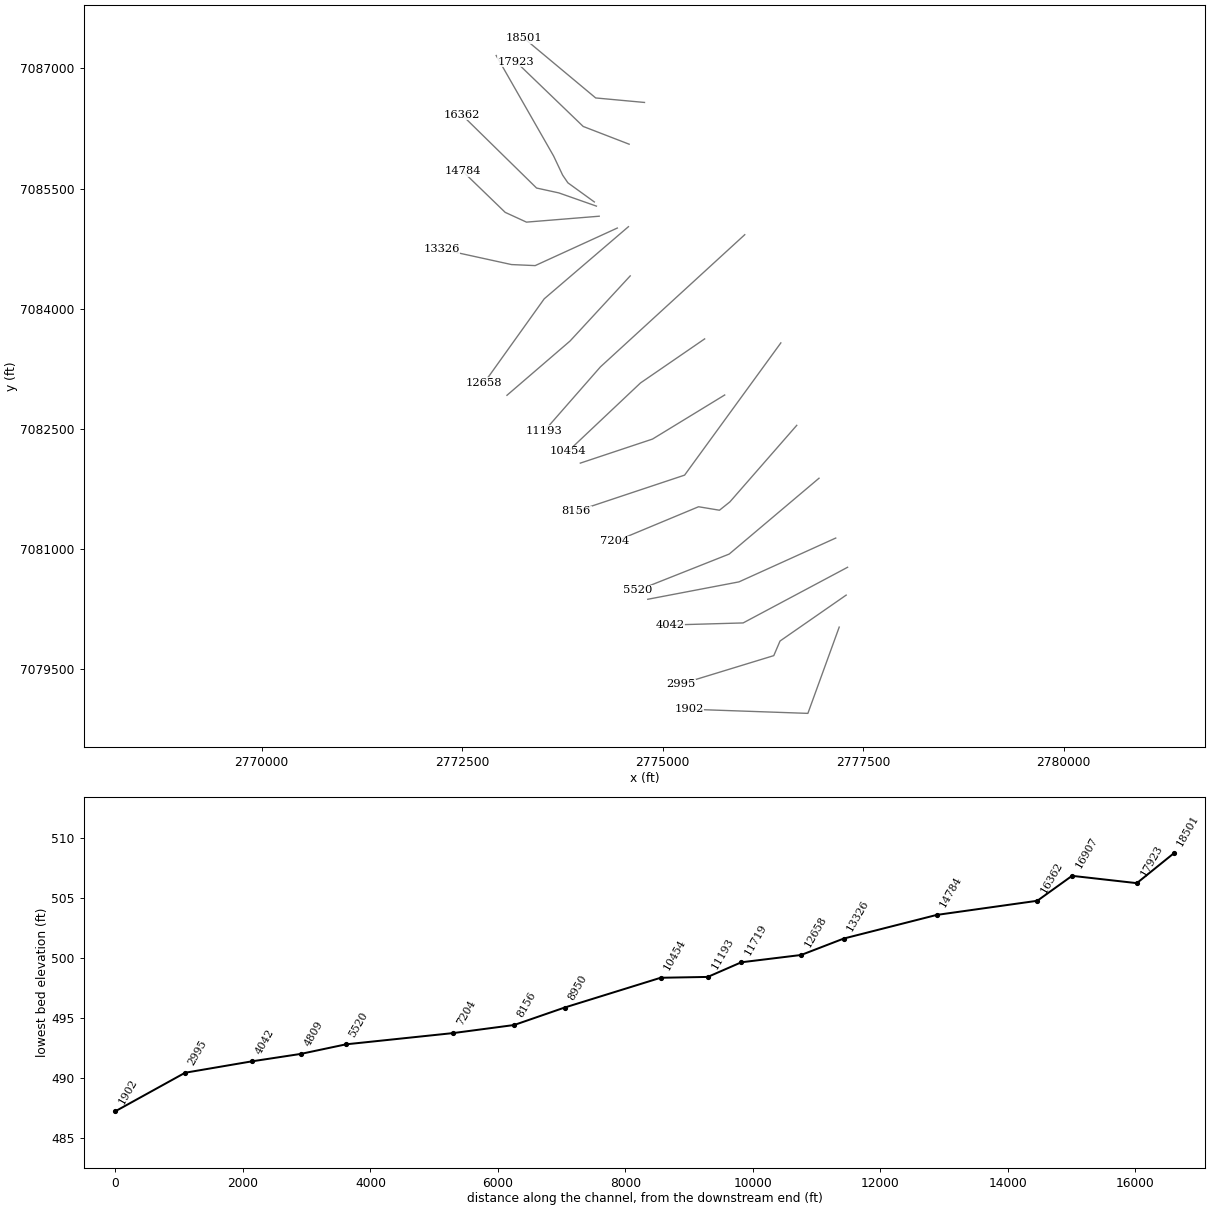
HEC-RAS study MIDDLE FORK TURKEY CREEK.prj: MIDDLE FORK TURKEY CREEK Base Level Engineering

--- MIDDLE FORK TURKEY CREEK.g01 (geometry) --- (continued)

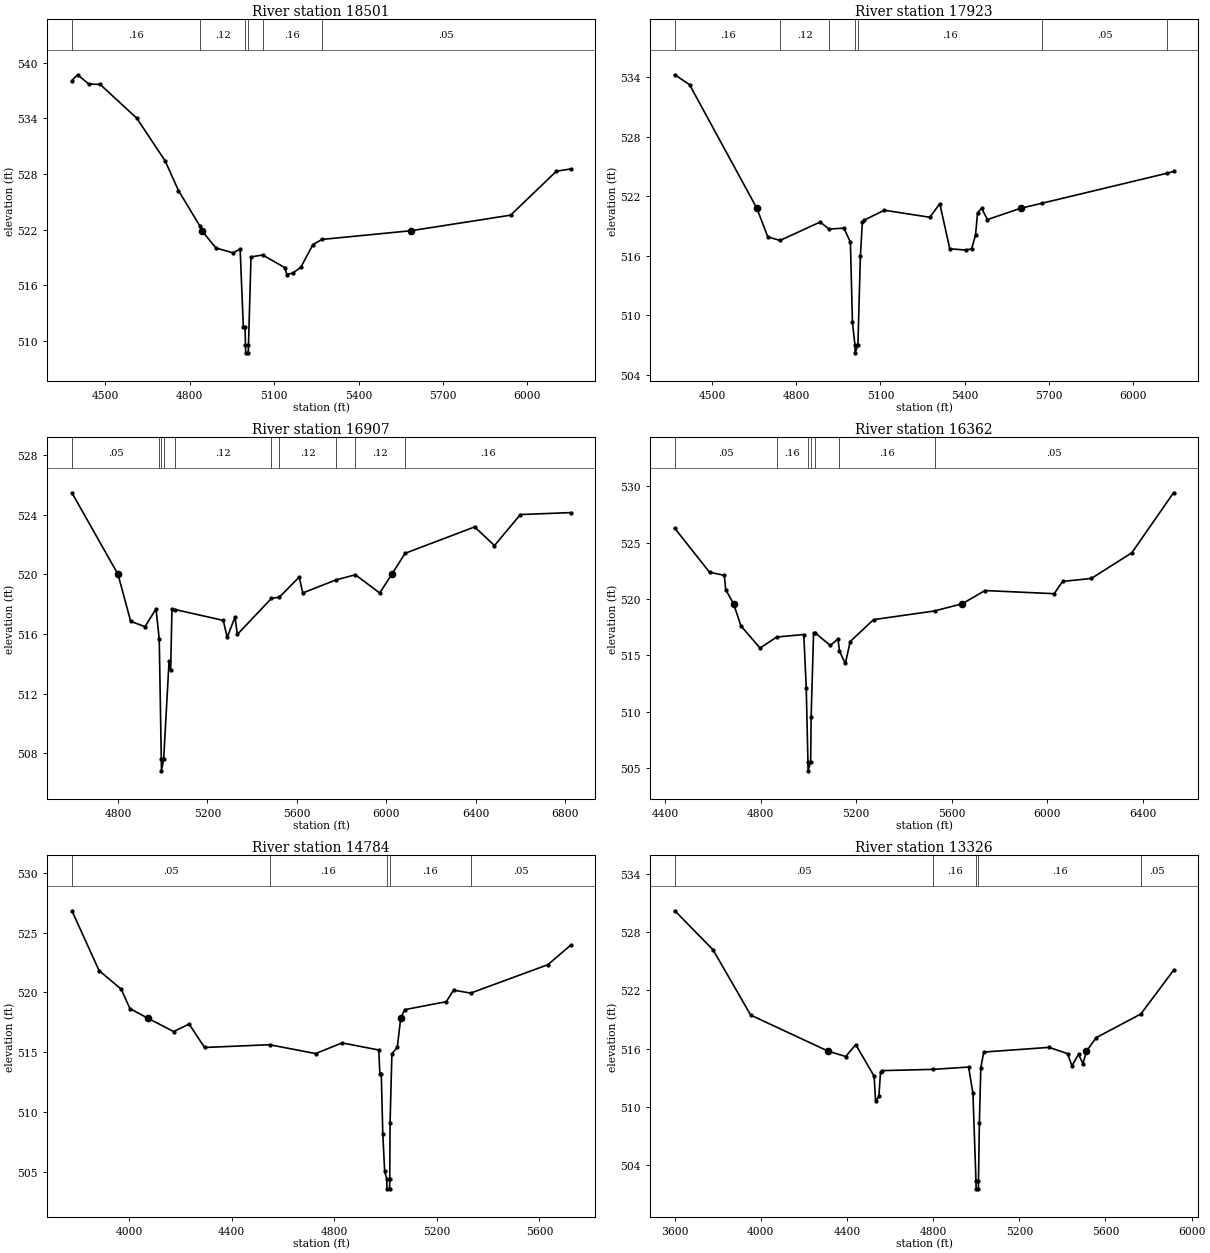
Type RM Length L Ch R = 1,18501,578,578,578
BEGIN DESCRIPTION:
MIDDLE FORK TURKEY CREEK 12.0
END DESCRIPTION:
XS GIS Cut Line= 3
      2774774.97      7086575.00      2774166.41      7086631.18
      2773275.02      7087374.98
#Sta/Elev= 30
  4381.0  538.09  4401.1  538.71  4441.2  537.71  4481.4  537.67  4611.9  534.01
  4712.4  529.41  4759.6  526.22  4835.6  522.40  4842.7  521.88  4893.1  520.01
  4953.4  519.50  4978.9  519.89  4990.3  511.45  4996.3  511.45  4997.9  509.50
  4998.7  508.70  5007.6  508.70  5008.5  509.50  5017.5  519.05  5059.0  519.26
  5137.3  517.90  5145.1  517.15  5165.9  517.31  5194.5  517.93  5237.5  520.38
  5269.7  520.94  5586.3  521.88  5940.3  523.56  6103.0  528.31  6153.1  528.54
#Mann=6,-1,0
  4381.0    0.16       0  4835.6    0.12       0  4997.9    0.07       0
  5008.5    0.12       0  5059.0    0.16       0  5269.7    0.05       0
Bank Sta=4842.7,5586.3
Exp/Cntr=0.3,0.1

Type RM Length L Ch R = 1,17923,1016,1016,1016
BEGIN DESCRIPTION:
Mapping XS 69497ca0
END DESCRIPTION:
XS GIS Cut Line= 3
      2774583.80      7086054.07      2774010.89      7086275.42
      2773174.62      7087081.36
#Sta/Elev= 30
  4367.9  534.22  4420.2  533.22  4659.7  520.78  4698.9  517.89  4742.4  517.54
  4885.2  519.39  4916.9  518.68  4969.7  518.78  4992.9  517.37  5000.1  509.30
  5009.0  507.02  5009.8  506.22  5019.6  507.02  5028.4  515.94  5035.4  519.35
  5042.6  519.59  5113.3  520.58  5275.9  519.87  5311.2  521.24  5346.7  516.70
  5403.3  516.57  5424.4  516.69  5438.5  518.08  5445.7  520.30  5459.9  520.78
  5481.0  519.64  5599.4  520.78  5676.0  521.29  6121.2  524.31  6143.5  524.49
#Mann=7,-1,0
  4367.9    0.16       0  4742.4    0.12       0  4916.9    0.16       0
  5009.0    0.07       0  5019.6    0.16       0  5676.0    0.05       0
  6121.2    0.16       0
Bank Sta=4659.7,5599.4
Exp/Cntr=0.3,0.1

Type RM Length L Ch R = 1,16907,545,545,545
BEGIN DESCRIPTION:
Mapping XS 360497cd
END DESCRIPTION:
XS GIS Cut Line= 5
      2774149.79      7085333.57      2773819.92      7085572.29
      2773754.82      7085667.78      2773641.97      7085906.49
      2772926.07      7087160.41
#Sta/Elev= 30
  4594.0  525.48  4800.2  520.01  4856.9  516.86  4920.9  516.50  4970.2  517.69
  4984.7  515.67  4993.9  507.63  4994.7  506.83  5004.5  507.63  5028.7  514.21
  5035.6  513.56  5041.7  517.70  5055.1  517.65  5271.2  516.92  5288.5  515.78
  5323.8  517.15  5334.0  515.98  5486.2  518.39  5522.3  518.48  5610.9  519.83
  5626.7  518.76  5776.2  519.64  5862.3  519.98  5970.9  518.76  6025.2  520.01
  6084.5  521.42  6395.7  523.19  6484.5  521.94  6600.2  524.02  6824.7  524.15
#Mann=10,-1,0
  4594.0    0.05       0  4984.7    0.16       0  4993.9    0.07       0
  5004.5    0.16       0  5055.1    0.12       0  5486.2    0.16       0
  5522.3    0.12       0  5776.2    0.16       0  5862.3    0.12       0
  6084.5    0.16       0
Bank Sta=4800.2,6025.2
Exp/Cntr=0.3,0.1

Type RM Length L Ch R = 1,16362,1578,1578,1578
BEGIN DESCRIPTION:
Mapping XS 67f610d0
END DESCRIPTION:
XS GIS Cut Line= 4
      2774175.79      7085281.51      2773707.07      7085446.42
      2773429.30      7085507.19      2772496.13      7086422.99
#Sta/Elev= 30
  4441.0  526.25  4586.0  522.36  4648.0  522.09  4653.9  520.82  4686.7  519.57
  4717.5  517.61  4797.5  515.64  4868.1  516.62  4980.9  516.84  4991.2  512.12
  4998.3  505.55  4998.9  504.75  5009.7  505.55  5011.7  509.52  5021.9  516.95
  5028.5  516.99  5091.7  515.87  5124.3  516.45  5130.4  515.36  5155.0  514.27
  5175.4  516.22  5273.2  518.16  5528.8  518.93  5644.9  519.57  5739.9  520.74
  6029.8  520.46  6065.2  521.55  6185.4  521.81  6355.1  524.09  6529.7  529.41
#Mann=7,-1,0
  4441.0    0.05       0  4868.1    0.16       0  4998.3    0.07       0
  5009.7    0.16       0  5028.5    0.12       0  5130.4    0.16       0
  5528.8    0.05       0
Bank Sta=4686.7,5644.9
Exp/Cntr=0.3,0.1

Type RM Length L Ch R = 1,14784,1458,1458,1458
BEGIN DESCRIPTION:
Mapping XS bb4be697
END DESCRIPTION:
XS GIS Cut Line= 4
      2774210.52      7085155.62      2773303.43      7085081.84
      2773038.67      7085203.37      2772504.83      7085719.85
#Sta/Elev= 30
  3777.1  526.82  3883.0  521.82  3969.0  520.27  4003.4  518.64  4074.5  517.82
  4173.9  516.72  4234.1  517.35  4294.3  515.39  4547.9  515.62  4727.3  514.88
  4830.3  515.77  4973.7  515.18  4977.8  513.21  4983.3  513.21  4989.3  508.17
  4996.5  505.04  5004.9  504.37  5005.5  503.57  5015.7  503.57  5016.4  504.37
  5017.6  509.05  5024.8  514.87  5045.9  515.41  5059.0  517.82  5074.2  518.55
  5236.8  519.22  5265.1  520.18  5332.3  519.94  5632.9  522.31  5721.3  523.93
#Mann=5,-1,0
  3777.1    0.05       0  4547.9    0.16       0  5004.9    0.07       0
  5016.4    0.16       0  5332.3    0.05       0
Bank Sta=4074.5,5059
Exp/Cntr=0.3,0.1

Type RM Length L Ch R = 1,13326,668,668,668
BEGIN DESCRIPTION:
Mapping XS 299e4e61
END DESCRIPTION:
XS GIS Cut Line= 4
      2774436.21      7085008.04      2773411.94      7084539.31
      2773116.80      7084552.33      2772244.41      7084743.30
#Sta/Elev= 30
  3600.9  530.18  3778.2  526.16  3952.7  519.46  4312.4  515.75  4394.4  515.20
  4440.4  516.43  4526.0  513.17  4532.5  510.60  4548.0  511.11  4555.5  513.59
  4561.0  513.75  4800.5  513.88  4964.5  514.12  4984.5  511.44  4998.7  502.40
  4999.3  501.60  5009.7  501.60  5010.3  502.40  5014.5  508.39  5021.2  514.05
  5034.8  515.66  5338.0  516.14  5423.8  515.50  5444.3  514.24  5474.7  515.42
  5495.5  514.47  5511.5  515.75  5556.9  517.14  5764.0  519.57  5915.8  524.06
#Mann=5,-1,0
  3600.9    0.05       0  4800.5    0.16       0  4998.7    0.07       0
  5010.3    0.16       0  5764.0    0.05       0
Bank Sta=4312.4,5511.5
Exp/Cntr=0.3,0.1

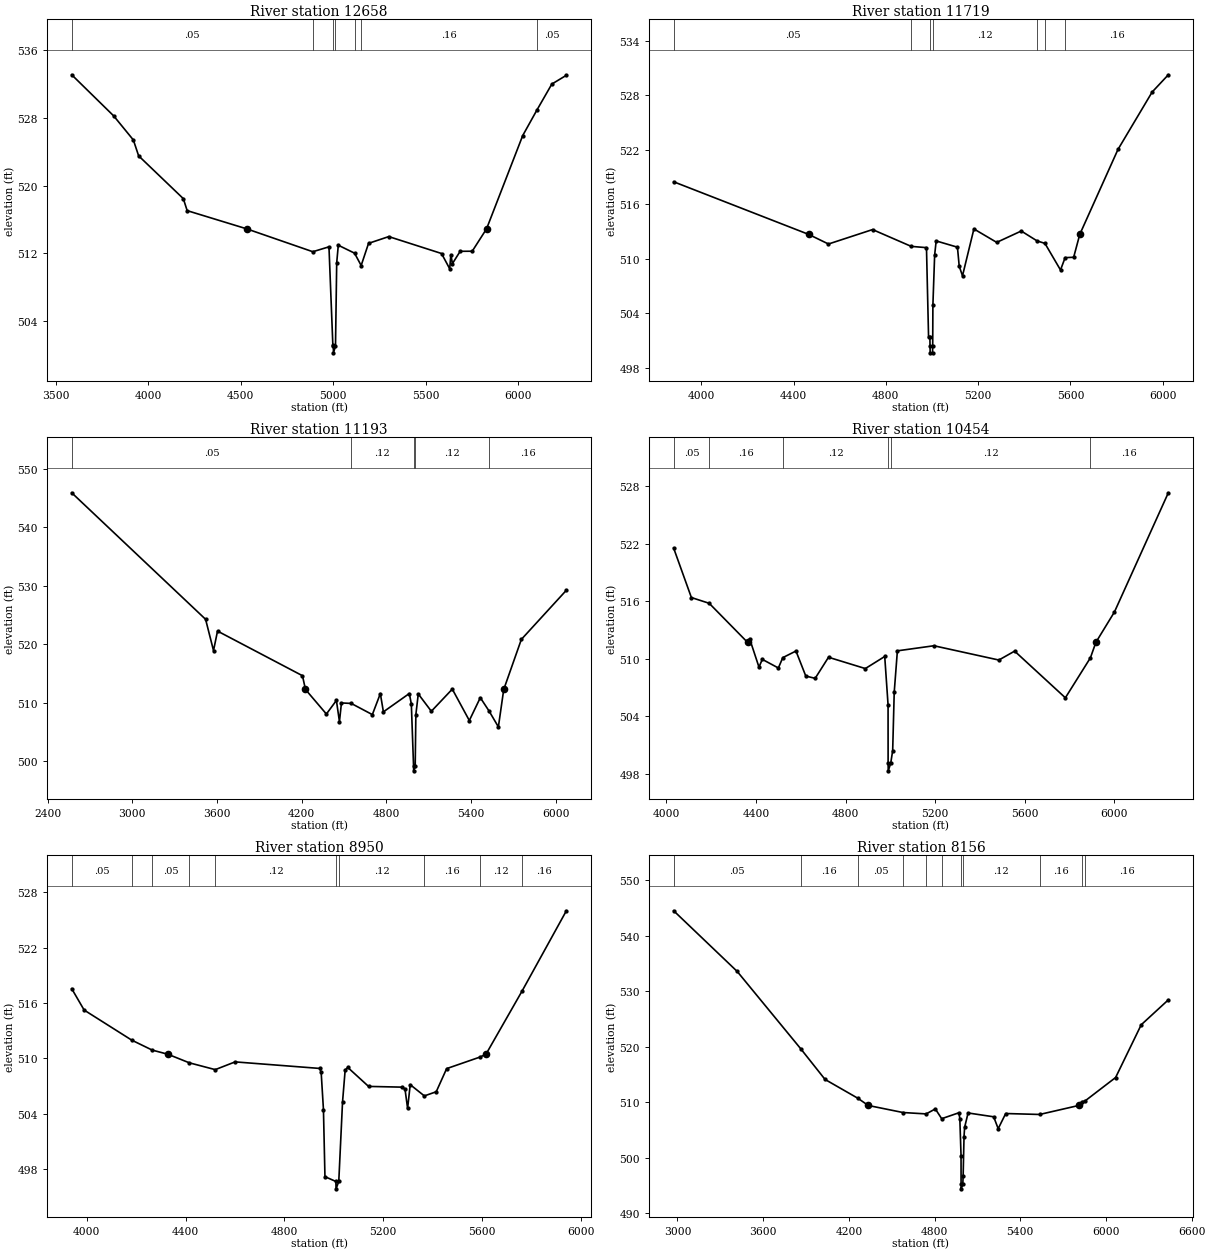
Type RM Length L Ch R = 1,12658,939,939,939
BEGIN DESCRIPTION:
MIDDLE FORK TURKEY CREEK 8.0
END DESCRIPTION:
XS GIS Cut Line= 3
      2774575.02      7085025.01      2773525.00      7084125.00
      2772775.00      7083075.00
#Sta/Elev= 30
  3587.6  533.12  3814.3  528.26  3920.7  525.41  3949.3  523.53  4190.7  518.47
  4211.6  517.05  4532.8  514.90  4890.6  512.19  4977.9  512.77  4998.8  501.20
  5001.6  501.03  5002.2  500.23  5013.2  501.03  5019.7  510.87  5028.3  512.96
  5116.1  512.02  5151.9  510.56  5191.8  513.18  5301.1  513.98  5586.2  511.98
  5630.5  510.17  5636.6  511.84  5645.2  510.79  5687.0  512.24  5752.1  512.25
  5829.6  514.90  6025.0  525.93  6101.0  528.92  6182.3  532.02  6260.9  533.06
#Mann=7,-1,0
  3587.6    0.05       0  4890.6    0.16       0  5001.6    0.07       0
  5013.2    0.16       0  5116.1    0.12       0  5151.9    0.16       0
  6101.0    0.05       0
Bank Sta=4532.8,5829.6
Exp/Cntr=0.3,0.1

Type RM Length L Ch R = 1,11719,526,526,526
BEGIN DESCRIPTION:
MIDDLE FORK TURKEY CREEK 7.0
END DESCRIPTION:
XS GIS Cut Line= 3
      2774596.86      7084410.86      2773846.83      7083598.33
      2773060.40      7082921.28
#Sta/Elev= 30
  3880.5  518.45  4465.4  512.66  4551.3  511.60  4742.4  513.19  4909.9  511.34
  4976.0  511.20  4985.1  501.31  4990.8  501.31  4991.4  500.42  4992.0  499.62
  5002.4  499.62  5003.0  500.42  5003.8  504.87  5011.4  510.39  5018.0  511.94
  5110.2  511.25  5117.9  509.15  5132.1  508.10  5181.5  513.26  5280.3  511.78
  5386.7  513.03  5455.4  511.94  5489.3  511.67  5556.8  508.74  5576.8  510.10
  5613.8  510.14  5640.3  512.66  5805.8  522.01  5953.9  528.33  6024.0  530.23
#Mann=7,-1,0
  3880.5    0.05       0  4909.9    0.12       0  4991.4    0.07       0
  5003.0    0.12       0  5455.4    0.16       0  5489.3    0.12       0
  5576.8    0.16       0
Bank Sta=4465.4,5640.3
Exp/Cntr=0.3,0.1

Type RM Length L Ch R = 1,11193,739,739,739
BEGIN DESCRIPTION:
MIDDLE FORK TURKEY CREEK 6.0
END DESCRIPTION:
XS GIS Cut Line= 3
      2776024.97      7084924.98      2774225.00      7083275.00
      2773525.00      7082475.00
#Sta/Elev= 30
  2571.1  545.87  3519.7  524.27  3575.8  518.93  3604.2  522.26  4206.0  514.64
  4227.4  512.29  4375.6  508.10  4446.5  510.42  4468.1  506.81  4482.3  509.99
  4551.5  509.91  4701.2  508.00  4757.9  511.59  4779.5  508.47  4963.2  511.60
  4977.4  509.82  4993.2  499.20  4993.8  498.40  5004.8  499.20  5009.5  508.00
  5026.6  511.53  5119.2  508.57  5267.7  512.35  5388.3  506.99  5466.1  510.89
  5528.0  508.62  5594.2  505.90  5632.1  512.29  5757.0  520.84  6075.9  529.23
#Mann=5,-1,0
  2571.1    0.05       0  4551.5    0.12       0  4993.2    0.07       0
  5004.8    0.12       0  5528.0    0.16       0
Bank Sta=4227.4,5632.1
Exp/Cntr=0.3,0.1

Type RM Length L Ch R = 1,10454,1504,1504,1504
BEGIN DESCRIPTION:
MIDDLE FORK TURKEY CREEK 5.0
END DESCRIPTION:
XS GIS Cut Line= 3
      2775524.99      7083624.99      2774725.00      7083075.00
      2773825.04      7082225.03
#Sta/Elev= 30
  4032.3  521.56  4111.4  516.41  4190.9  515.81  4362.4  511.73  4371.2  512.13
  4413.2  509.15  4428.1  509.96  4499.8  509.06  4519.5  510.14  4578.4  510.83
  4622.2  508.22  4664.1  507.98  4723.7  510.18  4888.1  509.00  4974.7  510.26
  4989.6  505.22  4989.8  499.13  4990.4  498.33  5001.5  499.13  5010.2  500.44
  5017.1  506.53  5031.2  510.85  5194.3  511.38  5484.3  509.89  5554.7  510.82
  5781.3  505.95  5893.3  510.13  5917.4  511.73  6000.3  514.90  6241.0  527.34
#Mann=6,-1,0
  4032.3    0.05       0  4190.9    0.16       0  4519.5    0.12       0
  4989.8    0.07       0  5001.5    0.12       0  5893.3    0.16       0
Bank Sta=4362.4,5917.4
Exp/Cntr=0.3,0.1

Type RM Length L Ch R = 1,8950,794,794,794
BEGIN DESCRIPTION:
MIDDLE FORK TURKEY CREEK 3.0
END DESCRIPTION:
XS GIS Cut Line= 3
      2775775.02      7082925.01      2774875.00      7082375.00
      2773974.96      7082074.99
#Sta/Elev= 30
  3938.6  517.56  3989.0  515.24  4181.6  511.98  4264.5  510.90  4328.0  510.45
  4414.8  509.52  4519.9  508.78  4600.5  509.62  4943.0  508.91  4948.9  508.51
  4958.2  504.45  4964.3  497.17  5008.6  496.65  5009.2  495.85  5020.3  496.65
  5035.5  505.27  5046.1  508.72  5056.6  509.02  5140.9  506.96  5278.0  506.88
  5288.5  506.67  5299.1  504.57  5309.6  507.15  5366.9  505.93  5415.0  506.38
  5457.2  508.89  5591.9  510.14  5616.5  510.45  5762.4  517.29  5942.1  526.01
#Mann=10,-1,0
  3938.6    0.05       0  4181.6    0.16       0  4264.5    0.05       0
  4414.8    0.16       0  4519.9    0.12       0  5008.6    0.07       0
  5020.3    0.12       0  5366.9    0.16       0  5591.9    0.12       0
  5762.4    0.16       0
Bank Sta=4328,5616.5
Exp/Cntr=0.3,0.1

Type RM Length L Ch R = 1,8156,952,952,952
BEGIN DESCRIPTION:
MIDDLE FORK TURKEY CREEK 2.0
END DESCRIPTION:
XS GIS Cut Line= 3
      2776475.01      7083575.01      2775275.00      7081925.00
      2773924.96      7081474.99
#Sta/Elev= 30
  2973.3  544.49  3418.1  533.56  3863.2  519.62  4033.2  514.10  4262.9  510.71
  4335.9  509.41  4579.0  508.14  4741.1  507.89  4805.3  508.79  4849.8  507.03
  4970.6  508.10  4976.8  507.03  4985.3  500.39  4985.6  495.19  4986.1  494.39
  4997.5  495.19  5000.0  496.64  5006.2  503.81  5010.4  505.47  5034.6  508.06
  5213.8  507.37  5245.4  505.23  5298.1  507.96  5535.5  507.79  5809.1  509.41
  5829.4  510.06  5853.7  510.23  6067.6  514.45  6246.8  523.95  6436.6  528.44
#Mann=11,-1,0
  2973.3    0.05       0  3863.2    0.16       0  4262.9    0.05       0
  4579.0    0.12       0  4741.1    0.16       0  4849.8    0.12       0
  4985.6    0.07       0  4997.5    0.12       0  5535.5    0.16       0
  5829.4    0.12       0  5853.7    0.16       0
Bank Sta=4335.9,5809.1
Exp/Cntr=0.3,0.1

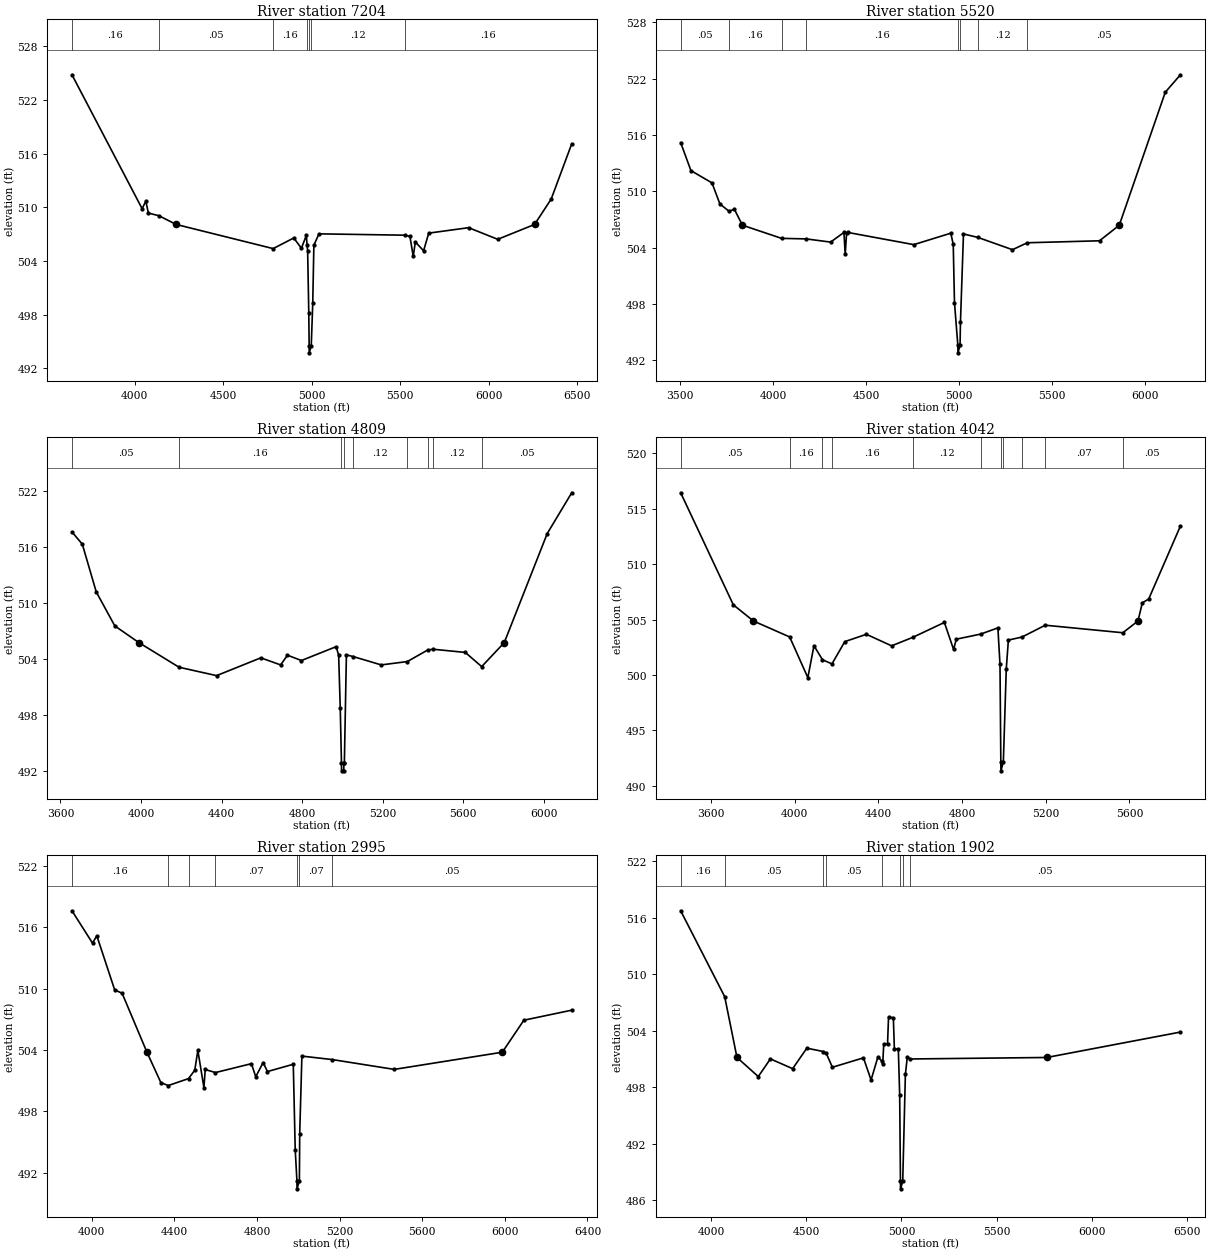
Type RM Length L Ch R = 1,7204,1684,1684,1684
BEGIN DESCRIPTION:
Mapping XS a34099c8
END DESCRIPTION:
XS GIS Cut Line= 5
      2776673.21      7082546.24      2775839.89      7081591.39
      2775709.68      7081487.22      2775449.26      7081530.63
      2774408.77      7081097.09
#Sta/Elev= 30
  3644.7  524.80  4041.4  509.83  4062.3  510.68  4076.6  509.34  4135.8  509.05
  4233.9  508.07  4782.2  505.37  4898.6  506.56  4941.9  505.41  4969.5  506.84
  4973.9  505.82  4977.1  505.08  4983.5  498.22  4985.6  494.52  4986.1  493.72
  4997.5  494.52  5005.9  499.24  5012.3  505.75  5041.1  507.02  5527.2  506.87
  5555.5  506.73  5574.0  504.49  5585.8  506.11  5632.5  505.13  5661.7  507.10
  5887.0  507.71  6051.7  506.41  6260.0  508.07  6354.0  510.91  6470.0  517.08
#Mann=7,-1,0
  3644.7    0.16       0  4135.8    0.05       0  4782.2    0.16       0
  4973.9    0.12       0  4985.6    0.07       0  4997.5    0.12       0
  5527.2    0.16       0
Bank Sta=4233.9,6260
Exp/Cntr=0.3,0.1

Type RM Length L Ch R = 1,5520,711,711,711
BEGIN DESCRIPTION:
Mapping XS 581e94c7
END DESCRIPTION:
XS GIS Cut Line= 3
      2776950.98      7081886.51      2775831.21      7080940.35
      2774695.40      7080489.49
#Sta/Elev= 30
  3503.7  515.18  3558.8  512.20  3672.0  510.89  3714.8  508.64  3763.2  507.88
  3792.8  508.07  3835.7  506.38  4046.2  504.98  4179.4  504.92  4310.3  504.58
  4381.8  505.61  4388.7  503.29  4396.1  505.54  4402.6  505.61  4757.6  504.31
  4956.5  505.53  4969.7  504.35  4976.4  498.13  4994.5  493.58  4995.0  492.78
  5006.4  493.58  5008.6  496.07  5024.8  505.45  5102.1  505.08  5288.4  503.77
  5367.9  504.51  5756.5  504.72  5862.8  506.38  6110.2  520.55  6191.7  522.41
#Mann=8,-1,0
  3503.7    0.05       0  3763.2    0.16       0  4046.2    0.05       0
  4179.4    0.16       0  4994.5    0.07       0  5006.4    0.16       0
  5102.1    0.12       0  5367.9    0.05       0
Bank Sta=3835.7,5862.8
Exp/Cntr=0.3,0.1

Type RM Length L Ch R = 1,4809,767,767,767
BEGIN DESCRIPTION:
Mapping XS 92fd98fa
END DESCRIPTION:
XS GIS Cut Line= 3
      2777159.33      7081140.00      2775952.73      7080593.13
      2774815.60      7080376.12
#Sta/Elev= 30
  3657.2  517.60  3708.5  516.29  3777.8  511.17  3870.1  507.52  3989.8  505.73
  4189.2  503.09  4375.6  502.19  4595.2  504.10  4693.7  503.34  4727.7  504.38
  4797.0  503.81  4969.6  505.30  4981.9  504.37  4989.8  498.73  4995.9  492.78
  4996.4  491.98  5007.3  491.98  5007.8  492.78  5010.2  492.81  5020.4  504.42
  5054.7  504.23  5193.4  503.34  5323.1  503.70  5423.5  504.93  5451.0  505.02
  5610.8  504.68  5692.4  503.16  5804.5  505.73  6018.0  517.43  6139.6  521.80
#Mann=9,-1,0
  3657.2    0.05       0  4189.2    0.16       0  4995.9    0.07       0
  5007.8    0.16       0  5054.7    0.12       0  5323.1    0.07       0
  5423.5    0.05       0  5451.0    0.12       0  5692.4    0.05       0
Bank Sta=3989.8,5804.5
Exp/Cntr=0.3,0.1

Type RM Length L Ch R = 1,4042,1047,1047,1047
BEGIN DESCRIPTION:
Mapping XS 4375712f
END DESCRIPTION:
XS GIS Cut Line= 3
      2777306.87      7080775.40      2776004.82      7080080.97
      2775093.35      7080054.93
#Sta/Elev= 30
  3456.0  516.45  3707.5  506.34  3803.7  504.88  3976.7  503.44  4063.5  499.77
  4092.8  502.65  4133.5  501.38  4178.8  501.01  4240.1  503.02  4343.3  503.68
  4463.7  502.64  4564.4  503.40  4715.8  504.75  4759.8  502.31  4772.8  503.24
  4889.3  503.70  4971.5  504.26  4981.5  500.96  4985.5  492.16  4986.0  491.36
  4997.5  492.16  5011.5  500.55  5021.5  503.16  5086.3  503.43  5197.8  504.50
  5568.3  503.82  5640.8  504.88  5661.4  506.52  5691.8  506.86  5843.5  513.45
#Mann=11,-1,0
  3456.0    0.05       0  3976.7    0.16       0  4133.5    0.12       0
  4178.8    0.16       0  4564.4    0.12       0  4889.3    0.07       0
  4985.5    0.07       0  4997.5    0.07       0  5086.3    0.05       0
  5197.8    0.07       0  5568.3    0.05       0
Bank Sta=3803.7,5640.8
Exp/Cntr=0.3,0.1

Type RM Length L Ch R = 1,2995,1093,1093,1093
BEGIN DESCRIPTION:
Mapping XS e4d9f02c
END DESCRIPTION:
XS GIS Cut Line= 4
      2777289.53      7080428.19      2776464.89      7079855.28
      2776386.76      7079672.99      2775223.54      7079317.08
#Sta/Elev= 30
  3904.8  517.60  4004.2  514.44  4025.2  515.15  4111.6  509.86  4147.4  509.54
  4267.7  503.77  4335.1  500.80  4371.0  500.51  4468.9  501.19  4499.2  502.01
  4514.1  503.95  4543.5  500.31  4549.8  502.08  4599.3  501.78  4773.4  502.65
  4794.3  501.37  4830.1  502.76  4851.0  501.88  4976.0  502.59  4985.4  494.23
  4993.6  491.21  4994.1  490.41  5005.6  491.21  5007.1  495.82  5017.7  503.39
  5164.8  503.05  5464.7  502.09  5987.7  503.77  6092.1  506.90  6323.7  507.88
#Mann=7,-1,0
  3904.8    0.16       0  4371.0    0.05       0  4468.9    0.16       0
  4599.3    0.07       0  4993.6    0.07       0  5005.6    0.07       0
  5164.8    0.05       0
Bank Sta=4267.7,5987.7
Exp/Cntr=0.3,0.1

Type RM Length L Ch R = 1,1902,0,0,0
BEGIN DESCRIPTION:
MIDDLE FORK TURKEY CREEK 1.0
END DESCRIPTION:
XS GIS Cut Line= 3
      2777202.73      7080028.88      2776812.11      7078952.50
      2775328.88      7079004.54
#Sta/Elev= 30
  3838.4  516.75  4070.0  507.62  4134.6  501.16  4246.8  499.13  4310.4  501.01
  4427.5  499.97  4502.1  502.15  4589.5  501.79  4604.4  501.60  4636.5  500.12
  4800.0  501.12  4840.1  498.77  4876.1  501.22  4896.5  500.78  4901.4  500.47
  4906.7  502.58  4926.7  502.60  4932.0  505.45  4957.3  505.38  4962.6  502.11
  4983.5  502.04  4990.6  497.17  4994.6  488.00  4995.1  487.20  5006.6  488.00
  5020.6  499.36  5030.6  501.20  5045.0  501.00  5764.4  501.16  6467.6  503.86
#Mann=8,-1,0
  3838.4    0.16       0  4070.0    0.05       0  4589.5    0.16       0
  4604.4    0.05       0  4896.5    0.16       0  4994.6    0.07       0
  5006.6    0.16       0  5045.0    0.05       0
Bank Sta=4134.6,5764.4
Exp/Cntr=0.3,0.1

Chan Stop Cuts=-1