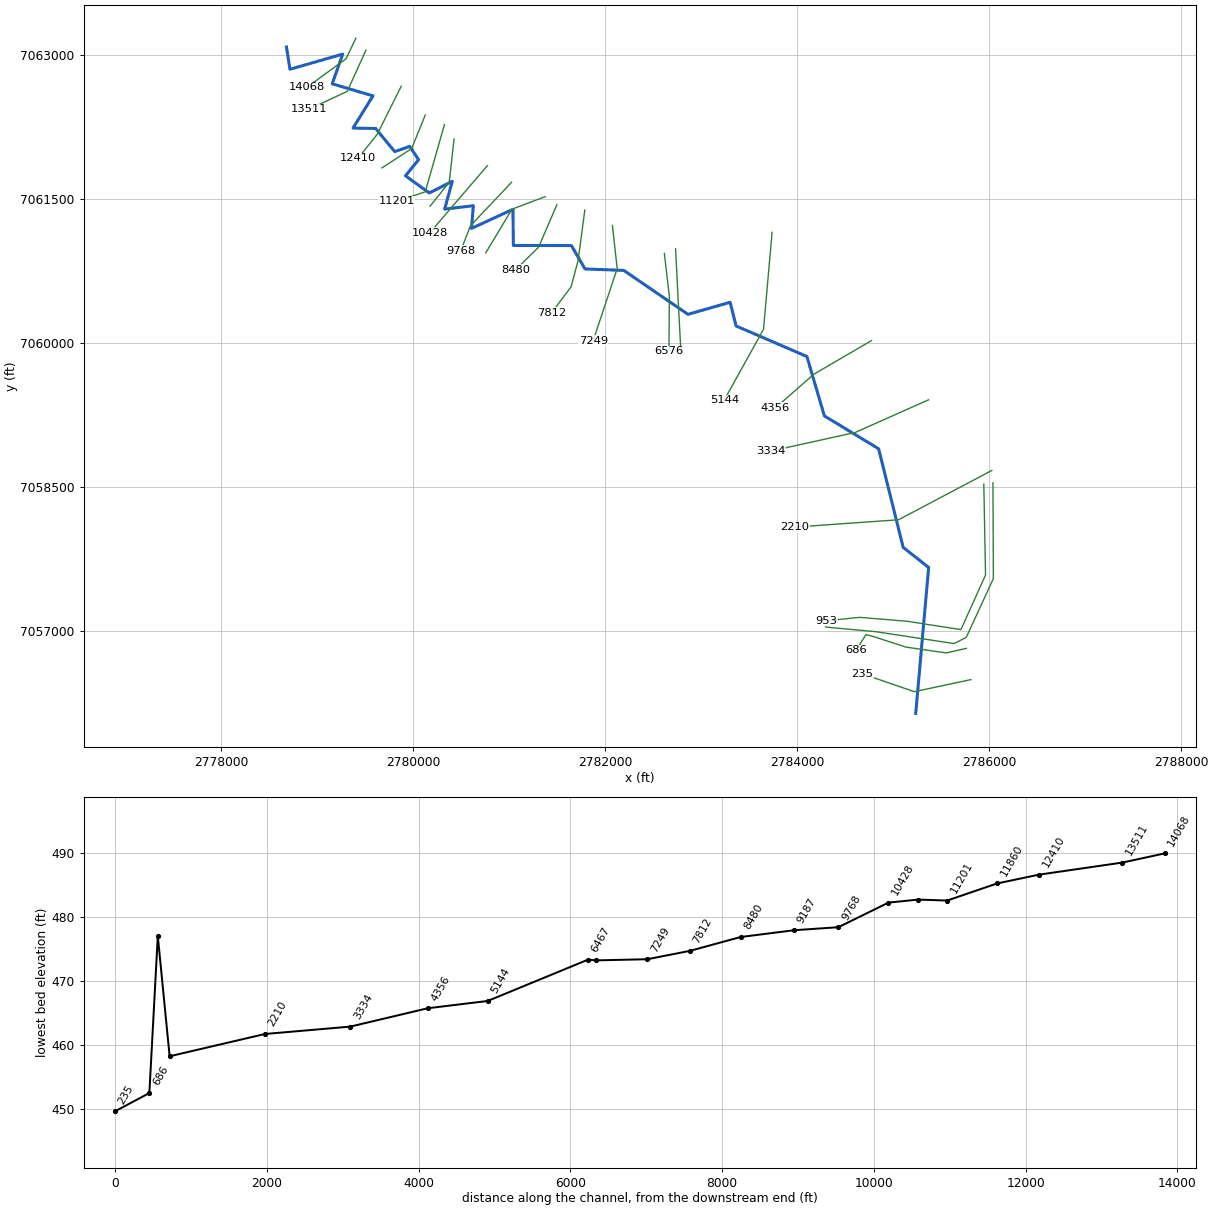
--- MITCHAM BRANCH.prj (project) ---

Proj Title=MITCHAM BRANCH Base Level Engineering
Current Plan=p01
Default Exp/Contr=0.3,0.1
English Units
Geom File=g01
Flow File=f01
Plan File=p01
BEGIN DESCRIPTION:
MITCHAM BRANCH
END DESCRIPTION:

--- MITCHAM BRANCH.p01 (plan) ---

Plan Title=Multiple Run
Short Identifier=Multiple
Geom File=g01
Flow File=f01
Subcritical Flow
K Sum by GR= 0
Std Step Tol= 0.01
Critical Tol= 0.01
Num of Std Step Trials= 20
Max Error Tol= 0.3
Flow Tol Ratio= 0.001
Split Flow NTrial= 30
Split Flow Tol= 0.02
Split Flow Ratio= 0.02
Log Output Level= 0
Friction Slope Method= 1
Unsteady Friction Slope Method= 2
Unsteady Bridges Friction Slope Method= 1
Parabolic Critical Depth
Global Vel Dist=  1 , 1 , 1
Global Log Level= 0
CheckData=True
Encroach Param= -1, 0, 0, 0
BEGIN DESCRIPTION:
Multiple Run
END DESCRIPTION:

--- MITCHAM BRANCH.f01 (steady flow) ---

Flow Title=Multiple
Number of Profiles=7
Profile Names=10-year,25-year,50-year,1pct_min,100-year,1pct_plu,500-year
River Rch & RM= MITCHAM BRANCH,Reach-1,14068
     681     910    1093     652    1300    2594    1834
River Rch & RM= MITCHAM BRANCH,Reach-1,13511
     732     979    1178     702    1401    2795    1979
River Rch & RM= MITCHAM BRANCH,Reach-1,7812
     983    1335    1623     977    1949    3888    2805
River Rch & RM= MITCHAM BRANCH,Reach-1,3334
    1386    1916    2357    1433    2859    5705    4205
Boundary for River Rch & Prof#=MITCHAM BRANCH,Reach-1,1
Up Type=0
Dn Type=3
Dn Slope=0.005
Boundary for River Rch & Prof#=MITCHAM BRANCH,Reach-1,2
Up Type=0
Dn Type=3
Dn Slope=0.005
Boundary for River Rch & Prof#=MITCHAM BRANCH,Reach-1,3
Up Type=0
Dn Type=3
Dn Slope=0.005
Boundary for River Rch & Prof#=MITCHAM BRANCH,Reach-1,4
Up Type=0
Dn Type=3
Dn Slope=0.005
Boundary for River Rch & Prof#=MITCHAM BRANCH,Reach-1,5
Up Type=0
Dn Type=3
Dn Slope=0.005
Boundary for River Rch & Prof#=MITCHAM BRANCH,Reach-1,6
Up Type=0
Dn Type=3
Dn Slope=0.005
Boundary for River Rch & Prof#=MITCHAM BRANCH,Reach-1,7
Up Type=0
Dn Type=3
Dn Slope=0.005

--- MITCHAM BRANCH.g01 (geometry) ---

Geom Title=Existing Conditions

River Reach=MITCHAM BRANCH,Reach-1
Reach XY= 30
      2778678.82      7063084.08      2778715.52      7062851.91
      2779265.22      7063009.91      2779155.63      7062700.56
      2779580.19      7062574.71      2779372.31      7062238.90
      2779607.88      7062235.32      2779806.96      7061994.18
      2779963.13      7062048.41      2780055.70      7061909.55
      2779918.93      7061742.04      2780166.97      7061563.35
      2780406.73      7061684.64      2780326.93      7061395.16
      2780625.90      7061429.96      2780606.80      7061193.57
      2781039.01      7061392.99      2781042.90      7061016.02
      2781647.99      7061015.06      2781789.66      7060771.42
      2782193.92      7060756.08      2782862.56      7060298.59
      2783301.11      7060424.02      2783363.37      7060177.68
      2784101.49      7059859.14      2784283.77      7059240.13
      2784849.54      7058897.24      2785104.01      7057871.26
      2785370.20      7057661.01      2785235.59      7056140.71

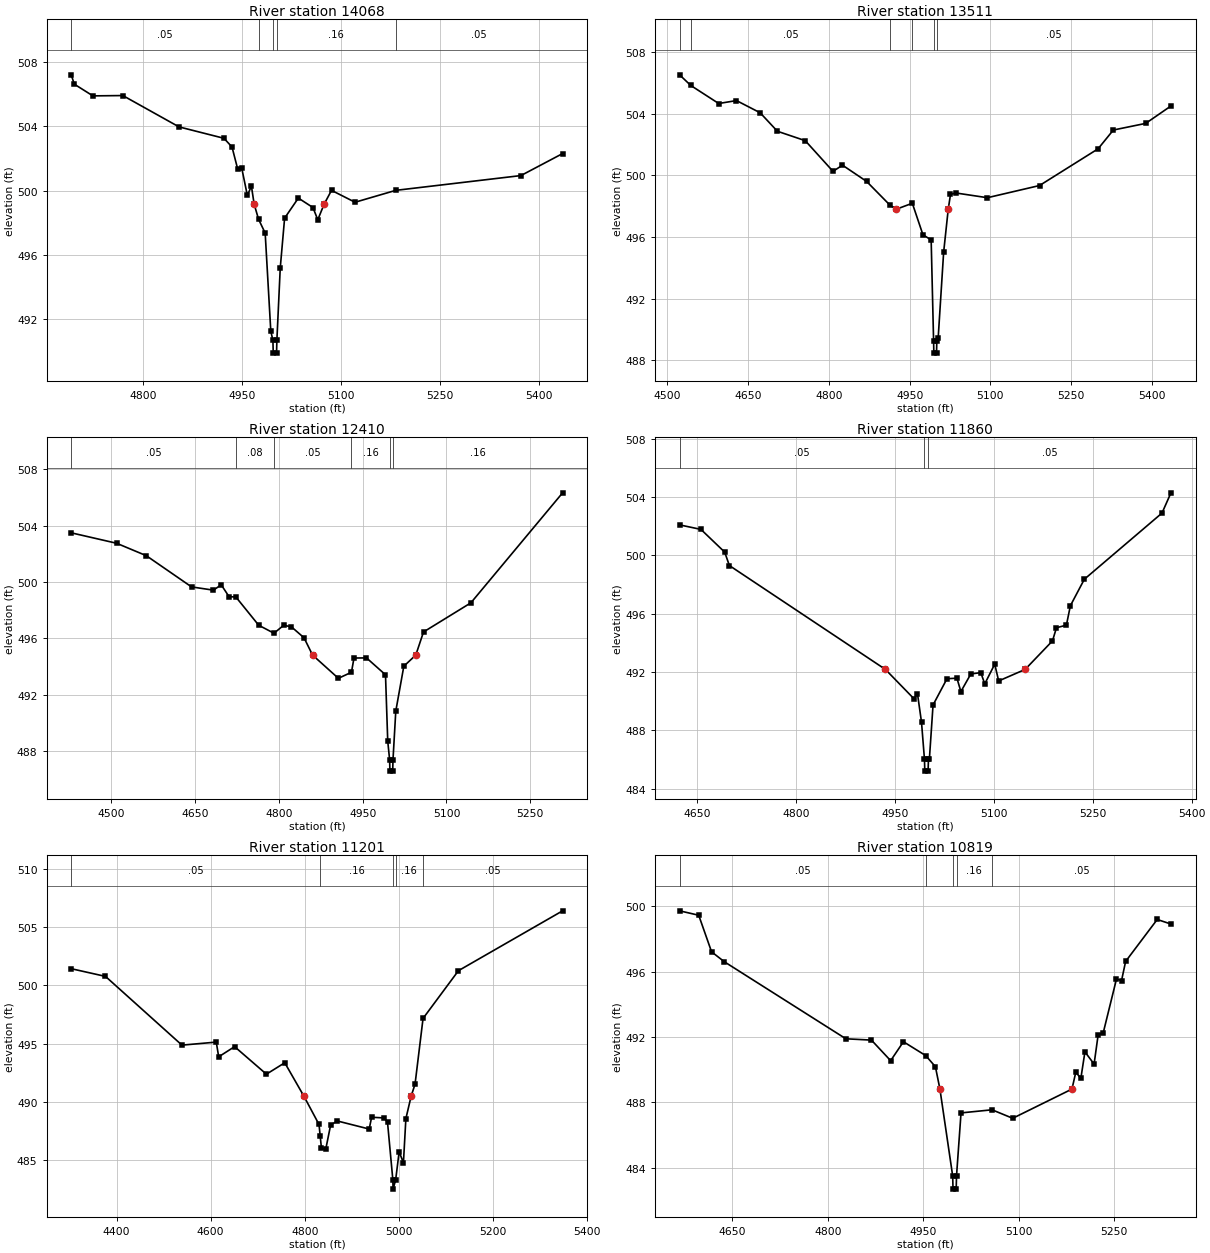
Type RM Length L Ch R = 1,14068,557,557,557
BEGIN DESCRIPTION:
MITCHAM BRANCH 21.0
END DESCRIPTION:
XS GIS Cut Line= 3
      2779401.92      7063174.25      2779299.90      7062961.54
      2778889.87      7062662.16
#Sta/Elev= 30
  4691.6  507.21  4696.2  506.63  4724.4  505.90  4769.7  505.92  4854.7  503.97
  4922.7  503.26  4934.9  502.72  4943.4  501.36  4949.6  501.41  4958.1  499.71
  4964.3  500.28  4968.4  499.16  4975.1  498.22  4985.1  497.36  4993.6  491.25
  4996.8  490.69  4997.3  489.89  5002.3  489.89  5002.8  490.69  5007.9  495.19
  5014.5  498.29  5035.3  499.54  5057.4  498.95  5064.7  498.19  5074.3  499.16
  5085.5  500.02  5121.1  499.28  5182.7  500.02  5372.1  500.94  5435.2  502.31
#Mann=5,-1,0
  4691.6    0.05       0  4975.1    0.16       0  4996.8    0.07       0
  5002.8    0.16       0  5182.7    0.05       0
Bank Sta=4968.4,5074.3
Exp/Cntr=0.3,0.1

Type RM Length L Ch R = 1,13511,1101,1101,1101
BEGIN DESCRIPTION:
Mapping XS aaa2c7f2
END DESCRIPTION:
XS GIS Cut Line= 3
      2779507.13      7063051.20      2779311.84      7062621.55
      2778912.55      7062434.93
#Sta/Elev= 30
  4522.7  506.51  4543.5  505.82  4595.4  504.65  4628.4  504.84  4672.3  504.05
  4704.4  502.85  4756.1  502.24  4807.7  500.25  4825.3  500.65  4870.0  499.60
  4913.4  498.06  4925.0  497.79  4955.0  498.18  4974.7  496.14  4990.0  495.80
  4994.5  489.26  4995.0  488.46  5000.0  488.46  5000.5  489.26  5003.0  489.43
  5013.2  495.01  5021.7  497.79  5025.9  498.75  5035.3  498.85  5094.4  498.54
  5191.3  499.33  5300.0  501.71  5328.4  502.93  5388.5  503.36  5435.4  504.49
#Mann=6,-1,0
  4522.7    0.08       0  4543.5    0.05       0  4913.4    0.16       0
  4955.0    0.05       0  4994.5    0.03       0  5000.5    0.05       0
Bank Sta=4925,5021.7
Exp/Cntr=0.3,0.1

Type RM Length L Ch R = 1,12410,550,550,550
BEGIN DESCRIPTION:
MITCHAM BRANCH 19.0
END DESCRIPTION:
XS GIS Cut Line= 3
      2779875.01      7062675.03      2779625.00      7062175.00
      2779425.00      7061925.00
#Sta/Elev= 30
  4428.6  503.49  4509.7  502.75  4562.8  501.87  4643.9  499.65  4683.0  499.42
  4697.0  499.80  4710.9  498.96  4723.3  498.93  4764.0  496.93  4791.4  496.36
  4808.8  496.93  4822.7  496.81  4845.1  496.04  4860.4  494.81  4906.6  493.16
  4930.0  493.59  4934.5  494.60  4956.9  494.61  4990.9  493.41  4994.9  488.70
  4998.3  487.37  4998.8  486.57  5003.8  486.57  5004.3  487.37  5009.3  490.83
  5023.7  494.02  5045.1  494.81  5058.9  496.45  5143.7  498.52  5307.8  506.33
#Mann=6,-1,0
  4428.6    0.05       0  4723.3    0.08       0  4791.4    0.05       0
  4930.0    0.16       0  4998.3    0.07       0  5004.3    0.16       0
Bank Sta=4860.4,5045.1
Exp/Cntr=0.3,0.1

Type RM Length L Ch R = 1,11860,659,659,659
BEGIN DESCRIPTION:
MITCHAM BRANCH 18.0
END DESCRIPTION:
XS GIS Cut Line= 3
      2780125.00      7062375.01      2779983.88      7062026.06
      2779674.96      7061824.97
#Sta/Elev= 30
  4623.6  502.10  4656.0  501.79  4692.0  500.23  4699.1  499.31  4935.7  492.18
  4978.9  490.17  4984.3  490.51  4990.4  488.56  4994.9  486.00  4995.4  485.20
  5000.4  485.20  5000.9  486.00  5002.3  486.00  5007.9  489.74  5029.0  491.54
  5044.1  491.58  5050.1  490.66  5065.2  491.87  5080.3  491.96  5086.3  491.19
  5101.4  492.54  5107.4  491.39  5147.5  492.18  5189.0  494.14  5195.0  495.04
  5210.1  495.22  5216.1  496.55  5237.3  498.37  5355.0  502.91  5368.6  504.30
#Mann=3,-1,0
  4623.6    0.05       0  4994.9    0.03       0  5000.9    0.05       0
Bank Sta=4935.7,5147.5
Exp/Cntr=0.3,0.1

Type RM Length L Ch R = 1,11201,382,382,382
BEGIN DESCRIPTION:
MITCHAM BRANCH 17.0
END DESCRIPTION:
XS GIS Cut Line= 3
      2780325.01      7062275.04      2780125.00      7061575.00
      2779824.99      7061475.00
#Sta/Elev= 30
  4303.7  501.42  4376.5  500.76  4539.0  494.87  4611.9  495.13  4617.1  493.87
  4650.9  494.74  4718.5  492.38  4757.5  493.36  4798.4  490.48  4830.3  488.07
  4832.8  487.08  4835.5  486.02  4844.6  485.95  4855.0  488.03  4869.3  488.37
  4936.9  487.68  4942.1  488.69  4969.4  488.63  4975.9  488.25  4987.2  483.33
  4987.7  482.53  4993.2  483.33  5000.6  485.73  5009.7  484.79  5014.9  488.57
  5026.0  490.48  5034.4  491.53  5051.4  497.16  5126.6  501.25  5348.0  506.38
#Mann=5,-1,0
  4303.7    0.05       0  4832.8    0.16       0  4987.2    0.07       0
  4993.2    0.16       0  5051.4    0.05       0
Bank Sta=4798.4,5026
Exp/Cntr=0.3,0.1

Type RM Length L Ch R = 1,10819,391,391,391
BEGIN DESCRIPTION:
MITCHAM BRANCH 16.0
END DESCRIPTION:
XS GIS Cut Line= 3
      2780425.00      7062124.96      2780375.00      7061675.00
      2780174.99      7061424.99
#Sta/Elev= 30
  4566.8  499.73  4596.9  499.46  4617.1  497.22  4637.2  496.61  4828.4  491.89
  4868.6  491.81  4898.8  490.55  4918.9  491.71  4954.0  490.86  4969.2  490.18
  4976.3  488.81  4996.4  483.48  4996.9  482.68  5001.9  482.68  5002.4  483.48
  5009.5  487.35  5058.3  487.54  5090.8  487.02  5184.0  488.81  5190.0  489.84
  5198.0  489.47  5204.4  491.09  5218.8  490.34  5225.2  492.14  5233.2  492.26
  5254.0  495.55  5262.0  495.46  5268.4  496.63  5318.1  499.20  5339.7  498.92
#Mann=5,-1,0
  4566.8    0.05       0  4954.0    0.16       0  4996.4    0.07       0
  5002.4    0.16       0  5058.3    0.05       0
Bank Sta=4976.3,5184
Exp/Cntr=0.3,0.1

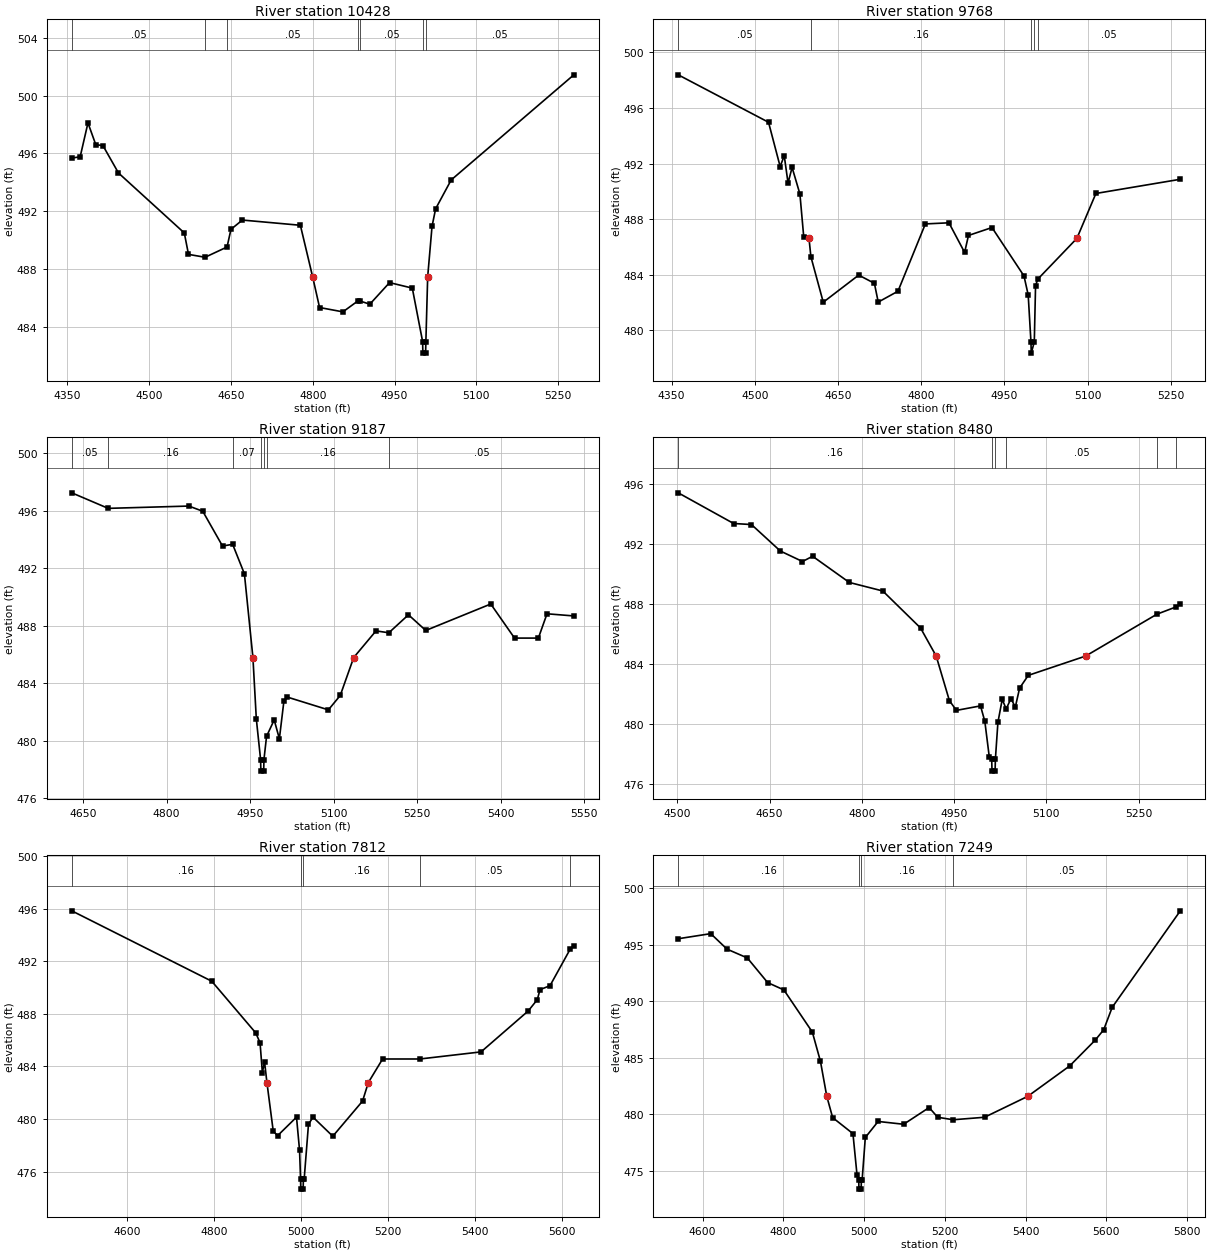
Type RM Length L Ch R = 1,10428,660,660,660
BEGIN DESCRIPTION:
MITCHAM BRANCH 15.0
END DESCRIPTION:
XS GIS Cut Line= 3
      2780772.89      7061848.40      2780472.92      7061498.44
      2780173.57      7061149.20
#Sta/Elev= 30
  4357.9  495.68  4373.3  495.77  4387.6  498.11  4401.9  496.61  4415.1  496.54
  4443.6  494.65  4564.3  490.51  4572.0  489.03  4602.4  488.83  4642.7  489.54
  4649.9  490.76  4670.8  491.40  4777.2  491.04  4799.7  487.48  4812.4  485.36
  4855.2  485.06  4883.3  485.83  4887.3  485.80  4904.6  485.59  4940.8  487.08
  4982.5  486.70  5001.4  483.01  5001.9  482.21  5006.9  482.21  5007.4  483.01
  5010.7  487.48  5018.7  490.97  5025.3  492.18  5053.8  494.17  5278.8  501.43
#Mann=7,-1,0
  4357.9    0.05       0  4602.4    0.16       0  4642.7    0.05       0
  4883.3    0.16       0  4887.3    0.05       0  5001.4    0.03       0
  5007.4    0.05       0
Bank Sta=4799.7,5010.7
Exp/Cntr=0.3,0.1

Type RM Length L Ch R = 1,9768,581,581,581
BEGIN DESCRIPTION:
MITCHAM BRANCH 14.0
END DESCRIPTION:
XS GIS Cut Line= 3
      2781024.98      7061674.98      2780596.61      7061222.14
      2780494.31      7060959.40
#Sta/Elev= 30
  4362.0  498.38  4524.8  494.97  4545.8  491.78  4553.1  492.57  4560.0  490.60
  4567.3  491.72  4581.4  489.81  4588.3  486.72  4597.8  486.62  4601.2  485.30
  4623.5  482.03  4687.4  483.98  4715.7  483.39  4722.6  482.04  4758.2  482.82
  4807.6  487.66  4850.1  487.74  4878.4  485.61  4885.3  486.83  4927.7  487.40
  4985.4  483.92  4993.0  482.56  4998.0  479.17  4998.5  478.37  5004.0  479.17
  5006.3  483.22  5010.3  483.69  5080.8  486.62  5115.1  489.85  5267.3  490.87
#Mann=5,-1,0
  4362.0    0.05       0  4601.2    0.16       0  4998.0    0.07       0
  5004.0    0.16       0  5010.3    0.05       0
Bank Sta=4597.8,5080.8
Exp/Cntr=0.3,0.1

Type RM Length L Ch R = 1,9187,707,707,707
BEGIN DESCRIPTION:
MITCHAM BRANCH 13.0
END DESCRIPTION:
XS GIS Cut Line= 3
      2781375.00      7061525.00      2781028.50      7061394.10
      2780755.35      7060938.51
#Sta/Elev= 30
  4629.6  497.25  4695.0  496.17  4839.9  496.33  4864.8  495.97  4900.3  493.55
  4918.5  493.67  4939.6  491.62  4954.9  485.80  4961.0  481.53  4968.7  478.70
  4969.2  477.90  4974.2  477.90  4974.7  478.70  4979.4  480.32  4993.1  481.46
  5002.4  480.15  5010.6  482.79  5016.5  483.05  5090.4  482.16  5111.7  483.16
  5135.9  485.80  5175.9  487.65  5199.0  487.52  5234.2  488.77  5265.3  487.68
  5382.0  489.52  5424.7  487.15  5467.5  487.15  5483.0  488.84  5531.2  488.69
#Mann=7,-1,0
  4629.6    0.05       0  4695.0    0.16       0  4918.5    0.07       0
  4968.7    0.07       0  4974.7    0.07       0  4979.4    0.16       0
  5199.0    0.05       0
Bank Sta=4954.9,5135.9
Exp/Cntr=0.3,0.1

Type RM Length L Ch R = 1,8480,668,668,668
BEGIN DESCRIPTION:
Mapping XS 2ccf8f05
END DESCRIPTION:
XS GIS Cut Line= 3
      2781496.67      7061440.53      2781305.70      7060997.83
      2781066.97      7060763.44
#Sta/Elev= 30
  4501.3  495.44  4591.4  493.39  4620.4  493.32  4667.4  491.55  4703.4  490.85
  4719.9  491.20  4779.6  489.45  4834.0  488.88  4895.4  486.41  4920.9  484.53
  4942.4  481.55  4953.8  480.90  4993.0  481.20  5000.0  480.17  5007.2  477.81
  5011.2  477.64  5011.7  476.84  5016.7  476.84  5017.2  477.64  5021.3  480.10
  5028.3  481.63  5034.8  481.00  5042.5  481.69  5049.6  481.12  5056.6  482.39
  5070.7  483.24  5164.0  484.53  5280.0  487.33  5310.8  487.81  5318.0  487.99
#Mann=6,-1,0
  4501.3    0.16       0  5011.2    0.07       0  5017.2    0.16       0
  5034.8    0.05       0  5280.0    0.12       0  5310.8    0.05       0
Bank Sta=4920.9,5164
Exp/Cntr=0.3,0.1

Type RM Length L Ch R = 1,7812,563,563,563
BEGIN DESCRIPTION:
Mapping XS 61803874
END DESCRIPTION:
XS GIS Cut Line= 4
      2781787.46      7061384.06      2781718.02      7060858.94
      2781644.24      7060585.50      2781440.22      7060312.03
#Sta/Elev= 30
  4472.5  495.83  4794.3  490.48  4895.2  486.56  4905.3  485.81  4910.6  483.53
  4915.6  484.36  4921.1  482.78  4935.6  479.09  4945.6  478.74  4989.1  480.15
  4996.1  477.63  4998.4  475.48  4998.9  474.68  5004.4  474.68  5004.9  475.48
  5006.8  475.48  5016.6  479.60  5027.0  480.15  5072.5  478.70  5140.9  481.37
  5154.2  482.78  5187.0  484.57  5272.6  484.57  5413.3  485.11  5521.7  488.22
  5542.6  489.08  5548.8  489.84  5571.8  490.14  5618.9  492.96  5626.6  493.15
#Mann=5,-1,0
  4472.5    0.16       0  4998.4    0.07       0  5004.9    0.16       0
  5272.6    0.05       0  5618.9    0.16       0
Bank Sta=4921.1,5154.2
Exp/Cntr=0.3,0.1

Type RM Length L Ch R = 1,7249,673,673,673
BEGIN DESCRIPTION:
MITCHAM BRANCH 10.0
END DESCRIPTION:
XS GIS Cut Line= 3
      2782075.00      7061225.02      2782125.00      7060775.00
      2781874.99      7060024.96
#Sta/Elev= 30
  4539.9  495.53  4620.4  495.98  4660.7  494.61  4711.0  493.83  4761.3  491.65
  4801.5  491.00  4872.0  487.27  4892.1  484.68  4907.8  481.58  4922.3  479.70
  4972.6  478.28  4982.6  474.65  4986.9  474.17  4987.4  473.37  4992.9  473.37
  4993.4  474.17  4995.3  474.17  5003.2  477.94  5034.9  479.36  5098.1  479.11
  5161.3  480.59  5182.4  479.73  5220.8  479.51  5298.4  479.73  5405.4  481.58
  5509.2  484.27  5572.4  486.55  5593.5  487.47  5614.6  489.46  5783.3  498.00
#Mann=4,-1,0
  4539.9    0.16       0  4986.9    0.07       0  4993.4    0.16       0
  5220.8    0.05       0
Bank Sta=4907.8,5405.4
Exp/Cntr=0.3,0.1

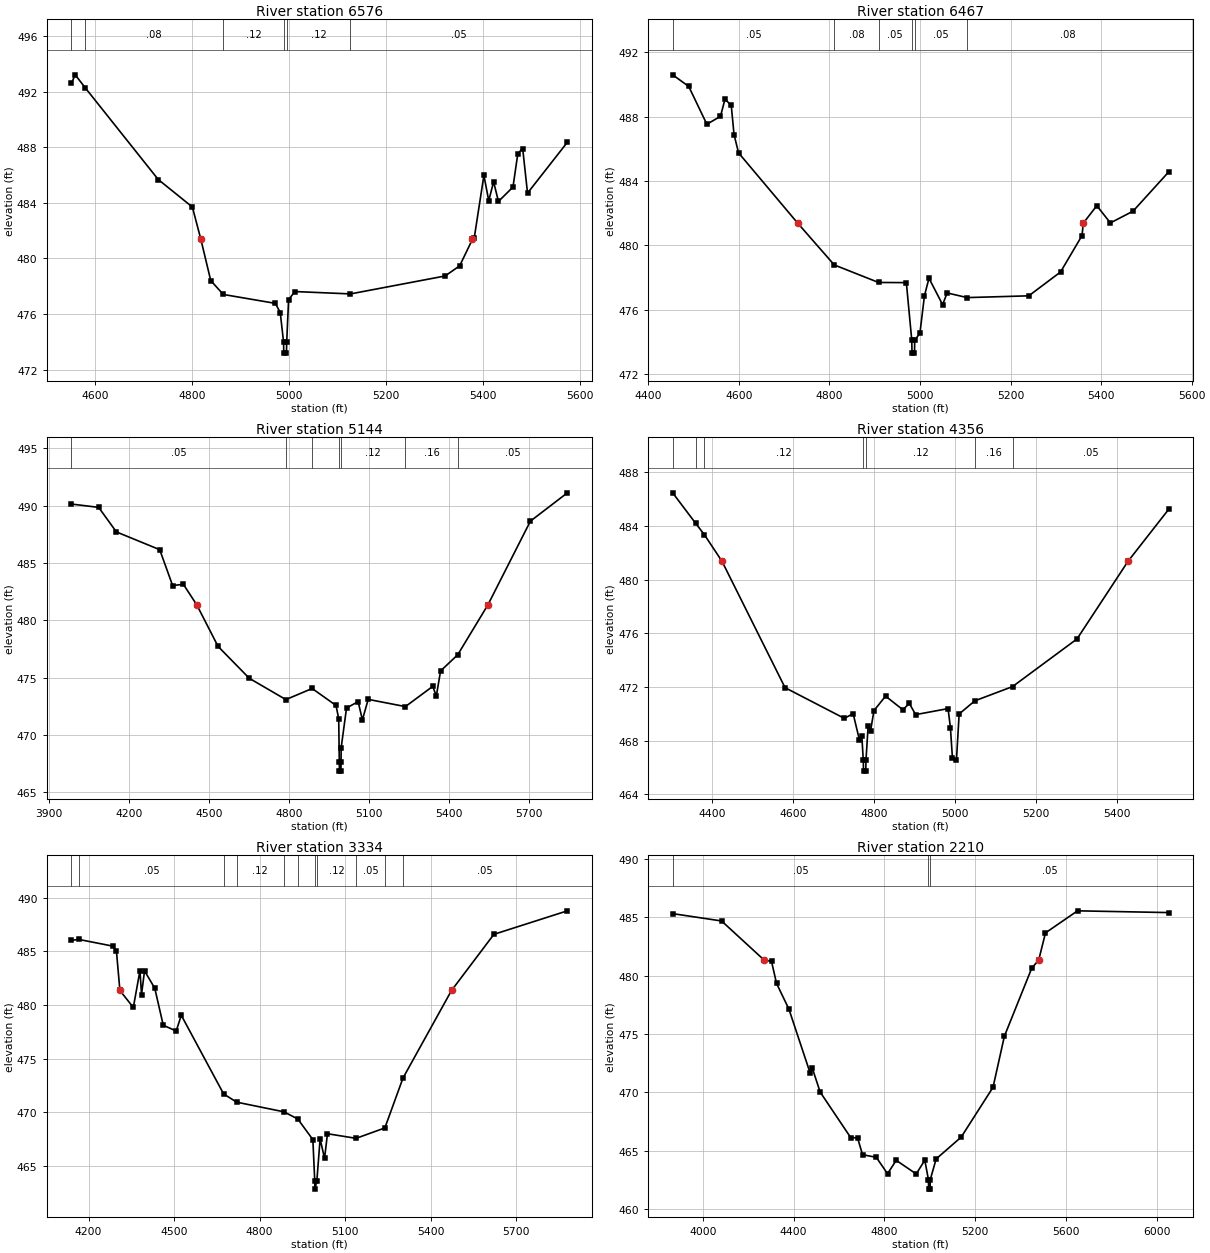
Type RM Length L Ch R = 1,6576,109,109,109
BEGIN DESCRIPTION:
Mapping XS dab821e2
END DESCRIPTION:
XS GIS Cut Line= 3
      2782616.46      7060932.76      2782668.54      7060485.67
      2782664.20      7059912.80
#Sta/Elev= 30
  4551.2  492.62  4559.0  493.21  4579.3  492.29  4730.2  485.68  4800.6  483.70
  4818.1  481.38  4838.5  478.41  4864.4  477.41  4971.8  476.77  4981.9  476.11
  4988.7  473.99  4989.2  473.19  4994.7  473.19  4995.2  473.99  4999.1  477.03
  5012.0  477.62  5126.8  477.45  5322.0  478.74  5352.0  479.47  5378.4  481.38
  5382.0  481.46  5402.0  485.98  5412.0  484.15  5422.0  485.52  5432.0  484.10
  5462.0  485.14  5472.0  487.55  5482.0  487.91  5492.0  484.70  5574.2  488.36
#Mann=6,-1,0
  4551.2    0.05       0  4579.3    0.08       0  4864.4    0.12       0
  4988.7    0.07       0  4995.2    0.12       0  5126.8    0.05       0
Bank Sta=4818.1,5378.4
Exp/Cntr=0.3,0.1

Type RM Length L Ch R = 1,6467,1323,1323,1323
BEGIN DESCRIPTION:
Mapping XS e839842e
END DESCRIPTION:
XS GIS Cut Line= 3
      2782733.65      7060980.44      2782759.69      7060455.29
      2782790.07      7059886.69
#Sta/Elev= 30
  4453.8  490.59  4489.3  489.87  4529.3  487.52  4559.4  488.01  4569.4  489.08
  4583.2  488.69  4589.4  486.87  4599.4  485.74  4729.8  481.38  4810.7  478.78
  4908.5  477.69  4969.9  477.68  4981.9  474.10  4982.4  473.30  4987.9  473.30
  4988.4  474.10  4999.9  474.54  5009.9  476.87  5019.9  477.95  5050.0  476.31
  5060.0  477.04  5104.2  476.75  5240.3  476.86  5310.4  478.34  5357.8  480.60
  5360.8  481.38  5390.5  482.46  5420.5  481.39  5470.6  482.12  5549.0  484.55
#Mann=6,-1,0
  4453.8    0.05       0  4810.7    0.08       0  4908.5    0.05       0
  4981.9    0.04       0  4988.4    0.05       0  5104.2    0.08       0
Bank Sta=4729.8,5360.8
Exp/Cntr=0.3,0.1

Type RM Length L Ch R = 1,5144,788,788,788
BEGIN DESCRIPTION:
Mapping XS 5ab836e9
END DESCRIPTION:
XS GIS Cut Line= 3
      2783738.89      7061152.76      2783649.45      7060142.79
      2783239.88      7059403.82
#Sta/Elev= 30
  3984.7  490.15  4086.7  489.86  4153.1  487.72  4315.5  486.17  4363.9  483.04
  4404.1  483.15  4454.3  481.36  4534.2  477.73  4651.2  474.95  4788.4  473.09
  4886.8  474.06  4976.3  472.58  4986.4  471.42  4988.6  467.65  4989.1  466.85
  4994.7  466.85  4995.2  467.65  4995.5  468.87  5015.7  472.36  5059.2  472.91
  5075.2  471.32  5096.9  473.11  5236.4  472.48  5339.1  474.25  5352.2  473.39
  5368.2  475.59  5432.4  477.00  5545.7  481.36  5704.9  488.66  5843.5  491.13
#Mann=7,-1,0
  3984.7    0.05       0  4788.4    0.16       0  4886.8    0.12       0
  4988.6    0.07       0  4995.2    0.12       0  5236.4    0.16       0
  5432.4    0.05       0
Bank Sta=4454.3,5545.7
Exp/Cntr=0.3,0.1

Type RM Length L Ch R = 1,4356,1022,1022,1022
BEGIN DESCRIPTION:
double MITCHAM BRANCH 7.0
END DESCRIPTION:
XS GIS Cut Line= 3
      2784775.03      7060025.02      2784175.00      7059675.00
      2783774.97      7059324.97
#Sta/Elev= 30
  4301.9  486.46  4359.0  484.18  4380.3  483.34  4423.9  481.36  4579.8  471.94
  4726.6  469.65  4748.1  470.01  4763.8  468.04  4769.6  468.34  4773.3  466.52
  4773.8  465.72  4779.4  465.72  4779.9  466.52  4785.3  469.11  4791.1  468.70
  4799.7  470.23  4828.3  471.31  4871.3  470.29  4887.0  470.77  4902.7  469.93
  4982.9  470.38  4988.7  468.96  4993.7  466.70  5003.7  466.58  5010.3  469.98
  5049.1  470.96  5142.3  472.02  5301.7  475.57  5427.9  481.36  5528.1  485.22
#Mann=7,-1,0
  4301.9    0.05       0  4359.0    0.16       0  4380.3    0.12       0
  4773.3    0.07       0  4779.9    0.12       0  5049.1    0.16       0
  5142.3    0.05       0
Bank Sta=4423.9,5427.9
Exp/Cntr=0.3,0.1

Type RM Length L Ch R = 1,3334,1124,1124,1124
BEGIN DESCRIPTION:
Mapping XS 9649c23f
END DESCRIPTION:
XS GIS Cut Line= 3
      2785369.11      7059407.93      2784605.20      7059067.65
      2783723.25      7058873.20
#Sta/Elev= 30
  4140.2  486.03  4167.1  486.10  4287.5  485.47  4298.0  485.00  4310.1  481.35
  4357.2  479.77  4380.5  483.21  4385.9  480.97  4396.5  483.18  4432.4  481.56
  4462.2  478.11  4507.6  477.58  4525.4  479.04  4673.8  471.72  4719.5  470.95
  4885.5  470.05  4934.1  469.38  4986.9  467.46  4993.4  463.65  4994.0  462.85
  5001.0  463.65  5012.3  467.53  5027.9  465.71  5038.1  468.01  5138.5  467.58
  5239.4  468.55  5303.1  473.20  5473.2  481.35  5621.8  486.58  5879.6  488.77
#Mann=11,-1,0
  4140.2    0.16       0  4167.1    0.05       0  4673.8    0.16       0
  4719.5    0.12       0  4885.5    0.16       0  4934.1    0.12       0
  4993.4    0.07       0  5001.0    0.12       0  5138.5    0.05       0
  5239.4    0.16       0  5303.1    0.05       0
Bank Sta=4310.1,5473.2
Exp/Cntr=0.3,0.1

Type RM Length L Ch R = 1,2210,1257,1257,1257
BEGIN DESCRIPTION:
Mapping XS f83d58a1
END DESCRIPTION:
XS GIS Cut Line= 3
      2786028.77      7058671.80      2785056.59      7058157.93
      2783973.22      7058081.54
#Sta/Elev= 30
  3866.6  485.32  4082.3  484.69  4269.1  481.35  4302.4  481.22  4324.4  479.34
  4379.1  477.13  4472.8  471.64  4481.7  472.09  4516.8  470.02  4651.3  466.12
  4681.6  466.09  4703.6  464.65  4764.0  464.43  4813.7  463.02  4852.0  464.17
  4940.1  463.00  4977.9  464.18  4994.1  462.50  4994.7  461.70  5001.2  461.70
  5001.8  462.50  5028.0  464.29  5138.3  466.16  5278.6  470.43  5328.7  474.81
  5449.0  480.63  5480.1  481.35  5509.8  483.67  5651.1  485.56  6052.3  485.41
#Mann=3,-1,0
  3866.6    0.05       0  4994.1    0.03       0  5001.8    0.05       0
Bank Sta=4269.1,5480.1
Exp/Cntr=0.3,0.1

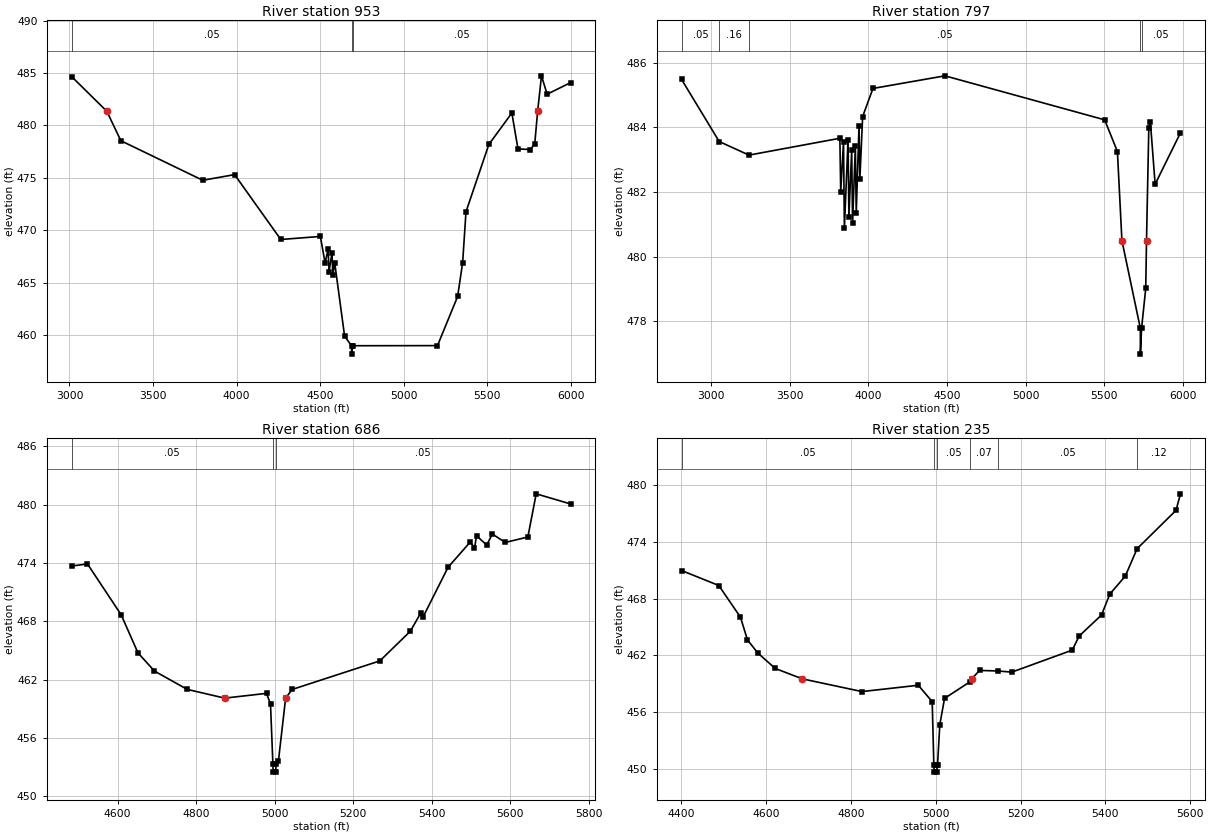
Type RM Length L Ch R = 1,953,156,156,156
BEGIN DESCRIPTION:
Mapping XS c9cf838b
END DESCRIPTION:
XS GIS Cut Line= 6
      2785945.05      7058529.48      2785962.81      7057582.03
      2785706.74      7057013.45      2785146.84      7057100.26
      2784651.35      7057141.26      2784301.97      7057105.67
#Sta/Elev= 30
  3012.8  484.66  3223.7  481.35  3307.4  478.55  3797.7  474.78  3988.3  475.32
  4264.8  469.14  4501.8  469.43  4530.4  466.87  4548.0  468.27  4553.5  466.08
  4571.2  467.84  4576.7  465.77  4587.6  466.92  4646.7  459.94  4688.1  459.02
  4688.8  458.22  4696.0  459.02  5202.8  459.03  5323.3  463.71  5353.4  466.94
  5373.4  471.78  5510.2  478.19  5648.0  481.19  5684.5  477.77  5759.5  477.71
  5785.1  478.28  5802.2  481.35  5825.3  484.73  5859.1  482.98  5999.2  484.08
#Mann=3,-1,0
  3012.8    0.05       0  4688.1   0.033       0  4696.0    0.05       0
Bank Sta=3223.7,5802.2
Exp/Cntr=0.3,0.1

Type RM Length L Ch R = 1,797,111,111,111
BEGIN DESCRIPTION:
Mapping XS 2ae2098e
END DESCRIPTION:
XS GIS Cut Line= 6
      2786040.25      7058542.64      2786044.50      7057544.68
      2785761.66      7056932.06      2785633.88      7056868.17
      2784823.25      7056991.40      2784296.23      7057040.04
#Sta/Elev= 30
  2813.7  485.48  3053.0  483.56  3242.2  483.14  3819.8  483.66  3825.2  482.01
  3843.0  483.55  3848.5  480.88  3871.8  483.62  3877.2  481.23  3895.0  483.31
  3900.5  481.04  3918.3  483.42  3923.8  481.35  3941.6  484.05  3947.0  482.41
  3964.5  484.33  4030.1  485.20  4487.4  485.59  5502.5  484.23  5583.5  483.25
  5612.1  480.50  5729.1  477.79  5729.7  476.99  5737.0  477.79  5763.5  479.02
  5768.4  480.50  5783.0  483.98  5793.0  484.16  5823.2  482.24  5984.2  483.83
#Mann=5,-1,0
  2813.7    0.05       0  3053.0    0.16       0  3242.2    0.05       0
  5729.1    0.03       0  5737.0    0.05       0
Bank Sta=5612.1,5768.4
Exp/Cntr=0.3,0.1

Type RM Length L Ch R = 1,686,451,451,451
BEGIN DESCRIPTION:
Mapping XS 5552d7f9
END DESCRIPTION:
XS GIS Cut Line= 6
      2785763.18      7056818.14      2785554.83      7056770.40
      2785133.82      7056831.16      2784799.62      7056939.67
      2784717.16      7056961.37      2784613.01      7056796.47
#Sta/Elev= 30
  4483.1  473.67  4523.5  473.89  4609.3  468.66  4652.2  464.74  4694.2  462.87
  4777.5  460.99  4872.9  460.09  4979.6  460.58  4989.7  459.47  4995.8  453.28
  4996.5  452.48  5003.1  452.48  5003.7  453.28  5009.9  453.64  5028.2  460.09
  5044.7  460.98  5268.2  463.92  5346.1  466.98  5372.8  468.88  5378.0  468.41
  5442.0  473.55  5499.0  476.17  5509.2  475.48  5514.4  476.79  5540.4  475.83
  5554.7  476.97  5587.6  476.10  5645.2  476.66  5666.4  481.10  5753.9  480.06
#Mann=3,-1,0
  4483.1    0.05       0  4995.8    0.03       0  5003.7    0.05       0
Bank Sta=4872.9,5028.2
Exp/Cntr=0.3,0.1

Type RM Length L Ch R = 1,235,0,0,0
BEGIN DESCRIPTION:
MITCHAM BRANCH 1.0
END DESCRIPTION:
XS GIS Cut Line= 3
      2785810.94      7056492.63      2785220.63      7056366.75
      2784679.06      7056553.05
#Sta/Elev= 30
  4400.7  470.99  4488.6  469.40  4539.7  466.04  4556.1  463.64  4580.6  462.25
  4621.5  460.62  4685.2  459.52  4826.0  458.17  4958.9  458.84  4991.7  457.10
  4995.5  450.44  4996.2  449.64  5002.8  449.64  5003.4  450.44  5004.3  450.44
  5009.6  454.67  5020.8  457.45  5080.2  459.19  5084.9  459.52  5103.3  460.41
  5146.5  460.35  5179.4  460.23  5321.9  462.56  5338.1  464.05  5390.9  466.28
  5410.4  468.49  5446.9  470.40  5474.8  473.30  5566.5  477.36  5577.0  479.11
#Mann=6,-1,0
  4400.7    0.05       0  4995.5    0.03       0  5003.4    0.05       0
  5080.2    0.07       0  5146.5    0.05       0  5474.8    0.12       0
Bank Sta=4685.2,5084.9
Exp/Cntr=0.3,0.1

Chan Stop Cuts=-1