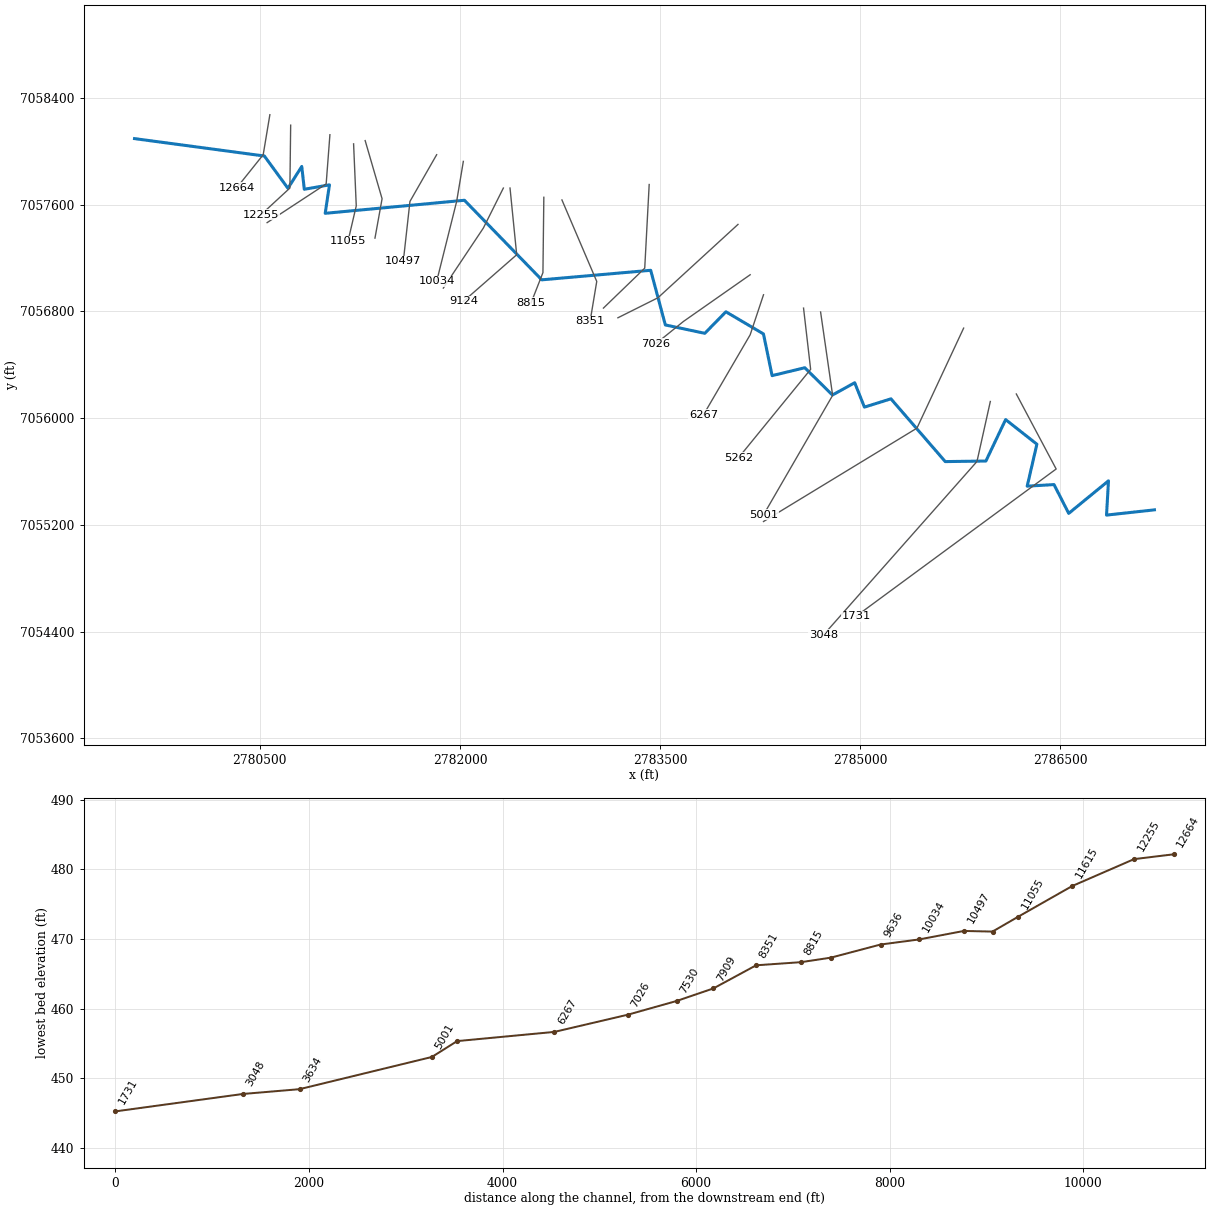
--- MOSS WASH BRANCH.prj (project) ---

Proj Title=MOSS WASH BRANCH Base Level Engineering
Current Plan=p01
Default Exp/Contr=0.3,0.1
English Units
Geom File=g01
Flow File=f01
Plan File=p01
BEGIN DESCRIPTION:
MOSS WASH BRANCH
END DESCRIPTION:

--- MOSS WASH BRANCH.p01 (plan) ---

Plan Title=Multiple Run
Short Identifier=Multiple
Geom File=g01
Flow File=f01
Subcritical Flow
K Sum by GR= 0
Std Step Tol= 0.01
Critical Tol= 0.01
Num of Std Step Trials= 20
Max Error Tol= 0.3
Flow Tol Ratio= 0.001
Split Flow NTrial= 30
Split Flow Tol= 0.02
Split Flow Ratio= 0.02
Log Output Level= 0
Friction Slope Method= 1
Unsteady Friction Slope Method= 2
Unsteady Bridges Friction Slope Method= 1
Parabolic Critical Depth
Global Vel Dist=  1 , 1 , 1
Global Log Level= 0
CheckData=True
Encroach Param= -1, 0, 0, 0
BEGIN DESCRIPTION:
Multiple Run
END DESCRIPTION:

--- MOSS WASH BRANCH.f01 (steady flow) ---

Flow Title=Multiple
Program Version=5.07
Number of Profiles= 7
Profile Names=10-year,25-year,50-year,1pct_min,100-year,1pct_plu,500-year
River Rch & RM=MOSS WASH BRANCH,Reach-1         ,12664
     491     649     775     460     918    1831    1286
River Rch & RM=MOSS WASH BRANCH,Reach-1         ,7909
     582     775     929     553    1104    2203    1557
River Rch & RM=MOSS WASH BRANCH,Reach-1         ,6267
     753    1020    1239     746    1489    2971    2154
River Rch & RM=MOSS WASH BRANCH,Reach-1         ,3634
    1805    2528    3137    1924    3839    7659    5747
Boundary for River Rch & Prof#=MOSS WASH BRANCH,Reach-1         , 1
Up Type= 0
Dn Type= 3
Dn Slope=0.005
Boundary for River Rch & Prof#=MOSS WASH BRANCH,Reach-1         , 2
Up Type= 0
Dn Type= 3
Dn Slope=0.005
Boundary for River Rch & Prof#=MOSS WASH BRANCH,Reach-1         , 3
Up Type= 0
Dn Type= 3
Dn Slope=0.005
Boundary for River Rch & Prof#=MOSS WASH BRANCH,Reach-1         , 4
Up Type= 0
Dn Type= 3
Dn Slope=0.005
Boundary for River Rch & Prof#=MOSS WASH BRANCH,Reach-1         , 5
Up Type= 0
Dn Type= 3
Dn Slope=0.005
Boundary for River Rch & Prof#=MOSS WASH BRANCH,Reach-1         , 6
Up Type= 0
Dn Type= 3
Dn Slope=0.005
Boundary for River Rch & Prof#=MOSS WASH BRANCH,Reach-1         , 7
Up Type= 0
Dn Type= 3
Dn Slope=0.005
DSS Import GetInterval= 0
DSS Import GetPeak= 0
DSS Import FillOption= 0

--- MOSS WASH BRANCH.g01 (geometry) ---

Geom Title=Existing Conditions

River Reach=MOSS WASH BRANCH,Reach-1
Reach XY= 30
      2779560.59      7058095.71      2780533.82      7057965.27
      2780710.26      7057723.23      2780813.89      7057887.09
      2780833.08      7057715.84      2781021.59      7057748.99
      2780989.64      7057535.67      2782033.37      7057633.41
      2782612.93      7057036.94      2783429.40      7057108.43
      2783539.11      7056698.68      2783834.95      7056635.92
      2783993.01      7056797.38      2784274.63      7056631.26
      2784339.36      7056318.61      2784584.28      7056377.83
      2784791.68      7056173.26      2784958.39      7056265.40
      2785031.36      7056082.57      2785229.99      7056144.68
      2785637.16      7055674.16      2785941.72      7055678.30
      2786089.66      7055988.98      2786323.94      7055804.65
      2786251.32      7055489.96      2786452.40      7055501.73
      2786562.61      7055285.77      2786860.64      7055530.04
      2786846.03      7055273.07      2787204.94      7055312.27

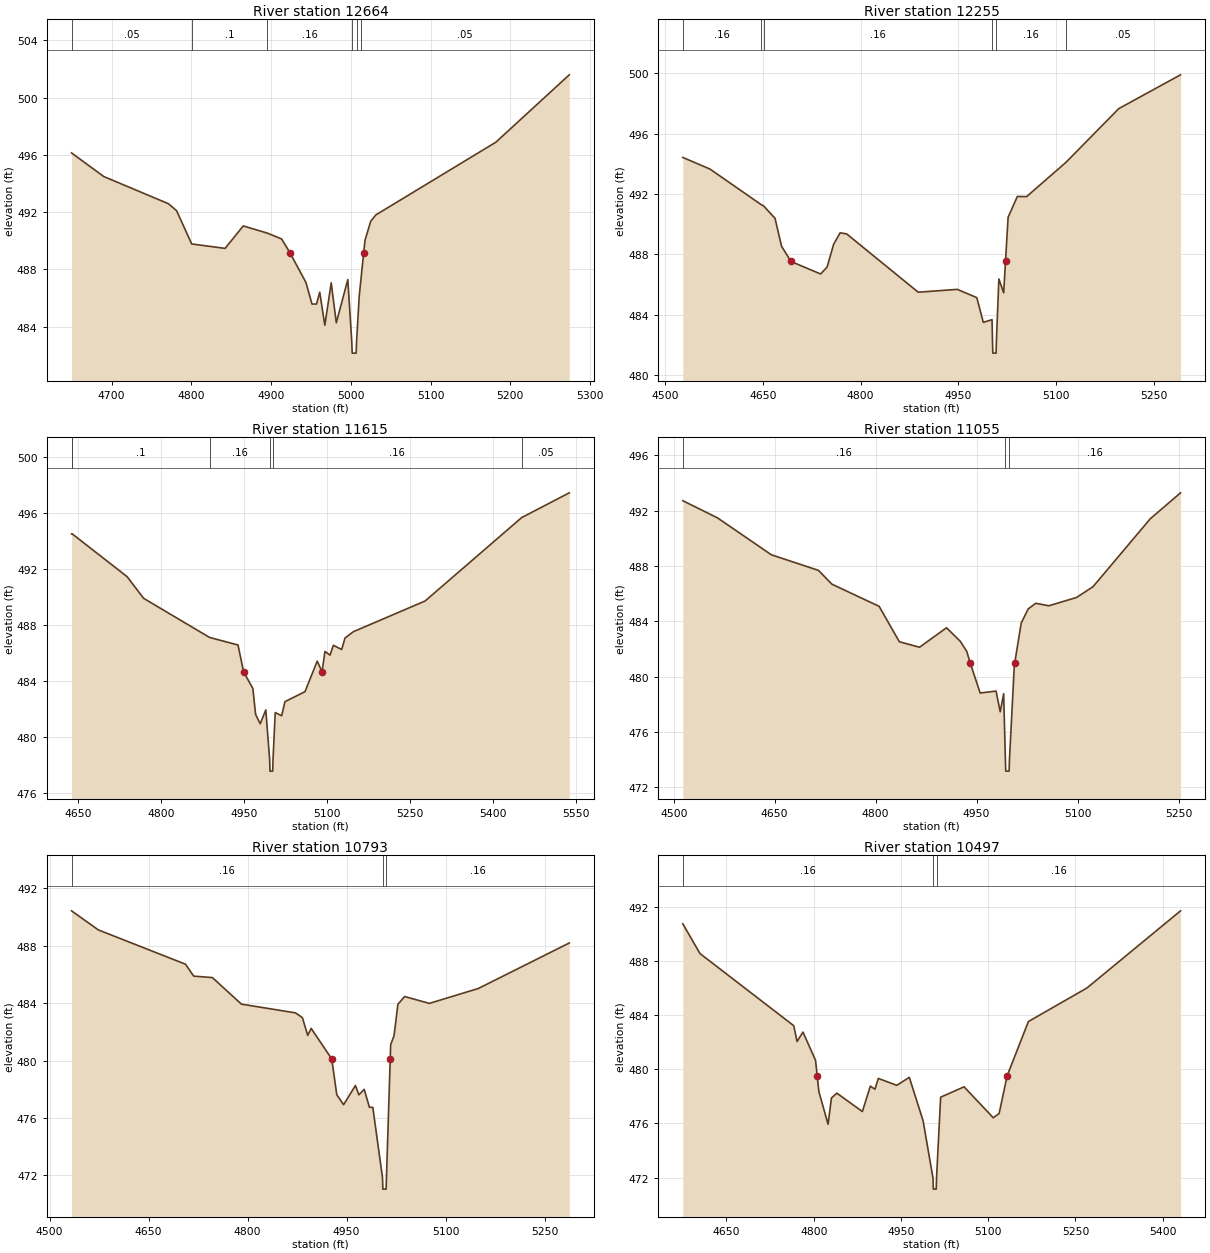
Type RM Length L Ch R = 1,12664,409,409,409
BEGIN DESCRIPTION:
MOSS WASH BRANCH 18.0
END DESCRIPTION:
XS GIS Cut Line= 3
      2780574.99      7058274.96      2780525.00      7057975.00
      2780324.97      7057724.96
#Sta/Elev= 30
  4649.7  496.13  4690.2  494.48  4771.3  492.58  4781.5  492.09  4800.4  489.77
  4842.3  489.46  4865.1  491.03  4895.1  490.53  4913.2  490.12  4923.8  489.14
  4943.7  487.08  4951.3  485.57  4957.0  485.57  4961.0  486.40  4967.4  484.09
  4975.4  487.05  4981.8  484.26  4996.2  487.28  5001.2  482.94  5001.7  482.14
  5006.7  482.14  5007.2  482.94  5010.6  486.15  5012.4  487.13  5016.1  489.14
  5017.8  490.03  5025.0  491.36  5031.4  491.80  5181.9  496.88  5274.0  501.59
#Mann=6,-1,0
  4649.7    0.05       0  4800.4     0.1       0  4895.1    0.16       0
  5001.2    0.07       0  5007.2    0.16       0  5012.4    0.05       0
Bank Sta=4923.8,5016.1
Exp/Cntr=0.3,0.1

Type RM Length L Ch R = 1,12255,640,640,640
BEGIN DESCRIPTION:
MOSS WASH BRANCH 17.0
END DESCRIPTION:
XS GIS Cut Line= 3
      2780730.85      7058196.71      2780725.00      7057725.00
      2780509.73      7057526.30
#Sta/Elev= 30
  4526.8  494.43  4568.5  493.66  4647.2  491.30  4650.8  491.22  4668.5  490.39
  4678.5  488.54  4693.0  487.53  4738.5  486.70  4748.5  487.16  4758.5  488.67
  4768.5  489.43  4778.5  489.36  4888.5  485.49  4948.5  485.68  4978.5  485.13
  4988.5  483.49  5001.9  483.67  5002.6  482.25  5003.1  481.45  5008.1  481.45
  5008.6  482.25  5012.4  486.37  5019.8  485.45  5022.6  487.53  5026.6  490.46
  5040.8  491.84  5055.0  491.83  5115.1  494.09  5196.7  497.67  5291.5  499.91
#Mann=6,-1,0
  4526.8    0.16       0  4647.2     0.1       0  4650.8    0.16       0
  5002.6    0.07       0  5008.6    0.16       0  5115.1    0.05       0
Bank Sta=4693,5022.6
Exp/Cntr=0.3,0.1

Type RM Length L Ch R = 1,11615,560,560,560
BEGIN DESCRIPTION:
MOSS WASH BRANCH 16.0
END DESCRIPTION:
XS GIS Cut Line= 3
      2781025.00      7058124.96      2780996.91      7057756.12
      2780554.24      7057465.78
#Sta/Elev= 30
  4638.2  494.51  4639.4  494.51  4738.5  491.46  4768.5  489.91  4887.6  487.12
  4939.0  486.58  4949.0  484.67  4965.8  483.48  4970.8  481.62  4979.1  480.96
  4989.2  481.95  4996.2  478.38  4996.7  477.58  5001.7  477.58  5002.2  478.38
  5006.2  481.76  5017.8  481.53  5023.8  482.54  5060.0  483.25  5082.1  485.43
  5090.8  484.67  5096.1  486.12  5105.3  485.86  5111.2  486.56  5126.3  486.26
  5132.3  487.08  5147.4  487.53  5277.0  489.72  5451.4  495.67  5537.5  497.44
#Mann=6,-1,0
  4638.2    0.16       0  4639.4     0.1       0  4887.6    0.16       0
  4996.2    0.07       0  5002.2    0.16       0  5451.4    0.05       0
Bank Sta=4949,5090.8
Exp/Cntr=0.3,0.1

Type RM Length L Ch R = 1,11055,262,262,262
BEGIN DESCRIPTION:
MOSS WASH BRANCH 15.0
END DESCRIPTION:
XS GIS Cut Line= 3
      2781202.45      7058056.41      2781222.47      7057591.47
      2781160.18      7057324.51
#Sta/Elev= 30
  4513.5  492.72  4565.0  491.48  4645.0  488.81  4715.1  487.68  4735.1  486.68
  4805.2  485.08  4835.2  482.52  4865.2  482.12  4905.3  483.53  4925.8  482.55
  4935.3  481.83  4940.4  481.00  4955.3  478.81  4978.9  478.95  4985.1  477.45
  4990.2  478.76  4992.8  473.96  4993.3  473.16  4998.3  473.16  4998.8  473.96
  5006.0  480.79  5006.7  481.00  5016.3  483.87  5026.6  484.89  5037.9  485.30
  5057.4  485.12  5098.5  485.72  5123.0  486.50  5208.0  491.41  5253.0  493.29
#Mann=3,-1,0
  4513.5    0.16       0  4992.8    0.07       0  4998.8    0.16       0
Bank Sta=4940.4,5006.7
Exp/Cntr=0.3,0.1

Type RM Length L Ch R = 1,10793,296,296,296
BEGIN DESCRIPTION:
Mapping XS 092dc0d8
END DESCRIPTION:
XS GIS Cut Line= 3
      2781289.21      7058080.84      2781416.00      7057644.85
      2781362.70      7057349.47
#Sta/Elev= 30
  4533.2  490.44  4573.8  489.11  4705.9  486.72  4718.3  485.89  4746.6  485.79
  4790.6  483.94  4872.5  483.33  4883.0  483.00  4891.1  481.76  4896.3  482.25
  4927.5  480.12  4935.1  477.63  4945.4  476.93  4963.4  478.27  4968.6  477.62
  4976.7  478.00  4984.6  476.75  4989.7  476.75  5004.4  471.85  5004.9  471.05
  5009.9  471.05  5010.4  471.85  5016.1  480.12  5016.8  481.11  5021.9  481.74
  5027.7  483.92  5037.9  484.47  5075.4  483.99  5149.7  485.03  5287.4  488.20
#Mann=3,-1,0
  4533.2    0.16       0  5004.4    0.07       0  5010.4    0.16       0
Bank Sta=4927.5,5016.1
Exp/Cntr=0.3,0.1

Type RM Length L Ch R = 1,10497,463,463,463
BEGIN DESCRIPTION:
MOSS WASH BRANCH 14.0
END DESCRIPTION:
XS GIS Cut Line= 3
      2781825.02      7057975.03      2781625.00      7057625.00
      2781575.00      7057175.01
#Sta/Elev= 30
  4574.9  490.77  4604.4  488.57  4765.7  483.23  4771.4  482.06  4781.5  482.76
  4803.1  480.68  4806.0  479.53  4808.9  478.35  4824.7  475.94  4830.5  477.88
  4839.8  478.24  4883.7  476.88  4897.4  478.76  4905.3  478.53  4911.1  479.33
  4942.8  478.82  4964.4  479.41  4988.1  476.20  5005.2  471.94  5005.7  471.14
  5010.7  471.14  5011.2  471.94  5018.3  477.94  5058.5  478.71  5108.8  476.42
  5118.9  476.74  5132.7  479.53  5169.2  483.54  5269.8  486.02  5430.8  491.73
#Mann=3,-1,0
  4574.9    0.16       0  5005.2    0.07       0  5011.2    0.16       0
Bank Sta=4806,5132.7
Exp/Cntr=0.3,0.1

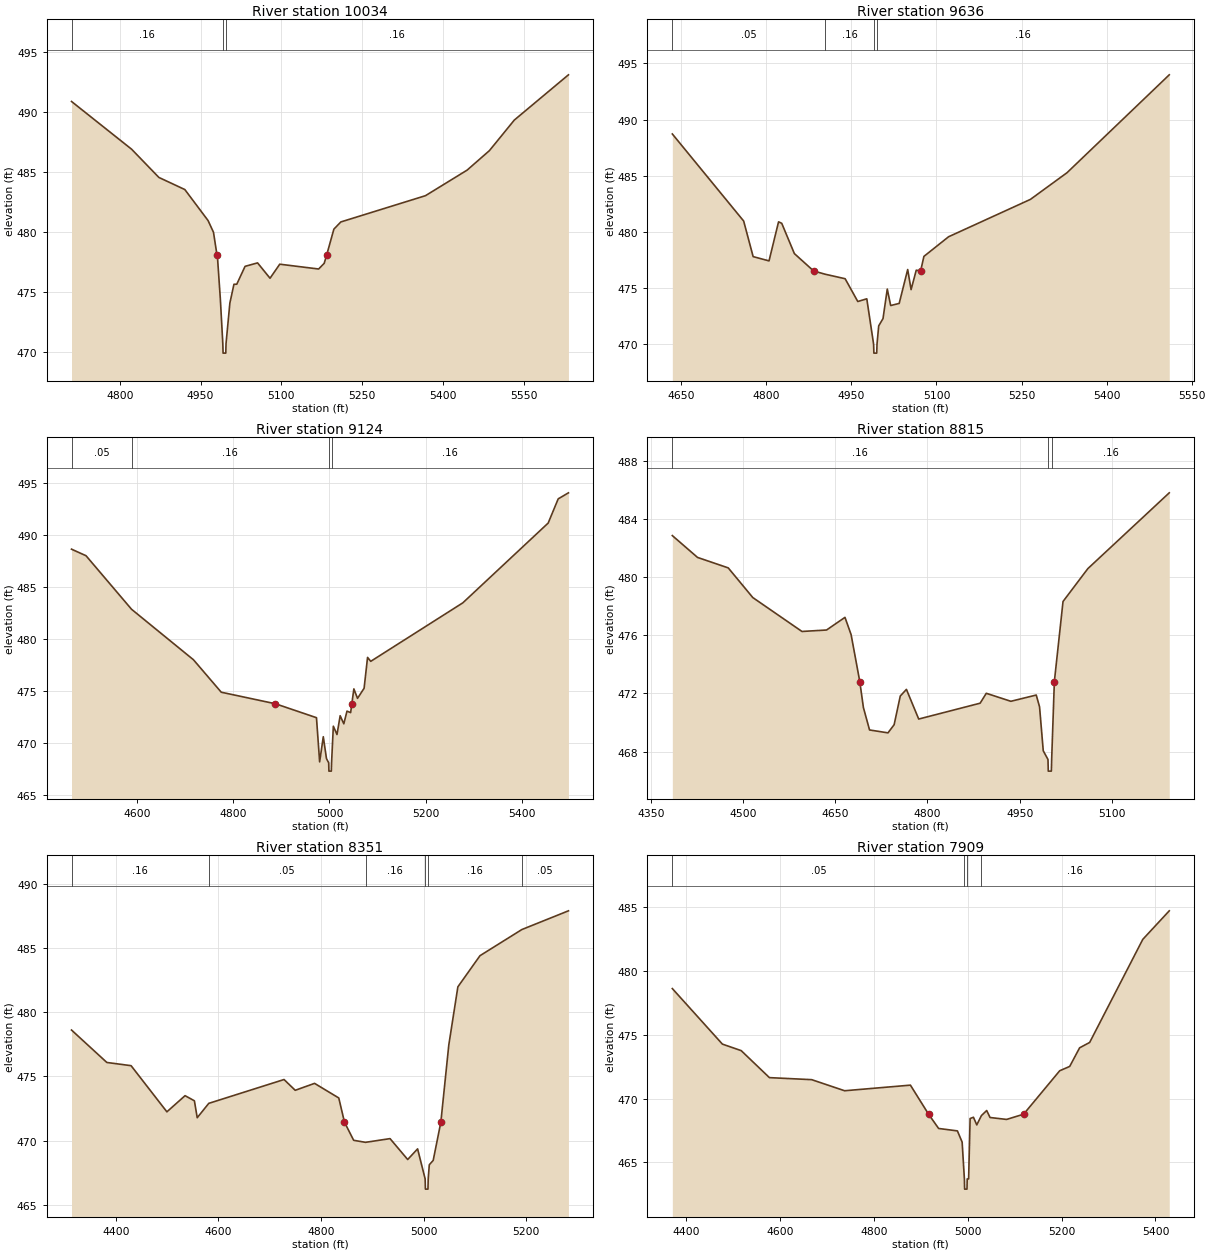
Type RM Length L Ch R = 1,10034,398,398,398
BEGIN DESCRIPTION:
MOSS WASH BRANCH 13.0
END DESCRIPTION:
XS GIS Cut Line= 3
      2782025.01      7057925.04      2781975.00      7057625.00
      2781825.01      7057025.04
#Sta/Elev= 30
  4710.5  490.89  4822.1  486.91  4872.7  484.56  4920.9  483.55  4964.0  480.97
  4974.1  479.99  4980.7  478.06  4981.7  477.78  4986.8  474.45  4991.4  470.72
  4991.9  469.92  4996.9  469.92  4997.4  470.72  5004.5  474.09  5012.1  475.66
  5017.3  475.66  5032.7  477.15  5055.9  477.44  5079.1  476.16  5097.1  477.33
  5169.3  476.93  5179.6  477.40  5184.0  478.06  5197.6  480.25  5210.5  480.85
  5367.7  483.04  5445.0  485.17  5486.3  486.79  5532.6  489.34  5633.1  493.11
#Mann=3,-1,0
  4710.5    0.16       0  4991.4    0.07       0  4997.4    0.16       0
Bank Sta=4980.7,5184
Exp/Cntr=0.3,0.1

Type RM Length L Ch R = 1,9636,512,512,512
BEGIN DESCRIPTION:
MOSS WASH BRANCH 12.0
END DESCRIPTION:
XS GIS Cut Line= 3
      2782325.00      7057725.00      2782175.00      7057425.00
      2781875.02      7056975.03
#Sta/Elev= 30
  4634.3  488.72  4760.1  480.96  4776.8  477.79  4804.8  477.41  4821.6  480.89
  4827.2  480.76  4849.5  478.06  4883.5  476.51  4903.9  476.22  4939.0  475.82
  4961.3  473.79  4977.2  474.03  4989.2  469.99  4989.7  469.19  4994.7  469.19
  4995.2  469.99  4998.2  471.62  5005.8  472.27  5013.3  474.90  5019.3  473.43
  5034.3  473.62  5049.3  476.64  5055.3  474.85  5064.4  476.58  5072.1  476.51
  5077.9  477.81  5121.4  479.56  5265.7  482.89  5330.3  485.27  5510.5  493.99
#Mann=4,-1,0
  4634.3    0.05       0  4903.9    0.16       0  4989.2    0.07       0
  4995.2    0.16       0
Bank Sta=4883.5,5072.1
Exp/Cntr=0.3,0.1

Type RM Length L Ch R = 1,9124,309,309,309
BEGIN DESCRIPTION:
MOSS WASH BRANCH 11.0
END DESCRIPTION:
XS GIS Cut Line= 3
      2782375.00      7057725.04      2782425.00      7057225.00
      2782025.03      7056875.03
#Sta/Elev= 30
  4463.3  488.66  4493.5  488.03  4588.2  482.88  4717.1  478.02  4774.9  474.90
  4887.6  473.79  4973.0  472.45  4979.6  468.20  4987.2  470.62  4993.8  468.52
  4998.4  468.11  4998.9  467.31  5003.9  467.31  5004.4  468.11  5008.1  471.63
  5015.7  470.83  5022.3  472.64  5029.9  471.86  5036.5  473.08  5044.1  472.94
  5046.6  473.79  5050.8  475.22  5058.4  474.31  5072.1  475.28  5079.3  478.25
  5085.9  477.87  5277.6  483.50  5455.1  491.17  5476.0  493.50  5497.3  494.08
#Mann=4,-1,0
  4463.3    0.05       0  4588.2    0.16       0  4998.4    0.07       0
  5004.4    0.16       0
Bank Sta=4887.6,5046.6
Exp/Cntr=0.3,0.1

Type RM Length L Ch R = 1,8815,464,464,464
BEGIN DESCRIPTION:
Mapping XS a51448a7
END DESCRIPTION:
XS GIS Cut Line= 3
      2782628.36      7057655.95      2782621.68      7057090.95
      2782532.69      7056864.02
#Sta/Elev= 30
  4384.7  482.85  4425.7  481.35  4475.7  480.63  4515.7  478.59  4595.7  476.26
  4635.7  476.36  4665.7  477.23  4675.7  476.04  4689.8  472.82  4695.7  471.03
  4705.7  469.49  4735.7  469.29  4745.7  469.85  4755.7  471.82  4765.7  472.28
  4785.7  470.24  4885.7  471.33  4895.7  472.01  4935.7  471.46  4977.0  471.89
  4982.4  471.08  4988.4  468.06  4996.1  467.46  4996.6  466.66  5001.6  466.66
  5002.1  467.46  5006.5  472.82  5020.6  478.32  5061.0  480.58  5193.5  485.79
#Mann=3,-1,0
  4384.7    0.16       0  4996.1    0.07       0  5002.1    0.16       0
Bank Sta=4689.8,5006.5
Exp/Cntr=0.3,0.1

Type RM Length L Ch R = 1,8351,442,442,442
BEGIN DESCRIPTION:
MOSS WASH BRANCH 10.0
END DESCRIPTION:
XS GIS Cut Line= 3
      2782764.06      7057635.92      2783025.00      7057025.00
      2782974.99      7056724.95
#Sta/Elev= 30
  4313.7  478.62  4382.6  476.09  4429.8  475.84  4499.6  472.24  4535.0  473.50
  4553.2  473.10  4558.7  471.78  4581.2  472.90  4727.9  474.76  4749.7  473.92
  4787.4  474.46  4834.6  473.32  4845.7  471.43  4863.6  470.02  4886.7  469.86
  4934.5  470.15  4968.9  468.52  4988.2  469.35  5002.9  467.01  5003.4  466.21
  5008.4  466.21  5008.9  467.01  5011.0  468.11  5018.6  468.45  5033.5  471.43
  5049.0  477.45  5066.7  481.99  5109.8  484.42  5191.4  486.46  5282.2  487.92
#Mann=6,-1,0
  4313.7    0.16       0  4581.2    0.05       0  4886.7    0.16       0
  5002.9    0.07       0  5008.9    0.16       0  5191.4    0.05       0
Bank Sta=4845.7,5033.5
Exp/Cntr=0.3,0.1

Type RM Length L Ch R = 1,7909,379,379,379
BEGIN DESCRIPTION:
MOSS WASH BRANCH 9.0
END DESCRIPTION:
XS GIS Cut Line= 3
      2783418.05      7057751.58      2783384.68      7057124.32
      2783075.03      7056825.03
#Sta/Elev= 30
  4370.6  478.63  4477.3  474.27  4517.3  473.76  4577.5  471.64  4667.6  471.48
  4737.7  470.61  4877.9  471.05  4916.6  468.77  4938.0  467.65  4978.0  467.46
  4988.1  466.58  4992.9  463.69  4993.4  462.89  4998.4  462.89  4998.9  463.69
  5001.9  463.69  5005.1  468.43  5012.2  468.53  5019.3  467.93  5029.2  468.66
  5040.4  469.06  5047.6  468.51  5082.8  468.36  5119.1  468.77  5196.0  472.18
  5217.3  472.52  5238.4  473.98  5259.8  474.40  5373.0  482.49  5429.4  484.73
#Mann=4,-1,0
  4370.6    0.05       0  4992.9    0.03       0  4998.9    0.05       0
  5029.2    0.16       0
Bank Sta=4916.6,5119.1
Exp/Cntr=0.3,0.1

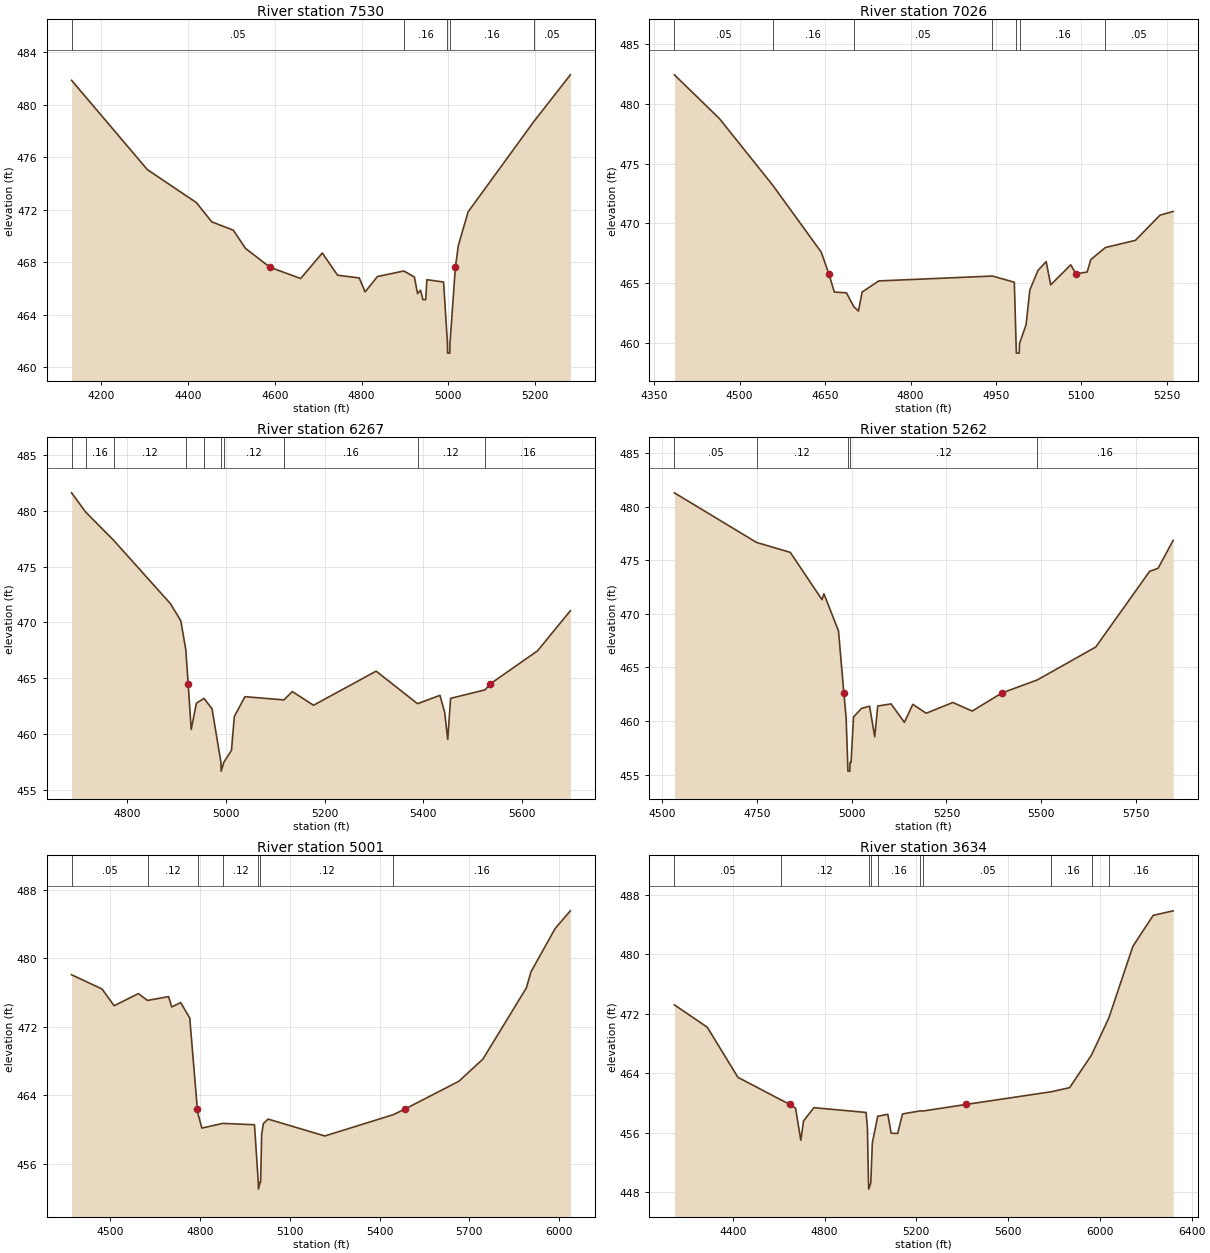
Type RM Length L Ch R = 1,7530,504,504,504
BEGIN DESCRIPTION:
MOSS WASH BRANCH 8.0
END DESCRIPTION:
XS GIS Cut Line= 3
      2784083.71      7057452.46      2783483.68      7056902.43
      2783183.68      7056752.43
#Sta/Elev= 30
  4131.9  481.85  4306.4  475.06  4419.3  472.55  4455.0  471.08  4504.4  470.45
  4532.7  469.06  4589.3  467.62  4659.8  466.77  4709.7  468.71  4744.8  467.02
  4794.8  466.81  4808.4  465.75  4836.7  466.92  4897.5  467.34  4921.8  466.89
  4929.2  465.62  4936.0  465.88  4941.6  465.16  4947.9  465.16  4950.7  466.68
  4989.1  466.50  4998.0  461.89  4998.5  461.09  5003.5  461.09  5004.0  461.89
  5016.3  467.62  5023.3  469.30  5045.7  471.84  5196.8  478.70  5281.3  482.27
#Mann=5,-1,0
  4131.9    0.05       0  4897.5    0.16       0  4998.0    0.07       0
  5004.0    0.16       0  5196.8    0.05       0
Bank Sta=4589.3,5016.3
Exp/Cntr=0.3,0.1

Type RM Length L Ch R = 1,7026,759,759,759
BEGIN DESCRIPTION:
MOSS WASH BRANCH 7.0
END DESCRIPTION:
XS GIS Cut Line= 3
      2784175.01      7057075.01      2783675.00      7056725.00
      2783468.53      7056558.32
#Sta/Elev= 30
  4385.4  482.44  4464.3  478.78  4558.2  473.18  4643.1  467.59  4656.6  465.76
  4666.2  464.24  4687.5  464.17  4700.4  463.01  4708.5  462.65  4715.0  464.24
  4744.2  465.17  4943.8  465.58  4982.2  465.06  4985.3  459.92  4985.8  459.12
  4990.8  459.12  4991.3  459.92  5002.9  461.51  5009.4  464.41  5023.7  466.04
  5038.1  466.79  5046.1  464.84  5081.3  466.52  5090.5  465.76  5110.1  465.92
  5116.5  466.96  5142.2  467.97  5194.8  468.57  5238.0  470.68  5261.1  470.99
#Mann=7,-1,0
  4385.4    0.05       0  4558.2    0.16       0  4700.4    0.05       0
  4943.8    0.16       0  4985.3    0.07       0  4991.3    0.16       0
  5142.2    0.05       0
Bank Sta=4656.6,5090.5
Exp/Cntr=0.3,0.1

Type RM Length L Ch R = 1,6267,1005,1005,1005
BEGIN DESCRIPTION:
double MOSS WASH BRANCH 5.0
END DESCRIPTION:
XS GIS Cut Line= 3
      2784274.99      7056924.96      2784175.00      7056625.00
      2783825.01      7056025.01
#Sta/Elev= 30
  4687.2  481.62  4715.6  479.90  4772.2  477.37  4887.4  471.68  4908.5  470.14
  4918.6  467.56  4923.5  464.46  4929.6  460.39  4940.1  462.74  4955.5  463.18
  4971.8  462.24  4989.8  457.45  4990.3  456.65  4995.8  457.45  5011.2  458.52
  5017.0  461.55  5038.5  463.33  5117.5  463.04  5134.5  463.79  5177.5  462.56
  5304.4  465.62  5388.3  462.70  5433.8  463.45  5443.3  461.92  5449.5  459.49
  5455.3  463.18  5525.1  463.94  5535.1  464.46  5631.4  467.44  5698.0  471.04
#Mann=10,-1,0
  4687.2    0.05       0  4715.6    0.16       0  4772.2    0.12       0
  4918.6    0.16       0  4955.5    0.12       0  4989.8    0.07       0
  4995.8    0.12       0  5117.5    0.16       0  5388.3    0.12       0
  5525.1    0.16       0
Bank Sta=4923.5,5535.1
Exp/Cntr=0.3,0.1

Type RM Length L Ch R = 1,5262,261,261,261
BEGIN DESCRIPTION:
MOSS WASH BRANCH 4.0
END DESCRIPTION:
XS GIS Cut Line= 3
      2784575.00      7056824.99      2784628.18      7056365.77
      2784088.79      7055704.30
#Sta/Elev= 30
  4532.4  481.28  4749.3  476.65  4838.0  475.73  4921.8  471.32  4926.8  471.87
  4965.3  468.40  4979.4  462.62  4985.4  460.32  4989.5  456.13  4990.0  455.33
  4995.2  455.33  4995.7  456.13  4998.4  456.13  5004.9  460.38  5025.7  461.17
  5047.3  461.39  5060.9  458.53  5068.8  461.40  5104.0  461.60  5139.1  459.88
  5161.4  461.56  5196.6  460.73  5267.0  461.73  5318.0  460.93  5396.5  462.62
  5489.5  463.83  5643.9  466.90  5786.1  473.96  5808.4  474.24  5848.2  476.85
#Mann=5,-1,0
  4532.4    0.05       0  4749.3    0.12       0  4989.5    0.07       0
  4995.7    0.12       0  5489.5    0.16       0
Bank Sta=4979.4,5396.5
Exp/Cntr=0.3,0.1

Type RM Length L Ch R = 1,5001,1367,1367,1367
BEGIN DESCRIPTION:
MOSS WASH BRANCH 3.0
END DESCRIPTION:
XS GIS Cut Line= 3
      2784702.81      7056795.69      2784793.08      7056170.71
      2784275.01      7055275.01
#Sta/Elev= 30
  4371.0  478.09  4472.7  476.43  4513.1  474.47  4594.0  475.89  4624.6  475.09
  4695.0  475.54  4705.6  474.33  4735.4  474.84  4765.7  473.04  4791.1  462.39
  4792.8  461.92  4806.2  460.18  4875.6  460.73  4981.9  460.57  4994.7  453.85
  4995.2  453.05  5000.9  453.85  5002.5  453.85  5005.9  459.43  5011.7  460.71
  5027.5  461.23  5217.0  459.26  5445.1  461.74  5483.8  462.39  5664.7  465.65
  5745.1  468.24  5890.1  476.55  5905.9  478.45  5986.3  483.49  6037.2  485.56
#Mann=7,-1,0
  4371.0    0.05       0  4624.6    0.12       0  4792.8    0.16       0
  4875.6    0.12       0  4994.7    0.07       0  5000.9    0.12       0
  5445.1    0.16       0
Bank Sta=4791.1,5483.8
Exp/Cntr=0.3,0.1

Type RM Length L Ch R = 1,3634,586,586,586
BEGIN DESCRIPTION:
MOSS WASH BRANCH 2.0
END DESCRIPTION:
XS GIS Cut Line= 3
      2785775.01      7056675.02      2785425.00      7055925.00
      2784274.97      7055224.98
#Sta/Elev= 30
  4145.4  473.18  4288.9  470.17  4422.1  463.45  4610.3  460.41  4649.0  459.81
  4673.5  459.29  4696.4  455.00  4708.2  457.58  4753.2  459.37  4980.8  458.73
  4986.7  456.68  4991.4  449.23  4992.3  448.43  5001.2  449.23  5008.2  454.65
  5031.7  458.22  5075.7  458.48  5090.1  455.94  5118.4  455.91  5139.7  458.53
  5216.8  458.94  5231.1  458.93  5417.5  459.81  5788.4  461.51  5868.0  462.06
  5963.5  466.44  6039.0  471.42  6143.8  481.04  6232.2  485.20  6319.4  485.81
#Mann=10,-1,0
  4145.4    0.05       0  4610.3    0.12       0  4991.4    0.07       0
  5001.2    0.12       0  5031.7    0.16       0  5216.8    0.07       0
  5231.1    0.05       0  5788.4    0.16       0  5963.5    0.12       0
  6039.0    0.16       0
Bank Sta=4649,5417.5
Exp/Cntr=0.3,0.1

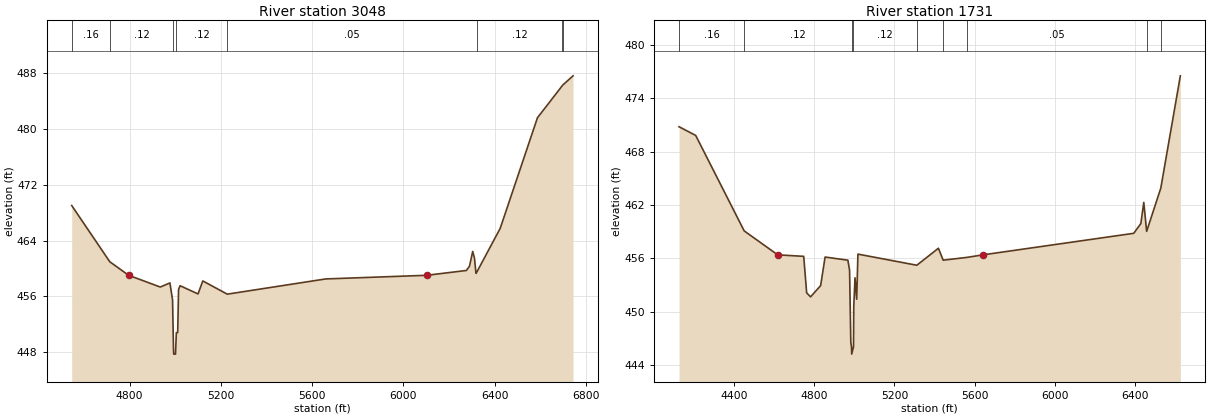
Type RM Length L Ch R = 1,3048,1317,1317,1317
BEGIN DESCRIPTION:
MOSS WASH BRANCH 1.0
END DESCRIPTION:
XS GIS Cut Line= 3
      2785975.00      7056124.98      2785875.00      7055675.00
      2784725.01      7054375.01
#Sta/Elev= 30
  4546.6  469.02  4713.4  460.97  4796.0  459.03  4934.6  457.35  4976.8  457.94
  4988.4  455.51  4992.4  448.54  4993.4  447.74  5001.3  447.74  5002.3  448.54
  5005.0  450.82  5010.9  450.82  5014.7  457.00  5021.3  457.54  5100.0  456.36
  5120.9  458.22  5228.2  456.33  5659.6  458.51  6101.5  459.03  6275.9  459.72
  6289.4  460.33  6303.6  462.45  6311.2  461.51  6317.9  459.31  6320.9  459.45
  6424.1  465.76  6587.2  481.59  6695.6  486.17  6698.9  486.30  6743.2  487.60
#Mann=8,-1,0
  4546.6    0.16       0  4713.4    0.12       0  4992.4    0.07       0
  5002.3    0.12       0  5228.2    0.05       0  6320.9    0.12       0
  6695.6    0.16       0  6698.9    0.12       0
Bank Sta=4796,6101.5
Exp/Cntr=0.3,0.1

Type RM Length L Ch R = 1,1731,0,0,0
BEGIN DESCRIPTION:
Mapping XS 8642a032
END DESCRIPTION:
XS GIS Cut Line= 3
      2786169.81      7056181.15      2786468.43      7055618.63
      2784969.19      7054515.02
#Sta/Elev= 30
  4126.2  470.80  4209.3  469.82  4451.0  459.09  4617.9  456.40  4747.6  456.23
  4762.3  452.12  4781.8  451.68  4831.9  452.94  4854.2  456.15  4967.7  455.80
  4976.1  454.68  4982.3  446.56  4985.8  446.04  4986.8  445.24  4995.7  446.04
  4997.0  450.60  5003.3  453.82  5011.6  451.41  5017.8  456.48  5311.3  455.23
  5418.9  457.14  5442.6  455.80  5560.1  456.11  5641.6  456.40  6392.4  458.82
  6427.9  459.92  6442.5  462.29  6456.8  459.04  6527.3  463.90  6624.7  476.52
#Mann=9,-1,0
  4126.2    0.16       0  4451.0    0.12       0  4985.8    0.07       0
  4995.7    0.12       0  5311.3    0.07       0  5442.6    0.12       0
  5560.1    0.05       0  6456.8    0.16       0  6527.3    0.12       0
Bank Sta=4617.9,5641.6
Exp/Cntr=0.3,0.1

Chan Stop Cuts=-1