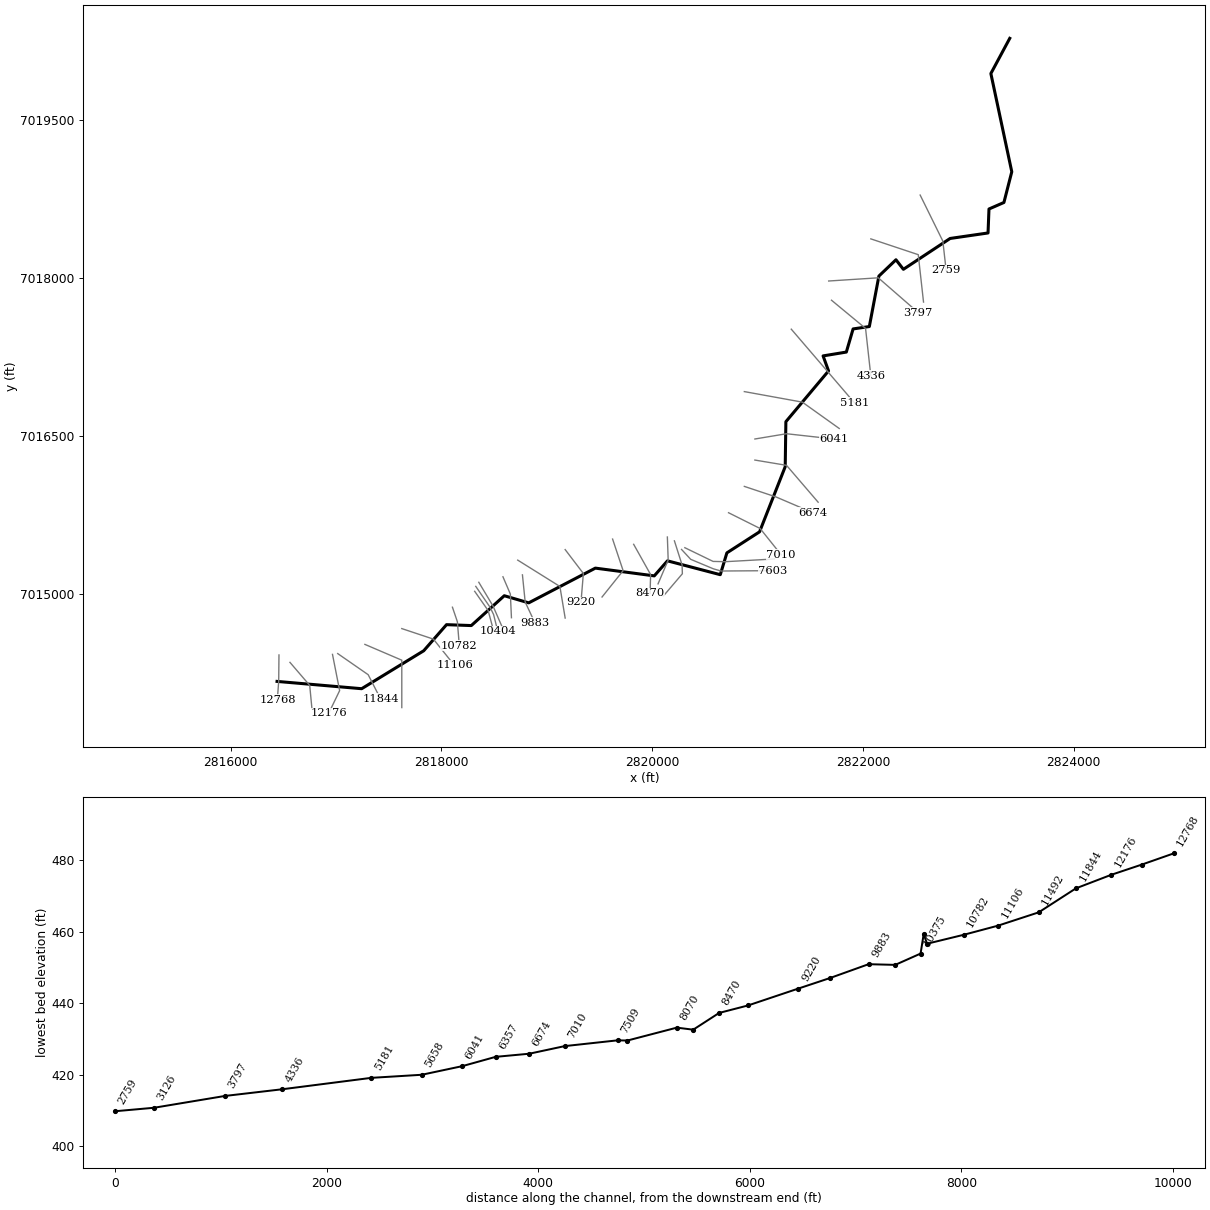
--- Magee Branch.prj (project) ---

Proj Title=Magee Branch Base Level Engineering
Current Plan=p01
Default Exp/Contr=0.3,0.1
English Units
Geom File=g01
Flow File=f01
Plan File=p01
BEGIN DESCRIPTION:
Magee Branch
END DESCRIPTION:

--- Magee Branch.p01 (plan) ---

Plan Title=Multiple Run
Short Identifier=Multiple
Geom File=g01
Flow File=f01
Subcritical Flow
K Sum by GR= 0
Std Step Tol= 0.01
Critical Tol= 0.01
Num of Std Step Trials= 20
Max Error Tol= 0.3
Flow Tol Ratio= 0.001
Split Flow NTrial= 30
Split Flow Tol= 0.02
Split Flow Ratio= 0.02
Log Output Level= 0
Friction Slope Method= 1
Unsteady Friction Slope Method= 2
Unsteady Bridges Friction Slope Method= 1
Parabolic Critical Depth
Global Vel Dist=  1 , 1 , 1
Global Log Level= 0
CheckData=True
Encroach Param= -1, 0, 0, 0
BEGIN DESCRIPTION:
Multiple Run
END DESCRIPTION:

--- Magee Branch.f01 (steady flow) ---

Flow Title=Multiple
Number of Profiles=7
Profile Names=10-year,25-year,50-year,1pct_min,100-year,1pct_plu,500-year
River Rch & RM= Magee Branch,Reach-1,12768
     388     509     607     360     719    1435    1010
River Rch & RM= Magee Branch,Reach-1,7603
     664     896    1086     655    1307    2607    1892
Boundary for River Rch & Prof#=Magee Branch,Reach-1,1
Up Type=0
Dn Type=3
Dn Slope=0.005
Boundary for River Rch & Prof#=Magee Branch,Reach-1,2
Up Type=0
Dn Type=3
Dn Slope=0.005
Boundary for River Rch & Prof#=Magee Branch,Reach-1,3
Up Type=0
Dn Type=3
Dn Slope=0.005
Boundary for River Rch & Prof#=Magee Branch,Reach-1,4
Up Type=0
Dn Type=3
Dn Slope=0.005
Boundary for River Rch & Prof#=Magee Branch,Reach-1,5
Up Type=0
Dn Type=3
Dn Slope=0.005
Boundary for River Rch & Prof#=Magee Branch,Reach-1,6
Up Type=0
Dn Type=3
Dn Slope=0.005
Boundary for River Rch & Prof#=Magee Branch,Reach-1,7
Up Type=0
Dn Type=3
Dn Slope=0.005

--- Magee Branch.g01 (geometry) ---

Geom Title=Existing Conditions

River Reach=Magee Branch,Reach-1
Reach XY= 30
      2816441.49      7014173.54      2817244.23      7014104.26
      2817833.02      7014464.50      2818049.27      7014712.26
      2818284.56      7014703.74      2818597.44      7014986.99
      2818829.12      7014919.25      2819461.51      7015249.08
      2820020.42      7015175.50      2820145.55      7015318.26
      2820646.68      7015186.68      2820709.28      7015393.79
      2821019.33      7015593.73      2821262.74      7016211.96
      2821269.00      7016639.33      2821673.87      7017121.46
      2821622.07      7017263.95      2821842.60      7017300.28
      2821906.84      7017520.09      2822060.86      7017542.67
      2822151.51      7018021.93      2822313.51      7018176.66
      2822383.84      7018085.98      2822827.08      7018378.87
      2823187.02      7018431.11      2823195.98      7018658.64
      2823337.72      7018720.56      2823412.32      7019012.26
      2823213.88      7019944.77      2823393.06      7020278.97

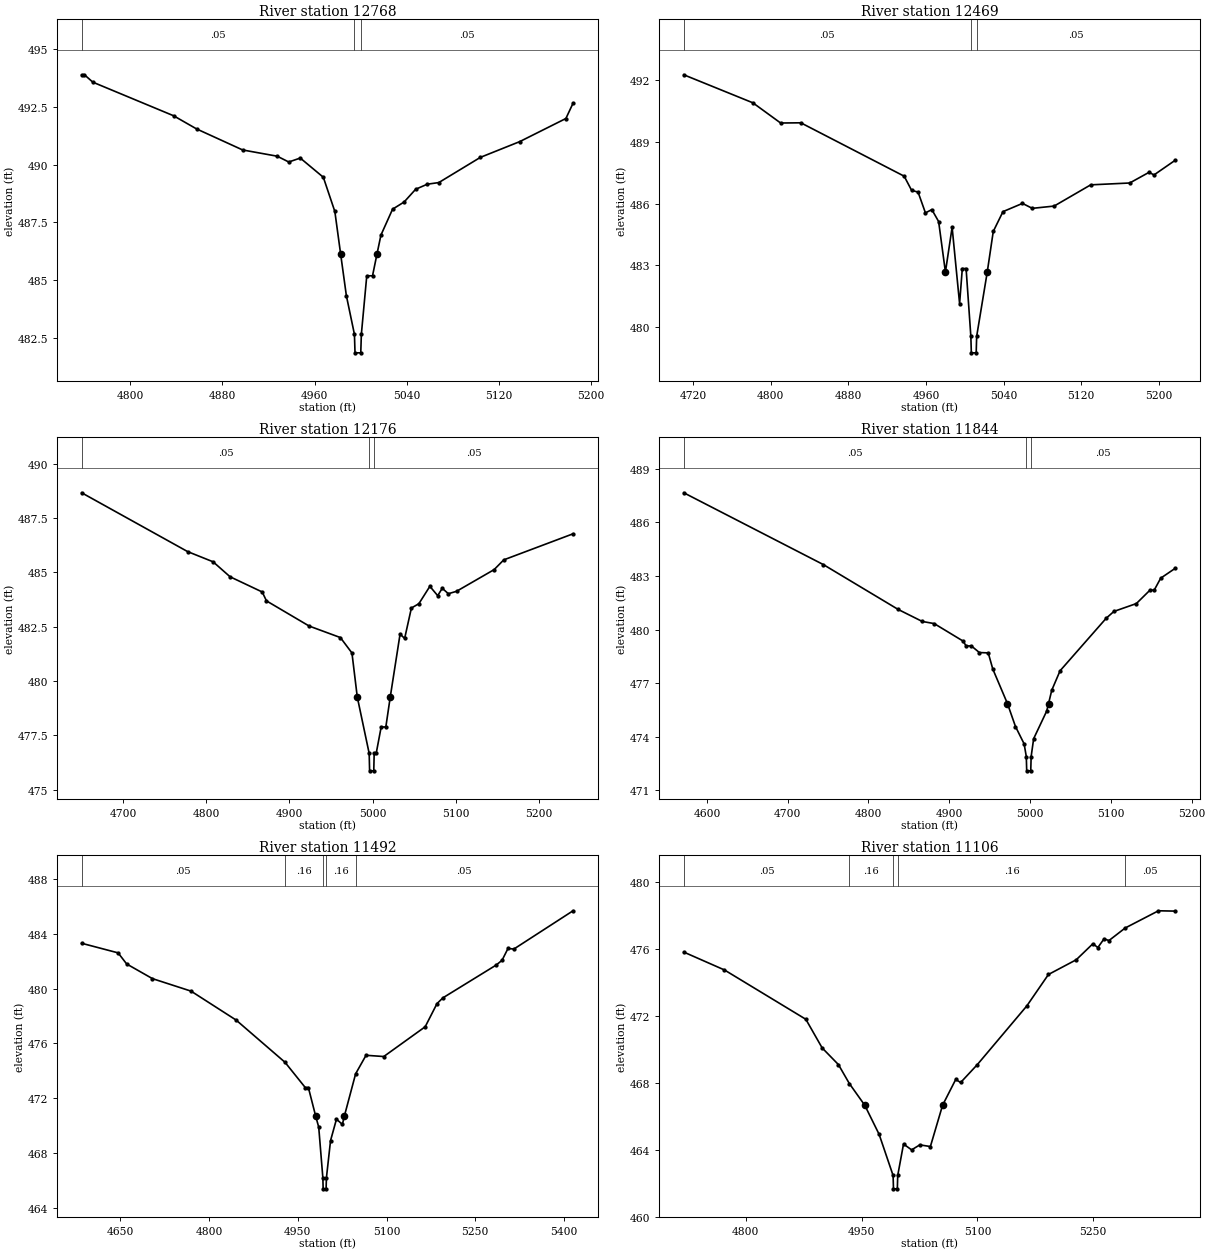
Type RM Length L Ch R = 1,12768,299,299,299
BEGIN DESCRIPTION:
Magee Branch 24.0
END DESCRIPTION:
XS GIS Cut Line= 3
      2816459.72      7014424.71      2816457.12      7014174.71
      2816444.18      7013998.79
#Sta/Elev= 30
  4757.9  493.88  4760.3  493.88  4767.6  493.56  4837.6  492.11  4857.6  491.54
  4897.6  490.63  4927.6  490.36  4937.6  490.11  4947.6  490.28  4967.6  489.45
  4977.6  487.97  4982.6  486.14  4987.6  484.33  4994.6  482.66  4995.1  481.86
  5000.1  481.86  5000.6  482.66  5005.3  485.19  5010.3  485.19  5014.2  486.14
  5017.6  486.95  5027.7  488.07  5037.7  488.38  5047.7  488.93  5057.8  489.15
  5067.8  489.22  5103.9  490.31  5138.0  490.99  5178.1  491.99  5184.3  492.65
#Mann=3,-1,0
  4757.9    0.05       0  4994.6    0.03       0  5000.6    0.05       0
Bank Sta=4982.6,5014.2
Exp/Cntr=0.3,0.1

Type RM Length L Ch R = 1,12469,293,293,293
BEGIN DESCRIPTION:
Mapping XS 6c0a08ca
END DESCRIPTION:
XS GIS Cut Line= 3
      2816563.89      7014354.39      2816751.39      7014135.65
      2816772.07      7013918.43
#Sta/Elev= 30
  4710.5  492.25  4781.7  490.89  4810.3  489.91  4831.1  489.92  4937.6  487.33
  4945.3  486.64  4951.9  486.56  4959.5  485.55  4966.1  485.71  4973.1  485.13
  4980.1  482.68  4987.0  484.85  4994.7  481.15  4997.5  482.85  5001.4  482.85
  5006.3  479.56  5006.8  478.76  5011.8  478.76  5012.3  479.56  5023.2  482.68
  5029.4  484.65  5039.4  485.61  5059.5  486.01  5069.6  485.77  5092.1  485.88
  5129.8  486.91  5170.0  487.00  5190.0  487.52  5195.0  487.39  5216.8  488.10
#Mann=3,-1,0
  4710.5    0.05       0  5006.3   0.035       0  5012.3    0.05       0
Bank Sta=4980.1,5023.2
Exp/Cntr=0.3,0.1

Type RM Length L Ch R = 1,12176,332,332,332
BEGIN DESCRIPTION:
Mapping XS 2aac847a
END DESCRIPTION:
XS GIS Cut Line= 3
      2816967.53      7014429.94      2817035.24      7014086.17
      2816931.08      7013870.03
#Sta/Elev= 30
  4650.4  488.67  4777.7  485.96  4808.3  485.49  4828.7  484.80  4867.3  484.10
  4872.4  483.69  4923.7  482.53  4961.2  482.00  4975.1  481.29  4981.5  479.26
  4995.8  476.66  4996.3  475.86  5001.3  475.86  5001.8  476.66  5004.2  476.66
  5010.2  477.88  5015.8  477.88  5021.1  479.26  5032.9  482.16  5038.4  481.96
  5046.5  483.36  5055.5  483.56  5068.7  484.36  5078.1  483.93  5083.6  484.27
  5090.9  484.02  5100.7  484.13  5145.9  485.13  5157.5  485.58  5240.7  486.78
#Mann=3,-1,0
  4650.4    0.05       0  4995.8   0.035       0  5001.8    0.05       0
Bank Sta=4981.5,5021.1
Exp/Cntr=0.3,0.1

Type RM Length L Ch R = 1,11844,352,352,352
BEGIN DESCRIPTION:
Mapping XS 26816a39
END DESCRIPTION:
XS GIS Cut Line= 3
      2817016.97      7014437.76      2817306.07      7014237.21
      2817422.74      7014009.06
#Sta/Elev= 30
  4571.4  487.66  4744.2  483.64  4836.8  481.13  4866.5  480.46  4881.3  480.34
  4917.1  479.36  4920.8  479.09  4927.3  479.09  4937.2  478.72  4948.2  478.70
  4953.8  477.80  4972.0  475.86  4981.9  474.58  4992.6  473.61  4995.3  472.90
  4995.8  472.10  5000.8  472.10  5001.3  472.90  5004.4  473.90  5020.5  475.44
  5022.8  475.86  5026.8  476.61  5037.1  477.70  5094.2  480.64  5103.7  481.02
  5131.5  481.46  5148.1  482.20  5153.7  482.22  5161.6  482.88  5179.5  483.43
#Mann=3,-1,0
  4571.4    0.05       0  4995.3    0.03       0  5001.3    0.05       0
Bank Sta=4972,5022.8
Exp/Cntr=0.3,0.1

Type RM Length L Ch R = 1,11492,386,386,386
BEGIN DESCRIPTION:
Magee Branch 23.0
END DESCRIPTION:
XS GIS Cut Line= 3
      2817275.02      7014524.99      2817625.00      7014375.00
      2817625.00      7013924.97
#Sta/Elev= 30
  4584.5  483.30  4646.1  482.60  4660.6  481.79  4704.2  480.72  4769.4  479.81
  4845.6  477.70  4928.3  474.62  4962.5  472.78  4967.8  472.78  4980.3  470.67
  4985.3  469.89  4992.3  466.19  4992.8  465.39  4997.8  465.39  4998.3  466.19
  5005.3  468.91  5015.3  470.47  5025.3  470.09  5028.5  470.67  5047.7  473.78
  5065.3  475.13  5095.3  475.04  5165.3  477.21  5185.3  478.90  5195.3  479.32
  5285.3  481.71  5295.3  482.06  5305.3  482.92  5315.3  482.88  5415.3  485.67
#Mann=5,-1,0
  4584.5    0.05       0  4928.3    0.16       0  4992.3    0.07       0
  4998.3    0.16       0  5047.7    0.05       0
Bank Sta=4980.3,5028.5
Exp/Cntr=0.3,0.1

Type RM Length L Ch R = 1,11106,324,324,324
BEGIN DESCRIPTION:
Magee Branch 22.0
END DESCRIPTION:
XS GIS Cut Line= 3
      2817625.01      7014675.00      2817925.00      7014575.00
      2818125.02      7014324.98
#Sta/Elev= 30
  4719.6  475.82  4772.3  474.75  4877.7  471.80  4898.8  470.09  4919.9  469.09
  4934.0  467.96  4954.0  466.66  4972.6  464.92  4990.7  462.46  4991.2  461.66
  4996.2  461.66  4996.7  462.46  5004.2  464.34  5014.7  463.99  5025.3  464.29
  5039.0  464.19  5054.8  466.66  5071.8  468.20  5078.2  468.02  5099.8  469.09
  5163.9  472.60  5191.9  474.48  5227.9  475.36  5249.5  476.32  5255.9  476.09
  5263.9  476.61  5270.3  476.51  5291.3  477.26  5334.4  478.29  5356.0  478.27
#Mann=5,-1,0
  4719.6    0.05       0  4934.0    0.16       0  4990.7    0.07       0
  4996.7    0.16       0  5291.3    0.05       0
Bank Sta=4954,5054.8
Exp/Cntr=0.3,0.1

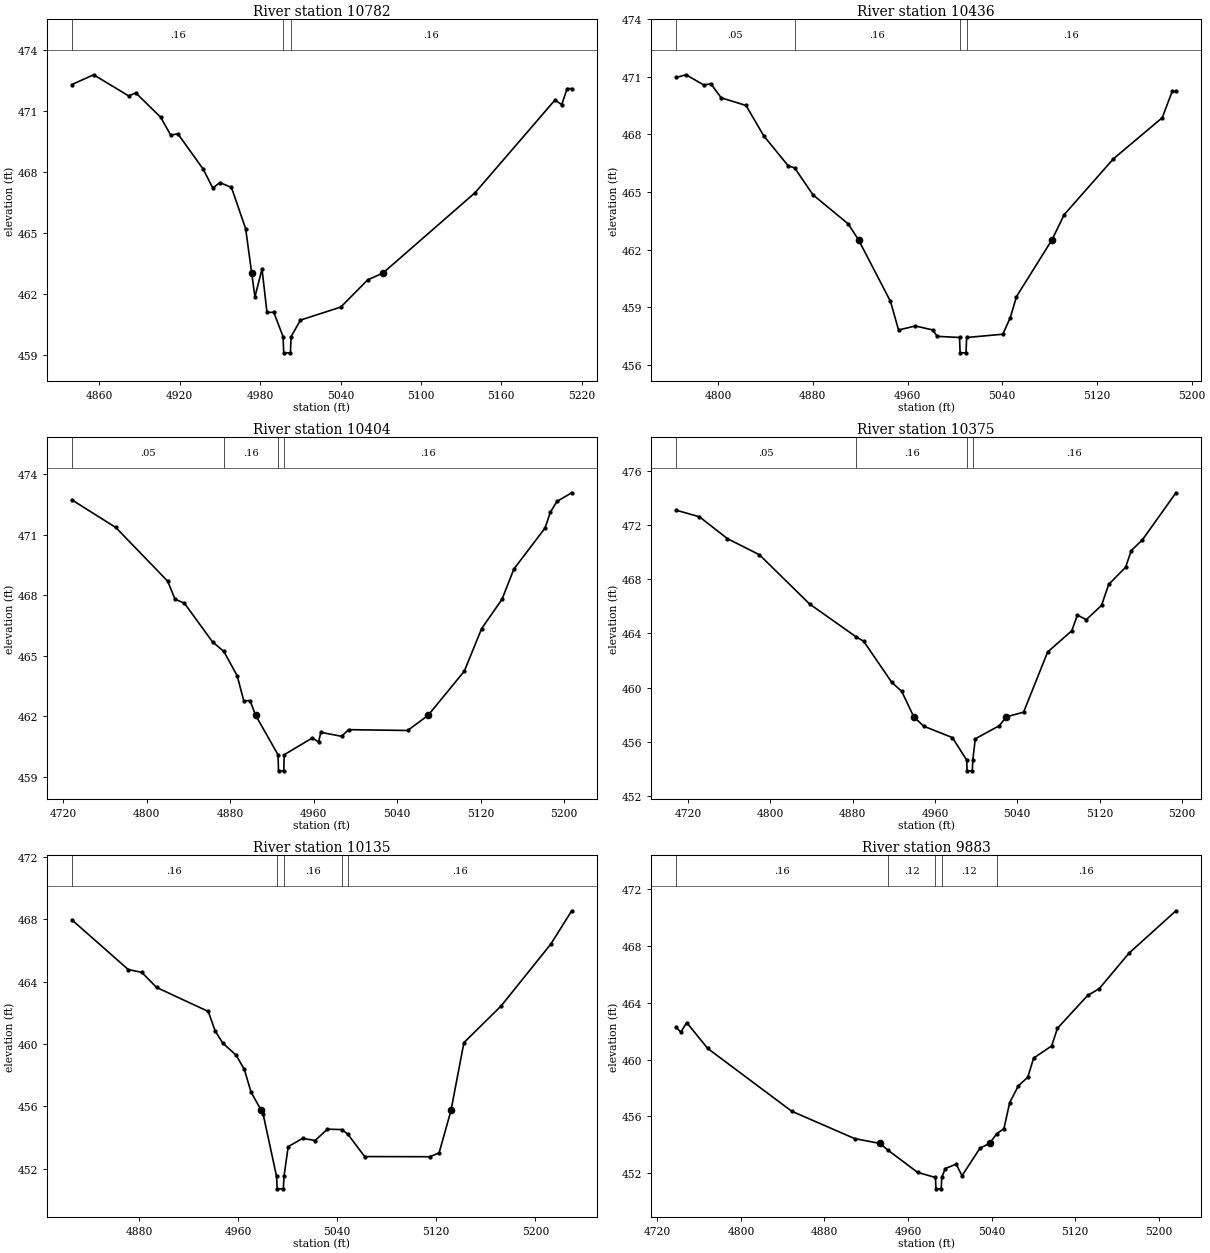
Type RM Length L Ch R = 1,10782,346,346,346
BEGIN DESCRIPTION:
Mapping XS 48840f4e
END DESCRIPTION:
XS GIS Cut Line= 3
      2818105.56      7014877.80      2818152.43      7014739.81
      2818170.66      7014513.27
#Sta/Elev= 30
  4839.5  472.30  4855.8  472.78  4881.9  471.74  4887.2  471.89  4905.8  470.69
  4913.3  469.81  4918.6  469.88  4937.5  468.14  4944.7  467.21  4950.0  467.48
  4958.6  467.24  4969.2  465.21  4973.7  463.03  4976.1  461.86  4981.4  463.23
  4985.1  461.10  4990.2  461.10  4997.1  459.91  4997.6  459.11  5002.6  459.11
  5003.1  459.91  5010.1  460.72  5040.2  461.36  5060.3  462.70  5071.6  463.03
  5140.5  466.99  5200.0  471.54  5205.0  471.31  5209.1  472.10  5212.5  472.10
#Mann=3,-1,0
  4839.5    0.16       0  4997.1    0.07       0  5003.1    0.16       0
Bank Sta=4973.7,5071.6
Exp/Cntr=0.3,0.1

Type RM Length L Ch R = 1,10436,32,32,32
BEGIN DESCRIPTION:
Mapping XS f112e795
END DESCRIPTION:
XS GIS Cut Line= 3
      2818316.48      7015028.89      2818444.09      7014846.59
      2818496.19      7014653.84
#Sta/Elev= 30
  4764.5  470.97  4773.0  471.11  4787.8  470.58  4793.9  470.64  4802.6  469.91
  4823.6  469.51  4838.4  467.94  4859.3  466.36  4864.6  466.26  4880.2  464.85
  4909.9  463.34  4918.6  462.51  4945.6  459.30  4952.4  457.81  4966.6  458.02
  4981.4  457.81  4985.0  457.48  5003.9  457.42  5004.4  456.62  5009.4  456.62
  5009.9  457.42  5040.5  457.59  5046.8  458.46  5052.0  459.55  5082.0  462.51
  5092.3  463.82  5133.7  466.72  5175.1  468.87  5183.5  470.24  5186.7  470.24
#Mann=4,-1,0
  4764.5    0.05       0  4864.6    0.16       0  5003.9    0.07       0
  5009.9    0.16       0
Bank Sta=4918.6,5082
Exp/Cntr=0.3,0.1

Type RM Length L Ch R = 1,10404,29,29,29
BEGIN DESCRIPTION:
Mapping XS 9f861e6e
END DESCRIPTION:
XS GIS Cut Line= 4
      2818326.91      7015075.74      2818462.32      7014877.84
      2818496.18      7014807.52      2818535.24      7014651.27
#Sta/Elev= 30
  4728.4  472.73  4770.5  471.36  4820.2  468.70  4827.3  467.80  4836.2  467.61
  4863.2  465.69  4874.0  465.22  4886.8  464.01  4893.1  462.77  4899.1  462.78
  4904.5  462.05  4925.9  460.10  4926.4  459.30  4931.4  459.30  4931.9  460.10
  4958.8  460.93  4964.8  460.73  4966.9  461.21  4986.9  461.01  4993.5  461.34
  5050.1  461.30  5069.7  462.05  5104.4  464.24  5121.0  466.35  5140.5  467.80
  5151.9  469.30  5181.7  471.33  5186.8  472.11  5193.1  472.65  5207.3  473.08
#Mann=4,-1,0
  4728.4    0.05       0  4874.0    0.16       0  4925.9    0.07       0
  4931.9    0.16       0
Bank Sta=4904.5,5069.7
Exp/Cntr=0.3,0.1

Type RM Length L Ch R = 1,10375,240,240,240
BEGIN DESCRIPTION:
Mapping XS 73c34859
END DESCRIPTION:
XS GIS Cut Line= 3
      2818355.58      7015114.77      2818490.97      7014888.25
      2818579.52      7014685.11
#Sta/Elev= 30
  4708.6  473.08  4731.3  472.59  4758.5  470.98  4789.6  469.79  4838.2  466.17
  4883.7  463.73  4890.8  463.42  4918.0  460.40  4927.7  459.73  4939.5  457.85
  4949.1  457.16  4977.0  456.32  4990.8  454.67  4991.3  453.87  4996.3  453.87
  4996.8  454.67  4999.2  456.23  5022.6  457.20  5029.3  457.85  5046.1  458.19
  5069.5  462.63  5092.9  464.19  5098.4  465.35  5107.0  465.01  5121.8  466.06
  5128.8  467.61  5145.2  468.87  5150.7  470.10  5161.5  470.89  5194.1  474.36
#Mann=4,-1,0
  4708.6    0.05       0  4883.7    0.16       0  4990.8    0.07       0
  4996.8    0.16       0
Bank Sta=4939.5,5029.3
Exp/Cntr=0.3,0.1

Type RM Length L Ch R = 1,10135,252,252,252
BEGIN DESCRIPTION:
Mapping XS ac13b44c
END DESCRIPTION:
XS GIS Cut Line= 3
      2818584.74      7015166.86      2818655.03      7015002.84
      2818665.36      7014778.12
#Sta/Elev= 30
  4825.9  467.97  4871.4  464.78  4882.3  464.60  4894.3  463.63  4936.0  462.09
  4941.5  460.85  4947.6  460.07  4958.5  459.28  4965.1  458.37  4970.5  456.92
  4978.7  455.75  4980.2  455.53  4991.1  451.51  4991.6  450.71  4996.6  450.71
  4997.1  451.51  5000.5  453.42  5012.2  453.95  5022.2  453.81  5032.2  454.54
  5043.8  454.51  5048.6  454.22  5062.2  452.78  5114.9  452.77  5122.3  453.02
  5131.9  455.75  5142.3  460.09  5172.4  462.45  5212.4  466.41  5229.3  468.55
#Mann=5,-1,0
  4825.9    0.16       0  4991.1    0.07       0  4997.1    0.16       0
  5043.8    0.12       0  5048.6    0.16       0
Bank Sta=4978.7,5131.9
Exp/Cntr=0.3,0.1

Type RM Length L Ch R = 1,9883,363,363,363
BEGIN DESCRIPTION:
Mapping XS a6478b7f
END DESCRIPTION:
XS GIS Cut Line= 3
      2818769.61      7015185.14      2818795.66      7014927.31
      2818888.65      7014728.41
#Sta/Elev= 30
  4737.9  462.29  4742.4  461.94  4748.1  462.61  4768.2  460.79  4848.6  456.37
  4908.9  454.44  4933.1  454.10  4940.9  453.62  4969.2  452.06  4986.3  451.70
  4986.8  450.90  4991.8  450.90  4992.3  451.70  4995.7  452.33  5006.2  452.64
  5011.7  451.82  5029.0  453.77  5038.1  454.10  5045.1  454.79  5051.9  455.15
  5057.4  456.98  5065.8  458.17  5074.7  458.76  5080.3  460.11  5097.6  460.97
  5103.1  462.21  5132.1  464.53  5143.1  465.00  5171.6  467.50  5216.6  470.49
#Mann=5,-1,0
  4737.9    0.16       0  4940.9    0.12       0  4986.3    0.07       0
  4992.3    0.12       0  5045.1    0.16       0
Bank Sta=4933.1,5038.1
Exp/Cntr=0.3,0.1

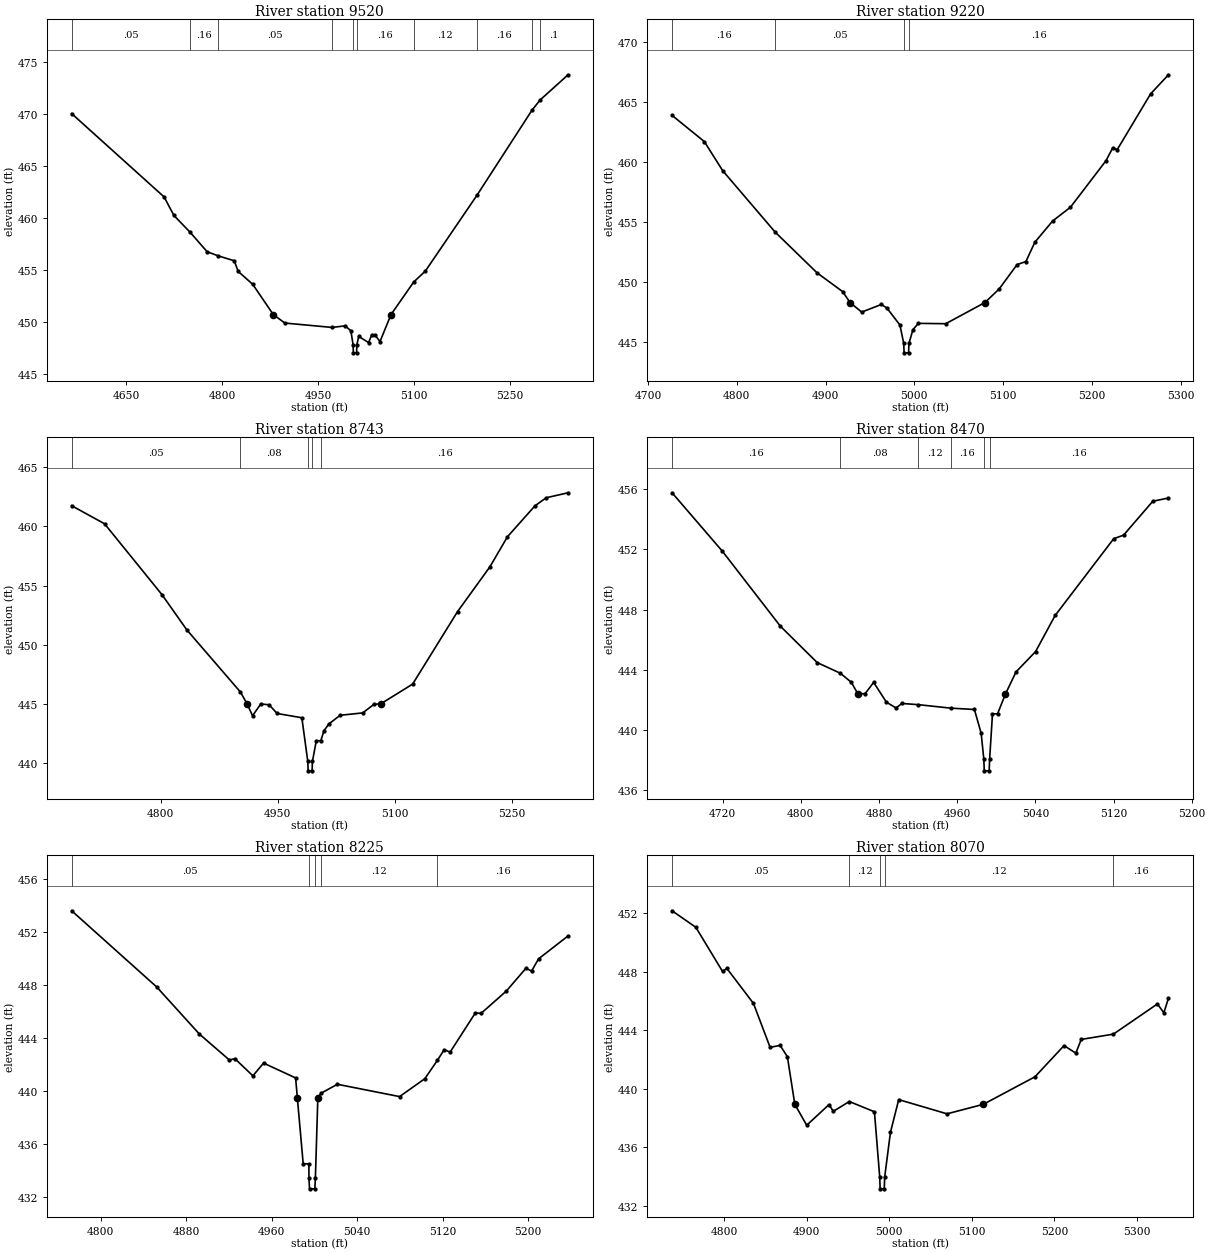
Type RM Length L Ch R = 1,9520,300,300,300
BEGIN DESCRIPTION:
Magee Branch 18.0
END DESCRIPTION:
XS GIS Cut Line= 3
      2818724.97      7015325.02      2819125.00      7015075.00
      2819175.01      7014774.97
#Sta/Elev= 30
  4564.9  470.02  4709.4  462.02  4724.7  460.24  4750.0  458.63  4776.6  456.76
  4794.0  456.36  4819.1  455.89  4825.0  454.88  4847.9  453.63  4880.0  450.73
  4898.1  449.91  4971.9  449.49  4992.4  449.64  5001.3  449.17  5004.7  447.85
  5005.2  447.05  5010.2  447.05  5010.7  447.85  5013.6  448.63  5029.0  448.03
  5033.7  448.75  5039.2  448.75  5046.8  448.13  5064.1  450.73  5099.5  453.85
  5117.7  454.90  5198.3  462.17  5284.2  470.33  5297.1  471.33  5340.8  473.75
#Mann=10,-1,0
  4564.9    0.05       0  4750.0    0.16       0  4794.0    0.05       0
  4971.9    0.16       0  5004.7    0.07       0  5010.7    0.16       0
  5099.5    0.12       0  5198.3    0.16       0  5284.2    0.07       0
  5297.1     0.1       0
Bank Sta=4880,5064.1
Exp/Cntr=0.3,0.1

Type RM Length L Ch R = 1,9220,477,477,477
BEGIN DESCRIPTION:
Magee Branch 17.0
END DESCRIPTION:
XS GIS Cut Line= 3
      2819175.03      7015424.97      2819347.74      7015198.15
      2819325.00      7014924.98
#Sta/Elev= 30
  4727.1  463.91  4763.4  461.73  4784.2  459.29  4843.4  454.16  4890.5  450.77
  4919.4  449.20  4927.5  448.30  4940.7  447.50  4963.0  448.14  4969.3  447.82
  4983.8  446.42  4988.0  444.90  4988.5  444.10  4993.5  444.10  4994.0  444.90
  4998.4  446.03  5004.6  446.56  5035.4  446.53  5079.6  448.30  5095.6  449.43
  5115.7  451.46  5125.7  451.72  5135.8  453.33  5155.8  455.10  5175.9  456.25
  5216.0  460.14  5223.5  461.20  5228.6  461.06  5266.2  465.71  5286.3  467.30
#Mann=4,-1,0
  4727.1    0.16       0  4843.4    0.05       0  4988.0    0.07       0
  4994.0    0.16       0
Bank Sta=4927.5,5079.6
Exp/Cntr=0.3,0.1

Type RM Length L Ch R = 1,8743,273,273,273
BEGIN DESCRIPTION:
Magee Branch 16.0
END DESCRIPTION:
XS GIS Cut Line= 3
      2819625.00      7015525.00      2819725.00      7015225.00
      2819524.99      7014974.98
#Sta/Elev= 30
  4685.9  461.75  4728.1  460.22  4801.8  454.23  4833.5  451.27  4902.3  446.02
  4910.7  445.03  4917.8  444.02  4928.3  445.01  4938.9  444.95  4949.4  444.21
  4981.0  443.85  4988.6  440.17  4989.1  439.37  4994.1  439.37  4994.6  440.17
  4999.5  441.91  5005.3  441.91  5009.3  442.75  5015.7  443.33  5030.1  444.06
  5059.0  444.26  5073.4  444.98  5082.3  445.03  5123.0  446.69  5180.6  452.81
  5222.2  456.60  5244.6  459.13  5279.9  461.74  5294.3  462.42  5322.3  462.84
#Mann=5,-1,0
  4685.9    0.05       0  4902.3    0.08       0  4988.6    0.07       0
  4994.6    0.08       0  5005.3    0.16       0
Bank Sta=4910.7,5082.3
Exp/Cntr=0.3,0.1

Type RM Length L Ch R = 1,8470,245,245,245
BEGIN DESCRIPTION:
Magee Branch 15.0
END DESCRIPTION:
XS GIS Cut Line= 3
      2819824.98      7015475.03      2819985.76      7015187.73
      2819980.58      7015009.04
#Sta/Elev= 30
  4668.2  455.77  4719.6  451.89  4779.0  446.90  4816.7  444.48  4840.4  443.77
  4851.6  443.17  4858.5  442.38  4865.8  442.42  4874.5  443.16  4887.5  441.85
  4897.4  441.46  4903.4  441.76  4920.3  441.68  4953.2  441.45  4977.6  441.36
  4984.5  439.78  4987.2  438.08  4987.7  437.28  4992.7  437.28  4993.2  438.08
  4996.1  441.07  5001.3  441.07  5009.3  442.38  5020.2  443.86  5040.2  445.21
  5060.2  447.61  5120.2  452.72  5130.2  452.95  5160.2  455.21  5176.2  455.42
#Mann=6,-1,0
  4668.2    0.16       0  4840.4    0.08       0  4920.3    0.12       0
  4953.2    0.16       0  4987.2    0.07       0  4993.2    0.16       0
Bank Sta=4858.5,5009.3
Exp/Cntr=0.3,0.1

Type RM Length L Ch R = 1,8225,155,155,155
BEGIN DESCRIPTION:
Mapping XS db5536bb
END DESCRIPTION:
XS GIS Cut Line= 3
      2820144.62      7015544.48      2820152.43      7015325.75
      2820056.26      7015099.62
#Sta/Elev= 30
  4772.7  453.61  4852.2  447.86  4892.3  444.29  4920.4  442.33  4925.4  442.44
  4942.3  441.14  4952.3  442.10  4982.3  440.98  4983.9  439.49  4989.4  434.49
  4994.7  434.49  4994.8  433.40  4995.3  432.60  5000.3  432.60  5000.8  433.40
  5003.1  439.49  5006.2  439.83  5021.4  440.50  5079.6  439.57  5103.2  440.92
  5115.0  442.31  5121.4  443.12  5126.9  442.93  5150.5  445.89  5155.9  445.86
  5179.6  447.55  5197.8  449.26  5203.2  449.06  5209.7  449.98  5237.3  451.71
#Mann=5,-1,0
  4772.7    0.05       0  4994.8    0.04       0  5000.8    0.05       0
  5006.2    0.12       0  5115.0    0.16       0
Bank Sta=4983.9,5003.1
Exp/Cntr=0.3,0.1

Type RM Length L Ch R = 1,8070,467,467,467
BEGIN DESCRIPTION:
Mapping XS e41aab61
END DESCRIPTION:
XS GIS Cut Line= 4
      2820211.45      7015508.07      2820284.37      7015278.88
      2820286.98      7015195.54      2820107.28      7014984.60
#Sta/Elev= 30
  4737.1  452.15  4765.9  451.02  4798.2  448.01  4803.4  448.22  4835.6  445.83
  4855.8  442.83  4867.9  442.96  4876.7  442.19  4885.7  438.94  4900.1  437.51
  4927.1  438.92  4932.3  438.46  4951.7  439.13  4982.1  438.43  4988.5  433.97
  4989.0  433.17  4994.0  433.17  4994.5  433.97  5001.5  437.03  5011.5  439.26
  5070.0  438.29  5114.0  438.94  5176.5  440.82  5211.7  442.95  5225.9  442.43
  5232.5  443.37  5271.4  443.73  5324.7  445.79  5332.5  445.19  5338.1  446.18
#Mann=5,-1,0
  4737.1    0.05       0  4951.7    0.12       0  4988.5    0.07       0
  4994.5    0.12       0  5271.4    0.16       0
Bank Sta=4885.7,5114
Exp/Cntr=0.3,0.1

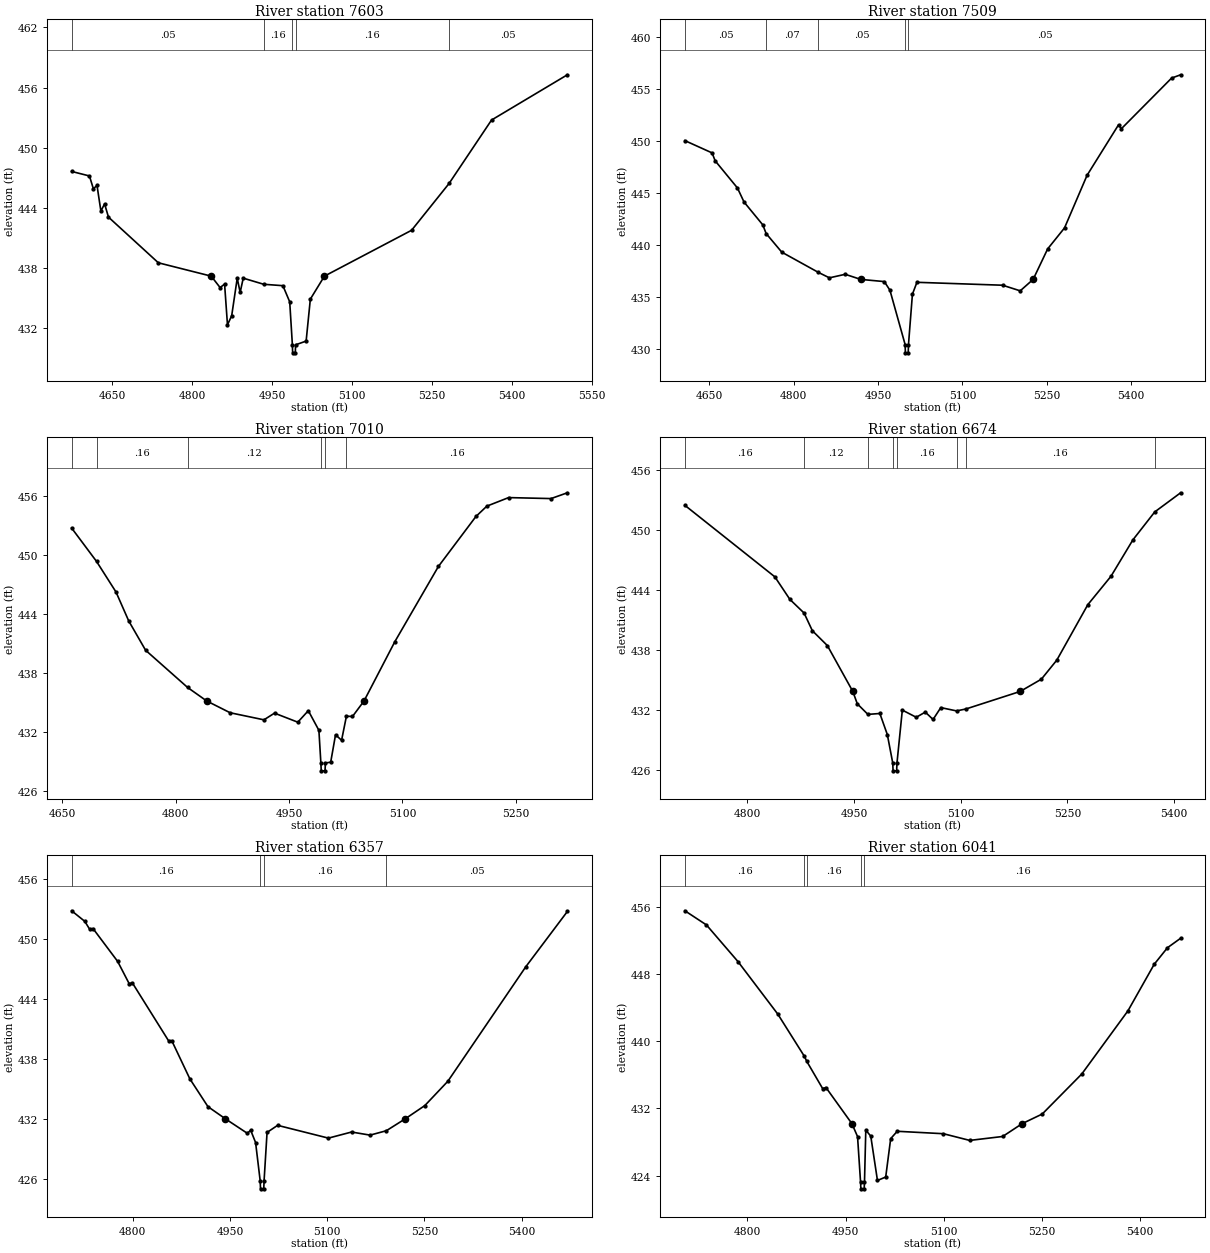
Type RM Length L Ch R = 1,7603,94,94,94
BEGIN DESCRIPTION:
Mapping XS fc4980b6
END DESCRIPTION:
XS GIS Cut Line= 5
      2820279.13      7015426.48      2820365.97      7015332.70
      2820581.25      7015242.42      2820654.16      7015221.59
      2821147.26      7015225.06
#Sta/Elev= 30
  4573.6  447.64  4607.0  447.19  4614.4  445.91  4621.2  446.25  4628.5  443.69
  4635.4  444.41  4642.7  443.09  4736.3  438.54  4835.5  437.21  4852.2  436.07
  4860.6  436.42  4866.0  432.36  4873.9  433.26  4884.3  437.00  4889.8  435.59
  4895.6  437.01  4934.0  436.40  4970.0  436.26  4982.8  434.65  4987.8  430.37
  4988.3  429.57  4993.3  429.57  4993.8  430.37  5013.6  430.74  5021.5  434.92
  5047.9  437.21  5211.5  441.78  5281.8  446.44  5361.5  452.76  5503.8  457.27
#Mann=5,-1,0
  4573.6    0.05       0  4934.0    0.16       0  4987.8    0.07       0
  4993.8    0.16       0  5281.8    0.05       0
Bank Sta=4835.5,5047.9
Exp/Cntr=0.3,0.1

Type RM Length L Ch R = 1,7509,499,499,499
BEGIN DESCRIPTION:
Mapping XS 011b23f3
END DESCRIPTION:
XS GIS Cut Line= 4
      2820310.42      7015442.94      2820578.64      7015312.73
      2820695.83      7015310.13      2821161.03      7015336.12
#Sta/Elev= 30
  4606.6  450.02  4654.9  448.84  4660.4  448.08  4700.0  445.47  4711.7  444.12
  4745.1  441.92  4751.0  441.09  4778.8  439.30  4844.0  437.35  4863.5  436.83
  4891.6  437.17  4919.2  436.68  4961.1  436.47  4971.1  435.64  4998.1  430.42
  4998.6  429.62  5003.6  429.62  5004.1  430.42  5011.1  435.26  5019.1  436.40
  5171.4  436.12  5202.7  435.58  5225.7  436.68  5251.5  439.61  5281.5  441.63
  5321.6  446.69  5377.5  451.54  5382.5  451.16  5471.8  456.03  5487.9  456.35
#Mann=5,-1,0
  4606.6    0.05       0  4751.0    0.07       0  4844.0    0.05       0
  4998.1    0.04       0  5004.1    0.05       0
Bank Sta=4919.2,5225.7
Exp/Cntr=0.3,0.1

Type RM Length L Ch R = 1,7010,336,336,336
BEGIN DESCRIPTION:
Magee Branch 11.0
END DESCRIPTION:
XS GIS Cut Line= 3
      2820725.00      7015775.00      2821025.00      7015625.00
      2821225.02      7015374.97
#Sta/Elev= 30
  4662.6  452.71  4695.5  449.32  4721.3  446.20  4738.1  443.26  4760.4  440.28
  4816.0  436.49  4841.2  435.12  4872.2  433.92  4916.9  433.20  4930.9  433.88
  4961.7  432.96  4975.6  434.13  4989.6  432.13  4992.2  428.81  4992.7  428.01
  4997.7  428.01  4998.2  428.81  5005.2  428.89  5011.6  431.68  5019.6  431.12
  5026.0  433.57  5034.0  433.54  5049.3  435.12  5090.1  441.16  5147.7  448.81
  5197.3  453.89  5211.7  454.94  5240.5  455.81  5296.6  455.71  5318.2  456.30
#Mann=6,-1,0
  4662.6    0.05       0  4695.5    0.16       0  4816.0    0.12       0
  4992.2    0.07       0  4998.2    0.12       0  5026.0    0.16       0
Bank Sta=4841.2,5049.3
Exp/Cntr=0.3,0.1

Type RM Length L Ch R = 1,6674,317,317,317
BEGIN DESCRIPTION:
Magee Branch 10.0
END DESCRIPTION:
XS GIS Cut Line= 3
      2820874.99      7016025.00      2821175.00      7015925.00
      2821524.98      7015775.01
#Sta/Elev= 30
  4712.2  452.50  4838.7  445.33  4859.8  443.07  4879.8  441.70  4891.4  439.93
  4912.5  438.44  4948.3  433.84  4954.6  432.60  4969.5  431.54  4986.3  431.63
  4996.8  429.52  5004.4  426.68  5004.9  425.88  5009.9  425.88  5010.4  426.68
  5017.9  431.97  5037.5  431.25  5050.2  431.77  5061.1  431.03  5072.0  432.22
  5094.1  431.89  5107.2  432.08  5183.6  433.84  5213.4  435.07  5235.1  436.98
  5278.7  442.54  5311.3  445.39  5342.1  449.04  5372.8  451.84  5409.2  453.76
#Mann=8,-1,0
  4712.2    0.16       0  4879.8    0.12       0  4969.5    0.16       0
  5004.4    0.07       0  5010.4    0.16       0  5094.1    0.12       0
  5107.2    0.16       0  5372.8    0.05       0
Bank Sta=4948.3,5183.6
Exp/Cntr=0.3,0.1

Type RM Length L Ch R = 1,6357,316,316,316
BEGIN DESCRIPTION:
Magee Branch 9.0
END DESCRIPTION:
XS GIS Cut Line= 3
      2820974.99      7016275.00      2821275.00      7016225.00
      2821574.98      7015875.02
#Sta/Elev= 30
  4705.6  452.86  4725.9  451.80  4733.5  451.00  4738.6  451.08  4776.6  447.79
  4794.3  445.57  4799.4  445.63  4855.1  439.85  4860.2  439.84  4888.1  436.02
  4916.0  433.24  4943.0  432.02  4976.8  430.57  4981.9  430.88  4989.5  429.65
  4996.6  425.81  4997.1  425.01  5002.1  425.01  5002.6  425.81  5007.2  430.66
  5023.5  431.37  5101.9  430.09  5137.6  430.70  5166.2  430.39  5191.3  430.83
  5220.4  432.02  5250.7  433.35  5286.3  435.79  5406.5  447.25  5470.7  452.79
#Mann=4,-1,0
  4705.6    0.16       0  4996.6    0.07       0  5002.6    0.16       0
  5191.3    0.05       0
Bank Sta=4943,5220.4
Exp/Cntr=0.3,0.1

Type RM Length L Ch R = 1,6041,383,383,383
BEGIN DESCRIPTION:
Magee Branch 8.0
END DESCRIPTION:
XS GIS Cut Line= 3
      2820975.02      7016475.00      2821275.00      7016525.00
      2821725.01      7016475.00
#Sta/Elev= 30
  4704.7  455.60  4737.6  453.91  4785.8  449.53  4846.6  443.26  4887.1  438.23
  4890.9  437.61  4915.0  434.38  4920.1  434.50  4959.7  430.19  4968.3  428.65
  4972.9  423.21  4973.4  422.41  4978.4  422.41  4978.9  423.21  4980.9  429.42
  4988.5  428.70  4998.7  423.41  5011.3  423.82  5018.9  428.40  5028.9  429.28
  5099.4  428.99  5139.6  428.19  5189.9  428.66  5219.6  430.19  5250.3  431.34
  5310.7  436.12  5381.1  443.65  5421.3  449.22  5441.5  451.19  5461.6  452.32
#Mann=5,-1,0
  4704.7    0.16       0  4887.1    0.12       0  4890.9    0.16       0
  4972.9    0.07       0  4978.9    0.16       0
Bank Sta=4959.7,5219.6
Exp/Cntr=0.3,0.1

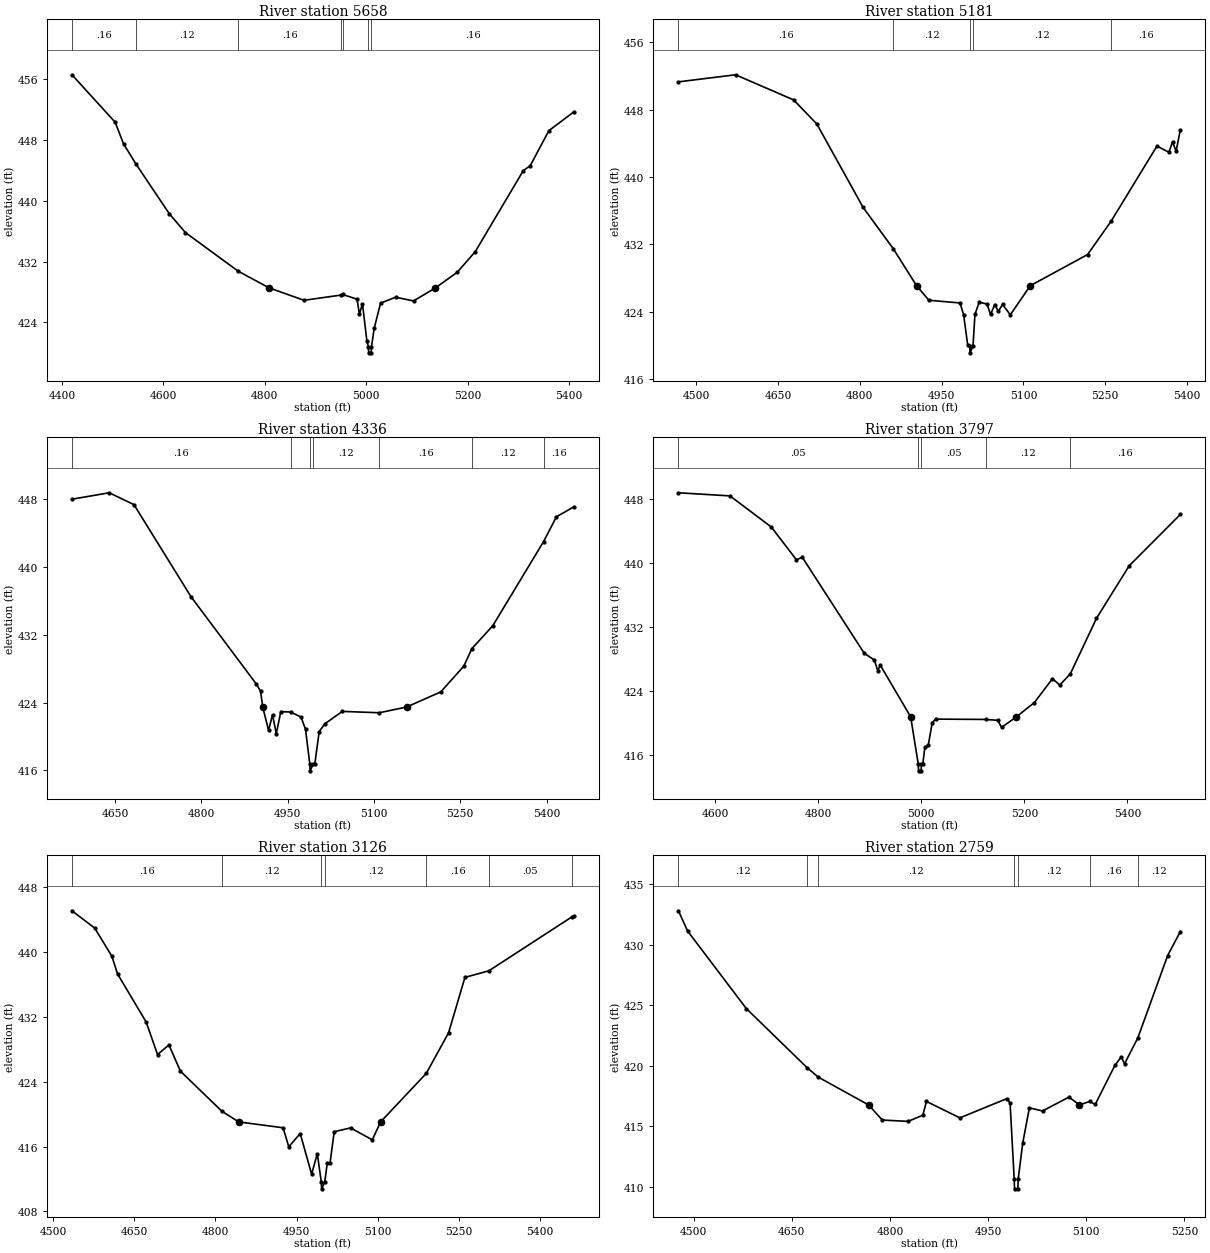
Type RM Length L Ch R = 1,5658,477,477,477
BEGIN DESCRIPTION:
Magee Branch 7.0
END DESCRIPTION:
XS GIS Cut Line= 3
      2820874.98      7016925.00      2821425.00      7016825.00
      2821775.04      7016574.97
#Sta/Elev= 30
  4419.8  456.57  4504.9  450.34  4521.5  447.48  4545.7  444.86  4611.7  438.29
  4643.4  435.82  4747.9  430.72  4808.6  428.54  4877.2  426.91  4950.5  427.60
  4953.2  427.68  4981.9  427.05  4986.2  425.09  4992.4  426.45  5001.0  421.60
  5004.1  420.80  5004.6  420.00  5009.6  420.00  5010.1  420.80  5015.7  423.28
  5028.0  426.53  5057.5  427.31  5093.1  426.83  5136.1  428.54  5179.1  430.59
  5214.8  433.32  5309.4  443.97  5322.9  444.60  5359.8  449.22  5409.0  451.69
#Mann=7,-1,0
  4419.8    0.16       0  4545.7    0.12       0  4747.9    0.16       0
  4950.5    0.12       0  4953.2    0.16       0  5004.1    0.07       0
  5010.1    0.16       0
Bank Sta=4808.6,5136.1
Exp/Cntr=0.3,0.1

Type RM Length L Ch R = 1,5181,845,845,845
BEGIN DESCRIPTION:
Magee Branch 6.0
END DESCRIPTION:
XS GIS Cut Line= 3
      2821320.32      7017517.70      2821620.31      7017167.71
      2821919.18      7016819.03
#Sta/Elev= 30
  4467.5  451.30  4572.2  452.14  4678.7  449.16  4721.3  446.30  4806.0  436.41
  4861.5  431.49  4904.1  427.11  4926.7  425.38  4983.8  425.06  4990.4  423.66
  4997.9  420.06  5001.6  419.94  5002.1  419.14  5007.6  419.94  5011.2  423.71
  5018.9  425.14  5033.2  424.94  5039.8  423.70  5047.5  424.87  5054.0  424.05
  5061.7  424.89  5076.0  423.65  5112.6  427.11  5217.6  430.80  5260.7  434.75
  5344.9  443.68  5366.7  442.95  5373.4  444.16  5380.0  443.09  5387.7  445.59
#Mann=5,-1,0
  4467.5    0.16       0  4861.5    0.12       0  5001.6    0.07       0
  5007.6    0.12       0  5260.7    0.16       0
Bank Sta=4904.1,5112.6
Exp/Cntr=0.3,0.1

Type RM Length L Ch R = 1,4336,539,539,539
BEGIN DESCRIPTION:
Magee Branch 5.0
END DESCRIPTION:
XS GIS Cut Line= 3
      2821701.75      7017792.70      2822025.00      7017525.00
      2822075.00      7017074.98
#Sta/Elev= 30
  4574.9  448.02  4639.7  448.78  4682.7  447.38  4781.7  436.52  4895.0  426.23
  4902.8  425.36  4906.5  423.48  4916.7  420.73  4923.6  422.56  4930.1  420.32
  4938.0  422.94  4955.1  422.88  4973.1  422.30  4980.9  420.85  4988.4  416.74
  4988.9  415.94  4994.4  416.74  4997.1  416.74  5004.7  420.58  5014.7  421.50
  5044.9  422.96  5109.2  422.80  5156.8  423.48  5216.0  425.26  5256.2  428.31
  5270.1  430.37  5306.5  433.08  5394.7  443.01  5417.2  445.95  5447.4  447.12
#Mann=7,-1,0
  4574.9    0.16       0  4955.1    0.12       0  4988.4    0.07       0
  4994.4    0.12       0  5109.2    0.16       0  5270.1    0.12       0
  5394.7    0.16       0
Bank Sta=4906.5,5156.8
Exp/Cntr=0.3,0.1

Type RM Length L Ch R = 1,3797,671,671,671
BEGIN DESCRIPTION:
Magee Branch 4.0
END DESCRIPTION:
XS GIS Cut Line= 3
      2821675.04      7017975.00      2822145.87      7018005.36
      2822525.02      7017674.98
#Sta/Elev= 30
  4528.2  448.81  4628.4  448.42  4708.5  444.54  4757.4  440.44  4768.7  440.76
  4888.9  428.78  4908.9  427.91  4915.3  426.58  4920.3  427.27  4979.2  420.83
  4994.1  414.88  4994.6  414.08  4999.6  414.08  5000.1  414.88  5002.7  414.88
  5006.8  417.02  5013.5  417.31  5021.1  420.09  5027.7  420.54  5124.6  420.50
  5148.3  420.39  5155.9  419.51  5184.7  420.83  5219.5  422.61  5254.6  425.59
  5268.8  424.79  5289.4  426.21  5340.1  433.13  5403.7  439.70  5502.9  446.10
#Mann=5,-1,0
  4528.2    0.05       0  4994.1    0.04       0  5000.1    0.05       0
  5124.6    0.12       0  5289.4    0.16       0
Bank Sta=4979.2,5184.7
Exp/Cntr=0.3,0.1

Type RM Length L Ch R = 1,3126,367,367,367
BEGIN DESCRIPTION:
Magee Branch 3.0
END DESCRIPTION:
XS GIS Cut Line= 3
      2822075.03      7018374.99      2822525.00      7018225.00
      2822575.00      7017774.98
#Sta/Elev= 30
  4535.2  445.10  4577.3  442.96  4609.0  439.48  4619.5  437.29  4672.2  431.38
  4693.3  427.36  4714.4  428.54  4735.5  425.31  4812.1  420.36  4843.2  419.04
  4925.2  418.32  4935.7  415.97  4956.8  417.61  4977.9  412.59  4988.4  415.11
  4995.9  411.58  4996.4  410.78  5002.0  411.58  5006.9  413.99  5012.0  413.99
  5019.6  417.83  5049.8  418.30  5090.0  416.83  5105.3  419.04  5189.7  425.03
  5230.9  430.04  5261.1  436.88  5305.3  437.69  5458.3  444.33  5462.3  444.41
#Mann=7,-1,0
  4535.2    0.16       0  4812.1    0.12       0  4995.9    0.07       0
  5002.0    0.12       0  5189.7    0.16       0  5305.3    0.05       0
  5458.3    0.16       0
Bank Sta=4843.2,5105.3
Exp/Cntr=0.3,0.1

Type RM Length L Ch R = 1,2759,258,258,258
BEGIN DESCRIPTION:
Mapping XS a4ed873e
END DESCRIPTION:
XS GIS Cut Line= 3
      2822543.07      7018790.99      2822758.33      7018353.53
      2822789.58      7018075.73
#Sta/Elev= 30
  4476.7  432.81  4490.7  431.14  4580.5  424.72  4673.8  419.81  4690.5  419.05
  4767.4  416.75  4788.3  415.50  4827.7  415.39  4850.2  415.90  4855.8  417.04
  4906.9  415.68  4978.5  417.27  4983.6  416.94  4989.9  410.61  4990.4  409.81
  4995.5  409.81  4996.0  410.61  5003.0  413.61  5013.1  416.51  5033.2  416.25
  5073.6  417.40  5089.7  416.75  5105.2  417.04  5113.7  416.79  5143.9  420.03
  5153.5  420.72  5158.5  420.15  5178.9  422.30  5224.4  429.10  5243.8  431.09
#Mann=7,-1,0
  4476.7    0.12       0  4673.8    0.16       0  4690.5    0.12       0
  4989.9    0.07       0  4996.0    0.12       0  5105.2    0.16       0
  5178.9    0.12       0
Bank Sta=4767.4,5089.7
Exp/Cntr=0.3,0.1