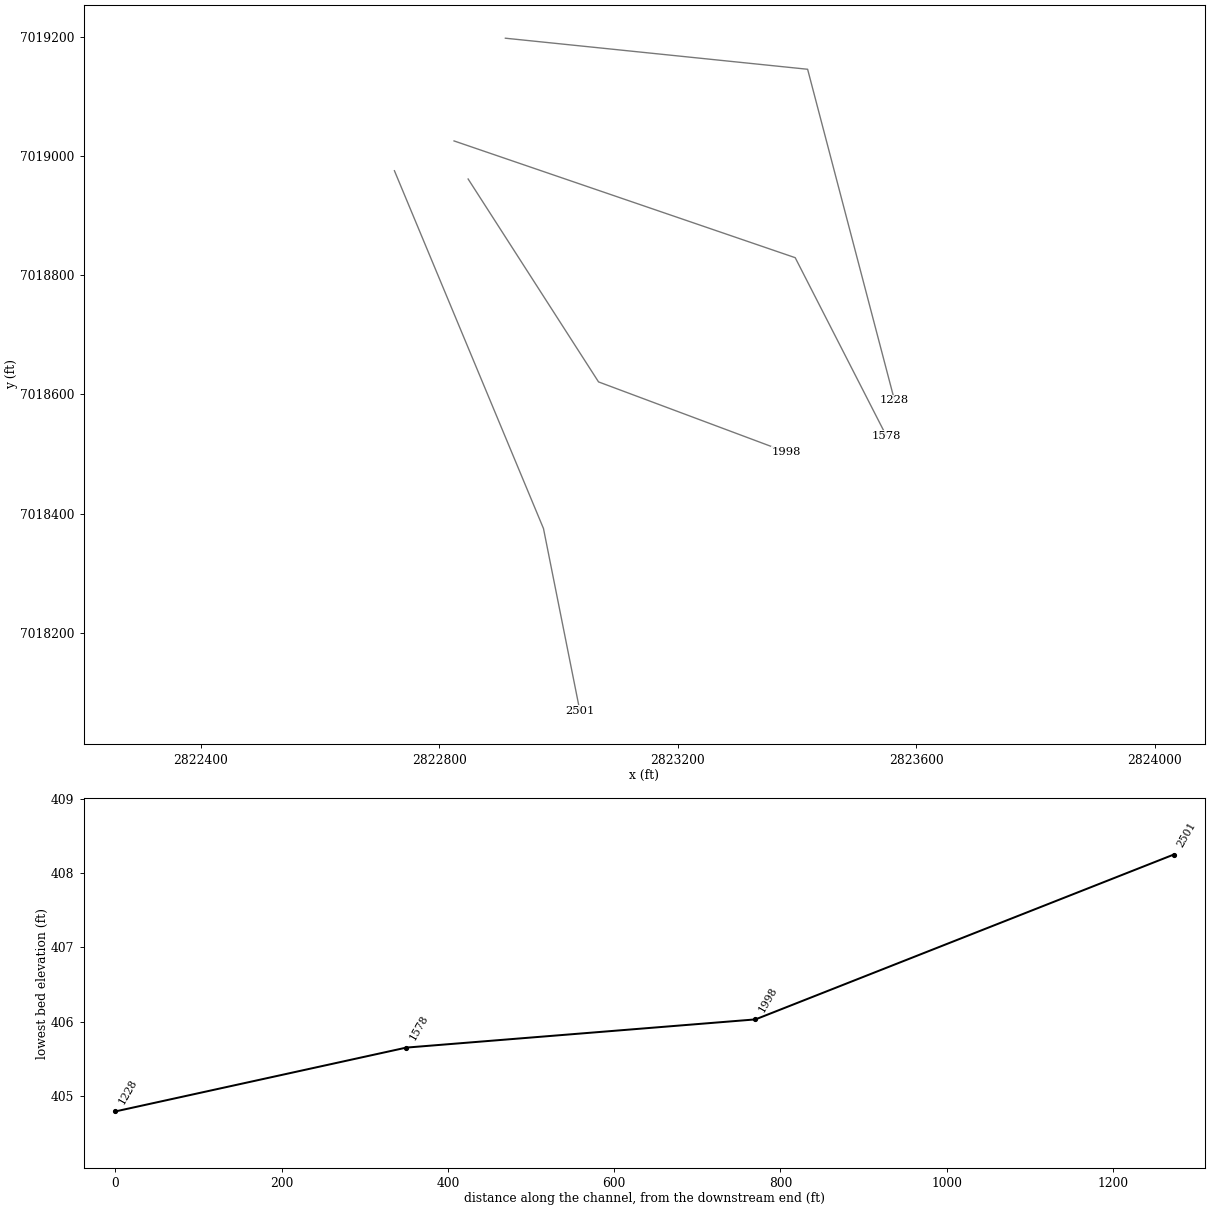
HEC-RAS study Magee Branch.prj: Magee Branch Base Level Engineering

--- Magee Branch.g01 (geometry) --- (continued)

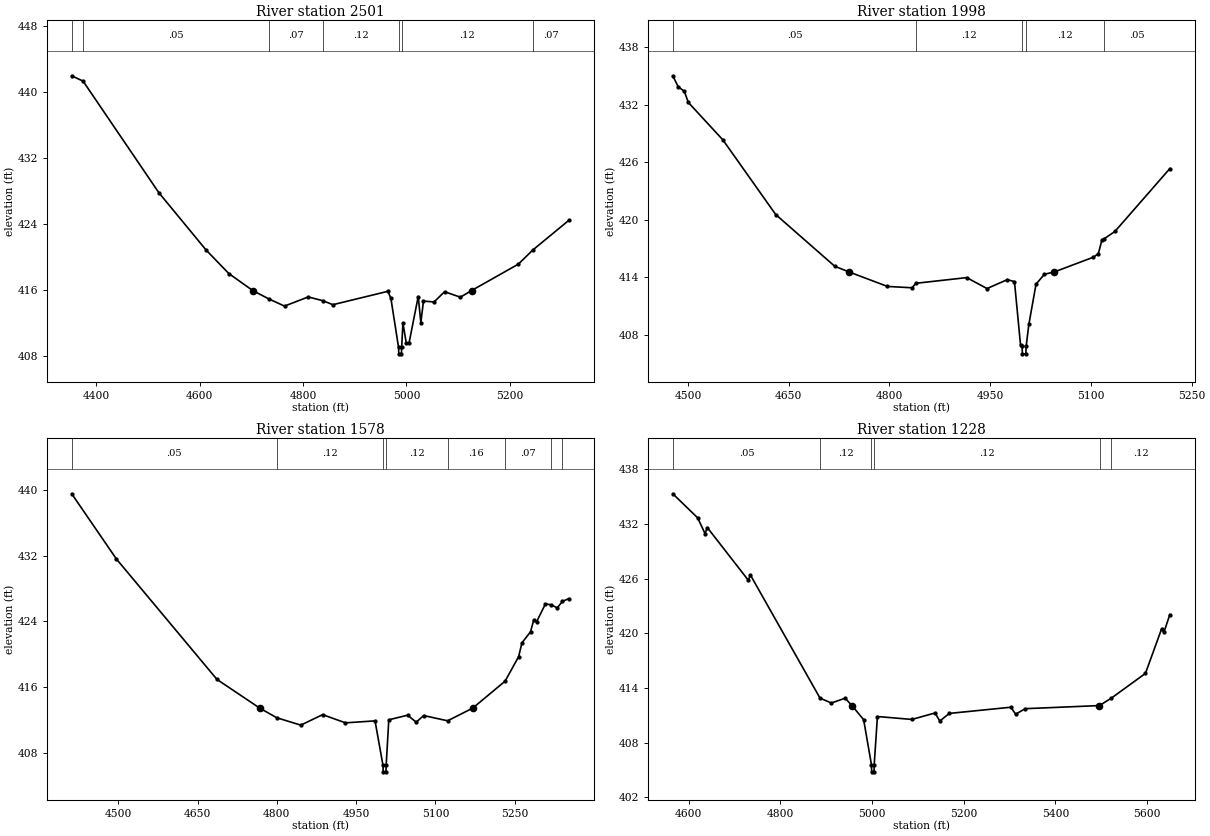
Type RM Length L Ch R = 1,2501,503,503,503
BEGIN DESCRIPTION:
Magee Branch 2.0
END DESCRIPTION:
XS GIS Cut Line= 3
      2822724.99      7018975.02      2822975.00      7018375.00
      2823035.98      7018069.45
#Sta/Elev= 30
  4352.4  441.97  4374.4  441.32  4520.9  427.80  4612.4  420.84  4656.3  417.99
  4702.6  415.93  4733.5  414.92  4764.1  414.04  4810.1  415.15  4838.4  414.69
  4857.8  414.21  4964.0  415.83  4969.9  415.00  4984.7  409.05  4985.2  408.25
  4990.3  408.25  4990.8  409.05  4993.2  412.00  4999.7  409.55  5005.0  409.55
  5022.8  415.20  5027.9  412.05  5033.0  414.65  5053.4  414.54  5073.8  415.78
  5104.4  415.12  5126.2  415.93  5216.6  419.13  5244.5  420.84  5314.0  424.43
#Mann=7,-1,0
  4352.4    0.12       0  4374.4    0.05       0  4733.5    0.07       0
  4838.4    0.12       0  4984.7    0.07       0  4990.8    0.12       0
  5244.5    0.07       0
Bank Sta=4702.6,5126.2
Exp/Cntr=0.3,0.1

Type RM Length L Ch R = 1,1998,420,420,420
BEGIN DESCRIPTION:
Mapping XS b5c7318d
END DESCRIPTION:
XS GIS Cut Line= 3
      2822848.62      7018961.16      2823067.36      7018620.89
      2823381.63      7018503.47
#Sta/Elev= 30
  4477.4  435.03  4485.3  433.90  4494.6  433.40  4500.5  432.25  4552.0  428.34
  4630.6  420.56  4718.4  415.17  4739.8  414.57  4797.0  413.06  4833.4  412.92
  4839.6  413.39  4914.9  413.98  4945.2  412.84  4975.5  413.77  4986.1  413.56
  4995.1  406.96  4997.4  406.83  4997.9  406.03  5003.0  406.03  5003.5  406.83
  5007.5  409.10  5018.2  413.30  5030.7  414.33  5045.3  414.57  5103.6  416.11
  5111.0  416.48  5116.3  417.92  5119.0  418.00  5135.6  418.79  5217.4  425.35
#Mann=5,-1,0
  4477.4    0.05       0  4839.6    0.12       0  4997.4    0.07       0
  5003.5    0.12       0  5119.0    0.05       0
Bank Sta=4739.8,5045.3
Exp/Cntr=0.3,0.1

Type RM Length L Ch R = 1,1578,350,350,350
BEGIN DESCRIPTION:
Magee Branch 1.0
END DESCRIPTION:
XS GIS Cut Line= 3
      2822824.98      7019025.01      2823397.22      7018829.22
      2823549.98      7018530.64
#Sta/Elev= 30
  4411.9  439.53  4496.5  431.58  4686.7  416.91  4767.7  413.41  4799.8  412.24
  4845.3  411.34  4886.5  412.62  4929.8  411.62  4985.7  411.86  5000.7  406.45
  5001.2  405.65  5006.3  405.65  5006.8  406.45  5011.7  411.99  5047.2  412.55
  5063.7  411.70  5077.6  412.51  5123.0  411.87  5170.4  413.41  5231.6  416.69
  5257.3  419.68  5263.6  421.37  5279.8  422.71  5285.9  424.15  5291.5  423.96
  5308.1  426.12  5319.4  425.99  5330.3  425.63  5340.2  426.42  5352.1  426.75
#Mann=8,-1,0
  4411.9    0.05       0  4799.8    0.12       0  5000.7    0.07       0
  5006.8    0.12       0  5123.0    0.16       0  5231.6    0.07       0
  5319.4    0.12       0  5340.2    0.05       0
Bank Sta=4767.7,5170.4
Exp/Cntr=0.3,0.1

Type RM Length L Ch R = 1,1228,0,0,0
BEGIN DESCRIPTION:
Mapping XS d7c4ff02
END DESCRIPTION:
XS GIS Cut Line= 3
      2822911.09      7019197.28      2823418.05      7019145.20
      2823563.83      7018589.84
#Sta/Elev= 30
  4565.7  435.30  4619.9  432.66  4636.0  430.93  4641.0  431.59  4730.1  425.83
  4735.1  426.37  4886.7  412.88  4911.4  412.34  4941.6  412.87  4956.3  412.06
  4981.8  410.52  4998.8  405.59  4999.3  404.79  5004.4  404.79  5004.9  405.59
  5011.9  410.86  5087.0  410.54  5137.6  411.25  5147.9  410.36  5168.6  411.20
  5303.0  411.88  5313.3  411.11  5334.0  411.72  5495.8  412.06  5497.9  412.12
  5522.1  412.88  5596.3  415.59  5631.5  420.47  5636.7  420.12  5649.5  422.04
#Mann=6,-1,0
  4565.7    0.05       0  4886.7    0.12       0  4998.8    0.07       0
  5004.9    0.12       0  5497.9    0.16       0  5522.1    0.12       0
Bank Sta=4956.3,5495.8
Exp/Cntr=0.3,0.1

Chan Stop Cuts=-1