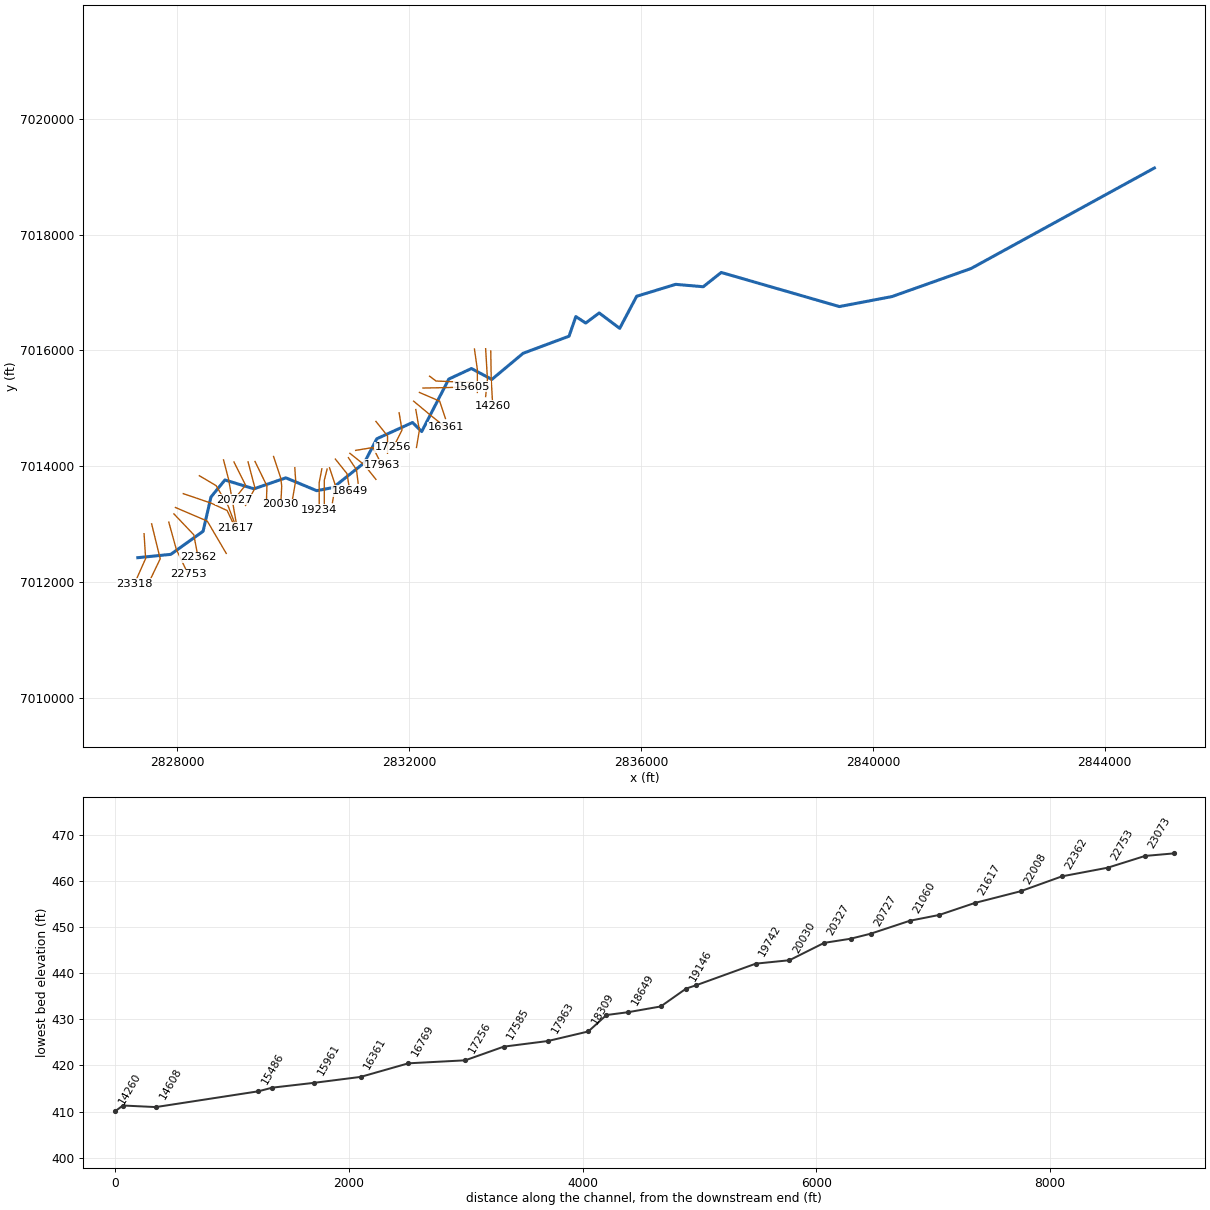
--- Penson Spring Branch.prj (project) ---

Proj Title=Penson Spring Branch Base Level Engineering
Current Plan=p01
Default Exp/Contr=0.3,0.1
English Units
Geom File=g01
Flow File=f01
Plan File=p01
BEGIN DESCRIPTION:
Penson Spring Branch
END DESCRIPTION:

--- Penson Spring Branch.p01 (plan) ---

Plan Title=Multiple Run
Short Identifier=Multiple
Geom File=g01
Flow File=f01
Subcritical Flow
K Sum by GR= 0
Std Step Tol= 0.01
Critical Tol= 0.01
Num of Std Step Trials= 20
Max Error Tol= 0.3
Flow Tol Ratio= 0.001
Split Flow NTrial= 30
Split Flow Tol= 0.02
Split Flow Ratio= 0.02
Log Output Level= 0
Friction Slope Method= 1
Unsteady Friction Slope Method= 2
Unsteady Bridges Friction Slope Method= 1
Parabolic Critical Depth
Global Vel Dist=  1 , 1 , 1
Global Log Level= 0
CheckData=True
Encroach Param= -1, 0, 0, 0
BEGIN DESCRIPTION:
Multiple Run
END DESCRIPTION:

--- Penson Spring Branch.f01 (steady flow) ---

Flow Title=Multiple
Number of Profiles=7
Profile Names=10-year,25-year,50-year,1pct_min,100-year,1pct_plu,500-year
River Rch & RM= Penson Spring Br,Reach-1,23318
     348     449     529     310     618    1234     846
River Rch & RM= Penson Spring Br,Reach-1,16361
     608     811     975     582    1162    2319    1653
River Rch & RM= Penson Spring Br,Reach-1,10302
     806    1087    1316     790    1577    3147    2269
River Rch & RM= Penson Spring Br,Reach-1,4753
     949    1283    1556     936    1867    3724    2691
Boundary for River Rch & Prof#=Penson Spring Br,Reach-1,1
Up Type=0
Dn Type=3
Dn Slope=0.005
Boundary for River Rch & Prof#=Penson Spring Br,Reach-1,2
Up Type=0
Dn Type=3
Dn Slope=0.005
Boundary for River Rch & Prof#=Penson Spring Br,Reach-1,3
Up Type=0
Dn Type=3
Dn Slope=0.005
Boundary for River Rch & Prof#=Penson Spring Br,Reach-1,4
Up Type=0
Dn Type=3
Dn Slope=0.005
Boundary for River Rch & Prof#=Penson Spring Br,Reach-1,5
Up Type=0
Dn Type=3
Dn Slope=0.005
Boundary for River Rch & Prof#=Penson Spring Br,Reach-1,6
Up Type=0
Dn Type=3
Dn Slope=0.005
Boundary for River Rch & Prof#=Penson Spring Br,Reach-1,7
Up Type=0
Dn Type=3
Dn Slope=0.005

--- Penson Spring Branch.g01 (geometry) ---

Geom Title=Existing Conditions

River Reach=Penson Spring Br,Reach-1
Reach XY= 30
      2827316.67      7012423.35      2827884.81      7012480.90
      2828442.40      7012879.47      2828578.51      7013470.44
      2828819.49      7013764.19      2829320.67      7013611.76
      2829870.91      7013801.20      2830402.92      7013579.62
      2830688.90      7013634.30      2831224.56      7014061.69
      2831440.10      7014476.00      2832056.71      7014756.18
      2832215.05      7014599.87      2832682.75      7015505.98
      2833073.62      7015687.46      2833425.05      7015499.41
      2833965.69      7015950.91      2834757.47      7016245.46
      2834874.85      7016584.48      2835044.70      7016472.62
      2835278.08      7016646.62      2835631.59      7016380.79
      2835924.35      7016934.54      2836596.86      7017140.30
      2837073.28      7017098.88      2837383.67      7017345.46
      2839422.51      7016756.89      2840329.75      7016929.24
      2841695.48      7017413.75      2844859.00      7019148.24

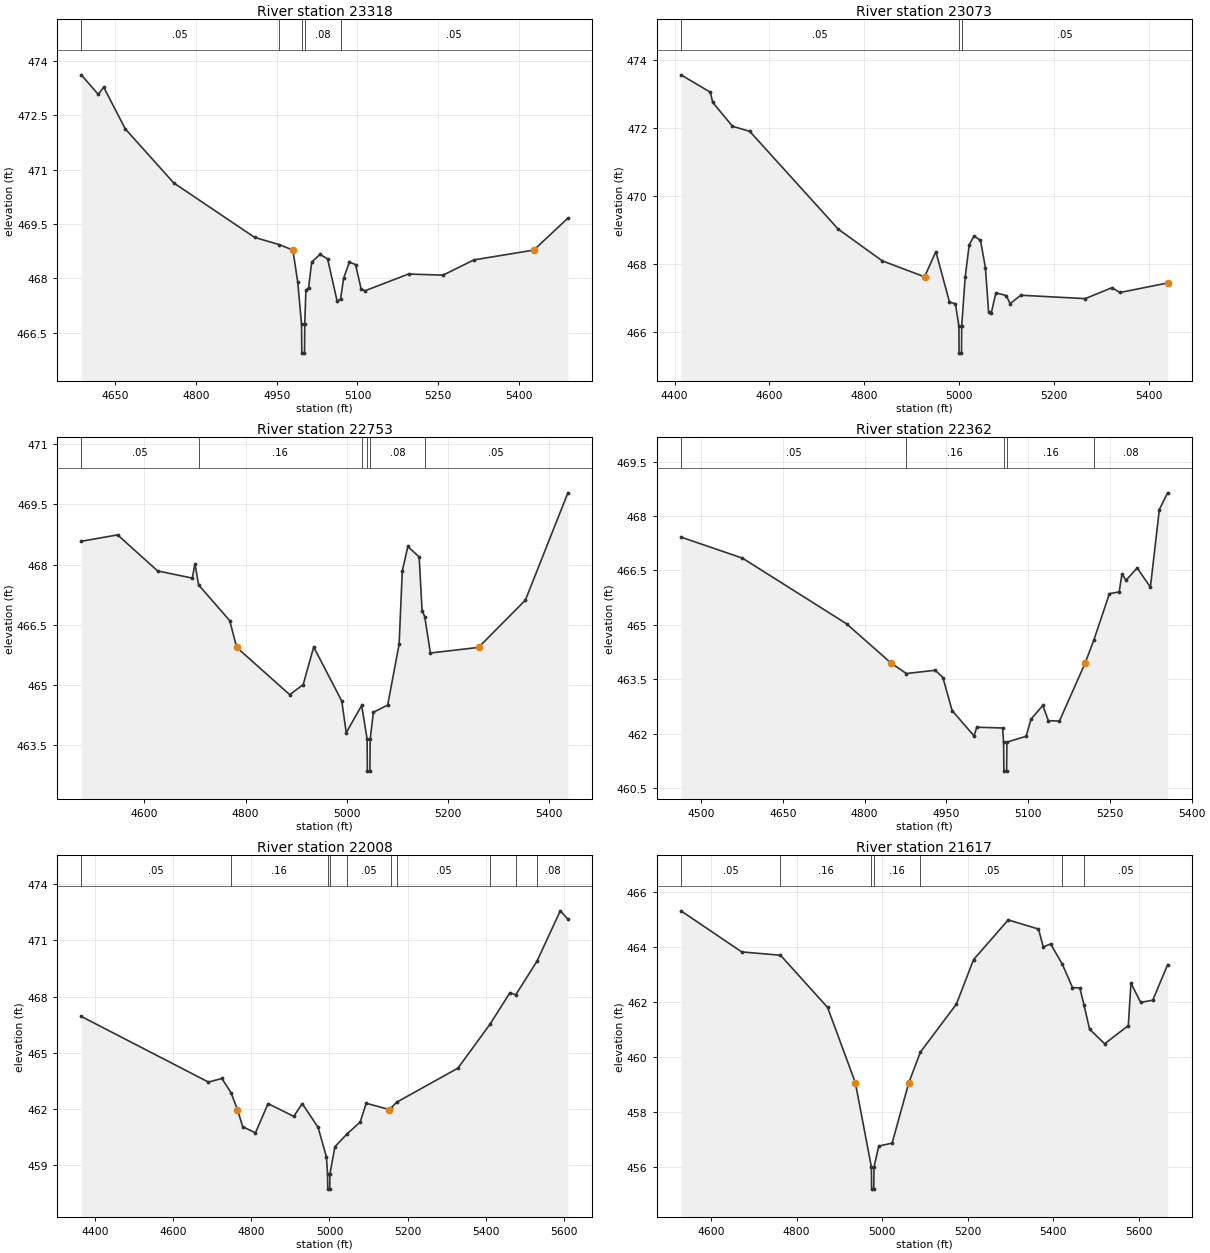
Type RM Length L Ch R = 1,23318,245,245,245
BEGIN DESCRIPTION:
Mapping XS a031f925
END DESCRIPTION:
XS GIS Cut Line= 3
      2827423.96      7012836.62      2827450.72      7012408.35
      2827257.41      7011974.14
#Sta/Elev= 30
  4586.7  473.61  4618.4  473.07  4628.4  473.27  4668.5  472.12  4758.7  470.63
  4908.9  469.13  4954.8  468.93  4980.0  468.78  4989.1  467.89  4996.1  466.74
  4996.6  465.94  5001.6  465.94  5002.1  466.74  5004.2  467.68  5009.2  467.74
  5015.0  468.45  5030.4  468.66  5044.5  468.54  5062.3  467.37  5068.7  467.43
  5074.2  468.00  5085.1  468.45  5096.5  468.38  5107.0  467.70  5114.2  467.66
  5194.9  468.12  5259.1  468.09  5316.6  468.51  5427.7  468.78  5491.1  469.66
#Mann=5,-1,0
  4586.7    0.05       0  4954.8    0.08       0  4996.1    0.07       0
  5002.1    0.08       0  5068.7    0.05       0
Bank Sta=4980,5427.7
Exp/Cntr=0.3,0.1

Type RM Length L Ch R = 1,23073,320,320,320
BEGIN DESCRIPTION:
Mapping XS 96172f62
END DESCRIPTION:
XS GIS Cut Line= 3
      2827554.56      7013007.18      2827702.37      7012403.67
      2827527.03      7012038.53
#Sta/Elev= 30
  4413.5  473.56  4475.4  473.05  4480.5  472.75  4522.1  472.05  4558.6  471.90
  4745.2  469.03  4837.9  468.10  4927.2  467.63  4951.1  468.37  4979.8  466.89
  4992.3  466.84  4999.6  466.19  5000.1  465.39  5005.1  465.39  5005.6  466.19
  5012.9  467.62  5021.4  468.57  5031.6  468.83  5045.2  468.70  5055.6  467.90
  5062.3  466.60  5067.8  466.56  5077.7  467.16  5099.9  467.08  5107.5  466.84
  5130.2  467.09  5266.1  466.99  5322.4  467.31  5339.5  467.17  5439.9  467.45
#Mann=3,-1,0
  4413.5    0.05       0  4999.6    0.04       0  5005.6    0.05       0
Bank Sta=4927.2,5439.9
Exp/Cntr=0.3,0.1

Type RM Length L Ch R = 1,22753,391,391,391
BEGIN DESCRIPTION:
Mapping XS 5185f28b
END DESCRIPTION:
XS GIS Cut Line= 3
      2827850.44      7013037.70      2827981.37      7012563.98
      2828184.19      7012139.86
#Sta/Elev= 30
  4475.2  468.58  4547.0  468.74  4626.1  467.84  4694.7  467.66  4699.9  468.02
  4707.1  467.49  4768.5  466.60  4782.4  465.93  4887.1  464.75  4913.7  465.00
  4934.5  465.94  4990.0  464.59  4998.8  463.80  5029.3  464.48  5040.1  463.64
  5040.6  462.84  5045.6  462.84  5046.1  463.64  5052.5  464.31  5080.7  464.49
  5103.3  466.01  5109.6  467.84  5120.5  468.45  5142.9  468.19  5148.7  466.85
  5153.9  466.70  5165.1  465.79  5260.3  465.93  5352.8  467.11  5436.8  469.79
#Mann=6,-1,0
  4475.2    0.05       0  4707.1    0.16       0  5029.3    0.08       0
  5040.1    0.07       0  5046.1    0.08       0  5153.9    0.05       0
Bank Sta=4782.4,5260.3
Exp/Cntr=0.3,0.1

Type RM Length L Ch R = 1,22362,354,354,354
BEGIN DESCRIPTION:
Mapping XS c18e8fc7
END DESCRIPTION:
XS GIS Cut Line= 3
      2827939.39      7013178.79      2828282.30      7012818.52
      2828356.09      7012430.04
#Sta/Elev= 30
  4463.1  467.42  4575.9  466.84  4766.9  465.03  4848.4  463.95  4876.5  463.66
  4929.5  463.75  4943.6  463.55  4960.5  462.64  5000.7  461.94  5005.8  462.18
  5053.0  462.16  5055.0  461.77  5055.5  460.97  5060.5  460.97  5061.0  461.77
  5096.4  461.93  5105.2  462.40  5126.9  462.78  5137.1  462.36  5157.4  462.35
  5204.6  463.95  5220.7  464.59  5249.1  465.86  5267.0  465.91  5272.1  466.40
  5279.6  466.23  5300.0  466.57  5324.3  466.04  5340.7  468.18  5355.9  468.64
#Mann=5,-1,0
  4463.1    0.05       0  4876.5    0.16       0  5055.0    0.07       0
  5061.0    0.16       0  5220.7    0.08       0
Bank Sta=4848.4,5204.6
Exp/Cntr=0.3,0.1

Type RM Length L Ch R = 1,22008,391,391,391
BEGIN DESCRIPTION:
Mapping XS 156e23c9
END DESCRIPTION:
XS GIS Cut Line= 3
      2827965.44      7013289.45      2828514.50      7013055.07
      2828842.21      7012497.31
#Sta/Elev= 30
  4365.6  466.95  4690.6  463.45  4725.1  463.64  4748.2  462.89  4764.9  461.98
  4778.3  461.07  4810.9  460.74  4843.1  462.30  4908.8  461.62  4930.5  462.30
  4971.0  461.03  4992.4  459.45  4995.2  458.54  4995.7  457.74  5000.7  457.74
  5001.2  458.54  5013.9  460.00  5044.4  460.67  5078.7  461.32  5094.0  462.32
  5153.5  461.98  5156.4  462.05  5172.2  462.38  5328.4  464.19  5410.3  466.53
  5461.3  468.21  5476.2  468.10  5530.1  469.88  5590.1  472.58  5609.5  472.14
#Mann=10,-1,0
  4365.6    0.05       0  4748.2    0.16       0  4995.2    0.07       0
  5001.2    0.16       0  5044.4    0.05       0  5156.4    0.08       0
  5172.2    0.05       0  5410.3    0.08       0  5476.2    0.05       0
  5530.1    0.08       0
Bank Sta=4764.9,5153.5
Exp/Cntr=0.3,0.1

Type RM Length L Ch R = 1,21617,305,305,305
BEGIN DESCRIPTION:
Mapping XS 64b09535
END DESCRIPTION:
XS GIS Cut Line= 4
      2828100.40      7013528.60      2828579.61      7013365.40
      2828857.38      7013236.92      2828996.29      7012941.75
#Sta/Elev= 30
  4529.4  465.30  4671.6  463.81  4762.2  463.69  4872.3  461.80  4937.3  459.07
  4974.9  456.01  4975.4  455.21  4980.4  455.21  4980.9  456.01  4992.1  456.77
  5023.4  456.88  5062.4  459.07  5089.6  460.18  5173.8  461.92  5213.8  463.53
  5295.0  464.97  5365.8  464.64  5377.0  463.99  5394.2  464.10  5421.7  463.36
  5445.3  462.52  5462.6  462.50  5472.5  461.87  5485.3  461.01  5520.6  460.48
  5575.9  461.14  5582.1  462.68  5604.8  461.98  5633.2  462.06  5667.9  463.35
#Mann=7,-1,0
  4529.4    0.05       0  4762.2    0.16       0  4974.9    0.07       0
  4980.9    0.16       0  5089.6    0.05       0  5421.7    0.08       0
  5472.5    0.05       0
Bank Sta=4937.3,5062.4
Exp/Cntr=0.3,0.1

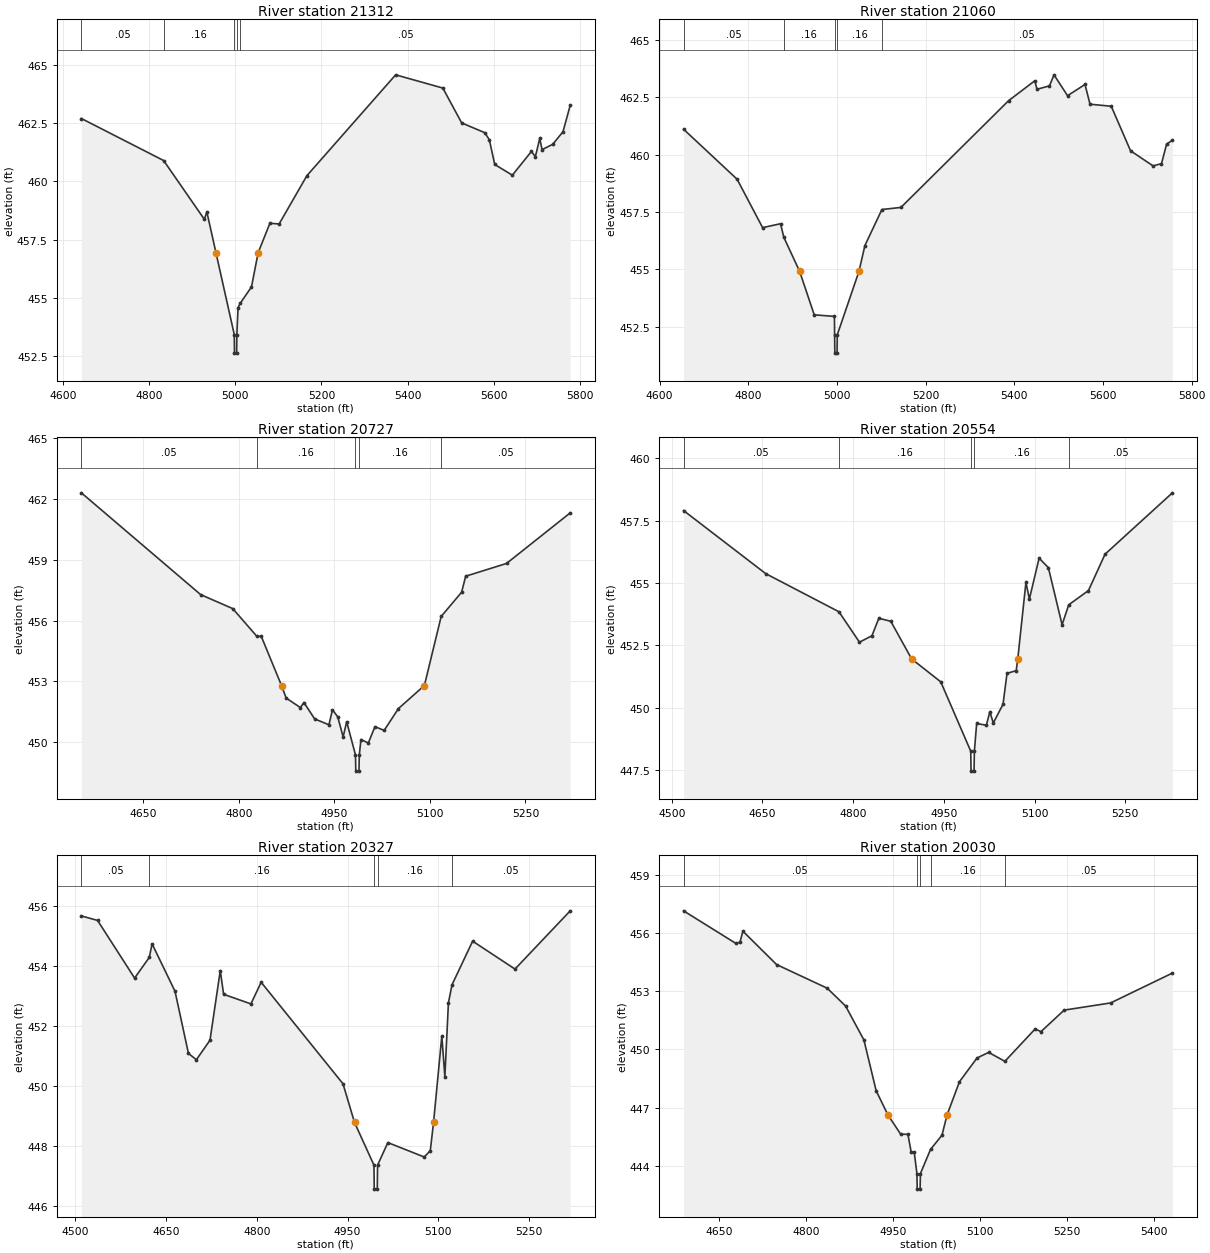
Type RM Length L Ch R = 1,21312,252,252,252
BEGIN DESCRIPTION:
Mapping XS 60fcf193
END DESCRIPTION:
XS GIS Cut Line= 4
      2828378.23      7013837.61      2828666.41      7013667.48
      2828871.27      7013323.73      2829013.41      7012949.32
#Sta/Elev= 30
  4642.5  462.71  4833.6  460.90  4928.1  458.37  4933.9  458.69  4955.1  456.93
  4997.6  453.41  4998.1  452.61  5003.1  452.61  5003.6  453.41  5006.4  454.57
  5012.0  454.77  5037.6  455.46  5053.0  456.93  5080.4  458.20  5101.8  458.17
  5166.3  460.25  5372.4  464.59  5482.0  464.02  5525.7  462.52  5579.2  462.10
  5589.9  461.80  5602.5  460.73  5643.4  460.27  5687.6  461.29  5696.9  461.07
  5707.0  461.85  5712.4  461.37  5737.2  461.60  5761.0  462.14  5777.8  463.28
#Mann=5,-1,0
  4642.5    0.05       0  4833.6    0.16       0  4997.6    0.07       0
  5003.6    0.16       0  5012.0    0.05       0
Bank Sta=4955.1,5053
Exp/Cntr=0.3,0.1

Type RM Length L Ch R = 1,21060,333,333,333
BEGIN DESCRIPTION:
Mapping XS eb6cf5df
END DESCRIPTION:
XS GIS Cut Line= 3
      2828794.89      7014111.89      2828881.69      7013778.59
      2829013.63      7013032.08
#Sta/Elev= 30
  4654.1  461.11  4774.9  458.93  4832.4  456.82  4872.9  456.99  4880.2  456.40
  4916.0  454.91  4948.8  453.02  4994.4  452.95  4994.8  452.15  4995.3  451.35
  5000.3  451.35  5000.8  452.15  5049.7  454.91  5063.1  456.04  5101.5  457.61
  5144.3  457.70  5387.0  462.35  5446.2  463.22  5451.3  462.85  5479.4  463.00
  5489.6  463.48  5520.1  462.57  5559.5  463.06  5570.8  462.20  5618.7  462.11
  5662.2  460.17  5713.0  459.51  5732.0  459.61  5743.5  460.46  5756.6  460.63
#Mann=5,-1,0
  4654.1    0.05       0  4880.2    0.16       0  4994.8    0.07       0
  5000.8    0.16       0  5101.5    0.05       0
Bank Sta=4916,5049.7
Exp/Cntr=0.3,0.1

Type RM Length L Ch R = 1,20727,173,173,173
BEGIN DESCRIPTION:
Penson Spring Branch 39.0
END DESCRIPTION:
XS GIS Cut Line= 3
      2828974.98      7014075.04      2829175.00      7013675.00
      2828975.01      7013425.02
#Sta/Elev= 30
  4553.0  462.31  4740.3  457.28  4790.6  456.59  4828.5  455.22  4835.4  455.22
  4867.2  452.79  4874.5  452.17  4896.8  451.70  4902.4  451.95  4919.2  451.14
  4941.6  450.85  4947.2  451.59  4955.5  451.24  4963.9  450.25  4969.5  451.00
  4983.3  449.36  4983.8  448.56  4988.8  448.56  4989.3  449.36  4991.9  450.12
  5003.5  449.95  5013.9  450.76  5028.3  450.57  5050.7  451.65  5091.5  452.79
  5117.8  456.20  5149.9  457.40  5156.3  458.19  5220.4  458.82  5320.4  461.32
#Mann=5,-1,0
  4553.0    0.05       0  4828.5    0.16       0  4983.3    0.07       0
  4989.3    0.16       0  5117.8    0.05       0
Bank Sta=4867.2,5091.5
Exp/Cntr=0.3,0.1

Type RM Length L Ch R = 1,20554,227,227,227
BEGIN DESCRIPTION:
Penson Spring Branch 38.0
END DESCRIPTION:
XS GIS Cut Line= 3
      2829218.49      7014076.37      2829338.29      7013623.21
      2829175.01      7013325.01
#Sta/Elev= 30
  4519.4  457.91  4655.3  455.38  4776.5  453.85  4810.4  452.63  4831.1  452.89
  4842.5  453.59  4862.2  453.47  4896.7  451.96  4944.9  451.04  4994.5  448.26
  4995.0  447.46  5000.0  447.46  5000.5  448.26  5004.3  449.37  5020.3  449.30
  5026.1  449.84  5031.8  449.39  5047.9  450.14  5054.5  451.38  5069.7  451.49
  5072.3  451.96  5085.8  455.03  5091.5  454.36  5107.6  456.00  5122.9  455.62
  5145.6  453.33  5156.6  454.13  5189.2  454.70  5216.7  456.16  5328.1  458.62
#Mann=5,-1,0
  4519.4    0.05       0  4776.5    0.16       0  4994.5    0.07       0
  5000.5    0.16       0  5156.6    0.05       0
Bank Sta=4896.7,5072.3
Exp/Cntr=0.3,0.1

Type RM Length L Ch R = 1,20327,297,297,297
BEGIN DESCRIPTION:
Mapping XS 2768c016
END DESCRIPTION:
XS GIS Cut Line= 3
      2829338.30      7014084.12      2829544.02      7013662.27
      2829533.60      7013323.76
#Sta/Elev= 30
  4510.1  455.66  4536.9  455.51  4598.1  453.59  4622.4  454.28  4627.0  454.73
  4664.9  453.15  4687.1  451.08  4700.2  450.87  4722.7  451.52  4739.7  453.84
  4745.2  453.05  4790.3  452.73  4807.3  453.45  4942.5  450.07  4961.6  448.78
  4993.7  447.36  4994.2  446.56  4999.2  446.56  4999.7  447.36  5016.7  448.11
  5076.8  447.63  5086.8  447.84  5092.2  448.78  5105.9  451.66  5110.9  450.30
  5116.8  452.77  5122.8  453.37  5156.8  454.82  5226.8  453.89  5318.1  455.83
#Mann=5,-1,0
  4510.1    0.05       0  4622.4    0.16       0  4993.7    0.07       0
  4999.7    0.16       0  5122.8    0.05       0
Bank Sta=4961.6,5092.2
Exp/Cntr=0.3,0.1

Type RM Length L Ch R = 1,20030,288,288,288
BEGIN DESCRIPTION:
Mapping XS b41825c1
END DESCRIPTION:
XS GIS Cut Line= 4
      2829658.59      7014170.11      2829783.60      7013795.08
      2829799.22      7013657.06      2829783.67      7013348.57
#Sta/Elev= 30
  4588.2  457.15  4677.9  455.48  4685.4  455.52  4690.6  456.10  4748.6  454.38
  4836.0  453.16  4867.7  452.24  4899.3  450.49  4920.4  447.87  4940.8  446.62
  4962.5  445.64  4975.2  445.62  4980.9  444.69  4986.1  444.69  4990.7  443.60
  4991.2  442.80  4996.2  442.80  4996.7  443.60  5014.2  444.85  5033.9  445.58
  5042.6  446.62  5064.1  448.34  5094.3  449.56  5114.4  449.85  5142.4  449.39
  5194.6  451.06  5204.6  450.92  5244.6  452.03  5324.7  452.40  5431.3  453.94
#Mann=5,-1,0
  4588.2    0.05       0  4990.7    0.03       0  4996.7    0.05       0
  5014.2    0.16       0  5142.4    0.05       0
Bank Sta=4940.8,5042.6
Exp/Cntr=0.3,0.1

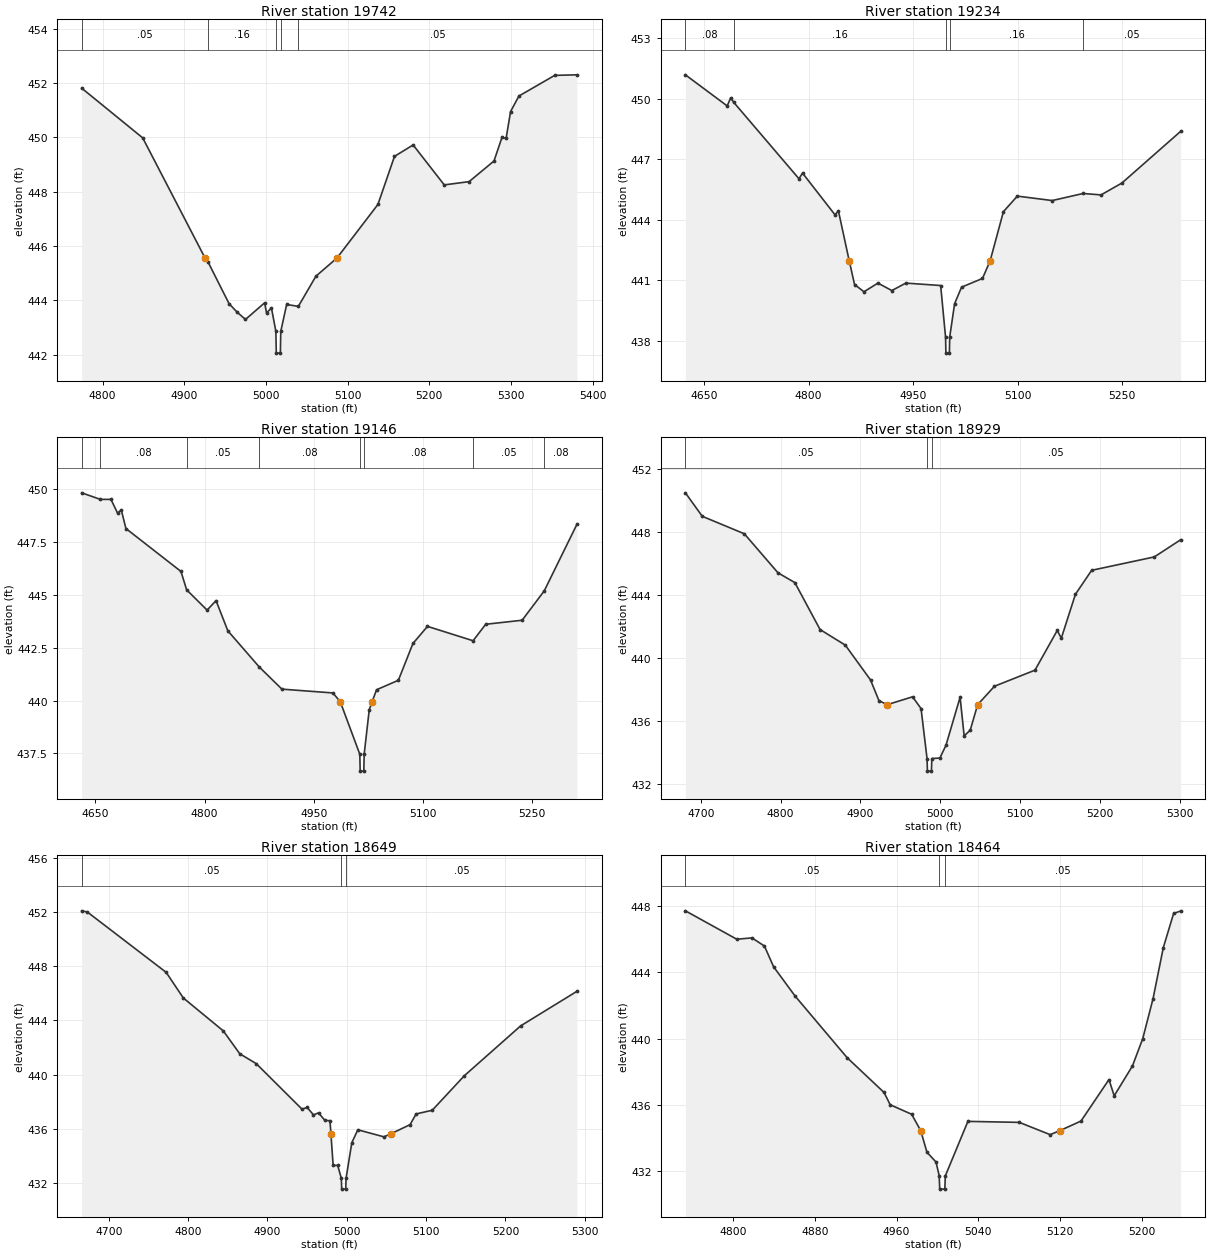
Type RM Length L Ch R = 1,19742,508,508,508
BEGIN DESCRIPTION:
Penson Spring Branch 37.0
END DESCRIPTION:
XS GIS Cut Line= 3
      2830025.00      7013975.03      2830040.32      7013748.47
      2829975.00      7013375.01
#Sta/Elev= 30
  4774.5  451.81  4849.2  449.98  4925.5  445.56  4929.4  445.40  4954.9  443.88
  4965.0  443.56  4975.0  443.30  4998.4  443.91  5000.8  443.54  5006.8  443.72
  5012.2  442.86  5012.7  442.06  5017.7  442.06  5018.2  442.86  5025.4  443.85
  5039.7  443.78  5061.2  444.89  5087.0  445.56  5137.1  447.53  5157.4  449.30
  5180.2  449.72  5218.3  448.25  5248.7  448.37  5279.2  449.13  5289.0  450.00
  5294.0  449.96  5299.5  450.95  5309.7  451.52  5353.5  452.28  5380.7  452.30
#Mann=5,-1,0
  4774.5    0.05       0  4929.4    0.16       0  5012.2    0.07       0
  5018.2    0.16       0  5039.7    0.05       0
Bank Sta=4925.5,5087
Exp/Cntr=0.3,0.1

Type RM Length L Ch R = 1,19234,88,88,88
BEGIN DESCRIPTION:
Penson Spring Branch 36.0
END DESCRIPTION:
XS GIS Cut Line= 3
      2830491.94      7013956.56      2830445.06      7013716.96
      2830447.66      7013250.81
#Sta/Elev= 30
  4623.4  451.19  4683.3  449.65  4688.4  450.05  4692.4  449.84  4786.3  446.04
  4791.4  446.32  4837.8  444.26  4842.9  444.44  4858.3  441.98  4866.0  440.80
  4879.5  440.44  4899.5  440.87  4919.5  440.50  4939.5  440.87  4989.5  440.75
  4996.5  438.20  4997.0  437.40  5002.0  437.40  5002.5  438.20  5009.5  439.85
  5019.5  440.67  5049.5  441.10  5060.5  441.98  5079.5  444.41  5099.5  445.18
  5149.5  444.96  5193.8  445.31  5219.5  445.24  5249.5  445.83  5333.7  448.39
#Mann=5,-1,0
  4623.4    0.08       0  4692.4    0.16       0  4996.5    0.07       0
  5002.5    0.16       0  5193.8    0.05       0
Bank Sta=4858.3,5060.5
Exp/Cntr=0.3,0.1

Type RM Length L Ch R = 1,19146,217,217,217
BEGIN DESCRIPTION:
Mapping XS 127b82db
END DESCRIPTION:
XS GIS Cut Line= 3
      2830583.08      7013953.94      2830533.60      7013758.62
      2830533.60      7013279.71
#Sta/Elev= 30
  4631.2  449.83  4656.8  449.52  4671.4  449.52  4680.5  448.87  4685.6  449.02
  4692.0  448.14  4767.6  446.11  4775.4  445.24  4803.5  444.28  4815.8  444.73
  4832.0  443.30  4875.4  441.58  4906.3  440.54  4976.3  440.36  4986.4  439.95
  5013.3  437.46  5013.8  436.66  5018.8  436.66  5019.3  437.46  5026.3  439.57
  5030.3  439.95  5036.3  440.51  5066.3  440.96  5086.3  442.70  5106.3  443.51
  5168.9  442.83  5186.3  443.61  5236.3  443.80  5266.7  445.19  5311.6  448.34
#Mann=8,-1,0
  4631.2    0.05       0  4656.8    0.08       0  4775.4    0.05       0
  4875.4    0.08       0  5013.3    0.07       0  5019.3    0.08       0
  5168.9    0.05       0  5266.7    0.08       0
Bank Sta=4986.4,5030.3
Exp/Cntr=0.3,0.1

Type RM Length L Ch R = 1,18929,280,280,280
BEGIN DESCRIPTION:
Penson Spring Branch 35.0
END DESCRIPTION:
XS GIS Cut Line= 3
      2830624.99      7013975.03      2830725.00      7013675.00
      2830675.00      7013374.99
#Sta/Elev= 30
  4680.7  450.46  4701.8  448.97  4754.5  447.86  4796.7  445.38  4817.8  444.76
  4849.4  441.78  4881.0  440.79  4912.6  438.58  4923.2  437.26  4933.6  437.01
  4965.3  437.51  4975.9  436.76  4983.4  433.59  4983.9  432.79  4988.9  432.79
  4989.4  433.59  4999.5  433.62  5007.1  434.43  5024.8  437.48  5029.9  435.03
  5037.5  435.39  5046.8  437.01  5067.9  438.18  5118.6  439.20  5146.5  441.72
  5151.6  441.23  5169.3  444.02  5189.6  445.54  5268.1  446.39  5301.1  447.48
#Mann=3,-1,0
  4680.7    0.05       0  4983.4    0.03       0  4989.4    0.05       0
Bank Sta=4933.6,5046.8
Exp/Cntr=0.3,0.1

Type RM Length L Ch R = 1,18649,185,185,185
BEGIN DESCRIPTION:
Penson Spring Branch 34.0
END DESCRIPTION:
XS GIS Cut Line= 3
      2830724.97      7014125.03      2830925.00      7013875.00
      2830974.99      7013575.03
#Sta/Elev= 30
  4665.8  452.08  4673.0  451.99  4772.3  447.54  4793.9  445.65  4844.3  443.22
  4865.1  441.53  4885.9  440.80  4943.6  437.44  4950.0  437.57  4958.0  437.02
  4964.4  437.17  4972.4  436.61  4978.8  436.59  4980.0  435.61  4982.8  433.29
  4988.5  433.29  4993.1  432.34  4993.6  431.54  4998.6  431.54  4999.1  432.34
  5006.3  434.96  5013.9  435.92  5046.8  435.40  5055.1  435.61  5079.8  436.30
  5087.4  437.09  5107.7  437.36  5148.2  439.91  5219.2  443.59  5290.1  446.14
#Mann=3,-1,0
  4665.8    0.05       0  4993.1    0.03       0  4999.1    0.05       0
Bank Sta=4980,5055.1
Exp/Cntr=0.3,0.1

Type RM Length L Ch R = 1,18464,155,155,155
BEGIN DESCRIPTION:
Mapping XS 875faa04
END DESCRIPTION:
XS GIS Cut Line= 3
      2830950.28      7014149.22      2831089.96      7013939.85
      2831118.23      7013708.15
#Sta/Elev= 30
  4753.2  447.69  4803.5  445.98  4818.4  446.06  4830.6  445.57  4839.6  444.32
  4860.6  442.56  4911.7  438.84  4947.8  436.75  4953.8  436.01  4974.8  435.44
  4983.7  434.45  4989.8  433.15  4998.7  432.56  5001.8  431.73  5002.3  430.93
  5007.3  430.93  5007.8  431.73  5029.9  435.01  5080.3  434.95  5110.5  434.21
  5119.9  434.45  5140.7  435.03  5168.1  437.53  5173.2  436.55  5191.1  438.35
  5201.2  440.00  5211.3  442.41  5221.3  445.47  5231.4  447.53  5238.3  447.68
#Mann=3,-1,0
  4753.2    0.05       0  5001.8    0.03       0  5007.8    0.05       0
Bank Sta=4983.7,5119.9
Exp/Cntr=0.3,0.1

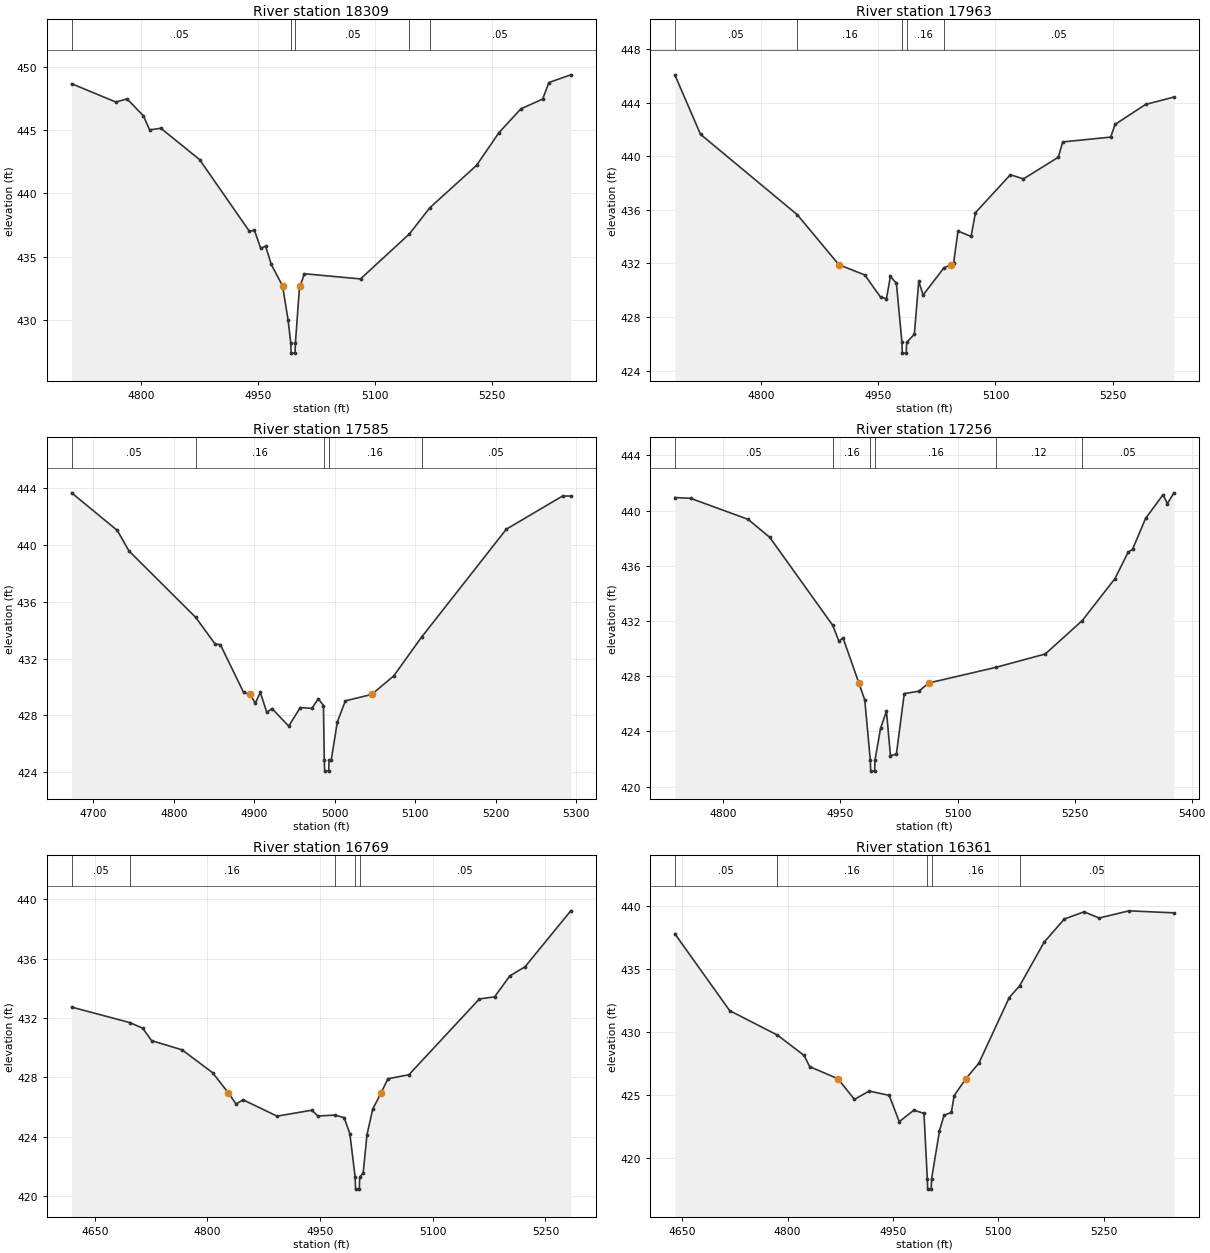
Type RM Length L Ch R = 1,18309,346,346,346
BEGIN DESCRIPTION:
Penson Spring Branch 33.0
END DESCRIPTION:
XS GIS Cut Line= 3
      2830974.99      7014225.01      2831225.00      7014025.00
      2831424.99      7013775.02
#Sta/Elev= 30
  4710.6  448.65  4767.4  447.20  4781.8  447.45  4802.7  446.11  4810.7  445.00
  4825.1  445.13  4874.7  442.66  4938.7  436.99  4945.1  437.08  4953.1  435.66
  4959.5  435.81  4966.7  434.38  4981.2  432.68  4988.3  429.99  4991.7  428.17
  4992.2  427.37  4997.2  427.37  4997.7  428.17  5002.8  432.48  5003.9  432.68
  5009.2  433.64  5081.2  433.23  5144.0  436.79  5170.1  438.85  5230.1  442.20
  5258.9  444.79  5286.9  446.66  5314.9  447.44  5322.9  448.74  5350.9  449.35
#Mann=5,-1,0
  4710.6    0.05       0  4991.7    0.03       0  4997.7    0.05       0
  5144.0    0.16       0  5170.1    0.05       0
Bank Sta=4981.2,5003.9
Exp/Cntr=0.3,0.1

Type RM Length L Ch R = 1,17963,378,378,378
BEGIN DESCRIPTION:
Penson Spring Branch 32.0
END DESCRIPTION:
XS GIS Cut Line= 3
      2831075.01      7014275.00      2831375.00      7014325.00
      2831524.98      7014025.03
#Sta/Elev= 30
  4689.2  446.08  4722.1  441.64  4846.2  435.63  4899.4  431.90  4932.5  431.14
  4952.8  429.48  4960.4  429.37  4965.4  431.03  4973.1  430.51  4980.2  426.10
  4980.7  425.30  4985.7  425.30  4986.2  426.10  4996.1  426.71  5001.7  430.66
  5007.3  429.64  5033.9  431.66  5042.9  431.90  5046.4  432.02  5052.0  434.42
  5068.8  434.01  5074.4  435.79  5119.1  438.62  5135.9  438.31  5180.6  439.93
  5186.2  441.07  5247.7  441.43  5253.3  442.38  5292.4  443.87  5328.7  444.42
#Mann=5,-1,0
  4689.2    0.05       0  4846.2    0.16       0  4980.2    0.07       0
  4986.2    0.16       0  5033.9    0.05       0
Bank Sta=4899.4,5042.9
Exp/Cntr=0.3,0.1

Type RM Length L Ch R = 1,17585,329,329,329
BEGIN DESCRIPTION:
Penson Spring Branch 31.0
END DESCRIPTION:
XS GIS Cut Line= 3
      2831425.03      7014774.97      2831625.00      7014525.00
      2831625.00      7014225.01
#Sta/Elev= 30
  4672.9  443.68  4729.7  441.03  4744.1  439.59  4827.2  434.90  4851.3  433.02
  4857.7  432.99  4886.6  429.62  4894.8  429.48  4901.0  428.86  4907.4  429.62
  4915.4  428.21  4921.8  428.49  4942.6  427.25  4957.0  428.56  4971.4  428.50
  4979.4  429.18  4985.8  428.70  4986.8  424.88  4987.3  424.08  4992.3  424.08
  4992.8  424.88  4995.5  424.88  5003.0  427.54  5013.0  429.03  5045.7  429.48
  5073.0  430.78  5107.6  433.51  5213.0  441.12  5283.0  443.46  5293.0  443.45
#Mann=5,-1,0
  4672.9    0.05       0  4827.2    0.16       0  4986.8    0.07       0
  4992.8    0.16       0  5107.6    0.05       0
Bank Sta=4894.8,5045.7
Exp/Cntr=0.3,0.1

Type RM Length L Ch R = 1,17256,487,487,487
BEGIN DESCRIPTION:
Penson Spring Branch 30.0
END DESCRIPTION:
XS GIS Cut Line= 3
      2831824.99      7014925.05      2831875.00      7014625.00
      2831725.00      7014325.00
#Sta/Elev= 30
  4737.7  440.95  4758.0  440.89  4831.5  439.37  4859.4  438.06  4940.0  431.69
  4948.1  430.52  4953.2  430.79  4973.5  427.51  4981.1  426.28  4988.2  421.92
  4988.7  421.12  4993.7  421.12  4994.2  421.92  5001.3  424.21  5008.9  425.46
  5014.0  422.25  5021.6  422.34  5031.7  426.74  5050.3  426.91  5063.2  427.51
  5149.1  428.64  5212.4  429.61  5259.8  432.03  5301.8  435.08  5318.6  436.99
  5324.2  437.19  5341.0  439.44  5363.3  441.15  5368.9  440.51  5377.3  441.29
#Mann=6,-1,0
  4737.7    0.05       0  4940.0    0.16       0  4988.2    0.07       0
  4994.2    0.16       0  5149.1    0.12       0  5259.8    0.05       0
Bank Sta=4973.5,5063.2
Exp/Cntr=0.3,0.1

Type RM Length L Ch R = 1,16769,408,408,408
BEGIN DESCRIPTION:
Penson Spring Branch 29.0
END DESCRIPTION:
XS GIS Cut Line= 3
      2832113.15      7014979.82      2832175.00      7014625.00
      2832125.00      7014325.01
#Sta/Elev= 30
  4619.3  432.74  4696.5  431.70  4713.9  431.32  4725.7  430.48  4766.3  429.86
  4806.9  428.32  4827.9  426.96  4838.2  426.21  4847.5  426.49  4892.7  425.39
  4938.9  425.79  4947.1  425.40  4969.2  425.46  4982.0  425.29  4989.6  424.21
  4996.7  421.27  4997.2  420.47  5002.2  420.47  5002.7  421.27  5007.4  421.57
  5012.4  424.13  5020.0  425.86  5031.2  426.96  5040.3  427.91  5068.2  428.18
  5162.0  433.29  5182.2  433.43  5202.5  434.84  5222.8  435.46  5283.6  439.23
#Mann=5,-1,0
  4619.3    0.05       0  4696.5    0.16       0  4969.2    0.05       0
  4996.7    0.03       0  5002.7    0.05       0
Bank Sta=4827.9,5031.2
Exp/Cntr=0.3,0.1

Type RM Length L Ch R = 1,16361,400,400,400
BEGIN DESCRIPTION:
Penson Spring Branch 28.0
END DESCRIPTION:
XS GIS Cut Line= 3
      2832075.04      7015124.97      2832375.00      7014875.00
      2832624.98      7014675.01
#Sta/Elev= 30
  4639.4  437.82  4717.5  431.71  4785.4  429.77  4823.5  428.15  4831.4  427.26
  4871.7  426.30  4895.1  424.66  4916.0  425.32  4944.6  424.98  4958.9  422.89
  4979.7  423.80  4994.1  423.55  4998.9  418.33  4999.4  417.53  5004.4  417.53
  5004.9  418.33  5016.2  422.16  5022.7  423.40  5033.1  423.62  5037.1  424.96
  5053.7  426.30  5072.3  427.54  5115.5  432.75  5130.4  433.69  5165.1  437.14
  5193.9  438.99  5222.0  439.56  5243.6  439.07  5286.0  439.64  5350.0  439.48
#Mann=5,-1,0
  4639.4    0.05       0  4785.4    0.16       0  4998.9    0.07       0
  5004.9    0.16       0  5130.4    0.05       0
Bank Sta=4871.7,5053.7
Exp/Cntr=0.3,0.1

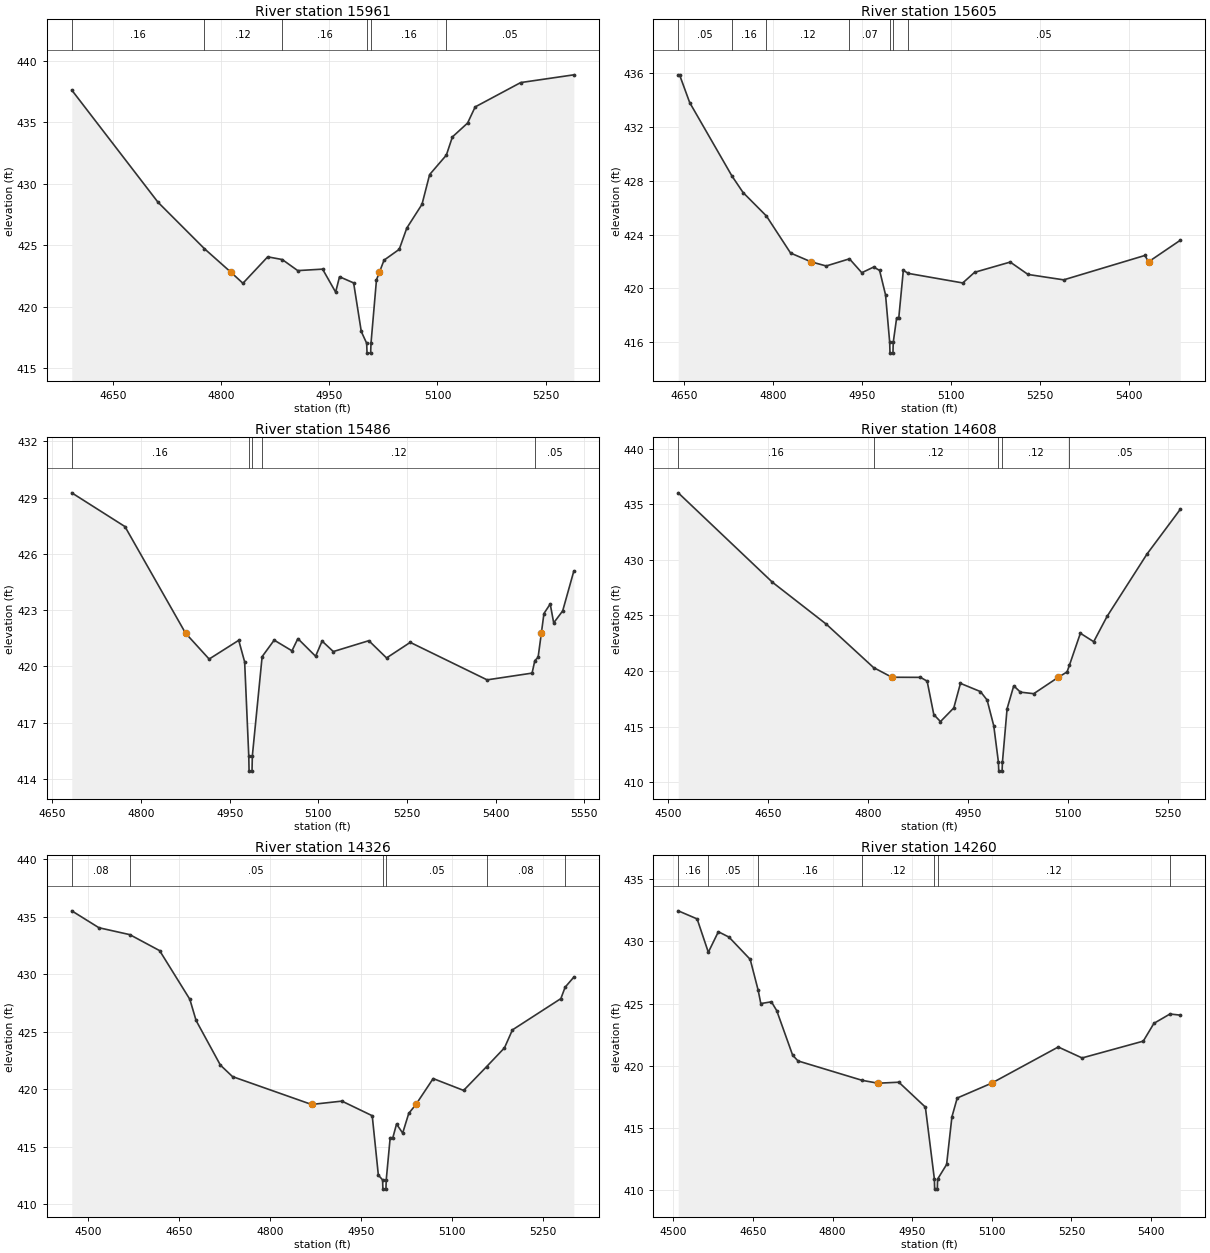
Type RM Length L Ch R = 1,15961,356,356,356
BEGIN DESCRIPTION:
Penson Spring Branch 27.0
END DESCRIPTION:
XS GIS Cut Line= 3
      2832174.98      7015275.01      2832525.00      7015125.00
      2832624.99      7014825.03
#Sta/Elev= 30
  4592.3  437.63  4712.0  428.51  4776.5  424.73  4813.2  422.82  4829.9  421.92
  4864.3  424.07  4884.5  423.85  4906.0  422.95  4940.5  423.07  4958.6  421.20
  4964.0  422.45  4983.6  421.95  4994.2  418.00  5001.7  417.04  5002.2  416.24
  5007.2  416.24  5007.7  417.04  5015.3  422.20  5019.4  422.82  5025.8  423.80
  5046.9  424.68  5057.4  426.41  5078.5  428.34  5089.1  430.76  5112.3  432.34
  5120.7  433.82  5141.8  434.95  5152.3  436.26  5215.5  438.24  5289.3  438.87
#Mann=6,-1,0
  4592.3    0.16       0  4776.5    0.12       0  4884.5    0.16       0
  5001.7    0.07       0  5007.7    0.16       0  5112.3    0.05       0
Bank Sta=4813.2,5019.4
Exp/Cntr=0.3,0.1

Type RM Length L Ch R = 1,15605,119,119,119
BEGIN DESCRIPTION:
Mapping XS 0fd09556
END DESCRIPTION:
XS GIS Cut Line= 3
      2832235.73      7015350.90      2832607.30      7015357.84
      2833081.47      7015371.69
#Sta/Elev= 30
  4640.8  435.86  4643.0  435.86  4660.1  433.80  4731.3  428.35  4750.1  427.12
  4789.4  425.38  4830.1  422.63  4864.5  421.98  4890.1  421.67  4929.3  422.20
  4950.1  421.17  4970.1  421.59  4980.1  421.34  4990.1  419.53  4997.1  416.00
  4997.6  415.20  5002.6  415.20  5003.1  416.00  5008.8  417.81  5012.4  417.81
  5020.1  421.35  5028.3  421.12  5120.2  420.41  5140.2  421.20  5200.2  421.96
  5230.2  421.04  5290.3  420.64  5427.1  422.45  5433.3  421.98  5486.8  423.58
#Mann=7,-1,0
  4640.8    0.05       0  4731.3    0.16       0  4789.4    0.12       0
  4929.3    0.07       0  4997.1    0.07       0  5003.1    0.07       0
  5028.3    0.05       0
Bank Sta=4864.5,5433.3
Exp/Cntr=0.3,0.1

Type RM Length L Ch R = 1,15486,878,878,878
BEGIN DESCRIPTION:
Mapping XS 73981e27
END DESCRIPTION:
XS GIS Cut Line= 5
      2832350.34      7015555.77      2832461.46      7015472.43
      2833010.07      7015448.12      2833096.88      7015448.12
      2833120.58      7015377.02
#Sta/Elev= 30
  4682.8  429.26  4772.8  427.46  4875.4  421.77  4915.3  420.39  4965.4  421.39
  4975.4  420.24  4982.4  415.21  4982.9  414.41  4987.9  414.41  4988.4  415.21
  5005.0  420.52  5025.4  421.40  5055.5  420.83  5065.5  421.48  5095.5  420.54
  5106.5  421.35  5125.5  420.79  5185.6  421.37  5215.6  420.45  5255.7  421.28
  5385.8  419.28  5461.9  419.64  5466.6  420.31  5472.1  420.48  5477.6  421.77
  5482.0  422.82  5492.6  423.33  5498.5  422.32  5513.7  422.96  5532.6  425.09
#Mann=5,-1,0
  4682.8    0.16       0  4982.4    0.07       0  4988.4    0.16       0
  5005.0    0.12       0  5466.6    0.05       0
Bank Sta=4875.4,5477.6
Exp/Cntr=0.3,0.1

Type RM Length L Ch R = 1,14608,282,282,282
BEGIN DESCRIPTION:
Penson Spring Branch 24.0
END DESCRIPTION:
XS GIS Cut Line= 3
      2833125.00      7016025.01      2833175.00      7015675.00
      2833175.00      7015274.97
#Sta/Elev= 30
  4515.3  436.04  4656.7  427.99  4737.5  424.22  4808.5  420.31  4836.0  419.44
  4878.9  419.43  4888.9  419.09  4898.9  416.08  4908.9  415.45  4928.9  416.68
  4938.9  418.89  4968.9  418.15  4978.9  417.39  4988.9  415.07  4995.9  411.79
  4996.4  410.99  5001.4  410.99  5001.9  411.79  5008.9  416.61  5018.9  418.67
  5028.9  418.10  5048.9  417.96  5085.8  419.44  5098.9  419.92  5102.5  420.53
  5118.9  423.40  5138.9  422.64  5158.9  424.91  5218.9  430.53  5268.9  434.56
#Mann=5,-1,0
  4515.3    0.16       0  4808.5    0.12       0  4995.9    0.07       0
  5001.9    0.12       0  5102.5    0.05       0
Bank Sta=4836,5085.8
Exp/Cntr=0.3,0.1

Type RM Length L Ch R = 1,14326,66,66,66
BEGIN DESCRIPTION:
Mapping XS 6dec72a1
END DESCRIPTION:
XS GIS Cut Line= 3
      2833318.24      7016029.68      2833349.48      7015501.07
      2833318.24      7015204.24
#Sta/Elev= 30
  4473.2  435.52  4518.0  434.05  4568.9  433.45  4618.1  432.06  4667.9  427.83
  4678.2  425.99  4718.3  422.11  4738.3  421.11  4868.6  418.69  4918.7  418.98
  4968.7  417.71  4978.8  412.55  4985.8  412.13  4986.3  411.33  4991.3  411.33
  4991.8  412.13  4998.3  415.80  5002.7  415.80  5008.8  416.99  5018.9  416.20
  5028.9  417.91  5040.8  418.69  5069.2  420.94  5119.4  419.91  5157.4  421.98
  5186.8  423.61  5199.9  425.17  5279.8  427.89  5286.8  428.88  5301.2  429.76
#Mann=6,-1,0
  4473.2    0.08       0  4568.9    0.05       0  4985.8    0.04       0
  4991.8    0.05       0  5157.4    0.08       0  5286.8    0.05       0
Bank Sta=4868.6,5040.8
Exp/Cntr=0.3,0.1

Type RM Length L Ch R = 1,14260,464,464,464
BEGIN DESCRIPTION:
Mapping XS 359292cb
END DESCRIPTION:
XS GIS Cut Line= 3
      2833406.78      7015990.62      2833414.59      7015498.47
      2833440.63      7015045.33
#Sta/Elev= 30
  4509.0  432.45  4544.6  431.80  4565.7  429.12  4584.6  430.77  4604.6  430.34
  4644.6  428.55  4659.5  426.09  4664.6  425.00  4684.6  425.14  4694.6  424.43
  4724.6  420.85  4734.7  420.39  4855.6  418.83  4885.4  418.60  4924.7  418.68
  4974.7  416.68  4991.7  410.89  4992.2  410.09  4997.2  410.09  4997.7  410.89
  5014.7  412.07  5024.7  415.89  5034.7  417.41  5099.4  418.60  5225.1  421.51
  5270.0  420.63  5385.3  421.98  5405.4  423.41  5435.6  424.16  5455.1  424.07
#Mann=7,-1,0
  4509.0    0.16       0  4565.7    0.05       0  4659.5    0.16       0
  4855.6    0.12       0  4991.7    0.07       0  4997.7    0.12       0
  5435.6    0.16       0
Bank Sta=4885.4,5099.4
Exp/Cntr=0.3,0.1