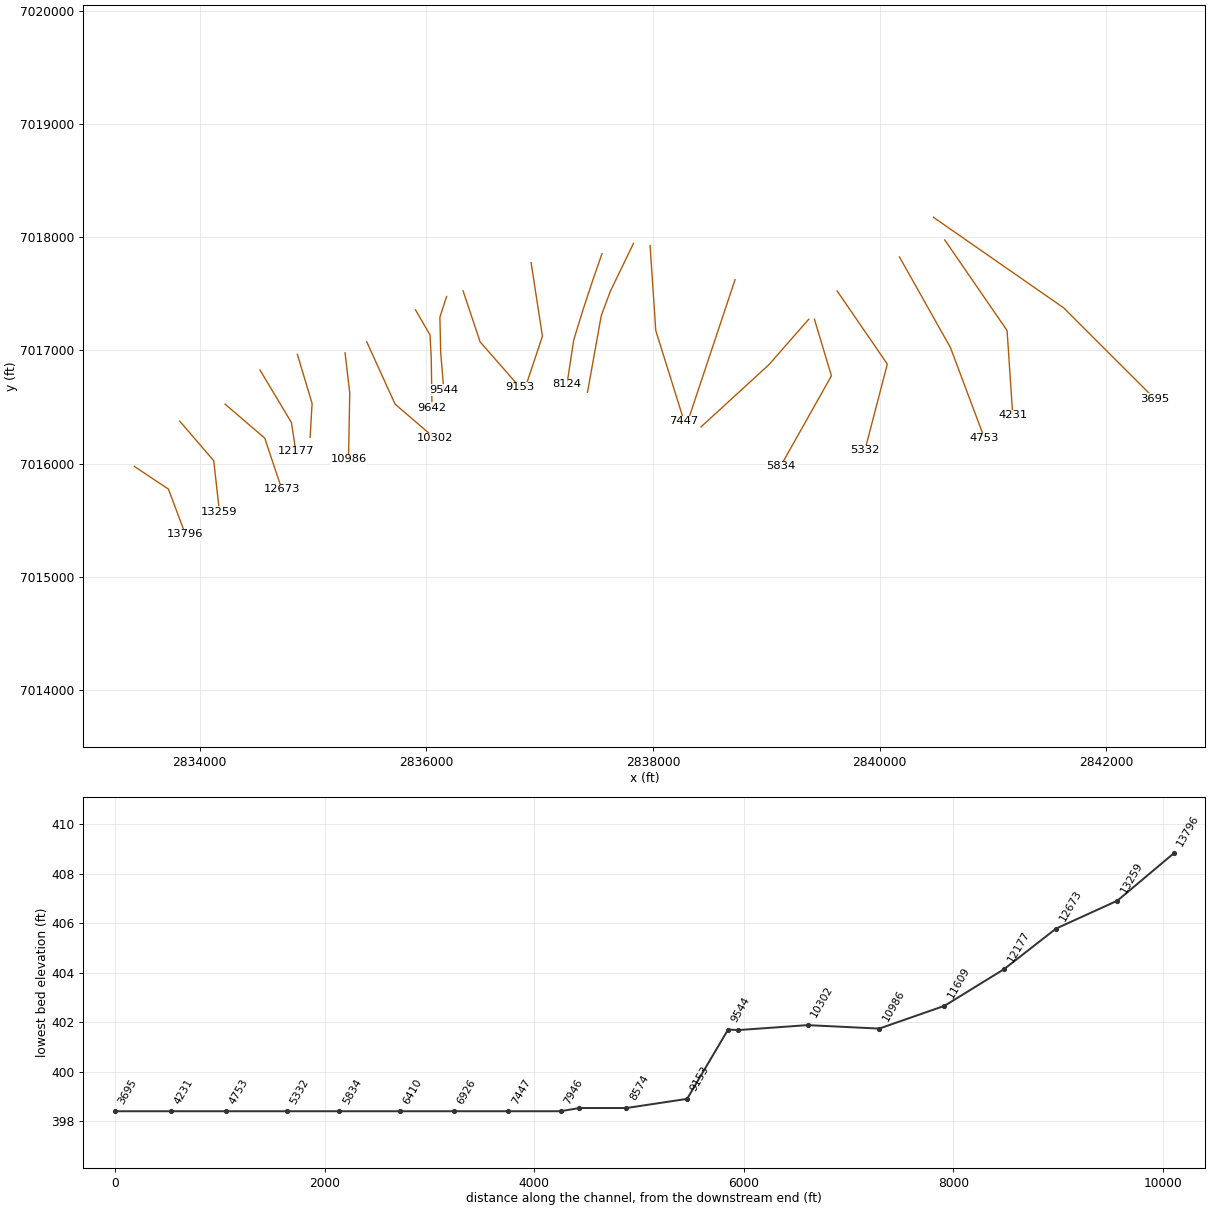
HEC-RAS study Penson Spring Branch.prj: Penson Spring Branch Base Level Engineering

--- Penson Spring Branch.g01 (geometry) --- (continued)

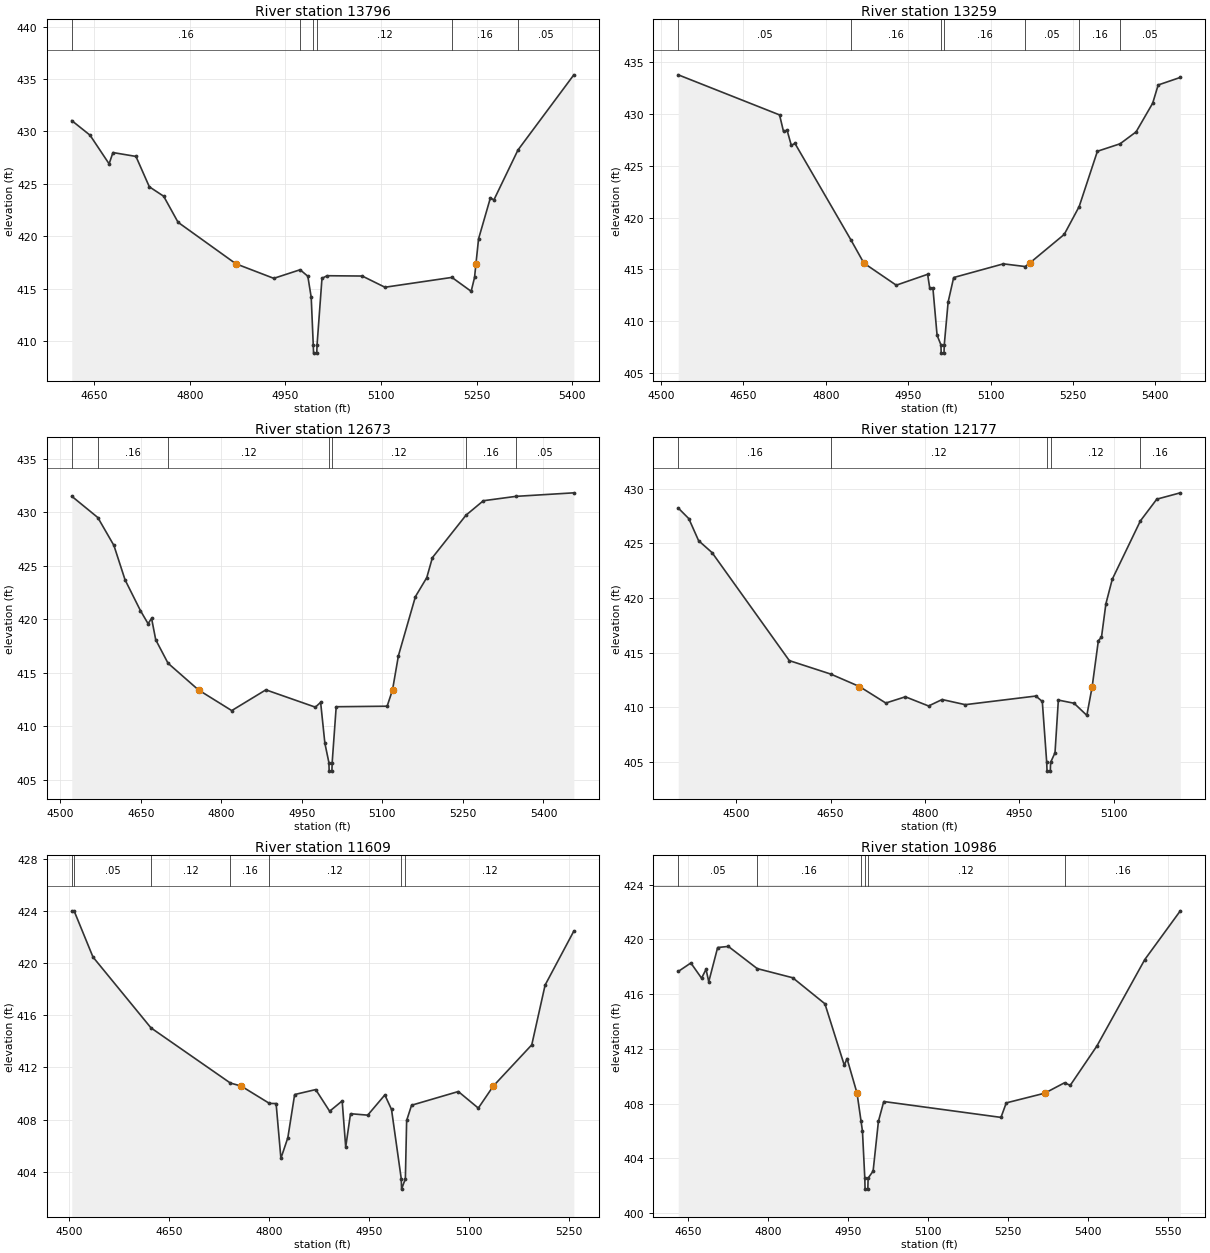
Type RM Length L Ch R = 1,13796,537,537,537
BEGIN DESCRIPTION:
Penson Spring Branch 22.0
END DESCRIPTION:
XS GIS Cut Line= 3
      2833424.98      7015975.01      2833725.00      7015775.00
      2833875.01      7015374.98
#Sta/Elev= 30
  4614.9  431.03  4643.5  429.64  4673.5  426.90  4679.5  427.98  4715.6  427.61
  4736.6  424.71  4759.1  423.81  4781.7  421.32  4872.4  417.36  4931.9  415.97
  4973.2  416.79  4985.3  416.17  4990.6  414.16  4993.8  409.63  4994.3  408.83
  4999.3  408.83  4999.8  409.63  5007.5  415.97  5015.5  416.22  5070.7  416.19
  5106.3  415.12  5211.4  416.06  5241.6  414.73  5246.9  416.06  5249.1  417.36
  5253.2  419.74  5271.8  423.66  5277.2  423.45  5315.0  428.22  5402.7  435.40
#Mann=6,-1,0
  4614.9    0.16       0  4973.2    0.12       0  4993.8    0.07       0
  4999.8    0.12       0  5211.4    0.16       0  5315.0    0.05       0
Bank Sta=4872.4,5249.1
Exp/Cntr=0.3,0.1

Type RM Length L Ch R = 1,13259,586,586,586
BEGIN DESCRIPTION:
Penson Spring Branch 21.0
END DESCRIPTION:
XS GIS Cut Line= 3
      2833824.98      7016375.02      2834125.00      7016025.00
      2834175.00      7015574.97
#Sta/Elev= 30
  4531.6  433.79  4716.0  429.92  4723.2  428.32  4729.7  428.44  4737.4  426.98
  4744.0  427.17  4845.8  417.86  4869.5  415.61  4928.4  413.48  4985.5  414.53
  4989.3  413.21  4995.1  413.21  5002.7  408.65  5009.7  407.72  5010.2  406.92
  5015.3  406.92  5015.8  407.72  5022.8  411.85  5032.9  414.22  5123.4  415.54
  5163.1  415.28  5171.2  415.61  5234.1  418.38  5261.3  421.07  5294.5  426.41
  5335.7  427.13  5364.9  428.28  5395.1  431.05  5405.1  432.81  5445.4  433.54
#Mann=7,-1,0
  4531.6    0.05       0  4845.8    0.16       0  5009.7    0.07       0
  5015.8    0.16       0  5163.1    0.05       0  5261.3    0.16       0
  5335.7    0.05       0
Bank Sta=4869.5,5171.2
Exp/Cntr=0.3,0.1

Type RM Length L Ch R = 1,12673,496,496,496
BEGIN DESCRIPTION:
Penson Spring Branch 20.0
END DESCRIPTION:
XS GIS Cut Line= 3
      2834225.00      7016525.00      2834575.00      7016225.00
      2834725.00      7015775.01
#Sta/Elev= 30
  4521.3  431.49  4569.8  429.50  4599.8  426.89  4620.6  423.67  4649.2  420.80
  4663.4  419.58  4670.0  420.07  4677.7  418.07  4700.6  415.88  4757.4  413.38
  4819.3  411.45  4882.9  413.39  4975.1  411.77  4984.9  412.22  4992.8  408.40
  5000.3  406.59  5000.8  405.79  5005.9  405.79  5006.4  406.59  5013.9  411.81
  5108.8  411.86  5118.8  413.38  5129.8  416.58  5161.5  422.11  5182.6  423.88
  5193.1  425.75  5255.7  429.72  5288.0  431.07  5348.8  431.48  5456.6  431.81
#Mann=7,-1,0
  4521.3    0.05       0  4569.8    0.16       0  4700.6    0.12       0
  5000.3    0.07       0  5006.4    0.12       0  5255.7    0.16       0
  5348.8    0.05       0
Bank Sta=4757.4,5118.8
Exp/Cntr=0.3,0.1

Type RM Length L Ch R = 1,12177,568,568,568
BEGIN DESCRIPTION:
Mapping XS c9ba0231
END DESCRIPTION:
XS GIS Cut Line= 3
      2834532.65      7016826.59      2834810.42      7016362.18
      2834849.19      7016108.06
#Sta/Elev= 30
  4407.9  428.22  4424.7  427.25  4440.3  425.23  4461.7  424.14  4584.5  414.26
  4650.3  413.03  4696.0  411.89  4737.9  410.38  4769.0  410.95  4805.9  410.11
  4827.4  410.70  4864.2  410.23  4976.5  411.02  4986.7  410.52  4993.7  404.95
  4994.2  404.15  4999.4  404.15  4999.9  404.95  5006.9  405.83  5012.2  410.65
  5037.2  410.36  5057.5  409.25  5066.0  411.89  5075.8  416.08  5080.8  416.41
  5087.8  419.46  5097.9  421.70  5142.6  427.04  5168.7  429.03  5206.1  429.61
#Mann=5,-1,0
  4407.9    0.16       0  4650.3    0.12       0  4993.7    0.07       0
  4999.9    0.12       0  5142.6    0.16       0
Bank Sta=4696,5066
Exp/Cntr=0.3,0.1

Type RM Length L Ch R = 1,11609,623,623,623
BEGIN DESCRIPTION:
Mapping XS b3c73512
END DESCRIPTION:
XS GIS Cut Line= 3
      2834862.52      7016965.45      2834992.71      7016531.45
      2834975.35      7016231.96
#Sta/Elev= 30
  4504.4  424.00  4508.1  423.97  4536.2  420.46  4623.2  415.03  4742.3  410.80
  4758.5  410.57  4800.9  409.24  4810.9  409.23  4818.1  405.03  4828.5  406.61
  4838.7  409.92  4870.3  410.30  4891.2  408.64  4910.0  409.43  4915.3  405.89
  4922.5  408.45  4948.3  408.34  4974.0  409.89  4984.0  408.78  4998.6  403.47
  4999.1  402.67  5004.8  403.47  5006.7  407.93  5014.1  409.10  5084.2  410.15
  5114.2  408.88  5136.7  410.57  5194.4  413.73  5214.4  418.31  5257.5  422.45
#Mann=7,-1,0
  4504.4    0.16       0  4508.1    0.05       0  4623.2    0.12       0
  4742.3    0.16       0  4800.9    0.12       0  4998.6    0.07       0
  5004.8    0.12       0
Bank Sta=4758.5,5136.7
Exp/Cntr=0.3,0.1

Type RM Length L Ch R = 1,10986,684,684,684
BEGIN DESCRIPTION:
Penson Spring Branch 19.0
END DESCRIPTION:
XS GIS Cut Line= 3
      2835283.51      7016978.50      2835325.00      7016625.00
      2835313.93      7016038.33
#Sta/Elev= 30
  4631.0  417.65  4654.7  418.27  4674.8  417.16  4683.2  417.81  4688.3  416.90
  4705.0  419.40  4725.1  419.48  4779.3  417.86  4846.0  417.19  4906.4  415.29
  4942.8  410.80  4947.9  411.29  4966.7  408.76  4974.3  406.70  4976.9  405.99
  4981.3  402.55  4981.8  401.75  4987.0  401.75  4987.5  402.55  4996.9  403.07
  5006.9  406.71  5016.9  408.15  5237.0  406.99  5246.9  408.05  5319.3  408.76
  5356.3  409.52  5367.0  409.33  5417.0  412.20  5507.0  418.52  5573.7  422.08
#Mann=6,-1,0
  4631.0    0.05       0  4779.3    0.16       0  4974.3    0.12       0
  4981.3    0.07       0  4987.5    0.12       0  5356.3    0.16       0
Bank Sta=4966.7,5319.3
Exp/Cntr=0.3,0.1

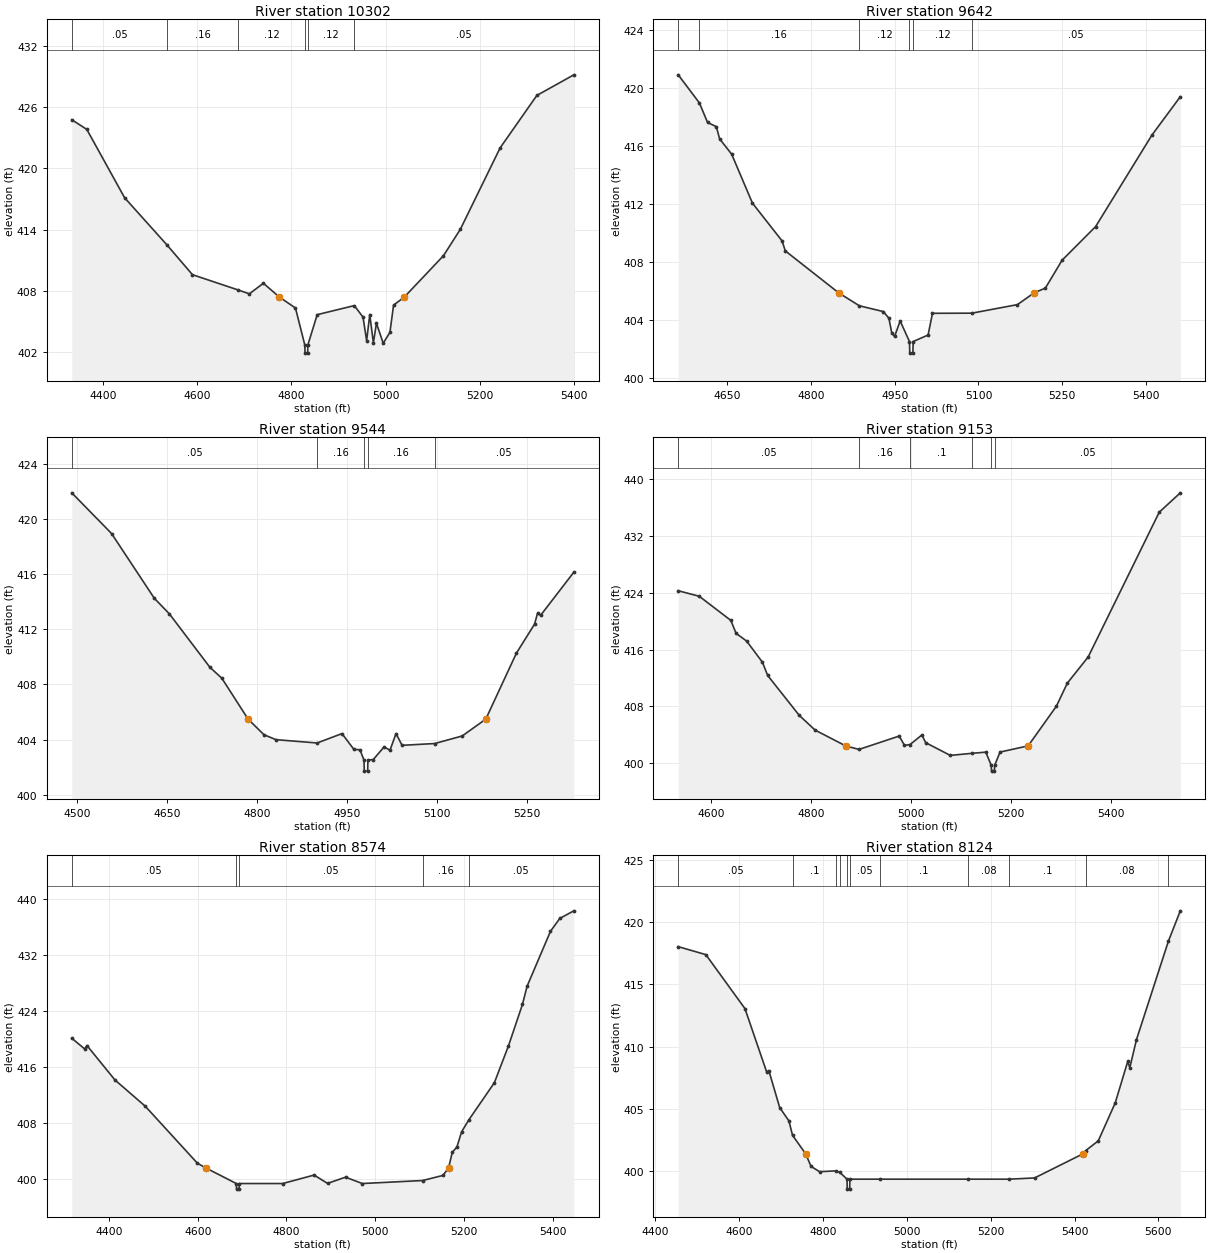
Type RM Length L Ch R = 1,10302,660,660,660
BEGIN DESCRIPTION:
Penson Spring Branch 18.0
END DESCRIPTION:
XS GIS Cut Line= 3
      2835474.98      7017075.03      2835725.00      7016525.00
      2836075.02      7016224.98
#Sta/Elev= 30
  4333.9  424.77  4365.8  423.82  4446.0  417.12  4535.8  412.50  4589.9  409.58
  4687.6  408.07  4710.7  407.70  4740.4  408.74  4774.3  407.39  4808.5  406.31
  4828.3  402.69  4828.8  401.89  4834.3  401.89  4834.8  402.69  4854.6  405.66
  4933.3  406.55  4951.8  405.42  4959.5  403.11  4966.1  405.67  4973.8  402.90
  4980.3  404.82  4994.6  402.86  5008.9  403.92  5016.6  406.59  5039.5  407.39
  5122.5  411.44  5158.2  414.02  5242.7  422.01  5320.6  427.15  5399.1  429.17
#Mann=6,-1,0
  4333.9    0.05       0  4535.8    0.16       0  4687.6    0.12       0
  4828.3    0.03       0  4834.8    0.12       0  4933.3    0.05       0
Bank Sta=4774.3,5039.5
Exp/Cntr=0.3,0.1

Type RM Length L Ch R = 1,9642,98,98,98
BEGIN DESCRIPTION:
Mapping XS 214b74b1
END DESCRIPTION:
XS GIS Cut Line= 4
      2835905.05      7017357.82      2836033.51      7017135.62
      2836043.93      7016934.23      2836050.87      7016493.31
#Sta/Elev= 30
  4562.2  420.91  4600.1  418.97  4614.7  417.62  4630.5  417.33  4636.3  416.49
  4657.9  415.43  4695.1  412.05  4748.2  409.44  4754.0  408.75  4849.7  405.85
  4886.6  404.96  4929.6  404.56  4939.5  404.10  4944.6  403.10  4949.7  402.84
  4959.7  403.91  4976.4  402.49  4976.9  401.69  4982.5  401.69  4983.0  402.49
  5009.7  402.94  5017.6  404.44  5088.1  404.45  5169.8  405.04  5199.5  405.85
  5219.8  406.18  5249.8  408.11  5309.8  410.43  5410.5  416.74  5461.5  419.40
#Mann=6,-1,0
  4562.2    0.05       0  4600.1    0.16       0  4886.6    0.12       0
  4976.4    0.07       0  4983.0    0.12       0  5088.1    0.05       0
Bank Sta=4849.7,5199.5
Exp/Cntr=0.3,0.1

Type RM Length L Ch R = 1,9544,391,391,391
BEGIN DESCRIPTION:
Mapping XS 69b7f9da
END DESCRIPTION:
XS GIS Cut Line= 4
      2836179.34      7017475.88      2836120.32      7017291.87
      2836127.26      7016982.84      2836155.02      7016649.75
#Sta/Elev= 30
  4491.7  421.88  4558.0  418.93  4629.2  414.24  4654.3  413.11  4721.8  409.24
  4741.8  408.44  4785.5  405.48  4811.9  404.35  4831.9  403.99  4900.6  403.75
  4941.9  404.43  4961.9  403.28  4971.9  403.26  4978.6  402.51  4979.1  401.71
  4984.7  401.71  4985.2  402.51  4994.1  402.55  5012.0  403.46  5022.0  403.23
  5032.0  404.43  5042.1  403.58  5096.5  403.71  5142.4  404.26  5181.6  405.48
  5232.7  410.27  5262.8  412.36  5267.8  413.15  5272.9  413.00  5328.3  416.13
#Mann=5,-1,0
  4491.7    0.05       0  4900.6    0.16       0  4978.6    0.07       0
  4985.2    0.16       0  5096.5    0.05       0
Bank Sta=4785.5,5181.6
Exp/Cntr=0.3,0.1

Type RM Length L Ch R = 1,9153,579,579,579
BEGIN DESCRIPTION:
Penson Spring Branch 16.0
END DESCRIPTION:
XS GIS Cut Line= 3
      2836325.00      7017524.99      2836475.00      7017075.00
      2836824.98      7016675.03
#Sta/Elev= 30
  4533.9  424.26  4576.1  423.48  4639.3  420.09  4649.8  418.27  4670.9  417.19
  4702.5  414.22  4713.1  412.35  4776.3  406.75  4808.0  404.68  4869.2  402.46
  4896.0  401.96  4976.6  403.84  4987.1  402.53  4998.3  402.65  5022.0  403.99
  5029.6  402.91  5078.9  401.12  5123.3  401.42  5150.1  401.58  5161.0  399.71
  5161.5  398.91  5167.2  398.91  5167.7  399.71  5178.6  401.59  5234.9  402.46
  5291.5  408.04  5313.4  411.28  5355.1  414.95  5497.5  435.30  5539.7  438.02
#Mann=6,-1,0
  4533.9    0.05       0  4896.0    0.16       0  4998.3     0.1       0
  5123.3    0.05       0  5161.0    0.07       0  5167.7    0.05       0
Bank Sta=4869.2,5234.9
Exp/Cntr=0.3,0.1

Type RM Length L Ch R = 1,8574,450,450,450
BEGIN DESCRIPTION:
Penson Spring Branch 15.0
END DESCRIPTION:
XS GIS Cut Line= 3
      2836925.00      7017775.02      2837025.00      7017125.00
      2836875.00      7016675.01
#Sta/Elev= 30
  4316.0  420.11  4345.1  418.58  4350.2  419.07  4413.4  414.14  4481.7  410.39
  4599.3  402.24  4618.2  401.57  4687.0  399.34  4687.5  398.54  4693.2  398.54
  4693.7  399.34  4791.5  399.34  4862.4  400.55  4892.7  399.36  4933.2  400.25
  4971.1  399.34  5107.0  399.77  5152.9  400.50  5165.5  401.57  5173.9  403.79
  5184.5  404.59  5195.0  406.74  5210.9  408.41  5268.8  413.75  5300.4  418.98
  5332.1  424.94  5342.6  427.54  5395.3  435.39  5416.4  437.24  5448.0  438.32
#Mann=5,-1,0
  4316.0    0.05       0  4687.0   0.033       0  4693.7    0.05       0
  5107.0    0.16       0  5210.9    0.05       0
Bank Sta=4618.2,5165.5
Exp/Cntr=0.3,0.1

Type RM Length L Ch R = 1,8124,178,178,178
BEGIN DESCRIPTION:
Mapping XS 109af196
END DESCRIPTION:
XS GIS Cut Line= 5
      2837550.87      7017854.36      2837467.54      7017614.79
      2837380.73      7017350.90      2837300.87      7017090.48
      2837241.84      7016701.58
#Sta/Elev= 30
  4455.0  418.03  4520.8  417.39  4614.1  413.05  4665.8  407.96  4671.0  408.07
  4696.9  405.10  4719.0  404.02  4727.5  402.87  4759.0  401.37  4771.6  400.37
  4792.1  399.94  4831.3  400.01  4840.5  399.88  4857.5  399.34  4858.0  398.54
  4863.8  398.54  4864.3  399.34  4935.1  399.34  5145.5  399.34  5244.7  399.34
  5304.8  399.44  5419.6  401.37  5426.7  401.64  5456.6  402.42  5497.0  405.47
  5526.8  408.80  5531.8  408.30  5547.6  410.55  5624.0  418.49  5652.2  420.91
#Mann=11,-1,0
  4455.0    0.05       0  4727.5     0.1       0  4831.3    0.15       0
  4840.5    0.05       0  4857.5    0.07       0  4864.3    0.05       0
  4935.1     0.1       0  5145.5    0.08       0  5244.7     0.1       0
  5426.7    0.08       0  5624.0    0.05       0
Bank Sta=4759,5419.6
Exp/Cntr=0.3,0.1

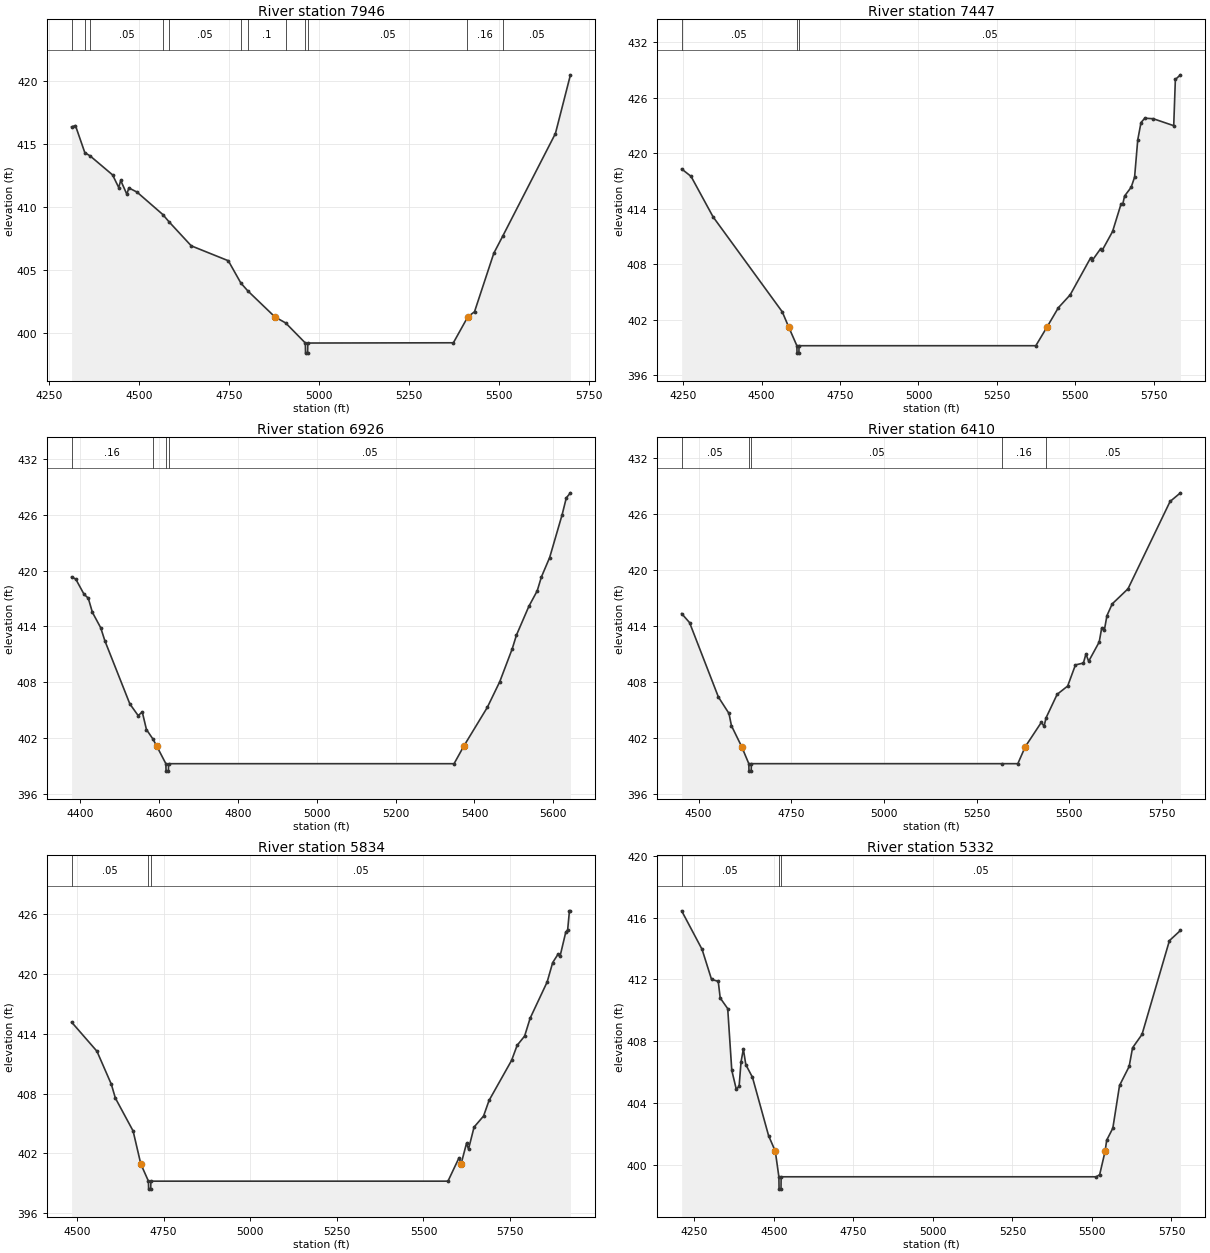
Type RM Length L Ch R = 1,7946,499,499,499
BEGIN DESCRIPTION:
Mapping XS 61f78c62
END DESCRIPTION:
XS GIS Cut Line= 4
      2837828.65      7017944.64      2837623.79      7017521.04
      2837543.93      7017305.76      2837422.52      7016629.32
#Sta/Elev= 30
  4311.7  416.34  4322.4  416.44  4348.5  414.29  4363.0  414.04  4425.7  412.53
  4442.7  411.53  4448.3  412.09  4465.3  411.00  4470.9  411.50  4493.5  411.17
  4565.4  409.39  4582.8  408.81  4644.5  406.91  4747.5  405.73  4782.5  403.96
  4801.8  403.34  4877.1  401.28  4907.1  400.80  4961.8  399.21  4962.3  398.41
  4968.1  398.41  4968.6  399.21  5373.5  399.23  5411.6  401.18  5413.7  401.28
  5432.3  401.69  5486.0  406.33  5511.5  407.72  5657.3  415.81  5699.1  420.46
#Mann=12,-1,0
  4311.7    0.05       0  4348.5    0.08       0  4363.0    0.05       0
  4565.4    0.08       0  4582.8    0.05       0  4782.5    0.08       0
  4801.8     0.1       0  4907.1    0.05       0  4961.8   0.033       0
  4968.6    0.05       0  5411.6    0.16       0  5511.5    0.05       0
Bank Sta=4877.1,5413.7
Exp/Cntr=0.3,0.1

Type RM Length L Ch R = 1,7447,521,521,521
BEGIN DESCRIPTION:
Penson Spring Branch 13.0
END DESCRIPTION:
XS GIS Cut Line= 3
      2837975.00      7017924.95      2838025.00      7017175.00
      2838275.01      7016374.97
#Sta/Elev= 30
  4245.2  418.29  4275.2  417.49  4345.4  413.12  4565.9  402.87  4586.9  401.19
  4612.5  399.21  4613.0  398.41  4618.9  398.41  4619.4  399.21  5374.0  399.21
  5409.0  401.19  5445.8  403.31  5483.5  404.70  5548.4  408.68  5553.7  408.41
  5580.9  409.70  5586.1  409.54  5618.6  411.54  5645.9  414.54  5651.1  414.51
  5656.9  415.37  5677.8  416.31  5688.8  417.41  5698.8  421.42  5709.2  423.30
  5721.3  423.77  5748.5  423.71  5813.5  422.96  5818.7  427.95  5835.0  428.45
#Mann=3,-1,0
  4245.2    0.05       0  4612.5   0.033       0  4619.4    0.05       0
Bank Sta=4586.9,5409
Exp/Cntr=0.3,0.1

Type RM Length L Ch R = 1,6926,516,516,516
BEGIN DESCRIPTION:
Penson Spring Branch 12.0
END DESCRIPTION:
XS GIS Cut Line= 3
      2838725.01      7017625.03      2838525.00      7017025.00
      2838325.01      7016425.04
#Sta/Elev= 30
  4378.5  419.31  4389.1  419.07  4410.2  417.43  4420.7  417.03  4431.2  415.50
  4452.3  413.84  4462.9  412.43  4526.1  405.65  4547.2  404.39  4557.7  404.77
  4568.3  402.88  4584.8  401.86  4594.1  401.12  4617.5  399.21  4618.0  398.41
  4623.9  398.41  4624.4  399.21  5348.3  399.21  5373.2  401.12  5432.6  405.27
  5464.2  408.04  5495.9  411.59  5506.4  413.04  5538.0  416.15  5559.1  417.81
  5569.7  419.30  5590.7  421.40  5622.4  426.02  5632.9  427.82  5643.4  428.36
#Mann=4,-1,0
  4378.5    0.16       0  4584.8    0.05       0  4617.5   0.033       0
  4624.4    0.05       0
Bank Sta=4594.1,5373.2
Exp/Cntr=0.3,0.1

Type RM Length L Ch R = 1,6410,576,576,576
BEGIN DESCRIPTION:
Penson Spring Branch 11.0
END DESCRIPTION:
XS GIS Cut Line= 3
      2839375.03      7017275.03      2839025.00      7016875.00
      2838424.99      7016324.99
#Sta/Elev= 30
  4454.1  415.32  4475.5  414.35  4553.3  406.36  4581.8  404.60  4588.4  403.29
  4616.0  401.04  4635.3  399.21  4635.8  398.41  4641.7  398.41  4642.2  399.21
  5319.5  399.21  5360.9  399.21  5381.1  401.04  5424.4  403.65  5431.8  403.22
  5436.8  404.11  5466.9  406.65  5495.3  407.54  5516.3  409.81  5537.8  410.01
  5544.6  410.98  5552.0  410.20  5580.4  412.27  5587.2  413.79  5594.6  413.61
  5601.3  415.10  5615.5  416.36  5658.1  417.98  5771.5  427.35  5799.6  428.28
#Mann=5,-1,0
  4454.1    0.05       0  4635.3   0.033       0  4642.2    0.05       0
  5319.5    0.16       0  5436.8    0.05       0
Bank Sta=4616,5381.1
Exp/Cntr=0.3,0.1

Type RM Length L Ch R = 1,5834,502,502,502
BEGIN DESCRIPTION:
Penson Spring Branch 10.0
END DESCRIPTION:
XS GIS Cut Line= 3
      2839425.00      7017275.00      2839575.00      7016775.00
      2839125.00      7015974.99
#Sta/Elev= 30
  4484.3  415.18  4557.4  412.26  4599.1  408.93  4610.5  407.56  4661.8  404.25
  4684.0  400.94  4706.1  399.21  4706.6  398.41  4712.6  398.41  4713.1  399.21
  5570.7  399.21  5602.6  401.56  5608.5  400.94  5624.3  403.02  5630.0  402.43
  5646.0  404.64  5673.4  405.75  5689.3  407.32  5754.3  411.34  5770.3  412.85
  5791.9  413.78  5807.9  415.58  5856.9  419.21  5872.9  421.16  5888.8  422.03
  5894.6  421.86  5910.5  424.19  5916.2  424.47  5921.3  426.36  5924.2  426.36
#Mann=3,-1,0
  4484.3    0.05       0  4706.1   0.033       0  4713.1    0.05       0
Bank Sta=4684,5608.5
Exp/Cntr=0.3,0.1

Type RM Length L Ch R = 1,5332,579,579,579
BEGIN DESCRIPTION:
Penson Spring Branch 9.0
END DESCRIPTION:
XS GIS Cut Line= 3
      2839624.97      7017525.04      2840068.23      7016878.68
      2839870.54      7016119.13
#Sta/Elev= 30
  4209.7  416.45  4274.0  413.95  4303.8  412.00  4324.8  411.88  4331.0  410.80
  4354.6  410.11  4367.4  406.11  4381.6  404.88  4390.5  405.08  4396.5  406.66
  4403.8  407.49  4411.5  406.48  4432.4  405.66  4483.2  401.87  4504.2  400.87
  4515.5  399.21  4516.1  398.41  4522.1  398.41  4522.6  399.21  5513.9  399.21
  5524.2  399.35  5541.4  400.87  5546.2  401.58  5565.6  402.36  5586.7  405.13
  5616.9  406.36  5627.6  407.57  5657.4  408.44  5743.6  414.52  5778.3  415.18
#Mann=3,-1,0
  4209.7    0.05       0  4515.5   0.033       0  4522.6    0.05       0
Bank Sta=4504.2,5541.4
Exp/Cntr=0.3,0.1

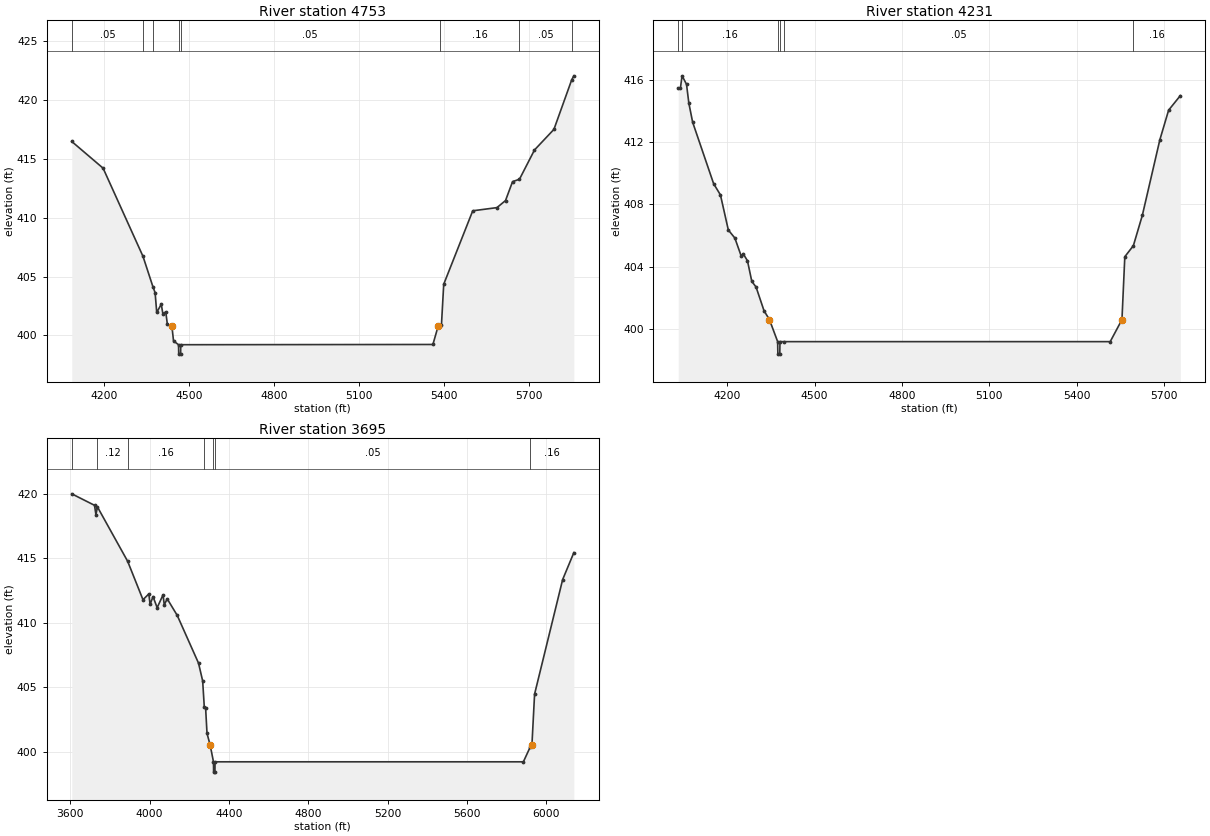
Type RM Length L Ch R = 1,4753,522,522,522
BEGIN DESCRIPTION:
Penson Spring Branch 8.0
END DESCRIPTION:
XS GIS Cut Line= 3
      2840175.00      7017825.00      2840625.00      7017025.00
      2840925.01      7016224.98
#Sta/Elev= 30
  4085.2  416.48  4195.8  414.21  4336.6  406.72  4371.6  404.14  4379.4  403.63
  4385.1  401.95  4401.0  402.65  4406.8  401.85  4417.0  402.00  4422.7  400.93
  4438.8  400.76  4444.4  399.53  4462.1  399.21  4462.8  398.41  4469.4  398.41
  4470.0  399.21  5360.0  399.23  5378.2  400.76  5383.3  400.82  5390.2  400.91
  5398.2  404.35  5500.6  410.59  5586.0  410.86  5616.3  411.46  5641.2  413.07
  5665.5  413.27  5718.6  415.76  5787.2  417.51  5849.8  421.71  5857.5  422.06
#Mann=8,-1,0
  4085.2    0.05       0  4336.6    0.16       0  4371.6    0.05       0
  4462.1   0.033       0  4470.0    0.05       0  5383.3    0.16       0
  5665.5    0.05       0  5849.8    0.08       0
Bank Sta=4438.8,5378.2
Exp/Cntr=0.3,0.1

Type RM Length L Ch R = 1,4231,536,536,536
BEGIN DESCRIPTION:
Penson Spring Branch 7.0
END DESCRIPTION:
XS GIS Cut Line= 3
      2840574.98      7017975.03      2841125.00      7017175.00
      2841175.00      7016425.03
#Sta/Elev= 30
  4032.4  415.47  4039.9  415.46  4045.6  416.24  4060.8  415.70  4068.8  414.49
  4081.8  413.27  4153.8  409.33  4177.2  408.61  4204.3  406.36  4226.6  405.85
  4248.9  404.67  4255.0  404.85  4269.9  404.39  4284.8  403.07  4299.4  402.71
  4326.7  401.19  4345.3  400.62  4373.5  399.21  4374.2  398.41  4380.8  398.41
  4381.4  399.21  4396.6  399.21  5514.4  399.21  5554.7  400.62  5564.5  404.65
  5593.9  405.36  5624.6  407.30  5684.8  412.15  5714.8  414.04  5754.9  414.97
#Mann=6,-1,0
  4032.4    0.05       0  4045.6    0.16       0  4373.5   0.033       0
  4381.4    0.16       0  4396.6    0.05       0  5593.9    0.16       0
Bank Sta=4345.3,5554.7
Exp/Cntr=0.3,0.1

Type RM Length L Ch R = 1,3695,544,544,544
BEGIN DESCRIPTION:
Penson Spring Branch 6.0
END DESCRIPTION:
XS GIS Cut Line= 3
      2840475.03      7018174.98      2841625.00      7017375.00
      2842424.98      7016575.02
#Sta/Elev= 30
  3607.2  419.99  3721.9  419.10  3729.0  418.38  3736.8  418.97  3889.0  414.76
  3966.3  411.78  3996.0  412.23  4002.1  411.41  4017.0  412.02  4037.9  411.16
  4067.6  412.16  4073.7  411.38  4088.5  411.85  4139.2  410.56  4246.5  406.86
  4267.4  405.48  4275.4  403.49  4282.3  403.37  4289.3  401.41  4305.0  400.52
  4321.9  399.21  4322.6  398.41  4329.2  398.41  4329.8  399.21  5884.9  399.21
  5918.2  400.32  5928.0  400.52  5941.4  404.46  6082.9  413.34  6139.4  415.43
#Mann=7,-1,0
  3607.2    0.16       0  3736.8    0.12       0  3889.0    0.16       0
  4275.4    0.05       0  4321.9   0.033       0  4329.8    0.05       0
  5918.2    0.16       0
Bank Sta=4305,5928
Exp/Cntr=0.3,0.1