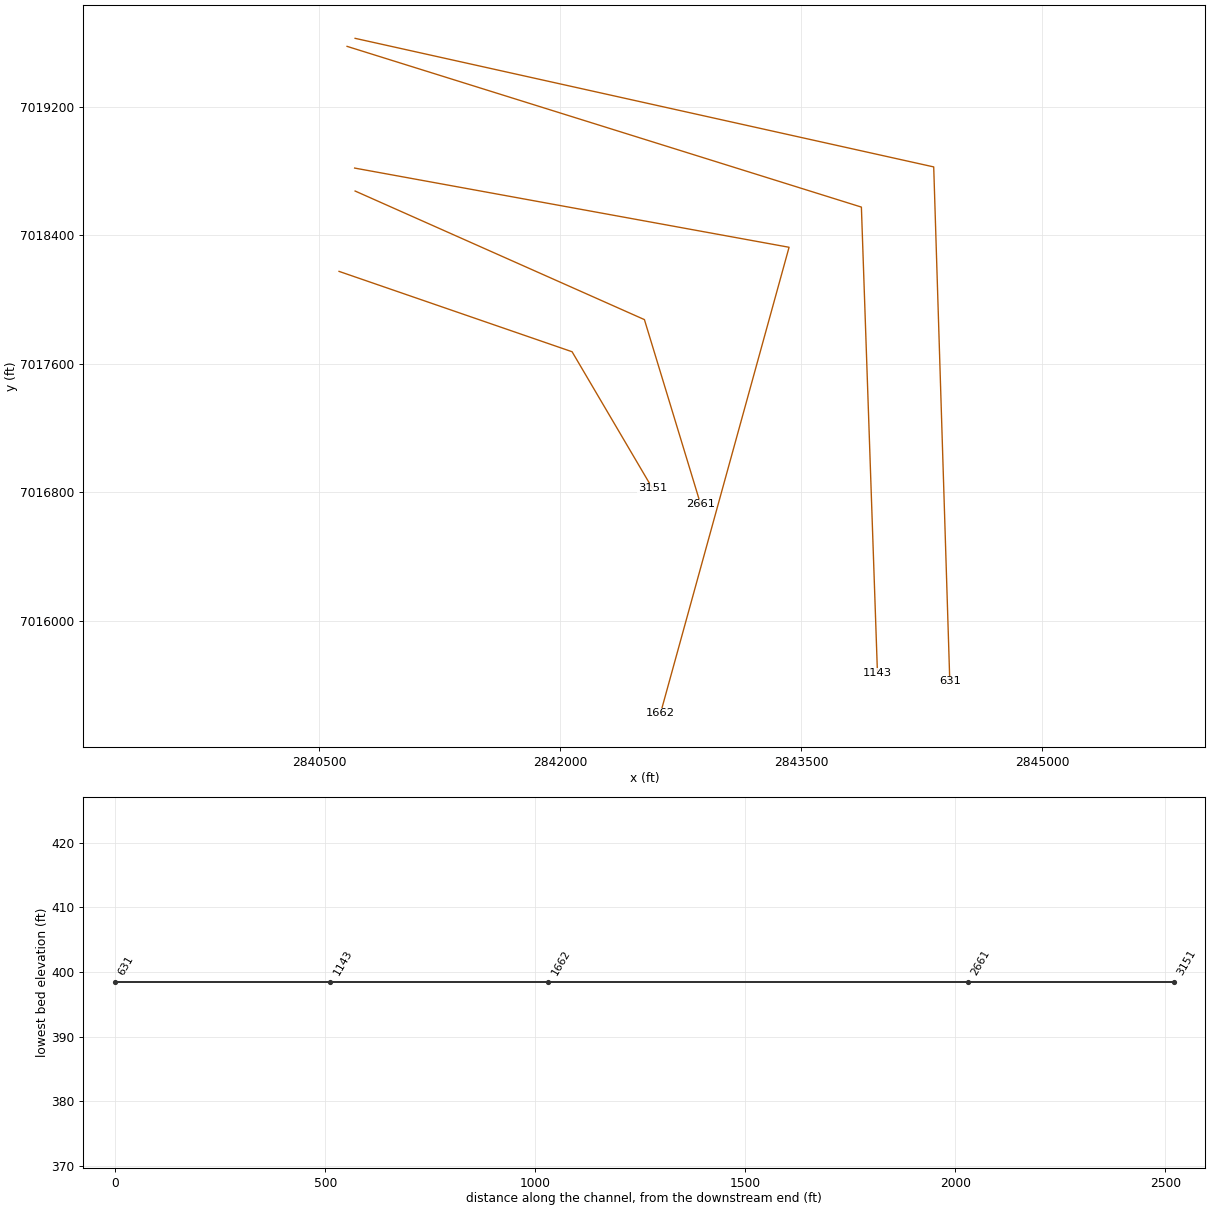
HEC-RAS study Penson Spring Branch.prj: Penson Spring Branch Base Level Engineering

--- Penson Spring Branch.g01 (geometry) --- (continued)

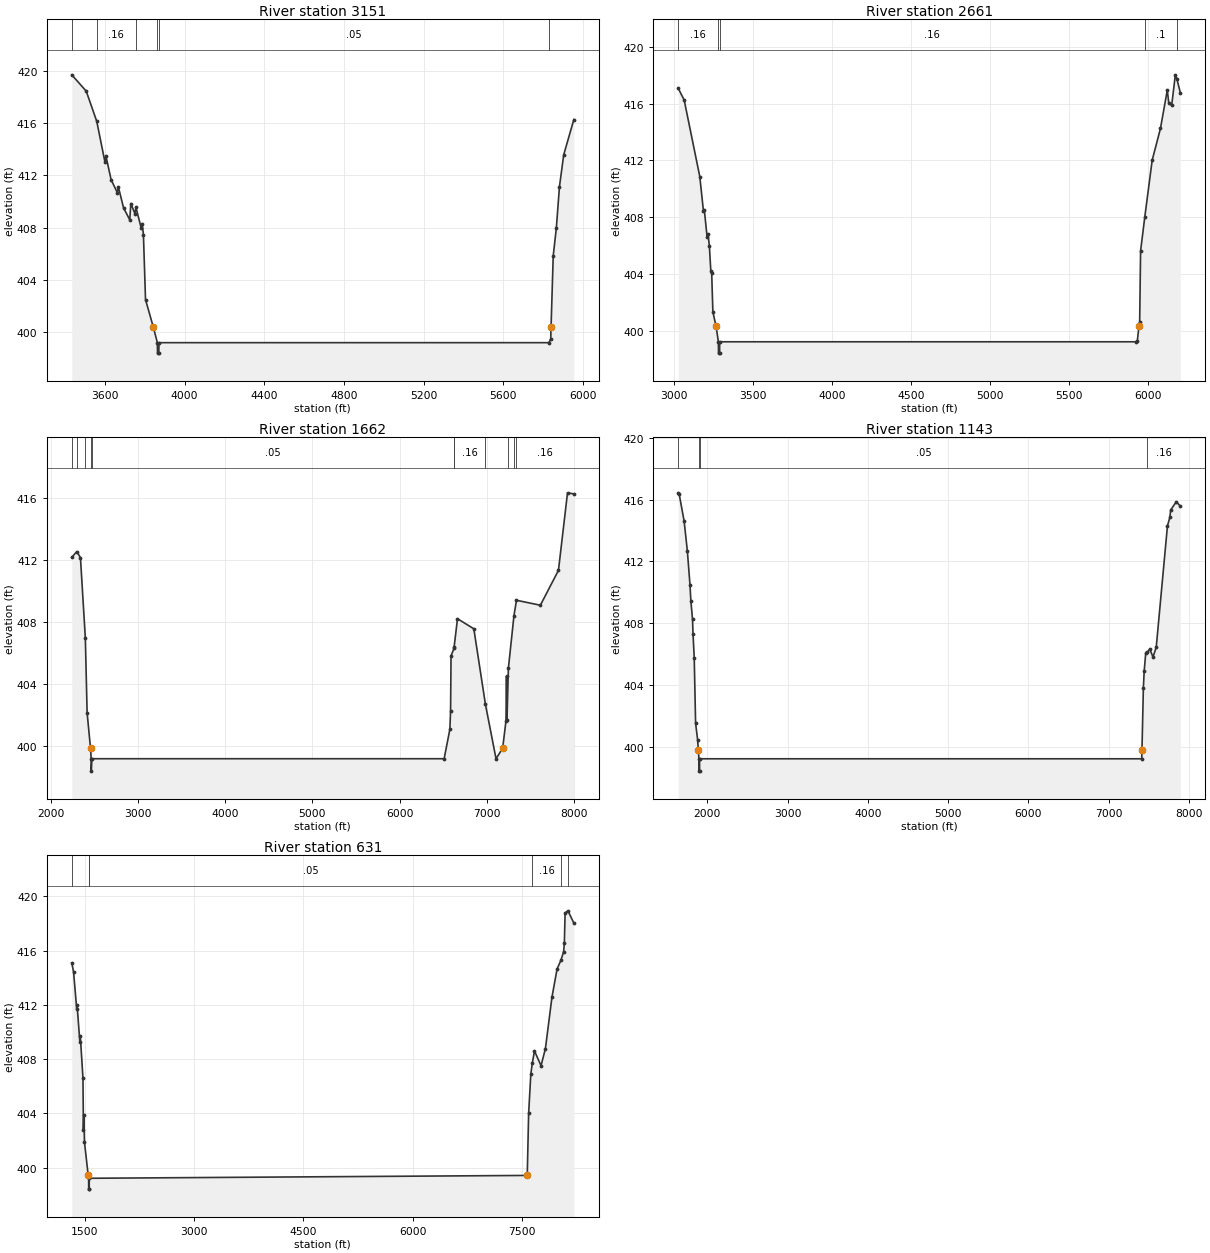
Type RM Length L Ch R = 1,3151,490,490,490
BEGIN DESCRIPTION:
Penson Spring Branch 5.0
END DESCRIPTION:
XS GIS Cut Line= 3
      2840625.04      7018174.99      2842075.00      7017675.00
      2842575.00      7016825.00
#Sta/Elev= 30
  3433.5  419.69  3506.2  418.44  3558.9  416.13  3599.8  413.04  3605.1  413.47
  3631.0  411.67  3662.2  410.68  3667.5  411.11  3693.4  409.52  3724.6  408.60
  3729.9  409.85  3750.5  409.08  3755.7  409.55  3781.7  407.99  3787.0  408.31
  3793.1  407.47  3803.7  402.50  3842.0  400.44  3863.1  399.21  3863.8  398.41
  3870.4  398.41  3871.1  399.21  5828.3  399.21  5837.4  399.49  5839.1  400.44
  5849.9  405.85  5865.5  407.96  5881.2  411.14  5902.6  413.58  5953.4  416.27
#Mann=6,-1,0
  3433.5    0.12       0  3558.9    0.16       0  3755.7    0.05       0
  3863.1   0.033       0  3871.1    0.05       0  5828.3    0.16       0
Bank Sta=3842,5839.1
Exp/Cntr=0.3,0.1

Type RM Length L Ch R = 1,2661,999,999,999
BEGIN DESCRIPTION:
Penson Spring Branch 4.0
END DESCRIPTION:
XS GIS Cut Line= 3
      2840725.05      7018674.98      2842525.00      7017875.00
      2842875.00      7016725.00
#Sta/Elev= 30
  3029.9  417.08  3067.5  416.25  3166.0  410.86  3189.2  408.42  3194.7  408.51
  3212.5  406.57  3217.9  406.81  3226.8  405.94  3235.7  404.20  3241.2  404.06
  3248.7  401.32  3268.8  400.30  3283.6  399.21  3284.3  398.41  3291.1  398.41
  3291.8  399.21  5919.5  399.21  5929.9  399.26  5940.6  400.30  5944.9  400.59
  5950.8  405.62  5977.1  407.99  6024.0  412.01  6076.3  414.25  6119.6  416.96
  6128.5  416.06  6147.2  415.87  6170.3  418.03  6180.2  417.74  6201.7  416.77
#Mann=5,-1,0
  3029.9    0.16       0  3283.6   0.033       0  3291.8    0.16       0
  5977.1     0.1       0  6180.2    0.16       0
Bank Sta=3268.8,5940.6
Exp/Cntr=0.3,0.1

Type RM Length L Ch R = 1,1662,519,519,519
BEGIN DESCRIPTION:
Penson Spring Branch 3.0
END DESCRIPTION:
XS GIS Cut Line= 3
      2840721.99      7018817.82      2843425.00      7018325.00
      2842625.00      7015424.99
#Sta/Elev= 30
  2241.4  412.20  2298.7  412.57  2340.9  412.18  2396.9  407.00  2417.3  402.18
  2456.4  399.88  2463.9  399.21  2464.7  398.41  2472.2  399.21  6510.3  399.21
  6576.1  401.11  6584.2  402.29  6589.4  405.85  6624.2  406.33  6624.5  406.40
  6663.3  408.24  6850.7  407.59  6983.9  402.71  7105.2  399.21  7180.9  399.88
  7219.3  401.65  7225.4  404.53  7230.6  401.69  7247.0  405.05  7310.9  408.44
  7339.6  409.43  7613.5  409.11  7820.9  411.36  7924.7  416.36  7997.3  416.29
#Mann=11,-1,0
  2241.4    0.12       0  2298.7    0.16       0  2396.9    0.05       0
  2463.9   0.033       0  2472.2    0.05       0  6624.2     0.1       0
  6624.5    0.16       0  6983.9    0.05       0  7247.0    0.16       0
  7310.9     0.1       0  7339.6    0.16       0
Bank Sta=2456.4,7180.9
Exp/Cntr=0.3,0.1

Type RM Length L Ch R = 1,1143,512,512,512
BEGIN DESCRIPTION:
Penson Spring Branch 2.0
END DESCRIPTION:
XS GIS Cut Line= 3
      2840674.99      7019575.00      2843875.00      7018575.00
      2843975.00      7015675.04
#Sta/Elev= 30
  1638.7  416.45  1649.2  416.40  1712.0  414.62  1752.4  412.68  1784.9  410.49
  1795.9  409.45  1816.8  408.24  1822.6  407.33  1837.8  405.77  1855.1  401.51
  1879.7  400.46  1889.6  399.76  1896.5  399.21  1897.2  398.41  1904.1  398.41
  1904.8  399.21  7412.8  399.21  7415.4  399.76  7432.8  403.79  7442.8  404.88
  7462.8  406.09  7481.5  406.11  7512.8  406.32  7552.8  405.81  7592.9  406.43
  7732.9  414.31  7763.0  414.86  7773.0  415.34  7843.0  415.87  7893.0  415.59
#Mann=4,-1,0
  1638.7    0.05       0  1896.5   0.033       0  1904.8    0.05       0
  7481.5    0.16       0
Bank Sta=1889.6,7415.4
Exp/Cntr=0.3,0.1

Type RM Length L Ch R = 1,631,0,0,0
BEGIN DESCRIPTION:
Penson Spring Branch 1.0
END DESCRIPTION:
XS GIS Cut Line= 3
      2840724.97      7019625.01      2844325.00      7018825.00
      2844425.00      7015625.01
#Sta/Elev= 30
  1321.4  415.09  1345.8  414.44  1389.3  411.69  1394.4  411.97  1432.8  409.23
  1438.0  409.73  1475.1  406.59  1481.5  402.79  1486.6  403.87  1495.6  401.87
  1547.1  399.42  1552.9  399.21  1553.6  398.41  1560.5  398.41  1561.2  399.21
  7571.5  399.42  7590.5  403.99  7620.5  406.89  7640.9  407.70  7670.5  408.60
  7760.6  407.51  7820.6  408.77  7910.7  412.57  7980.7  414.64  8032.2  415.27
  8070.7  415.91  8080.7  416.57  8090.7  418.77  8130.0  418.93  8210.8  418.03
#Mann=6,-1,0
  1321.4    0.05       0  1552.9   0.033       0  1561.2    0.05       0
  7640.9    0.16       0  8032.2    0.05       0  8130.0    0.08       0
Bank Sta=1547.1,7571.5
Exp/Cntr=0.3,0.1

Chan Stop Cuts=-1