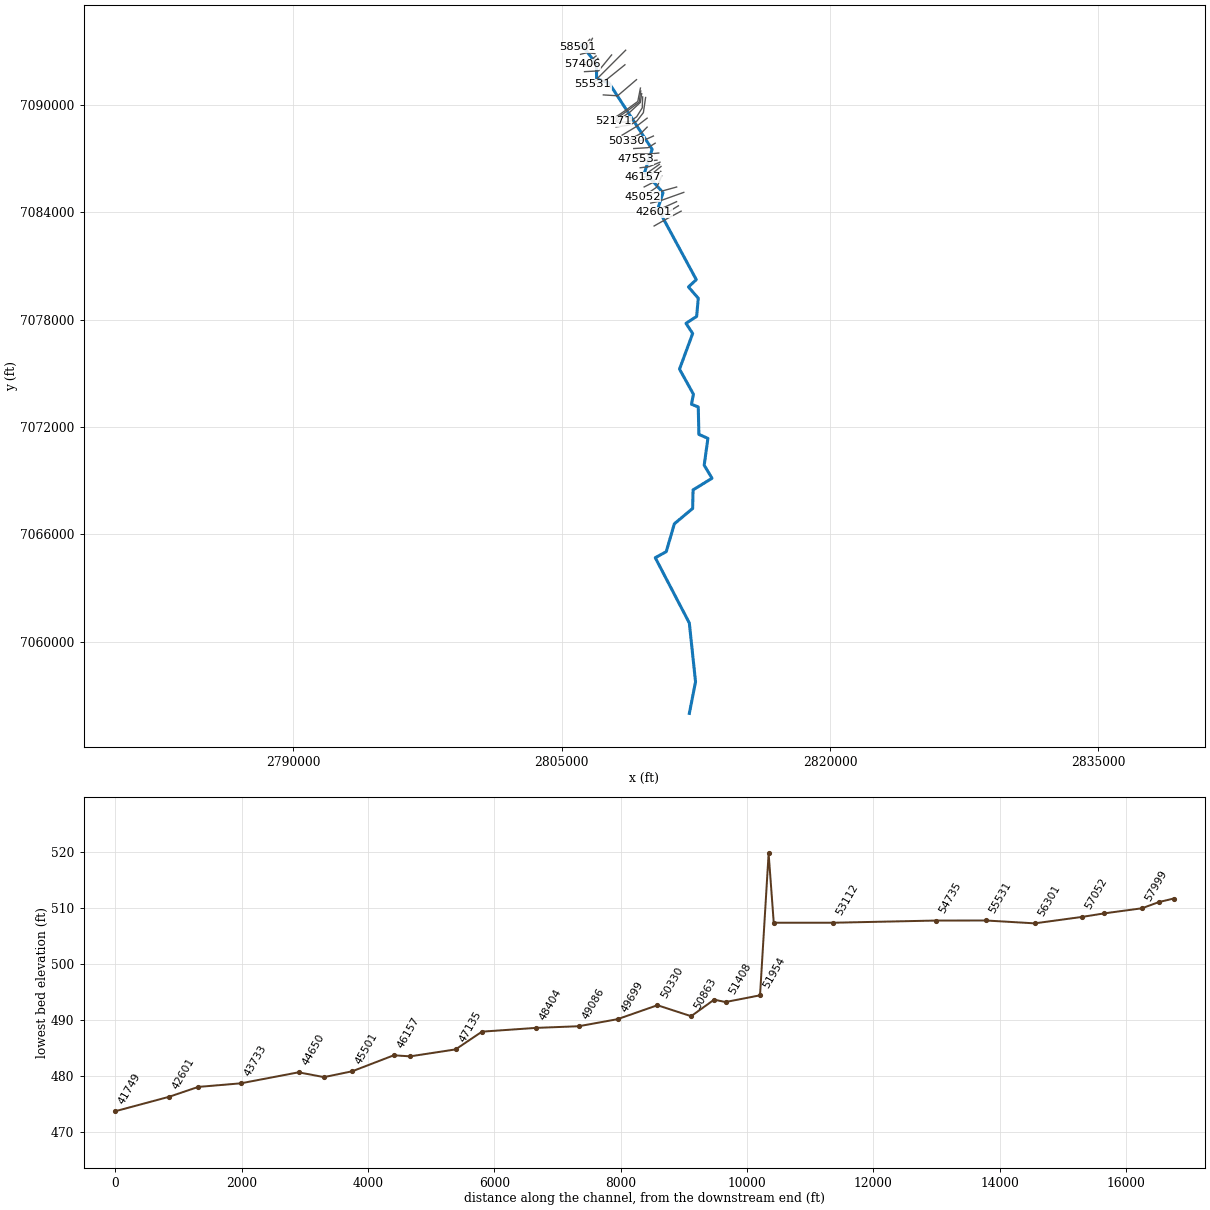
--- REDDIG CREEK.prj (project) ---

Proj Title=REDDIG CREEK Base Level Engineering
Current Plan=p01
Default Exp/Contr=0.3,0.1
English Units
Geom File=g01
Flow File=f01
Plan File=p01
Y Axis Title=Elevation
X Axis Title(PF)=Main Channel Distance
X Axis Title(XS)=Station
BEGIN DESCRIPTION:
REDDIG CREEK
END DESCRIPTION:
DSS Export Rating Curves= 0
DSS Export Rating Curve Sorted= 0
DSS Export Volume Flow Curves= 0
DXF OffsetX= 0
DXF OffsetY= 0
DXF ScaleX= 1
DXF ScaleY= 10

--- REDDIG CREEK.p01 (plan) ---

Plan Title=Multiple Run
Short Identifier=Multiple
Geom File=g01
Flow File=f01
Subcritical Flow
K Sum by GR= 0
Std Step Tol= 0.01
Critical Tol= 0.01
Num of Std Step Trials= 20
Max Error Tol= 0.3
Flow Tol Ratio= 0.001
Split Flow NTrial= 30
Split Flow Tol= 0.02
Split Flow Ratio= 0.02
Log Output Level= 0
Friction Slope Method= 1
Unsteady Friction Slope Method= 2
Unsteady Bridges Friction Slope Method= 1
Parabolic Critical Depth
Global Vel Dist=  1 , 1 , 1
Global Log Level= 0
CheckData=True
Encroach Param= -1, 0, 0, 0
BEGIN DESCRIPTION:
Multiple Run
END DESCRIPTION:

--- REDDIG CREEK.f01 (steady flow) ---

Flow Title=Multiple
Program Version=5.07
Number of Profiles= 7
Profile Names=10-year,25-year,50-year,1pct_min,100-year,1pct_plu,500-year
River Rch & RM=REDDIG CREEK,Reach-1         ,58501
     568     748     890     526    1050    2094    1454
River Rch & RM=REDDIG CREEK,Reach-1         ,57999
     908    1228    1488     893    1782    3555    2550
River Rch & RM=REDDIG CREEK,Reach-1         ,54735
    1318    1813    2223    1348    2689    5365    3930
River Rch & RM=REDDIG CREEK,Reach-1         ,47553
    1425    1961    2404    1457    2906    5799    4244
River Rch & RM=REDDIG CREEK,Reach-1         ,44650
    2226    3125    3883    2381    4751    9480    7107
River Rch & RM=REDDIG CREEK,Reach-1         ,35232
    3208    4564    5721    3535    7054   14075   10715
River Rch & RM=REDDIG CREEK,Reach-1         ,27023
    3466    4947    6216    3849    7680   15324   11715
River Rch & RM=REDDIG CREEK,Reach-1         ,22079
    4478    6434    8121    5048   10072   20097   15479
Boundary for River Rch & Prof#=REDDIG CREEK,Reach-1         , 1
Up Type= 0
Dn Type= 3
Dn Slope=0.00119
Boundary for River Rch & Prof#=REDDIG CREEK,Reach-1         , 2
Up Type= 0
Dn Type= 3
Dn Slope=0.00119
Boundary for River Rch & Prof#=REDDIG CREEK,Reach-1         , 3
Up Type= 0
Dn Type= 3
Dn Slope=0.00119
Boundary for River Rch & Prof#=REDDIG CREEK,Reach-1         , 4
Up Type= 0
Dn Type= 3
Dn Slope=0.00119
Boundary for River Rch & Prof#=REDDIG CREEK,Reach-1         , 5
Up Type= 0
Dn Type= 3
Dn Slope=0.00119
Boundary for River Rch & Prof#=REDDIG CREEK,Reach-1         , 6
Up Type= 0
Dn Type= 3
Dn Slope=0.00119
Boundary for River Rch & Prof#=REDDIG CREEK,Reach-1         , 7
Up Type= 0
Dn Type= 3
Dn Slope=0.00119
DSS Import GetInterval= 0
DSS Import GetPeak= 0
DSS Import FillOption= 0

--- REDDIG CREEK.g01 (geometry) ---

Geom Title=Existing Conditions

River Reach=REDDIG CREEK,Reach-1
Reach XY= 30
      2806103.49      7093384.47      2806938.32      7092313.49
      2806949.96      7091468.69      2807633.45      7091255.83
      2810054.54      7087530.16      2809639.90      7086261.63
      2810662.27      7085108.94      2810377.67      7084216.85
      2812523.92      7080244.89      2812084.86      7079835.73
      2812634.14      7079205.20      2812543.33      7078186.53
      2811947.97      7077799.98      2812321.12      7077231.90
      2811585.32      7075240.92      2812362.33      7073839.56
      2812255.03      7073276.17      2812633.94      7073124.99
      2812668.87      7071592.16      2813172.96      7071369.52
      2812965.43      7069865.79      2813403.16      7069136.17
      2812343.46      7068487.07      2812320.20      7067447.91
      2811296.35      7066590.39      2810843.43      7065031.66
      2810229.41      7064695.84      2812133.98      7061044.95
      2812481.73      7057755.69      2812135.59      7055990.71

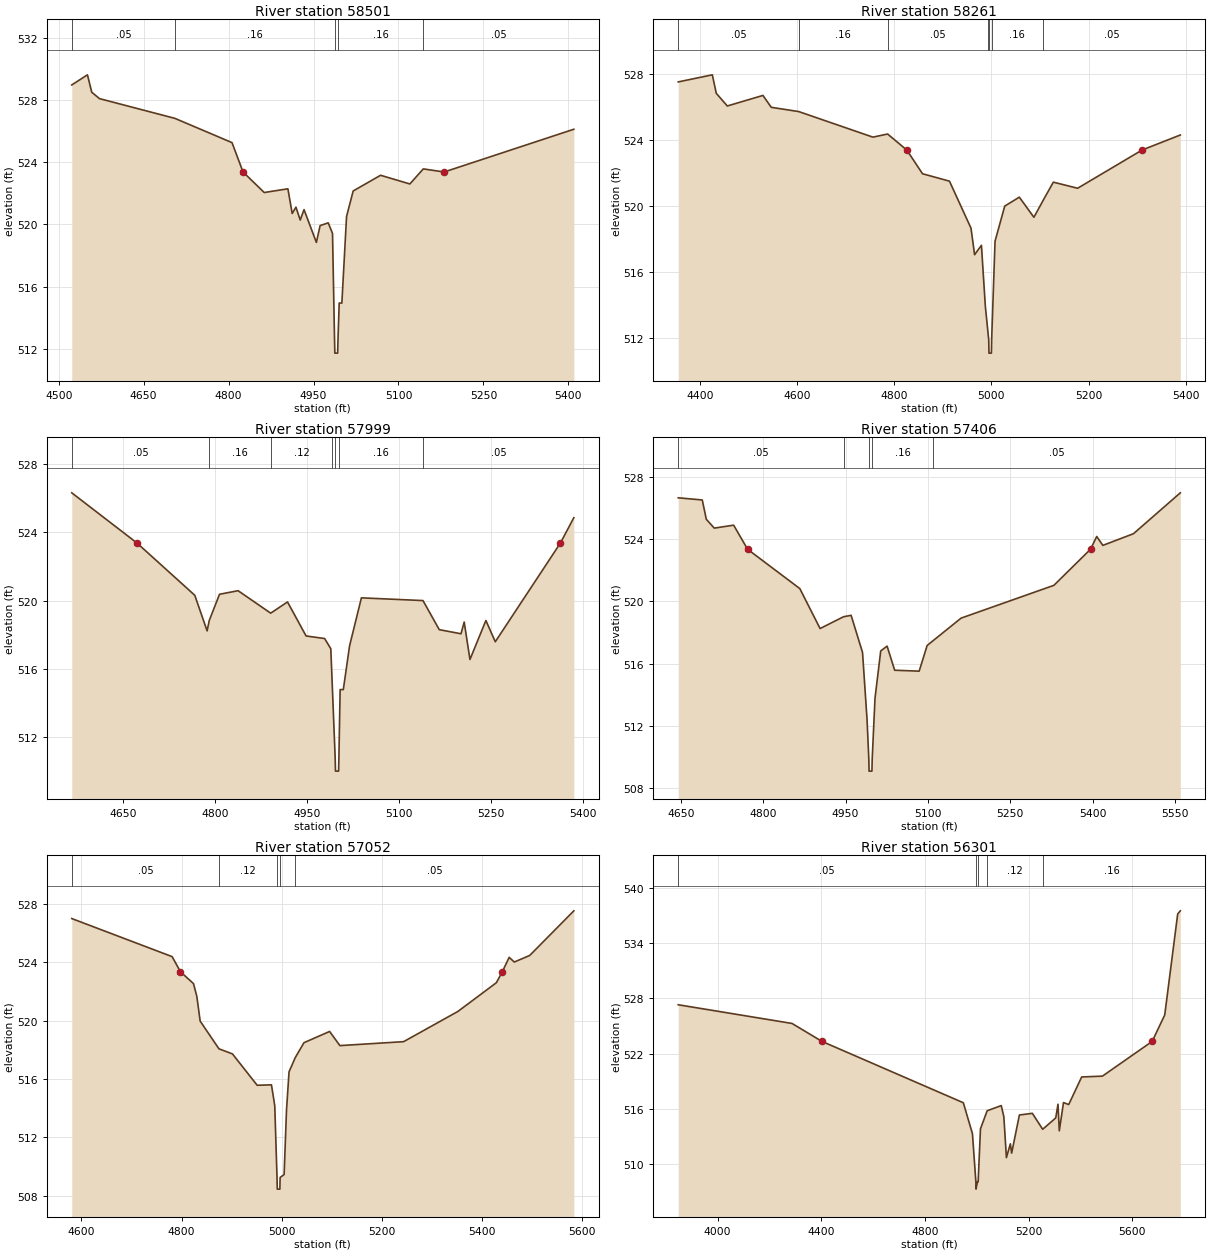
Type RM Length L Ch R = 1,58501,240,240,240
BEGIN DESCRIPTION:
REDDIG CREEK 43.0
END DESCRIPTION:
XS GIS Cut Line= 3
      2806567.44      7093681.77      2806253.16      7093322.94
      2805850.01      7093250.00
#Sta/Elev= 30
  4523.0  528.97  4550.7  529.62  4558.3  528.50  4571.9  528.09  4705.1  526.82
  4806.0  525.26  4825.5  523.37  4862.9  522.05  4904.7  522.29  4912.3  520.70
  4918.9  521.11  4926.5  520.28  4933.2  520.95  4955.0  518.84  4961.6  519.92
  4975.9  520.10  4983.5  519.42  4987.1  512.52  4987.6  511.72  4992.6  511.72
  4993.1  512.52  4995.3  514.94  5000.0  514.94  5008.3  520.51  5020.0  522.15
  5068.4  523.16  5120.1  522.60  5143.8  523.57  5180.6  523.37  5409.7  526.12
#Mann=5,-1,0
  4523.0    0.05       0  4705.1    0.16       0  4987.1    0.07       0
  4993.1    0.16       0  5143.8    0.05       0
Bank Sta=4825.5,5180.6
Exp/Cntr=0.3,0.1

Type RM Length L Ch R = 1,58261,262,262,262
BEGIN DESCRIPTION:
Mapping XS dbc4a841
END DESCRIPTION:
XS GIS Cut Line= 3
      2806715.05      7093738.24      2806445.94      7093178.33
      2806033.57      7093178.33
#Sta/Elev= 30
  4355.4  527.52  4425.6  527.95  4433.7  526.83  4456.4  526.06  4529.8  526.70
  4546.9  525.98  4603.6  525.72  4756.2  524.17  4786.4  524.36  4825.9  523.39
  4858.3  521.95  4913.8  521.50  4958.1  518.65  4965.5  517.04  4979.6  517.61
  4987.6  513.92  4992.9  512.37  4994.6  511.87  4995.1  511.07  5000.1  511.07
  5000.6  511.87  5007.6  517.86  5027.6  519.99  5057.6  520.53  5087.6  519.31
  5105.6  520.28  5127.6  521.44  5177.6  521.07  5310.4  523.39  5389.0  524.30
#Mann=7,-1,0
  4355.4    0.05       0  4603.6    0.16       0  4786.4    0.05       0
  4992.9    0.16       0  4994.6    0.07       0  5000.6    0.16       0
  5105.6    0.05       0
Bank Sta=4825.9,5310.4
Exp/Cntr=0.3,0.1

Type RM Length L Ch R = 1,57999,593,593,593
BEGIN DESCRIPTION:
Mapping XS fb1dfa17
END DESCRIPTION:
XS GIS Cut Line= 3
      2806853.89      7092883.19      2806419.90      7092939.61
      2806051.00      7092844.13
#Sta/Elev= 30
  4565.9  526.33  4672.3  523.38  4766.5  520.31  4786.6  518.22  4790.1  518.83
  4806.8  520.37  4837.1  520.58  4890.3  519.26  4917.7  519.92  4948.0  517.92
  4978.2  517.77  4988.3  517.17  4990.5  515.19  4995.4  510.78  4995.9  509.98
  5001.0  509.98  5001.5  510.78  5003.5  514.77  5008.7  514.77  5018.9  517.34
  5038.2  520.16  5138.6  520.00  5165.2  518.29  5200.6  518.05  5205.8  518.74
  5215.2  516.54  5241.2  518.83  5256.5  517.58  5362.7  523.38  5384.6  524.87
#Mann=7,-1,0
  4565.9    0.05       0  4790.1    0.16       0  4890.3    0.12       0
  4990.5    0.16       0  4995.4    0.07       0  5001.5    0.16       0
  5138.6    0.05       0
Bank Sta=4672.3,5362.7
Exp/Cntr=0.3,0.1

Type RM Length L Ch R = 1,57406,354,354,354
BEGIN DESCRIPTION:
REDDIG CREEK 42.0
END DESCRIPTION:
XS GIS Cut Line= 3
      2806919.69      7092751.76      2806625.00      7092525.00
      2806138.52      7092285.23
#Sta/Elev= 30
  4645.3  526.66  4689.1  526.52  4696.4  525.28  4710.9  524.71  4746.2  524.90
  4771.6  523.35  4866.7  520.82  4903.6  518.25  4946.3  519.01  4960.1  519.10
  4980.9  516.71  4989.1  512.40  4992.3  509.88  4992.8  509.08  4998.0  509.08
  4998.5  509.88  5003.6  513.77  5014.0  516.81  5025.6  517.12  5039.4  515.57
  5084.0  515.51  5098.5  517.16  5109.0  517.46  5160.3  518.92  5329.3  521.03
  5396.0  523.35  5407.3  524.17  5418.5  523.60  5474.2  524.35  5559.5  526.98
#Mann=5,-1,0
  4645.3    0.05       0  4946.3    0.16       0  4992.3    0.07       0
  4998.5    0.16       0  5109.0    0.05       0
Bank Sta=4771.6,5396
Exp/Cntr=0.3,0.1

Type RM Length L Ch R = 1,57052,751,751,751
BEGIN DESCRIPTION:
REDDIG CREEK 41.0
END DESCRIPTION:
XS GIS Cut Line= 3
      2807024.84      7092617.44      2806747.39      7092302.02
      2806178.93      7092176.67
#Sta/Elev= 30
  4580.7  526.99  4781.0  524.38  4797.7  523.34  4823.7  522.53  4830.3  521.66
  4837.0  519.96  4874.5  518.06  4901.5  517.71  4950.8  515.56  4979.3  515.59
  4985.9  514.16  4990.4  509.24  4990.9  508.44  4996.1  508.44  4996.6  509.24
  5004.6  509.44  5009.3  513.83  5014.4  516.48  5026.7  517.45  5044.2  518.48
  5095.4  519.25  5115.9  518.28  5243.1  518.55  5351.4  520.62  5428.2  522.59
  5440.1  523.34  5453.8  524.33  5464.0  524.01  5494.8  524.46  5582.9  527.52
#Mann=5,-1,0
  4580.7    0.05       0  4874.5    0.12       0  4990.4    0.07       0
  4996.6    0.12       0  5026.7    0.05       0
Bank Sta=4797.7,5440.1
Exp/Cntr=0.3,0.1

Type RM Length L Ch R = 1,56301,770,770,770
BEGIN DESCRIPTION:
REDDIG CREEK 40.0
END DESCRIPTION:
XS GIS Cut Line= 3
      2807788.57      7092809.22      2807057.91      7091916.86
      2806274.96      7091875.00
#Sta/Elev= 30
  3847.9  527.31  4287.0  525.28  4402.6  523.33  4948.0  516.67  4983.2  513.31
  4996.4  508.09  4996.9  507.29  5002.7  508.09  5005.2  508.09  5014.2  513.84
  5040.0  515.80  5094.3  516.36  5104.3  515.17  5114.3  510.71  5129.5  512.21
  5134.5  511.20  5164.4  515.34  5214.4  515.52  5254.2  513.79  5304.6  515.02
  5313.3  516.51  5318.3  513.62  5334.6  516.69  5354.6  516.47  5404.7  519.47
  5484.8  519.56  5676.7  523.33  5725.2  526.20  5775.2  537.17  5785.3  537.51
#Mann=5,-1,0
  3847.9    0.05       0  4996.4    0.03       0  5002.7    0.05       0
  5040.0    0.12       0  5254.2    0.16       0
Bank Sta=4402.6,5676.7
Exp/Cntr=0.3,0.1

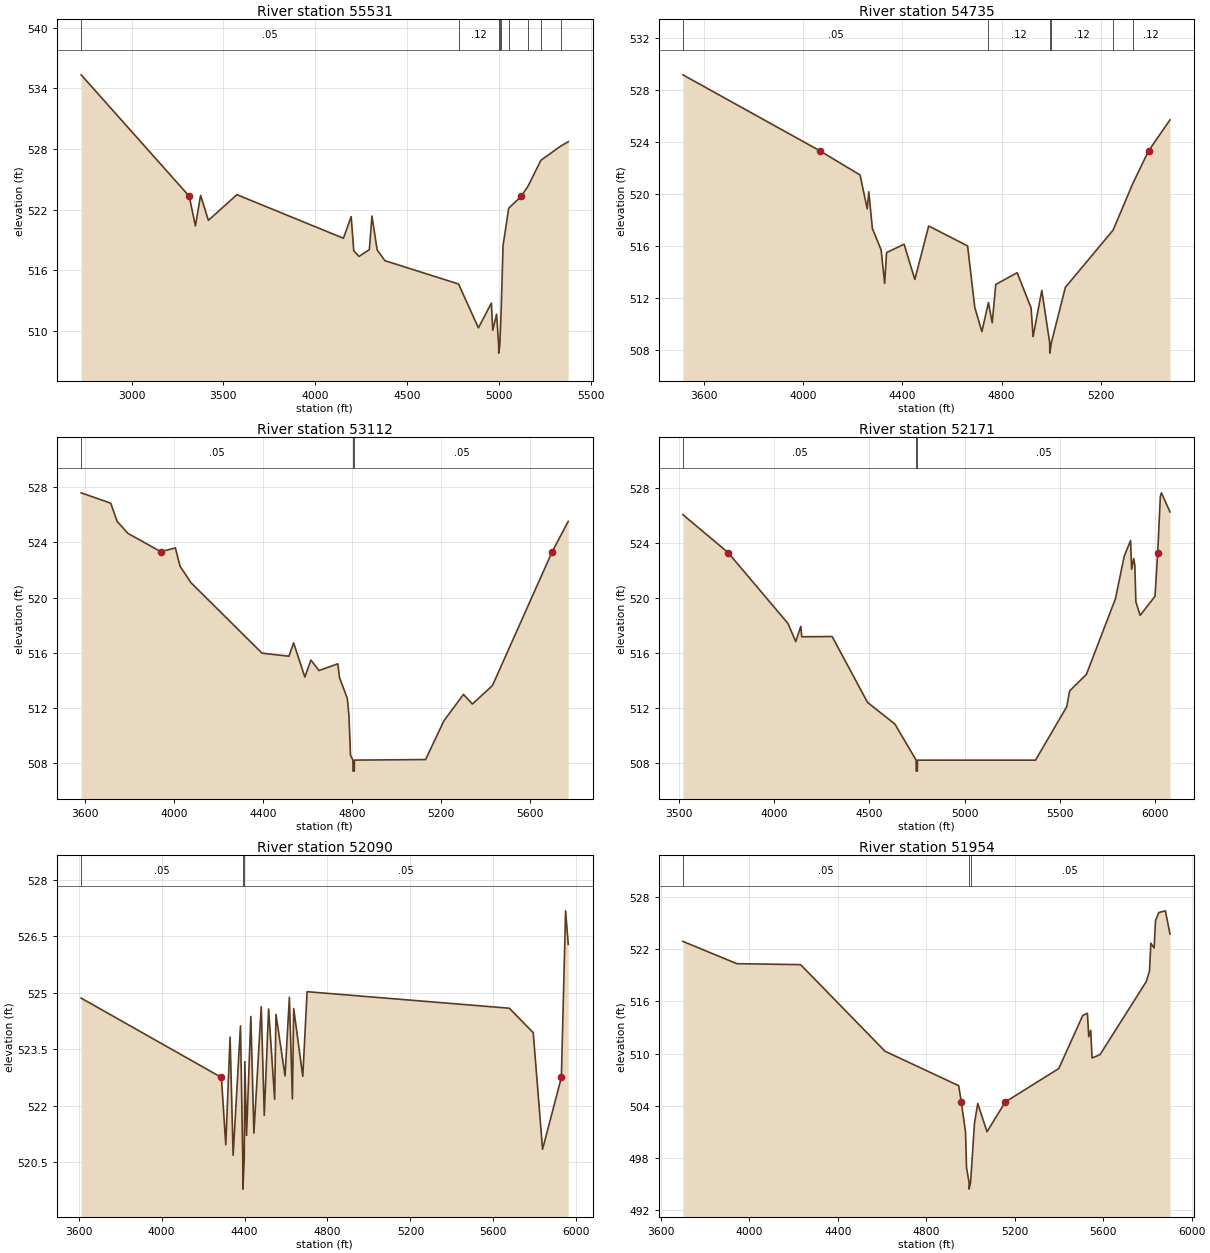
Type RM Length L Ch R = 1,55531,796,796,796
BEGIN DESCRIPTION:
REDDIG CREEK 39.0
END DESCRIPTION:
XS GIS Cut Line= 3
      2808575.01      7093075.01      2807025.00      7091525.00
      2806725.01      7091175.02
#Sta/Elev= 30
  2725.1  535.34  3313.8  523.33  3347.4  520.39  3375.7  523.41  3418.1  520.94
  3573.6  523.48  4153.5  519.17  4195.9  521.31  4210.0  517.92  4238.3  517.37
  4294.9  518.04  4309.0  521.37  4337.3  518.02  4379.7  516.95  4780.7  514.64
  4888.9  510.30  4959.4  512.75  4967.1  510.06  4987.9  511.65  4999.1  508.60
  4999.6  507.80  5005.4  508.60  5012.2  511.68  5023.1  518.44  5053.9  522.14
  5122.8  523.33  5160.3  524.36  5229.1  526.88  5336.4  528.28  5378.1  528.72
#Mann=9,-1,0
  2725.1    0.05       0  4780.7    0.12       0  4999.1    0.07       0
  5005.4    0.12       0  5012.2    0.16       0  5053.9     0.1       0
  5160.3    0.05       0  5229.1    0.16       0  5336.4    0.05       0
Bank Sta=3313.8,5122.8
Exp/Cntr=0.3,0.1

Type RM Length L Ch R = 1,54735,1623,1623,1623
BEGIN DESCRIPTION:
REDDIG CREEK 38.0
END DESCRIPTION:
XS GIS Cut Line= 3
      2808533.73      7092260.05      2807375.00      7091325.00
      2806924.99      7091175.00
#Sta/Elev= 30
  3515.5  529.18  4068.5  523.33  4229.6  521.48  4258.4  518.88  4264.8  520.19
  4279.2  517.37  4314.4  515.73  4328.8  513.15  4336.3  515.52  4407.1  516.16
  4450.3  513.45  4506.3  517.56  4663.0  516.03  4691.8  511.32  4720.6  509.44
  4747.0  511.68  4762.2  510.12  4776.6  513.07  4862.9  513.97  4918.9  511.26
  4926.9  509.05  4962.1  512.61  4993.9  508.59  4994.4  507.79  5000.6  508.59
  5057.2  512.85  5249.4  517.24  5328.4  520.80  5392.2  523.33  5478.8  525.72
#Mann=6,-1,0
  3515.5    0.05       0  4747.0    0.12       0  4993.9    0.07       0
  5000.6    0.12       0  5249.4    0.16       0  5328.4    0.12       0
Bank Sta=4068.5,5392.2
Exp/Cntr=0.3,0.1

Type RM Length L Ch R = 1,53112,941,941,941
BEGIN DESCRIPTION:
REDDIG CREEK 36.0
END DESCRIPTION:
XS GIS Cut Line= 3
      2809179.91      7091427.42      2808125.00      7090525.00
      2807325.00      7090575.00
#Sta/Elev= 30
  3582.2  527.60  3715.2  526.85  3743.7  525.53  3793.1  524.65  3940.1  523.33
  4006.1  523.60  4026.9  522.27  4076.3  521.07  4395.8  515.96  4516.5  515.74
  4537.4  516.71  4587.9  514.23  4615.3  515.46  4651.5  514.70  4736.1  515.19
  4743.8  514.19  4778.9  512.67  4786.2  511.44  4793.2  508.55  4804.0  508.20
  4804.5  507.40  4810.3  507.40  4810.8  508.20  5130.7  508.24  5213.4  511.06
  5301.1  512.97  5341.2  512.27  5431.3  513.61  5700.0  523.33  5772.0  525.53
#Mann=3,-1,0
  3582.2    0.05       0  4804.0   0.033       0  4810.8    0.05       0
Bank Sta=3940.1,5700
Exp/Cntr=0.3,0.1

Type RM Length L Ch R = 1,52171,81,81,81
BEGIN DESCRIPTION:
REDDIG CREEK 35.0
END DESCRIPTION:
XS GIS Cut Line= 6
      2809400.61      7090956.70      2809252.39      7090208.49
      2808669.06      7089781.41      2808210.73      7089463.70
      2807974.18      7089318.05      2807867.43      7089104.53
#Sta/Elev= 30
  3519.5  526.09  3756.6  523.33  4071.7  518.16  4112.5  516.84  4139.1  517.95
  4144.2  517.19  4303.8  517.21  4489.7  512.41  4633.7  510.83  4745.2  508.20
  4745.7  507.40  4751.8  507.40  4752.3  508.20  5372.7  508.20  5536.9  512.10
  5551.7  513.24  5640.1  514.45  5792.7  519.96  5838.8  523.06  5872.2  524.20
  5877.8  522.11  5888.8  522.89  5894.6  522.40  5900.2  519.74  5922.5  518.75
  6000.6  520.14  6014.9  523.33  6028.7  527.42  6034.3  527.68  6079.4  526.29
#Mann=3,-1,0
  3519.5    0.05       0  4745.2    0.03       0  4752.3    0.05       0
Bank Sta=3756.6,6014.9
Exp/Cntr=0.3,0.1

Type RM Length L Ch R = 1,52090,136,136,136
BEGIN DESCRIPTION:
Mapping XS dae7a9f8
END DESCRIPTION:
XS GIS Cut Line= 6
      2809419.06      7090795.32      2809330.52      7090170.30
      2808726.35      7089722.38      2808090.93      7089279.67
      2808059.68      7089243.21      2808038.85      7089102.58
#Sta/Elev= 30
  3611.9  524.86  4288.4  522.75  4309.4  520.96  4330.3  523.82  4344.9  520.68
  4380.4  524.12  4391.4  520.58  4391.9  519.78  4398.5  520.58  4401.2  523.17
  4409.6  521.21  4430.4  524.37  4445.1  521.27  4480.5  524.63  4495.1  521.74
  4516.0  524.57  4545.2  522.17  4551.5  524.43  4595.3  522.79  4616.2  524.88
  4630.8  522.18  4637.0  524.58  4680.9  522.78  4701.7  525.03  5677.1  524.59
  5792.3  523.94  5837.3  520.84  5928.0  522.75  5948.4  527.18  5961.1  526.29
#Mann=3,-1,0
  3611.9    0.05       0  4391.4    0.03       0  4398.5    0.05       0
Bank Sta=4288.4,5928
Exp/Cntr=0.3,0.1

Type RM Length L Ch R = 1,51954,546,546,546
BEGIN DESCRIPTION:
REDDIG CREEK 34.0
END DESCRIPTION:
XS GIS Cut Line= 4
      2809471.14      7090646.00      2809393.02      7090151.20
      2808825.00      7089625.00      2808060.51      7089099.68
#Sta/Elev= 30
  3699.2  522.89  3943.2  520.33  4231.4  520.22  4613.5  510.27  4946.3  506.32
  4958.3  504.45  4977.5  500.94  4981.9  496.89  4993.2  495.24  4993.7  494.44
  5000.3  495.24  5017.7  501.98  5032.6  504.27  5074.5  501.03  5157.2  504.45
  5399.1  508.29  5507.6  514.39  5528.6  514.63  5534.6  511.94  5543.5  512.68
  5549.5  509.50  5585.4  509.88  5794.5  518.26  5809.4  519.50  5815.4  522.68
  5830.3  522.13  5836.4  525.26  5851.3  526.20  5881.1  526.40  5902.0  523.75
#Mann=3,-1,0
  3699.2    0.05       0  4993.2    0.03       0  5000.3    0.05       0
Bank Sta=4958.3,5157.2
Exp/Cntr=0.3,0.1

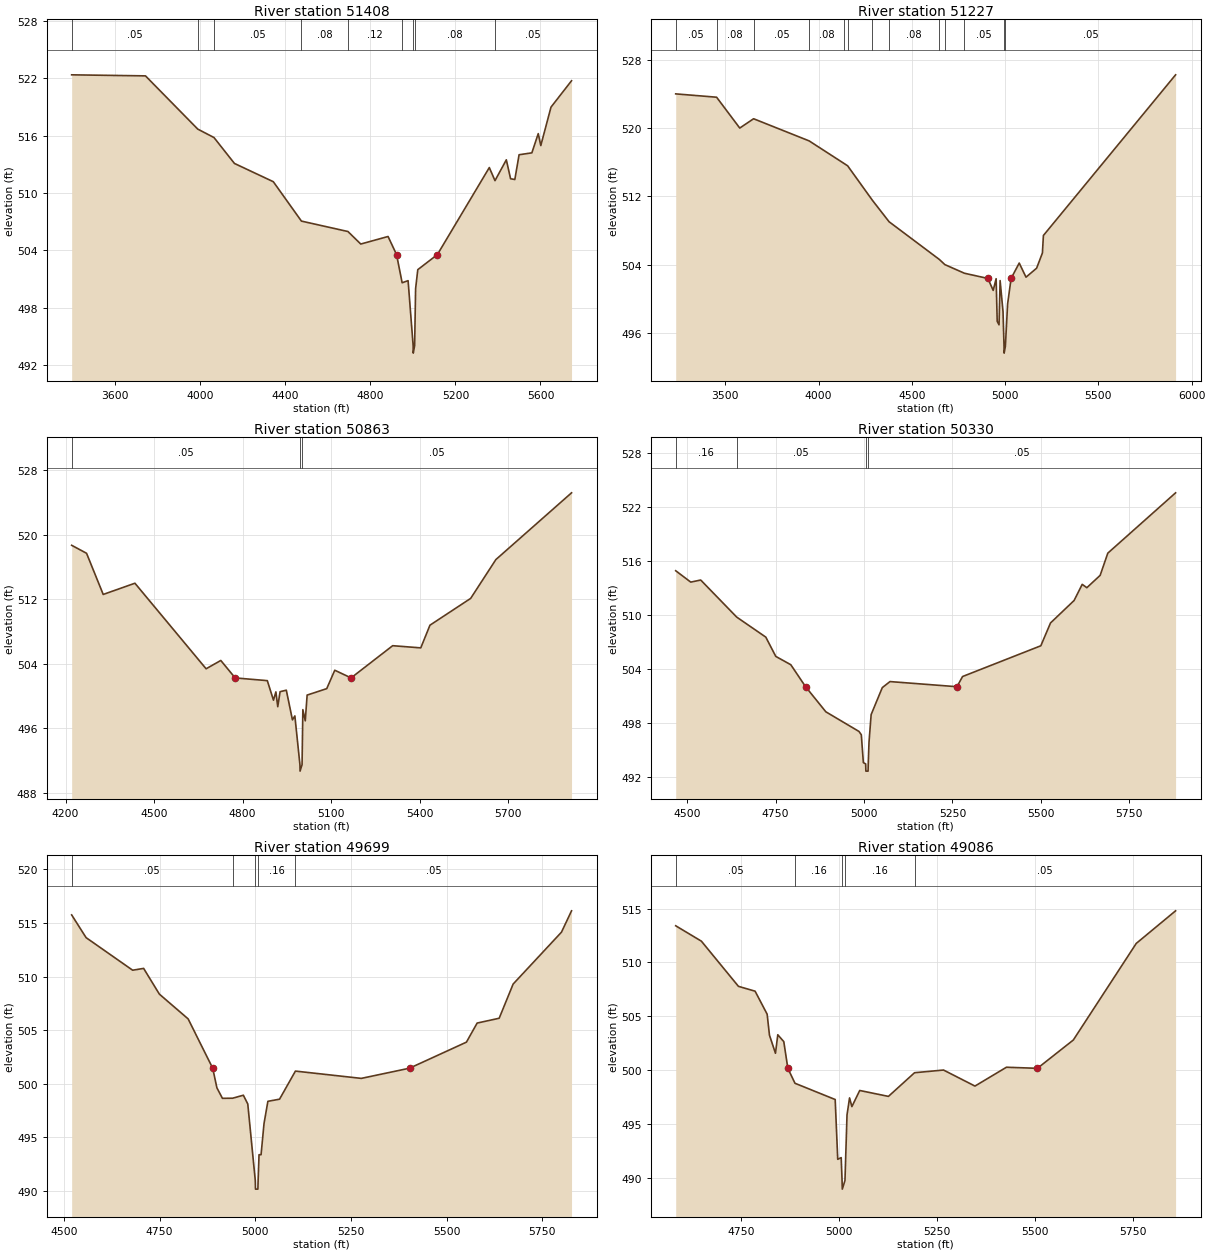
Type RM Length L Ch R = 1,51408,181,181,181
BEGIN DESCRIPTION:
Mapping XS 05edc45b
END DESCRIPTION:
XS GIS Cut Line= 6
      2809523.23      7090461.96      2809502.39      7089852.59
      2809189.89      7089352.59      2808851.35      7089118.21
      2808611.77      7089060.92      2808118.46      7089045.34
#Sta/Elev= 30
  3395.1  522.35  3742.3  522.24  3988.3  516.67  4064.5  515.79  4160.7  513.08
  4343.5  511.17  4475.7  507.05  4694.5  505.96  4754.8  504.65  4883.2  505.44
  4923.1  503.55  4949.4  500.60  4977.4  500.82  5001.1  494.04  5001.6  493.24
  5008.2  494.04  5012.7  499.97  5023.0  501.97  5115.2  503.55  5359.4  512.65
  5386.1  511.28  5439.4  513.46  5459.4  511.48  5479.4  511.40  5499.4  513.99
  5559.5  514.19  5589.5  516.20  5601.5  514.95  5649.5  518.97  5746.1  521.73
#Mann=9,-1,0
  3395.1    0.05       0  3988.3    0.08       0  4064.5    0.05       0
  4475.7    0.08       0  4694.5    0.12       0  4949.4    0.08       0
  5001.1    0.07       0  5008.2    0.08       0  5386.1    0.05       0
Bank Sta=4923.1,5115.2
Exp/Cntr=0.3,0.1

Type RM Length L Ch R = 1,51227,364,364,364
BEGIN DESCRIPTION:
Mapping XS 8ea75972
END DESCRIPTION:
XS GIS Cut Line= 6
      2809689.89      7090430.67      2809564.89      7089581.75
      2809210.73      7089123.42      2808929.48      7088956.75
      2808689.89      7088873.42      2808033.62      7088784.88
#Sta/Elev= 30
  3233.8  524.00  3453.0  523.61  3577.2  520.00  3651.4  521.09  3949.0  518.50
  4136.9  515.85  4155.7  515.58  4288.3  511.55  4377.6  509.04  4647.4  504.62
  4676.8  504.02  4781.6  503.01  4907.5  502.40  4936.0  501.00  4951.7  502.37
  4957.5  497.38  4967.3  496.97  4973.1  502.15  4988.7  498.51  4994.1  494.46
  4994.7  493.66  5001.3  494.46  5013.3  499.41  5032.0  502.40  5075.5  504.20
  5111.9  502.55  5168.8  503.60  5199.9  505.38  5205.2  507.43  5913.9  526.23
#Mann=13,-1,0
  3233.8    0.05       0  3453.0    0.08       0  3651.4    0.05       0
  3949.0    0.08       0  4136.9    0.05       0  4155.7    0.08       0
  4288.3    0.05       0  4377.6    0.08       0  4647.4    0.05       0
  4676.8    0.08       0  4781.6    0.05       0  4994.1    0.03       0
  5001.3    0.05       0
Bank Sta=4907.5,5032
Exp/Cntr=0.3,0.1

Type RM Length L Ch R = 1,50863,533,533,533
BEGIN DESCRIPTION:
REDDIG CREEK 32.0
END DESCRIPTION:
XS GIS Cut Line= 3
      2809775.03      7089275.03      2809125.00      7088775.00
      2808375.04      7088325.02
#Sta/Elev= 30
  4220.5  518.69  4271.0  517.70  4327.5  512.60  4435.0  513.99  4676.3  503.39
  4726.1  504.42  4774.8  502.26  4883.8  501.92  4904.7  499.50  4912.9  500.53
  4919.2  498.69  4927.1  500.55  4948.2  500.74  4969.0  497.06  4977.2  497.55
  4994.4  491.51  4994.9  490.71  5001.6  491.51  5004.3  498.33  5012.5  496.94
  5018.8  500.13  5085.3  500.93  5112.5  503.21  5167.8  502.26  5308.8  506.25
  5404.1  505.98  5435.2  508.79  5573.2  512.11  5658.7  516.92  5915.2  525.19
#Mann=3,-1,0
  4220.5    0.05       0  4994.4    0.03       0  5001.6    0.05       0
Bank Sta=4774.8,5167.8
Exp/Cntr=0.3,0.1

Type RM Length L Ch R = 1,50330,631,631,631
BEGIN DESCRIPTION:
REDDIG CREEK 31.0
END DESCRIPTION:
XS GIS Cut Line= 3
      2809775.02      7088775.02      2809425.00      7088425.00
      2808624.99      7087974.99
#Sta/Elev= 30
  4467.7  514.89  4510.2  513.63  4538.4  513.86  4640.1  509.75  4722.3  507.53
  4750.6  505.39  4793.0  504.47  4834.8  502.03  4892.0  499.25  4985.7  497.07
  4992.3  496.70  4998.1  493.61  5004.6  493.47  5005.2  492.67  5011.4  492.67
  5011.9  493.47  5014.0  495.83  5020.1  498.94  5051.6  501.93  5073.3  502.60
  5262.7  502.03  5278.5  503.16  5499.7  506.57  5527.1  509.10  5593.7  511.59
  5616.7  513.38  5629.8  513.01  5667.4  514.38  5689.0  516.84  5880.6  523.53
#Mann=4,-1,0
  4467.7    0.16       0  4640.1    0.05       0  5004.6    0.03       0
  5011.9    0.05       0
Bank Sta=4834.8,5262.7
Exp/Cntr=0.3,0.1

Type RM Length L Ch R = 1,49699,613,613,613
BEGIN DESCRIPTION:
REDDIG CREEK 30.0
END DESCRIPTION:
XS GIS Cut Line= 3
      2810125.03      7088275.01      2809675.00      7088075.00
      2808875.02      7087925.00
#Sta/Elev= 30
  4520.3  515.76  4558.0  513.64  4679.7  510.60  4708.4  510.77  4749.5  508.37
  4824.7  506.06  4888.9  501.46  4899.9  499.63  4914.3  498.65  4941.0  498.66
  4969.0  498.94  4980.6  498.12  5000.2  490.98  5000.7  490.18  5007.0  490.18
  5007.6  490.98  5010.0  493.39  5015.3  493.39  5023.0  496.29  5033.1  498.37
  5063.6  498.57  5105.1  501.19  5277.3  500.51  5403.3  501.46  5552.0  503.89
  5580.0  505.67  5637.6  506.12  5674.1  509.31  5800.4  514.15  5826.7  516.14
#Mann=5,-1,0
  4520.3    0.05       0  4941.0    0.16       0  5000.2    0.07       0
  5007.6    0.16       0  5105.1    0.05       0
Bank Sta=4888.9,5403.3
Exp/Cntr=0.3,0.1

Type RM Length L Ch R = 1,49086,682,682,682
BEGIN DESCRIPTION:
REDDIG CREEK 29.0
END DESCRIPTION:
XS GIS Cut Line= 3
      2810224.97      7087874.98      2809825.00      7087625.00
      2809025.02      7087575.00
#Sta/Elev= 30
  4584.4  513.40  4649.8  511.97  4744.2  507.77  4786.6  507.32  4817.3  505.18
  4823.2  503.23  4838.5  501.55  4844.4  503.27  4859.7  502.63  4870.0  500.15
  4888.2  498.76  4990.6  497.25  4997.1  491.69  5005.9  491.85  5008.1  489.72
  5008.7  488.92  5015.5  489.72  5020.7  495.81  5027.2  497.40  5033.1  496.59
  5053.1  498.09  5126.2  497.54  5192.7  499.74  5266.5  499.99  5346.6  498.50
  5426.8  500.25  5505.7  500.15  5597.1  502.78  5757.4  511.76  5857.6  514.79
#Mann=5,-1,0
  4584.4    0.05       0  4888.2    0.16       0  5008.1    0.07       0
  5015.5    0.16       0  5192.7    0.05       0
Bank Sta=4870,5505.7
Exp/Cntr=0.3,0.1

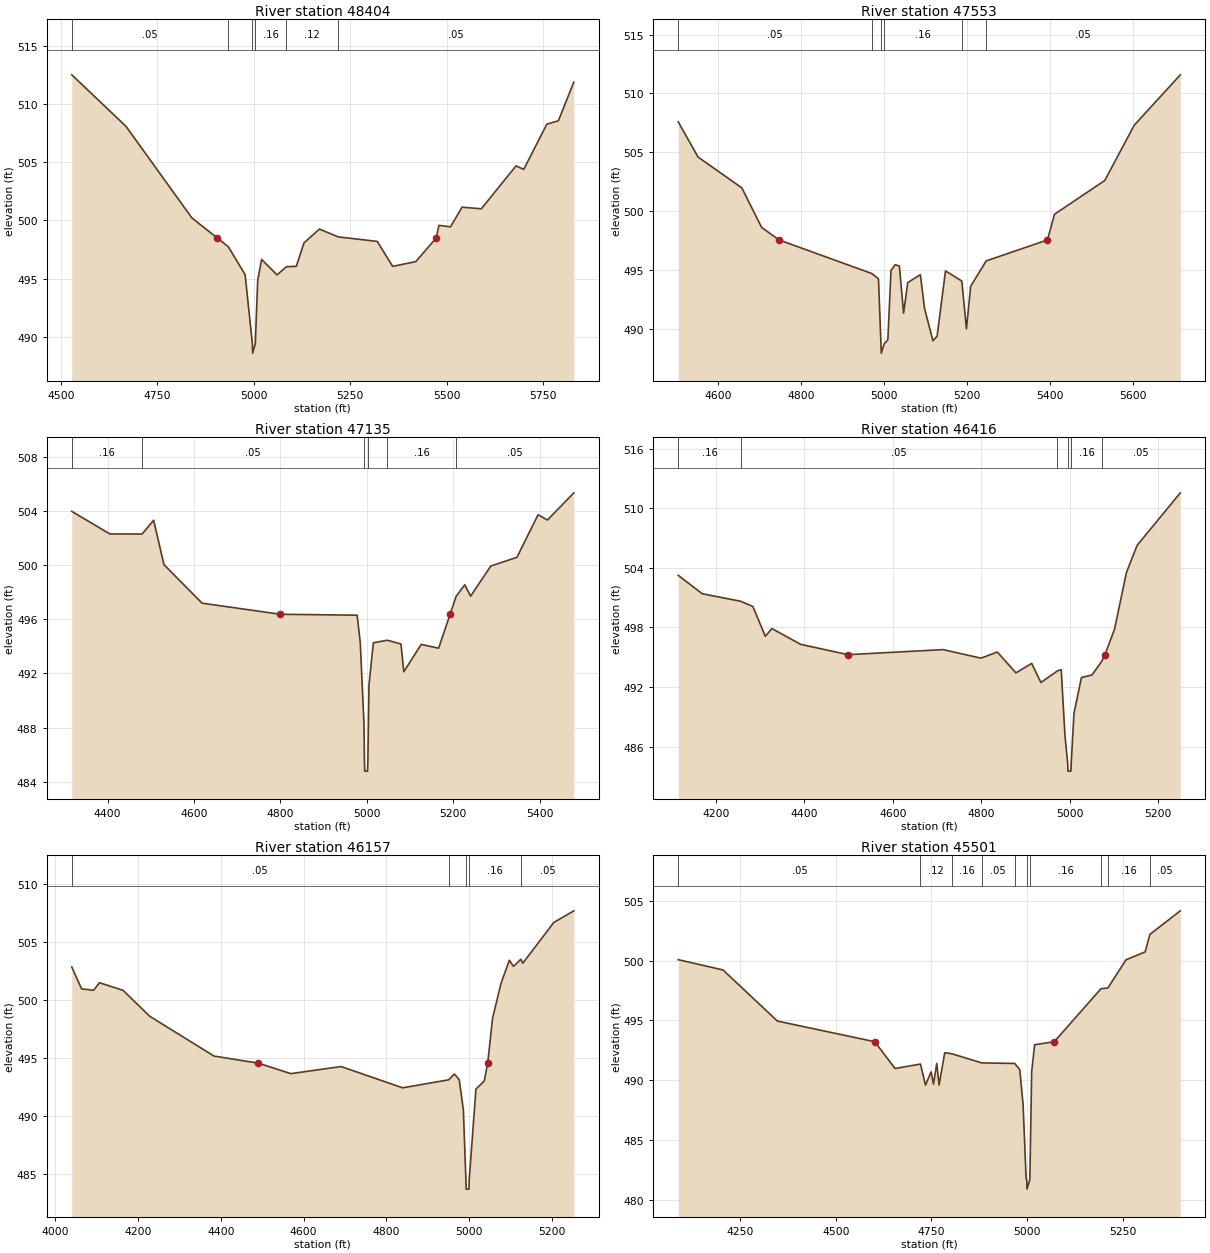
Type RM Length L Ch R = 1,48404,851,851,851
BEGIN DESCRIPTION:
REDDIG CREEK 28.0
END DESCRIPTION:
XS GIS Cut Line= 3
      2810425.01      7087325.00      2809925.00      7087275.00
      2809125.00      7087275.00
#Sta/Elev= 30
  4527.7  512.49  4668.4  508.07  4839.3  500.22  4905.3  498.49  4933.9  497.74
  4977.4  495.35  4996.3  489.42  4996.9  488.62  5003.8  489.42  5010.1  494.86
  5020.2  496.66  5060.2  495.33  5084.6  496.03  5110.2  496.07  5130.2  498.08
  5170.2  499.26  5218.9  498.59  5320.2  498.20  5360.2  496.06  5420.2  496.47
  5473.0  498.49  5480.2  499.58  5510.2  499.45  5540.2  501.14  5590.2  501.00
  5680.2  504.68  5700.2  504.38  5760.2  508.26  5790.2  508.55  5830.2  511.87
#Mann=6,-1,0
  4527.7    0.05       0  4933.9    0.16       0  4996.3    0.07       0
  5003.8    0.16       0  5084.6    0.12       0  5218.9    0.05       0
Bank Sta=4905.3,5473
Exp/Cntr=0.3,0.1

Type RM Length L Ch R = 1,47553,418,418,418
BEGIN DESCRIPTION:
REDDIG CREEK 27.0
END DESCRIPTION:
XS GIS Cut Line= 3
      2810324.97      7086925.00      2809825.00      7086875.00
      2809124.97      7086975.00
#Sta/Elev= 30
  4503.7  507.59  4551.4  504.60  4656.9  501.98  4704.7  498.62  4746.7  497.56
  4970.0  494.71  4986.1  494.26  4992.1  488.75  4992.8  487.95  5000.1  488.75
  5008.7  489.07  5016.3  494.97  5026.4  495.46  5036.5  495.34  5046.6  491.35
  5056.7  493.94  5087.0  494.61  5097.1  491.75  5117.3  489.00  5127.4  489.39
  5147.6  494.93  5186.9  494.07  5198.1  490.01  5208.2  493.62  5245.6  495.78
  5393.2  497.56  5410.2  499.74  5531.4  502.61  5602.2  507.30  5713.3  511.58
#Mann=6,-1,0
  4503.7    0.05       0  4970.0    0.16       0  4992.1    0.07       0
  5000.1    0.16       0  5186.9    0.12       0  5245.6    0.05       0
Bank Sta=4746.7,5393.2
Exp/Cntr=0.3,0.1

Type RM Length L Ch R = 1,47135,719,719,719
BEGIN DESCRIPTION:
Mapping XS 71f92adf
END DESCRIPTION:
XS GIS Cut Line= 3
      2810493.67      7086812.64      2809884.34      7086562.66
      2809384.35      7086500.16
#Sta/Elev= 30
  4317.0  503.99  4405.2  502.32  4479.8  502.31  4506.6  503.33  4530.5  500.05
  4618.7  497.20  4799.8  496.38  4977.8  496.31  4985.0  494.27  4993.6  488.31
  4994.6  485.58  4995.3  484.78  5001.9  484.78  5002.6  485.58  5005.2  491.17
  5015.3  494.27  5047.6  494.46  5079.2  494.18  5085.8  492.13  5126.1  494.15
  5166.4  493.87  5193.0  496.38  5207.0  497.71  5226.9  498.56  5240.5  497.72
  5287.4  499.95  5347.8  500.59  5396.7  503.74  5418.4  503.35  5479.5  505.36
#Mann=6,-1,0
  4317.0    0.16       0  4479.8    0.05       0  4994.6    0.03       0
  5002.6    0.05       0  5047.6    0.16       0  5207.0    0.05       0
Bank Sta=4799.8,5193
Exp/Cntr=0.3,0.1

Type RM Length L Ch R = 1,46416,259,259,259
BEGIN DESCRIPTION:
REDDIG CREEK 26.0
END DESCRIPTION:
XS GIS Cut Line= 3
      2810462.48      7086692.87      2809777.08      7086204.17
      2809489.26      7086146.14
#Sta/Elev= 30
  4114.8  503.25  4169.2  501.39  4255.8  500.64  4283.6  500.11  4311.8  497.11
  4326.5  497.89  4391.7  496.30  4498.8  495.26  4713.5  495.77  4799.5  494.91
  4836.3  495.53  4878.5  493.43  4914.1  494.38  4935.0  492.46  4972.4  493.63
  4980.9  493.76  4989.3  487.16  4995.5  484.34  4996.2  483.54  5002.9  483.54
  5003.5  484.34  5009.7  489.35  5026.6  492.96  5050.5  493.22  5073.0  494.63
  5079.8  495.26  5101.5  497.83  5128.3  503.52  5152.5  506.26  5250.2  511.55
#Mann=6,-1,0
  4114.8    0.16       0  4255.8    0.05       0  4972.4    0.16       0
  4995.5    0.07       0  5003.5    0.16       0  5073.0    0.05       0
Bank Sta=4498.8,5079.8
Exp/Cntr=0.3,0.1

Type RM Length L Ch R = 1,46157,656,656,656
BEGIN DESCRIPTION:
Mapping XS e18415b1
END DESCRIPTION:
XS GIS Cut Line= 3
      2810550.97      7086573.04      2809868.71      7086015.78
      2809540.56      7085974.11
#Sta/Elev= 30
  4040.6  502.83  4064.4  500.95  4093.2  500.83  4107.5  501.48  4164.5  500.82
  4228.9  498.59  4384.0  495.17  4491.1  494.56  4569.2  493.66  4690.5  494.27
  4839.1  492.44  4950.3  493.13  4964.0  493.63  4975.7  493.13  4985.7  490.54
  4991.8  484.53  4992.5  483.73  4999.2  483.73  4999.8  484.53  5016.0  492.33
  5036.1  493.03  5044.4  494.56  5056.3  498.46  5076.5  501.41  5096.6  503.41
  5106.7  502.88  5124.3  503.49  5129.0  503.15  5204.0  506.66  5252.3  507.66
#Mann=5,-1,0
  4040.6    0.05       0  4950.3    0.16       0  4991.8    0.07       0
  4999.8    0.16       0  5124.3    0.05       0
Bank Sta=4491.1,5044.4
Exp/Cntr=0.3,0.1

Type RM Length L Ch R = 1,45501,449,449,449
BEGIN DESCRIPTION:
Mapping XS d0775379
END DESCRIPTION:
XS GIS Cut Line= 3
      2810540.61      7086302.27      2810077.05      7085666.82
      2809609.18      7085427.69
#Sta/Elev= 30
  4088.5  500.09  4205.5  499.23  4347.7  494.95  4602.0  493.22  4655.1  490.98
  4721.5  491.35  4734.6  489.59  4749.3  490.70  4755.5  489.67  4764.0  491.40
  4770.2  489.59  4784.9  492.30  4802.7  492.22  4881.4  491.45  4968.0  491.40
  4981.0  490.87  4989.7  487.94  4997.6  481.73  4999.2  481.68  4999.9  480.88
  5007.3  481.68  5012.1  490.70  5019.8  492.97  5071.1  493.22  5193.3  497.66
  5211.2  497.72  5258.6  500.08  5308.6  500.74  5321.1  502.21  5400.5  504.18
#Mann=10,-1,0
  4088.5    0.05       0  4721.5    0.12       0  4802.7    0.16       0
  4881.4    0.05       0  4968.0    0.16       0  4999.2    0.07       0
  5007.3    0.16       0  5193.3    0.12       0  5211.2    0.16       0
  5321.1    0.05       0
Bank Sta=4602,5071.1
Exp/Cntr=0.3,0.1

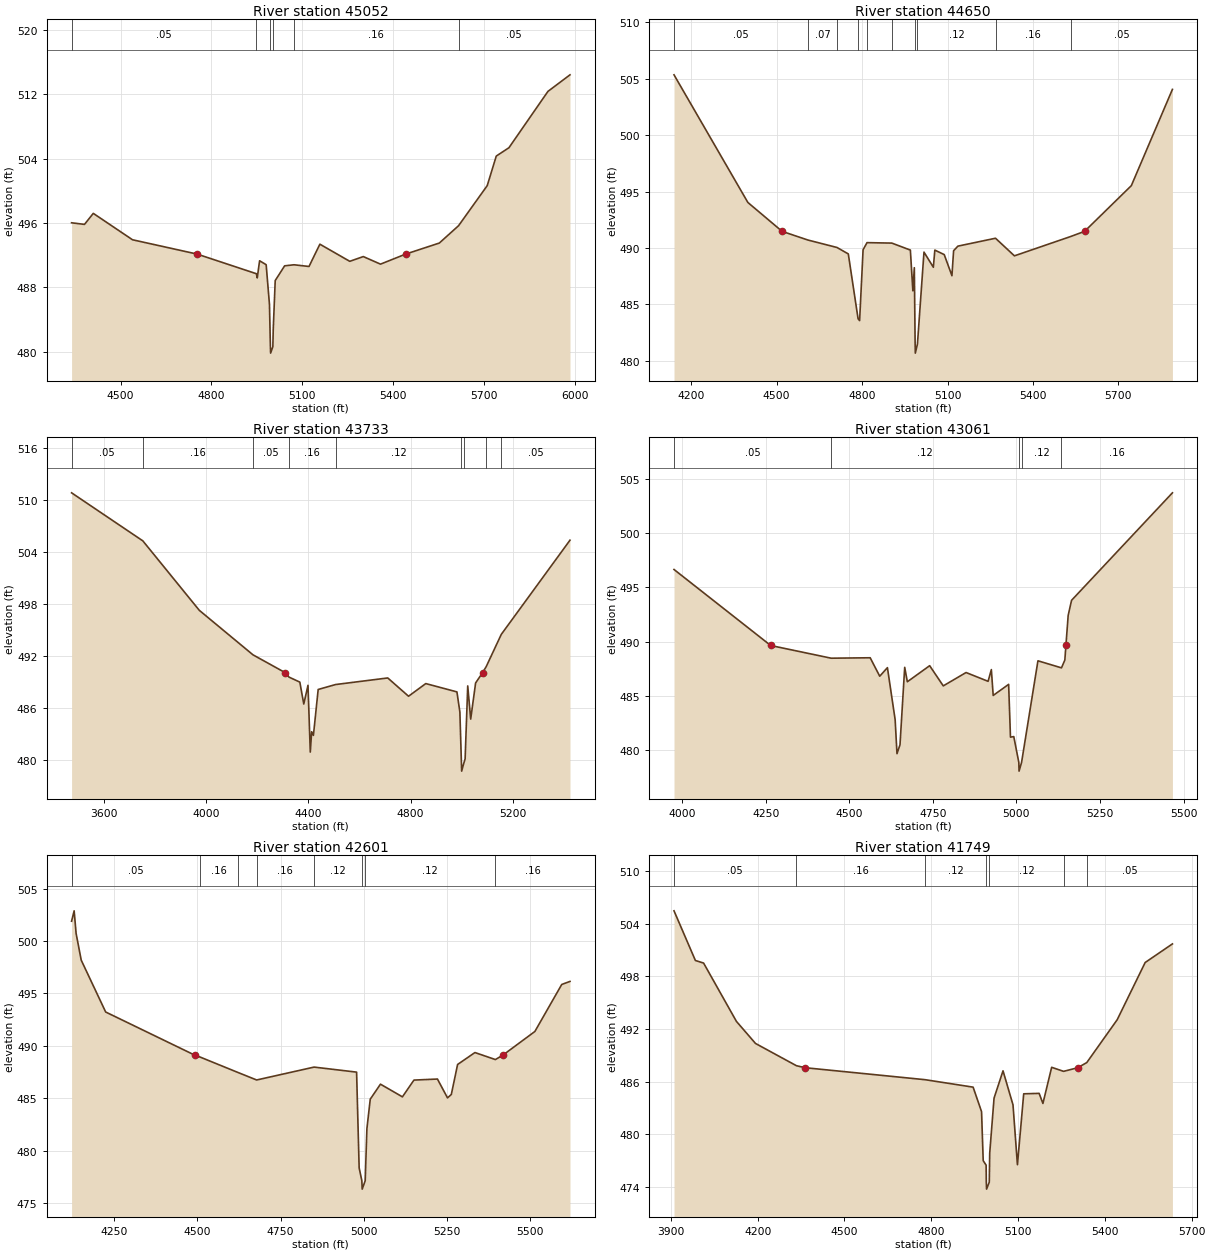
Type RM Length L Ch R = 1,45052,402,402,402
BEGIN DESCRIPTION:
REDDIG CREEK 25.0
END DESCRIPTION:
XS GIS Cut Line= 3
      2810587.48      7086047.07      2810325.00      7085425.00
      2809525.00      7084875.00
#Sta/Elev= 30
  4338.1  496.03  4380.7  495.83  4409.8  497.20  4539.3  493.92  4752.7  492.14
  4948.4  489.70  4951.3  489.18  4959.0  491.31  4980.7  490.82  4991.6  485.89
  4994.7  480.63  4995.4  479.83  5002.8  480.63  5004.1  482.81  5010.6  488.85
  5041.7  490.68  5072.8  490.81  5122.2  490.60  5158.1  493.37  5256.8  491.24
  5301.5  491.83  5358.3  490.89  5441.5  492.14  5552.5  493.51  5616.2  495.67
  5710.8  500.65  5740.6  504.32  5782.5  505.36  5911.3  512.36  5984.1  514.42
#Mann=6,-1,0
  4338.1    0.05       0  4948.4    0.12       0  4994.7    0.07       0
  5002.8    0.12       0  5072.8    0.16       0  5616.2    0.05       0
Bank Sta=4752.7,5441.5
Exp/Cntr=0.3,0.1

Type RM Length L Ch R = 1,44650,917,917,917
BEGIN DESCRIPTION:
double REDDIG CREEK 24.0
END DESCRIPTION:
XS GIS Cut Line= 3
      2811425.00      7085425.00      2810587.46      7085192.87
      2809743.73      7084937.66
#Sta/Elev= 30
  4139.4  505.35  4398.8  494.04  4519.1  491.48  4609.9  490.71  4712.0  490.05
  4751.6  489.48  4785.9  483.74  4791.3  483.57  4803.5  489.85  4817.3  490.48
  4904.5  490.44  4969.6  489.82  4978.3  486.21  4983.5  488.26  4986.3  481.49
  4987.0  480.69  4994.4  481.49  5017.4  489.64  5050.3  488.30  5055.5  489.82
  5088.5  489.42  5115.6  487.55  5121.4  489.76  5136.5  490.17  5268.6  490.87
  5335.0  489.31  5532.3  491.02  5581.5  491.48  5745.7  495.53  5890.0  504.06
#Mann=10,-1,0
  4139.4    0.05       0  4609.9    0.07       0  4712.0    0.16       0
  4785.9    0.12       0  4817.3    0.16       0  4904.5    0.12       0
  4986.3    0.07       0  4994.4    0.12       0  5268.6    0.16       0
  5532.3    0.05       0
Bank Sta=4519.1,5581.5
Exp/Cntr=0.3,0.1

Type RM Length L Ch R = 1,43733,672,672,672
BEGIN DESCRIPTION:
double REDDIG CREEK 23.0
END DESCRIPTION:
XS GIS Cut Line= 3
      2811824.98      7085124.99      2810425.00      7084625.00
      2809974.96      7084524.99
#Sta/Elev= 30
  3475.0  510.86  3753.5  505.31  3974.1  497.29  4183.9  492.15  4309.9  490.09
  4324.5  489.58  4366.9  489.00  4382.3  486.47  4398.8  488.63  4407.8  480.92
  4413.1  483.27  4420.0  482.85  4438.6  488.15  4506.7  488.72  4710.5  489.48
  4791.7  487.37  4859.1  488.83  4980.8  487.87  4992.3  485.55  4998.5  479.52
  4999.2  478.72  5006.6  479.52  5012.8  480.14  5023.0  488.56  5034.6  484.73
  5053.8  488.90  5080.9  490.09  5095.1  490.78  5154.1  494.51  5422.6  505.39
#Mann=9,-1,0
  3475.0    0.05       0  3753.5    0.16       0  4183.9    0.05       0
  4324.5    0.16       0  4506.7    0.12       0  4998.5    0.07       0
  5006.6    0.12       0  5095.1    0.16       0  5154.1    0.05       0
Bank Sta=4309.9,5080.9
Exp/Cntr=0.3,0.1

Type RM Length L Ch R = 1,43061,460,460,460
BEGIN DESCRIPTION:
double REDDIG CREEK 22.0
END DESCRIPTION:
XS GIS Cut Line= 3
      2811420.78      7084604.31      2810475.00      7084175.00
      2810025.02      7084125.00
#Sta/Elev= 30
  3975.4  496.65  4264.7  489.65  4445.7  488.48  4562.4  488.52  4591.0  486.82
  4614.0  487.61  4637.1  482.82  4642.6  479.69  4651.6  480.50  4665.7  487.64
  4673.6  486.31  4740.4  487.79  4781.1  485.93  4849.3  487.16  4915.2  486.35
  4925.0  487.43  4930.5  485.05  4976.7  486.07  4982.2  481.21  4992.1  481.26
  5007.2  478.88  5007.9  478.08  5015.4  478.88  5064.4  488.24  5134.8  487.59
  5144.9  488.31  5148.1  489.65  5154.9  492.43  5165.0  493.81  5466.8  503.71
#Mann=5,-1,0
  3975.4    0.05       0  4445.7    0.12       0  5007.2    0.07       0
  5015.4    0.12       0  5134.8    0.16       0
Bank Sta=4264.7,5148.1
Exp/Cntr=0.3,0.1

Type RM Length L Ch R = 1,42601,852,852,852
BEGIN DESCRIPTION:
REDDIG CREEK 3.1
END DESCRIPTION:
XS GIS Cut Line= 3
      2811524.98      7084374.99      2810785.38      7083922.03
      2810160.40      7084010.57
#Sta/Elev= 30
  4121.7  501.90  4129.4  502.89  4135.3  500.73  4150.7  498.18  4224.2  493.23
  4492.1  489.11  4507.2  488.94  4621.7  487.46  4678.1  486.74  4850.8  487.97
  4978.6  487.49  4986.3  478.35  4994.4  477.12  4995.4  476.32  5004.5  477.12
  5009.6  482.09  5019.7  484.91  5050.4  486.34  5116.4  485.13  5151.0  486.73
  5221.7  486.83  5252.0  485.03  5263.4  485.36  5282.3  488.22  5334.4  489.36
  5395.9  488.69  5418.4  489.11  5514.6  491.37  5595.4  495.86  5620.2  496.15
#Mann=8,-1,0
  4121.7    0.05       0  4507.2    0.16       0  4621.7    0.12       0
  4678.1    0.16       0  4850.8    0.12       0  4994.4    0.07       0
  5004.5    0.12       0  5395.9    0.16       0
Bank Sta=4492.1,5418.4
Exp/Cntr=0.3,0.1

Type RM Length L Ch R = 1,41749,732,732,732
BEGIN DESCRIPTION:
REDDIG CREEK 20.0
END DESCRIPTION:
XS GIS Cut Line= 3
      2811675.04      7084075.02      2810790.59      7083599.12
      2810165.62      7083244.97
#Sta/Elev= 30
  3910.8  505.45  3984.7  499.79  4013.0  499.50  4126.6  492.85  4192.4  490.34
  4334.0  487.80  4365.0  487.57  4778.4  486.21  4944.6  485.36  4973.8  482.57
  4979.5  476.98  4989.6  476.47  4990.2  474.54  4991.2  473.74  5000.5  474.54
  5002.0  477.84  5017.0  484.11  5048.0  487.22  5082.5  483.34  5097.8  476.52
  5119.5  484.60  5172.9  484.65  5185.9  483.50  5216.1  487.62  5257.3  487.16
  5306.0  487.57  5337.5  488.16  5442.6  493.04  5539.3  499.56  5633.5  501.68
#Mann=7,-1,0
  3910.8    0.05       0  4334.0    0.16       0  4778.4    0.12       0
  4990.2    0.07       0  5000.5    0.12       0  5257.3    0.16       0
  5337.5    0.05       0
Bank Sta=4365,5306
Exp/Cntr=0.3,0.1