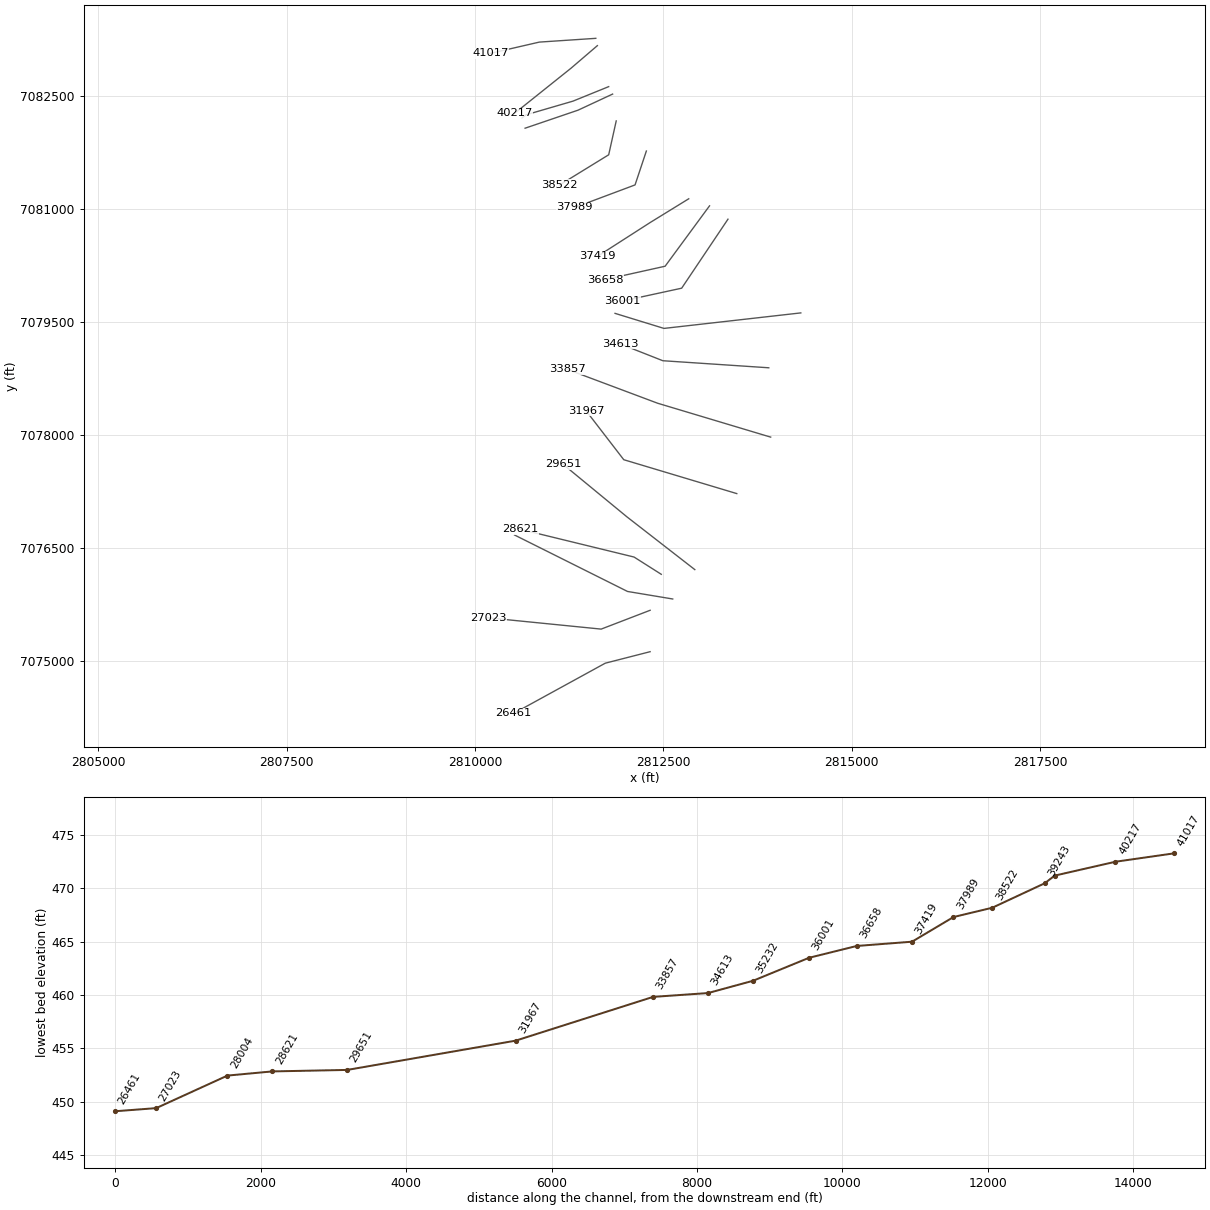
HEC-RAS study REDDIG CREEK.prj: REDDIG CREEK Base Level Engineering

--- REDDIG CREEK.g01 (geometry) --- (continued)

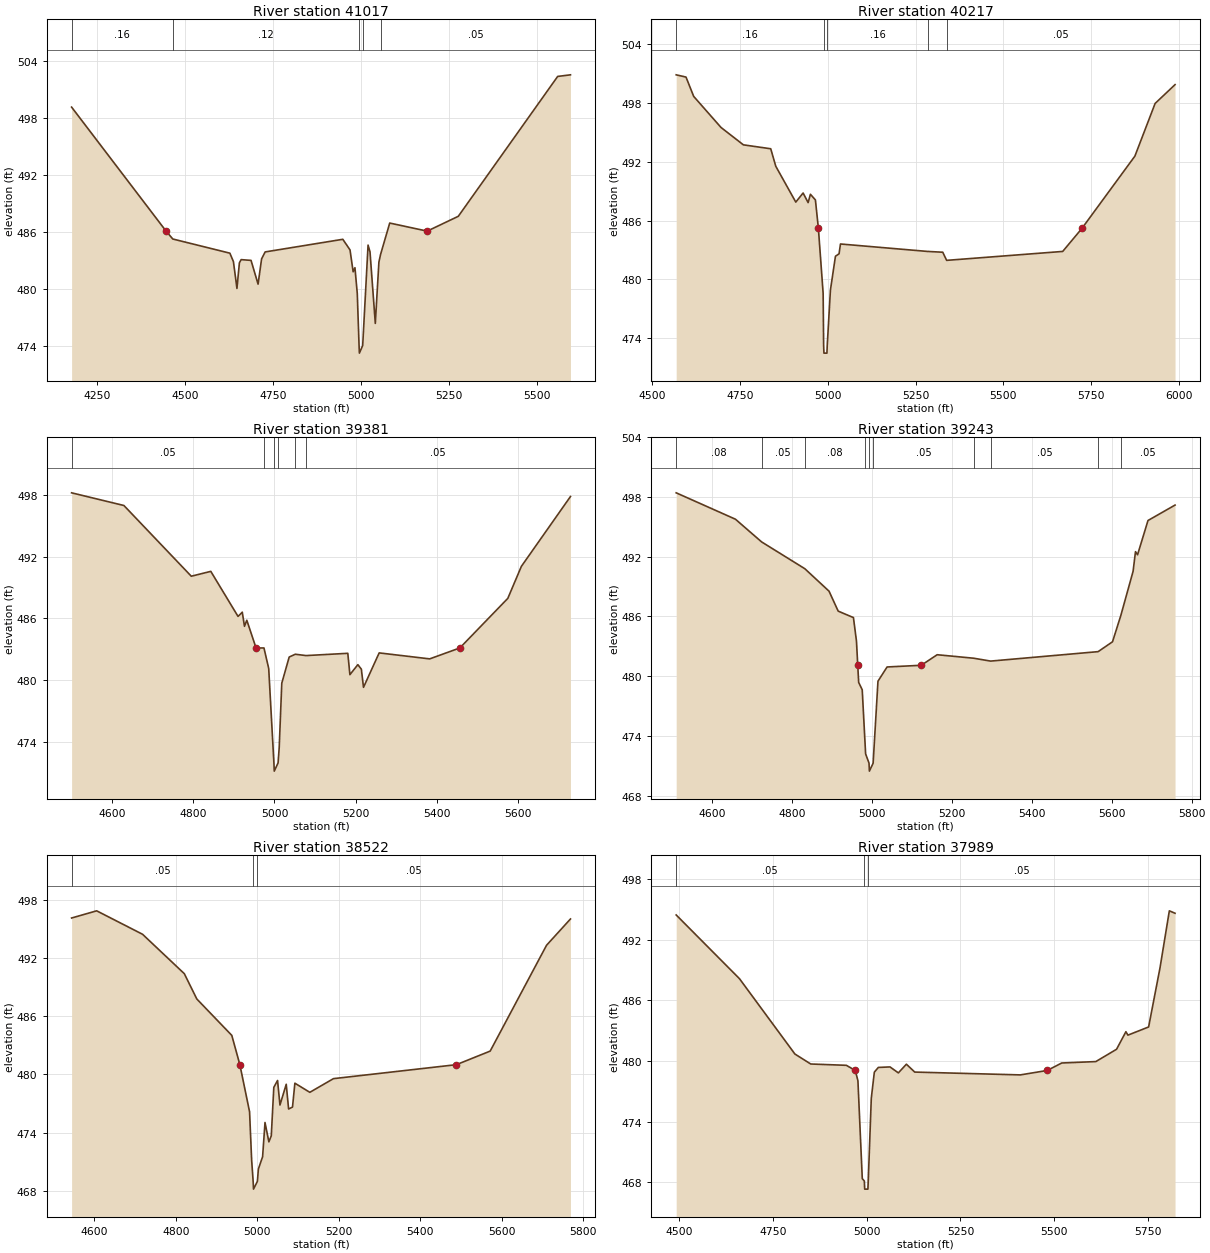
Type RM Length L Ch R = 1,41017,800,800,800
BEGIN DESCRIPTION:
REDDIG CREEK 19.0
END DESCRIPTION:
XS GIS Cut Line= 3
      2811604.13      7083271.87      2810854.17      7083221.88
      2810204.18      7083071.88
#Sta/Elev= 30
  4176.8  499.15  4445.5  486.10  4464.6  485.27  4626.9  483.78  4637.0  482.89
  4647.0  480.07  4654.0  482.77  4659.0  483.10  4687.1  483.02  4707.1  480.52
  4717.1  483.18  4727.2  483.91  4948.1  485.24  4968.6  484.12  4977.5  481.82
  4982.6  482.25  4989.2  479.54  4994.3  474.06  4995.2  473.26  5004.6  474.06
  5019.9  484.63  5025.4  483.92  5040.5  476.39  5050.7  482.83  5055.4  483.64
  5081.5  486.95  5188.1  486.10  5276.5  487.66  5559.1  502.38  5595.5  502.55
#Mann=5,-1,0
  4176.8    0.16       0  4464.6    0.12       0  4994.3    0.07       0
  5004.6    0.12       0  5055.4    0.05       0
Bank Sta=4445.5,5188.1
Exp/Cntr=0.3,0.1

Type RM Length L Ch R = 1,40217,836,836,836
BEGIN DESCRIPTION:
REDDIG CREEK 18.0
END DESCRIPTION:
XS GIS Cut Line= 3
      2811624.97      7083174.98      2811275.00      7082875.00
      2810525.01      7082275.01
#Sta/Elev= 30
  4567.8  500.86  4595.8  500.63  4617.7  498.66  4695.6  495.49  4759.3  493.72
  4837.2  493.32  4851.5  491.54  4908.6  487.88  4929.4  488.81  4943.7  487.83
  4950.3  488.68  4964.5  488.10  4973.0  485.19  4986.5  478.58  4987.9  473.28
  4988.8  472.48  4997.3  472.48  4998.2  473.28  5007.3  478.92  5021.6  482.36
  5031.9  482.61  5035.9  483.61  5283.9  482.85  5327.3  482.77  5338.4  481.94
  5669.1  482.85  5723.7  485.19  5874.8  492.57  5932.4  497.94  5989.2  499.86
#Mann=5,-1,0
  4567.8    0.16       0  4987.9    0.07       0  4998.2    0.16       0
  5283.9    0.12       0  5338.4    0.05       0
Bank Sta=4973,5723.7
Exp/Cntr=0.3,0.1

Type RM Length L Ch R = 1,39381,138,138,138
BEGIN DESCRIPTION:
Mapping XS 0af79251
END DESCRIPTION:
XS GIS Cut Line= 4
      2811774.93      7082630.35      2811301.00      7082437.66
      2810676.00      7082255.37      2810623.95      7082213.73
#Sta/Elev= 30
  4500.1  498.18  4629.0  496.95  4795.0  490.09  4843.1  490.56  4910.2  486.19
  4920.7  486.60  4926.1  485.23  4931.8  485.82  4954.6  483.13  4974.1  483.13
  4985.8  481.14  4998.6  471.98  4999.5  471.18  5008.9  471.98  5011.7  473.48
  5018.0  479.71  5036.3  482.25  5051.3  482.52  5077.8  482.39  5180.7  482.61
  5185.9  480.54  5205.5  481.51  5214.1  481.07  5219.4  479.31  5258.0  482.65
  5382.5  482.07  5456.8  483.13  5575.0  487.94  5608.5  491.05  5729.4  497.82
#Mann=6,-1,0
  4500.1    0.05       0  4974.1    0.16       0  4998.6    0.07       0
  5008.9    0.16       0  5051.3    0.08       0  5077.8    0.05       0
Bank Sta=4954.6,5456.8
Exp/Cntr=0.3,0.1

Type RM Length L Ch R = 1,39243,721,721,721
BEGIN DESCRIPTION:
Mapping XS e8496ecb
END DESCRIPTION:
XS GIS Cut Line= 3
      2811827.08      7082531.42      2811368.71      7082317.87
      2810665.59      7082078.28
#Sta/Elev= 30
  4510.0  498.41  4658.3  495.76  4723.8  493.48  4831.9  490.79  4892.6  488.53
  4915.4  486.53  4953.6  485.88  4961.2  483.52  4964.4  481.09  4966.7  479.37
  4975.6  478.63  4982.3  473.55  4984.1  472.19  4992.6  471.26  4993.5  470.46
  5002.9  471.26  5015.0  479.49  5037.8  480.92  5123.3  481.09  5163.2  482.15
  5254.5  481.80  5296.9  481.51  5566.0  482.46  5602.0  483.45  5622.8  486.09
  5653.5  490.53  5659.5  492.50  5664.7  492.19  5690.8  495.63  5758.5  497.18
#Mann=10,-1,0
  4510.0    0.08       0  4723.8    0.05       0  4831.9    0.08       0
  4982.3    0.05       0  4992.6    0.03       0  5002.9    0.05       0
  5254.5    0.08       0  5296.9    0.05       0  5566.0    0.08       0
  5622.8    0.05       0
Bank Sta=4964.4,5123.3
Exp/Cntr=0.3,0.1

Type RM Length L Ch R = 1,38522,533,533,533
BEGIN DESCRIPTION:
REDDIG CREEK 15.0
END DESCRIPTION:
XS GIS Cut Line= 3
      2811875.00      7082175.01      2811775.00      7081725.00
      2811125.00      7081325.00
#Sta/Elev= 30
  4544.4  496.12  4605.9  496.86  4718.6  494.44  4821.0  490.38  4851.7  487.77
  4937.5  484.02  4957.3  481.00  4981.1  476.15  4986.2  471.18  4989.9  468.97
  4990.8  468.17  5000.3  468.97  5002.8  470.25  5013.1  471.51  5019.0  475.04
  5028.5  473.04  5034.4  473.67  5040.6  478.66  5049.8  479.37  5055.7  476.84
  5071.1  478.98  5076.9  476.43  5086.5  476.63  5092.3  479.09  5129.0  478.15
  5187.0  479.56  5488.7  481.00  5571.6  482.40  5709.9  493.31  5768.6  496.02
#Mann=3,-1,0
  4544.4    0.05       0  4989.9    0.03       0  5000.3    0.05       0
Bank Sta=4957.3,5488.7
Exp/Cntr=0.3,0.1

Type RM Length L Ch R = 1,37989,570,570,570
BEGIN DESCRIPTION:
REDDIG CREEK 14.0
END DESCRIPTION:
XS GIS Cut Line= 3
      2812275.00      7081775.01      2812125.00      7081325.00
      2811324.96      7081024.98
#Sta/Elev= 30
  4492.9  494.47  4661.6  488.15  4809.1  480.69  4851.3  479.70  4946.2  479.57
  4970.0  479.06  4977.0  478.04  4988.6  468.34  4994.1  468.10  4995.0  467.30
  5003.6  467.30  5004.5  468.10  5012.6  476.30  5020.7  478.89  5031.3  479.36
  5062.5  479.41  5084.7  478.82  5106.1  479.68  5128.3  478.90  5409.6  478.62
  5481.3  479.06  5519.9  479.80  5610.7  479.94  5665.9  481.16  5690.8  482.90
  5696.2  482.56  5751.3  483.37  5781.6  489.22  5806.5  494.88  5821.7  494.64
#Mann=3,-1,0
  4492.9    0.05       0  4994.1    0.03       0  5004.5    0.05       0
Bank Sta=4970,5481.3
Exp/Cntr=0.3,0.1

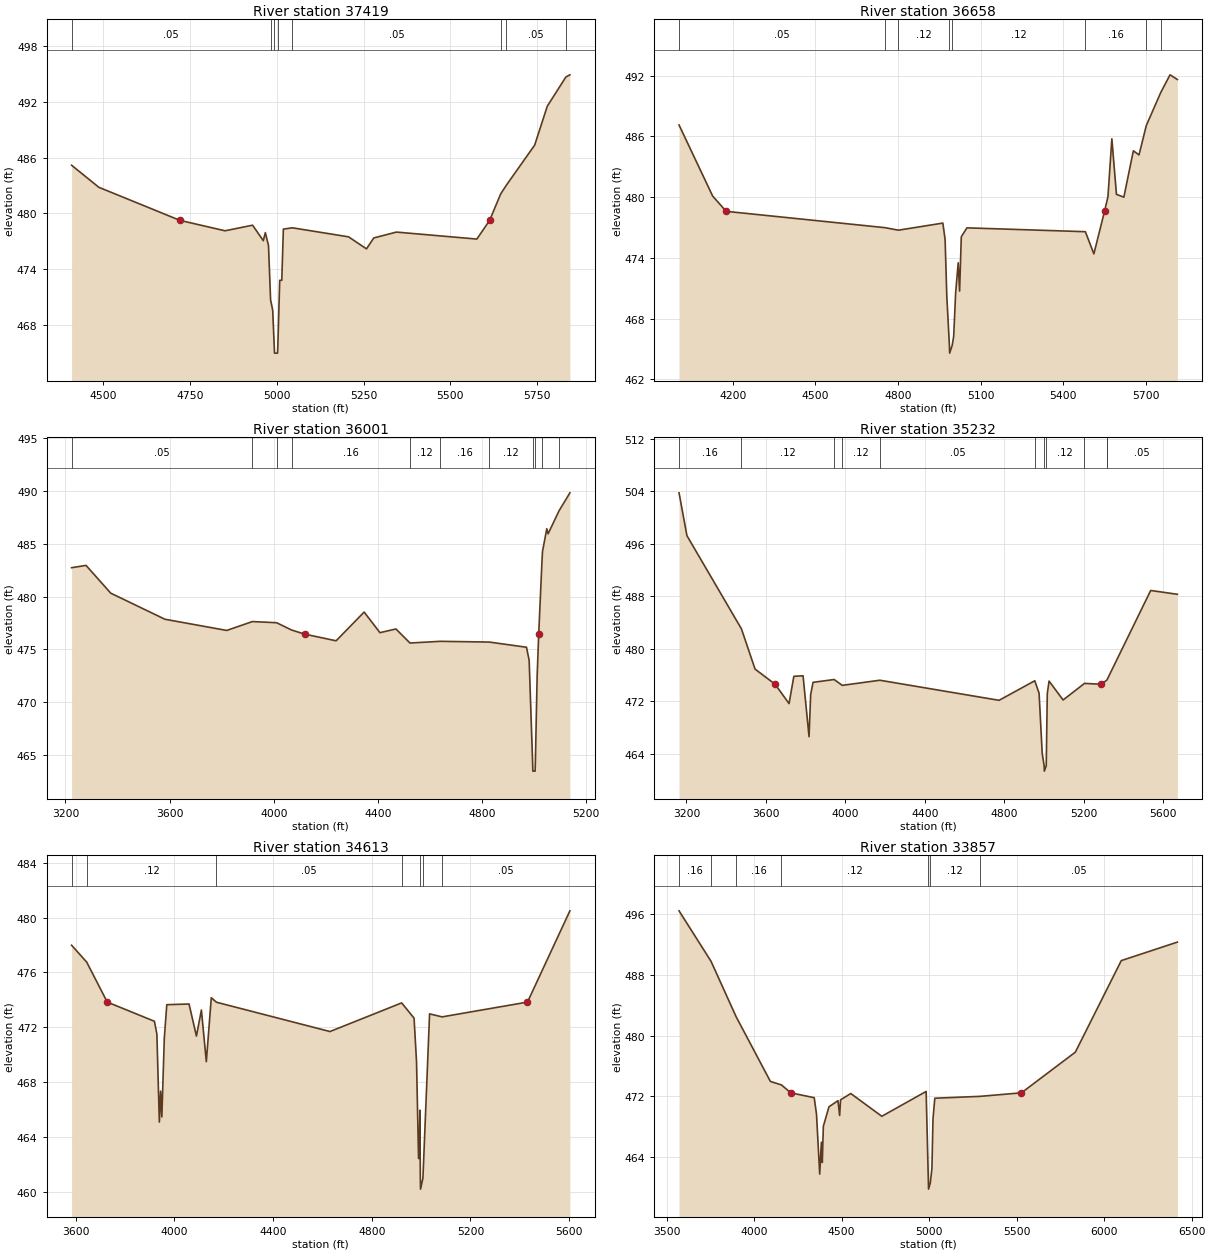
Type RM Length L Ch R = 1,37419,761,761,761
BEGIN DESCRIPTION:
REDDIG CREEK 13.0
END DESCRIPTION:
XS GIS Cut Line= 3
      2812837.46      7081140.78      2812325.00      7080825.00
      2811625.00      7080375.00
#Sta/Elev= 30
  4409.8  485.17  4488.3  482.80  4721.5  479.25  4851.4  478.13  4930.7  478.73
  4961.5  477.07  4967.4  477.93  4976.5  476.54  4982.5  470.71  4988.6  469.60
  4992.9  465.79  4993.8  464.99  5002.5  464.99  5003.4  465.79  5008.8  472.81
  5014.7  472.81  5019.3  478.31  5045.1  478.45  5206.9  477.48  5258.4  476.19
  5279.5  477.36  5344.6  477.99  5576.1  477.24  5612.9  479.25  5644.7  482.09
  5661.3  483.04  5742.5  487.33  5778.8  491.51  5832.4  494.65  5843.9  494.88
#Mann=8,-1,0
  4409.8    0.05       0  4982.5    0.16       0  4992.9    0.07       0
  5003.4    0.16       0  5045.1    0.05       0  5644.7    0.12       0
  5661.3    0.05       0  5832.4    0.16       0
Bank Sta=4721.5,5612.9
Exp/Cntr=0.3,0.1

Type RM Length L Ch R = 1,36658,657,657,657
BEGIN DESCRIPTION:
REDDIG CREEK 12.0
END DESCRIPTION:
XS GIS Cut Line= 3
      2813113.50      7081047.02      2812523.92      7080244.89
      2811729.05      7080068.08
#Sta/Elev= 30
  4004.5  487.12  4126.8  480.09  4175.9  478.59  4751.9  476.98  4801.4  476.73
  4962.6  477.43  4970.8  475.82  4977.0  470.18  4986.4  465.39  4987.3  464.59
  4996.9  465.39  5002.0  466.26  5009.1  470.55  5018.4  473.51  5023.5  470.71
  5029.6  476.08  5050.1  476.96  5480.3  476.58  5511.1  474.39  5549.8  478.59
  5562.3  480.05  5576.4  485.75  5593.1  480.27  5620.0  479.99  5654.5  484.57
  5675.0  484.16  5701.5  487.06  5754.1  490.33  5787.7  492.07  5814.3  491.61
#Mann=8,-1,0
  4004.5    0.05       0  4751.9    0.07       0  4801.4    0.12       0
  4986.4    0.07       0  4996.9    0.12       0  5480.3    0.16       0
  5701.5    0.05       0  5754.1    0.16       0
Bank Sta=4175.9,5549.8
Exp/Cntr=0.3,0.1

Type RM Length L Ch R = 1,36001,769,769,769
BEGIN DESCRIPTION:
Mapping XS d2dd7c91
END DESCRIPTION:
XS GIS Cut Line= 3
      2813358.29      7080869.93      2812743.71      7079953.28
      2811952.06      7079781.41
#Sta/Elev= 30
  3223.7  482.74  3279.2  482.96  3374.1  480.33  3582.3  477.86  3819.6  476.80
  3918.0  477.64  4011.2  477.53  4068.7  476.84  4119.0  476.45  4239.6  475.82
  4347.2  478.54  4407.9  476.59  4469.3  476.94  4523.3  475.61  4639.8  475.77
  4827.6  475.70  4970.7  475.21  4980.9  473.97  4994.2  464.28  4995.0  463.48
  5003.8  463.48  5004.7  464.28  5011.6  472.49  5017.6  476.45  5029.7  483.10
  5032.1  484.27  5048.6  486.43  5053.7  485.95  5095.7  488.13  5137.4  489.83
#Mann=11,-1,0
  3223.7    0.05       0  3918.0    0.16       0  4011.2    0.05       0
  4068.7    0.16       0  4523.3    0.12       0  4639.8    0.16       0
  4827.6    0.12       0  4994.2    0.07       0  5004.7    0.12       0
  5029.7    0.16       0  5095.7    0.05       0
Bank Sta=4119,5017.6
Exp/Cntr=0.3,0.1

Type RM Length L Ch R = 1,35232,619,619,619
BEGIN DESCRIPTION:
double REDDIG CREEK 11.0
END DESCRIPTION:
XS GIS Cut Line= 3
      2814325.03      7079625.00      2812508.75      7079418.95
      2811859.42      7079618.75
#Sta/Elev= 30
  3162.9  503.74  3202.7  497.21  3476.9  483.01  3545.4  476.88  3646.3  474.57
  3716.5  471.62  3740.6  475.78  3786.9  475.86  3817.1  466.58  3825.2  472.98
  3837.2  474.86  3943.4  475.29  3984.1  474.40  4173.3  475.18  4773.2  472.12
  4952.8  475.10  4974.5  473.20  4990.2  464.05  5000.0  462.13  5000.8  461.33
  5010.5  462.13  5015.7  473.12  5024.7  475.05  5095.3  472.17  5202.9  474.70
  5286.8  474.57  5314.6  475.18  5316.6  475.26  5536.0  488.86  5670.2  488.28
#Mann=11,-1,0
  3162.9    0.16       0  3476.9    0.12       0  3943.4    0.16       0
  3984.1    0.12       0  4173.3    0.05       0  4952.8    0.12       0
  5000.0    0.07       0  5010.5    0.12       0  5202.9    0.05       0
  5314.6    0.07       0  5316.6    0.05       0
Bank Sta=3646.3,5286.8
Exp/Cntr=0.3,0.1

Type RM Length L Ch R = 1,34613,756,756,756
BEGIN DESCRIPTION:
double Mapping XS 8c02d967
END DESCRIPTION:
XS GIS Cut Line= 3
      2813899.92      7078895.99      2812493.71      7078989.74
      2811926.02      7079213.69
#Sta/Elev= 30
  3583.7  477.98  3644.9  476.75  3728.3  473.83  3919.4  472.43  3929.4  471.50
  3939.4  465.07  3944.5  467.33  3949.5  465.45  3959.5  471.19  3969.5  473.64
  4059.7  473.69  4089.7  471.35  4109.8  473.25  4129.8  469.48  4149.9  474.15
  4170.8  473.82  4630.9  471.68  4921.4  473.77  4971.7  472.66  4981.7  469.47
  4989.9  462.42  4993.0  462.42  4995.4  465.94  4997.1  460.98  4998.0  460.18
  5007.6  460.98  5034.6  472.97  5085.1  472.75  5431.4  473.83  5603.3  480.49
#Mann=7,-1,0
  3583.7    0.16       0  3644.9    0.12       0  4170.8    0.05       0
  4921.4    0.12       0  4997.1    0.07       0  5007.6    0.12       0
  5085.1    0.05       0
Bank Sta=3728.3,5431.4
Exp/Cntr=0.3,0.1

Type RM Length L Ch R = 1,33857,1890,1890,1890
BEGIN DESCRIPTION:
double REDDIG CREEK 10.0
END DESCRIPTION:
XS GIS Cut Line= 3
      2813924.95      7077975.01      2812425.00      7078425.00
      2811225.00      7078875.00
#Sta/Elev= 30
  3570.9  496.38  3753.8  489.75  3896.9  482.48  4092.9  473.97  4156.0  473.51
  4209.7  472.47  4343.4  471.83  4356.5  469.65  4374.8  461.80  4384.3  465.98
  4389.5  463.32  4395.6  468.08  4427.8  470.64  4479.2  471.44  4488.7  469.50
  4493.9  471.55  4552.2  472.38  4729.7  469.39  4982.9  472.65  4995.9  460.62
  4996.7  459.82  5006.5  460.62  5016.0  462.52  5022.1  469.05  5032.5  471.76
  5292.2  472.01  5527.5  472.47  5835.5  477.81  6098.1  489.84  6418.5  492.27
#Mann=7,-1,0
  3570.9    0.16       0  3753.8    0.12       0  3896.9    0.16       0
  4156.0    0.12       0  4995.9    0.07       0  5006.5    0.12       0
  5292.2    0.05       0
Bank Sta=4209.7,5527.5
Exp/Cntr=0.3,0.1

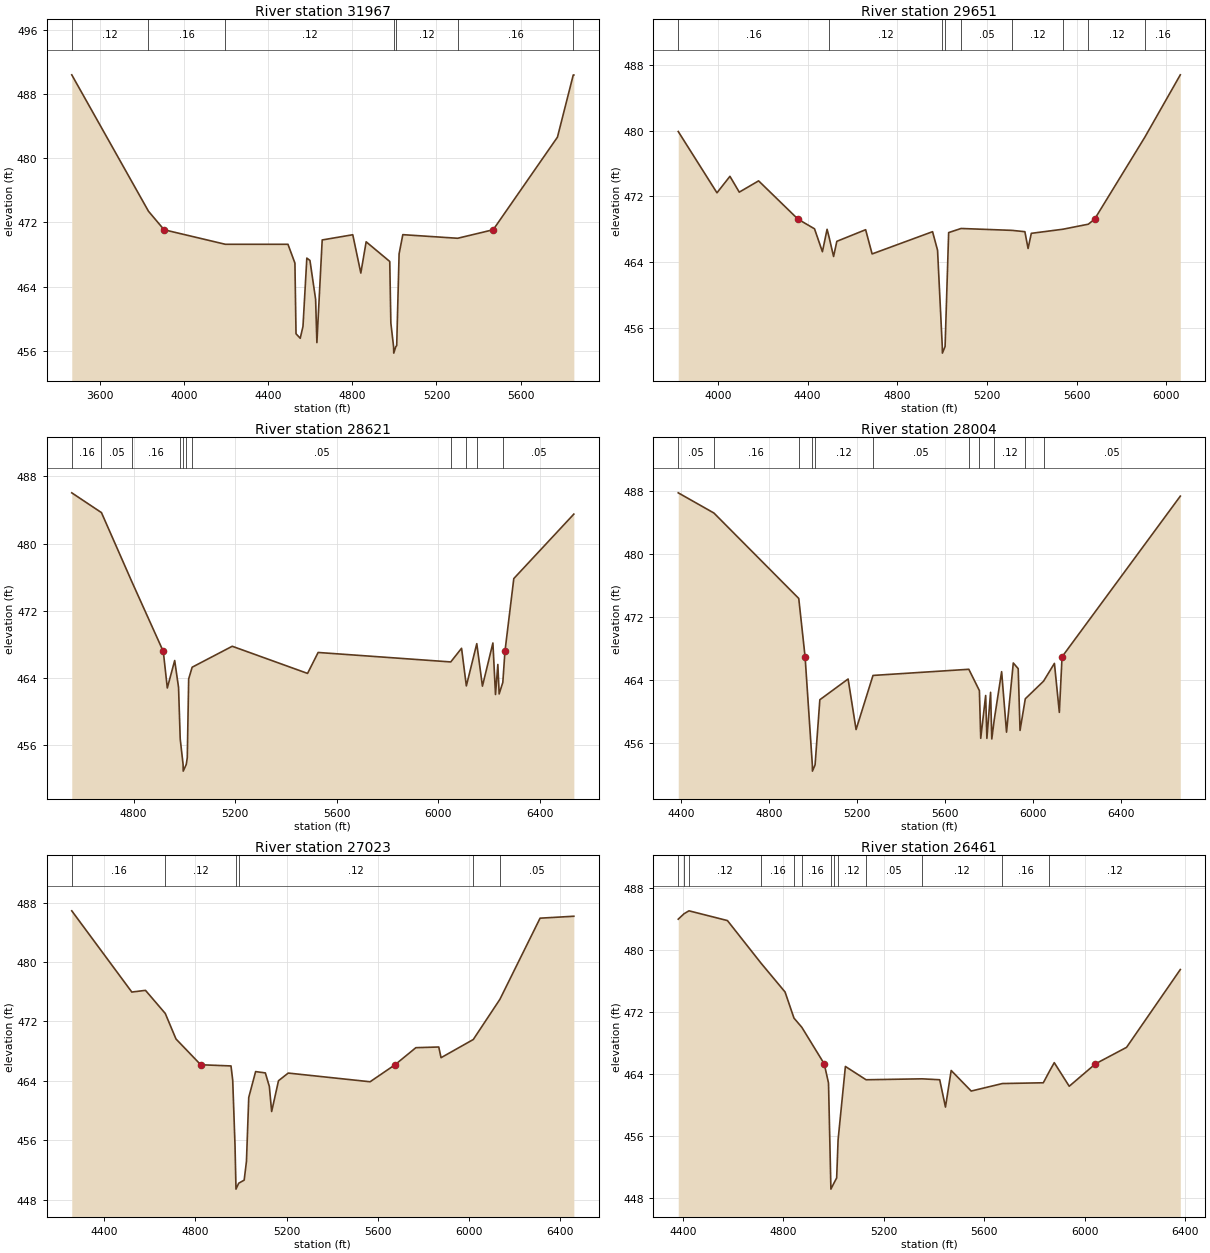
Type RM Length L Ch R = 1,31967,2316,2316,2316
BEGIN DESCRIPTION:
double REDDIG CREEK 9.0
END DESCRIPTION:
XS GIS Cut Line= 3
      2813475.05      7077224.99      2811975.00      7077675.00
      2811474.97      7078325.03
#Sta/Elev= 30
  3466.9  490.37  3831.4  473.39  3905.7  471.08  4197.0  469.27  4494.4  469.27
  4527.5  466.93  4532.7  458.13  4552.7  457.57  4565.8  459.05  4584.1  467.55
  4598.9  467.26  4625.8  462.43  4631.9  457.03  4657.1  469.81  4802.4  470.46
  4840.7  465.69  4866.0  469.58  4978.2  467.13  4983.4  459.47  4996.4  456.52
  4997.2  455.72  5007.0  456.52  5011.2  456.66  5022.6  468.08  5040.3  470.47
  5300.8  470.02  5469.7  471.08  5775.2  482.61  5850.3  490.35  5853.1  490.35
#Mann=7,-1,0
  3466.9    0.12       0  3831.4    0.16       0  4197.0    0.12       0
  4996.4    0.07       0  5007.0    0.12       0  5300.8    0.16       0
  5850.3    0.05       0
Bank Sta=3905.7,5469.7
Exp/Cntr=0.3,0.1

Type RM Length L Ch R = 1,29651,1030,1030,1030
BEGIN DESCRIPTION:
REDDIG CREEK 8.0
END DESCRIPTION:
XS GIS Cut Line= 3
      2812918.09      7076215.25      2812018.06      7076915.28
      2811169.02      7077614.48
#Sta/Elev= 30
  3822.5  479.88  3995.3  472.44  4053.2  474.44  4094.8  472.52  4181.1  473.89
  4356.9  469.24  4430.5  468.07  4465.8  465.29  4486.6  468.01  4495.3  467.09
  4515.6  464.71  4530.1  466.55  4658.6  467.96  4687.5  465.02  4957.2  467.72
  4979.5  465.47  5000.6  453.78  5001.1  452.98  5013.1  453.78  5029.0  467.61
  5084.4  468.11  5312.0  467.88  5369.1  467.72  5383.4  465.68  5397.8  467.52
  5539.1  468.02  5652.2  468.63  5680.2  469.24  5904.3  479.19  6062.6  486.76
#Mann=9,-1,0
  3822.5    0.16       0  4495.3    0.12       0  5000.6    0.07       0
  5013.1    0.12       0  5084.4    0.05       0  5312.0    0.12       0
  5539.1    0.16       0  5652.2    0.12       0  5904.3    0.16       0
Bank Sta=4356.9,5680.2
Exp/Cntr=0.3,0.1

Type RM Length L Ch R = 1,28621,617,617,617
BEGIN DESCRIPTION:
REDDIG CREEK 7.0
END DESCRIPTION:
XS GIS Cut Line= 3
      2812472.85      7076152.95      2812111.77      7076382.10
      2810605.11      7076750.09
#Sta/Elev= 30
  4556.3  486.05  4673.3  483.69  4792.4  475.49  4917.0  467.12  4932.8  462.76
  4961.9  466.04  4977.1  462.83  4983.7  456.68  4995.0  453.64  4995.5  452.84
  5007.5  453.64  5011.5  454.44  5017.0  463.84  5030.7  465.24  5188.7  467.74
  5485.5  464.50  5527.2  467.00  6049.8  465.87  6092.4  467.50  6111.3  463.01
  6152.4  468.05  6174.7  462.98  6215.9  468.13  6226.2  461.98  6235.4  465.57
  6240.6  462.05  6255.0  463.43  6263.4  467.12  6298.3  475.82  6534.9  483.51
#Mann=11,-1,0
  4556.3    0.16       0  4673.3    0.05       0  4792.4    0.16       0
  4983.7    0.12       0  4995.0    0.07       0  5007.5    0.12       0
  5030.7    0.05       0  6049.8    0.16       0  6111.3    0.05       0
  6152.4    0.16       0  6255.0    0.05       0
Bank Sta=4917,6263.4
Exp/Cntr=0.3,0.1

Type RM Length L Ch R = 1,28004,981,981,981
BEGIN DESCRIPTION:
REDDIG CREEK 6.0
END DESCRIPTION:
XS GIS Cut Line= 3
      2812625.01      7075825.00      2812025.00      7075925.00
      2810525.03      7076674.98
#Sta/Elev= 30
  4385.6  487.73  4548.0  485.17  4934.2  474.34  4963.0  466.94  4996.0  453.25
  4996.5  452.45  5008.5  453.25  5030.2  461.50  5158.8  464.13  5195.1  457.72
  5272.1  464.58  5708.3  465.36  5756.4  462.66  5762.5  456.61  5784.9  462.04
  5790.5  456.60  5807.3  462.44  5812.8  456.53  5824.1  458.99  5857.6  465.06
  5879.9  457.39  5910.7  466.16  5933.0  465.44  5941.4  457.61  5965.3  461.62
  6048.3  463.85  6097.9  466.11  6120.3  459.90  6132.6  466.94  6670.9  487.31
#Mann=11,-1,0
  4385.6    0.05       0  4548.0    0.16       0  4934.2    0.12       0
  4996.0    0.07       0  5008.5    0.12       0  5272.1    0.05       0
  5708.3    0.12       0  5756.4    0.07       0  5824.1    0.12       0
  5965.3    0.16       0  6048.3    0.05       0
Bank Sta=4963,6132.6
Exp/Cntr=0.3,0.1

Type RM Length L Ch R = 1,27023,562,562,562
BEGIN DESCRIPTION:
REDDIG CREEK 5.0
END DESCRIPTION:
XS GIS Cut Line= 3
      2812325.04      7075675.01      2811675.00      7075425.00
      2810175.04      7075575.00
#Sta/Elev= 30
  4257.3  486.88  4520.9  475.94  4580.9  476.17  4667.7  473.06  4714.8  469.62
  4823.4  466.15  4956.3  465.99  4963.8  464.06  4973.9  455.28  4977.6  450.20
  4978.1  449.40  4990.2  450.20  5014.1  450.61  5024.1  453.14  5034.2  461.75
  5064.3  465.23  5107.0  465.05  5124.6  463.23  5134.7  459.85  5164.8  464.00
  5207.5  465.03  5566.8  463.86  5676.3  466.15  5767.8  468.45  5868.3  468.54
  5878.3  467.10  6019.8  469.55  6136.6  474.96  6313.0  485.89  6461.2  486.15
#Mann=6,-1,0
  4257.3    0.16       0  4667.7    0.12       0  4977.6    0.07       0
  4990.2    0.12       0  6019.8    0.16       0  6136.6    0.05       0
Bank Sta=4823.4,5676.3
Exp/Cntr=0.3,0.1

Type RM Length L Ch R = 1,26461,1452,1452,1452
BEGIN DESCRIPTION:
REDDIG CREEK 4.0
END DESCRIPTION:
XS GIS Cut Line= 3
      2812324.99      7075125.00      2811729.82      7074972.38
      2810514.50      7074305.69
#Sta/Elev= 30
  4380.9  484.01  4403.9  484.71  4423.7  485.09  4577.0  483.83  4710.9  478.32
  4806.5  474.60  4842.1  471.22  4873.4  470.03  4962.6  465.31  4979.7  462.83
  4988.7  449.91  4989.2  449.11  5001.7  449.91  5012.2  450.56  5017.9  455.49
  5047.0  464.97  5129.4  463.25  5352.5  463.37  5422.8  463.25  5445.7  459.72
  5468.5  464.45  5548.3  461.79  5672.5  462.76  5835.6  462.86  5858.8  464.27
  5879.2  465.46  5938.9  462.41  6043.5  465.31  6167.3  467.44  6381.5  477.50
#Mann=13,-1,0
  4380.9    0.05       0  4403.9    0.16       0  4423.7    0.12       0
  4710.9    0.16       0  4842.1    0.12       0  4873.4    0.16       0
  4988.7    0.07       0  5001.7    0.16       0  5017.9    0.12       0
  5129.4    0.05       0  5352.5    0.12       0  5672.5    0.16       0
  5858.8    0.12       0
Bank Sta=4962.6,6043.5
Exp/Cntr=0.3,0.1