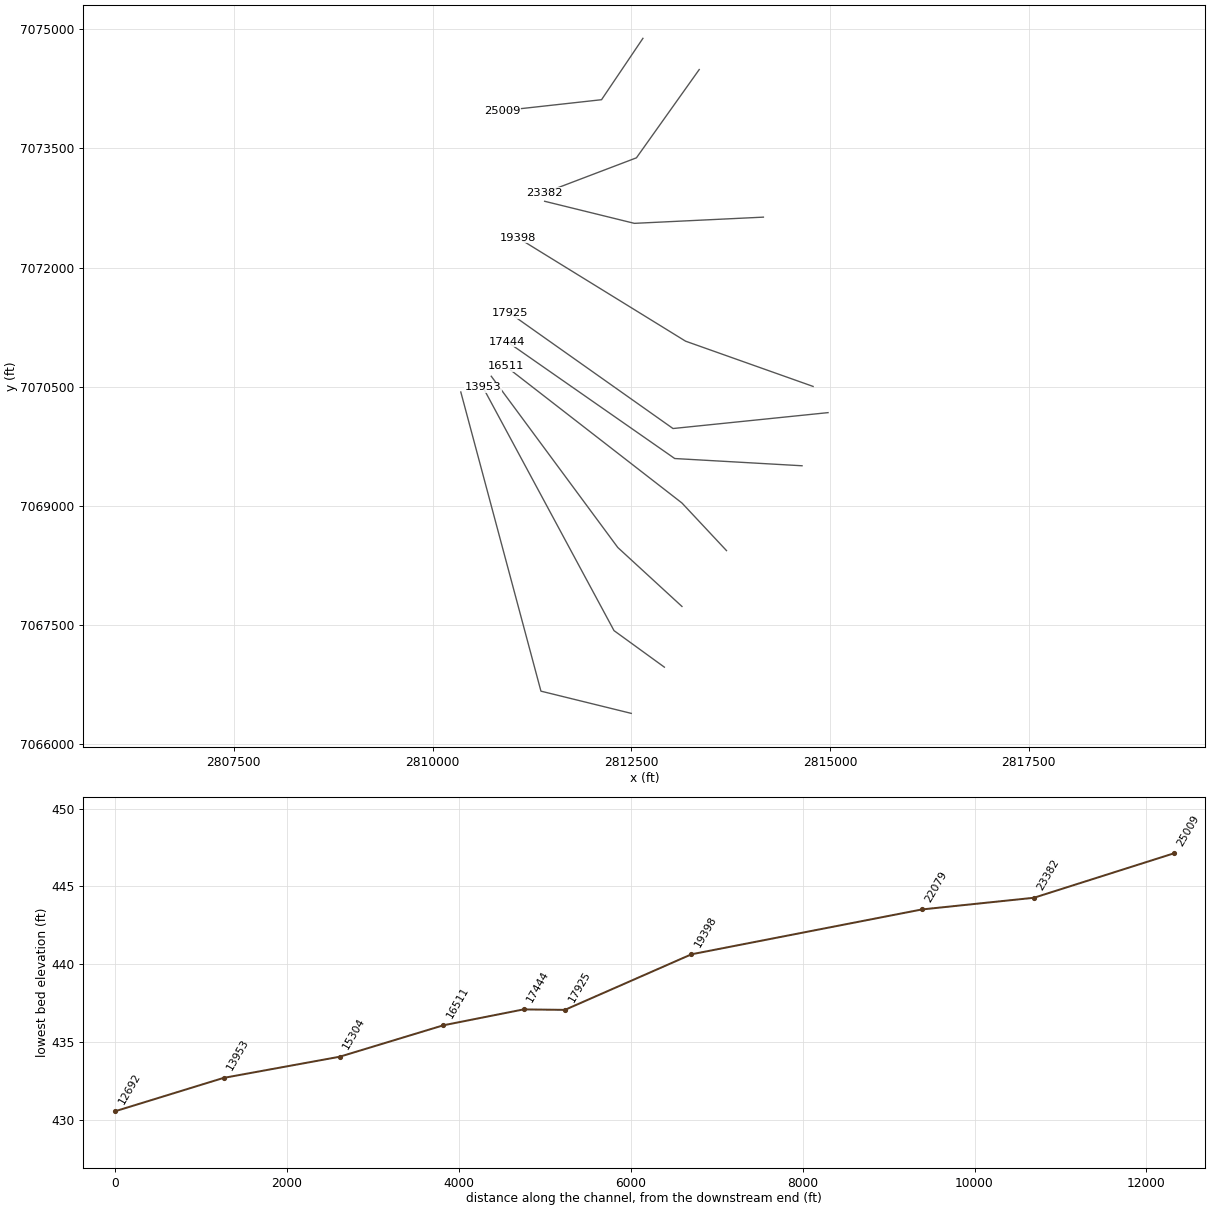
HEC-RAS study REDDIG CREEK.prj: REDDIG CREEK Base Level Engineering

--- REDDIG CREEK.g01 (geometry) --- (continued)

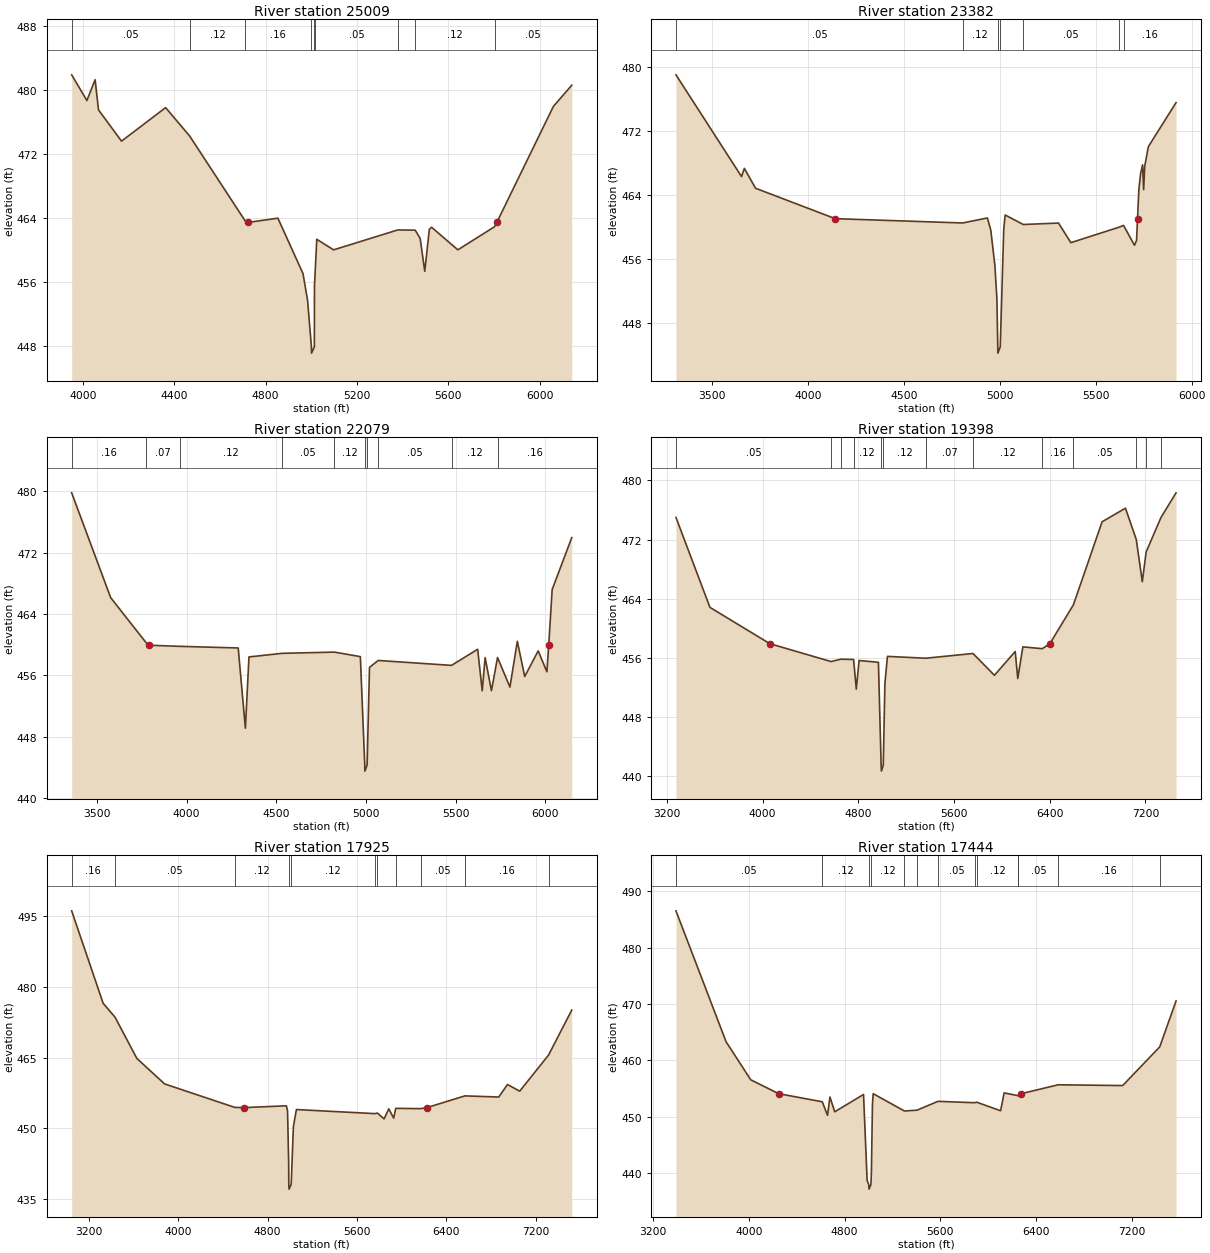
Type RM Length L Ch R = 1,25009,1627,1627,1627
BEGIN DESCRIPTION:
REDDIG CREEK 3.0
END DESCRIPTION:
XS GIS Cut Line= 3
      2812646.75      7074886.08      2812125.93      7074113.53
      2810875.00      7073975.00
#Sta/Elev= 30
  3950.8  481.91  4017.5  478.70  4053.5  481.30  4068.4  477.52  4169.2  473.62
  4362.3  477.81  4467.6  474.26  4710.7  463.65  4723.6  463.46  4854.0  463.99
  4963.9  457.07  4984.1  453.72  5000.8  447.92  5001.3  447.12  5013.8  447.92
  5014.2  455.49  5015.8  456.42  5024.3  461.35  5098.0  460.03  5379.2  462.52
  5455.4  462.49  5477.1  461.46  5497.2  457.35  5517.3  462.60  5527.4  462.85
  5642.2  460.03  5802.8  462.92  5812.9  463.46  6060.6  477.96  6141.1  480.61
#Mann=9,-1,0
  3950.8    0.05       0  4467.6    0.12       0  4710.7    0.16       0
  5000.8    0.07       0  5013.8    0.16       0  5015.8    0.05       0
  5379.2    0.16       0  5455.4    0.12       0  5802.8    0.05       0
Bank Sta=4723.6,5812.9
Exp/Cntr=0.3,0.1

Type RM Length L Ch R = 1,23382,1303,1303,1303
BEGIN DESCRIPTION:
Mapping XS 10e5141d
END DESCRIPTION:
XS GIS Cut Line= 3
      2813354.80      7074493.19      2812564.89      7073382.10
      2811402.49      7072939.70
#Sta/Elev= 30
  3311.7  479.04  3653.5  466.33  3668.3  467.35  3726.6  464.87  4142.2  461.07
  4806.7  460.53  4935.4  461.16  4953.0  459.62  4974.4  455.22  4984.9  451.01
  4989.3  445.07  4989.8  444.27  5002.3  445.07  5020.4  459.70  5027.9  461.53
  5121.9  460.34  5306.1  460.52  5370.3  458.07  5619.9  459.99  5645.1  460.22
  5702.0  457.75  5712.7  458.34  5717.9  461.07  5724.9  464.72  5734.1  466.73
  5744.3  467.80  5749.7  464.70  5755.5  467.63  5774.4  470.07  5918.7  475.57
#Mann=7,-1,0
  3311.7    0.05       0  4806.7    0.12       0  4989.3    0.07       0
  5002.3    0.12       0  5121.9    0.05       0  5619.9    0.12       0
  5645.1    0.16       0
Bank Sta=4142.2,5717.9
Exp/Cntr=0.3,0.1

Type RM Length L Ch R = 1,22079,2681,2681,2681
BEGIN DESCRIPTION:
double Mapping XS 68eaa225
END DESCRIPTION:
XS GIS Cut Line= 3
      2814162.11      7072635.57      2812538.85      7072557.45
      2811410.37      7072835.23
#Sta/Elev= 30
  3359.2  479.81  3576.6  466.14  3775.3  460.23  3787.5  459.94  3963.6  459.79
  4287.4  459.58  4327.4  449.12  4347.4  458.41  4531.8  458.88  4823.6  459.04
  4968.2  458.45  4992.8  444.32  4993.4  443.52  5005.9  444.32  5019.2  457.05
  5067.7  457.95  5476.4  457.31  5622.1  459.41  5647.4  454.00  5663.6  458.32
  5698.9  454.01  5732.8  458.34  5801.9  454.48  5843.1  460.45  5884.3  455.86
  5959.4  459.20  6007.9  456.47  6018.0  459.94  6037.3  467.20  6146.5  473.97
#Mann=10,-1,0
  3359.2    0.16       0  3775.3    0.07       0  3963.6    0.12       0
  4531.8    0.05       0  4823.6    0.12       0  4992.8    0.07       0
  5005.9    0.12       0  5067.7    0.05       0  5476.4    0.12       0
  5732.8    0.16       0
Bank Sta=3787.5,6018
Exp/Cntr=0.3,0.1

Type RM Length L Ch R = 1,19398,1473,1473,1473
BEGIN DESCRIPTION:
REDDIG CREEK 2.0
END DESCRIPTION:
XS GIS Cut Line= 3
      2814787.36      7070504.89      2813183.17      7071074.34
      2811074.98      7072375.01
#Sta/Elev= 30
  3276.0  475.00  3560.0  462.82  4060.3  457.90  4571.9  455.48  4654.7  455.80
  4760.7  455.76  4783.0  451.75  4806.5  455.62  4968.1  455.38  4990.7  441.44
  4993.1  440.64  5008.5  441.44  5022.2  452.49  5043.5  456.18  5364.3  455.93
  5758.2  456.57  5937.5  453.62  6111.3  456.84  6132.6  453.18  6175.2  457.47
  6337.1  457.22  6400.8  457.90  6597.5  463.16  6837.5  474.41  7032.6  476.25
  7123.0  472.01  7173.4  466.29  7205.4  470.31  7329.2  474.98  7455.4  478.33
#Mann=13,-1,0
  3276.0    0.05       0  4571.9    0.12       0  4654.7    0.16       0
  4760.7    0.12       0  4990.7    0.07       0  5008.5    0.12       0
  5364.3    0.07       0  5758.2    0.12       0  6337.1    0.16       0
  6597.5    0.05       0  7123.0    0.16       0  7205.4    0.05       0
  7329.2    0.16       0
Bank Sta=4060.3,6400.8
Exp/Cntr=0.3,0.1

Type RM Length L Ch R = 1,17925,481,481,481
BEGIN DESCRIPTION:
REDDIG CREEK 1.0
END DESCRIPTION:
XS GIS Cut Line= 3
      2814974.99      7070175.00      2813025.00      7069975.00
      2810974.99      7071425.00
#Sta/Elev= 30
  3049.0  496.20  3330.5  476.55  3436.3  473.62  3632.0  464.83  3880.2  459.42
  4506.8  454.44  4586.7  454.39  4969.0  454.77  4979.1  453.68  4989.1  442.71
  4990.2  437.87  4992.7  437.07  5008.1  437.87  5012.3  438.43  5031.4  450.40
  5058.4  453.98  5760.7  453.11  5782.7  453.23  5842.1  452.00  5884.4  454.12
  5927.9  452.16  5946.6  454.23  6168.0  454.17  6225.3  454.39  6564.7  456.88
  6867.8  456.64  6945.3  459.30  7054.7  457.89  7312.7  465.55  7520.2  475.11
#Mann=11,-1,0
  3049.0    0.16       0  3436.3    0.05       0  4506.8    0.12       0
  4990.2    0.07       0  5008.1    0.12       0  5760.7    0.07       0
  5782.7    0.12       0  5946.6    0.16       0  6168.0    0.05       0
  6564.7    0.16       0  7312.7    0.05       0
Bank Sta=4586.7,6225.3
Exp/Cntr=0.3,0.1

Type RM Length L Ch R = 1,17444,933,933,933
BEGIN DESCRIPTION:
Mapping XS 559f373a
END DESCRIPTION:
XS GIS Cut Line= 3
      2814648.18      7069506.24      2813046.66      7069597.38
      2810938.64      7071067.79
#Sta/Elev= 30
  3392.4  486.55  3811.0  463.28  4016.6  456.53  4249.5  454.06  4613.8  452.62
  4657.6  450.21  4677.7  453.47  4717.7  450.84  4958.1  453.92  4988.2  438.66
  5001.8  437.90  5004.2  437.10  5019.7  437.90  5023.8  440.11  5032.5  452.17
  5038.6  454.06  5300.0  450.98  5405.2  451.13  5579.3  452.70  5886.9  452.45
  5902.2  452.55  6102.1  451.03  6131.8  454.20  6251.0  453.69  6251.3  453.69
  6274.5  454.06  6583.2  455.64  7121.1  455.50  7430.6  462.38  7566.7  470.53
#Mann=13,-1,0
  3392.4    0.05       0  4613.8    0.12       0  5001.8    0.07       0
  5019.7    0.12       0  5300.0    0.05       0  5405.2    0.12       0
  5579.3    0.05       0  5886.9    0.16       0  5902.2    0.12       0
  6251.0    0.16       0  6251.3    0.05       0  6583.2    0.16       0
  7430.6    0.05       0
Bank Sta=4249.5,6274.5
Exp/Cntr=0.3,0.1

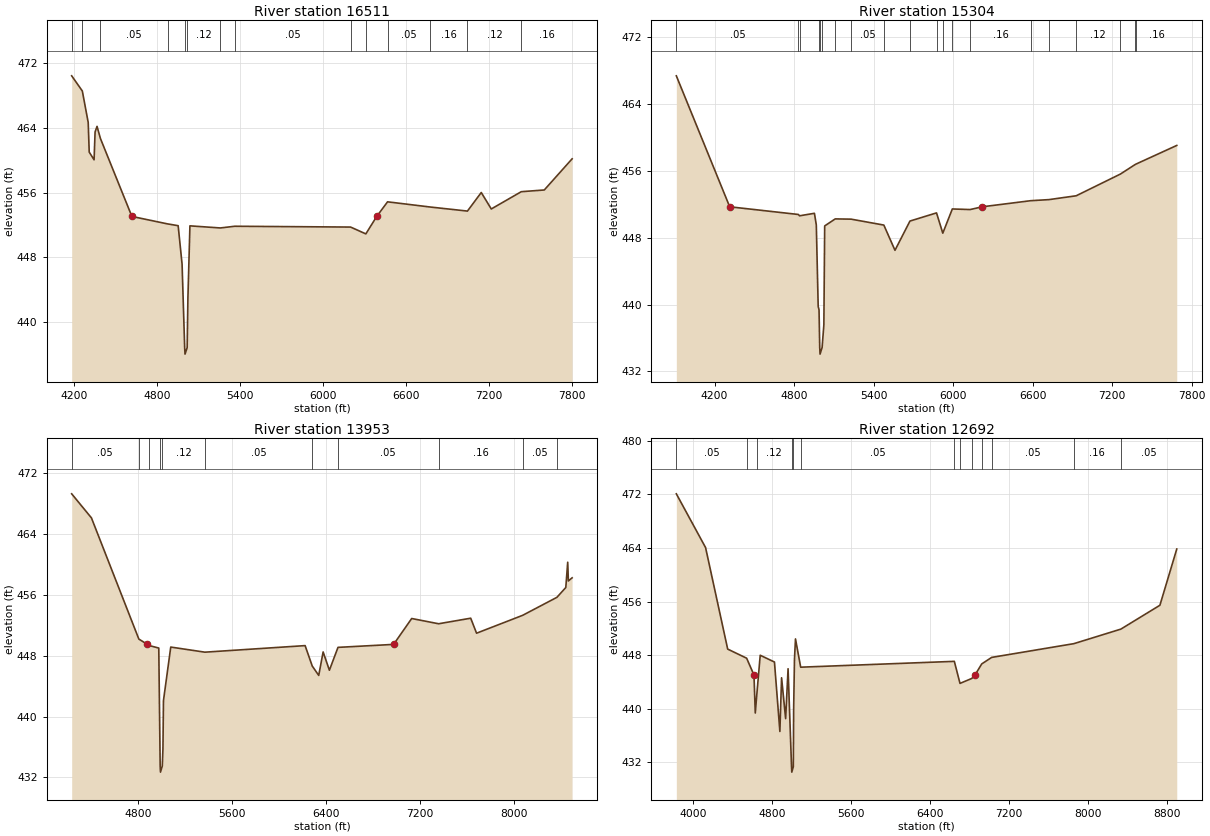
Type RM Length L Ch R = 1,16511,1207,1207,1207
BEGIN DESCRIPTION:
Mapping XS ee371b9c
END DESCRIPTION:
XS GIS Cut Line= 3
      2813697.74      7068438.49      2813137.81      7069037.48
      2810924.29      7070756.22
#Sta/Elev= 30
  4180.2  470.38  4257.2  468.51  4299.8  464.63  4307.1  460.98  4342.3  460.03
  4349.6  463.46  4363.7  464.15  4388.2  462.66  4616.0  453.05  4874.2  452.13
  4950.9  451.91  4979.3  447.16  4998.1  436.88  5000.6  436.08  5016.1  436.88
  5021.6  443.06  5036.1  451.89  5256.4  451.63  5360.8  451.84  6199.1  451.74
  6309.5  450.90  6388.3  453.05  6466.7  454.85  6775.9  454.21  7045.0  453.71
  7145.0  456.00  7217.4  453.97  7434.8  456.10  7601.1  456.31  7802.6  460.15
#Mann=14,-1,0
  4180.2    0.05       0  4257.2    0.08       0  4388.2    0.05       0
  4874.2    0.12       0  4998.1    0.07       0  5016.1    0.12       0
  5256.4    0.07       0  5360.8    0.05       0  6199.1    0.16       0
  6309.5    0.12       0  6466.7    0.05       0  6775.9    0.16       0
  7045.0    0.12       0  7434.8    0.16       0
Bank Sta=4616,6388.3
Exp/Cntr=0.3,0.1

Type RM Length L Ch R = 1,15304,1351,1351,1351
BEGIN DESCRIPTION:
Mapping XS 54268c5f
END DESCRIPTION:
XS GIS Cut Line= 3
      2813137.79      7067735.42      2812330.52      7068477.59
      2810738.88      7070633.04
#Sta/Elev= 30
  3911.7  467.40  4314.4  451.71  4832.8  450.79  4841.2  450.63  4953.7  450.93
  4967.9  449.53  4982.1  439.77  4988.4  439.37  4993.7  434.86  4996.2  434.06
  5011.7  434.86  5024.9  437.57  5031.1  449.42  5110.9  450.26  5230.4  450.23
  5477.5  449.52  5561.5  446.50  5674.5  450.00  5875.0  450.98  5922.3  448.55
  5994.3  451.45  6128.5  451.38  6219.9  451.71  6585.4  452.44  6723.2  452.57
  6929.0  453.03  7262.2  455.63  7372.3  456.76  7381.8  456.84  7687.7  459.06
#Mann=20,-1,0
  3911.7    0.05       0  4832.8    0.07       0  4841.2    0.12       0
  4988.4    0.08       0  4993.7    0.07       0  5011.7    0.08       0
  5110.9    0.12       0  5230.4    0.05       0  5477.5    0.12       0
  5674.5    0.16       0  5875.0    0.12       0  5922.3    0.16       0
  5994.3    0.05       0  6128.5    0.16       0  6585.4    0.12       0
  6723.2    0.16       0  6929.0    0.12       0  7262.2    0.16       0
  7372.3    0.12       0  7381.8    0.16       0
Bank Sta=4314.4,6219.9
Exp/Cntr=0.3,0.1

Type RM Length L Ch R = 1,13953,1261,1261,1261
BEGIN DESCRIPTION:
Mapping XS 19cb7a25
END DESCRIPTION:
XS GIS Cut Line= 3
      2812916.55      7066971.38      2812282.91      7067431.42
      2810633.62      7070495.62
#Sta/Elev= 30
  4233.7  469.24  4402.0  466.08  4805.8  450.17  4878.9  449.47  4891.6  449.33
  4975.6  448.99  4987.5  433.50  4990.0  432.70  5005.5  433.50  5011.1  435.78
  5015.5  442.09  5077.6  449.12  5368.3  448.45  6222.2  449.31  6282.9  446.63
  6338.2  445.40  6375.6  448.48  6429.0  446.08  6502.3  449.08  6976.2  449.47
  7130.1  452.87  7359.4  452.18  7632.8  452.91  7682.6  450.94  8075.6  453.29
  8367.1  455.65  8442.9  456.94  8459.1  460.26  8464.8  457.80  8496.6  458.21
#Mann=11,-1,0
  4233.7    0.05       0  4805.8    0.16       0  4891.6    0.12       0
  4987.5    0.07       0  5005.5    0.12       0  5368.3    0.05       0
  6282.9    0.12       0  6502.3    0.05       0  7359.4    0.16       0
  8075.6    0.05       0  8367.1    0.16       0
Bank Sta=4878.9,6976.2
Exp/Cntr=0.3,0.1

Type RM Length L Ch R = 1,12692,0,0,0
BEGIN DESCRIPTION:
Mapping XS 2a41c6df
END DESCRIPTION:
XS GIS Cut Line= 3
      2812499.88      7066389.76      2811363.90      7066669.42
      2810355.82      7070434.91
#Sta/Elev= 30
  3830.1  472.09  4126.3  464.07  4350.1  448.92  4542.1  447.56  4616.4  445.05
  4629.6  439.38  4644.7  442.07  4679.6  448.00  4823.8  446.99  4878.7  436.63
  4895.9  444.64  4937.1  438.54  4961.7  445.99  4996.8  431.36  4999.3  430.56
  5014.8  431.36  5018.2  439.93  5026.5  447.37  5036.8  450.44  5089.4  446.22
  6645.5  447.09  6702.9  443.80  6822.4  444.54  6854.6  445.05  6923.1  446.71
  7023.7  447.68  7855.8  449.73  8331.9  451.90  8727.3  455.46  8898.1  463.85
#Mann=13,-1,0
  3830.1    0.05       0  4542.1    0.07       0  4644.7    0.12       0
  4996.8    0.07       0  5014.8    0.12       0  5089.4    0.05       0
  6645.5    0.07       0  6702.9    0.05       0  6822.4    0.08       0
  6923.1     0.1       0  7023.7    0.05       0  7855.8    0.16       0
  8331.9    0.05       0
Bank Sta=4616.4,6854.6
Exp/Cntr=0.3,0.1

Chan Stop Cuts=-1