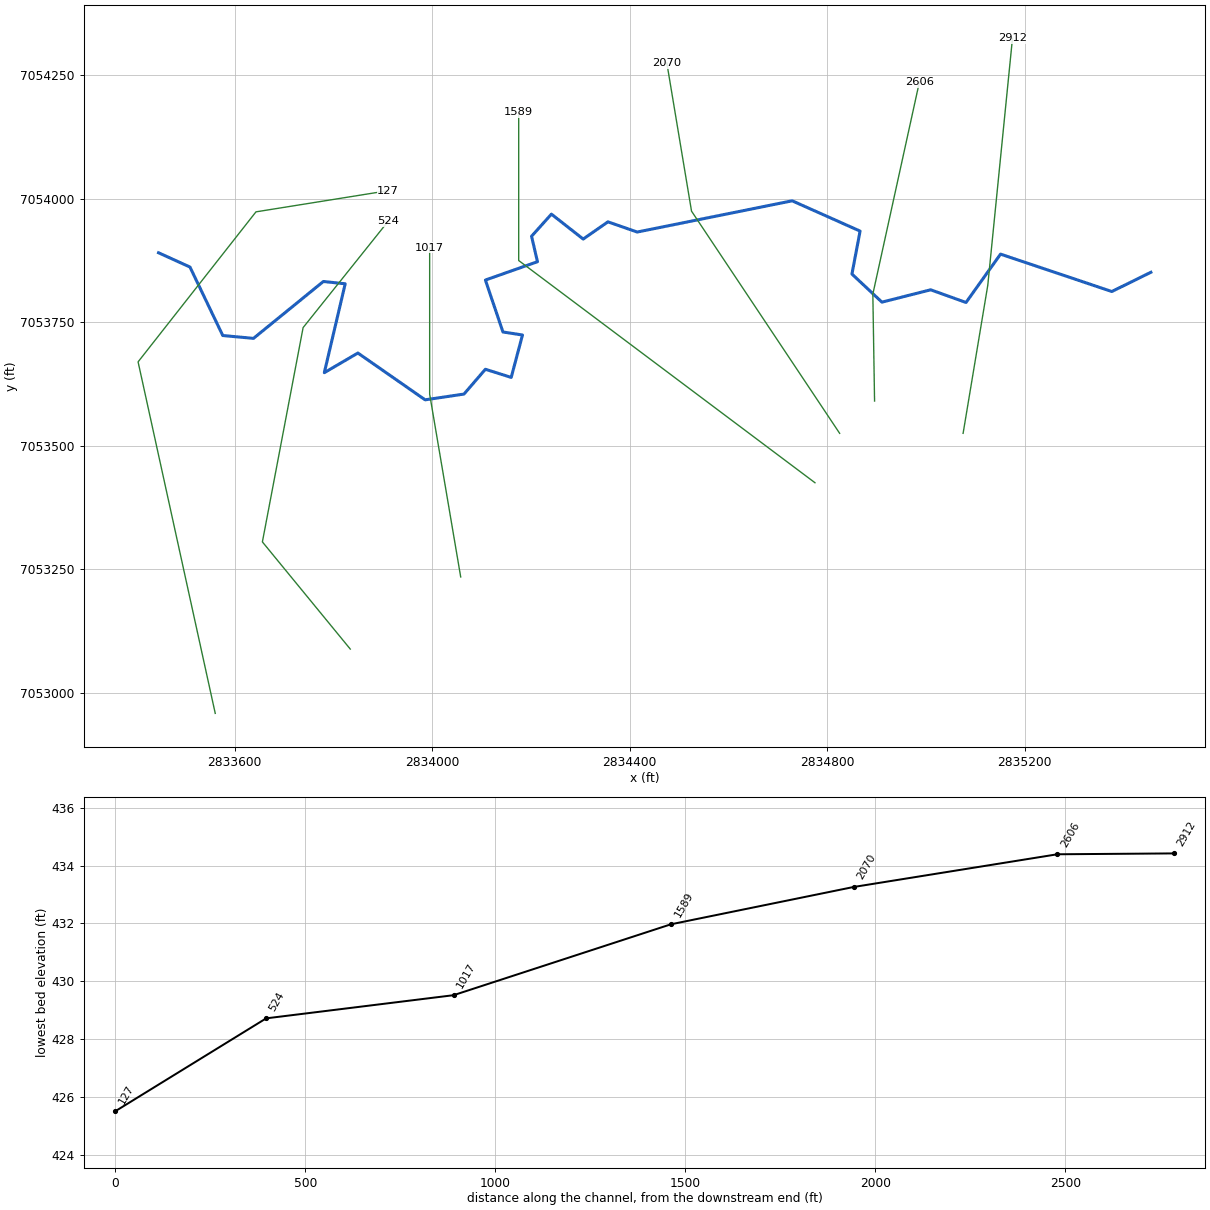
--- ROCK BRANCH.prj (project) ---

Proj Title=ROCK BRANCH Base Level Engineering
Current Plan=p01
Default Exp/Contr=0.3,0.1
English Units
Geom File=g01
Flow File=f01
Plan File=p01
BEGIN DESCRIPTION:
ROCK BRANCH
END DESCRIPTION:

--- ROCK BRANCH.p01 (plan) ---

Plan Title=Multiple Run
Short Identifier=Multiple
Geom File=g01
Flow File=f01
Subcritical Flow
K Sum by GR= 0
Std Step Tol= 0.01
Critical Tol= 0.01
Num of Std Step Trials= 20
Max Error Tol= 0.3
Flow Tol Ratio= 0.001
Split Flow NTrial= 30
Split Flow Tol= 0.02
Split Flow Ratio= 0.02
Log Output Level= 0
Friction Slope Method= 1
Unsteady Friction Slope Method= 2
Unsteady Bridges Friction Slope Method= 1
Parabolic Critical Depth
Global Vel Dist=  1 , 1 , 1
Global Log Level= 0
CheckData=True
Encroach Param= -1, 0, 0, 0
BEGIN DESCRIPTION:
Multiple Run
END DESCRIPTION:

--- ROCK BRANCH.f01 (steady flow) ---

Flow Title=Multiple
Number of Profiles=7
Profile Names=10-year,25-year,50-year,1pct_min,100-year,1pct_plu,500-year
River Rch & RM= ROCK BRANCH,Reach-1,2912
     536     712     854     510    1017    2029    1443
Boundary for River Rch & Prof#=ROCK BRANCH,Reach-1,1
Up Type=0
Dn Type=3
Dn Slope=0.005
Boundary for River Rch & Prof#=ROCK BRANCH,Reach-1,2
Up Type=0
Dn Type=3
Dn Slope=0.005
Boundary for River Rch & Prof#=ROCK BRANCH,Reach-1,3
Up Type=0
Dn Type=3
Dn Slope=0.005
Boundary for River Rch & Prof#=ROCK BRANCH,Reach-1,4
Up Type=0
Dn Type=3
Dn Slope=0.005
Boundary for River Rch & Prof#=ROCK BRANCH,Reach-1,5
Up Type=0
Dn Type=3
Dn Slope=0.005
Boundary for River Rch & Prof#=ROCK BRANCH,Reach-1,6
Up Type=0
Dn Type=3
Dn Slope=0.005
Boundary for River Rch & Prof#=ROCK BRANCH,Reach-1,7
Up Type=0
Dn Type=3
Dn Slope=0.005

--- ROCK BRANCH.g01 (geometry) ---

Geom Title=Existing Conditions

River Reach=ROCK BRANCH,Reach-1
Reach XY= 30
      2835455.27      7053851.17      2835376.23      7053812.23
      2835150.80      7053887.95      2835080.92      7053789.99
      2835009.34      7053815.70      2834910.58      7053790.69
      2834849.89      7053847.59      2834866.36      7053934.57
      2834728.87      7053995.93      2834415.03      7053932.66
      2834355.74      7053953.33      2834305.62      7053918.45
      2834241.27      7053968.93      2834201.03      7053924.14
      2834213.02      7053872.59      2834107.57      7053835.45
      2834143.10      7053730.27      2834182.68      7053724.13
      2834159.85      7053638.28      2834107.54      7053654.76
      2834064.22      7053604.54      2833985.52      7053592.85
      2833849.35      7053687.67      2833781.33      7053647.83
      2833823.66      7053827.87      2833779.40      7053832.51
      2833637.91      7053717.34      2833575.72      7053723.07
      2833509.28      7053861.80      2833445.59      7053890.71

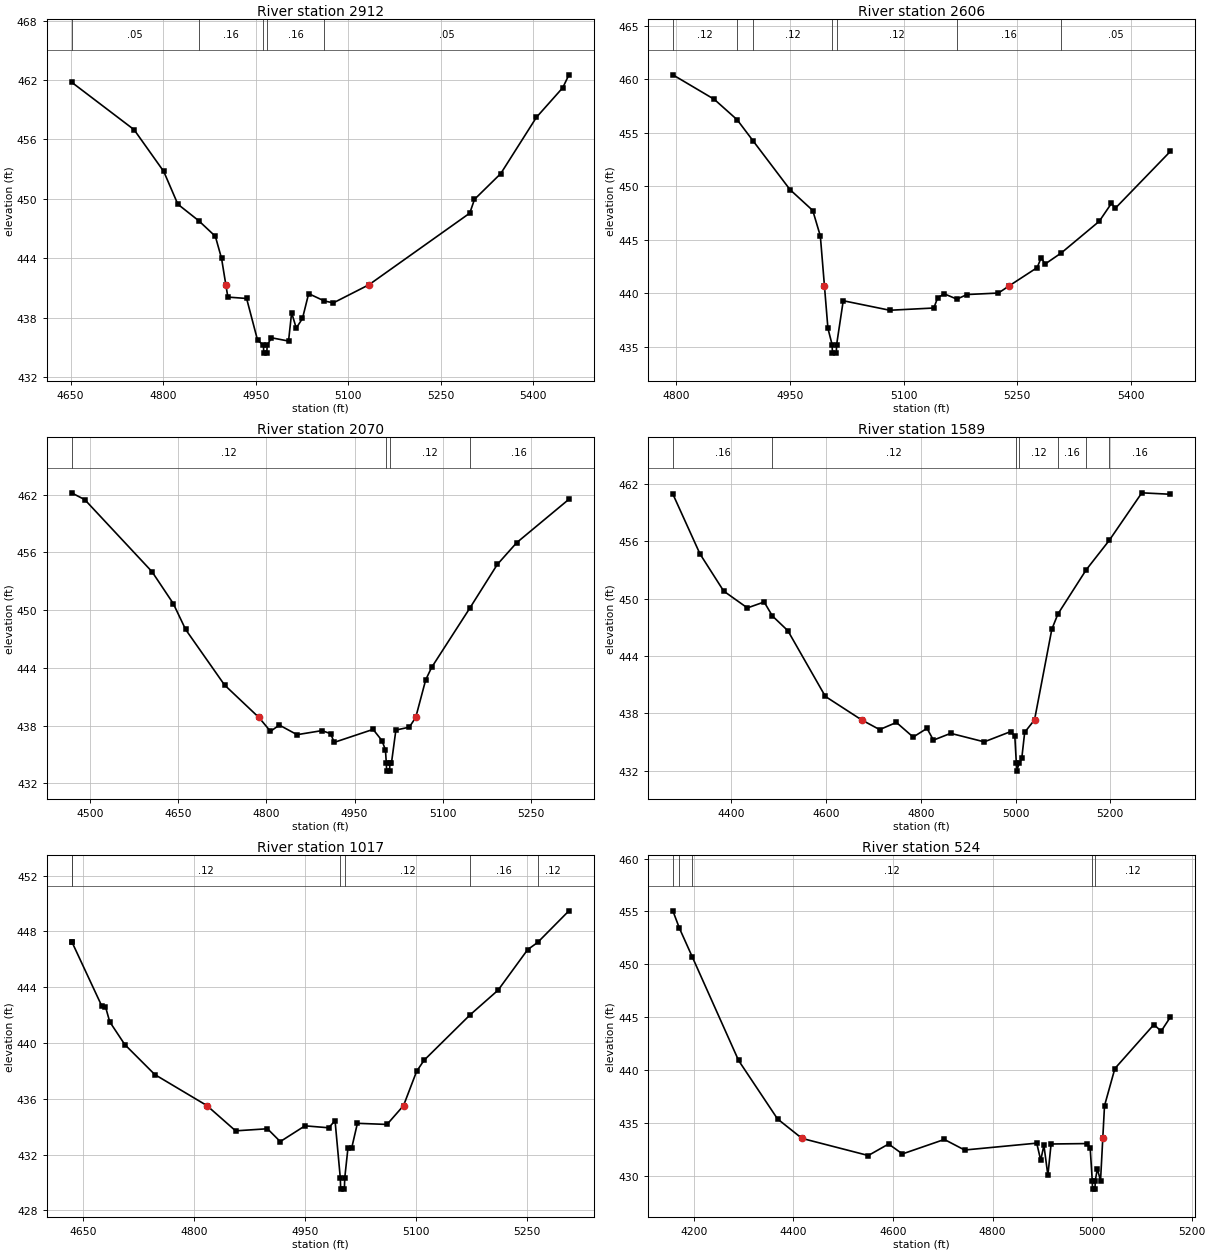
Type RM Length L Ch R = 1,2912,306,306,306
BEGIN DESCRIPTION:
ROCK BRANCH 4.0
END DESCRIPTION:
XS GIS Cut Line= 3
      2835075.00      7053524.99      2835125.00      7053825.00
      2835175.00      7054324.96
#Sta/Elev= 30
  4651.4  461.79  4752.8  456.99  4800.9  452.77  4823.8  449.46  4857.7  447.79
  4884.6  446.22  4894.7  443.98  4901.6  441.33  4904.9  440.08  4935.3  439.94
  4953.0  435.74  4962.6  435.22  4963.1  434.42  4968.1  434.42  4968.6  435.22
  4975.6  435.97  5003.3  435.64  5008.3  438.50  5015.8  436.95  5025.9  437.92
  5035.9  440.43  5061.6  439.68  5076.1  439.50  5133.8  441.33  5297.2  448.56
  5304.8  449.95  5347.5  452.56  5405.3  458.24  5448.0  461.23  5458.0  462.53
#Mann=5,-1,0
  4651.4    0.05       0  4857.7    0.16       0  4962.6    0.07       0
  4968.6    0.16       0  5061.6    0.05       0
Bank Sta=4901.6,5133.8
Exp/Cntr=0.3,0.1

Type RM Length L Ch R = 1,2606,536,536,536
BEGIN DESCRIPTION:
Mapping XS 03ef4c79
END DESCRIPTION:
XS GIS Cut Line= 3
      2834895.70      7053590.44      2834892.21      7053806.94
      2834986.50      7054236.49
#Sta/Elev= 30
  4795.6  460.42  4850.2  458.13  4880.4  456.22  4901.6  454.23  4950.2  449.68
  4980.2  447.73  4990.2  445.34  4995.6  440.68  5000.2  436.71  5005.7  435.19
  5006.2  434.39  5011.2  434.39  5011.7  435.19  5020.4  439.29  5081.8  438.40
  5139.9  438.61  5145.0  439.56  5153.5  439.94  5170.4  439.44  5183.7  439.87
  5225.1  440.01  5239.3  440.68  5276.3  442.39  5281.6  443.32  5286.7  442.72
  5308.1  443.76  5358.2  446.72  5374.3  448.40  5379.4  447.94  5451.9  453.25
#Mann=7,-1,0
  4795.6    0.12       0  4880.4    0.16       0  4901.6    0.12       0
  5005.7    0.07       0  5011.7    0.12       0  5170.4    0.16       0
  5308.1    0.05       0
Bank Sta=4995.6,5239.3
Exp/Cntr=0.3,0.1

Type RM Length L Ch R = 1,2070,481,481,481
BEGIN DESCRIPTION:
ROCK BRANCH 3.0
END DESCRIPTION:
XS GIS Cut Line= 3
      2834825.00      7053525.00      2834525.00      7053975.00
      2834475.00      7054275.02
#Sta/Elev= 30
  4469.1  462.20  4491.6  461.49  4605.8  454.00  4641.9  450.69  4662.9  447.99
  4729.0  442.22  4787.4  438.84  4807.1  437.40  4822.1  438.05  4852.2  437.05
  4894.3  437.47  4909.3  437.16  4915.3  436.25  4981.4  437.60  4996.4  436.44
  5002.4  435.46  5003.9  434.06  5004.4  433.26  5009.4  433.26  5009.9  434.06
  5012.5  434.06  5020.1  437.53  5042.9  437.83  5053.8  438.84  5070.8  442.76
  5080.9  444.05  5145.5  450.19  5192.4  454.75  5225.4  457.02  5314.1  461.53
#Mann=4,-1,0
  4469.1    0.12       0  5003.9    0.07       0  5009.9    0.12       0
  5145.5    0.16       0
Bank Sta=4787.4,5053.8
Exp/Cntr=0.3,0.1

Type RM Length L Ch R = 1,1589,572,572,572
BEGIN DESCRIPTION:
ROCK BRANCH 2.0
END DESCRIPTION:
XS GIS Cut Line= 3
      2834775.00      7053425.00      2834175.00      7053875.00
      2834175.00      7054175.00
#Sta/Elev= 30
  4276.5  460.93  4333.8  454.67  4383.8  450.79  4433.8  449.03  4469.2  449.65
  4486.6  448.19  4519.2  446.65  4598.4  439.78  4674.8  437.33  4713.0  436.31
  4748.4  437.06  4783.8  435.53  4813.0  436.44  4826.5  435.21  4863.0  435.92
  4933.8  435.03  4990.0  436.11  4998.4  435.59  5001.6  432.77  5002.1  431.97
  5007.6  432.77  5013.0  433.29  5019.2  436.03  5040.0  437.33  5076.5  446.80
  5089.3  448.39  5149.0  453.01  5197.7  456.09  5266.5  461.06  5326.5  460.91
#Mann=7,-1,0
  4276.5    0.16       0  4486.6    0.12       0  5001.6    0.07       0
  5007.6    0.12       0  5089.3    0.16       0  5149.0    0.12       0
  5197.7    0.16       0
Bank Sta=4674.8,5040
Exp/Cntr=0.3,0.1

Type RM Length L Ch R = 1,1017,493,493,493
BEGIN DESCRIPTION:
Mapping XS 1bd2cb22
END DESCRIPTION:
XS GIS Cut Line= 3
      2834057.55      7053234.16      2833994.68      7053604.38
      2833994.68      7053900.66
#Sta/Elev= 30
  4634.9  447.25  4635.4  447.25  4675.6  442.67  4680.7  442.61  4686.5  441.52
  4706.8  439.89  4747.3  437.74  4817.8  435.51  4856.5  433.70  4899.5  433.85
  4916.8  432.93  4950.2  434.06  4982.2  433.92  4990.8  434.43  4997.9  430.32
  4998.4  429.52  5003.4  429.52  5003.9  430.32  5008.2  432.45  5013.2  432.45
  5021.0  434.24  5061.0  434.16  5083.3  435.51  5101.0  437.97  5111.0  438.76
  5173.2  442.02  5211.0  443.79  5251.0  446.70  5264.4  447.21  5306.7  449.48
#Mann=6,-1,0
  4634.9    0.16       0  4635.4    0.12       0  4997.9    0.07       0
  5003.9    0.12       0  5173.2    0.16       0  5264.4    0.12       0
Bank Sta=4817.8,5083.3
Exp/Cntr=0.3,0.1

Type RM Length L Ch R = 1,524,397,397,397
BEGIN DESCRIPTION:
Mapping XS 4787ddb7
END DESCRIPTION:
XS GIS Cut Line= 4
      2833833.87      7053088.14      2833655.94      7053305.14
      2833738.40      7053739.17      2833910.99      7053954.91
#Sta/Elev= 30
  4158.2  455.05  4171.4  453.40  4197.1  450.70  4290.2  440.89  4368.4  435.36
  4417.5  433.52  4550.6  431.90  4591.4  432.99  4619.1  432.05  4703.3  433.42
  4744.0  432.42  4888.8  433.07  4896.8  431.45  4903.2  432.87  4911.2  430.02
  4917.6  432.99  4989.7  433.03  4996.1  432.62  5000.3  429.52  5000.8  428.72
  5005.8  428.72  5006.3  429.52  5010.5  430.64  5016.9  429.52  5021.4  433.52
  5024.9  436.61  5045.7  440.13  5124.1  444.29  5138.6  443.66  5156.9  444.98
#Mann=5,-1,0
  4158.2    0.12       0  4171.4    0.16       0  4197.1    0.12       0
  5000.3    0.07       0  5006.3    0.12       0
Bank Sta=4417.5,5021.4
Exp/Cntr=0.3,0.1

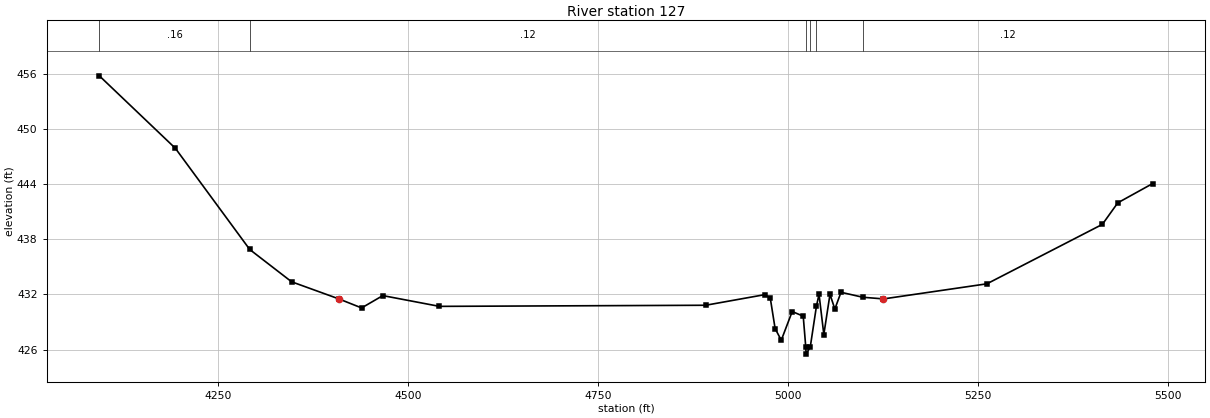
Type RM Length L Ch R = 1,127,0,0,0
BEGIN DESCRIPTION:
ROCK BRANCH 1.0
END DESCRIPTION:
XS GIS Cut Line= 4
      2833560.46      7052957.88      2833404.20      7053669.73
      2833642.92      7053973.55      2833910.43      7054016.41
#Sta/Elev= 30
  4094.2  455.75  4194.2  447.88  4292.1  436.88  4347.2  433.37  4409.4  431.51
  4439.3  430.53  4467.2  431.87  4541.7  430.70  4892.0  430.82  4969.6  431.97
  4977.0  431.62  4983.4  428.29  4991.5  427.02  5005.9  430.14  5020.4  429.63
  5023.7  426.31  5024.2  425.51  5029.7  426.31  5037.8  430.73  5041.2  432.01
  5047.5  427.64  5055.6  432.01  5062.0  430.41  5070.1  432.23  5098.8  431.69
  5126.0  431.51  5262.1  433.15  5414.0  439.61  5434.3  441.95  5480.3  444.05
#Mann=6,-1,0
  4094.2    0.16       0  4292.1    0.12       0  5023.7    0.07       0
  5029.7    0.12       0  5037.8    0.16       0  5098.8    0.12       0
Bank Sta=4409.4,5126
Exp/Cntr=0.3,0.1

Chan Stop Cuts=-1