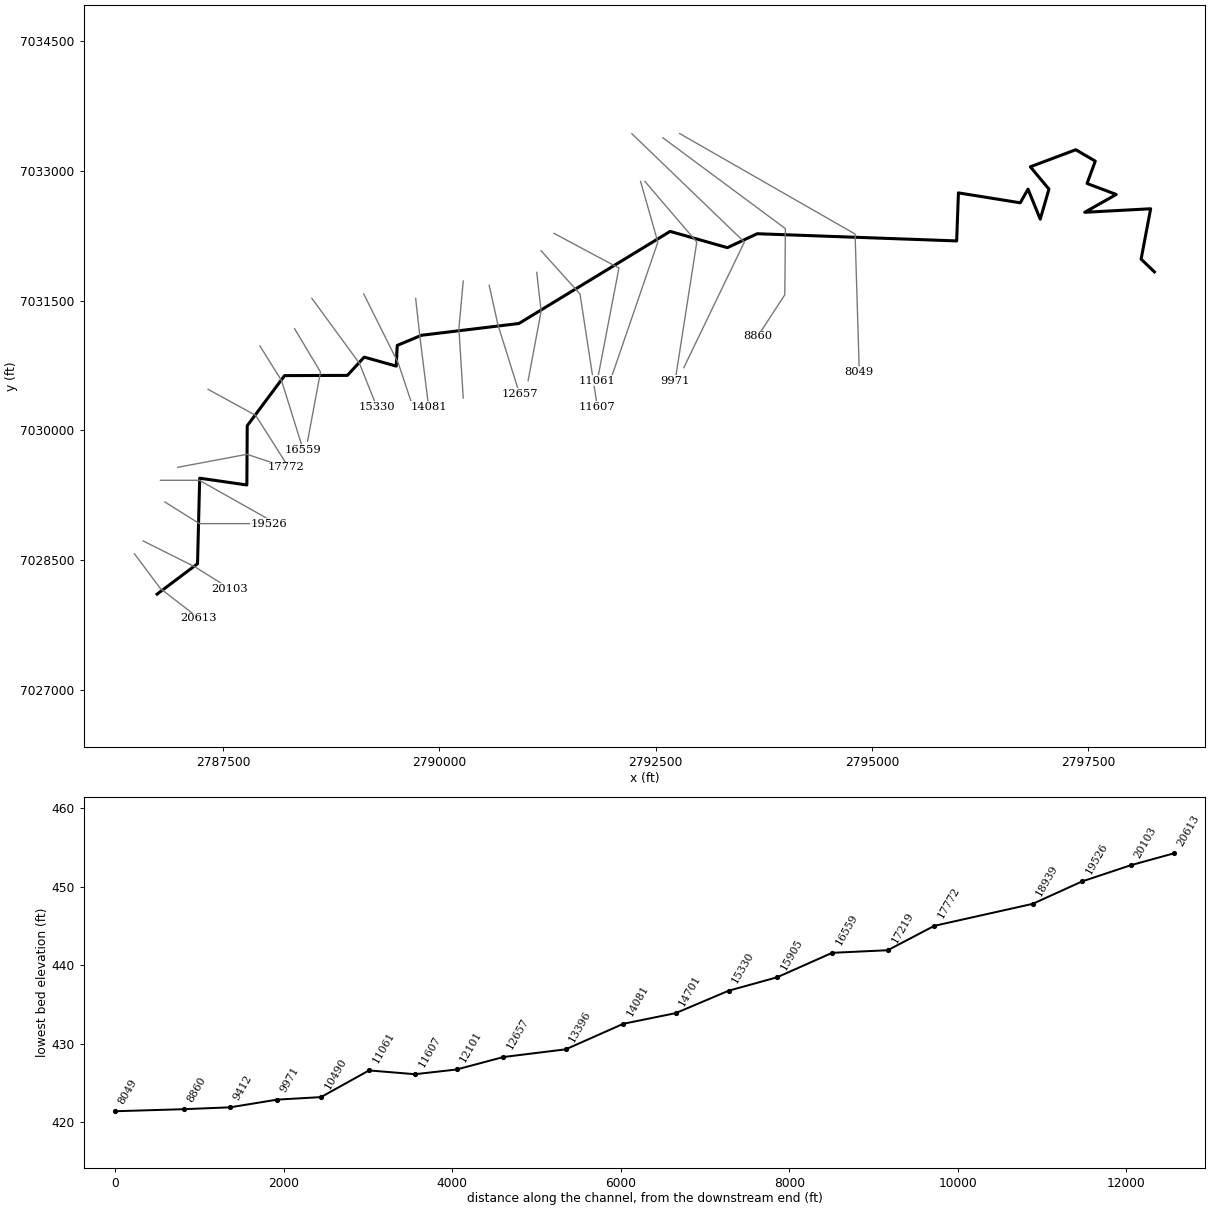
--- Rains Branch.prj (project) ---

Proj Title=Rains Branch Base Level Engineering
Current Plan=p01
Default Exp/Contr=0.3,0.1
English Units
Geom File=g01
Flow File=f01
Plan File=p01
BEGIN DESCRIPTION:
Rains Branch
END DESCRIPTION:

--- Rains Branch.p01 (plan) ---

Plan Title=Multiple Run
Short Identifier=Multiple
Geom File=g01
Flow File=f01
Subcritical Flow
K Sum by GR= 0
Std Step Tol= 0.01
Critical Tol= 0.01
Num of Std Step Trials= 20
Max Error Tol= 0.3
Flow Tol Ratio= 0.001
Split Flow NTrial= 30
Split Flow Tol= 0.02
Split Flow Ratio= 0.02
Log Output Level= 0
Friction Slope Method= 1
Unsteady Friction Slope Method= 2
Unsteady Bridges Friction Slope Method= 1
Parabolic Critical Depth
Global Vel Dist=  1 , 1 , 1
Global Log Level= 0
CheckData=True
Encroach Param= -1, 0, 0, 0
BEGIN DESCRIPTION:
Multiple Run
END DESCRIPTION:

--- Rains Branch.f01 (steady flow) ---

Flow Title=Multiple
Number of Profiles=7
Profile Names=10-year,25-year,50-year,1pct_min,100-year,1pct_plu,500-year
River Rch & RM= Rains Branch,Reach-1,20613
     655     881    1066     641    1278    2550    1841
River Rch & RM= Rains Branch,Reach-1,17219
     873    1191    1453     880    1755    3502    2566
River Rch & RM= Rains Branch,Reach-1,11061
     947    1292    1577     954    1904    3799    2782
Boundary for River Rch & Prof#=Rains Branch,Reach-1,1
Up Type=0
Dn Type=3
Dn Slope=0.005
Boundary for River Rch & Prof#=Rains Branch,Reach-1,2
Up Type=0
Dn Type=3
Dn Slope=0.005
Boundary for River Rch & Prof#=Rains Branch,Reach-1,3
Up Type=0
Dn Type=3
Dn Slope=0.005
Boundary for River Rch & Prof#=Rains Branch,Reach-1,4
Up Type=0
Dn Type=3
Dn Slope=0.005
Boundary for River Rch & Prof#=Rains Branch,Reach-1,5
Up Type=0
Dn Type=3
Dn Slope=0.005
Boundary for River Rch & Prof#=Rains Branch,Reach-1,6
Up Type=0
Dn Type=3
Dn Slope=0.005
Boundary for River Rch & Prof#=Rains Branch,Reach-1,7
Up Type=0
Dn Type=3
Dn Slope=0.005

--- Rains Branch.g01 (geometry) ---

Geom Title=Existing Conditions

River Reach=Rains Branch,Reach-1
Reach XY= 30
      2786735.59      7028110.71      2787203.20      7028461.69
      2787228.23      7029449.28      2787773.50      7029370.90
      2787777.81      7030054.87      2788209.47      7030633.32
      2788935.58      7030635.95      2789130.06      7030846.88
      2789500.66      7030743.12      2789511.81      7030981.74
      2789792.09      7031099.03      2790918.43      7031234.95
      2792666.75      7032298.15      2793328.87      7032110.35
      2793673.39      7032271.25      2795979.35      7032188.21
      2795999.70      7032742.76      2796714.50      7032628.20
      2796804.33      7032785.86      2796945.49      7032439.37
      2797046.32      7032785.86      2796831.07      7033043.80
      2797356.34      7033240.72      2797581.96      7033109.37
      2797486.75      7032851.16      2797824.31      7032724.52
      2797459.10      7032518.60      2798221.90      7032559.35
      2798111.72      7031978.10      2798265.59      7031830.71

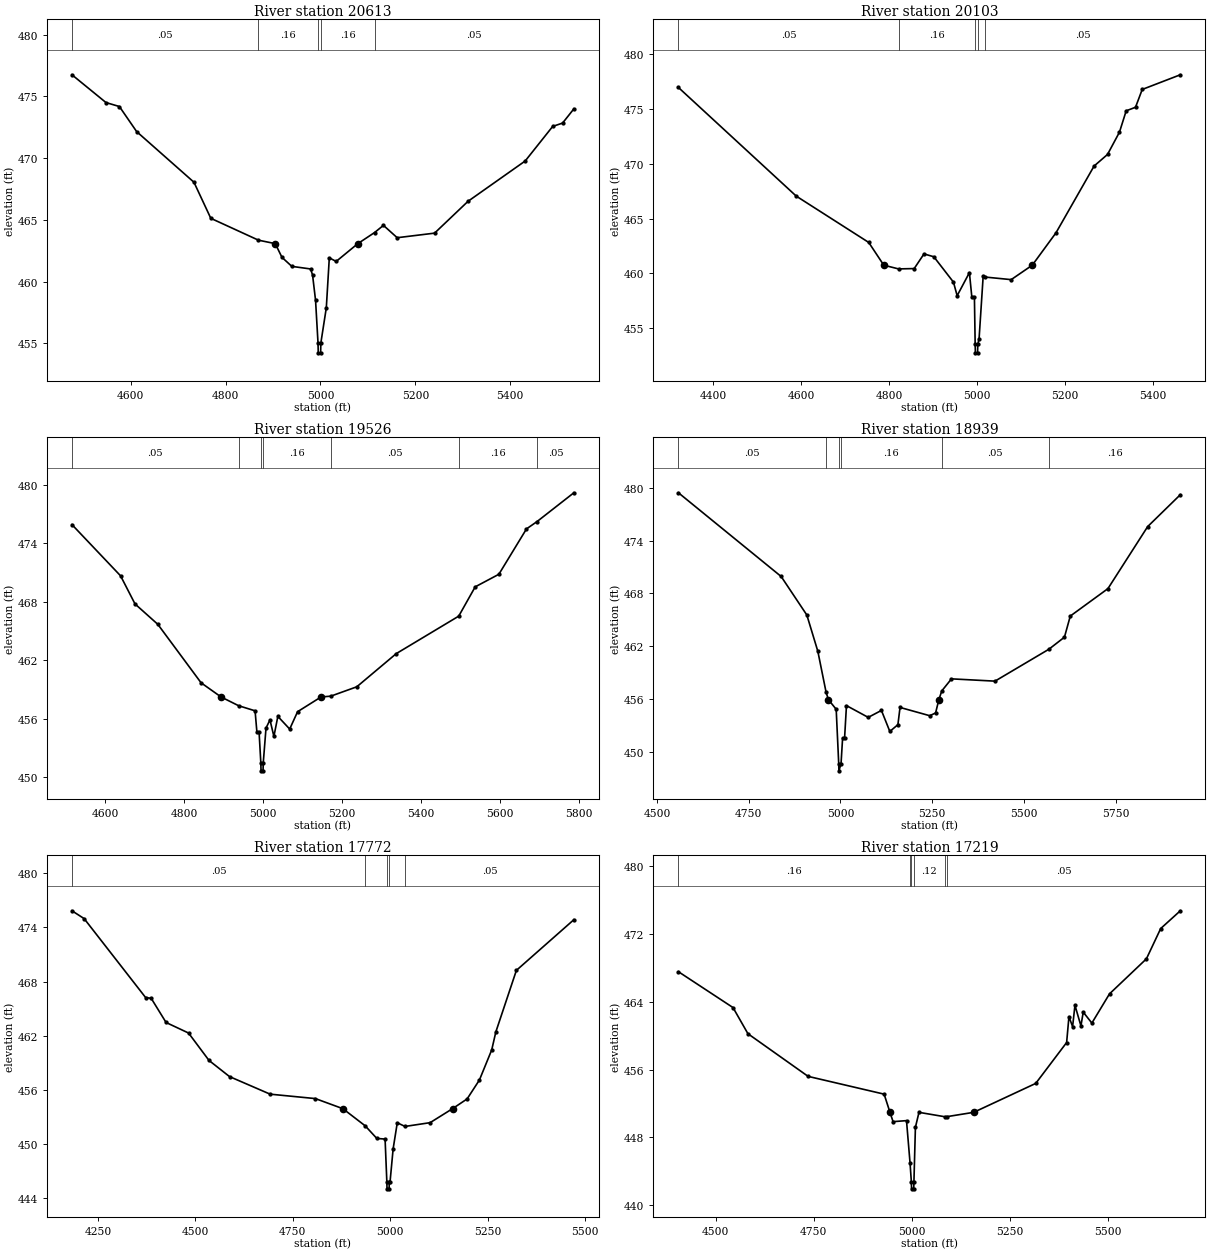
Type RM Length L Ch R = 1,20613,510,510,510
BEGIN DESCRIPTION:
Rains Branch 20.0
END DESCRIPTION:
XS GIS Cut Line= 3
      2786475.03      7028574.96      2786775.00      7028175.00
      2787216.52      7027833.71
#Sta/Elev= 30
  4476.2  476.75  4548.0  474.50  4576.2  474.18  4612.6  472.15  4733.4  468.05
  4768.9  465.13  4869.4  463.36  4904.8  463.08  4918.9  461.97  4939.7  461.24
  4979.3  461.03  4983.4  460.54  4989.7  458.50  4994.9  455.04  4995.4  454.24
  5000.4  454.24  5000.9  455.04  5012.4  457.89  5018.7  461.93  5033.2  461.64
  5078.8  463.08  5114.2  463.98  5132.8  464.56  5161.8  463.56  5240.6  463.93
  5311.2  466.51  5431.6  469.77  5489.6  472.57  5510.4  472.84  5534.2  473.99
#Mann=5,-1,0
  4476.2    0.05       0  4869.4    0.16       0  4994.9    0.07       0
  5000.9    0.16       0  5114.2    0.05       0
Bank Sta=4904.8,5078.8
Exp/Cntr=0.3,0.1

Type RM Length L Ch R = 1,20103,577,577,577
BEGIN DESCRIPTION:
Rains Branch 19.0
END DESCRIPTION:
XS GIS Cut Line= 3
      2786575.00      7028725.00      2787175.00      7028425.00
      2787574.99      7028175.01
#Sta/Elev= 30
  4320.4  476.98  4588.7  467.05  4753.6  462.82  4787.9  460.74  4821.5  460.40
  4857.1  460.43  4879.4  461.77  4901.8  461.51  4946.5  459.19  4954.9  457.95
  4982.8  460.06  4988.4  457.79  4994.2  457.79  4995.9  453.53  4996.4  452.73
  5001.4  452.73  5001.9  453.53  5004.8  454.01  5014.2  459.78  5017.3  459.66
  5077.9  459.42  5125.9  460.74  5179.9  463.70  5266.6  469.80  5297.2  470.86
  5324.4  472.90  5339.7  474.85  5360.9  475.17  5376.2  476.80  5462.9  478.14
#Mann=5,-1,0
  4320.4    0.05       0  4821.5    0.16       0  4995.9    0.07       0
  5001.9    0.16       0  5017.3    0.05       0
Bank Sta=4787.9,5125.9
Exp/Cntr=0.3,0.1

Type RM Length L Ch R = 1,19526,587,587,587
BEGIN DESCRIPTION:
Rains Branch 18.0
END DESCRIPTION:
XS GIS Cut Line= 3
      2786825.02      7029174.99      2787225.00      7028925.00
      2788025.02      7028925.00
#Sta/Elev= 30
  4515.1  475.90  4638.3  470.65  4674.9  467.77  4732.7  465.68  4842.3  459.69
  4892.9  458.24  4937.5  457.34  4979.1  456.82  4983.8  454.61  4989.3  454.61
  4993.7  451.47  4994.2  450.67  4999.3  450.67  4999.8  451.47  5006.8  455.05
  5016.8  455.89  5026.8  454.20  5036.8  456.25  5066.8  454.95  5086.8  456.73
  5146.3  458.24  5170.8  458.32  5236.8  459.28  5336.8  462.68  5495.1  466.52
  5536.8  469.52  5596.8  470.81  5666.8  475.46  5693.2  476.20  5786.8  479.16
#Mann=7,-1,0
  4515.1    0.05       0  4937.5    0.16       0  4993.7    0.07       0
  4999.8    0.16       0  5170.8    0.05       0  5495.1    0.16       0
  5693.2    0.05       0
Bank Sta=4892.9,5146.3
Exp/Cntr=0.3,0.1

Type RM Length L Ch R = 1,18939,1167,1167,1167
BEGIN DESCRIPTION:
Rains Branch 17.0
END DESCRIPTION:
XS GIS Cut Line= 3
      2786774.97      7029425.00      2787225.00      7029425.00
      2788024.99      7028975.00
#Sta/Elev= 30
  4558.4  479.43  4838.4  469.91  4908.4  465.53  4938.4  461.40  4960.9  456.74
  4967.3  455.90  4988.4  454.81  4995.3  448.61  4995.8  447.81  5001.6  448.61
  5005.9  451.55  5011.3  451.55  5016.4  455.23  5075.7  453.89  5111.7  454.68
  5134.6  452.29  5156.6  453.06  5162.4  455.02  5243.3  454.08  5259.3  454.39
  5268.2  455.90  5276.2  456.90  5302.6  458.27  5421.2  458.01  5568.2  461.64
  5610.5  463.01  5626.4  465.41  5729.0  468.53  5837.4  475.59  5926.3  479.21
#Mann=6,-1,0
  4558.4    0.05       0  4960.9    0.16       0  4995.3    0.07       0
  5001.6    0.16       0  5276.2    0.05       0  5568.2    0.16       0
Bank Sta=4967.3,5268.2
Exp/Cntr=0.3,0.1

Type RM Length L Ch R = 1,17772,553,553,553
BEGIN DESCRIPTION:
Rains Branch 16.0
END DESCRIPTION:
XS GIS Cut Line= 3
      2786975.04      7029575.01      2787775.00      7029725.00
      2788224.96      7029575.01
#Sta/Elev= 30
  4183.1  475.85  4214.4  474.98  4372.1  466.23  4386.5  466.14  4424.7  463.46
  4482.4  462.29  4534.9  459.25  4587.5  457.46  4691.8  455.51  4807.9  455.02
  4878.5  453.90  4935.7  452.00  4965.6  450.60  4986.8  450.53  4991.3  445.81
  4991.8  445.01  4997.1  445.01  4997.6  445.81  4999.6  445.81  5007.5  449.46
  5018.1  452.34  5037.9  451.93  5102.4  452.35  5159.9  453.90  5197.3  454.98
  5228.9  457.08  5260.5  460.42  5271.1  462.42  5323.8  469.24  5471.3  474.86
#Mann=5,-1,0
  4183.1    0.05       0  4935.7    0.12       0  4991.3    0.07       0
  4997.6    0.12       0  5037.9    0.05       0
Bank Sta=4878.5,5159.9
Exp/Cntr=0.3,0.1

Type RM Length L Ch R = 1,17219,660,660,660
BEGIN DESCRIPTION:
Rains Branch 15.0
END DESCRIPTION:
XS GIS Cut Line= 3
      2787324.97      7030475.02      2787875.00      7030175.00
      2788225.03      7029624.96
#Sta/Elev= 30
  4405.3  467.56  4544.4  463.32  4582.4  460.23  4735.7  455.19  4929.3  453.09
  4944.2  450.94  4952.1  449.84  4986.3  449.96  4995.3  444.98  4998.7  442.70
  4999.2  441.90  5004.7  441.90  5005.2  442.70  5009.0  449.17  5018.1  450.94
  5084.0  450.42  5090.5  450.44  5157.4  450.94  5315.5  454.36  5394.2  459.19
  5400.1  462.25  5409.4  461.07  5415.4  463.59  5430.6  461.16  5436.5  462.78
  5458.5  461.49  5503.4  464.94  5597.4  469.08  5633.8  472.66  5683.8  474.76
#Mann=6,-1,0
  4405.3    0.16       0  4995.3    0.12       0  4998.7    0.07       0
  5005.2    0.12       0  5084.0    0.16       0  5090.5    0.05       0
Bank Sta=4944.2,5157.4
Exp/Cntr=0.3,0.1

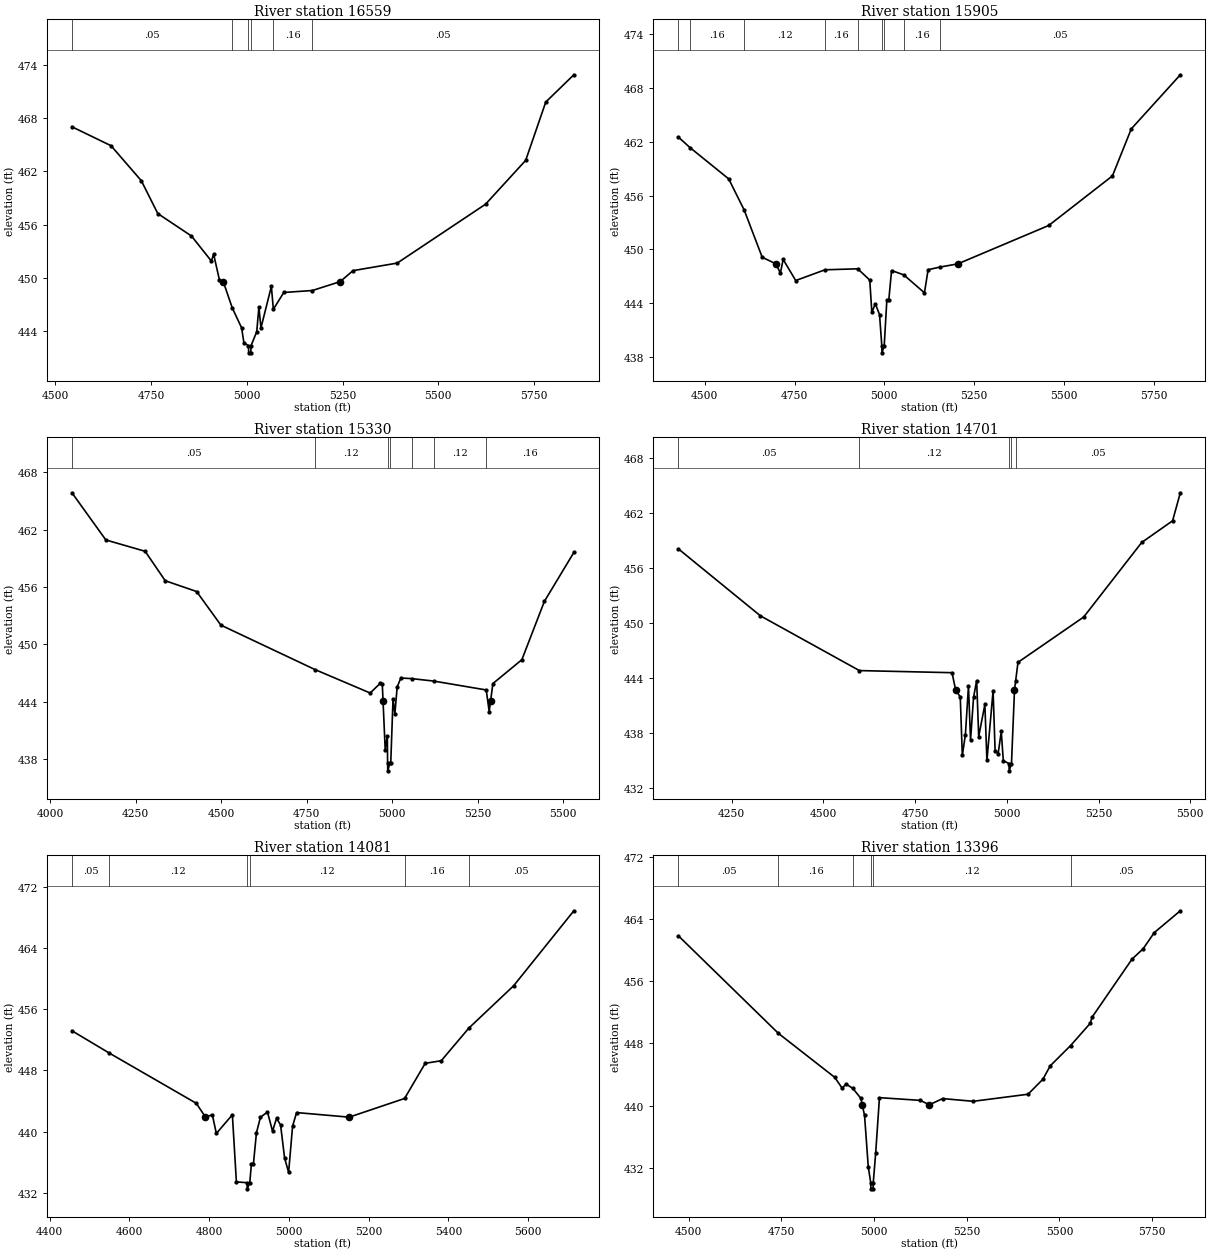
Type RM Length L Ch R = 1,16559,654,654,654
BEGIN DESCRIPTION:
Rains Branch 14.0
END DESCRIPTION:
XS GIS Cut Line= 3
      2787925.01      7030974.99      2788175.00      7030575.00
      2788424.99      7029775.04
#Sta/Elev= 30
  4543.8  467.03  4645.8  464.90  4724.8  460.96  4767.8  457.26  4855.7  454.73
  4907.6  451.91  4913.5  452.68  4928.8  449.76  4938.7  449.59  4962.0  446.65
  4986.6  444.38  4992.5  442.72  5004.5  442.37  5005.0  441.57  5010.6  441.57
  5011.1  442.37  5026.0  443.94  5031.7  446.72  5037.0  444.37  5064.2  449.05
  5069.4  446.48  5096.7  448.37  5171.1  448.59  5243.7  449.59  5277.4  450.83
  5392.7  451.68  5623.1  458.31  5727.9  463.25  5780.3  469.82  5853.6  472.89
#Mann=6,-1,0
  4543.8    0.05       0  4962.0    0.12       0  5004.5    0.07       0
  5011.1    0.12       0  5069.4    0.16       0  5171.1    0.05       0
Bank Sta=4938.7,5243.7
Exp/Cntr=0.3,0.1

Type RM Length L Ch R = 1,15905,575,575,575
BEGIN DESCRIPTION:
Rains Branch 13.0
END DESCRIPTION:
XS GIS Cut Line= 3
      2788325.00      7031175.00      2788625.00      7030675.00
      2788475.01      7029875.03
#Sta/Elev= 30
  4426.8  462.53  4459.1  461.36  4566.7  457.87  4609.8  454.40  4660.0  449.12
  4698.5  448.38  4710.6  447.34  4718.3  448.88  4753.3  446.52  4834.7  447.72
  4925.9  447.83  4959.4  446.57  4965.2  442.96  4974.9  443.93  4986.6  442.72
  4992.9  439.25  4993.4  438.45  4999.6  439.25  5007.0  444.37  5012.4  444.37
  5020.1  447.64  5054.2  447.15  5111.6  445.15  5121.8  447.73  5154.2  448.02
  5204.4  448.38  5457.6  452.67  5634.8  458.20  5687.3  463.45  5823.8  469.49
#Mann=9,-1,0
  4426.8    0.05       0  4459.1    0.16       0  4609.8    0.12       0
  4834.7    0.16       0  4925.9    0.12       0  4992.9    0.07       0
  4999.6    0.12       0  5054.2    0.16       0  5154.2    0.05       0
Bank Sta=4698.5,5204.4
Exp/Cntr=0.3,0.1

Type RM Length L Ch R = 1,15330,629,629,629
BEGIN DESCRIPTION:
Rains Branch 12.0
END DESCRIPTION:
XS GIS Cut Line= 3
      2788524.98      7031525.03      2789075.00      7030775.00
      2789275.00      7030275.01
#Sta/Elev= 30
  4063.3  465.86  4162.5  460.92  4277.5  459.73  4336.2  456.65  4428.0  455.52
  4499.1  452.00  4774.2  447.35  4935.9  444.89  4965.2  445.90  4971.4  445.79
  4973.6  444.04  4979.9  438.97  4986.1  440.35  4986.9  437.54  4987.4  436.74
  4993.6  437.54  4996.1  437.54  5002.8  444.28  5008.2  442.72  5014.9  445.52
  5025.7  446.46  5056.9  446.40  5122.1  446.14  5275.5  445.21  5284.2  442.95
  5288.2  444.04  5295.0  445.88  5379.8  448.38  5445.7  454.49  5531.9  459.61
#Mann=7,-1,0
  4063.3    0.05       0  4774.2    0.12       0  4986.9    0.07       0
  4993.6    0.12       0  5056.9    0.16       0  5122.1    0.12       0
  5275.5    0.16       0
Bank Sta=4973.6,5288.2
Exp/Cntr=0.3,0.1

Type RM Length L Ch R = 1,14701,620,620,620
BEGIN DESCRIPTION:
Rains Branch 11.0
END DESCRIPTION:
XS GIS Cut Line= 3
      2789125.02      7031574.96      2789525.00      7030775.00
      2789674.99      7030325.03
#Sta/Elev= 30
  4104.4  458.12  4328.0  450.81  4598.0  444.83  4850.6  444.60  4860.4  442.70
  4873.0  441.96  4878.6  435.56  4887.0  437.84  4895.4  443.14  4901.0  437.24
  4909.3  441.92  4917.7  443.73  4923.3  437.63  4940.1  441.13  4945.7  435.01
  4962.5  442.64  4968.0  436.06  4976.4  435.77  4984.8  438.18  4990.4  434.98
  5005.9  434.68  5006.4  433.88  5012.7  434.68  5020.9  442.70  5024.1  443.72
  5030.4  445.73  5209.6  450.68  5367.7  458.82  5452.0  461.19  5473.1  464.25
#Mann=5,-1,0
  4104.4    0.05       0  4598.0    0.12       0  5005.9    0.07       0
  5012.7    0.12       0  5024.1    0.05       0
Bank Sta=4860.4,5020.9
Exp/Cntr=0.3,0.1

Type RM Length L Ch R = 1,14081,685,685,685
BEGIN DESCRIPTION:
Rains Branch 10.0
END DESCRIPTION:
XS GIS Cut Line= 3
      2789725.00      7031524.99      2789775.00      7031075.00
      2789875.00      7030274.98
#Sta/Elev= 30
  4455.9  453.17  4549.8  450.25  4767.8  443.70  4790.9  441.89  4808.0  442.21
  4818.1  439.76  4858.3  442.20  4868.4  433.44  4895.1  433.33  4895.6  432.53
  4902.0  433.33  4906.1  435.83  4911.2  435.83  4918.7  439.85  4928.8  441.88
  4946.4  442.56  4959.0  440.06  4969.1  441.74  4979.2  440.88  4989.3  436.55
  4999.4  434.69  5009.4  440.74  5019.5  442.49  5151.3  441.89  5290.3  444.33
  5342.0  448.92  5382.3  449.26  5451.5  453.52  5563.7  459.04  5714.9  468.84
#Mann=6,-1,0
  4455.9    0.05       0  4549.8    0.12       0  4895.1    0.07       0
  4902.0    0.12       0  5290.3    0.16       0  5451.5    0.05       0
Bank Sta=4790.9,5151.3
Exp/Cntr=0.3,0.1

Type RM Length L Ch R = 1,13396,739,739,739
BEGIN DESCRIPTION:
Rains Branch 9.0
END DESCRIPTION:
XS GIS Cut Line= 3
      2790275.00      7031725.03      2790225.00      7031175.00
      2790275.00      7030374.96
#Sta/Elev= 30
  4472.2  461.87  4741.8  449.31  4894.0  443.63  4914.0  442.23  4924.1  442.78
  4942.5  442.22  4964.3  440.94  4968.1  440.10  4974.3  438.73  4984.3  432.11
  4990.9  430.07  4991.4  429.27  4997.3  429.27  4997.8  430.07  5004.4  433.93
  5014.5  441.02  5124.7  440.67  5149.2  440.10  5184.8  440.90  5267.5  440.55
  5415.3  441.46  5455.3  443.39  5475.4  445.13  5530.3  447.74  5583.1  450.60
  5588.1  451.39  5695.8  458.87  5725.9  460.21  5755.9  462.29  5826.1  465.10
#Mann=6,-1,0
  4472.2    0.05       0  4741.8    0.16       0  4942.5    0.12       0
  4990.9    0.07       0  4997.8    0.12       0  5530.3    0.05       0
Bank Sta=4968.1,5149.2
Exp/Cntr=0.3,0.1

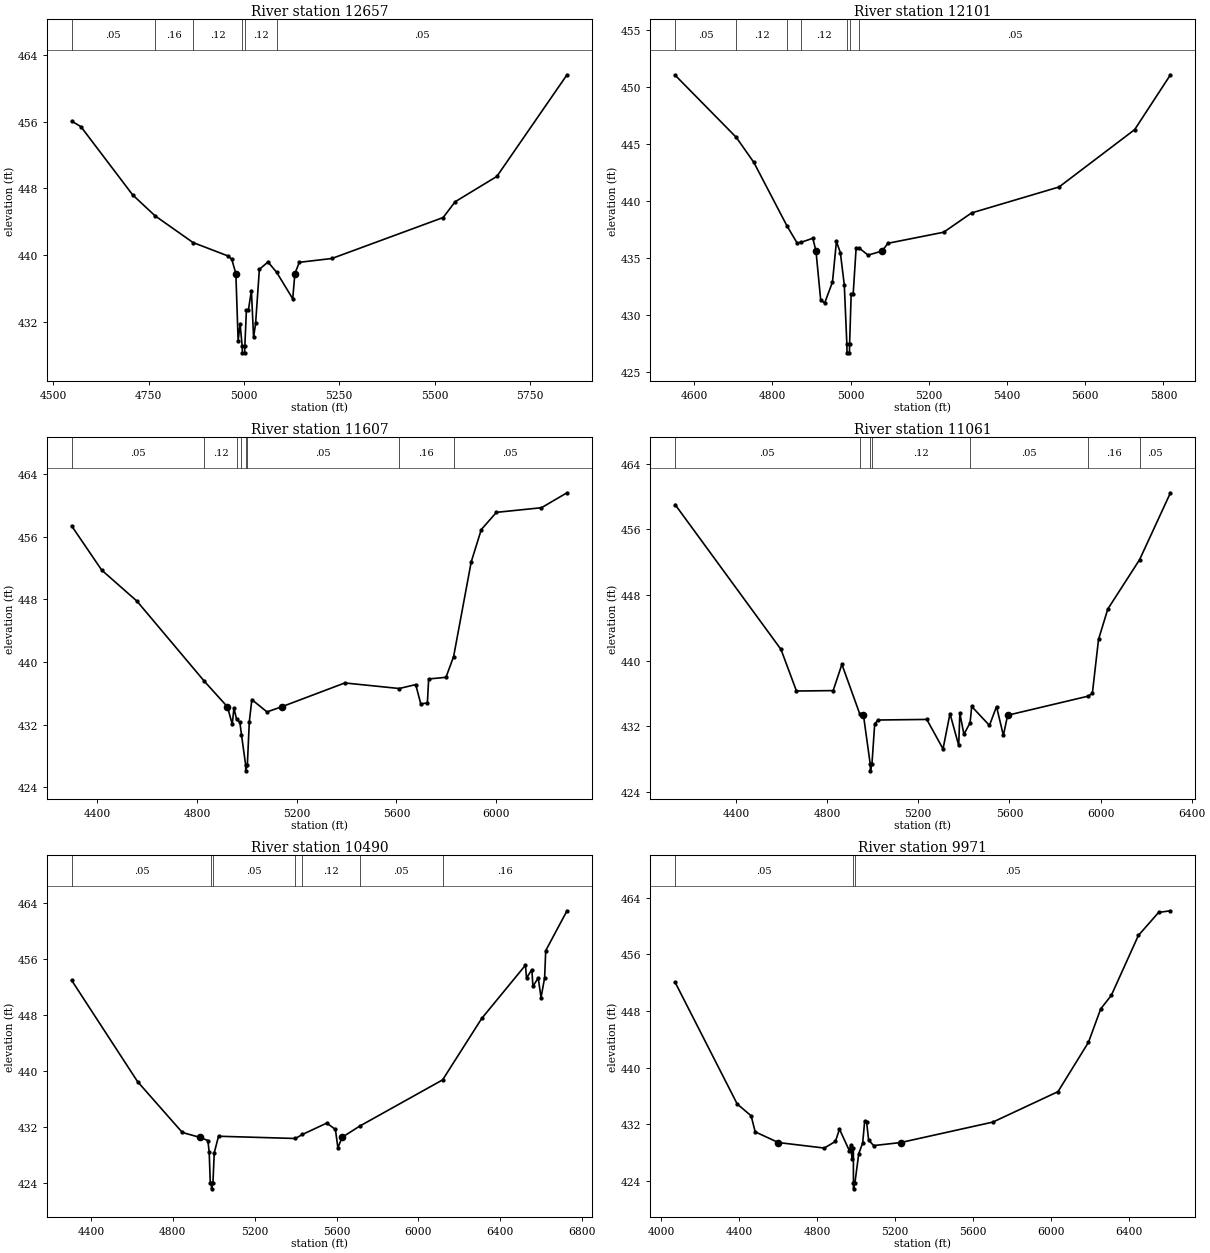
Type RM Length L Ch R = 1,12657,556,556,556
BEGIN DESCRIPTION:
Rains Branch 8.0
END DESCRIPTION:
XS GIS Cut Line= 3
      2790574.99      7031675.03      2790675.00      7031225.00
      2790925.01      7030424.96
#Sta/Elev= 30
  4548.3  456.07  4572.7  455.40  4708.4  447.22  4767.0  444.72  4866.7  441.51
  4958.1  439.91  4968.3  439.51  4979.0  437.79  4985.0  429.74  4990.1  431.74
  4995.6  429.09  4996.1  428.29  5002.1  428.29  5002.6  429.09  5006.7  433.40
  5011.9  433.40  5019.8  435.76  5025.5  430.13  5030.8  431.81  5040.7  438.30
  5063.3  439.18  5085.9  437.95  5128.2  434.77  5133.8  437.79  5145.5  439.14
  5230.9  439.60  5522.7  444.51  5554.1  446.40  5663.6  449.44  5847.5  461.62
#Mann=6,-1,0
  4548.3    0.05       0  4767.0    0.16       0  4866.7    0.12       0
  4995.6    0.07       0  5002.6    0.12       0  5085.9    0.05       0
Bank Sta=4979,5133.8
Exp/Cntr=0.3,0.1

Type RM Length L Ch R = 1,12101,494,494,494
BEGIN DESCRIPTION:
Rains Branch 7.0
END DESCRIPTION:
XS GIS Cut Line= 3
      2791125.00      7031825.04      2791175.00      7031375.00
      2791025.01      7030575.05
#Sta/Elev= 30
  4551.4  451.06  4707.9  445.60  4752.7  443.41  4837.3  437.85  4863.3  436.34
  4874.2  436.40  4903.6  436.75  4911.7  435.63  4923.7  431.35  4933.8  431.06
  4953.9  432.91  4964.0  436.47  4974.0  435.49  4984.1  432.66  4990.6  427.50
  4991.1  426.70  4997.2  426.70  4997.7  427.50  5001.7  431.86  5006.8  431.86
  5014.4  435.91  5022.6  435.88  5044.9  435.27  5080.5  435.63  5095.8  436.31
  5238.2  437.28  5309.4  438.97  5533.3  441.25  5726.6  446.28  5818.1  451.09
#Mann=7,-1,0
  4551.4    0.05       0  4707.9    0.12       0  4837.3    0.16       0
  4874.2    0.12       0  4990.6    0.07       0  4997.7    0.12       0
  5022.6    0.05       0
Bank Sta=4911.7,5080.5
Exp/Cntr=0.3,0.1

Type RM Length L Ch R = 1,11607,546,546,546
BEGIN DESCRIPTION:
Rains Branch 6.0
END DESCRIPTION:
XS GIS Cut Line= 3
      2791175.01      7032074.99      2791625.00      7031575.00
      2791825.00      7030274.97
#Sta/Elev= 30
  4296.6  457.40  4417.3  451.75  4558.6  447.79  4829.7  437.53  4921.9  434.28
  4941.2  432.05  4948.0  434.12  4958.6  432.69  4971.8  432.30  4978.1  430.73
  4994.8  426.90  4995.3  426.10  5001.9  426.90  5009.7  432.39  5019.9  435.20
  5080.6  433.63  5139.2  434.28  5392.9  437.33  5611.2  436.62  5677.5  437.12
  5697.7  434.66  5724.3  434.77  5729.4  437.84  5798.9  438.05  5829.6  440.71
  5900.1  452.79  5940.6  456.93  6001.3  459.13  6182.1  459.72  6284.6  461.63
#Mann=8,-1,0
  4296.6    0.05       0  4829.7    0.12       0  4958.6    0.07       0
  4978.1    0.05       0  4994.8    0.03       0  5001.9    0.05       0
  5611.2    0.16       0  5829.6    0.05       0
Bank Sta=4921.9,5139.2
Exp/Cntr=0.3,0.1

Type RM Length L Ch R = 1,11061,571,571,571
BEGIN DESCRIPTION:
Rains Branch 5.0
END DESCRIPTION:
XS GIS Cut Line= 3
      2791324.97      7032275.02      2792075.00      7031875.00
      2791824.99      7030574.96
#Sta/Elev= 30
  4132.8  459.01  4597.5  441.37  4665.5  436.30  4826.6  436.35  4864.9  439.55
  4942.6  433.56  4959.5  433.35  4989.3  427.38  4989.9  426.58  4996.7  427.38
  5008.8  432.30  5023.6  432.77  5237.4  432.84  5308.7  429.25  5339.2  433.55
  5377.4  429.68  5382.5  433.59  5400.3  431.03  5427.4  432.43  5434.5  434.42
  5512.4  432.11  5543.4  434.41  5573.5  430.89  5592.2  433.35  5945.1  435.67
  5964.0  436.01  5991.0  442.58  6031.7  446.28  6171.2  452.29  6306.7  460.44
#Mann=7,-1,0
  4132.8    0.05       0  4942.6    0.12       0  4989.3    0.07       0
  4996.7    0.12       0  5427.4    0.05       0  5945.1    0.16       0
  6171.2    0.05       0
Bank Sta=4959.5,5592.2
Exp/Cntr=0.3,0.1

Type RM Length L Ch R = 1,10490,519,519,519
BEGIN DESCRIPTION:
Rains Branch 4.0
END DESCRIPTION:
XS GIS Cut Line= 3
      2792324.99      7032875.02      2792525.00      7032175.00
      2791975.01      7030575.03
#Sta/Elev= 30
  4306.1  453.00  4628.5  438.50  4846.9  431.24  4931.1  430.55  4971.7  430.09
  4978.2  428.39  4983.4  424.04  4988.8  423.98  4989.4  423.18  4996.3  423.98
  5002.9  428.35  5023.7  430.70  5399.2  430.38  5433.9  430.96  5552.3  432.58
  5594.6  431.68  5606.8  429.05  5627.5  430.55  5714.0  432.16  6118.3  438.76
  6309.5  447.55  6523.0  455.16  6528.2  453.32  6554.2  454.54  6559.5  452.13
  6585.4  453.34  6599.1  450.52  6616.7  453.37  6622.0  457.24  6726.0  462.94
#Mann=7,-1,0
  4306.1    0.05       0  4988.8    0.03       0  4996.3    0.05       0
  5399.2    0.07       0  5433.9    0.12       0  5714.0    0.05       0
  6118.3    0.16       0
Bank Sta=4931.1,5627.5
Exp/Cntr=0.3,0.1

Type RM Length L Ch R = 1,9971,559,559,559
BEGIN DESCRIPTION:
Rains Branch 3.0
END DESCRIPTION:
XS GIS Cut Line= 3
      2792375.02      7032874.97      2792975.00      7032175.00
      2792725.01      7030575.03
#Sta/Elev= 30
  4072.5  452.05  4391.3  434.84  4462.6  433.18  4483.5  430.91  4602.5  429.40
  4838.0  428.62  4895.1  429.56  4915.9  431.29  4966.4  428.26  4973.0  429.00
  4980.7  427.05  4987.3  428.67  4987.4  423.66  4987.9  422.86  4994.9  423.66
  5014.7  427.82  5034.9  429.33  5045.0  432.40  5055.1  432.30  5065.3  429.76
  5091.1  428.97  5230.2  429.40  5702.9  432.29  6036.9  436.59  6193.3  443.57
  6256.0  448.28  6310.2  450.18  6449.4  458.66  6553.1  461.91  6613.8  462.14
#Mann=3,-1,0
  4072.5    0.05       0  4987.4    0.03       0  4994.9    0.05       0
Bank Sta=4602.5,5230.2
Exp/Cntr=0.3,0.1

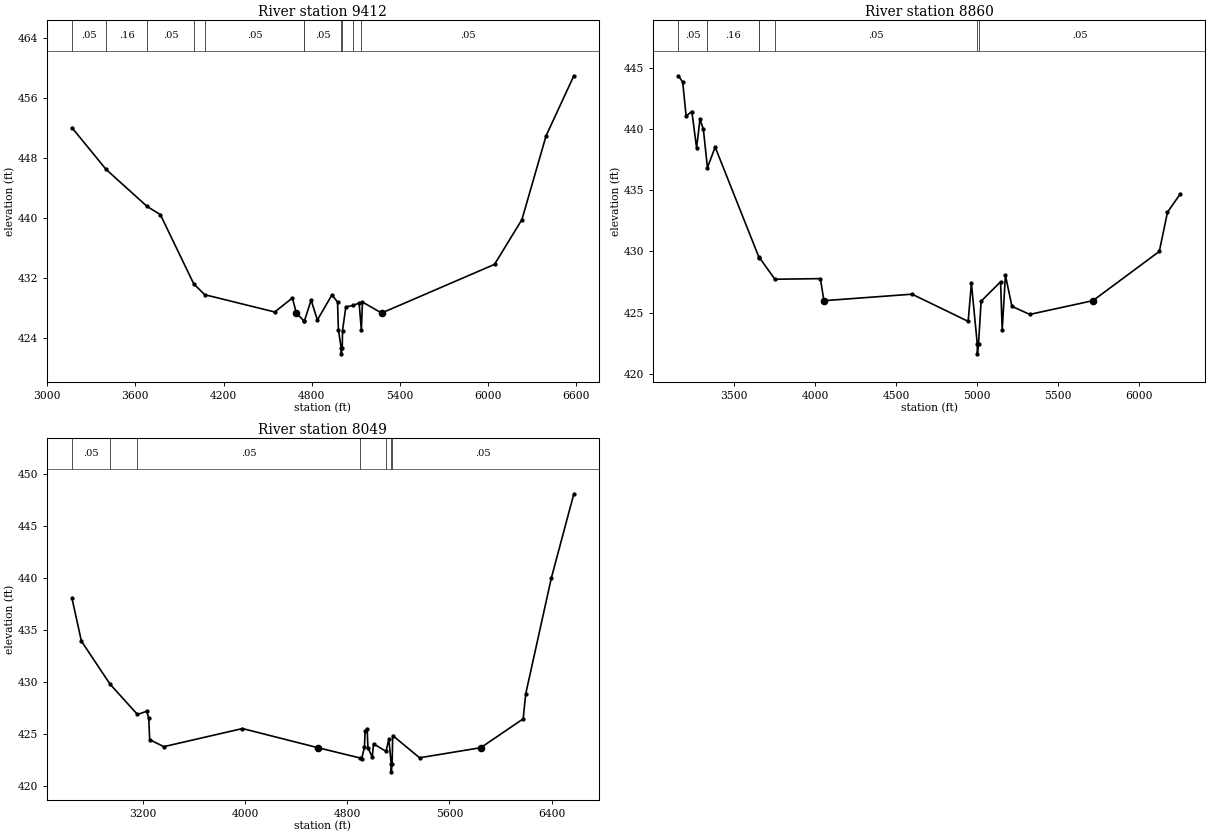
Type RM Length L Ch R = 1,9412,552,552,552
BEGIN DESCRIPTION:
Rains Branch 2.0
END DESCRIPTION:
XS GIS Cut Line= 3
      2792224.97      7033425.03      2793525.00      7032175.00
      2792825.02      7030725.03
#Sta/Elev= 30
  3169.2  452.09  3401.0  446.52  3680.2  441.57  3770.4  440.48  3998.0  431.21
  4072.6  429.78  4548.3  427.47  4668.5  429.34  4695.5  427.33  4748.9  426.23
  4749.7  426.22  4795.8  429.06  4838.3  426.40  4937.3  429.75  4975.5  428.80
  4981.2  425.11  5000.0  422.68  5000.6  421.88  5007.7  422.68  5009.4  424.99
  5032.0  428.16  5081.9  428.34  5122.4  428.67  5137.6  425.02  5145.0  428.80
  5275.3  427.33  6043.3  433.83  6229.7  439.82  6394.1  451.01  6582.8  459.02
#Mann=11,-1,0
  3169.2    0.05       0  3401.0    0.16       0  3680.2    0.05       0
  3998.0    0.12       0  4072.6    0.05       0  4748.9    0.12       0
  4749.7    0.05       0  5000.0    0.03       0  5007.7    0.05       0
  5081.9    0.12       0  5137.6    0.05       0
Bank Sta=4695.5,5275.3
Exp/Cntr=0.3,0.1

Type RM Length L Ch R = 1,8860,811,811,811
BEGIN DESCRIPTION:
Mapping XS 0d964a3e
END DESCRIPTION:
XS GIS Cut Line= 4
      2792582.82      7033378.87      2793999.51      7032330.24
      2793992.56      7031566.35      2793680.96      7031088.56
#Sta/Elev= 30
  3157.9  444.34  3184.4  443.82  3205.3  441.06  3240.8  441.42  3270.0  438.46
  3290.9  440.78  3311.7  439.99  3337.0  436.84  3384.6  438.52  3655.7  429.49
  3656.9  429.51  3753.2  427.73  4033.9  427.78  4055.5  425.98  4599.6  426.51
  4945.7  424.29  4965.7  427.40  5001.9  422.44  5002.5  421.64  5009.6  422.44
  5025.7  425.94  5145.7  427.52  5155.7  423.58  5175.7  428.05  5215.7  425.52
  5325.7  424.86  5715.3  425.98  6125.1  430.00  6175.5  433.20  6254.8  434.70
#Mann=7,-1,0
  3157.9    0.05       0  3337.0    0.16       0  3655.7    0.12       0
  3656.9    0.07       0  3753.2    0.05       0  5001.9    0.03       0
  5009.6    0.05       0
Bank Sta=4055.5,5715.3
Exp/Cntr=0.3,0.1

Type RM Length L Ch R = 1,8049,0,0,0
BEGIN DESCRIPTION:
Rains Branch 1.0
END DESCRIPTION:
XS GIS Cut Line= 3
      2792777.25      7033427.48      2794805.06      7032267.74
      2794853.63      7030678.71
#Sta/Elev= 30
  2646.9  438.07  2720.8  433.94  2944.7  429.81  3159.4  426.89  3231.8  427.20
  3247.6  426.55  3254.9  424.47  3365.6  423.80  3980.6  425.54  4571.0  423.70
  4897.9  422.72  4913.0  422.66  4934.6  423.73  4940.3  425.33  4956.1  425.53
  4961.9  423.70  4995.7  422.79  5005.7  424.07  5103.2  423.35  5125.7  424.52
  5143.8  422.18  5144.4  421.38  5151.5  422.18  5155.7  424.87  5365.8  422.73
  5844.5  423.70  6176.2  426.47  6196.2  428.87  6396.3  439.99  6572.7  448.10
#Mann=7,-1,0
  2646.9    0.05       0  2944.7    0.07       0  3159.4    0.05       0
  4897.9    0.12       0  5103.2    0.05       0  5143.8    0.07       0
  5151.5    0.05       0
Bank Sta=4571,5844.5
Exp/Cntr=0.3,0.1

Chan Stop Cuts=-1