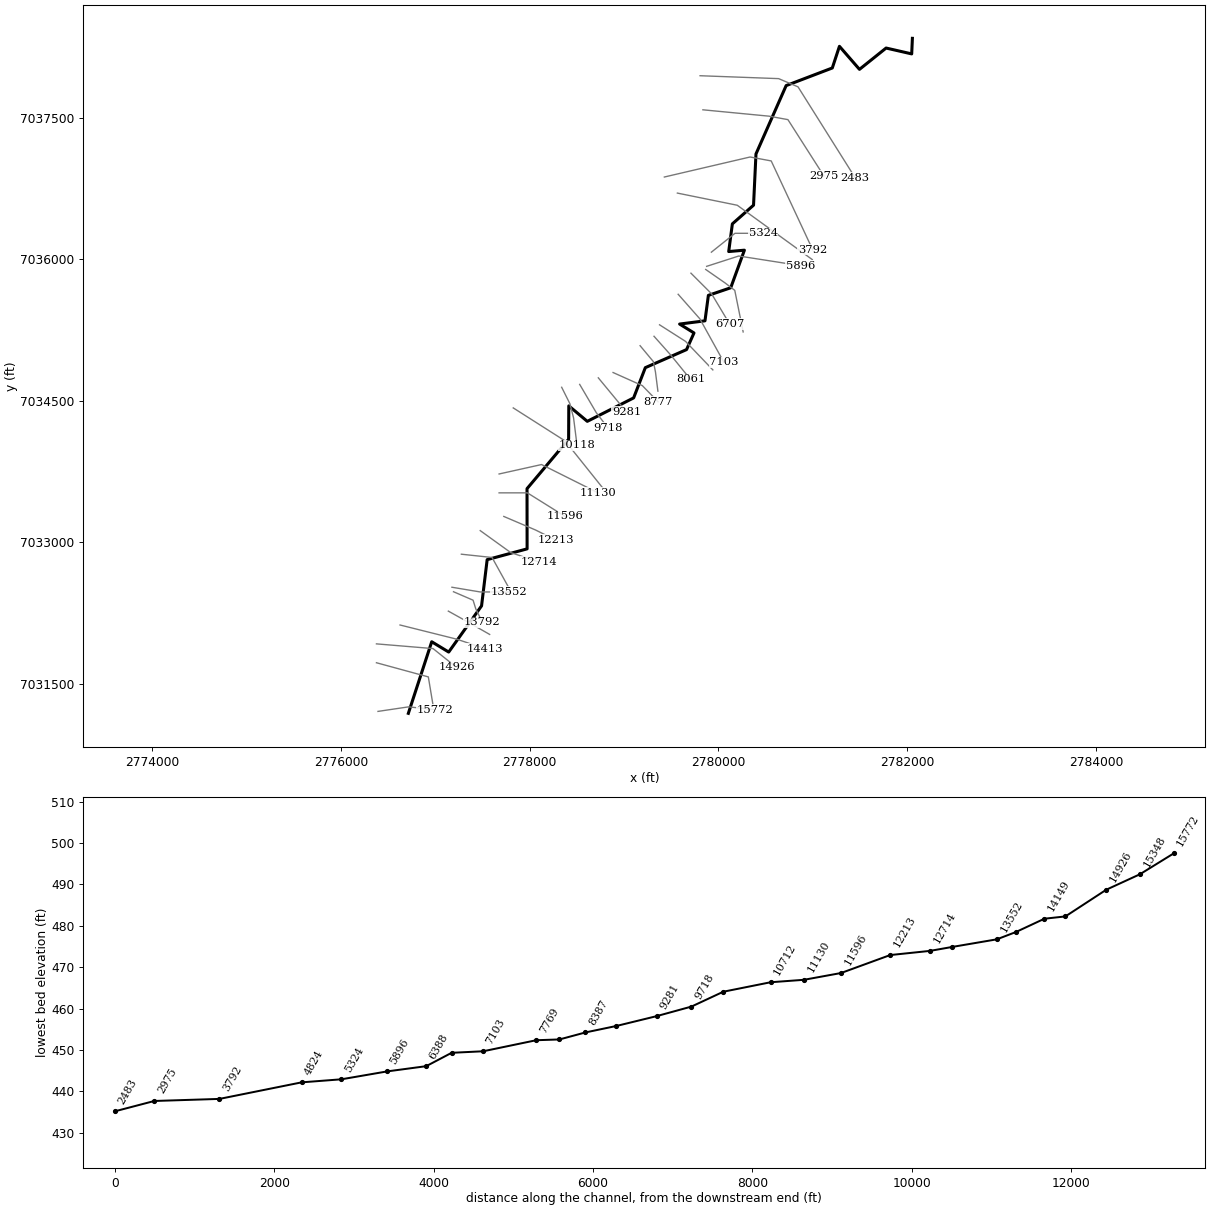
--- Rice Branch.prj (project) ---

Proj Title=Rice Branch Base Level Engineering
Current Plan=p01
Default Exp/Contr=0.3,0.1
English Units
Geom File=g01
Flow File=f01
Plan File=p01
BEGIN DESCRIPTION:
Rice Branch
END DESCRIPTION:

--- Rice Branch.p01 (plan) ---

Plan Title=Multiple Run
Short Identifier=Multiple
Geom File=g01
Flow File=f01
Subcritical Flow
K Sum by GR= 0
Std Step Tol= 0.01
Critical Tol= 0.01
Num of Std Step Trials= 20
Max Error Tol= 0.3
Flow Tol Ratio= 0.001
Split Flow NTrial= 30
Split Flow Tol= 0.02
Split Flow Ratio= 0.02
Log Output Level= 0
Friction Slope Method= 1
Unsteady Friction Slope Method= 2
Unsteady Bridges Friction Slope Method= 1
Parabolic Critical Depth
Global Vel Dist=  1 , 1 , 1
Global Log Level= 0
CheckData=True
Encroach Param= -1, 0, 0, 0
BEGIN DESCRIPTION:
Multiple Run
END DESCRIPTION:

--- Rice Branch.f01 (steady flow) ---

Flow Title=Multiple
Number of Profiles=7
Profile Names=10-year,25-year,50-year,1pct_min,100-year,1pct_plu,500-year
River Rch & RM= Rice Branch,Reach-1,15772
     315     407     479     281     561    1118     768
River Rch & RM= Rice Branch,Reach-1,11130
     415     544     648     384     765    1527    1070
River Rch & RM= Rice Branch,Reach-1,8061
     714     965    1171     706    1409    2811    2041
Boundary for River Rch & Prof#=Rice Branch,Reach-1,1
Up Type=0
Dn Type=3
Dn Slope=0.005
Boundary for River Rch & Prof#=Rice Branch,Reach-1,2
Up Type=0
Dn Type=3
Dn Slope=0.005
Boundary for River Rch & Prof#=Rice Branch,Reach-1,3
Up Type=0
Dn Type=3
Dn Slope=0.005
Boundary for River Rch & Prof#=Rice Branch,Reach-1,4
Up Type=0
Dn Type=3
Dn Slope=0.005
Boundary for River Rch & Prof#=Rice Branch,Reach-1,5
Up Type=0
Dn Type=3
Dn Slope=0.005
Boundary for River Rch & Prof#=Rice Branch,Reach-1,6
Up Type=0
Dn Type=3
Dn Slope=0.005
Boundary for River Rch & Prof#=Rice Branch,Reach-1,7
Up Type=0
Dn Type=3
Dn Slope=0.005

--- Rice Branch.g01 (geometry) ---

Geom Title=Existing Conditions

River Reach=Rice Branch,Reach-1
Reach XY= 30
      2776713.22      7031188.93      2776960.94      7031947.38
      2777140.95      7031838.17      2777489.17      7032327.57
      2777548.51      7032817.40      2777971.90      7032931.52
      2777970.97      7033569.33      2778411.98      7034093.11
      2778413.73      7034446.91      2778609.73      7034282.71
      2779101.03      7034530.98      2779224.92      7034851.43
      2779661.89      7035042.85      2779740.78      7035219.15
      2779588.32      7035313.50      2779857.16      7035347.66
      2779893.21      7035617.51      2780130.14      7035697.96
      2780275.02      7036096.05      2780108.73      7036081.71
      2780147.44      7036374.92      2780371.91      7036572.91
      2780397.72      7037115.72      2780717.49      7037839.91
      2781206.76      7038026.62      2781282.35      7038256.21
      2781494.74      7038011.93      2781776.90      7038237.87
      2782048.24      7038175.83      2782055.59      7038340.71

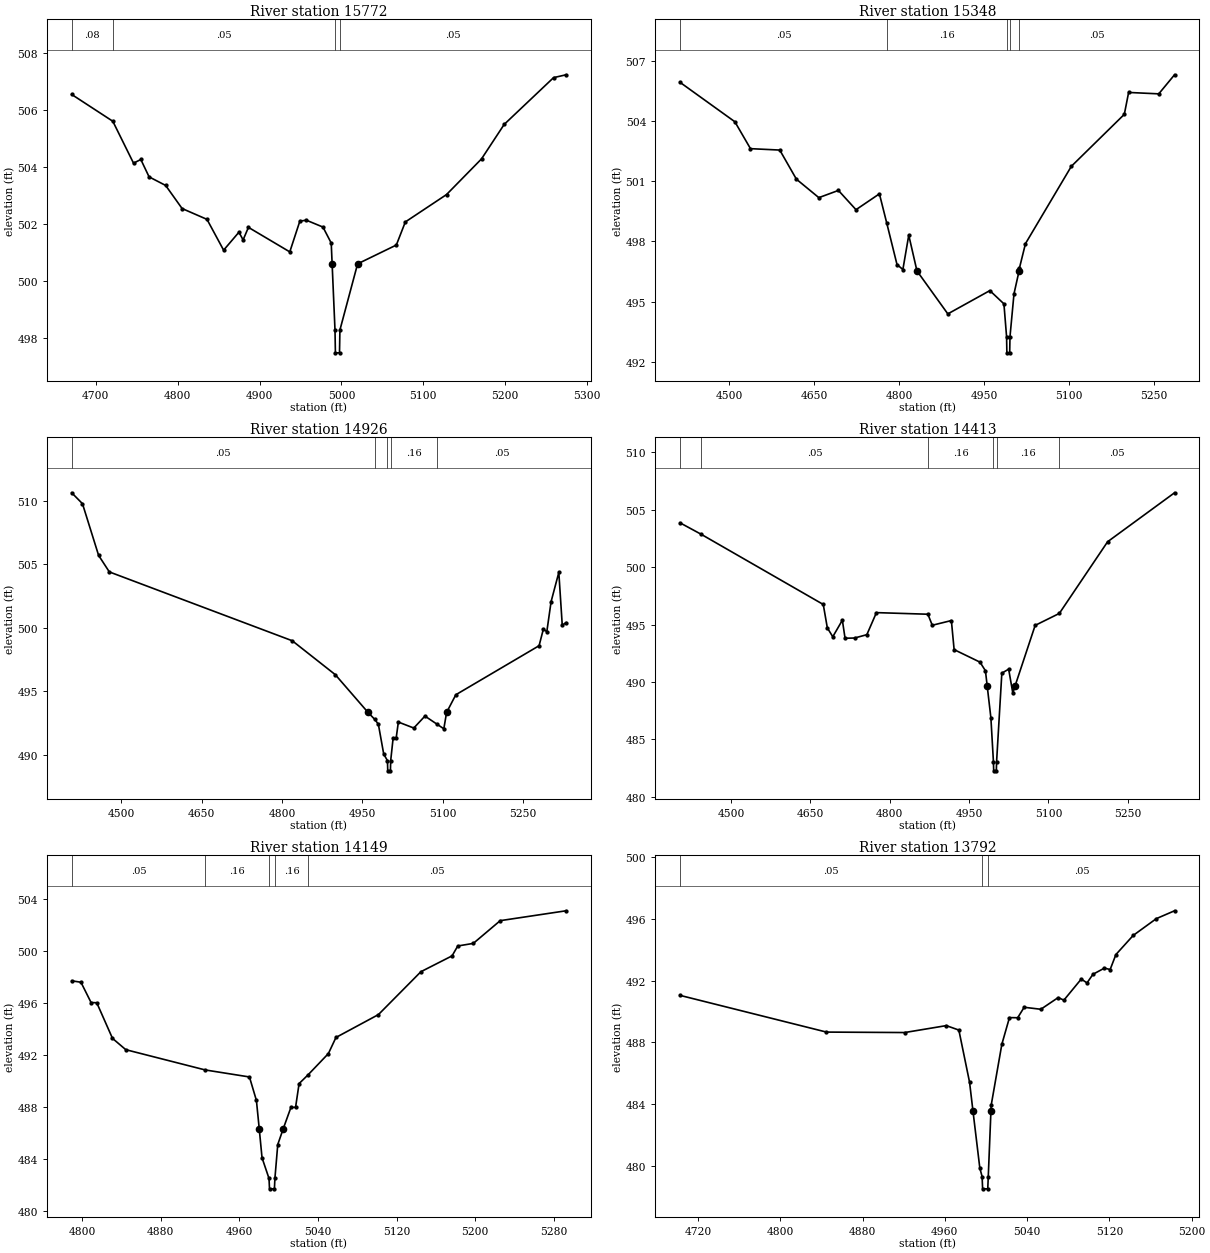
Type RM Length L Ch R = 1,15772,424,424,424
BEGIN DESCRIPTION:
Rice Branch 28.0
END DESCRIPTION:
XS GIS Cut Line= 3
      2776391.56      7031209.45      2776715.06      7031257.54
      2776990.25      7031229.15
#Sta/Elev= 30
  4670.6  506.55  4720.8  505.61  4746.1  504.14  4755.0  504.27  4765.1  503.66
  4785.3  503.36  4805.4  502.55  4835.8  502.17  4856.1  501.09  4874.8  501.72
  4879.9  501.45  4886.4  501.89  4936.9  501.03  4949.2  502.11  4957.2  502.14
  4977.4  501.90  4987.5  501.34  4988.6  500.61  4992.1  498.29  4992.6  497.49
  4997.6  497.49  4998.1  498.29  5019.7  500.61  5067.0  501.27  5078.0  502.08
  5128.3  503.04  5171.0  504.29  5198.7  505.50  5259.0  507.14  5274.3  507.24
#Mann=4,-1,0
  4670.6    0.08       0  4720.8    0.05       0  4992.1    0.03       0
  4998.1    0.05       0
Bank Sta=4988.6,5019.7
Exp/Cntr=0.3,0.1

Type RM Length L Ch R = 1,15348,422,422,422
BEGIN DESCRIPTION:
Rice Branch 27.0
END DESCRIPTION:
XS GIS Cut Line= 3
      2776374.98      7031725.01      2776925.00      7031575.00
      2776975.01      7031274.95
#Sta/Elev= 30
  4412.8  505.92  4509.6  503.96  4537.2  502.62  4589.0  502.55  4618.4  501.10
  4658.1  500.18  4692.7  500.54  4723.8  499.58  4765.2  500.37  4778.3  498.90
  4796.3  496.85  4806.7  496.60  4817.1  498.31  4831.6  496.53  4886.2  494.39
  4960.5  495.55  4985.4  494.89  4990.1  493.25  4990.6  492.45  4995.6  492.45
  4996.1  493.25  5003.2  495.39  5012.2  496.53  5012.9  496.68  5023.5  497.89
  5104.6  501.74  5198.3  504.33  5205.9  505.42  5259.2  505.35  5287.1  506.30
#Mann=5,-1,0
  4412.8    0.05       0  4778.3    0.16       0  4990.1    0.07       0
  4996.1    0.16       0  5012.9    0.05       0
Bank Sta=4831.6,5012.2
Exp/Cntr=0.3,0.1

Type RM Length L Ch R = 1,14926,513,513,513
BEGIN DESCRIPTION:
Rice Branch 26.0
END DESCRIPTION:
XS GIS Cut Line= 3
      2776375.00      7031925.00      2776975.00      7031875.00
      2777224.97      7031675.02
#Sta/Elev= 30
  4407.8  510.61  4427.9  509.75  4458.0  505.68  4478.0  504.38  4819.2  498.96
  4899.5  496.29  4960.5  493.32  4973.1  492.77  4979.8  492.39  4989.8  490.04
  4996.8  489.52  4997.3  488.72  5002.3  488.72  5002.8  489.52  5007.4  491.32
  5013.1  491.32  5017.1  492.56  5045.9  492.09  5066.7  493.03  5090.0  492.37
  5101.9  492.03  5107.1  493.32  5124.3  494.71  5279.6  498.57  5287.6  499.88
  5294.0  499.67  5302.0  502.04  5316.4  504.34  5322.8  500.19  5330.0  500.39
#Mann=5,-1,0
  4407.8    0.05       0  4973.1    0.16       0  4996.8    0.07       0
  5002.8    0.16       0  5090.0    0.05       0
Bank Sta=4960.5,5107.1
Exp/Cntr=0.3,0.1

Type RM Length L Ch R = 1,14413,264,264,264
BEGIN DESCRIPTION:
Rice Branch 25.0
END DESCRIPTION:
XS GIS Cut Line= 3
      2776625.00      7032125.00      2777225.00      7031975.00
      2777525.01      7031875.00
#Sta/Elev= 30
  4403.7  503.85  4443.4  502.86  4674.3  496.75  4682.0  494.71  4692.3  493.94
  4710.4  495.38  4715.5  493.81  4733.5  493.83  4756.7  494.12  4774.8  496.04
  4872.1  495.90  4880.4  494.94  4916.5  495.35  4921.7  492.82  4970.6  491.73
  4980.9  490.98  4984.2  489.67  4991.2  486.89  4996.0  483.07  4996.5  482.27
  5001.5  482.27  5002.0  483.07  5011.9  490.77  5024.8  491.12  5032.7  489.03
  5037.0  489.67  5074.9  494.93  5120.6  495.97  5211.9  502.21  5338.4  506.47
#Mann=6,-1,0
  4403.7    0.08       0  4443.4    0.05       0  4872.1    0.16       0
  4996.0    0.07       0  5002.0    0.16       0  5120.6    0.05       0
Bank Sta=4984.2,5037
Exp/Cntr=0.3,0.1

Type RM Length L Ch R = 1,14149,357,357,357
BEGIN DESCRIPTION:
Rice Branch 24.0
END DESCRIPTION:
XS GIS Cut Line= 3
      2777136.94      7032271.92      2777333.74      7032162.59
      2777575.03      7032024.98
#Sta/Elev= 30
  4789.5  497.72  4798.9  497.61  4809.2  496.05  4815.0  496.03  4831.0  493.29
  4844.5  492.42  4925.3  490.86  4970.3  490.32  4977.4  488.51  4980.3  486.30
  4983.1  484.10  4990.2  482.51  4990.7  481.71  4995.7  481.71  4996.2  482.51
  4999.1  485.12  5004.5  486.30  5012.5  487.98  5017.2  487.98  5020.8  489.81
  5030.0  490.49  5050.6  492.12  5058.3  493.36  5101.5  495.12  5144.7  498.42
  5176.4  499.64  5182.2  500.40  5198.0  500.60  5225.4  502.35  5292.4  503.11
#Mann=5,-1,0
  4789.5    0.05       0  4925.3    0.16       0  4990.2    0.07       0
  4996.2    0.16       0  5030.0    0.05       0
Bank Sta=4980.3,5004.5
Exp/Cntr=0.3,0.1

Type RM Length L Ch R = 1,13792,240,240,240
BEGIN DESCRIPTION:
Mapping XS 153c7793
END DESCRIPTION:
XS GIS Cut Line= 4
      2777191.63      7032477.40      2777399.32      7032387.77
      2777427.74      7032295.95      2777497.69      7032153.86
#Sta/Elev= 30
  4702.6  491.05  4844.9  488.67  4920.9  488.64  4961.4  489.09  4973.6  488.80
  4984.0  485.42  4987.3  483.56  4994.0  479.84  4996.2  479.30  4996.7  478.50
  5001.7  478.50  5002.2  479.30  5004.8  483.56  5005.0  483.91  5015.4  487.88
  5022.8  489.61  5030.8  489.60  5037.1  490.28  5053.3  490.15  5070.2  490.91
  5075.7  490.74  5092.6  492.11  5098.2  491.86  5104.0  492.42  5115.1  492.82
  5120.7  492.73  5126.3  493.70  5143.1  494.94  5165.6  496.03  5183.3  496.54
#Mann=3,-1,0
  4702.6    0.05       0  4996.2    0.03       0  5002.2    0.05       0
Bank Sta=4987.3,5004.8
Exp/Cntr=0.3,0.1

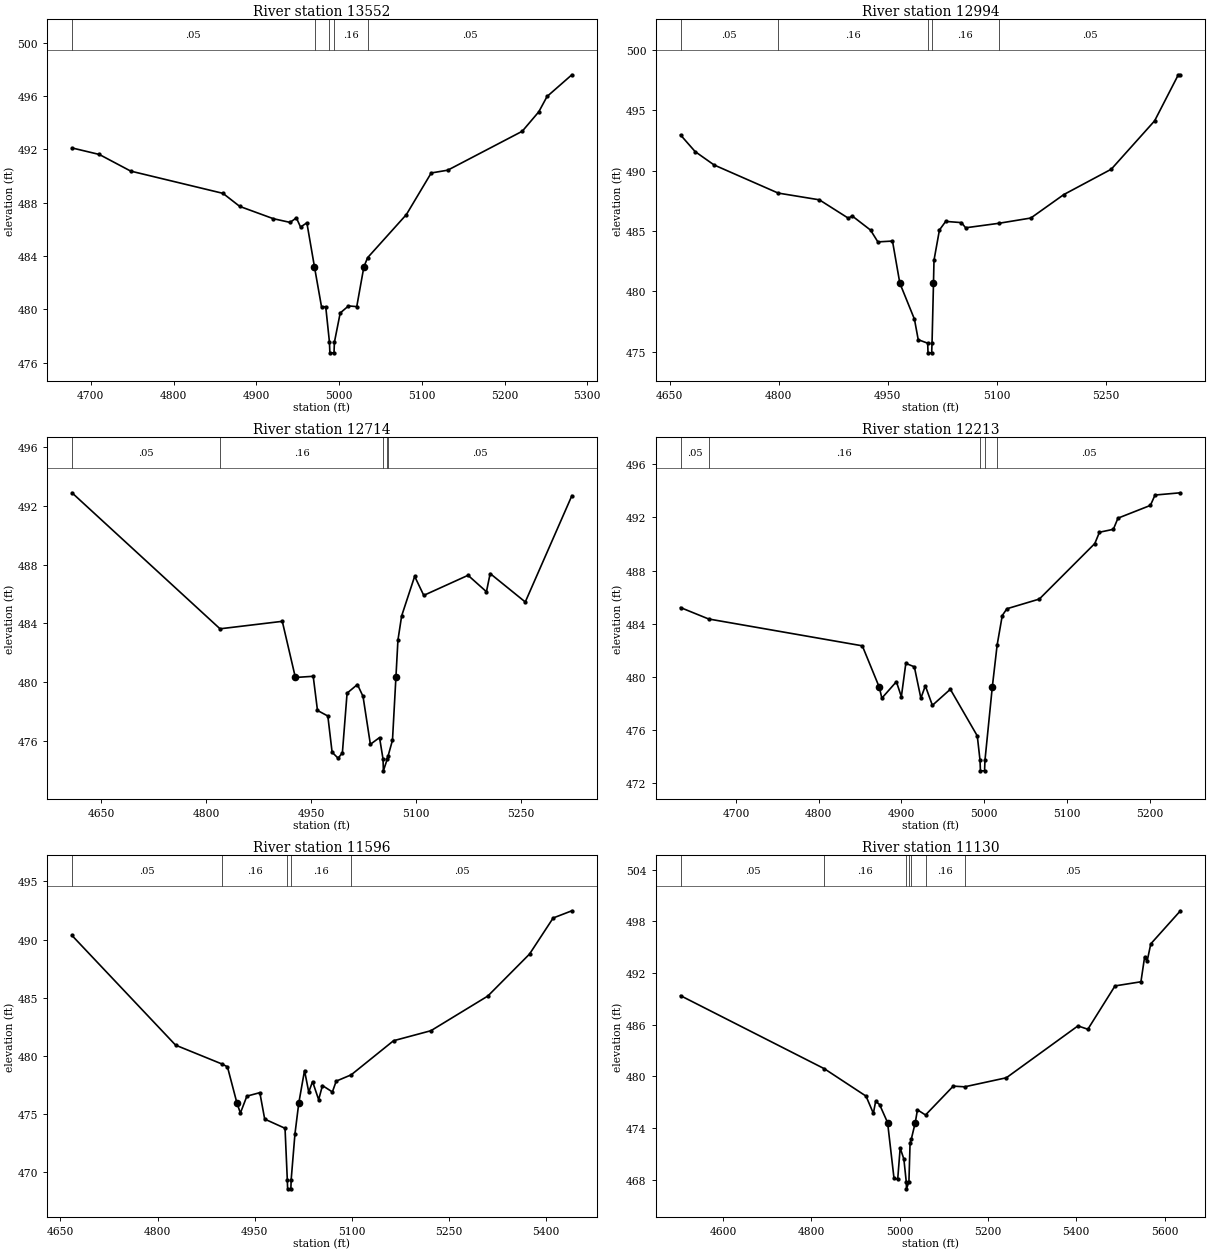
Type RM Length L Ch R = 1,13552,558,558,558
BEGIN DESCRIPTION:
Rice Branch 23.0
END DESCRIPTION:
XS GIS Cut Line= 3
      2777174.96      7032525.01      2777475.00      7032475.00
      2777775.02      7032475.00
#Sta/Elev= 30
  4677.2  492.11  4710.2  491.62  4748.2  490.37  4859.7  488.70  4880.0  487.72
  4920.5  486.80  4940.8  486.52  4948.4  486.86  4953.5  486.17  4961.1  486.49
  4970.3  483.18  4970.6  483.07  4978.8  480.19  4983.9  480.19  4988.4  477.53
  4988.9  476.73  4993.9  476.73  4994.4  477.53  5001.4  479.72  5011.4  480.25
  5021.4  480.20  5030.0  483.18  5034.5  483.87  5081.4  487.11  5111.4  490.23
  5131.4  490.44  5221.4  493.36  5241.4  494.82  5251.4  495.97  5281.4  497.60
#Mann=5,-1,0
  4677.2    0.05       0  4970.6    0.16       0  4988.4    0.07       0
  4994.4    0.16       0  5034.5    0.05       0
Bank Sta=4970.3,5030
Exp/Cntr=0.3,0.1

Type RM Length L Ch R = 1,12994,280,280,280
BEGIN DESCRIPTION:
Rice Branch 22.0
END DESCRIPTION:
XS GIS Cut Line= 3
      2777275.03      7032875.00      2777600.44      7032840.29
      2777775.02      7032524.96
#Sta/Elev= 30
  4665.1  492.97  4685.2  491.59  4711.3  490.48  4799.4  488.15  4856.1  487.59
  4896.1  486.06  4901.1  486.26  4926.5  485.08  4936.6  484.10  4956.7  484.17
  4966.8  480.68  4986.9  477.69  4992.1  475.99  5005.1  475.70  5005.6  474.90
  5010.6  474.90  5011.1  475.70  5013.1  480.67  5013.8  482.58  5021.3  485.09
  5029.9  485.80  5051.6  485.70  5057.3  485.27  5102.7  485.64  5147.0  486.08
  5192.5  488.03  5257.7  490.13  5317.3  494.14  5349.9  497.96  5352.8  497.96
#Mann=5,-1,0
  4665.1    0.05       0  4799.4    0.16       0  5005.1    0.07       0
  5011.1    0.16       0  5102.7    0.05       0
Bank Sta=4966.8,5013.1
Exp/Cntr=0.3,0.1

Type RM Length L Ch R = 1,12714,501,501,501
BEGIN DESCRIPTION:
Rice Branch 21.0
END DESCRIPTION:
XS GIS Cut Line= 3
      2777475.04      7033124.97      2777798.20      7032892.21
      2778098.21      7032792.21
#Sta/Elev= 30
  4607.8  492.91  4819.4  483.63  4908.4  484.14  4927.1  480.31  4952.6  480.39
  4958.7  478.06  4973.5  477.68  4979.6  475.21  4988.2  474.80  4994.3  475.17
  5001.0  479.24  5015.8  479.83  5023.8  479.02  5034.3  475.75  5047.4  476.21
  5052.4  474.74  5052.9  473.94  5058.4  474.74  5059.6  474.95  5065.9  476.03
  5070.8  480.31  5073.7  482.86  5079.0  484.51  5097.6  487.21  5110.6  485.91
  5173.9  487.28  5200.2  486.16  5205.5  487.40  5255.7  485.46  5322.3  492.71
#Mann=5,-1,0
  4607.8    0.05       0  4819.4    0.16       0  5052.4    0.07       0
  5058.4    0.16       0  5059.6    0.05       0
Bank Sta=4927.1,5070.8
Exp/Cntr=0.3,0.1

Type RM Length L Ch R = 1,12213,617,617,617
BEGIN DESCRIPTION:
Rice Branch 20.0
END DESCRIPTION:
XS GIS Cut Line= 3
      2777724.96      7033275.02      2778061.57      7033131.35
      2778274.96      7033025.02
#Sta/Elev= 30
  4632.9  485.22  4666.9  484.36  4852.7  482.34  4873.3  479.21  4876.3  478.40
  4893.9  479.64  4899.9  478.51  4905.3  481.02  4915.6  480.76  4923.5  478.40
  4928.9  479.33  4937.4  477.86  4959.1  479.07  4991.7  475.56  4995.0  473.73
  4995.5  472.93  5000.5  472.93  5001.0  473.73  5009.8  479.21  5015.7  482.40
  5021.9  484.62  5027.5  485.13  5066.7  485.86  5133.8  490.04  5139.4  490.89
  5156.2  491.11  5161.8  491.95  5201.0  492.91  5206.6  493.69  5237.3  493.86
#Mann=5,-1,0
  4632.9    0.05       0  4666.9    0.16       0  4995.0    0.07       0
  5001.0    0.16       0  5015.7    0.05       0
Bank Sta=4873.3,5009.8
Exp/Cntr=0.3,0.1

Type RM Length L Ch R = 1,11596,466,466,466
BEGIN DESCRIPTION:
Rice Branch 19.0
END DESCRIPTION:
XS GIS Cut Line= 3
      2777674.99      7033525.00      2777975.00      7033525.00
      2778374.99      7033275.01
#Sta/Elev= 30
  4667.8  490.35  4827.8  480.93  4899.4  479.31  4907.8  479.07  4922.5  475.95
  4927.8  475.10  4937.8  476.55  4957.8  476.85  4965.3  474.58  4996.7  473.79
  5000.2  469.39  5000.7  468.59  5005.7  468.59  5006.2  469.39  5012.0  473.30
  5017.9  475.95  5026.8  478.75  5033.3  476.90  5039.2  477.80  5048.6  476.25
  5054.5  477.46  5069.8  476.91  5075.7  477.84  5098.8  478.38  5164.2  481.31
  5221.9  482.17  5309.8  485.15  5374.1  488.75  5410.6  491.85  5439.5  492.47
#Mann=5,-1,0
  4667.8    0.05       0  4899.4    0.16       0  5000.2    0.07       0
  5006.2    0.16       0  5098.8    0.05       0
Bank Sta=4922.5,5017.9
Exp/Cntr=0.3,0.1

Type RM Length L Ch R = 1,11130,418,418,418
BEGIN DESCRIPTION:
Rice Branch 18.0
END DESCRIPTION:
XS GIS Cut Line= 3
      2777675.00      7033725.00      2778125.00      7033825.00
      2778725.01      7033525.00
#Sta/Elev= 30
  4504.0  489.37  4829.6  480.89  4924.0  477.71  4940.6  475.71  4945.8  477.11
  4954.7  476.73  4972.8  474.64  4987.3  468.19  4995.7  468.06  5001.3  471.69
  5009.7  470.40  5015.1  467.75  5015.6  466.95  5021.1  467.75  5023.7  472.26
  5026.3  472.68  5035.5  474.64  5040.4  476.12  5058.7  475.52  5121.5  478.87
  5147.2  478.79  5241.7  479.84  5403.8  485.86  5426.2  485.47  5487.7  490.50
  5546.4  490.98  5554.7  493.85  5560.3  493.34  5568.7  495.38  5635.8  499.22
#Mann=7,-1,0
  4504.0    0.05       0  4829.6    0.16       0  5015.1    0.07       0
  5021.1    0.16       0  5026.3    0.05       0  5058.7    0.16       0
  5147.2    0.05       0
Bank Sta=4972.8,5035.5
Exp/Cntr=0.3,0.1

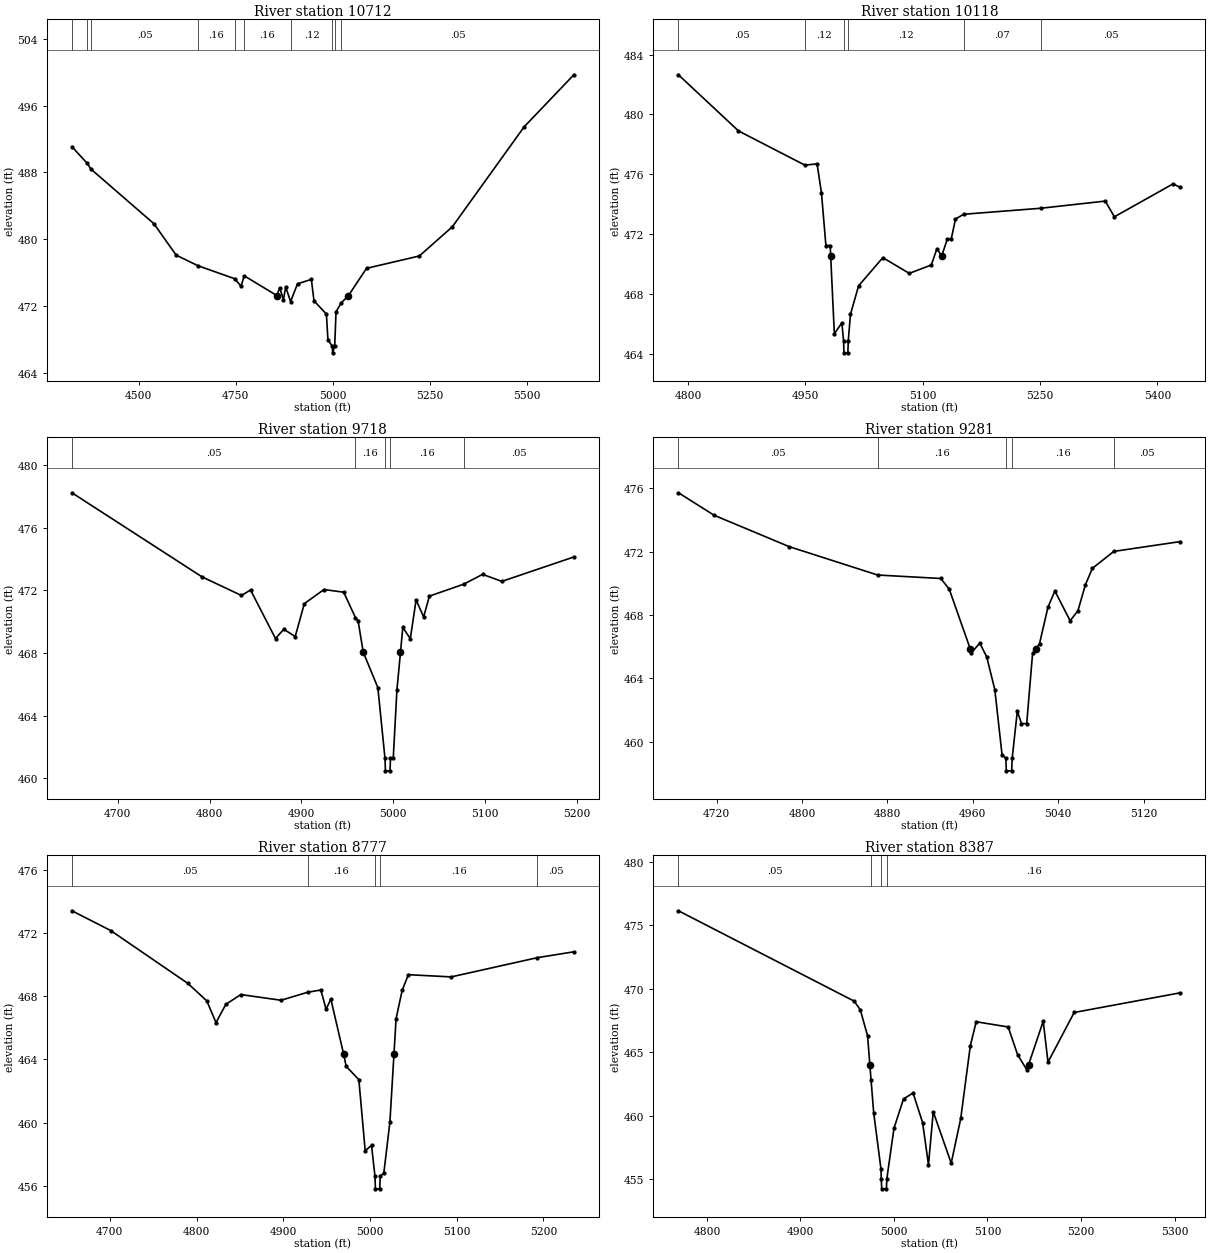
Type RM Length L Ch R = 1,10712,594,594,594
BEGIN DESCRIPTION:
Rice Branch 17.0
END DESCRIPTION:
XS GIS Cut Line= 3
      2777825.00      7034425.00      2778375.00      7034075.00
      2778774.98      7033575.03
#Sta/Elev= 30
  4328.6  491.07  4367.4  489.10  4377.6  488.38  4539.4  481.85  4597.0  478.07
  4653.1  476.80  4747.8  475.24  4763.8  474.35  4772.3  475.59  4856.0  473.23
  4863.7  474.17  4873.0  472.71  4878.9  474.25  4891.5  472.51  4909.4  474.64
  4945.0  475.16  4951.7  472.60  4983.7  471.01  4987.7  467.89  4999.1  467.16
  4999.6  466.36  5005.1  467.16  5008.5  471.28  5021.9  472.35  5040.6  473.23
  5087.0  476.49  5223.0  477.97  5307.9  481.47  5492.8  493.45  5620.8  499.69
#Mann=10,-1,0
  4328.6    0.05       0  4367.4    0.16       0  4377.6    0.05       0
  4653.1    0.16       0  4747.8    0.05       0  4772.3    0.16       0
  4891.5    0.12       0  4999.1    0.07       0  5005.1    0.12       0
  5021.9    0.05       0
Bank Sta=4856,5040.6
Exp/Cntr=0.3,0.1

Type RM Length L Ch R = 1,10118,400,400,400
BEGIN DESCRIPTION:
Mapping XS 705feac6
END DESCRIPTION:
XS GIS Cut Line= 4
      2778338.28      7034643.71      2778425.11      7034470.06
      2778464.17      7034320.32      2778501.04      7034029.74
#Sta/Elev= 30
  4787.6  482.65  4864.4  478.90  4949.4  476.61  4964.9  476.70  4970.5  474.76
  4976.2  471.24  4981.7  471.24  4982.3  470.54  4987.0  465.34  4996.6  466.08
  4998.8  464.87  4999.3  464.07  5004.3  464.07  5004.8  464.87  5007.6  466.64
  5018.0  468.55  5049.0  470.43  5082.8  469.38  5111.0  469.94  5118.1  471.02
  5124.3  470.54  5131.5  471.69  5136.5  471.69  5141.9  473.01  5152.3  473.33
  5250.7  473.73  5333.4  474.21  5345.1  473.16  5420.1  475.36  5429.4  475.12
#Mann=6,-1,0
  4787.6    0.05       0  4949.4    0.12       0  4998.8    0.07       0
  5004.8    0.12       0  5152.3    0.07       0  5250.7    0.05       0
Bank Sta=4982.3,5124.3
Exp/Cntr=0.3,0.1

Type RM Length L Ch R = 1,9718,437,437,437
BEGIN DESCRIPTION:
Mapping XS 75835592
END DESCRIPTION:
XS GIS Cut Line= 3
      2778529.30      7034674.01      2778705.06      7034374.57
      2778826.60      7034216.13
#Sta/Elev= 30
  4650.1  478.24  4791.8  472.87  4834.8  471.68  4844.7  472.03  4871.9  468.93
  4880.9  469.52  4893.4  469.06  4903.3  471.16  4924.7  472.06  4946.2  471.89
  4959.0  470.27  4961.9  470.06  4967.5  468.06  4983.4  465.80  4991.2  461.28
  4991.7  460.48  4996.7  460.48  4997.2  461.28  5000.2  461.28  5004.2  465.64
  5008.1  468.06  5010.6  469.64  5018.8  468.92  5025.1  471.40  5033.3  470.31
  5039.6  471.64  5076.9  472.40  5097.6  473.03  5118.5  472.58  5197.0  474.14
#Mann=5,-1,0
  4650.1    0.05       0  4959.0    0.16       0  4991.2    0.07       0
  4997.2    0.16       0  5076.9    0.05       0
Bank Sta=4967.5,5008.1
Exp/Cntr=0.3,0.1

Type RM Length L Ch R = 1,9281,504,504,504
BEGIN DESCRIPTION:
Mapping XS 878e2385
END DESCRIPTION:
XS GIS Cut Line= 3
      2778726.74      7034743.52      2778932.92      7034493.93
      2779026.26      7034381.06
#Sta/Elev= 30
  4684.2  475.72  4717.7  474.30  4788.0  472.32  4870.8  470.53  4930.0  470.31
  4937.9  469.64  4957.7  465.85  4958.7  465.62  4966.5  466.23  4973.0  465.37
  4980.6  463.30  4987.4  459.18  4990.9  458.97  4991.4  458.17  4996.4  458.17
  4996.9  458.97  5001.7  461.94  5005.6  461.15  5010.5  461.15  5016.0  465.59
  5018.8  465.85  5022.5  466.20  5030.4  468.50  5036.9  469.52  5051.2  467.64
  5058.5  468.28  5065.5  469.92  5072.0  470.95  5092.1  472.02  5154.4  472.64
#Mann=5,-1,0
  4684.2    0.05       0  4870.8    0.16       0  4990.9    0.07       0
  4996.9    0.16       0  5092.1    0.05       0
Bank Sta=4957.7,5018.8
Exp/Cntr=0.3,0.1

Type RM Length L Ch R = 1,8777,390,390,390
BEGIN DESCRIPTION:
Mapping XS 8ae53ffc
END DESCRIPTION:
XS GIS Cut Line= 3
      2778883.05      7034799.90      2779193.34      7034661.03
      2779359.99      7034490.05
#Sta/Elev= 30
  4656.3  473.42  4700.9  472.17  4789.9  468.82  4811.8  467.71  4822.4  466.33
  4833.7  467.49  4851.0  468.11  4897.4  467.75  4928.3  468.26  4943.3  468.40
  4949.3  467.18  4954.8  467.82  4969.5  464.35  4972.5  463.56  4987.1  462.72
  4994.4  458.22  5001.7  458.55  5005.7  456.60  5006.2  455.80  5011.2  455.80
  5011.7  456.60  5015.9  456.80  5022.9  460.03  5027.6  464.35  5030.0  466.57
  5037.0  468.37  5044.2  469.37  5093.6  469.23  5193.0  470.45  5235.0  470.82
#Mann=5,-1,0
  4656.3    0.05       0  4928.3    0.16       0  5005.7    0.07       0
  5011.7    0.16       0  5193.0    0.05       0
Bank Sta=4969.5,5027.6
Exp/Cntr=0.3,0.1

Type RM Length L Ch R = 1,8387,326,326,326
BEGIN DESCRIPTION:
Mapping XS 452c0c87
END DESCRIPTION:
XS GIS Cut Line= 4
      2779169.46      7035084.22      2779310.53      7034914.94
      2779332.23      7034806.43      2779358.28      7034602.39
#Sta/Elev= 30
  4769.5  476.13  4957.5  469.01  4964.0  468.33  4971.8  466.27  4974.2  464.00
  4975.5  462.80  4978.3  460.23  4986.1  455.79  4986.4  455.03  4986.9  454.23
  4991.9  454.23  4992.4  455.03  5000.0  459.00  5010.2  461.31  5020.4  461.78
  5030.6  459.45  5036.9  456.13  5042.0  460.30  5061.2  456.25  5071.4  459.77
  5081.6  465.48  5087.9  467.39  5122.1  466.98  5132.2  464.80  5142.3  463.57
  5143.9  464.00  5159.6  467.43  5164.7  464.21  5192.7  468.12  5306.2  469.67
#Mann=4,-1,0
  4769.5    0.05       0  4975.5    0.16       0  4986.4    0.07       0
  4992.4    0.16       0
Bank Sta=4974.2,5143.9
Exp/Cntr=0.3,0.1

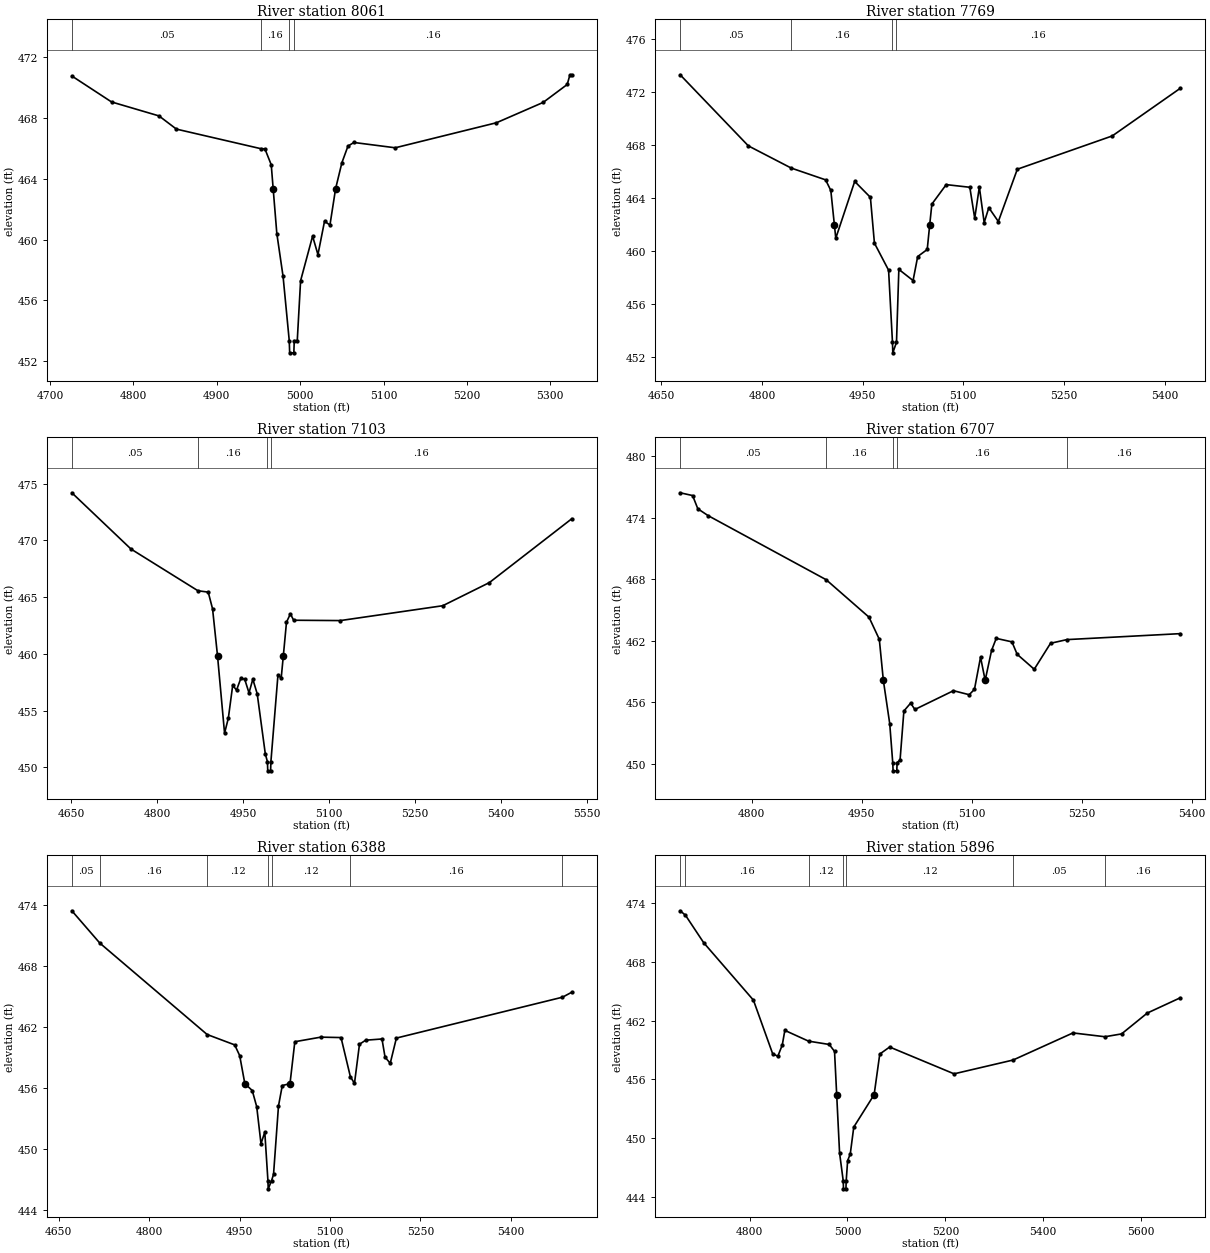
Type RM Length L Ch R = 1,8061,292,292,292
BEGIN DESCRIPTION:
Mapping XS 74797036
END DESCRIPTION:
XS GIS Cut Line= 3
      2779317.01      7035184.06      2779494.99      7034984.38
      2779704.13      7034726.52
#Sta/Elev= 30
  4726.2  470.78  4773.8  469.07  4830.7  468.15  4851.6  467.28  4952.9  465.99
  4957.7  465.98  4965.3  464.93  4967.6  463.36  4972.0  460.40  4979.5  457.57
  4986.9  453.34  4987.4  452.54  4992.4  452.54  4992.9  453.34  4996.5  453.34
  5000.5  457.29  5014.9  460.23  5021.3  459.01  5029.2  461.21  5035.7  460.96
  5042.5  463.36  5050.0  465.06  5057.3  466.16  5064.4  466.40  5114.0  466.05
  5235.4  467.70  5291.4  469.04  5320.2  470.22  5323.5  470.86  5325.7  470.86
#Mann=4,-1,0
  4726.2    0.05       0  4952.9    0.16       0  4986.9    0.07       0
  4992.9    0.16       0
Bank Sta=4967.6,5042.5
Exp/Cntr=0.3,0.1

Type RM Length L Ch R = 1,7769,666,666,666
BEGIN DESCRIPTION:
Mapping XS 2a39125f
END DESCRIPTION:
XS GIS Cut Line= 3
      2779375.63      7035305.56      2779651.24      7035129.78
      2779940.61      7034827.71
#Sta/Elev= 30
  4678.0  473.31  4779.7  467.95  4843.5  466.28  4894.8  465.39  4902.6  464.59
  4907.9  462.00  4910.0  460.99  4938.2  465.27  4961.6  464.07  4967.6  460.62
  4988.7  458.58  4994.5  453.15  4995.0  452.35  5000.5  453.15  5004.0  458.64
  5025.2  457.80  5032.1  459.61  5046.3  460.14  5050.0  462.00  5053.2  463.56
  5074.6  465.03  5109.8  464.83  5117.1  462.49  5124.0  464.85  5131.2  462.17
  5138.1  463.29  5152.3  462.25  5180.6  466.19  5322.1  468.70  5423.2  472.28
#Mann=4,-1,0
  4678.0    0.05       0  4843.5    0.16       0  4994.5    0.07       0
  5000.5    0.16       0
Bank Sta=4907.9,5050
Exp/Cntr=0.3,0.1

Type RM Length L Ch R = 1,7103,396,396,396
BEGIN DESCRIPTION:
Mapping XS 65d71694
END DESCRIPTION:
XS GIS Cut Line= 3
      2779573.13      7035628.89      2779803.15      7035368.49
      2780057.11      7034909.75
#Sta/Elev= 30
  4651.7  474.20  4754.8  469.24  4871.6  465.56  4889.5  465.44  4897.1  463.96
  4905.7  459.83  4918.0  453.00  4924.6  454.33  4932.2  457.22  4938.9  456.80
  4946.4  457.84  4953.1  457.76  4960.6  456.56  4967.3  457.76  4974.9  456.48
  4989.1  451.16  4992.8  450.48  4993.3  449.68  4998.3  449.68  4998.8  450.48
  5011.1  458.12  5016.8  457.88  5020.5  459.83  5026.0  462.79  5032.8  463.52
  5038.5  462.96  5119.8  462.93  5298.5  464.24  5379.8  466.28  5523.5  471.91
#Mann=4,-1,0
  4651.7    0.05       0  4871.6    0.16       0  4992.8    0.07       0
  4998.8    0.16       0
Bank Sta=4905.7,5020.5
Exp/Cntr=0.3,0.1

Type RM Length L Ch R = 1,6707,319,319,319
BEGIN DESCRIPTION:
Mapping XS c526aa36
END DESCRIPTION:
XS GIS Cut Line= 3
      2779708.55      7035852.56      2779927.28      7035633.83
      2780118.25      7035314.40
#Sta/Elev= 30
  4702.7  476.41  4719.7  476.14  4726.8  474.85  4740.9  474.18  4901.7  467.94
  4960.1  464.29  4974.2  462.13  4979.7  458.13  4988.4  453.91  4992.5  450.11
  4993.0  449.31  4998.0  449.31  4998.5  450.11  5002.5  450.37  5007.7  455.14
  5016.9  455.91  5022.7  455.29  5075.3  457.12  5096.7  456.73  5103.9  457.25
  5112.2  460.39  5118.5  458.13  5127.2  461.04  5133.6  462.22  5155.0  461.88
  5162.1  460.67  5185.4  459.21  5207.6  461.74  5229.9  462.10  5384.2  462.68
#Mann=5,-1,0
  4702.7    0.05       0  4901.7    0.16       0  4992.5    0.07       0
  4998.5    0.16       0  5229.9    0.16       0
Bank Sta=4979.7,5118.5
Exp/Cntr=0.3,0.1

Type RM Length L Ch R = 1,6388,492,492,492
BEGIN DESCRIPTION:
Mapping XS b8d7b58e
END DESCRIPTION:
XS GIS Cut Line= 4
      2779864.81      7035891.76      2780071.01      7035748.50
      2780173.00      7035670.38      2780261.96      7035229.92
#Sta/Elev= 30
  4672.0  473.43  4718.4  470.25  4896.3  461.26  4942.0  460.24  4950.3  459.18
  4958.8  456.43  4971.1  455.75  4978.5  454.16  4985.6  450.52  4991.9  451.66
  4997.1  446.88  4997.6  446.08  5003.1  446.88  5006.4  447.50  5014.6  454.23
  5020.9  456.24  5033.7  456.43  5041.7  460.55  5084.7  461.00  5118.3  460.96
  5133.8  457.11  5140.6  456.45  5148.9  460.30  5159.1  460.70  5186.2  460.82
  5191.3  459.03  5199.9  458.43  5210.1  460.91  5485.5  464.93  5500.9  465.42
#Mann=7,-1,0
  4672.0    0.05       0  4718.4    0.16       0  4896.3    0.12       0
  4997.1    0.07       0  5003.1    0.12       0  5133.8    0.16       0
  5485.5    0.05       0
Bank Sta=4958.8,5033.7
Exp/Cntr=0.3,0.1

Type RM Length L Ch R = 1,5896,572,572,572
BEGIN DESCRIPTION:
Rice Branch 7.0
END DESCRIPTION:
XS GIS Cut Line= 3
      2779874.95      7035924.98      2780215.18      7036034.39
      2780871.16      7035932.06
#Sta/Elev= 30
  4658.2  473.22  4669.0  472.77  4706.4  469.95  4807.9  464.09  4847.3  458.60
  4857.8  458.36  4866.8  459.50  4872.1  461.00  4920.5  459.90  4962.9  459.56
  4973.6  458.85  4978.0  454.43  4983.9  448.47  4991.4  445.61  4991.9  444.81
  4996.9  444.81  4997.4  445.61  5000.4  447.70  5005.7  448.36  5012.9  451.12
  5054.5  454.43  5066.0  458.58  5086.2  459.30  5217.8  456.56  5338.3  457.97
  5460.7  460.74  5526.0  460.35  5560.0  460.64  5612.5  462.77  5679.5  464.32
#Mann=7,-1,0
  4658.2    0.05       0  4669.0    0.16       0  4920.5    0.12       0
  4991.4    0.07       0  4997.4    0.12       0  5338.3    0.05       0
  5526.0    0.16       0
Bank Sta=4978,5054.5
Exp/Cntr=0.3,0.1

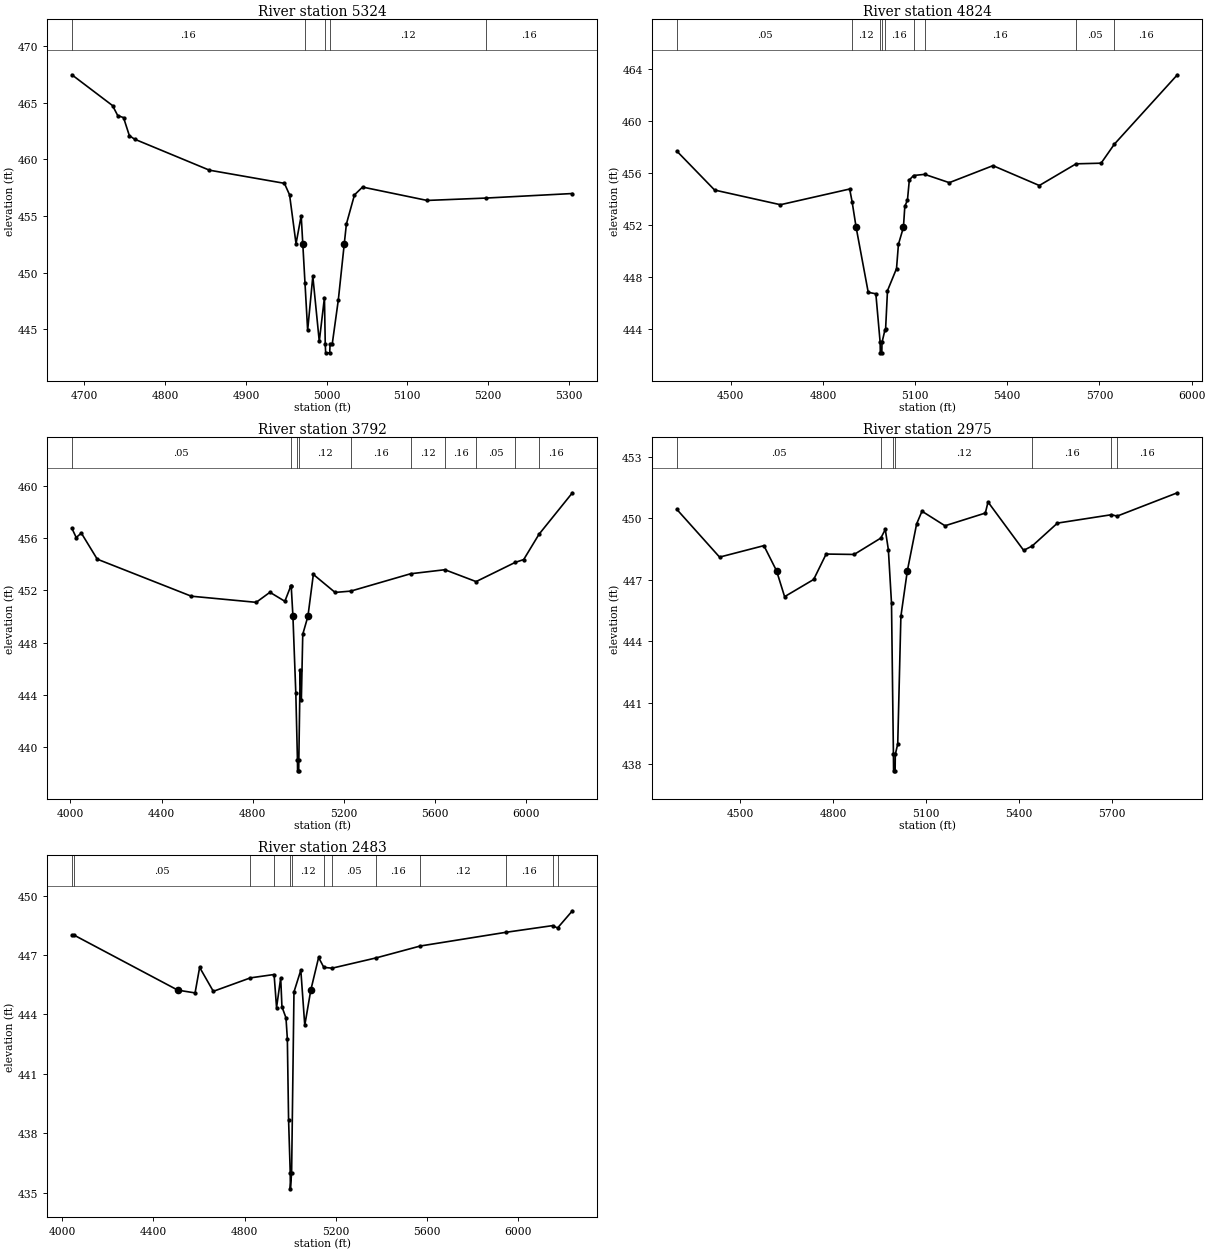
Type RM Length L Ch R = 1,5324,500,500,500
BEGIN DESCRIPTION:
Rice Branch 6.0
END DESCRIPTION:
XS GIS Cut Line= 3
      2779925.04      7036075.03      2780175.00      7036275.00
      2780474.99      7036275.00
#Sta/Elev= 30
  4684.4  467.45  4734.8  464.73  4741.2  463.85  4748.4  463.67  4755.6  462.08
  4762.0  461.77  4854.8  459.03  4947.7  457.87  4954.1  456.85  4962.1  452.54
  4968.5  455.02  4970.5  452.49  4973.2  449.07  4976.5  444.90  4982.9  449.67
  4990.9  443.92  4997.3  447.79  4998.3  443.71  4998.8  442.91  5003.8  442.91
  5004.3  443.71  5007.0  443.71  5014.5  447.58  5021.8  452.49  5024.5  454.28
  5034.5  456.85  5044.5  457.54  5124.5  456.36  5197.6  456.57  5304.5  456.97
#Mann=5,-1,0
  4684.4    0.16       0  4973.2    0.12       0  4998.3    0.07       0
  5004.3    0.12       0  5197.6    0.16       0
Bank Sta=4970.5,5021.8
Exp/Cntr=0.3,0.1

Type RM Length L Ch R = 1,4824,1032,1032,1032
BEGIN DESCRIPTION:
Rice Branch 5.0
END DESCRIPTION:
XS GIS Cut Line= 3
      2779564.47      7036701.10      2780199.34      7036572.21
      2780994.33      7035996.81
#Sta/Elev= 30
  4324.3  457.71  4447.3  454.71  4661.6  453.58  4886.9  454.79  4894.8  453.81
  4907.9  451.84  4947.3  446.83  4972.1  446.72  4986.1  442.97  4986.6  442.17
  4991.6  442.17  4992.1  442.97  5001.8  443.94  5003.8  443.98  5010.0  446.96
  5039.4  448.66  5045.6  450.53  5061.9  451.84  5066.4  453.45  5075.0  453.94
  5081.1  455.49  5094.8  455.83  5131.0  455.92  5211.1  455.28  5353.4  456.59
  5504.2  455.06  5623.8  456.73  5705.3  456.78  5748.3  458.24  5953.5  463.59
#Mann=9,-1,0
  4324.3    0.05       0  4894.8    0.12       0  4986.1    0.07       0
  4992.1    0.12       0  5001.8    0.16       0  5094.8    0.12       0
  5131.0    0.16       0  5623.8    0.05       0  5748.3    0.16       0
Bank Sta=4907.9,5061.9
Exp/Cntr=0.3,0.1

Type RM Length L Ch R = 1,3792,817,817,817
BEGIN DESCRIPTION:
Mapping XS ddfdea91
END DESCRIPTION:
XS GIS Cut Line= 4
      2779426.51      7036871.28      2780335.27      7037083.48
      2780559.22      7037041.82      2780998.38      7036101.41
#Sta/Elev= 30
  4006.2  456.77  4025.2  456.06  4047.7  456.40  4117.6  454.40  4530.9  451.56
  4815.9  451.09  4876.3  451.86  4941.8  451.17  4967.7  452.33  4969.7  452.36
  4977.3  450.02  4990.0  444.11  4997.2  438.97  4997.7  438.17  5002.7  438.17
  5003.2  438.97  5009.2  445.90  5014.3  443.58  5020.5  448.64  5043.2  450.02
  5067.0  453.23  5162.5  451.85  5231.3  451.95  5493.9  453.28  5644.8  453.59
  5782.0  452.68  5953.5  454.15  5991.1  454.37  6058.4  456.31  6205.1  459.49
#Mann=10,-1,0
  4006.2    0.05       0  4967.7    0.12       0  4997.2    0.07       0
  5003.2    0.12       0  5231.3    0.16       0  5493.9    0.12       0
  5644.8    0.16       0  5782.0    0.05       0  5953.5    0.12       0
  6058.4    0.16       0
Bank Sta=4977.3,5043.2
Exp/Cntr=0.3,0.1

Type RM Length L Ch R = 1,2975,492,492,492
BEGIN DESCRIPTION:
Mapping XS 8e0abc83
END DESCRIPTION:
XS GIS Cut Line= 4
      2779835.23      7037583.49      2780538.39      7037515.78
      2780736.31      7037479.32      2781117.73      7036882.67
#Sta/Elev= 30
  4294.8  450.43  4432.8  448.10  4575.9  448.66  4616.8  447.43  4642.7  446.17
  4736.6  447.01  4776.8  448.25  4867.2  448.23  4953.4  449.03  4967.7  449.45
  4977.7  448.46  4987.8  445.86  4994.0  438.47  4994.5  437.67  4999.5  437.67
  5000.0  438.47  5007.9  438.98  5018.1  445.21  5038.9  447.43  5068.9  449.72
  5086.2  450.34  5160.5  449.63  5290.7  450.25  5299.4  450.79  5414.4  448.43
  5441.7  448.64  5523.5  449.76  5698.0  450.17  5716.0  450.10  5910.6  451.24
#Mann=7,-1,0
  4294.8    0.05       0  4953.4    0.12       0  4994.0    0.07       0
  5000.0    0.12       0  5441.7    0.16       0  5698.0    0.12       0
  5716.0    0.16       0
Bank Sta=4616.8,5038.9
Exp/Cntr=0.3,0.1

Type RM Length L Ch R = 1,2483,0,0,0
BEGIN DESCRIPTION:
Rice Branch 3.0
END DESCRIPTION:
XS GIS Cut Line= 4
      2779805.20      7037944.50      2780637.97      7037913.78
      2780843.40      7037826.54      2781449.32      7036862.94
#Sta/Elev= 30
  4042.8  448.02  4050.7  448.02  4507.1  445.23  4583.0  445.09  4603.0  446.38
  4663.0  445.17  4825.6  445.85  4929.5  446.02  4940.3  444.35  4958.5  445.85
  4963.9  444.39  4981.6  443.83  4987.6  442.78  4993.0  438.69  5000.3  435.99
  5000.8  435.19  5006.3  435.99  5016.7  445.14  5046.7  446.24  5064.0  443.45
  5090.4  445.23  5124.7  446.88  5147.6  446.38  5183.9  446.34  5377.2  446.86
  5570.6  447.46  5944.7  448.15  6150.6  448.49  6172.5  448.37  6237.6  449.24
#Mann=13,-1,0
  4042.8    0.08       0  4050.7    0.05       0  4825.6    0.16       0
  4929.5    0.12       0  5000.3    0.07       0  5006.3    0.12       0
  5147.6    0.07       0  5183.9    0.05       0  5377.2    0.16       0
  5570.6    0.12       0  5944.7    0.16       0  6150.6    0.05       0
  6172.5    0.16       0
Bank Sta=4507.1,5090.4
Exp/Cntr=0.3,0.1

Chan Stop Cuts=-1