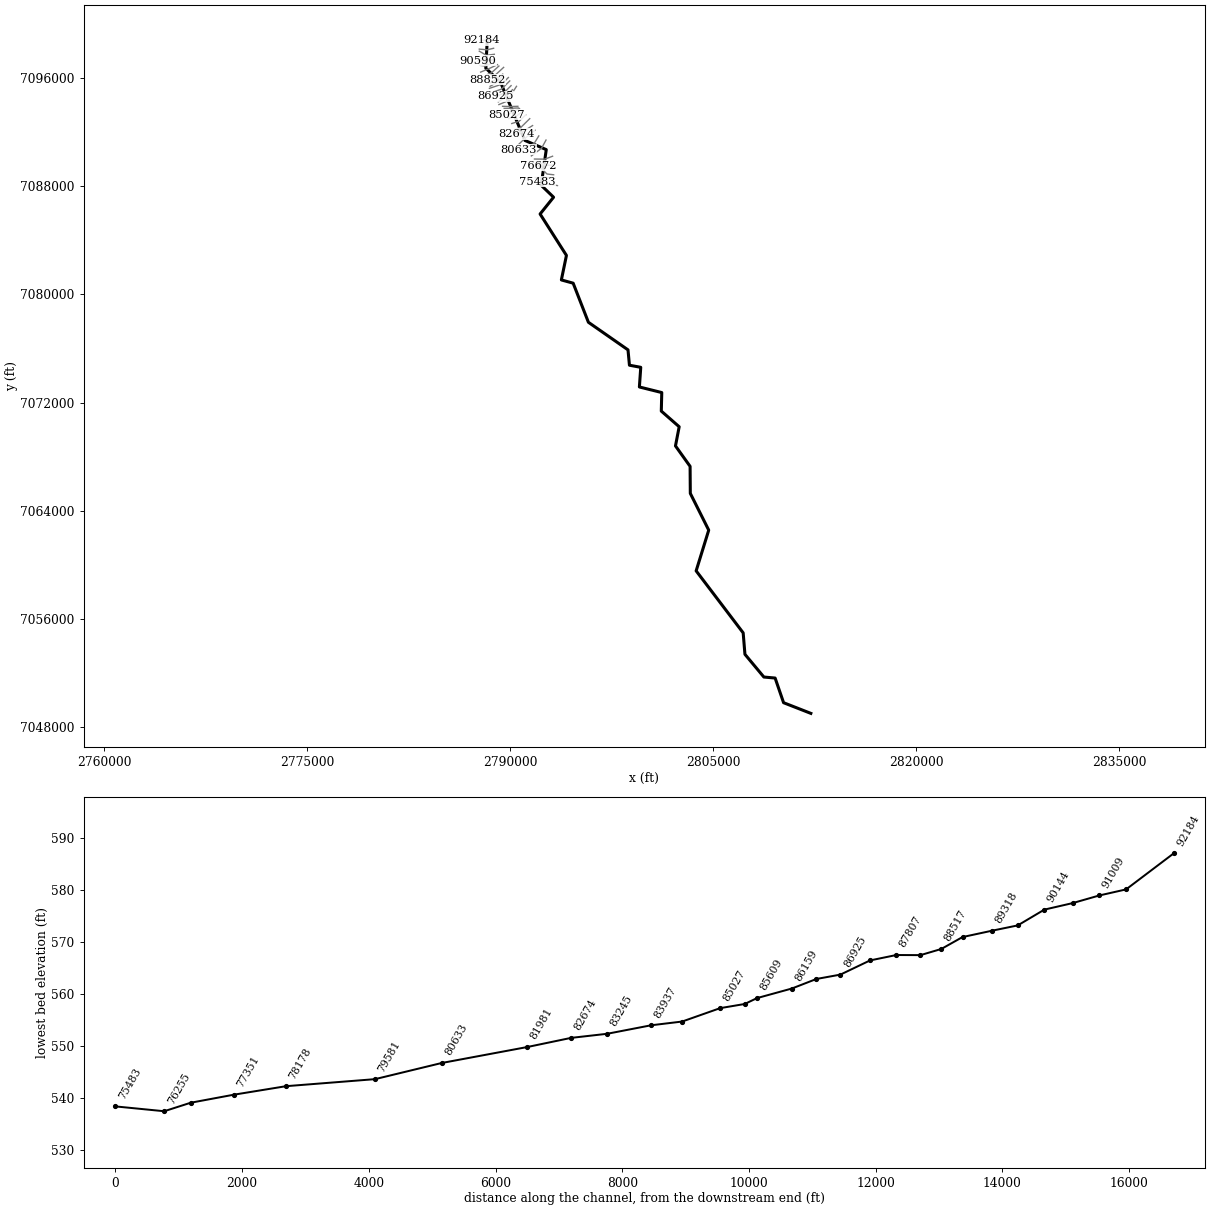
--- SCHOOLEY CREEK.prj (project) ---

Proj Title=SCHOOLEY CREEK Base Level Engineering
Current Plan=p01
Default Exp/Contr=0.3,0.1
English Units
Geom File=g01
Flow File=f01
Plan File=p01
Y Axis Title=Elevation
X Axis Title(PF)=Main Channel Distance
X Axis Title(XS)=Station
BEGIN DESCRIPTION:
SCHOOLEY CREEK
END DESCRIPTION:
DSS Export Rating Curves= 0
DSS Export Rating Curve Sorted= 0
DSS Export Volume Flow Curves= 0
DXF OffsetX= 0
DXF OffsetY= 0
DXF ScaleX= 1
DXF ScaleY= 10

--- SCHOOLEY CREEK.p01 (plan) ---

Plan Title=Multiple Run
Short Identifier=Multiple
Geom File=g01
Flow File=f01
Subcritical Flow
K Sum by GR= 0
Std Step Tol= 0.01
Critical Tol= 0.01
Num of Std Step Trials= 20
Max Error Tol= 0.3
Flow Tol Ratio= 0.001
Split Flow NTrial= 30
Split Flow Tol= 0.02
Split Flow Ratio= 0.02
Log Output Level= 0
Friction Slope Method= 1
Unsteady Friction Slope Method= 2
Unsteady Bridges Friction Slope Method= 1
Parabolic Critical Depth
Global Vel Dist=  1 , 1 , 1
Global Log Level= 0
CheckData=True
Encroach Param= -1, 0, 0, 0
BEGIN DESCRIPTION:
Multiple Run
END DESCRIPTION:

--- SCHOOLEY CREEK.f01 (steady flow) ---

Flow Title=Multiple
Program Version=5.07
Number of Profiles= 7
Profile Names=10-year,25-year,50-year,1pct_min,100-year,1pct_plu,500-year
River Rch & RM=SCHOOLEY CREEK,Reach-1         ,92184
     674     891    1065     630    1258    2509    1750
River Rch & RM=SCHOOLEY CREEK,Reach-1         ,83245
     823    1099    1320     785    1567    3126    2203
River Rch & RM=SCHOOLEY CREEK,Reach-1         ,75483
    1111    1509    1833    1102    2198    4385    3155
River Rch & RM=SCHOOLEY CREEK,Reach-1         ,70961
    1411    1935    2366    1429    2852    5691    4140
River Rch & RM=SCHOOLEY CREEK,Reach-1         ,60475
    1686    2327    2858    1733    3458    6900    5057
River Rch & RM=SCHOOLEY CREEK,Reach-1         ,53359
    1991    2771    3421    2085    4160    8300    6144
River Rch & RM=SCHOOLEY CREEK,Reach-1         ,45926
    2072    2882    3558    2167    4324    8627    6380
River Rch & RM=SCHOOLEY CREEK,Reach-1         ,40067
    2347    3285    4072    2490    4967    9911    7386
River Rch & RM=SCHOOLEY CREEK,Reach-1         ,33173
    2504    3507    4350    2660    5308   10591    7896
River Rch & RM=SCHOOLEY CREEK,Reach-1         ,24026
    2891    4070    5066    3108    6201   12372    9282
River Rch & RM=SCHOOLEY CREEK,Reach-1         ,13882
    3551    5038    6303    3886    7753   15470   11725
Boundary for River Rch & Prof#=SCHOOLEY CREEK,Reach-1         , 1
Up Type= 0
Dn Type= 3
Dn Slope=0.00094
Boundary for River Rch & Prof#=SCHOOLEY CREEK,Reach-1         , 2
Up Type= 0
Dn Type= 3
Dn Slope=0.00094
Boundary for River Rch & Prof#=SCHOOLEY CREEK,Reach-1         , 3
Up Type= 0
Dn Type= 3
Dn Slope=0.00094
Boundary for River Rch & Prof#=SCHOOLEY CREEK,Reach-1         , 4
Up Type= 0
Dn Type= 3
Dn Slope=0.00094
Boundary for River Rch & Prof#=SCHOOLEY CREEK,Reach-1         , 5
Up Type= 0
Dn Type= 3
Dn Slope=0.00094
Boundary for River Rch & Prof#=SCHOOLEY CREEK,Reach-1         , 6
Up Type= 0
Dn Type= 3
Dn Slope=0.00094
Boundary for River Rch & Prof#=SCHOOLEY CREEK,Reach-1         , 7
Up Type= 0
Dn Type= 3
Dn Slope=0.00094
DSS Import GetInterval= 0
DSS Import GetPeak= 0
DSS Import FillOption= 0

--- SCHOOLEY CREEK.g01 (geometry) ---

Geom Title=Existing Conditions

River Reach=SCHOOLEY CREEK,Reach-1
Reach XY= 30
      2788318.63      7098921.97      2788207.04      7096715.90
      2789300.24      7095663.14      2791090.18      7091377.57
      2792673.41      7090695.03      2792295.90      7088061.52
      2793213.33      7087176.41      2792217.56      7085935.80
      2794163.97      7082874.90      2793788.92      7081061.91
      2794660.26      7080822.81      2795787.04      7077931.68
      2798711.33      7075893.18      2798818.46      7074758.06
      2799653.89      7074603.11      2799553.04      7073150.07
      2801206.75      7072736.95      2801170.87      7071367.97
      2802492.31      7070209.59      2802218.84      7068792.27
      2803298.90      7067282.18      2803314.70      7065284.48
      2804675.30      7062567.13      2803745.53      7059556.17
      2807220.18      7054973.57      2807350.43      7053387.85
      2808749.15      7051708.03      2809580.01      7051633.30
      2810205.59      7049810.71      2812220.03      7049021.60

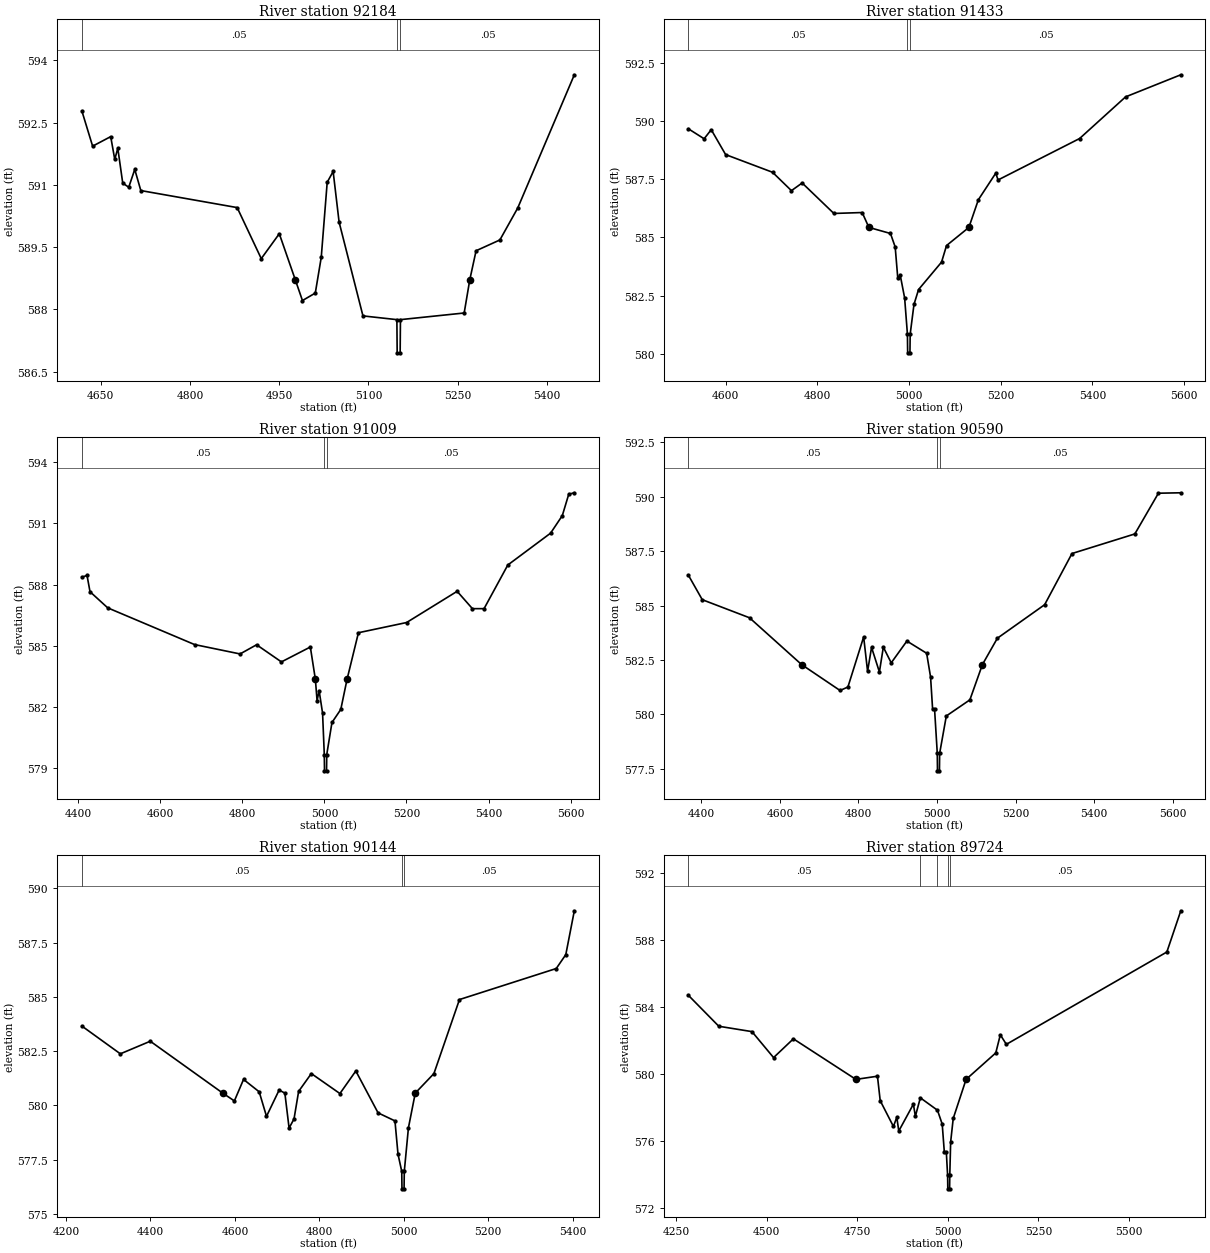
Type RM Length L Ch R = 1,92184,751,751,751
BEGIN DESCRIPTION:
SCHOOLEY CREEK 99.0
END DESCRIPTION:
XS GIS Cut Line= 3
      2788702.90      7098828.75      2788333.11      7098771.46
      2787879.98      7098787.09
#Sta/Elev= 30
  4618.3  592.78  4636.4  591.93  4666.8  592.16  4673.6  591.61  4678.7  591.88
  4687.0  591.04  4697.1  590.94  4707.2  591.37  4717.4  590.86  4879.3  590.45
  4919.8  589.22  4950.1  589.82  4977.0  588.71  4989.0  588.21  5010.6  588.39
  5020.6  589.25  5030.6  591.06  5040.6  591.32  5050.6  590.10  5090.7  587.84
  5147.7  587.75  5148.2  586.95  5153.2  586.95  5153.7  587.75  5260.8  587.91
  5270.2  588.71  5280.8  589.41  5320.8  589.67  5350.8  590.44  5445.9  593.65
#Mann=3,-1,0
  4618.3    0.05       0  5147.7    0.03       0  5153.7    0.05       0
Bank Sta=4977,5270.2
Exp/Cntr=0.3,0.1

Type RM Length L Ch R = 1,91433,424,424,424
BEGIN DESCRIPTION:
SCHOOLEY CREEK 98.0
END DESCRIPTION:
XS GIS Cut Line= 3
      2788783.62      7098188.12      2788312.28      7098073.54
      2787725.00      7098125.00
#Sta/Elev= 30
  4518.2  589.67  4552.7  589.24  4568.2  589.63  4599.6  588.56  4702.0  587.80
  4743.2  587.01  4766.6  587.34  4835.8  586.03  4897.6  586.07  4912.2  585.43
  4959.3  585.17  4969.6  584.59  4975.3  583.24  4980.5  583.39  4990.2  582.40
  4996.3  580.84  4996.8  580.04  5001.8  580.04  5002.3  580.84  5010.6  582.12
  5020.6  582.76  5070.8  583.94  5081.6  584.65  5130.4  585.43  5151.1  586.62
  5189.0  587.76  5194.1  587.47  5372.0  589.25  5472.3  591.04  5592.8  591.99
#Mann=3,-1,0
  4518.2    0.05       0  4996.3    0.03       0  5002.3    0.05       0
Bank Sta=4912.2,5130.4
Exp/Cntr=0.3,0.1

Type RM Length L Ch R = 1,91009,419,419,419
BEGIN DESCRIPTION:
SCHOOLEY CREEK 97.0
END DESCRIPTION:
XS GIS Cut Line= 3
      2788837.46      7097742.81      2788251.02      7097667.88
      2787725.01      7097974.99
#Sta/Elev= 30
  4408.8  588.36  4421.4  588.45  4428.7  587.65  4471.8  586.86  4683.5  585.06
  4794.4  584.60  4834.7  585.05  4895.2  584.21  4965.7  584.94  4978.0  583.35
  4982.1  582.31  4987.1  582.80  4995.5  581.70  4999.7  579.67  5000.2  578.87
  5005.2  578.87  5005.7  579.67  5018.4  581.24  5039.9  581.88  5055.1  583.35
  5082.9  585.64  5200.3  586.14  5323.5  587.67  5360.7  586.82  5389.1  586.82
  5447.0  588.96  5551.2  590.52  5579.8  591.38  5595.5  592.43  5609.1  592.50
#Mann=3,-1,0
  4408.8    0.05       0  4999.7    0.03       0  5005.7    0.05       0
Bank Sta=4978,5055.1
Exp/Cntr=0.3,0.1

Type RM Length L Ch R = 1,90590,446,446,446
BEGIN DESCRIPTION:
SCHOOLEY CREEK 96.0
END DESCRIPTION:
XS GIS Cut Line= 3
      2788890.44      7097339.17      2788269.74      7097295.77
      2787637.99      7097282.78
#Sta/Elev= 30
  4366.8  586.40  4402.3  585.27  4522.6  584.44  4655.3  582.29  4753.2  581.10
  4773.2  581.26  4813.3  583.56  4823.3  581.98  4833.4  583.08  4853.4  581.95
  4863.4  583.09  4883.5  582.37  4923.4  583.37  4973.7  582.81  4983.7  581.72
  4988.9  580.24  4993.9  580.24  5000.8  578.21  5001.3  577.41  5006.3  577.41
  5006.8  578.21  5023.8  579.93  5083.8  580.67  5115.7  582.29  5153.8  583.50
  5274.2  585.04  5343.8  587.39  5503.9  588.29  5563.9  590.16  5620.9  590.18
#Mann=3,-1,0
  4366.8    0.05       0  5000.8    0.03       0  5006.8    0.05       0
Bank Sta=4655.3,5115.7
Exp/Cntr=0.3,0.1

Type RM Length L Ch R = 1,90144,420,420,420
BEGIN DESCRIPTION:
SCHOOLEY CREEK 95.0
END DESCRIPTION:
XS GIS Cut Line= 3
      2788877.39      7097174.24      2788175.00      7096875.00
      2787774.99      7096925.00
#Sta/Elev= 30
  4237.5  583.66  4328.7  582.38  4399.6  582.96  4571.3  580.57  4598.8  580.21
  4620.5  581.20  4657.6  580.63  4674.9  579.50  4704.8  580.71  4718.4  580.57
  4728.4  578.96  4740.1  579.38  4751.0  580.65  4781.1  581.47  4848.8  580.55
  4886.5  581.59  4939.2  579.66  4979.2  579.29  4986.4  577.76  4995.3  576.96
  4995.8  576.16  5000.8  576.16  5001.3  576.96  5011.1  578.97  5027.3  580.57
  5071.5  581.47  5132.0  584.88  5361.3  586.31  5383.9  586.95  5404.1  588.97
#Mann=3,-1,0
  4237.5    0.05       0  4995.3    0.03       0  5001.3    0.05       0
Bank Sta=4571.3,5027.3
Exp/Cntr=0.3,0.1

Type RM Length L Ch R = 1,89724,406,406,406
BEGIN DESCRIPTION:
SCHOOLEY CREEK 94.0
END DESCRIPTION:
XS GIS Cut Line= 3
      2789068.36      7096974.59      2788425.00      7096675.00
      2787824.99      7096425.00
#Sta/Elev= 30
  4283.5  584.68  4367.7  582.83  4459.2  582.51  4518.9  580.96  4573.6  582.08
  4746.2  579.66  4805.7  579.85  4813.3  578.39  4849.8  576.85  4859.1  577.40
  4864.6  576.58  4904.9  578.18  4910.4  577.46  4924.1  578.56  4971.4  577.82
  4984.5  576.99  4990.4  575.30  4995.9  575.30  4999.4  573.93  4999.9  573.13
  5004.9  573.13  5005.4  573.93  5007.8  575.93  5014.9  577.33  5050.4  579.66
  5132.4  581.24  5144.9  582.32  5161.6  581.75  5604.7  587.26  5643.2  589.72
#Mann=5,-1,0
  4283.5    0.05       0  4924.1    0.16       0  4971.4    0.05       0
  4999.4    0.03       0  5005.4    0.05       0
Bank Sta=4746.2,5050.4
Exp/Cntr=0.3,0.1

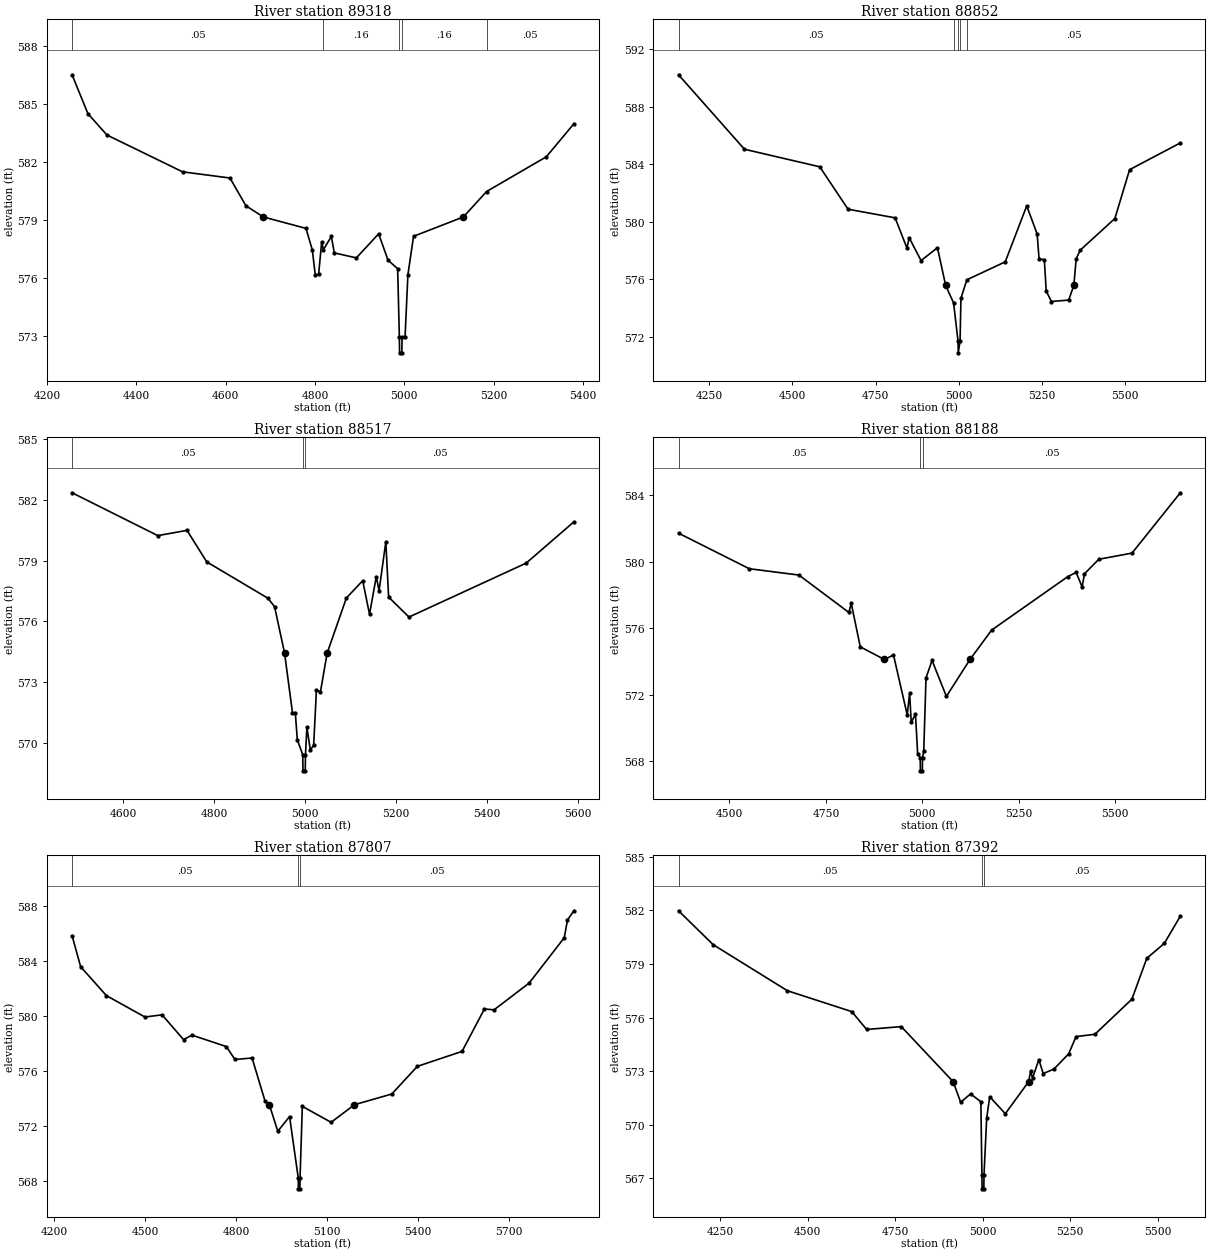
Type RM Length L Ch R = 1,89318,466,466,466
BEGIN DESCRIPTION:
SCHOOLEY CREEK 93.0
END DESCRIPTION:
XS GIS Cut Line= 3
      2789174.98      7096874.98      2788625.00      7096375.00
      2788274.96      7096224.98
#Sta/Elev= 30
  4255.7  586.52  4291.1  584.51  4333.7  583.40  4503.3  581.49  4609.4  581.17
  4645.2  579.73  4684.4  579.15  4779.7  578.56  4793.9  577.44  4800.6  576.13
  4808.1  576.19  4814.8  577.84  4818.8  577.46  4836.5  578.14  4843.2  577.29
  4892.5  577.03  4942.5  578.28  4963.5  576.91  4985.1  576.47  4988.9  572.91
  4989.4  572.11  4994.4  572.11  4994.9  572.91  5001.7  572.94  5008.0  576.15
  5020.7  578.15  5132.2  579.15  5184.3  580.47  5318.1  582.27  5379.8  583.98
#Mann=5,-1,0
  4255.7    0.05       0  4818.8    0.16       0  4988.9    0.07       0
  4994.9    0.16       0  5184.3    0.05       0
Bank Sta=4684.4,5132.2
Exp/Cntr=0.3,0.1

Type RM Length L Ch R = 1,88852,335,335,335
BEGIN DESCRIPTION:
SCHOOLEY CREEK 92.0
END DESCRIPTION:
XS GIS Cut Line= 3
      2789524.97      7096774.97      2788925.00      7096225.00
      2788325.02      7095875.01
#Sta/Elev= 30
  4157.7  590.23  4355.9  585.05  4582.2  583.83  4667.3  580.88  4808.8  580.28
  4844.3  578.18  4851.1  578.89  4886.8  577.31  4936.1  578.20  4960.7  575.58
  4984.6  574.36  4998.0  571.69  4998.5  570.89  5004.0  571.69  5006.7  574.69
  5024.5  575.97  5139.9  577.22  5204.4  581.11  5235.8  579.16  5241.6  577.41
  5257.3  577.37  5263.1  575.18  5278.8  574.46  5330.5  574.56  5346.1  575.58
  5353.2  577.44  5365.2  578.03  5469.4  580.23  5513.7  583.63  5666.2  585.49
#Mann=5,-1,0
  4157.7    0.05       0  4984.6    0.16       0  4998.0    0.07       0
  5004.0    0.16       0  5024.5    0.05       0
Bank Sta=4960.7,5346.1
Exp/Cntr=0.3,0.1

Type RM Length L Ch R = 1,88517,329,329,329
BEGIN DESCRIPTION:
SCHOOLEY CREEK 91.0
END DESCRIPTION:
XS GIS Cut Line= 3
      2789459.00      7096275.82      2789075.00      7095975.00
      2788565.57      7095629.57
#Sta/Elev= 30
  4487.3  582.36  4675.8  580.24  4740.0  580.50  4783.4  578.94  4918.1  577.14
  4932.6  576.72  4954.5  574.43  4971.9  571.48  4978.1  571.48  4982.6  570.13
  4994.5  569.40  4995.0  568.60  5000.0  568.60  5000.5  569.40  5003.6  570.75
  5011.3  569.62  5018.5  569.88  5024.6  572.59  5033.5  572.52  5048.2  574.43
  5090.4  577.15  5126.3  578.01  5141.3  576.35  5156.2  578.21  5162.3  577.51
  5177.2  579.94  5183.3  577.20  5228.1  576.21  5485.8  578.88  5590.6  580.92
#Mann=3,-1,0
  4487.3    0.05       0  4994.5    0.03       0  5000.5    0.05       0
Bank Sta=4954.5,5048.2
Exp/Cntr=0.3,0.1

Type RM Length L Ch R = 1,88188,381,381,381
BEGIN DESCRIPTION:
SCHOOLEY CREEK 90.0
END DESCRIPTION:
XS GIS Cut Line= 3
      2789476.36      7096219.41      2789125.00      7095725.00
      2788524.97      7095374.98
#Sta/Elev= 30
  4367.9  581.72  4551.4  579.58  4680.0  579.20  4809.6  576.95  4815.8  577.49
  4839.2  574.88  4901.8  574.12  4925.3  574.39  4960.9  570.79  4967.1  572.09
  4971.4  570.33  4982.3  570.84  4988.1  568.41  4994.6  568.22  4995.1  567.42
  5000.1  567.42  5000.6  568.22  5003.8  568.64  5009.6  573.01  5025.3  574.06
  5062.5  571.90  5123.7  574.12  5179.9  575.89  5377.6  579.11  5399.1  579.36
  5414.4  578.48  5420.6  579.28  5457.8  580.15  5543.8  580.52  5669.1  584.15
#Mann=3,-1,0
  4367.9    0.05       0  4994.6    0.03       0  5000.6    0.05       0
Bank Sta=4901.8,5123.7
Exp/Cntr=0.3,0.1

Type RM Length L Ch R = 1,87807,415,415,415
BEGIN DESCRIPTION:
SCHOOLEY CREEK 89.0
END DESCRIPTION:
XS GIS Cut Line= 3
      2789875.01      7096025.01      2789375.00      7095525.00
      2788475.00      7095225.00
#Sta/Elev= 30
  4258.2  585.86  4286.5  583.60  4371.4  581.50  4498.6  579.94  4555.2  580.10
  4625.9  578.30  4654.2  578.62  4767.3  577.79  4795.6  576.85  4852.2  576.96
  4894.6  573.85  4909.2  573.56  4937.0  571.63  4975.9  572.70  5004.5  568.24
  5005.0  567.44  5010.0  567.44  5010.5  568.24  5018.0  573.44  5112.9  572.28
  5190.0  573.56  5313.2  574.34  5397.5  576.35  5545.1  577.44  5618.9  580.53
  5650.5  580.46  5766.4  582.41  5882.4  585.71  5892.9  587.00  5914.0  587.67
#Mann=3,-1,0
  4258.2    0.05       0  5004.5    0.03       0  5010.5    0.05       0
Bank Sta=4909.2,5190
Exp/Cntr=0.3,0.1

Type RM Length L Ch R = 1,87392,467,467,467
BEGIN DESCRIPTION:
SCHOOLEY CREEK 88.0
END DESCRIPTION:
XS GIS Cut Line= 3
      2789974.98      7095774.98      2789375.00      7095175.00
      2788825.04      7094975.01
#Sta/Elev= 30
  4130.9  581.98  4229.9  580.08  4442.0  577.50  4625.9  576.33  4668.3  575.33
  4767.3  575.49  4915.7  572.40  4937.0  571.25  4965.3  571.72  4994.7  571.28
  4997.7  567.20  4998.2  566.40  5003.2  566.40  5003.7  567.20  5011.3  570.35
  5020.0  571.56  5064.5  570.61  5131.1  572.40  5137.0  573.00  5142.3  572.60
  5160.3  573.64  5172.9  572.86  5203.5  573.11  5245.4  573.96  5266.7  574.93
  5320.6  575.06  5426.3  577.03  5468.9  579.32  5518.8  580.15  5564.6  581.68
#Mann=3,-1,0
  4130.9    0.05       0  4997.7    0.03       0  5003.7    0.05       0
Bank Sta=4915.7,5131.1
Exp/Cntr=0.3,0.1

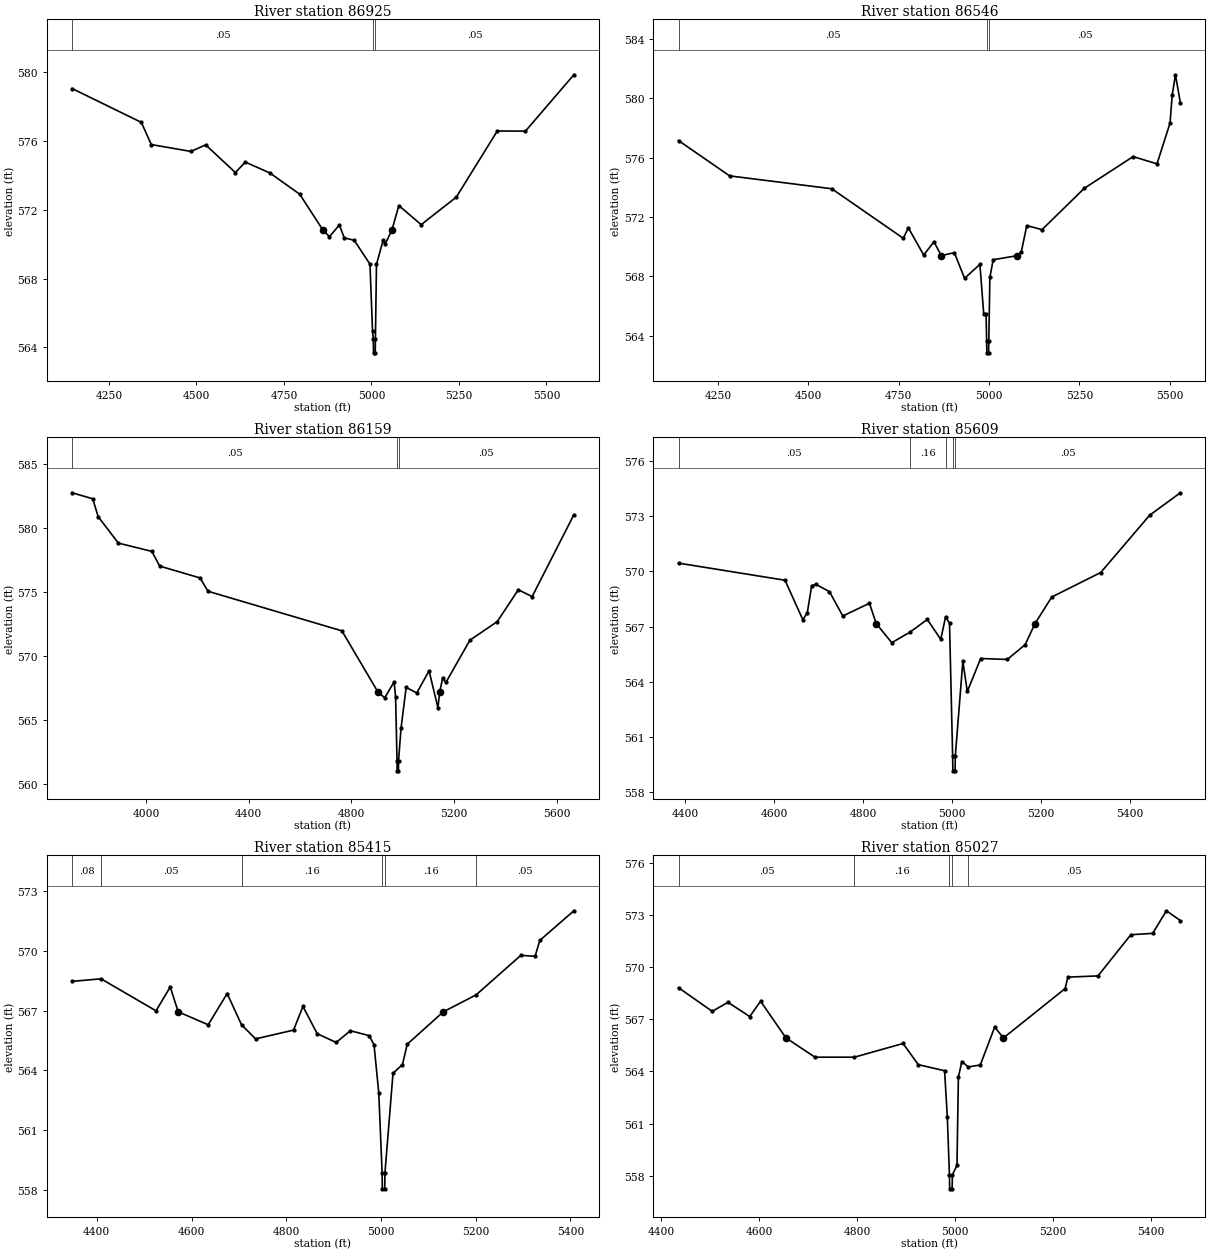
Type RM Length L Ch R = 1,86925,379,379,379
BEGIN DESCRIPTION:
SCHOOLEY CREEK 87.0
END DESCRIPTION:
XS GIS Cut Line= 3
      2790075.00      7095425.00      2789475.00      7094825.00
      2788924.97      7094624.99
#Sta/Elev= 30
  4144.6  579.06  4342.6  577.09  4370.9  575.80  4484.0  575.40  4526.4  575.78
  4611.3  574.17  4639.6  574.78  4710.3  574.14  4795.1  572.91  4861.2  570.83
  4880.0  570.44  4908.3  571.12  4922.4  570.37  4950.7  570.23  4995.8  568.84
  5003.1  564.97  5005.4  564.48  5005.9  563.68  5010.9  563.68  5011.4  564.48
  5014.4  568.83  5033.7  570.25  5039.0  570.00  5058.6  570.83  5078.3  572.25
  5142.1  571.14  5242.5  572.74  5359.6  576.59  5440.0  576.58  5578.4  579.86
#Mann=3,-1,0
  4144.6    0.05       0  5005.4    0.03       0  5011.4    0.05       0
Bank Sta=4861.2,5058.6
Exp/Cntr=0.3,0.1

Type RM Length L Ch R = 1,86546,387,387,387
BEGIN DESCRIPTION:
SCHOOLEY CREEK 86.0
END DESCRIPTION:
XS GIS Cut Line= 3
      2790174.99      7095124.99      2789575.00      7094525.00
      2789125.04      7094225.03
#Sta/Elev= 30
  4140.3  577.16  4281.7  574.78  4564.6  573.91  4762.5  570.57  4776.7  571.27
  4819.1  569.44  4847.4  570.33  4867.9  569.40  4904.0  569.60  4932.2  567.87
  4974.7  568.81  4985.3  565.46  4991.8  565.46  4993.3  563.64  4993.8  562.84
  4998.8  562.84  4999.3  563.64  5002.3  567.93  5011.4  569.12  5078.7  569.40
  5089.5  569.67  5104.5  571.43  5146.6  571.15  5263.7  573.94  5398.9  576.08
  5465.0  575.59  5501.1  578.34  5507.1  580.23  5516.1  581.60  5529.6  579.72
#Mann=3,-1,0
  4140.3    0.05       0  4993.3    0.03       0  4999.3    0.05       0
Bank Sta=4867.9,5078.7
Exp/Cntr=0.3,0.1

Type RM Length L Ch R = 1,86159,550,550,550
BEGIN DESCRIPTION:
SCHOOLEY CREEK 85.0
END DESCRIPTION:
XS GIS Cut Line= 3
      2790475.01      7095375.02      2789775.00      7094275.00
      2789174.96      7094024.98
#Sta/Elev= 30
  3712.4  582.78  3792.9  582.31  3814.0  580.91  3892.8  578.84  4023.1  578.19
  4053.6  577.04  4211.1  576.11  4241.6  575.07  4763.1  571.97  4904.3  567.15
  4929.9  566.73  4966.3  567.97  4972.2  566.78  4977.7  561.81  4978.2  561.01
  4983.2  561.01  4983.7  561.81  4993.4  564.36  5013.3  567.54  5054.7  567.11
  5102.4  568.84  5137.1  565.95  5143.5  567.15  5155.5  568.27  5167.9  567.93
  5261.6  571.24  5367.8  572.69  5450.1  575.19  5503.8  574.65  5666.3  581.06
#Mann=3,-1,0
  3712.4    0.05       0  4977.7    0.03       0  4983.7    0.05       0
Bank Sta=4904.3,5143.5
Exp/Cntr=0.3,0.1

Type RM Length L Ch R = 1,85609,194,194,194
BEGIN DESCRIPTION:
Mapping XS ce8bb70a
END DESCRIPTION:
XS GIS Cut Line= 3
      2790574.46      7093897.33      2789984.15      7093879.97
      2789445.99      7093897.33
#Sta/Elev= 30
  4384.9  570.45  4624.5  569.52  4664.5  567.38  4674.5  567.74  4684.5  569.23
  4694.5  569.29  4724.5  568.90  4754.5  567.58  4814.5  568.27  4829.6  567.17
  4864.6  566.13  4905.0  566.69  4944.6  567.39  4974.9  566.31  4985.8  567.54
  4994.6  567.18  5001.6  559.97  5002.1  559.17  5007.1  559.17  5007.6  559.97
  5024.6  565.12  5034.6  563.48  5064.7  565.27  5124.7  565.22  5164.7  566.02
  5187.0  567.17  5224.7  568.61  5334.8  569.94  5444.9  573.05  5513.9  574.27
#Mann=5,-1,0
  4384.9    0.05       0  4905.0    0.16       0  4985.8    0.05       0
  5001.6    0.03       0  5007.6    0.05       0
Bank Sta=4829.6,5187
Exp/Cntr=0.3,0.1

Type RM Length L Ch R = 1,85415,388,388,388
BEGIN DESCRIPTION:
Mapping XS 44831bfe
END DESCRIPTION:
XS GIS Cut Line= 3
      2790622.16      7093775.80      2790014.53      7093749.76
      2789563.13      7093745.42
#Sta/Elev= 30
  4347.8  568.47  4408.9  568.60  4525.1  566.99  4555.1  568.19  4571.9  566.94
  4635.2  566.29  4675.3  567.86  4705.6  566.29  4735.3  565.58  4815.4  566.02
  4835.4  567.21  4865.4  565.84  4905.5  565.40  4935.5  565.99  4975.5  565.74
  4985.5  565.27  4995.5  562.84  5002.5  558.84  5003.0  558.04  5008.0  558.04
  5008.5  558.84  5025.5  563.85  5045.5  564.29  5055.5  565.31  5131.7  566.94
  5200.9  567.79  5295.5  569.78  5325.5  569.73  5335.5  570.53  5407.4  572.02
#Mann=6,-1,0
  4347.8    0.08       0  4408.9    0.05       0  4705.6    0.16       0
  5002.5    0.07       0  5008.5    0.16       0  5200.9    0.05       0
Bank Sta=4571.9,5131.7
Exp/Cntr=0.3,0.1

Type RM Length L Ch R = 1,85027,599,599,599
BEGIN DESCRIPTION:
Mapping XS 2b88dbf7
END DESCRIPTION:
XS GIS Cut Line= 3
      2790695.91      7093728.04      2790183.80      7093480.66
      2789775.79      7093276.65
#Sta/Elev= 30
  4435.6  568.82  4504.4  567.46  4536.6  567.98  4581.0  567.16  4603.2  568.04
  4655.0  565.93  4714.3  564.82  4794.8  564.82  4894.2  565.61  4925.3  564.39
  4979.0  564.04  4984.6  561.37  4988.9  558.04  4989.4  557.24  4994.4  557.24
  4994.9  558.04  5004.3  558.59  5007.2  563.67  5014.2  564.57  5027.4  564.26
  5051.9  564.37  5081.3  566.55  5099.3  565.93  5225.2  568.77  5230.8  569.43
  5292.3  569.50  5359.4  571.87  5404.1  571.95  5432.0  573.25  5460.5  572.69
#Mann=5,-1,0
  4435.6    0.05       0  4794.8    0.16       0  4988.9    0.07       0
  4994.9    0.16       0  5027.4    0.05       0
Bank Sta=4655,5099.3
Exp/Cntr=0.3,0.1

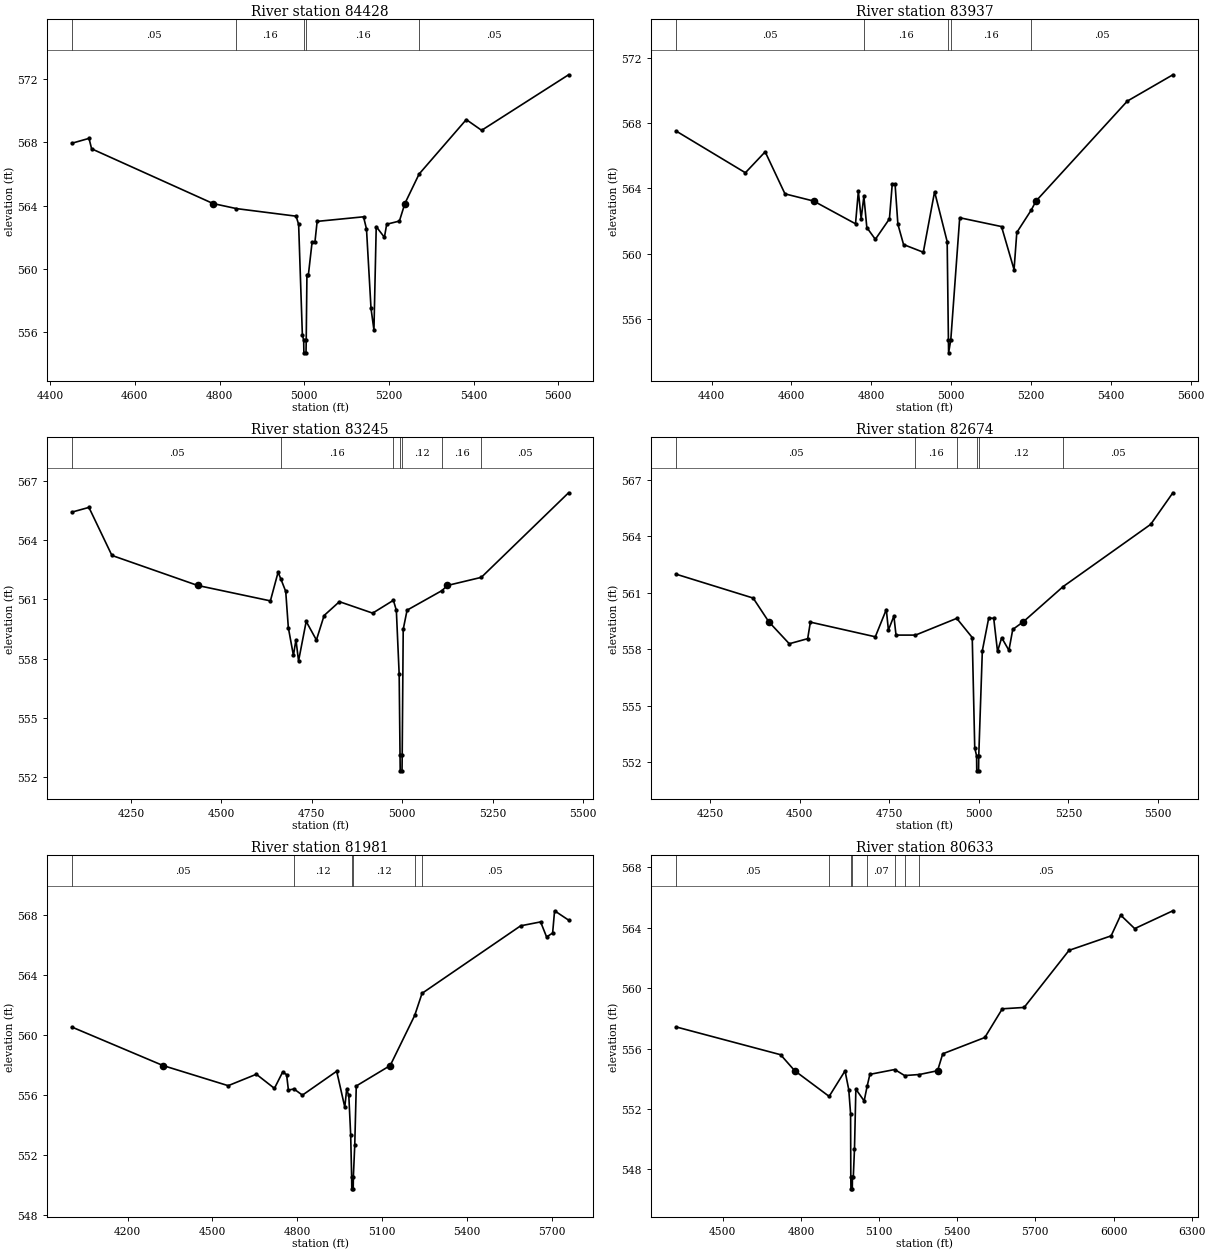
Type RM Length L Ch R = 1,84428,491,491,491
BEGIN DESCRIPTION:
SCHOOLEY CREEK 80.0
END DESCRIPTION:
XS GIS Cut Line= 3
      2790952.06      7093524.08      2790496.30      7093207.22
      2789919.53      7092986.05
#Sta/Elev= 30
  4451.3  567.95  4491.9  568.26  4498.0  567.60  4784.8  564.13  4840.0  563.81
  4980.8  563.33  4986.8  562.81  4995.6  555.81  4998.7  555.47  4999.2  554.67
  5004.2  554.67  5004.7  555.47  5006.4  559.61  5009.8  559.61  5018.5  561.67
  5025.2  561.67  5030.5  563.00  5140.0  563.29  5147.0  562.52  5157.7  557.48
  5164.6  556.12  5170.0  562.67  5189.3  561.99  5194.7  562.82  5224.7  563.02
  5237.6  564.13  5271.2  566.00  5382.6  569.45  5418.8  568.77  5624.1  572.29
#Mann=5,-1,0
  4451.3    0.05       0  4840.0    0.16       0  4998.7    0.07       0
  5004.7    0.16       0  5271.2    0.05       0
Bank Sta=4784.8,5237.6
Exp/Cntr=0.3,0.1

Type RM Length L Ch R = 1,83937,692,692,692
BEGIN DESCRIPTION:
SCHOOLEY CREEK 79.0
END DESCRIPTION:
XS GIS Cut Line= 3
      2791151.71      7093263.67      2790674.26      7092794.90
      2790125.04      7092625.01
#Sta/Elev= 30
  4311.1  567.51  4484.6  564.96  4534.1  566.24  4583.7  563.67  4655.5  563.23
  4760.4  561.84  4767.5  563.83  4774.5  562.15  4781.3  563.52  4788.7  561.61
  4810.0  560.89  4845.3  562.14  4852.4  564.28  4859.4  564.27  4866.5  561.81
  4880.7  560.57  4930.1  560.10  4958.4  563.80  4989.9  560.75  4993.0  554.75
  4993.5  553.95  4999.0  554.75  5021.3  562.21  5126.0  561.67  5157.4  559.04
  5164.3  561.31  5200.5  562.68  5212.3  563.23  5441.0  569.34  5555.1  570.95
#Mann=5,-1,0
  4311.1    0.05       0  4781.3    0.16       0  4993.0    0.07       0
  4999.0    0.16       0  5200.5    0.05       0
Bank Sta=4655.5,5212.3
Exp/Cntr=0.3,0.1

Type RM Length L Ch R = 1,83245,571,571,571
BEGIN DESCRIPTION:
SCHOOLEY CREEK 78.0
END DESCRIPTION:
XS GIS Cut Line= 3
      2791452.88      7092983.97      2790812.71      7092354.65
      2790368.90      7092181.46
#Sta/Elev= 30
  4086.0  565.41  4133.3  565.65  4196.9  563.22  4434.2  561.70  4635.3  560.92
  4656.6  562.37  4664.6  562.01  4677.7  561.40  4684.9  559.57  4699.0  558.16
  4706.0  558.95  4713.2  557.88  4734.3  559.88  4762.6  558.94  4783.9  560.18
  4826.2  560.88  4918.2  560.30  4975.6  560.95  4983.7  560.44  4991.5  557.21
  4993.9  553.12  4994.4  552.32  4999.4  552.32  4999.9  553.12  5002.7  559.48
  5013.4  560.45  5109.8  561.44  5124.9  561.70  5218.7  562.11  5460.1  566.39
#Mann=7,-1,0
  4086.0    0.05       0  4664.6    0.16       0  4975.6    0.12       0
  4993.9    0.07       0  4999.9    0.12       0  5109.8    0.16       0
  5218.7    0.05       0
Bank Sta=4434.2,5124.9
Exp/Cntr=0.3,0.1

Type RM Length L Ch R = 1,82674,693,693,693
BEGIN DESCRIPTION:
Mapping XS 33a87c5b
END DESCRIPTION:
XS GIS Cut Line= 3
      2791662.99      7092473.58      2790961.58      7092036.07
      2790433.78      7091848.56
#Sta/Elev= 30
  4154.8  561.99  4369.9  560.72  4413.5  559.46  4470.7  558.29  4522.1  558.56
  4529.6  559.44  4710.9  558.66  4741.6  560.11  4747.5  559.02  4762.8  559.76
  4768.7  558.75  4823.1  558.75  4938.2  559.64  4981.5  558.62  4988.5  552.75
  4993.6  552.33  4994.1  551.53  4999.2  551.53  4999.7  552.33  5009.7  557.92
  5027.5  559.66  5041.5  559.64  5052.1  557.88  5063.7  558.61  5083.9  557.94
  5094.6  559.05  5124.2  559.46  5235.2  561.33  5479.7  564.64  5541.6  566.32
#Mann=6,-1,0
  4154.8    0.05       0  4823.1    0.16       0  4938.2    0.12       0
  4993.6    0.07       0  4999.7    0.12       0  5235.2    0.05       0
Bank Sta=4413.5,5124.2
Exp/Cntr=0.3,0.1

Type RM Length L Ch R = 1,81981,1348,1348,1348
BEGIN DESCRIPTION:
SCHOOLEY CREEK 77.0
END DESCRIPTION:
XS GIS Cut Line= 3
      2791842.79      7092135.69      2791061.54      7091495.06
      2790525.03      7090975.03
#Sta/Elev= 30
  4002.6  560.53  4325.1  557.97  4555.8  556.63  4655.5  557.39  4719.4  556.45
  4748.1  557.52  4762.4  557.37  4768.9  556.34  4788.7  556.41  4818.4  556.00
  4939.7  557.59  4968.4  555.20  4974.9  556.38  4982.6  555.98  4989.2  553.36
  4992.6  550.57  4993.1  549.77  4998.2  549.77  4998.7  550.57  5003.6  552.67
  5009.0  556.61  5129.1  557.97  5215.7  561.30  5241.7  562.77  5590.5  567.26
  5661.2  567.52  5682.3  566.52  5703.7  566.78  5710.6  568.26  5760.1  567.64
#Mann=6,-1,0
  4002.6    0.05       0  4788.7    0.12       0  4992.6    0.07       0
  4998.7    0.12       0  5215.7    0.16       0  5241.7    0.05       0
Bank Sta=4325.1,5129.1
Exp/Cntr=0.3,0.1

Type RM Length L Ch R = 1,80633,1052,1052,1052
BEGIN DESCRIPTION:
SCHOOLEY CREEK 76.0
END DESCRIPTION:
XS GIS Cut Line= 3
      2792121.30      7091709.67      2791767.14      7091133.29
      2790625.05      7090675.02
#Sta/Elev= 30
  4320.8  557.43  4721.9  555.59  4776.1  554.53  4908.3  552.83  4969.3  554.52
  4983.6  553.28  4990.6  551.69  4991.5  547.51  4992.0  546.71  4997.2  546.71
  4997.7  547.51  5001.1  547.51  5005.6  549.35  5010.9  553.31  5042.7  552.53
  5054.4  553.52  5064.7  554.29  5160.1  554.61  5198.0  554.21  5255.0  554.28
  5324.5  554.53  5344.4  555.65  5506.0  556.73  5573.1  558.63  5656.9  558.72
  5829.3  562.50  5990.9  563.46  6027.6  564.83  6081.4  563.94  6227.9  565.12
#Mann=8,-1,0
  4320.8    0.05       0  4908.3    0.12       0  4991.5    0.07       0
  4997.7    0.12       0  5054.4    0.07       0  5160.1    0.05       0
  5198.0    0.16       0  5255.0    0.05       0
Bank Sta=4776.1,5324.5
Exp/Cntr=0.3,0.1

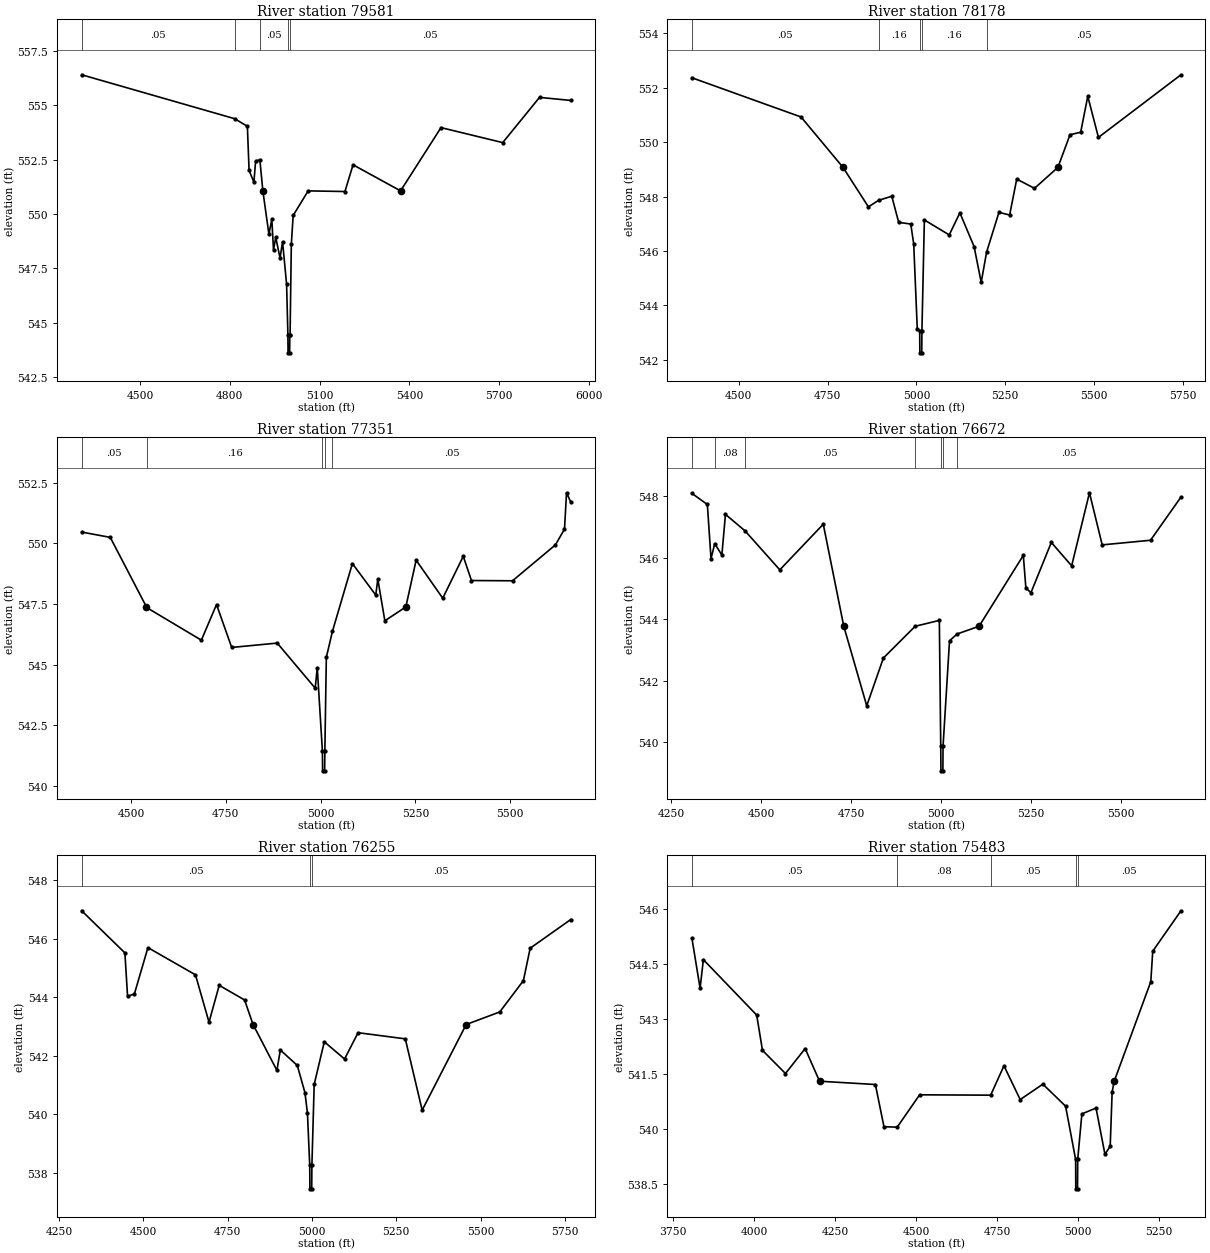
Type RM Length L Ch R = 1,79581,1403,1403,1403
BEGIN DESCRIPTION:
SCHOOLEY CREEK 75.0
END DESCRIPTION:
XS GIS Cut Line= 3
      2792656.01      7091404.10      2792322.69      7090793.02
      2791572.67      7090230.50
#Sta/Elev= 30
  4305.4  556.40  4816.3  554.38  4858.9  554.03  4864.6  552.00  4880.7  551.46
  4886.4  552.43  4900.6  552.49  4910.6  551.06  4930.9  549.06  4940.5  549.76
  4946.2  548.35  4953.7  548.92  4968.0  547.97  4976.4  548.72  4989.9  546.77
  4994.3  544.41  4994.8  543.61  5000.1  543.61  5000.6  544.41  5001.5  544.41
  5005.7  548.60  5011.9  549.93  5061.9  551.06  5184.8  551.03  5211.9  552.26
  5370.7  551.06  5505.7  553.97  5711.9  553.28  5834.8  555.36  5939.0  555.22
#Mann=5,-1,0
  4305.4    0.05       0  4816.3    0.08       0  4900.6    0.05       0
  4994.3    0.04       0  5000.6    0.05       0
Bank Sta=4910.6,5370.7
Exp/Cntr=0.3,0.1

Type RM Length L Ch R = 1,78178,827,827,827
BEGIN DESCRIPTION:
Mapping XS fe712d39
END DESCRIPTION:
XS GIS Cut Line= 3
      2793139.56      7090207.96      2792566.62      7089990.93
      2791802.74      7089999.61
#Sta/Elev= 30
  4368.2  552.36  4675.4  550.92  4793.5  549.07  4865.0  547.62  4893.6  547.86
  4930.8  548.01  4950.2  547.05  4984.2  546.99  4992.5  546.26  5002.5  543.15
  5009.3  543.06  5009.8  542.26  5015.1  542.26  5015.6  543.06  5022.5  547.14
  5092.5  546.59  5122.5  547.40  5162.5  546.16  5182.5  544.85  5197.7  545.96
  5232.5  547.42  5262.5  547.32  5282.5  548.64  5332.5  548.30  5398.4  549.07
  5432.5  550.27  5462.5  550.36  5482.5  551.68  5512.5  550.17  5744.8  552.47
#Mann=5,-1,0
  4368.2    0.05       0  4893.6    0.16       0  5009.3    0.07       0
  5015.6    0.16       0  5197.7    0.05       0
Bank Sta=4793.5,5398.4
Exp/Cntr=0.3,0.1

Type RM Length L Ch R = 1,77351,679,679,679
BEGIN DESCRIPTION:
Mapping XS e2e06187
END DESCRIPTION:
XS GIS Cut Line= 3
      2793200.30      7089548.23      2792592.66      7089535.20
      2791963.29      7089795.63
#Sta/Elev= 30
  4370.2  550.47  4445.5  550.25  4541.0  547.38  4542.1  547.35  4685.6  546.01
  4725.6  547.48  4765.6  545.71  4885.6  545.89  4985.7  544.03  4991.1  544.88
  5004.7  541.42  5005.2  540.62  5010.6  540.62  5011.1  541.42  5015.0  545.30
  5031.2  546.38  5083.7  549.17  5145.3  547.87  5150.7  548.53  5169.2  546.81
  5224.5  547.38  5251.7  549.31  5321.8  547.74  5375.9  549.47  5397.5  548.47
  5505.7  548.46  5618.8  549.94  5642.7  550.59  5648.1  552.09  5659.1  551.71
#Mann=5,-1,0
  4370.2    0.05       0  4542.1    0.16       0  5004.7    0.07       0
  5011.1    0.16       0  5031.2    0.05       0
Bank Sta=4541,5224.5
Exp/Cntr=0.3,0.1

Type RM Length L Ch R = 1,76672,417,417,417
BEGIN DESCRIPTION:
Mapping XS a35f9850
END DESCRIPTION:
XS GIS Cut Line= 3
      2793217.61      7088836.43      2792727.21      7088892.84
      2792115.23      7089504.82
#Sta/Elev= 30
  4307.5  548.08  4350.4  547.72  4360.5  545.96  4370.9  546.45  4390.7  546.08
  4400.7  547.40  4455.5  546.86  4551.7  545.60  4672.5  547.08  4729.5  543.77
  4793.3  541.19  4839.6  542.74  4928.0  543.77  4995.1  543.96  4999.0  539.88
  4999.5  539.08  5004.9  539.08  5005.4  539.88  5023.4  543.30  5044.6  543.52
  5105.5  543.77  5228.5  546.07  5235.6  545.01  5249.7  544.86  5306.3  546.49
  5362.8  545.73  5412.3  548.10  5447.7  546.41  5582.0  546.56  5666.6  547.96
#Mann=7,-1,0
  4307.5    0.05       0  4370.9    0.08       0  4455.5    0.05       0
  4928.0    0.16       0  4999.0    0.07       0  5005.4    0.16       0
  5044.6    0.05       0
Bank Sta=4729.5,5105.5
Exp/Cntr=0.3,0.1

Type RM Length L Ch R = 1,76255,772,772,772
BEGIN DESCRIPTION:
Mapping XS ec0b2429
END DESCRIPTION:
XS GIS Cut Line= 3
      2793300.16      7088576.00      2792644.74      7088649.79
      2791854.80      7088628.09
#Sta/Elev= 30
  4317.3  546.96  4445.4  545.52  4453.3  544.04  4473.4  544.11  4513.7  545.70
  4654.6  544.77  4694.8  543.15  4725.0  544.41  4800.2  543.91  4825.4  543.07
  4896.1  541.50  4906.2  542.20  4956.5  541.67  4979.2  540.74  4986.6  540.04
  4993.4  538.25  4993.9  537.45  4999.3  537.45  4999.8  538.25  5006.6  541.02
  5036.6  542.48  5096.6  541.89  5136.7  542.79  5276.7  542.58  5326.7  540.14
  5457.2  543.07  5556.8  543.50  5626.8  544.57  5646.9  545.68  5767.1  546.66
#Mann=3,-1,0
  4317.3    0.05       0  4993.4    0.03       0  4999.8    0.05       0
Bank Sta=4825.4,5457.2
Exp/Cntr=0.3,0.1

Type RM Length L Ch R = 1,75483,82,82,82
BEGIN DESCRIPTION:
Mapping XS 910df978
END DESCRIPTION:
XS GIS Cut Line= 4
      2793499.82      7088037.80      2792922.52      7088133.29
      2792323.56      7088159.34      2792038.57      7088314.79
#Sta/Elev= 30
  3808.8  545.20  3834.0  543.84  3844.1  544.62  4008.7  543.11  4026.5  542.15
  4097.5  541.52  4158.3  542.20  4202.6  541.31  4375.0  541.22  4401.5  540.07
  4442.3  540.06  4511.6  540.94  4730.8  540.93  4771.8  541.73  4821.9  540.81
  4891.9  541.23  4962.0  540.63  4993.0  539.18  4993.5  538.38  4998.9  538.38
  4999.4  539.18  5012.3  540.42  5056.0  540.58  5083.5  539.32  5099.7  539.54
  5105.7  541.02  5112.1  541.31  5225.0  544.02  5231.0  544.85  5318.1  545.95
#Mann=5,-1,0
  3808.8    0.05       0  4442.3    0.08       0  4730.8    0.05       0
  4993.0    0.03       0  4999.4    0.05       0
Bank Sta=4202.6,5112.1
Exp/Cntr=0.3,0.1