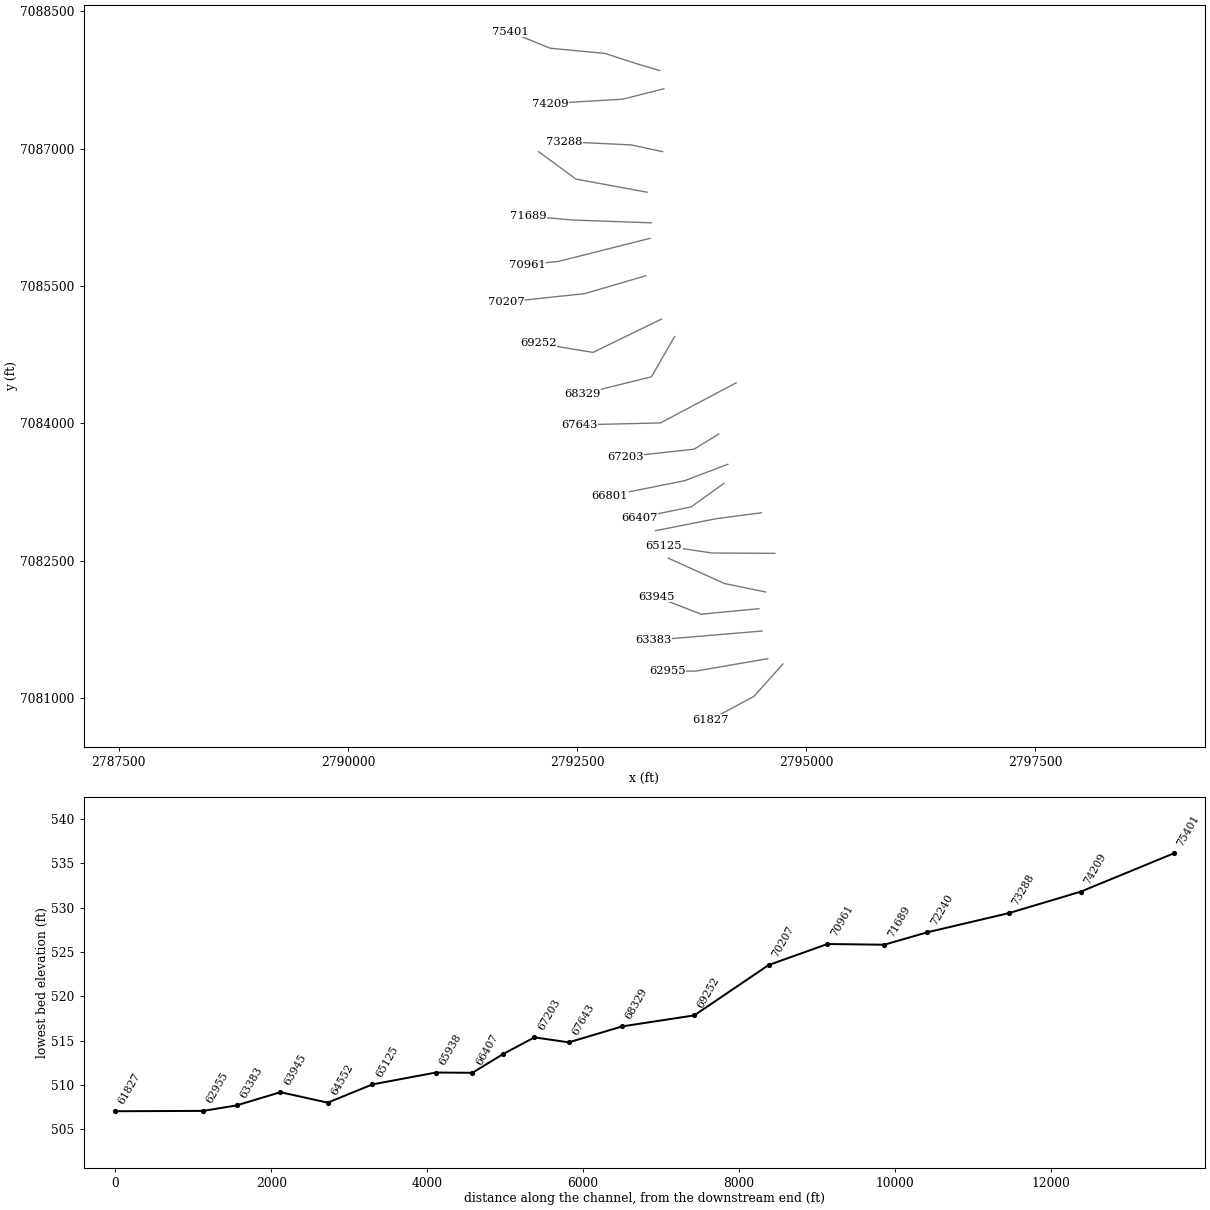
HEC-RAS study SCHOOLEY CREEK.prj: SCHOOLEY CREEK Base Level Engineering

--- SCHOOLEY CREEK.g01 (geometry) --- (continued)

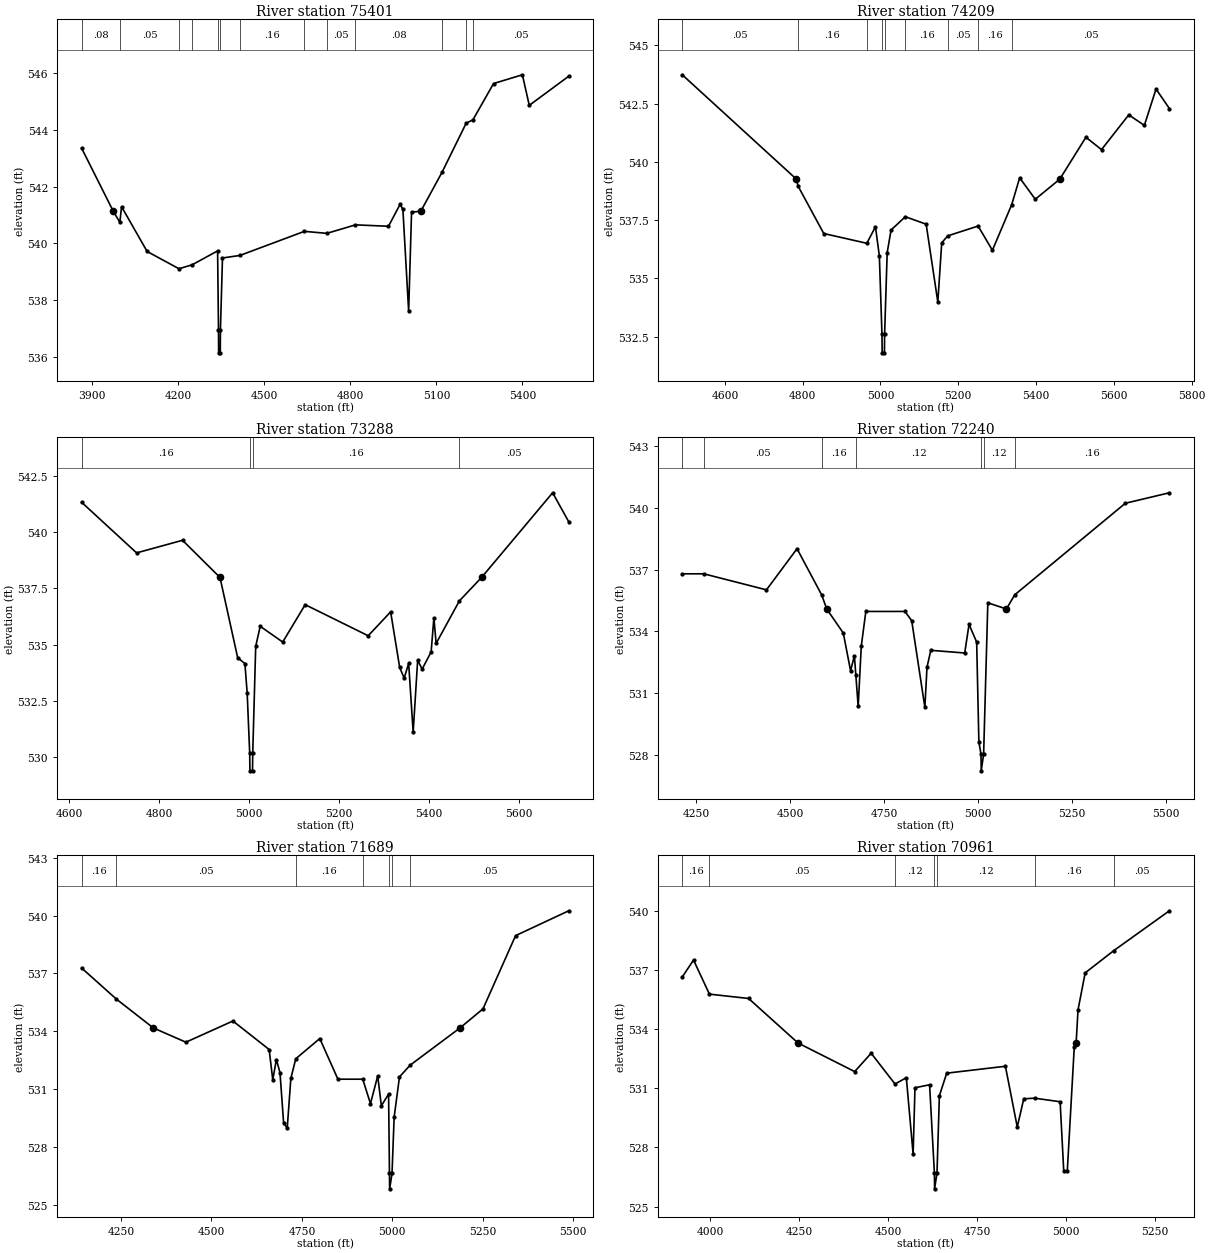
Type RM Length L Ch R = 1,75401,1192,1192,1192
BEGIN DESCRIPTION:
Mapping XS db7d6fdd
END DESCRIPTION:
XS GIS Cut Line= 5
      2793404.28      7087851.18      2793165.58      7087920.62
      2792805.33      7088037.81      2792206.37      7088094.23
      2791772.37      7088272.17
#Sta/Elev= 30
  3863.3  543.36  3973.7  541.13  3996.6  540.74  4002.7  541.29  4091.7  539.71
  4202.8  539.10  4248.7  539.24  4337.4  539.73  4340.5  536.93  4341.0  536.13
  4346.7  536.13  4347.2  536.93  4354.4  539.48  4415.3  539.57  4639.8  540.42
  4718.3  540.35  4818.0  540.65  4933.0  540.60  4973.2  541.37  4983.2  541.20
  5003.3  537.60  5013.4  541.10  5045.6  541.13  5119.3  542.50  5203.8  544.24
  5227.4  544.36  5299.2  545.64  5399.7  545.95  5423.7  544.87  5561.4  545.90
#Mann=13,-1,0
  3863.3    0.08       0  3996.6    0.05       0  4202.8    0.16       0
  4248.7    0.08       0  4340.5    0.07       0  4347.2    0.08       0
  4415.3    0.16       0  4639.8    0.08       0  4718.3    0.05       0
  4818.0    0.08       0  5119.3    0.05       0  5203.8    0.08       0
  5227.4    0.05       0
Bank Sta=3973.7,5045.6
Exp/Cntr=0.3,0.1

Type RM Length L Ch R = 1,74209,921,921,921
BEGIN DESCRIPTION:
Mapping XS 1627e4d1
END DESCRIPTION:
XS GIS Cut Line= 3
      2793447.74      7087651.53      2793000.64      7087538.68
      2792210.70      7087490.93
#Sta/Elev= 30
  4490.3  543.74  4783.9  539.26  4787.9  538.97  4854.1  536.93  4964.8  536.51
  4987.1  537.22  4997.1  535.96  5003.8  532.61  5004.3  531.81  5010.1  531.81
  5010.6  532.61  5017.2  536.11  5027.2  537.08  5063.9  537.65  5117.4  537.33
  5147.4  533.99  5157.4  536.53  5173.0  536.83  5251.0  537.25  5287.7  536.21
  5337.4  538.17  5357.8  539.32  5397.9  538.40  5460.9  539.26  5528.1  541.06
  5568.2  540.53  5638.3  542.02  5678.4  541.57  5708.4  543.13  5742.8  542.29
#Mann=9,-1,0
  4490.3    0.05       0  4787.9    0.16       0  4964.8    0.12       0
  5003.8    0.07       0  5010.6    0.12       0  5063.9    0.16       0
  5173.0    0.05       0  5251.0    0.16       0  5337.4    0.05       0
Bank Sta=4783.9,5460.9
Exp/Cntr=0.3,0.1

Type RM Length L Ch R = 1,73288,1048,1048,1048
BEGIN DESCRIPTION:
Mapping XS e4aac29d
END DESCRIPTION:
XS GIS Cut Line= 3
      2793434.71      7086965.75      2793087.45      7087039.54
      2792359.09      7087074.23
#Sta/Elev= 30
  4627.3  541.32  4749.7  539.07  4851.9  539.63  4935.3  537.98  4974.6  534.42
  4990.8  534.15  4995.8  532.85  5001.4  530.19  5001.9  529.39  5007.7  529.39
  5008.2  530.19  5014.8  534.92  5024.8  535.81  5074.9  535.11  5124.9  536.77
  5265.1  535.39  5315.1  536.45  5335.2  533.98  5345.2  533.51  5355.2  534.16
  5365.2  531.10  5375.2  534.30  5385.2  533.91  5405.2  534.67  5411.3  536.19
  5416.3  535.05  5468.1  536.94  5517.5  537.98  5675.6  541.74  5711.5  540.45
#Mann=4,-1,0
  4627.3    0.16       0  5001.4    0.07       0  5008.2    0.16       0
  5468.1    0.05       0
Bank Sta=4935.3,5517.5
Exp/Cntr=0.3,0.1

Type RM Length L Ch R = 1,72240,551,551,551
BEGIN DESCRIPTION:
Mapping XS 1d93e9ea
END DESCRIPTION:
XS GIS Cut Line= 3
      2793265.36      7086523.06      2792488.49      7086666.28
      2792080.48      7086965.78
#Sta/Elev= 30
  4212.7  536.80  4269.9  536.80  4436.8  536.02  4518.1  538.02  4583.8  535.77
  4597.1  535.09  4641.2  533.92  4660.5  532.09  4670.7  532.81  4674.6  531.86
  4680.8  530.35  4689.1  533.30  4701.2  534.97  4805.2  534.97  4823.2  534.52
  4858.2  530.31  4863.9  532.26  4874.0  533.08  4964.2  532.95  4975.7  534.34
  4996.0  533.48  5001.9  528.62  5007.6  528.02  5008.1  527.22  5014.5  528.02
  5025.7  535.39  5075.1  535.09  5097.4  535.78  5391.5  540.23  5508.8  540.74
#Mann=7,-1,0
  4212.7    0.16       0  4269.9    0.05       0  4583.8    0.16       0
  4674.6    0.12       0  5007.6    0.07       0  5014.5    0.12       0
  5097.4    0.16       0
Bank Sta=4597.1,5075.1
Exp/Cntr=0.3,0.1

Type RM Length L Ch R = 1,71689,728,728,728
BEGIN DESCRIPTION:
SCHOOLEY CREEK 70.0
END DESCRIPTION:
XS GIS Cut Line= 3
      2793313.13      7086188.85      2792458.11      7086219.23
      2791968.78      7086262.54
#Sta/Elev= 30
  4141.0  537.28  4237.0  535.67  4339.3  534.17  4429.3  533.43  4559.4  534.53
  4659.5  533.05  4669.5  531.48  4679.5  532.53  4689.5  531.85  4699.5  529.24
  4709.5  528.97  4719.5  531.55  4733.1  532.57  4799.5  533.62  4849.6  531.51
  4918.3  531.51  4939.6  530.24  4959.6  531.68  4969.7  530.13  4989.7  530.74
  4992.1  526.62  4992.6  525.82  4999.2  526.62  5005.0  529.53  5019.8  531.63
  5049.4  532.24  5187.1  534.17  5250.7  535.16  5340.8  538.96  5487.8  540.25
#Mann=7,-1,0
  4141.0    0.16       0  4237.0    0.05       0  4733.1    0.16       0
  4918.3    0.12       0  4992.1    0.07       0  4999.2    0.12       0
  5049.4    0.05       0
Bank Sta=4339.3,5187.1
Exp/Cntr=0.3,0.1

Type RM Length L Ch R = 1,70961,754,754,754
BEGIN DESCRIPTION:
Mapping XS 712b3aef
END DESCRIPTION:
XS GIS Cut Line= 3
      2793295.82      7086019.59      2792297.52      7085767.84
      2791959.45      7085733.17
#Sta/Elev= 30
  3921.1  536.65  3952.9  537.51  3997.5  535.78  4107.6  535.56  4246.6  533.30
  4405.8  531.85  4452.1  532.78  4519.2  531.22  4551.0  531.54  4570.1  527.66
  4575.3  531.03  4616.4  531.18  4629.9  526.70  4630.4  525.90  4637.2  526.70
  4643.9  530.62  4664.5  531.77  4829.5  532.12  4862.8  529.04  4881.1  530.47
  4911.6  530.50  4983.3  530.32  4993.4  526.83  5003.4  526.79  5023.0  533.08
  5028.3  533.30  5033.6  534.98  5053.7  536.86  5134.2  537.99  5290.5  540.01
#Mann=7,-1,0
  3921.1    0.16       0  3997.5    0.05       0  4519.2    0.12       0
  4629.9    0.07       0  4637.2    0.12       0  4911.6    0.16       0
  5134.2    0.05       0
Bank Sta=4246.6,5028.3
Exp/Cntr=0.3,0.1

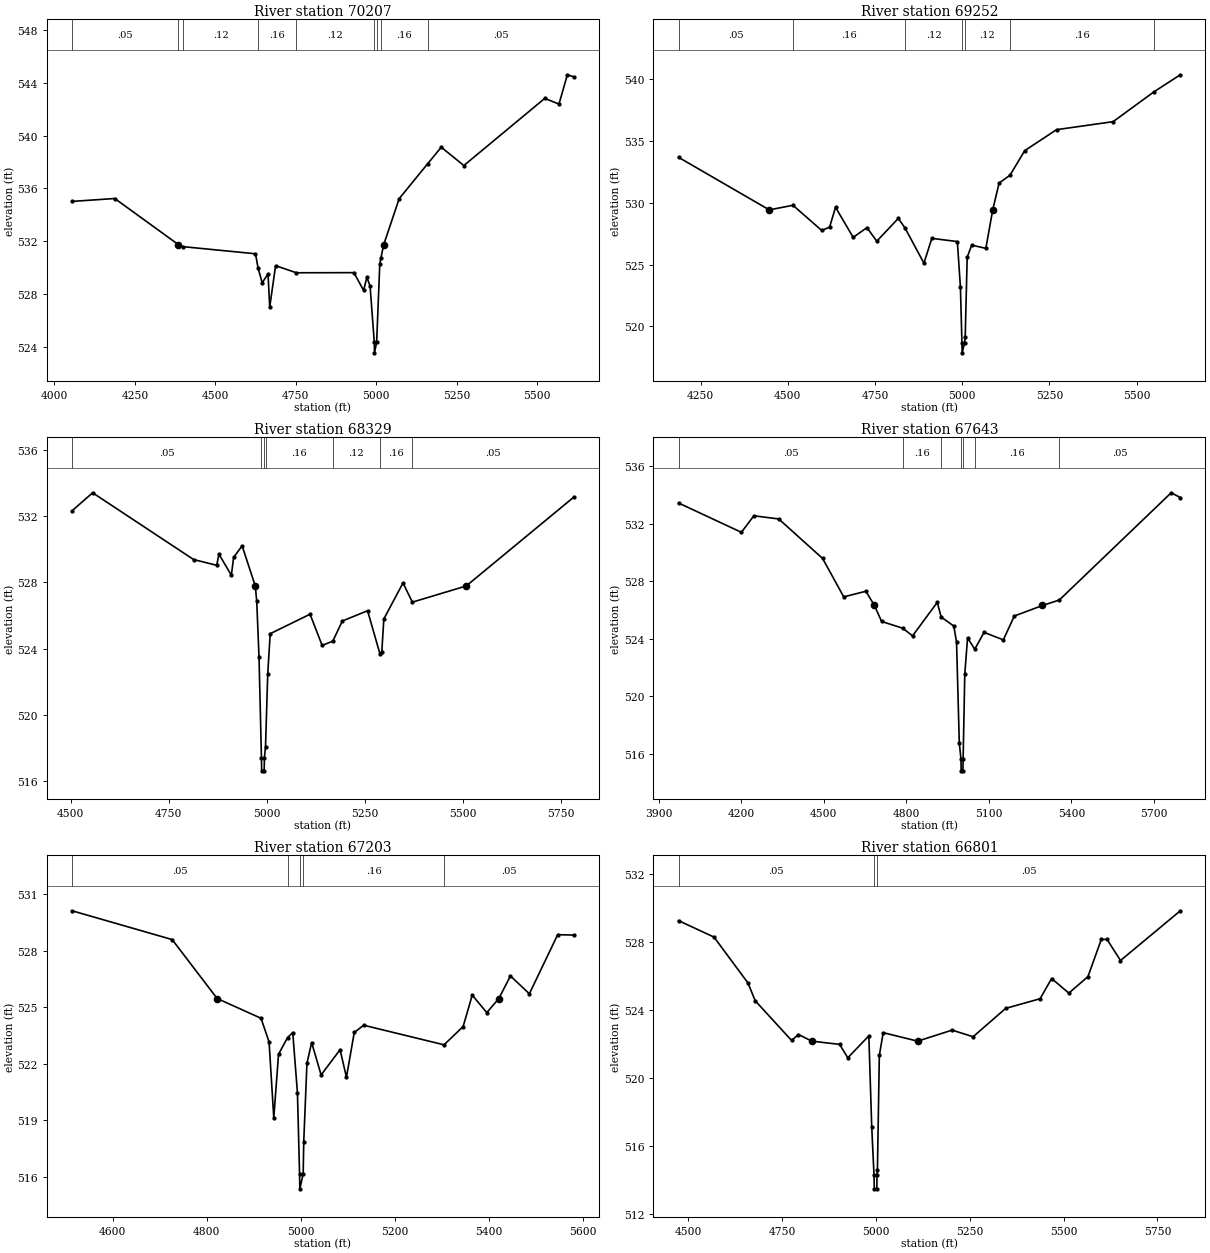
Type RM Length L Ch R = 1,70207,955,955,955
BEGIN DESCRIPTION:
SCHOOLEY CREEK 69.0
END DESCRIPTION:
XS GIS Cut Line= 3
      2793252.37      7085611.59      2792583.98      7085416.28
      2791724.96      7085325.00
#Sta/Elev= 30
  4054.7  535.01  4187.4  535.23  4384.4  531.75  4385.6  531.69  4399.5  531.58
  4625.0  531.04  4632.9  529.98  4645.8  528.84  4664.0  529.51  4669.2  526.99
  4687.5  530.14  4752.1  529.60  4931.0  529.61  4961.2  528.26  4971.3  529.26
  4981.3  528.59  4994.4  524.33  4995.0  523.53  5001.7  524.33  5011.5  530.28
  5014.8  530.69  5023.1  531.69  5071.8  535.22  5160.8  537.88  5202.6  539.12
  5272.9  537.73  5524.4  542.82  5568.6  542.39  5594.7  544.61  5614.9  544.45
#Mann=9,-1,0
  4054.7    0.05       0  4384.4    0.16       0  4399.5    0.12       0
  4632.9    0.16       0  4752.1    0.12       0  4994.4    0.07       0
  5001.7    0.12       0  5014.8    0.16       0  5160.8    0.05       0
Bank Sta=4385.6,5023.1
Exp/Cntr=0.3,0.1

Type RM Length L Ch R = 1,69252,923,923,923
BEGIN DESCRIPTION:
SCHOOLEY CREEK 68.0
END DESCRIPTION:
XS GIS Cut Line= 3
      2793421.62      7085138.49      2792675.00      7084775.00
      2792074.98      7084875.00
#Sta/Elev= 30
  4186.6  533.69  4446.7  529.43  4514.7  529.80  4597.1  527.76  4619.7  528.03
  4636.7  529.64  4687.3  527.20  4726.8  527.99  4755.0  526.89  4816.8  528.74
  4835.7  527.97  4890.2  525.11  4912.8  527.12  4986.0  526.86  4994.8  523.16
  4999.2  518.64  4999.8  517.84  5006.6  518.64  5008.5  519.11  5014.2  525.59
  5027.1  526.57  5067.7  526.31  5087.4  529.43  5105.7  531.60  5137.0  532.24
  5179.2  534.23  5270.4  535.93  5432.7  536.58  5550.3  539.01  5625.3  540.38
#Mann=7,-1,0
  4186.6    0.05       0  4514.7    0.16       0  4835.7    0.12       0
  4999.2    0.07       0  5006.6    0.12       0  5137.0    0.16       0
  5550.3    0.05       0
Bank Sta=4446.7,5087.4
Exp/Cntr=0.3,0.1

Type RM Length L Ch R = 1,68329,686,686,686
BEGIN DESCRIPTION:
SCHOOLEY CREEK 67.0
END DESCRIPTION:
XS GIS Cut Line= 3
      2793564.90      7084947.56      2793313.14      7084509.16
      2792562.23      7084322.52
#Sta/Elev= 30
  4503.8  532.34  4556.2  533.43  4813.6  529.39  4872.5  529.04  4878.3  529.71
  4909.9  528.44  4915.7  529.52  4937.3  530.22  4970.9  527.79  4974.6  526.86
  4980.4  523.50  4986.6  517.40  4987.2  516.60  4993.6  516.60  4994.2  517.40
  4997.0  518.07  5002.6  522.44  5008.9  524.90  5110.5  526.08  5141.4  524.19
  5168.5  524.45  5192.9  525.67  5257.2  526.29  5288.7  523.68  5293.4  523.78
  5298.6  525.79  5347.5  527.97  5371.4  526.81  5508.7  527.79  5783.1  533.17
#Mann=7,-1,0
  4503.8    0.05       0  4986.6    0.07       0  4994.2    0.05       0
  4997.0    0.16       0  5168.5    0.12       0  5288.7    0.16       0
  5371.4    0.05       0
Bank Sta=4970.9,5508.7
Exp/Cntr=0.3,0.1

Type RM Length L Ch R = 1,67643,440,440,440
BEGIN DESCRIPTION:
Mapping XS ba3d3f71
END DESCRIPTION:
XS GIS Cut Line= 3
      2794236.96      7084442.96      2793410.61      7084005.48
      2792521.76      7083984.65
#Sta/Elev= 30
  3971.8  533.43  4200.3  531.39  4245.6  532.54  4336.0  532.32  4495.6  529.57
  4572.3  526.90  4652.9  527.29  4683.9  526.30  4710.0  525.19  4786.6  524.72
  4822.6  524.19  4912.4  526.52  4926.4  525.50  4972.4  524.87  4982.4  523.76
  4992.4  516.75  4998.6  515.60  4999.2  514.80  5005.6  514.80  5006.3  515.60
  5012.4  521.55  5022.5  524.05  5048.6  523.26  5082.5  524.43  5152.5  523.91
  5192.5  525.57  5294.7  526.30  5355.9  526.68  5762.7  534.14  5795.9  533.81
#Mann=7,-1,0
  3971.8    0.05       0  4786.6    0.16       0  4926.4    0.12       0
  4998.6    0.07       0  5006.3    0.12       0  5048.6    0.16       0
  5355.9    0.05       0
Bank Sta=4683.9,5294.7
Exp/Cntr=0.3,0.1

Type RM Length L Ch R = 1,67203,402,402,402
BEGIN DESCRIPTION:
Mapping XS 98ea4085
END DESCRIPTION:
XS GIS Cut Line= 3
      2794046.64      7083884.15      2793777.55      7083719.23
      2793031.00      7083636.76
#Sta/Elev= 30
  4513.5  530.13  4726.3  528.60  4821.9  525.47  4915.2  524.42  4932.3  523.16
  4942.3  519.13  4952.4  522.51  4971.5  523.39  4982.6  523.66  4992.6  520.46
  4997.1  516.16  4997.7  515.36  5004.8  516.16  5006.0  517.87  5012.8  522.03
  5022.8  523.13  5042.9  521.41  5083.2  522.75  5096.8  521.29  5113.4  523.67
  5133.5  524.05  5304.2  523.01  5344.8  523.98  5364.2  525.65  5395.1  524.72
  5420.7  525.47  5445.4  526.67  5485.6  525.72  5545.8  528.86  5580.2  528.84
#Mann=5,-1,0
  4513.5    0.05       0  4971.5    0.16       0  4997.1    0.07       0
  5004.8    0.16       0  5304.2    0.05       0
Bank Sta=4821.9,5420.7
Exp/Cntr=0.3,0.1

Type RM Length L Ch R = 1,66801,394,394,394
BEGIN DESCRIPTION:
SCHOOLEY CREEK 65.0
END DESCRIPTION:
XS GIS Cut Line= 3
      2794146.51      7083554.31      2793675.00      7083375.00
      2792858.73      7083211.68
#Sta/Elev= 30
  4474.1  529.28  4568.6  528.31  4659.0  525.61  4678.4  524.56  4775.3  522.22
  4793.5  522.57  4829.5  522.18  4903.3  521.99  4925.1  521.20  4981.1  522.49
  4988.8  517.14  4994.9  514.28  4995.6  513.48  5002.3  513.48  5002.9  514.28
  5004.0  514.60  5009.1  521.34  5019.3  522.68  5111.2  522.18  5202.9  522.83
  5258.9  522.44  5345.7  524.11  5437.5  524.68  5468.1  525.87  5513.9  525.01
  5564.8  525.98  5600.6  528.18  5615.8  528.17  5651.6  526.93  5811.0  529.86
#Mann=3,-1,0
  4474.1    0.05       0  4994.9    0.03       0  5002.9    0.05       0
Bank Sta=4829.5,5111.2
Exp/Cntr=0.3,0.1

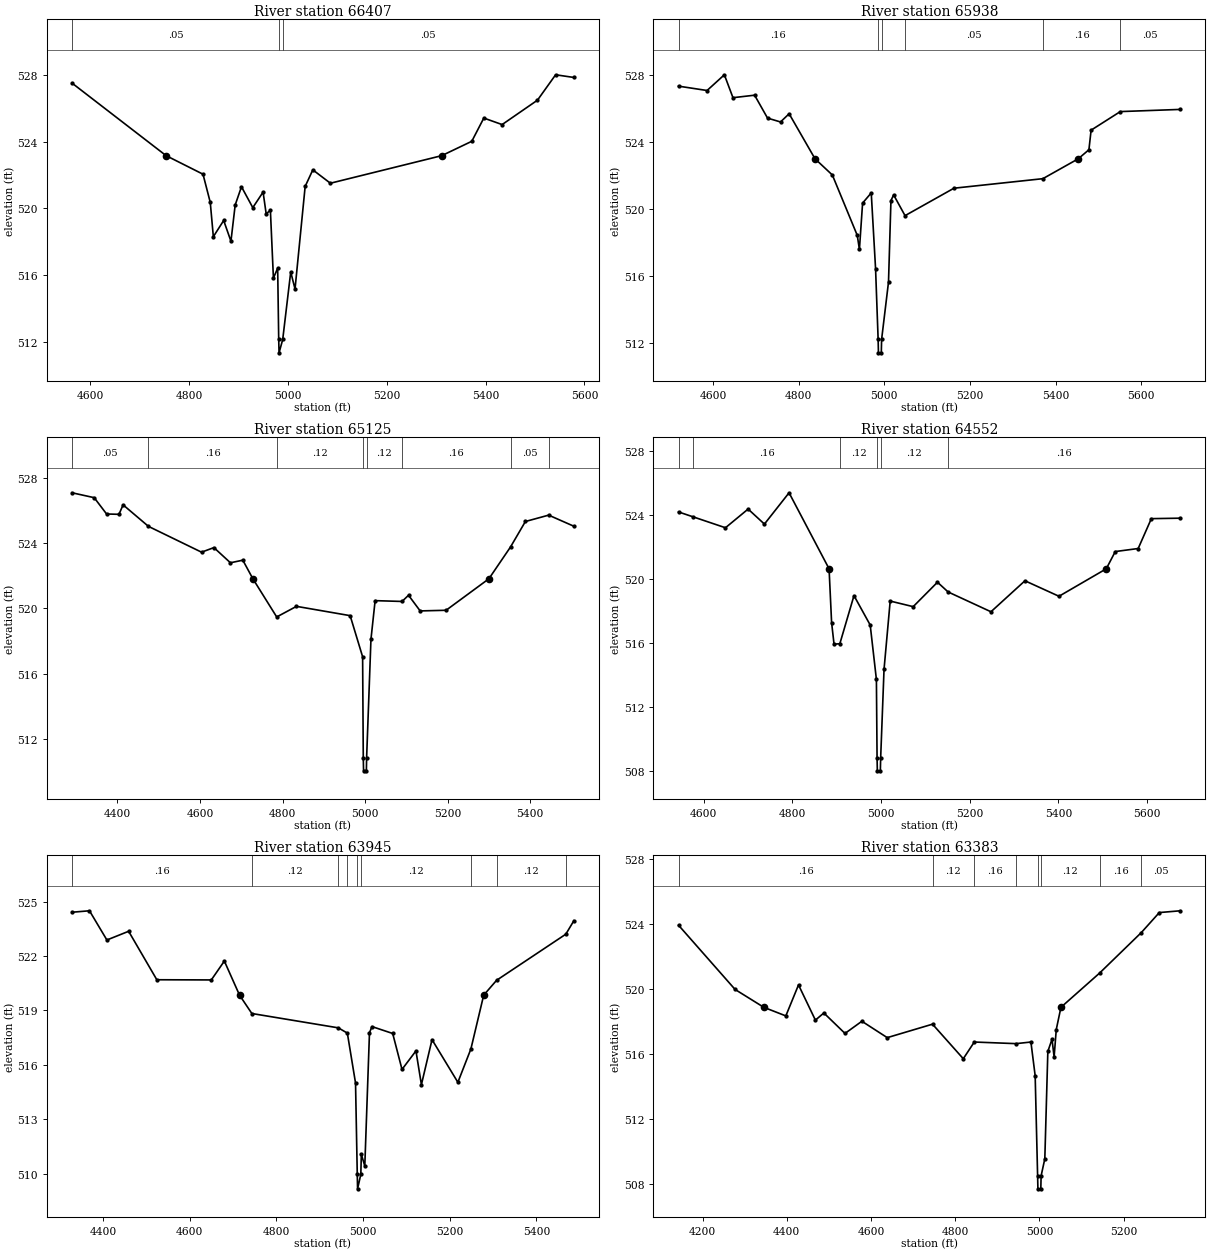
Type RM Length L Ch R = 1,66407,469,469,469
BEGIN DESCRIPTION:
SCHOOLEY CREEK 64.0
END DESCRIPTION:
XS GIS Cut Line= 3
      2794103.11      7083345.99      2793747.17      7083089.89
      2793182.91      7082972.70
#Sta/Elev= 30
  4563.7  527.50  4753.9  523.16  4828.5  522.05  4843.2  520.36  4849.4  518.31
  4870.3  519.28  4885.0  518.04  4893.6  520.21  4906.3  521.30  4929.2  520.05
  4950.0  520.98  4956.2  519.69  4964.8  519.88  4970.9  515.83  4979.5  516.43
  4981.6  512.16  4982.3  511.36  4989.7  512.16  5005.9  516.20  5014.6  515.18
  5035.1  521.32  5050.6  522.31  5086.1  521.51  5311.3  523.16  5372.1  524.02
  5396.4  525.41  5433.4  525.02  5504.9  526.48  5541.6  528.00  5578.5  527.84
#Mann=3,-1,0
  4563.7    0.05       0  4981.6    0.03       0  4989.7    0.05       0
Bank Sta=4753.9,5311.3
Exp/Cntr=0.3,0.1

Type RM Length L Ch R = 1,65938,813,813,813
BEGIN DESCRIPTION:
Mapping XS efe10ccf
END DESCRIPTION:
XS GIS Cut Line= 3
      2794511.04      7083024.78      2794016.27      7082959.68
      2793356.53      7082829.47
#Sta/Elev= 30
  4519.5  527.33  4586.1  527.07  4626.5  528.01  4646.6  526.64  4697.1  526.79
  4727.3  525.42  4757.6  525.19  4777.7  525.68  4838.1  522.99  4878.6  522.02
  4936.8  518.41  4941.8  517.57  4949.2  520.34  4969.4  520.95  4979.5  516.42
  4985.5  512.19  4986.2  511.39  4992.9  511.39  4993.6  512.19  5009.7  515.62
  5015.4  520.49  5021.7  520.83  5048.3  519.59  5162.5  521.23  5370.1  521.80
  5452.8  522.99  5477.6  523.53  5482.7  524.70  5550.9  525.81  5691.0  525.94
#Mann=6,-1,0
  4519.5    0.16       0  4985.5    0.07       0  4993.6    0.16       0
  5048.3    0.05       0  5370.1    0.16       0  5550.9    0.05       0
Bank Sta=4838.1,5452.8
Exp/Cntr=0.3,0.1

Type RM Length L Ch R = 1,65125,573,573,573
BEGIN DESCRIPTION:
Mapping XS 0068b819
END DESCRIPTION:
XS GIS Cut Line= 3
      2794658.60      7082582.08      2793972.87      7082586.42
      2793448.88      7082664.37
#Sta/Elev= 30
  4290.2  527.09  4343.8  526.79  4373.8  525.79  4403.8  525.77  4413.8  526.35
  4475.3  525.03  4603.8  523.45  4633.8  523.73  4673.8  522.80  4703.8  522.96
  4728.2  521.82  4785.9  519.48  4833.8  520.13  4963.8  519.56  4994.0  517.04
  4995.6  510.85  4996.3  510.05  5003.1  510.05  5003.7  510.85  5014.2  518.11
  5024.3  520.48  5089.5  520.43  5105.2  520.81  5133.4  519.85  5196.2  519.89
  5299.9  521.82  5352.3  523.77  5388.3  525.33  5444.7  525.72  5505.7  525.04
#Mann=8,-1,0
  4290.2    0.05       0  4475.3    0.16       0  4785.9    0.12       0
  4995.6    0.07       0  5003.7    0.12       0  5089.5    0.16       0
  5352.3    0.05       0  5444.7    0.16       0
Bank Sta=4728.2,5299.9
Exp/Cntr=0.3,0.1

Type RM Length L Ch R = 1,64552,607,607,607
BEGIN DESCRIPTION:
Mapping XS 77c02908
END DESCRIPTION:
XS GIS Cut Line= 3
      2794558.80      7082161.07      2794111.76      7082252.22
      2793495.41      7082530.01
#Sta/Elev= 30
  4543.0  524.20  4576.2  523.89  4648.9  523.21  4700.0  524.38  4736.8  523.44
  4792.4  525.40  4882.7  520.64  4888.4  517.27  4893.9  515.92  4907.0  515.95
  4938.9  518.96  4975.5  517.12  4989.5  513.71  4991.0  508.79  4991.6  507.99
  4998.4  507.99  4999.1  508.79  5006.7  514.34  5020.6  518.62  5072.5  518.27
  5127.3  519.80  5151.3  519.19  5248.0  517.95  5324.7  519.89  5401.5  518.92
  5508.2  520.64  5528.5  521.72  5580.2  521.91  5609.9  523.78  5675.3  523.81
#Mann=6,-1,0
  4543.0    0.05       0  4576.2    0.16       0  4907.0    0.12       0
  4991.0    0.07       0  4999.1    0.12       0  5151.3    0.16       0
Bank Sta=4882.7,5508.2
Exp/Cntr=0.3,0.1

Type RM Length L Ch R = 1,63945,562,562,562
BEGIN DESCRIPTION:
Mapping XS cd1c71ad
END DESCRIPTION:
XS GIS Cut Line= 3
      2794485.02      7081978.78      2793855.68      7081918.02
      2793365.22      7082108.99
#Sta/Elev= 30
  4328.0  524.41  4368.2  524.49  4408.4  522.88  4458.6  523.36  4523.7  520.69
  4649.5  520.68  4679.6  521.72  4714.7  519.84  4743.1  518.83  4942.8  518.04
  4963.6  517.75  4982.5  515.00  4986.5  509.97  4987.2  509.17  4994.7  509.97
  4995.9  511.07  5003.9  510.43  5014.7  517.77  5020.4  518.11  5068.3  517.73
  5089.8  515.75  5122.0  516.77  5134.6  514.91  5159.1  517.39  5218.8  515.04
  5248.9  516.88  5278.4  519.84  5308.2  520.66  5468.0  523.20  5486.6  523.94
#Mann=9,-1,0
  4328.0    0.16       0  4743.1    0.12       0  4942.8    0.16       0
  4963.6    0.12       0  4986.5    0.07       0  4994.7    0.12       0
  5248.9    0.16       0  5308.2    0.12       0  5468.0    0.05       0
Bank Sta=4714.7,5278.4
Exp/Cntr=0.3,0.1

Type RM Length L Ch R = 1,63383,428,428,428
BEGIN DESCRIPTION:
Mapping XS 2c6168d4
END DESCRIPTION:
XS GIS Cut Line= 3
      2794518.85      7081734.86      2793654.29      7081661.94
      2793331.37      7081635.90
#Sta/Elev= 30
  4142.9  523.93  4277.2  519.97  4345.4  518.87  4397.7  518.34  4427.8  520.25
  4467.9  518.08  4488.0  518.52  4538.2  517.26  4578.3  518.01  4638.5  517.00
  4746.0  517.83  4819.1  515.70  4845.2  516.73  4944.4  516.63  4979.7  516.73
  4989.8  514.65  4995.6  508.48  4996.3  507.68  5003.2  507.68  5003.9  508.48
  5012.7  509.53  5019.9  516.15  5029.8  516.90  5034.8  515.81  5039.9  517.50
  5051.0  518.87  5142.8  520.98  5242.0  523.48  5284.6  524.71  5334.5  524.82
#Mann=8,-1,0
  4142.9    0.16       0  4746.0    0.12       0  4845.2    0.16       0
  4944.4    0.12       0  4995.6    0.07       0  5003.9    0.12       0
  5142.8    0.16       0  5242.0    0.05       0
Bank Sta=4345.4,5051
Exp/Cntr=0.3,0.1

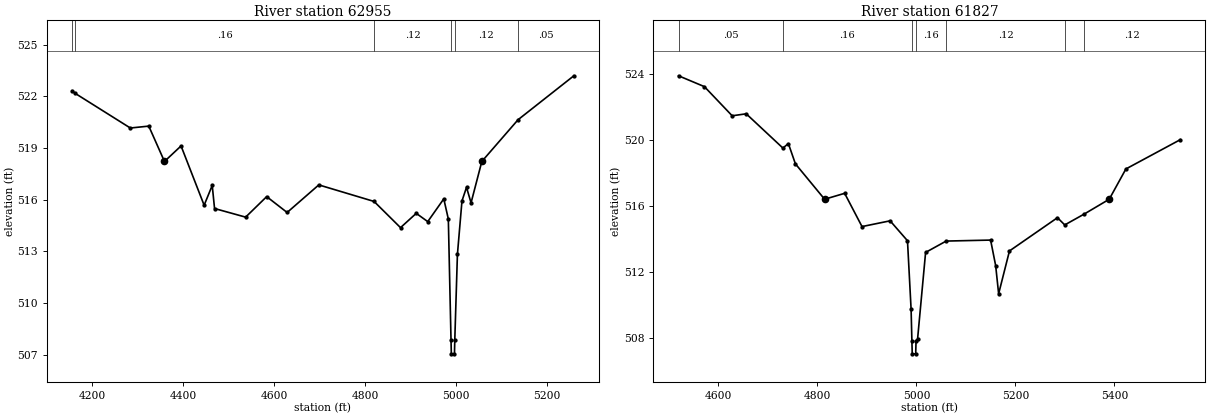
Type RM Length L Ch R = 1,62955,1128,1128,1128
BEGIN DESCRIPTION:
Mapping XS 35d86e75
END DESCRIPTION:
XS GIS Cut Line= 3
      2794581.36      7081432.77      2793794.92      7081297.36
      2793488.83      7081297.36
#Sta/Elev= 30
  4155.2  522.32  4162.0  522.17  4283.4  520.16  4324.0  520.27  4358.5  518.22
  4395.0  519.12  4445.8  515.68  4463.6  516.83  4468.7  515.49  4537.1  514.99
  4583.4  516.18  4628.4  515.26  4698.1  516.86  4819.7  515.90  4877.9  514.38
  4912.5  515.21  4937.8  514.73  4973.1  516.05  4983.1  514.88  4989.0  507.86
  4989.7  507.06  4996.6  507.06  4997.3  507.86  5003.1  512.83  5013.1  515.93
  5023.1  516.72  5033.1  515.82  5056.8  518.22  5136.5  520.64  5259.3  523.19
#Mann=6,-1,0
  4155.2    0.05       0  4162.0    0.16       0  4819.7    0.12       0
  4989.0    0.07       0  4997.3    0.12       0  5136.5    0.05       0
Bank Sta=4358.5,5056.8
Exp/Cntr=0.3,0.1

Type RM Length L Ch R = 1,61827,663,663,663
BEGIN DESCRIPTION:
Mapping XS 00b215db
END DESCRIPTION:
XS GIS Cut Line= 3
      2794748.06      7081375.50      2794430.33      7081021.32
      2793956.39      7080766.11
#Sta/Elev= 30
  4519.3  523.91  4571.6  523.25  4627.7  521.48  4656.1  521.60  4730.2  519.52
  4741.3  519.79  4755.5  518.56  4814.5  516.41  4855.0  516.77  4890.1  514.75
  4946.9  515.10  4982.0  513.89  4989.3  509.73  4990.9  507.82  4991.6  507.02
  4998.6  507.02  4999.3  507.82  5002.4  507.92  5018.6  513.18  5060.2  513.87
  5150.0  513.93  5160.2  512.38  5166.2  510.67  5188.1  513.27  5285.1  515.29
  5299.8  514.85  5339.7  515.52  5389.7  516.41  5423.4  518.25  5533.4  520.03
#Mann=7,-1,0
  4519.3    0.05       0  4730.2    0.16       0  4990.9    0.07       0
  4999.3    0.16       0  5060.2    0.12       0  5299.8    0.16       0
  5339.7    0.12       0
Bank Sta=4814.5,5389.7
Exp/Cntr=0.3,0.1