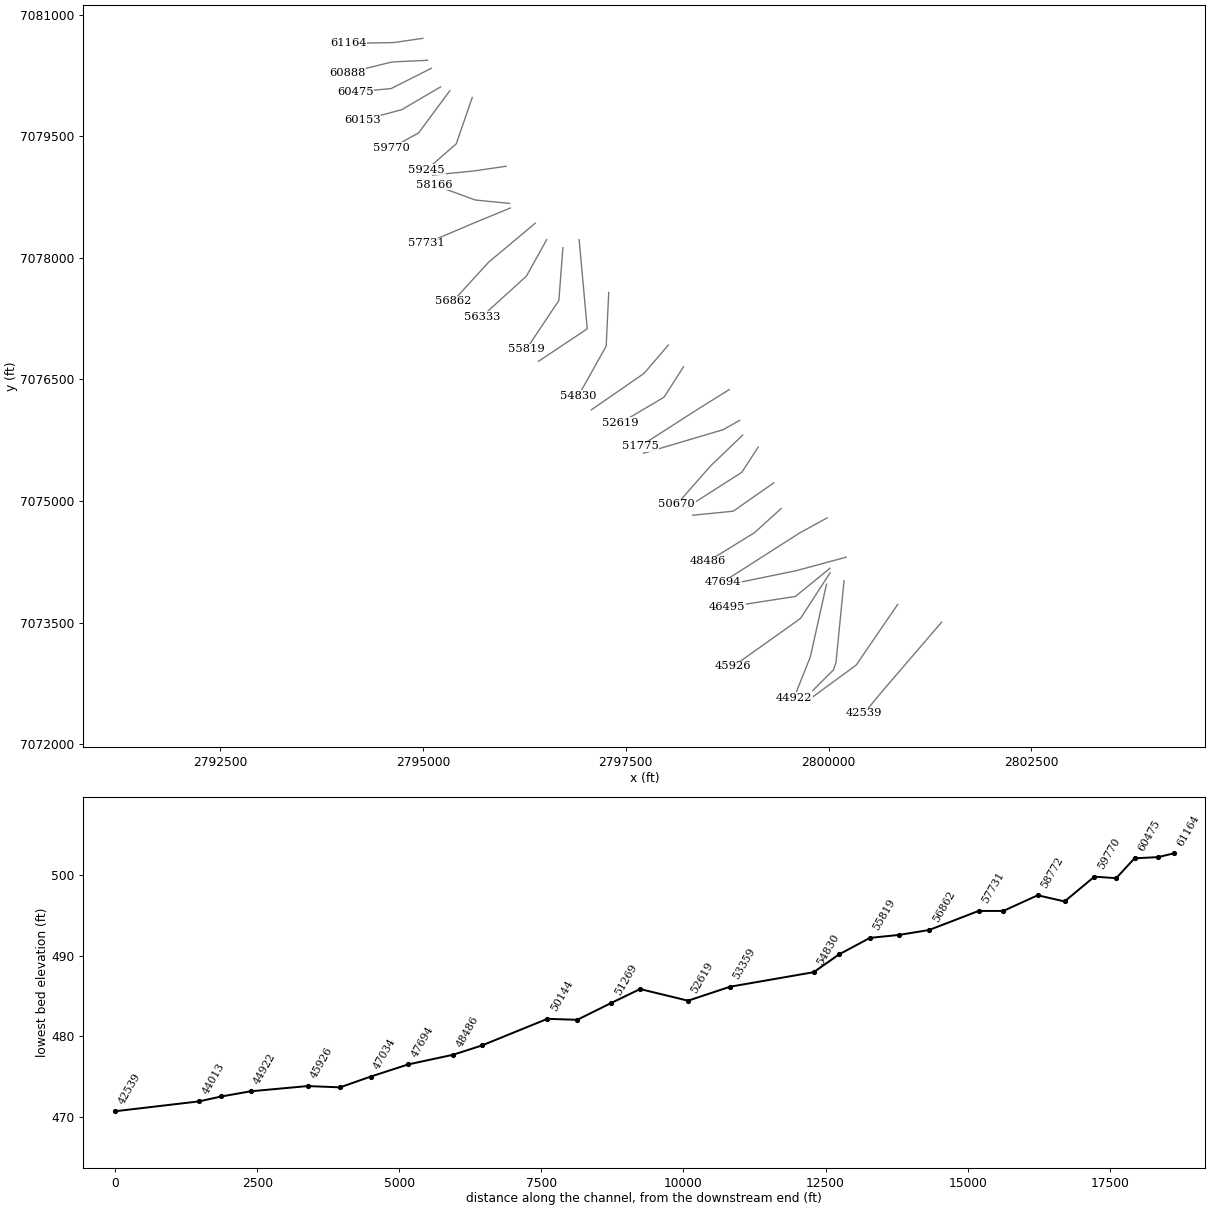
HEC-RAS study SCHOOLEY CREEK.prj: SCHOOLEY CREEK Base Level Engineering

--- SCHOOLEY CREEK.g01 (geometry) --- (continued)

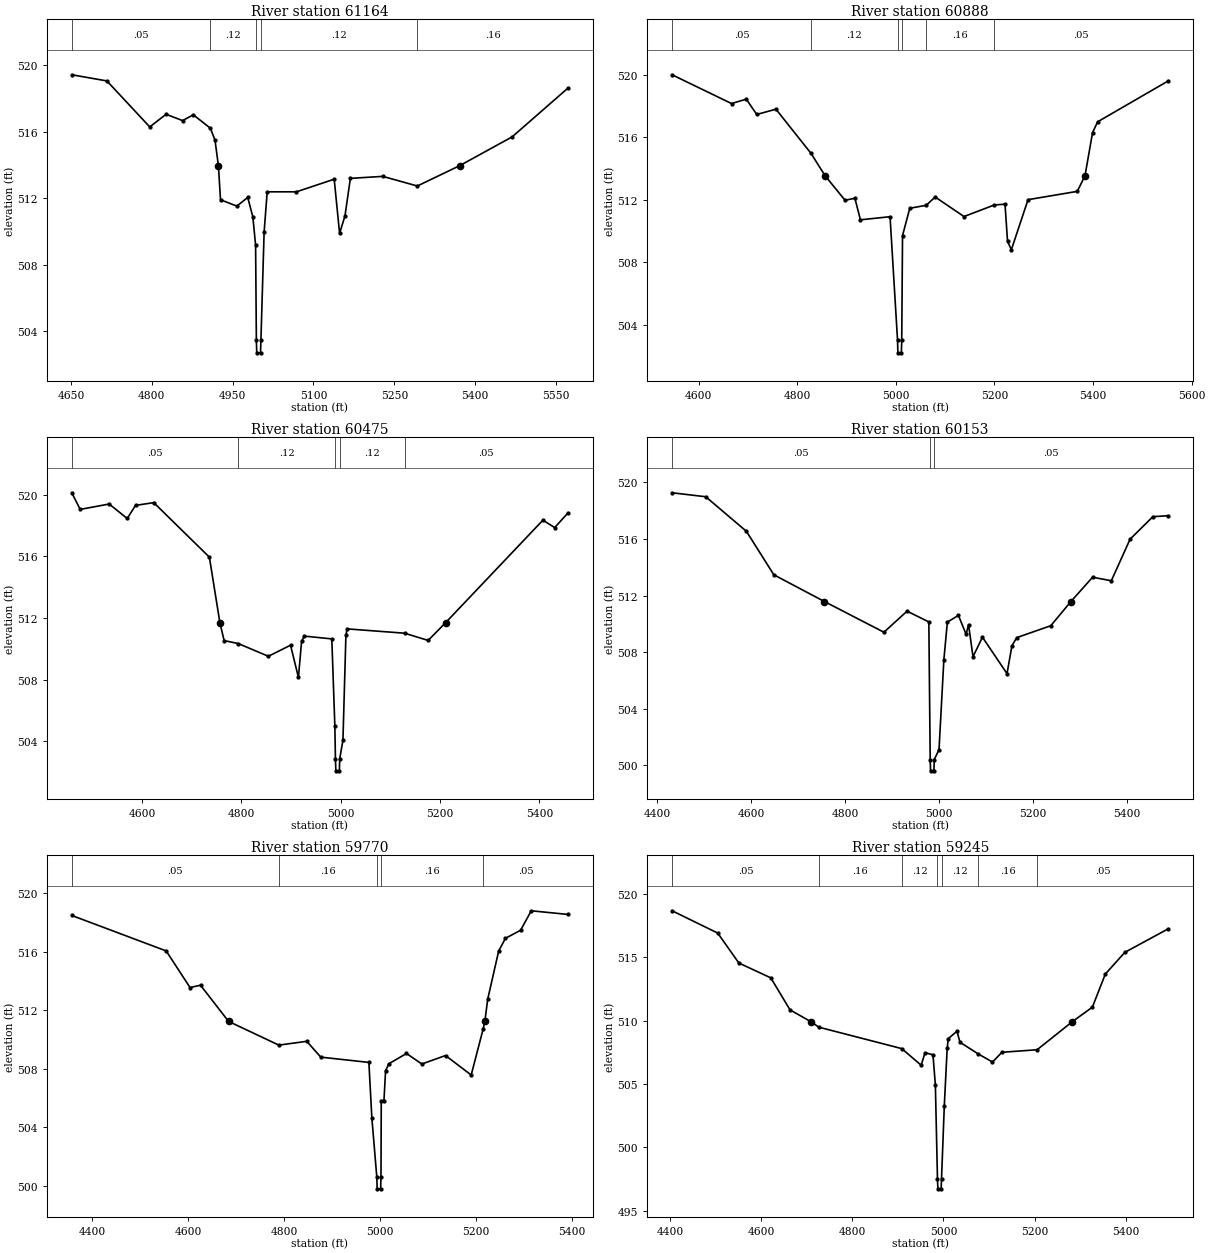
Type RM Length L Ch R = 1,61164,276,276,276
BEGIN DESCRIPTION:
Mapping XS 7ac767ed
END DESCRIPTION:
XS GIS Cut Line= 3
      2794998.06      7080708.82      2794638.67      7080656.73
      2794081.42      7080646.32
#Sta/Elev= 30
  4651.6  519.43  4716.7  519.06  4796.2  516.29  4826.5  517.05  4857.2  516.67
  4877.0  517.02  4908.7  516.21  4917.3  515.49  4923.6  513.95  4927.5  511.90
  4957.8  511.52  4978.0  512.04  4987.5  510.87  4992.6  509.16  4994.0  503.48
  4994.7  502.68  5001.7  502.68  5002.5  503.48  5008.4  509.96  5014.1  512.38
  5068.4  512.38  5138.4  513.14  5148.4  509.88  5158.4  510.93  5168.4  513.19
  5228.5  513.31  5292.6  512.73  5370.9  513.95  5468.5  515.69  5572.1  518.63
#Mann=5,-1,0
  4651.6    0.05       0  4908.7    0.12       0  4994.0    0.07       0
  5002.5    0.12       0  5292.6    0.16       0
Bank Sta=4923.6,5370.9
Exp/Cntr=0.3,0.1

Type RM Length L Ch R = 1,60888,413,413,413
BEGIN DESCRIPTION:
Mapping XS 73adc2a7
END DESCRIPTION:
XS GIS Cut Line= 3
      2795055.38      7080437.98      2794617.83      7080417.15
      2794065.74      7080281.73
#Sta/Elev= 30
  4546.1  520.01  4666.6  518.17  4696.6  518.45  4717.8  517.47  4756.7  517.81
  4827.7  514.99  4856.2  513.56  4896.9  511.98  4916.9  512.11  4928.1  510.73
  4988.2  510.93  5003.4  503.02  5004.1  502.22  5011.1  502.22  5011.9  503.02
  5013.5  509.72  5028.2  511.47  5061.6  511.66  5079.7  512.19  5138.2  510.94
  5199.6  511.68  5221.4  511.73  5226.5  509.36  5234.2  508.81  5268.1  512.02
  5368.0  512.55  5383.7  513.56  5398.9  516.30  5409.2  517.00  5552.6  519.62
#Mann=6,-1,0
  4546.1    0.05       0  4827.7    0.12       0  5003.4    0.07       0
  5011.9    0.12       0  5061.6    0.16       0  5199.6    0.05       0
Bank Sta=4856.2,5383.7
Exp/Cntr=0.3,0.1

Type RM Length L Ch R = 1,60475,322,322,322
BEGIN DESCRIPTION:
Mapping XS c6ccfbf8
END DESCRIPTION:
XS GIS Cut Line= 3
      2795102.23      7080339.03      2794607.42      7080089.02
      2794164.76      7080047.36
#Sta/Elev= 30
  4458.4  520.13  4475.3  519.05  4533.7  519.40  4570.0  518.46  4586.7  519.31
  4623.4  519.49  4735.4  515.95  4756.6  511.69  4765.1  510.53  4793.3  510.34
  4854.2  509.51  4898.8  510.23  4914.7  508.14  4921.1  510.49  4926.7  510.82
  4981.9  510.64  4988.0  505.01  4989.2  502.87  4990.0  502.07  4997.1  502.07
  4997.9  502.87  5004.3  504.05  5010.3  510.88  5012.8  511.29  5128.3  511.01
  5175.9  510.54  5210.9  511.69  5406.9  518.35  5430.6  517.87  5457.4  518.82
#Mann=5,-1,0
  4458.4    0.05       0  4793.3    0.12       0  4989.2    0.07       0
  4997.9    0.12       0  5128.3    0.05       0
Bank Sta=4756.6,5210.9
Exp/Cntr=0.3,0.1

Type RM Length L Ch R = 1,60153,383,383,383
BEGIN DESCRIPTION:
Mapping XS 3781ebbd
END DESCRIPTION:
XS GIS Cut Line= 3
      2795216.77      7080109.84      2794737.62      7079828.61
      2794253.20      7079698.39
#Sta/Elev= 30
  4431.4  519.27  4503.0  518.99  4589.6  516.55  4648.2  513.47  4756.0  511.58
  4882.7  509.41  4932.0  510.90  4978.4  510.14  4981.3  500.41  4982.1  499.61
  4989.2  499.61  4990.0  500.41  5000.1  501.11  5010.4  507.45  5017.9  510.13
  5041.5  510.60  5057.8  509.26  5063.0  509.95  5072.5  507.68  5092.6  509.06
  5145.0  506.48  5155.4  508.45  5165.7  509.03  5238.2  509.87  5281.1  511.58
  5327.3  513.30  5367.2  513.05  5407.2  515.99  5455.7  517.58  5488.6  517.65
#Mann=3,-1,0
  4431.4    0.05       0  4981.3    0.03       0  4990.0    0.05       0
Bank Sta=4756,5281.1
Exp/Cntr=0.3,0.1

Type RM Length L Ch R = 1,59770,525,525,525
BEGIN DESCRIPTION:
Mapping XS 0e0d6a56
END DESCRIPTION:
XS GIS Cut Line= 3
      2795331.39      7080063.00      2794945.96      7079542.15
      2794608.68      7079355.35
#Sta/Elev= 30
  4357.8  518.46  4554.4  516.04  4604.1  513.54  4625.9  513.70  4684.3  511.23
  4789.1  509.61  4847.2  509.87  4876.4  508.79  4976.6  508.43  4982.8  504.64
  4993.1  500.60  4993.9  499.80  5001.1  499.80  5001.8  500.60  5002.4  505.82
  5008.0  505.82  5011.4  507.87  5018.3  508.34  5054.9  509.04  5086.9  508.32
  5136.2  508.90  5189.7  507.57  5214.5  510.70  5218.2  511.23  5224.0  512.73
  5246.9  516.03  5261.0  516.90  5292.6  517.45  5314.8  518.78  5391.3  518.53
#Mann=5,-1,0
  4357.8    0.05       0  4789.1    0.16       0  4993.1    0.07       0
  5001.8    0.16       0  5214.5    0.05       0
Bank Sta=4684.3,5218.2
Exp/Cntr=0.3,0.1

Type RM Length L Ch R = 1,59245,473,473,473
BEGIN DESCRIPTION:
Mapping XS 4c072483
END DESCRIPTION:
XS GIS Cut Line= 3
      2795607.43      7079979.69      2795409.50      7079406.73
      2795045.50      7079089.53
#Sta/Elev= 30
  4404.6  518.66  4504.8  516.90  4551.1  514.54  4621.2  513.37  4663.5  510.84
  4708.9  509.92  4726.6  509.48  4908.6  507.79  4951.2  506.48  4959.7  507.47
  4977.1  507.30  4982.4  504.93  4987.0  497.53  4987.9  496.73  4995.1  496.73
  4995.9  497.53  5002.0  503.28  5008.3  507.81  5010.8  508.58  5029.8  509.16
  5036.4  508.29  5077.0  507.36  5107.7  506.73  5128.5  507.50  5205.7  507.70
  5283.2  509.92  5327.0  511.06  5355.4  513.67  5398.2  515.38  5493.6  517.24
#Mann=7,-1,0
  4404.6    0.05       0  4726.6    0.16       0  4908.6    0.12       0
  4987.0    0.07       0  4995.9    0.12       0  5077.0    0.16       0
  5205.7    0.05       0
Bank Sta=4708.9,5283.2
Exp/Cntr=0.3,0.1

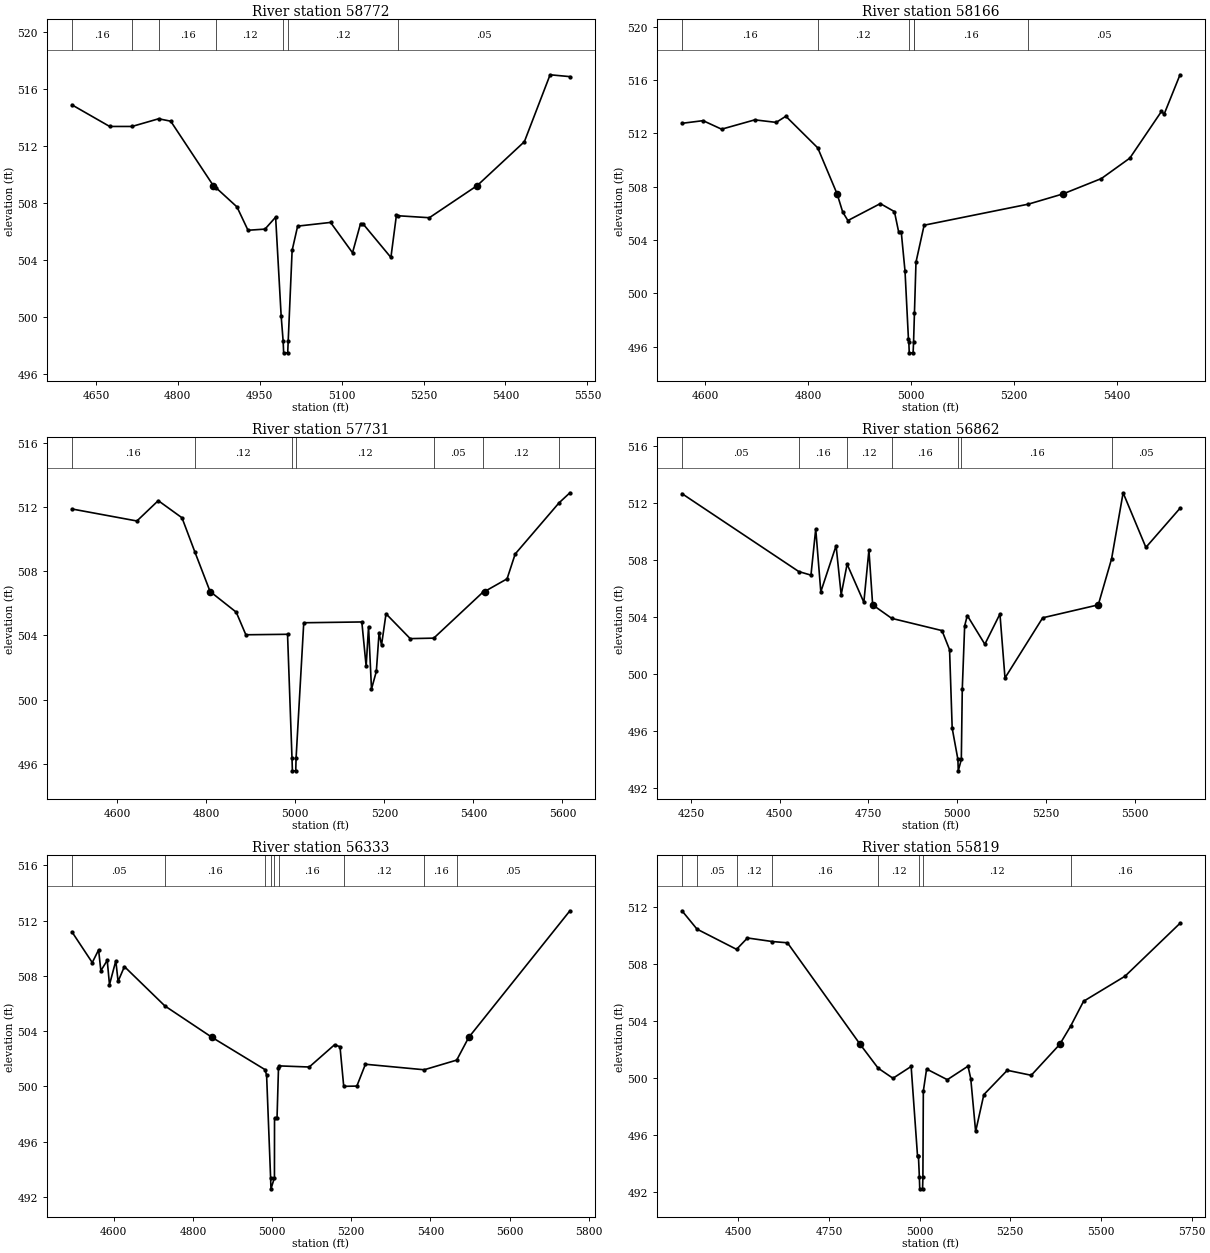
Type RM Length L Ch R = 1,58772,606,606,606
BEGIN DESCRIPTION:
Mapping XS cedcf879
END DESCRIPTION:
XS GIS Cut Line= 3
      2796024.11      7079130.69      2795633.46      7079073.40
      2795118.91      7079021.42
#Sta/Elev= 30
  4606.0  514.91  4675.2  513.39  4716.1  513.39  4764.9  513.93  4787.0  513.76
  4864.9  509.24  4870.7  509.06  4908.3  507.74  4928.5  506.10  4959.6  506.18
  4979.1  507.02  4989.2  500.10  4992.9  498.29  4993.8  497.49  5001.2  497.49
  5002.1  498.29  5009.3  504.68  5019.4  506.39  5079.7  506.65  5119.9  504.52
  5134.6  506.57  5140.0  506.51  5190.2  504.19  5200.3  507.16  5202.8  507.12
  5260.6  506.98  5348.3  509.24  5434.6  512.32  5481.7  517.02  5518.0  516.89
#Mann=7,-1,0
  4606.0    0.16       0  4716.1    0.12       0  4764.9    0.16       0
  4870.7    0.12       0  4992.9    0.07       0  5002.1    0.12       0
  5202.8    0.05       0
Bank Sta=4864.9,5348.3
Exp/Cntr=0.3,0.1

Type RM Length L Ch R = 1,58166,435,435,435
BEGIN DESCRIPTION:
Mapping XS eff255d8
END DESCRIPTION:
XS GIS Cut Line= 3
      2796065.80      7078672.35      2795643.87      7078714.02
      2795133.50      7078901.51
#Sta/Elev= 30
  4555.3  512.76  4596.3  512.96  4632.3  512.32  4696.8  513.02  4738.4  512.83
  4757.1  513.29  4819.1  510.92  4856.7  507.47  4867.6  506.11  4877.7  505.47
  4940.7  506.74  4968.1  506.14  4976.2  504.64  4981.3  504.64  4988.7  501.67
  4995.3  496.62  4996.1  496.35  4996.9  495.55  5004.4  495.55  5005.3  496.35
  5007.0  498.52  5010.0  502.35  5025.8  505.12  5228.4  506.70  5295.9  507.47
  5370.3  508.62  5425.5  510.15  5486.9  513.65  5492.2  513.45  5523.0  516.40
#Mann=6,-1,0
  4555.3    0.16       0  4819.1    0.12       0  4996.1    0.07       0
  5005.3    0.12       0  5007.0    0.16       0  5228.4    0.05       0
Bank Sta=4856.7,5295.9
Exp/Cntr=0.3,0.1

Type RM Length L Ch R = 1,57731,869,869,869
BEGIN DESCRIPTION:
Mapping XS dbd7e08e
END DESCRIPTION:
XS GIS Cut Line= 3
      2796076.19      7078615.08      2795633.46      7078432.77
      2795044.95      7078182.79
#Sta/Elev= 30
  4498.5  511.89  4644.5  511.14  4692.4  512.41  4745.7  511.34  4774.6  509.21
  4808.8  506.74  4867.5  505.45  4889.1  504.04  4982.7  504.07  4992.7  496.35
  4993.6  495.55  5001.1  495.55  5001.9  496.35  5019.1  504.79  5149.5  504.84
  5159.2  502.07  5164.6  504.55  5171.2  500.65  5182.1  501.76  5188.2  504.17
  5193.7  503.39  5203.8  505.35  5258.1  503.80  5311.0  503.83  5420.7  506.68
  5425.3  506.74  5475.6  507.53  5493.8  509.08  5592.2  512.27  5616.7  512.90
#Mann=7,-1,0
  4498.5    0.16       0  4774.6    0.12       0  4992.7    0.07       0
  5001.9    0.12       0  5311.0    0.05       0  5420.7    0.12       0
  5592.2    0.16       0
Bank Sta=4808.8,5425.3
Exp/Cntr=0.3,0.1

Type RM Length L Ch R = 1,56862,529,529,529
BEGIN DESCRIPTION:
Mapping XS db7d5bde
END DESCRIPTION:
XS GIS Cut Line= 3
      2796383.45      7078427.56      2795810.54      7077948.40
      2795368.90      7077465.20
#Sta/Elev= 30
  4225.1  512.68  4553.9  507.20  4588.1  506.95  4601.5  510.20  4615.8  505.78
  4658.8  509.02  4673.1  505.57  4689.8  507.72  4736.9  505.04  4751.2  508.71
  4761.7  504.86  4815.4  503.91  4956.8  503.05  4978.1  501.71  4985.5  496.19
  5001.6  493.99  5002.6  493.19  5011.2  493.99  5013.9  498.93  5020.6  503.38
  5028.0  504.11  5077.4  502.09  5119.9  504.22  5134.1  499.72  5240.2  503.95
  5396.6  504.86  5434.1  508.10  5466.5  512.74  5530.6  508.90  5626.6  511.65
#Mann=7,-1,0
  4225.1    0.05       0  4553.9    0.16       0  4689.8    0.12       0
  4815.4    0.16       0  5001.6    0.07       0  5011.2    0.16       0
  5434.1    0.05       0
Bank Sta=4761.7,5396.6
Exp/Cntr=0.3,0.1

Type RM Length L Ch R = 1,56333,514,514,514
BEGIN DESCRIPTION:
SCHOOLEY CREEK 53.0
END DESCRIPTION:
XS GIS Cut Line= 3
      2796525.01      7078225.02      2796275.00      7077775.00
      2795725.01      7077275.01
#Sta/Elev= 30
  4494.2  511.19  4545.7  508.96  4561.7  509.88  4567.4  508.37  4583.5  509.12
  4589.2  507.36  4605.2  509.09  4610.9  507.60  4626.9  508.67  4729.2  505.82
  4848.5  503.54  4982.1  501.21  4986.1  500.80  4996.2  493.38  4997.1  492.58
  5005.9  493.38  5006.1  497.68  5012.4  497.68  5016.1  501.31  5018.4  501.48
  5093.8  501.40  5157.7  503.01  5171.5  502.87  5180.9  500.00  5214.1  500.02
  5235.7  501.60  5384.2  501.20  5466.3  501.90  5496.6  503.54  5752.3  512.71
#Mann=9,-1,0
  4494.2    0.05       0  4729.2    0.16       0  4982.1    0.12       0
  4996.2    0.07       0  5005.9    0.12       0  5018.4    0.16       0
  5180.9    0.12       0  5384.2    0.16       0  5466.3    0.05       0
Bank Sta=4848.5,5496.6
Exp/Cntr=0.3,0.1

Type RM Length L Ch R = 1,55819,544,544,544
BEGIN DESCRIPTION:
SCHOOLEY CREEK 52.0
END DESCRIPTION:
XS GIS Cut Line= 3
      2796725.00      7078124.96      2796675.00      7077475.00
      2796275.00      7076874.99
#Sta/Elev= 30
  4345.0  511.75  4386.5  510.46  4495.5  509.04  4525.5  509.84  4593.8  509.59
  4635.8  509.50  4836.3  502.36  4885.8  500.69  4926.7  499.98  4976.8  500.81
  4994.4  494.51  4996.9  494.51  4999.5  493.01  5000.5  492.21  5008.3  492.21
  5009.2  493.01  5010.4  499.08  5019.4  500.63  5076.5  499.88  5133.6  500.83
  5141.1  499.96  5154.6  496.24  5177.2  498.83  5241.8  500.54  5307.9  500.19
  5386.4  502.36  5416.6  503.65  5452.1  505.39  5566.3  507.15  5718.0  510.87
#Mann=8,-1,0
  4345.0    0.16       0  4386.5    0.05       0  4495.5    0.12       0
  4593.8    0.16       0  4885.8    0.12       0  4999.5    0.07       0
  5009.2    0.12       0  5416.6    0.16       0
Bank Sta=4836.3,5386.4
Exp/Cntr=0.3,0.1

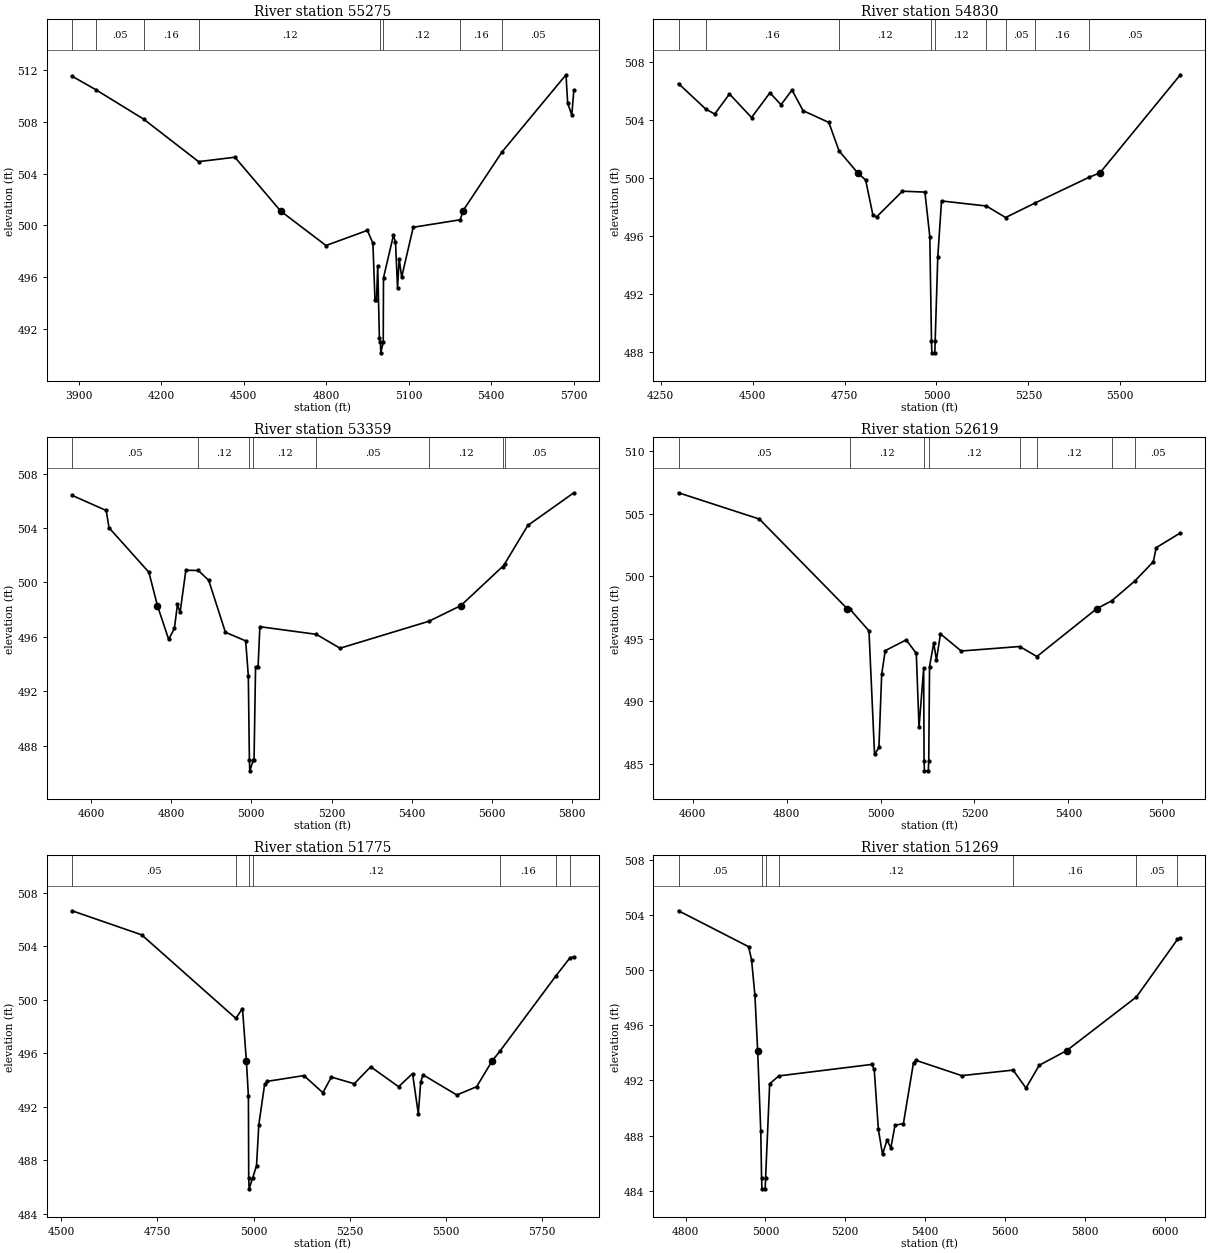
Type RM Length L Ch R = 1,55275,445,445,445
BEGIN DESCRIPTION:
SCHOOLEY CREEK 51.0
END DESCRIPTION:
XS GIS Cut Line= 3
      2796925.00      7078225.05      2797025.00      7077125.00
      2796424.99      7076725.00
#Sta/Elev= 30
  3875.5  511.53  3960.8  510.50  4135.5  508.22  4335.8  504.93  4468.0  505.27
  4634.6  501.11  4799.3  498.45  4950.0  499.62  4970.0  498.63  4977.6  494.23
  4983.1  494.23  4987.6  496.90  4993.6  491.30  4997.6  490.96  4998.6  490.16
  5007.6  490.96  5008.6  495.96  5044.7  499.23  5052.2  498.73  5059.7  495.18
  5065.7  497.42  5074.7  496.01  5116.8  499.86  5288.0  500.44  5297.1  501.11
  5439.9  505.68  5672.6  511.64  5678.7  509.44  5693.7  508.54  5701.2  510.47
#Mann=8,-1,0
  3875.5    0.16       0  3960.8    0.05       0  4135.5    0.16       0
  4335.8    0.12       0  4997.6    0.07       0  5007.6    0.12       0
  5288.0    0.16       0  5439.9    0.05       0
Bank Sta=4634.6,5297.1
Exp/Cntr=0.3,0.1

Type RM Length L Ch R = 1,54830,1471,1471,1471
BEGIN DESCRIPTION:
SCHOOLEY CREEK 50.0
END DESCRIPTION:
XS GIS Cut Line= 3
      2797289.71      7077573.35      2797258.46      7076911.94
      2796915.46      7076298.70
#Sta/Elev= 30
  4298.5  506.48  4372.6  504.73  4397.0  504.39  4437.0  505.77  4497.1  504.15
  4547.1  505.85  4577.2  505.03  4607.2  506.04  4637.2  504.62  4707.3  503.81
  4735.0  501.86  4785.8  500.34  4807.4  499.85  4827.4  497.41  4837.5  497.32
  4907.5  499.08  4968.6  499.02  4981.9  495.96  4986.5  488.76  4987.5  487.96
  4995.5  487.96  4996.5  488.76  5003.6  494.57  5013.8  498.41  5136.0  498.06
  5188.0  497.27  5269.2  498.28  5415.2  500.04  5444.6  500.34  5663.3  507.09
#Mann=9,-1,0
  4298.5    0.05       0  4372.6    0.16       0  4735.0    0.12       0
  4986.5    0.07       0  4996.5    0.12       0  5136.0    0.16       0
  5188.0    0.05       0  5269.2    0.16       0  5415.2    0.05       0
Bank Sta=4785.8,5444.6
Exp/Cntr=0.3,0.1

Type RM Length L Ch R = 1,53359,740,740,740
BEGIN DESCRIPTION:
SCHOOLEY CREEK 49.0
END DESCRIPTION:
XS GIS Cut Line= 3
      2798025.02      7076925.02      2797725.00      7076575.00
      2797074.98      7076124.99
#Sta/Elev= 30
  4552.8  506.40  4637.9  505.29  4645.0  504.02  4744.4  500.75  4765.7  498.30
  4793.7  495.82  4808.0  496.62  4815.7  498.39  4822.3  497.80  4836.6  500.90
  4867.5  500.88  4893.6  500.16  4935.3  496.34  4985.8  495.71  4992.4  493.15
  4995.1  486.96  4996.1  486.16  5005.1  486.96  5006.7  486.99  5010.5  493.81
  5016.8  493.81  5021.2  496.75  5162.0  496.19  5221.2  495.17  5442.8  497.15
  5522.5  498.30  5626.7  501.17  5631.9  501.37  5689.5  504.19  5804.4  506.59
#Mann=8,-1,0
  4552.8    0.05       0  4867.5    0.12       0  4995.1    0.07       0
  5005.1    0.12       0  5162.0    0.05       0  5442.8    0.12       0
  5626.7    0.16       0  5631.9    0.05       0
Bank Sta=4765.7,5522.5
Exp/Cntr=0.3,0.1

Type RM Length L Ch R = 1,52619,844,844,844
BEGIN DESCRIPTION:
Mapping XS 1b70d985
END DESCRIPTION:
XS GIS Cut Line= 3
      2798211.57      7076656.71      2797972.00      7076281.73
      2797435.50      7075964.00
#Sta/Elev= 30
  4569.8  506.66  4741.9  504.56  4929.1  497.39  4935.3  497.33  4975.3  495.62
  4987.2  485.74  4996.5  486.30  5002.4  492.16  5009.9  494.04  5054.7  494.90
  5076.1  493.82  5081.9  487.91  5091.8  492.62  5092.6  485.23  5093.5  484.43
  5101.6  484.43  5102.6  485.23  5104.3  492.77  5113.2  494.65  5119.0  493.29
  5127.5  495.38  5171.7  494.01  5296.3  494.37  5332.9  493.57  5460.2  497.39
  5492.0  498.02  5541.3  499.60  5580.8  501.15  5586.9  502.27  5638.3  503.45
#Mann=8,-1,0
  4569.8    0.05       0  4935.3    0.12       0  5092.6    0.07       0
  5102.6    0.12       0  5296.3    0.05       0  5332.9    0.12       0
  5492.0    0.16       0  5541.3    0.05       0
Bank Sta=4929.1,5460.2
Exp/Cntr=0.3,0.1

Type RM Length L Ch R = 1,51775,506,506,506
BEGIN DESCRIPTION:
SCHOOLEY CREEK 47.0
END DESCRIPTION:
XS GIS Cut Line= 3
      2798775.01      7076375.01      2798375.00      7076125.00
      2797674.99      7075674.99
#Sta/Elev= 30
  4528.5  506.64  4709.5  504.84  4954.1  498.60  4971.3  499.34  4981.5  495.40
  4986.7  492.80  4987.5  486.67  4988.5  485.87  4997.6  486.67  5007.8  487.60
  5013.8  490.67  5028.9  493.68  5035.9  493.90  5131.0  494.33  5180.2  493.05
  5202.3  494.22  5261.8  493.72  5304.4  494.99  5377.0  493.50  5413.3  494.48
  5428.2  491.47  5434.5  493.86  5440.4  494.39  5528.2  492.88  5579.8  493.50
  5619.5  495.40  5640.7  496.17  5785.6  501.77  5822.7  503.14  5832.4  503.19
#Mann=7,-1,0
  4528.5    0.05       0  4954.1    0.12       0  4987.5    0.07       0
  4997.6    0.12       0  5640.7    0.16       0  5785.6    0.05       0
  5822.7    0.16       0
Bank Sta=4981.5,5619.5
Exp/Cntr=0.3,0.1

Type RM Length L Ch R = 1,51269,599,599,599
BEGIN DESCRIPTION:
Mapping XS 2390259d
END DESCRIPTION:
XS GIS Cut Line= 3
      2798904.30      7075995.28      2798701.17      7075880.69
      2797720.05      7075589.99
#Sta/Elev= 30
  4782.5  504.29  4957.9  501.69  4965.4  500.73  4973.8  498.16  4980.6  494.16
  4988.4  488.34  4990.4  484.95  4991.4  484.15  4999.5  484.15  5000.5  484.95
  5010.7  491.76  5033.7  492.33  5265.9  493.16  5272.5  492.81  5282.9  488.45
  5293.3  486.65  5304.4  487.67  5314.2  487.13  5324.6  488.76  5345.5  488.87
  5370.9  493.29  5376.8  493.46  5491.5  492.35  5620.3  492.75  5652.5  491.45
  5685.7  493.10  5754.3  494.16  5929.1  498.05  6031.7  502.21  6039.0  502.31
#Mann=7,-1,0
  4782.5    0.05       0  4990.4    0.03       0  5000.5    0.05       0
  5033.7    0.12       0  5620.3    0.16       0  5929.1    0.05       0
  6031.7    0.16       0
Bank Sta=4980.6,5754.3
Exp/Cntr=0.3,0.1

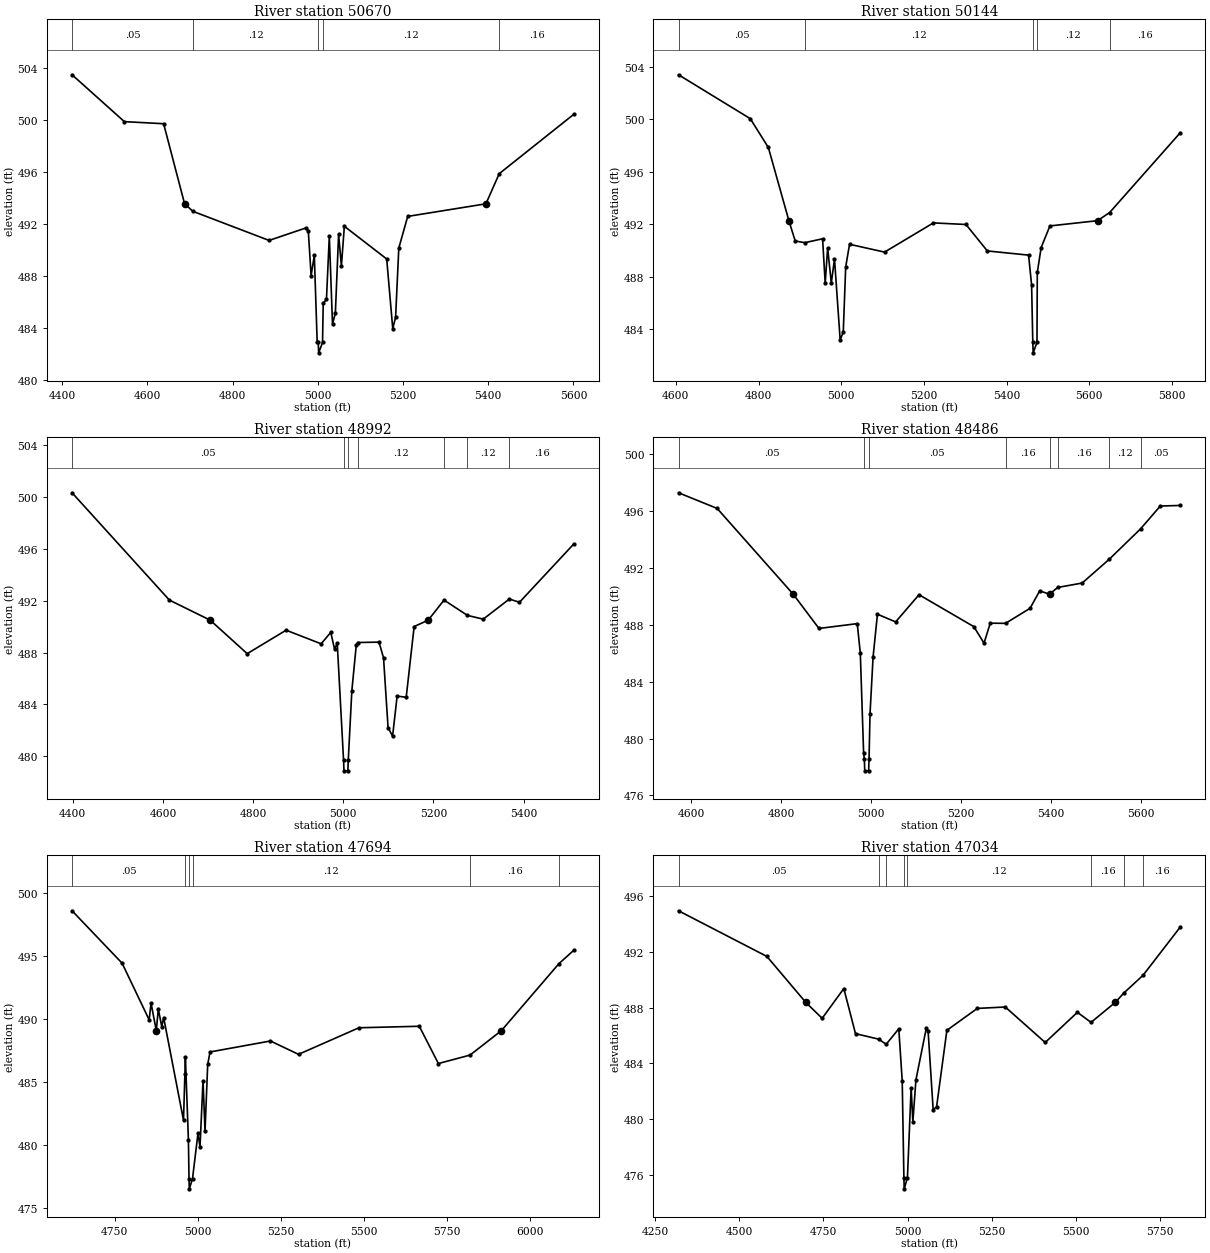
Type RM Length L Ch R = 1,50670,526,526,526
BEGIN DESCRIPTION:
Mapping XS 21576f1e
END DESCRIPTION:
XS GIS Cut Line= 3
      2798940.74      7075812.97      2798544.92      7075432.77
      2798129.64      7074960.40
#Sta/Elev= 30
  4423.2  503.48  4546.0  499.87  4638.1  499.71  4687.3  493.54  4706.9  492.96
  4885.6  490.72  4972.0  491.68  4977.6  491.48  4984.3  488.01  4991.8  489.57
  4998.5  482.93  5001.0  482.86  5002.0  482.06  5011.1  482.86  5012.7  485.87
  5020.3  486.18  5027.0  491.05  5034.5  484.28  5041.2  485.11  5048.8  491.18
  5055.4  488.76  5062.3  491.81  5161.7  489.29  5175.9  483.93  5182.6  484.80
  5190.1  490.13  5211.0  492.57  5394.6  493.54  5425.8  495.86  5601.0  500.44
#Mann=5,-1,0
  4423.2    0.05       0  4706.9    0.12       0  5001.0    0.07       0
  5011.1    0.12       0  5425.8    0.16       0
Bank Sta=4687.3,5394.6
Exp/Cntr=0.3,0.1

Type RM Length L Ch R = 1,50144,1152,1152,1152
BEGIN DESCRIPTION:
Mapping XS 379c79c3
END DESCRIPTION:
XS GIS Cut Line= 3
      2799133.45      7075667.13      2798930.33      7075354.65
      2798221.97      7074901.50
#Sta/Elev= 30
  4606.5  503.41  4780.0  500.06  4823.7  497.86  4873.4  492.27  4888.7  490.72
  4911.9  490.59  4954.9  490.89  4961.2  487.48  4967.1  490.19  4976.0  487.51
  4983.7  489.35  4997.4  483.17  5004.9  483.77  5010.8  488.74  5020.1  490.47
  5104.7  489.87  5222.9  492.10  5301.7  491.98  5353.3  489.96  5453.1  489.64
  5460.4  487.36  5463.3  482.98  5464.2  482.18  5473.4  482.98  5474.2  488.32
  5483.5  490.22  5504.7  491.87  5619.8  492.27  5649.1  492.89  5820.1  498.99
#Mann=5,-1,0
  4606.5    0.05       0  4911.9    0.12       0  5463.3    0.07       0
  5473.4    0.12       0  5649.1    0.16       0
Bank Sta=4873.4,5619.8
Exp/Cntr=0.3,0.1

Type RM Length L Ch R = 1,48992,506,506,506
BEGIN DESCRIPTION:
SCHOOLEY CREEK 43.0
END DESCRIPTION:
XS GIS Cut Line= 3
      2799325.00      7075225.00      2798825.00      7074875.00
      2798325.02      7074825.00
#Sta/Elev= 30
  4398.6  500.31  4614.4  492.04  4705.0  490.49  4787.0  487.91  4873.3  489.72
  4950.9  488.67  4972.3  489.55  4980.6  488.28  4986.7  488.70  5000.7  479.68
  5001.6  478.88  5010.2  478.88  5011.1  479.68  5019.0  485.04  5029.0  488.61
  5032.0  488.77  5079.3  488.80  5089.3  487.59  5099.4  482.20  5109.4  481.56
  5119.5  484.64  5139.6  484.55  5157.2  490.00  5188.3  490.49  5223.5  492.04
  5275.3  490.86  5310.4  490.57  5368.3  492.12  5390.8  491.87  5511.4  496.37
#Mann=7,-1,0
  4398.6    0.05       0  5000.7    0.03       0  5011.1    0.05       0
  5032.0    0.12       0  5223.5    0.16       0  5275.3    0.12       0
  5368.3    0.16       0
Bank Sta=4705,5188.3
Exp/Cntr=0.3,0.1

Type RM Length L Ch R = 1,48486,792,792,792
BEGIN DESCRIPTION:
Mapping XS 95c5c224
END DESCRIPTION:
XS GIS Cut Line= 3
      2799414.73      7074906.75      2799086.58      7074609.86
      2798513.64      7074255.67
#Sta/Elev= 30
  4571.5  497.26  4657.4  496.16  4826.7  490.13  4883.9  487.73  4969.0  488.07
  4975.8  486.00  4983.2  478.96  4984.8  478.53  4985.7  477.73  4994.3  477.73
  4995.2  478.53  4997.4  481.73  5004.2  485.72  5013.9  488.73  5054.4  488.19
  5106.4  490.10  5228.2  487.86  5251.0  486.70  5264.8  488.10  5298.9  488.09
  5353.5  489.15  5374.8  490.37  5397.3  490.13  5398.0  490.17  5414.7  490.61
  5469.3  490.92  5529.5  492.59  5599.3  494.73  5643.1  496.33  5687.6  496.37
#Mann=8,-1,0
  4571.5    0.05       0  4984.8    0.07       0  4995.2    0.05       0
  5298.9    0.16       0  5398.0    0.12       0  5414.7    0.16       0
  5529.5    0.12       0  5599.3    0.05       0
Bank Sta=4826.7,5397.3
Exp/Cntr=0.3,0.1

Type RM Length L Ch R = 1,47694,660,660,660
BEGIN DESCRIPTION:
Mapping XS c45b1784
END DESCRIPTION:
XS GIS Cut Line= 3
      2799982.39      7074792.14      2799649.08      7074609.86
      2798695.93      7074000.47
#Sta/Elev= 30
  4621.9  498.61  4772.5  494.45  4854.1  489.95  4859.8  491.27  4875.6  489.09
  4881.6  490.80  4892.0  489.42  4897.7  490.13  4957.5  481.98  4961.7  485.66
  4963.2  486.98  4972.3  480.39  4974.1  477.33  4975.0  476.53  4984.6  477.33
  5001.1  480.94  5007.2  479.85  5016.3  485.12  5022.3  481.10  5030.4  486.43
  5037.5  487.40  5219.3  488.27  5303.9  487.21  5485.8  489.32  5667.6  489.44
  5725.1  486.48  5820.4  487.15  5914.8  489.09  6088.1  494.41  6133.1  495.48
#Mann=6,-1,0
  4621.9    0.05       0  4961.7    0.12       0  4974.1    0.07       0
  4984.6    0.12       0  5820.4    0.16       0  6088.1    0.05       0
Bank Sta=4875.6,5914.8
Exp/Cntr=0.3,0.1

Type RM Length L Ch R = 1,47034,539,539,539
BEGIN DESCRIPTION:
Mapping XS b1785774
END DESCRIPTION:
XS GIS Cut Line= 3
      2800216.84      7074307.79      2799602.21      7074141.11
      2798765.53      7073969.61
#Sta/Elev= 30
  4319.5  494.93  4582.1  491.66  4697.6  488.37  4746.2  487.23  4810.6  489.36
  4845.3  486.13  4913.9  485.74  4936.4  485.37  4973.9  486.48  4984.1  482.75
  4989.1  475.82  4990.0  475.02  4999.6  475.82  5010.6  482.27  5015.7  479.82
  5024.9  482.83  5055.6  486.52  5061.1  486.29  5076.0  480.70  5086.2  480.89
  5116.8  486.37  5207.2  487.94  5290.3  488.04  5408.9  485.50  5504.6  487.66
  5545.1  486.94  5617.1  488.37  5643.3  489.06  5699.6  490.31  5810.4  493.77
#Mann=8,-1,0
  4319.5    0.05       0  4913.9    0.07       0  4936.4    0.12       0
  4989.1    0.07       0  4999.6    0.12       0  5545.1    0.16       0
  5643.3    0.12       0  5699.6    0.16       0
Bank Sta=4697.6,5617.1
Exp/Cntr=0.3,0.1

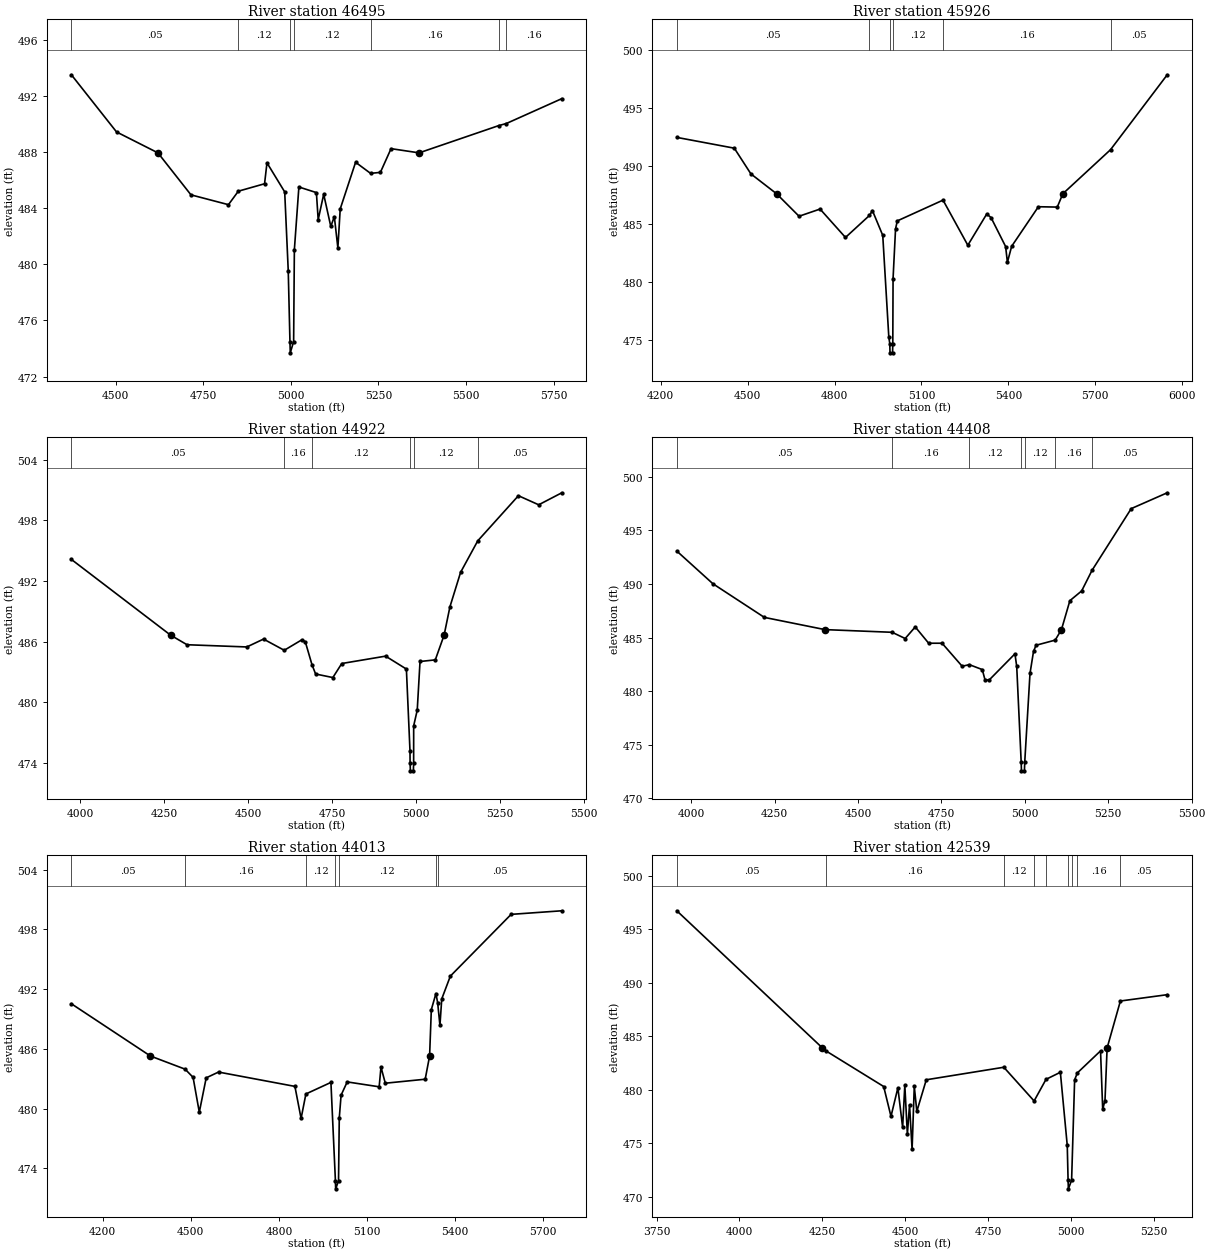
Type RM Length L Ch R = 1,46495,569,569,569
BEGIN DESCRIPTION:
XS2972A
END DESCRIPTION:
XS GIS Cut Line= 3
      2800018.88      7074172.36      2799591.79      7073823.40
      2798753.26      7073693.19
#Sta/Elev= 30
  4373.6  493.49  4502.5  489.42  4620.7  487.93  4715.0  484.94  4822.0  484.24
  4850.2  485.20  4925.1  485.73  4932.0  487.22  4982.6  485.15  4992.7  479.55
  4997.6  474.49  4998.5  473.69  5008.1  474.49  5010.2  481.03  5023.1  485.50
  5073.1  485.10  5078.2  483.17  5093.9  484.98  5114.2  482.69  5124.3  483.39
  5134.4  481.16  5141.1  483.94  5185.0  487.26  5227.7  486.47  5255.8  486.54
  5286.2  488.23  5366.3  487.93  5593.5  489.87  5615.4  490.02  5773.7  491.79
#Mann=7,-1,0
  4373.6    0.05       0  4850.2    0.12       0  4997.6    0.07       0
  5008.1    0.12       0  5227.7    0.16       0  5593.5    0.12       0
  5615.4    0.16       0
Bank Sta=4620.7,5366.3
Exp/Cntr=0.3,0.1

Type RM Length L Ch R = 1,45926,1004,1004,1004
BEGIN DESCRIPTION:
XS2973A
END DESCRIPTION:
XS GIS Cut Line= 4
      2800018.85      7074115.02      2799654.29      7073552.57
      2799487.62      7073432.77      2798821.77      7072959.39
#Sta/Elev= 30
  4255.6  492.43  4454.0  491.50  4511.4  489.28  4599.9  487.57  4677.5  485.63
  4750.0  486.25  4837.7  483.80  4920.5  485.70  4930.7  486.12  4966.3  483.98
  4987.2  475.23  4990.5  474.65  4991.4  473.85  5000.2  473.85  5001.0  474.65
  5001.9  480.25  5010.5  484.55  5016.6  485.23  5174.3  487.02  5259.9  483.13
  5325.1  485.82  5339.9  485.52  5390.3  483.02  5396.5  481.66  5411.2  483.04
  5503.4  486.45  5568.6  486.42  5587.8  487.57  5752.4  491.37  5948.1  497.83
#Mann=6,-1,0
  4255.6    0.05       0  4920.5    0.12       0  4990.5    0.07       0
  5001.0    0.12       0  5174.3    0.16       0  5752.4    0.05       0
Bank Sta=4599.9,5587.8
Exp/Cntr=0.3,0.1

Type RM Length L Ch R = 1,44922,514,514,514
BEGIN DESCRIPTION:
SCHOOLEY CREEK 39.0
END DESCRIPTION:
XS GIS Cut Line= 3
      2799975.00      7073974.99      2799775.99      7073080.00
      2799574.99      7072574.98
#Sta/Elev= 30
  3973.4  494.14  4268.8  486.64  4317.8  485.69  4495.8  485.47  4545.6  486.25
  4607.3  485.14  4659.8  486.18  4670.0  485.98  4690.0  483.70  4700.7  482.79
  4752.0  482.44  4778.6  483.83  4909.1  484.56  4971.0  483.28  4981.7  475.19
  4982.0  474.00  4982.9  473.20  4991.8  473.20  4992.6  474.00  4992.7  477.66
  5003.3  479.21  5011.6  484.03  5057.1  484.19  5083.3  486.64  5100.6  489.44
  5132.4  492.86  5183.5  495.98  5304.6  500.45  5365.0  499.55  5433.8  500.74
#Mann=6,-1,0
  3973.4    0.05       0  4607.3    0.16       0  4690.0    0.12       0
  4982.0    0.07       0  4992.6    0.12       0  5183.5    0.05       0
Bank Sta=4268.8,5083.3
Exp/Cntr=0.3,0.1

Type RM Length L Ch R = 1,44408,395,395,395
BEGIN DESCRIPTION:
XS2974A
END DESCRIPTION:
XS GIS Cut Line= 4
      2800190.75      7074016.13      2800091.79      7073010.90
      2800060.54      7072917.15      2799805.35      7072661.96
#Sta/Elev= 30
  3957.0  493.07  4065.2  490.02  4219.4  486.88  4401.0  485.74  4602.3  485.49
  4641.4  484.91  4671.6  485.99  4711.8  484.47  4752.0  484.47  4812.2  482.32
  4833.7  482.47  4872.5  482.01  4880.4  481.08  4892.6  481.02  4970.4  483.48
  4975.7  482.30  4989.1  473.36  4989.9  472.56  4998.8  472.56  4999.7  473.36
  5015.5  481.65  5026.0  483.70  5033.6  484.28  5091.0  484.76  5109.8  485.74
  5135.0  488.44  5170.3  489.35  5201.2  491.26  5318.8  497.03  5426.8  498.51
#Mann=7,-1,0
  3957.0    0.05       0  4602.3    0.16       0  4833.7    0.12       0
  4989.1    0.07       0  4999.7    0.12       0  5091.0    0.16       0
  5201.2    0.05       0
Bank Sta=4401,5109.8
Exp/Cntr=0.3,0.1

Type RM Length L Ch R = 1,44013,1474,1474,1474
BEGIN DESCRIPTION:
SCHOOLEY CREEK 38.0
END DESCRIPTION:
XS GIS Cut Line= 3
      2800852.19      7073724.41      2800340.40      7072976.32
      2799724.97      7072524.98
#Sta/Elev= 30
  4093.6  490.54  4362.8  485.29  4480.8  483.97  4507.9  483.15  4529.1  479.65
  4552.6  483.10  4594.5  483.68  4854.6  482.24  4875.6  479.02  4892.0  481.48
  4977.2  482.64  4992.5  472.75  4993.3  471.95  5003.1  472.75  5005.6  479.06
  5011.8  481.36  5032.6  482.69  5141.4  482.20  5147.6  484.18  5162.3  482.56
  5298.1  482.96  5313.1  485.29  5319.0  489.95  5334.7  491.57  5340.6  490.63
  5348.3  488.37  5354.5  491.03  5383.8  493.32  5590.7  499.52  5763.2  499.88
#Mann=7,-1,0
  4093.6    0.05       0  4480.8    0.16       0  4892.0    0.12       0
  4992.5    0.07       0  5003.1    0.12       0  5334.7    0.16       0
  5340.6    0.05       0
Bank Sta=4362.8,5313.1
Exp/Cntr=0.3,0.1

Type RM Length L Ch R = 1,42539,1311,1311,1311
BEGIN DESCRIPTION:
XS2975A
END DESCRIPTION:
XS GIS Cut Line= 3
      2801393.85      7073505.66      2800664.71      7072656.73
      2800435.51      7072380.65
#Sta/Elev= 30
  3811.1  496.71  4250.0  483.89  4261.5  483.60  4434.5  480.29  4456.5  477.50
  4477.3  480.17  4491.6  476.47  4498.2  480.42  4505.9  475.82  4512.4  478.59
  4520.1  474.41  4526.7  480.31  4534.4  477.97  4562.9  480.92  4796.5  482.09
  4887.8  478.94  4923.7  480.96  4966.9  481.62  4987.7  474.78  4990.2  471.53
  4991.1  470.73  5000.8  471.53  5009.9  480.91  5018.1  481.56  5088.0  483.62
  5094.5  478.17  5101.4  478.98  5107.8  483.89  5147.8  488.28  5289.0  488.87
#Mann=9,-1,0
  3811.1    0.05       0  4261.5    0.16       0  4796.5    0.12       0
  4887.8    0.16       0  4923.7    0.12       0  4990.2    0.07       0
  5000.8    0.12       0  5018.1    0.16       0  5147.8    0.05       0
Bank Sta=4250,5107.8
Exp/Cntr=0.3,0.1