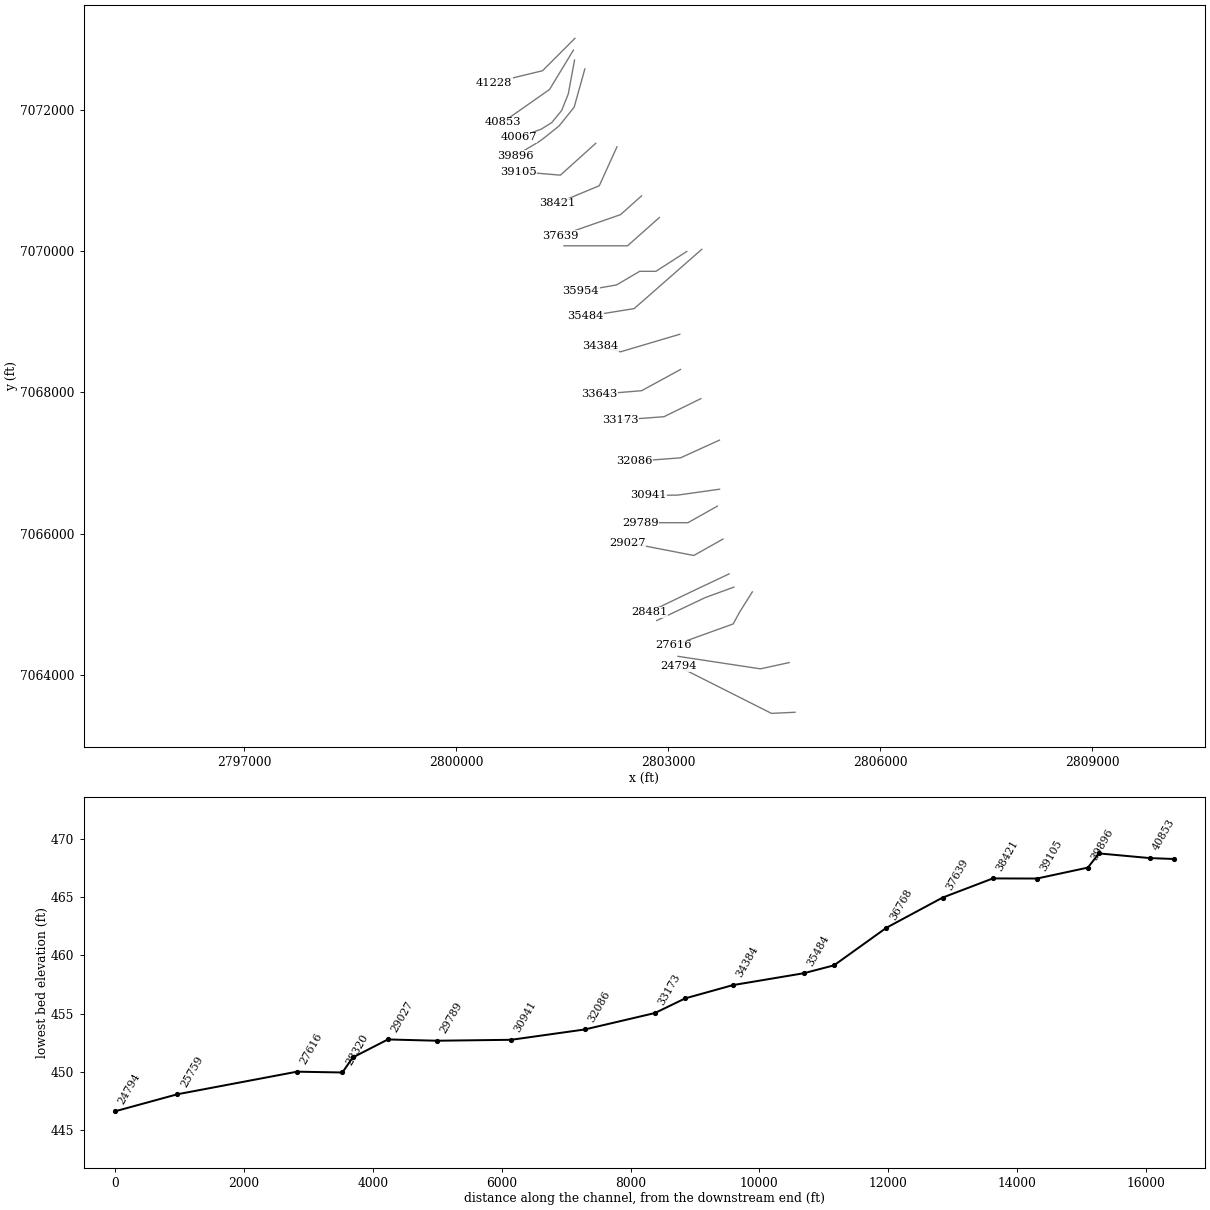
HEC-RAS study SCHOOLEY CREEK.prj: SCHOOLEY CREEK Base Level Engineering

--- SCHOOLEY CREEK.g01 (geometry) --- (continued)

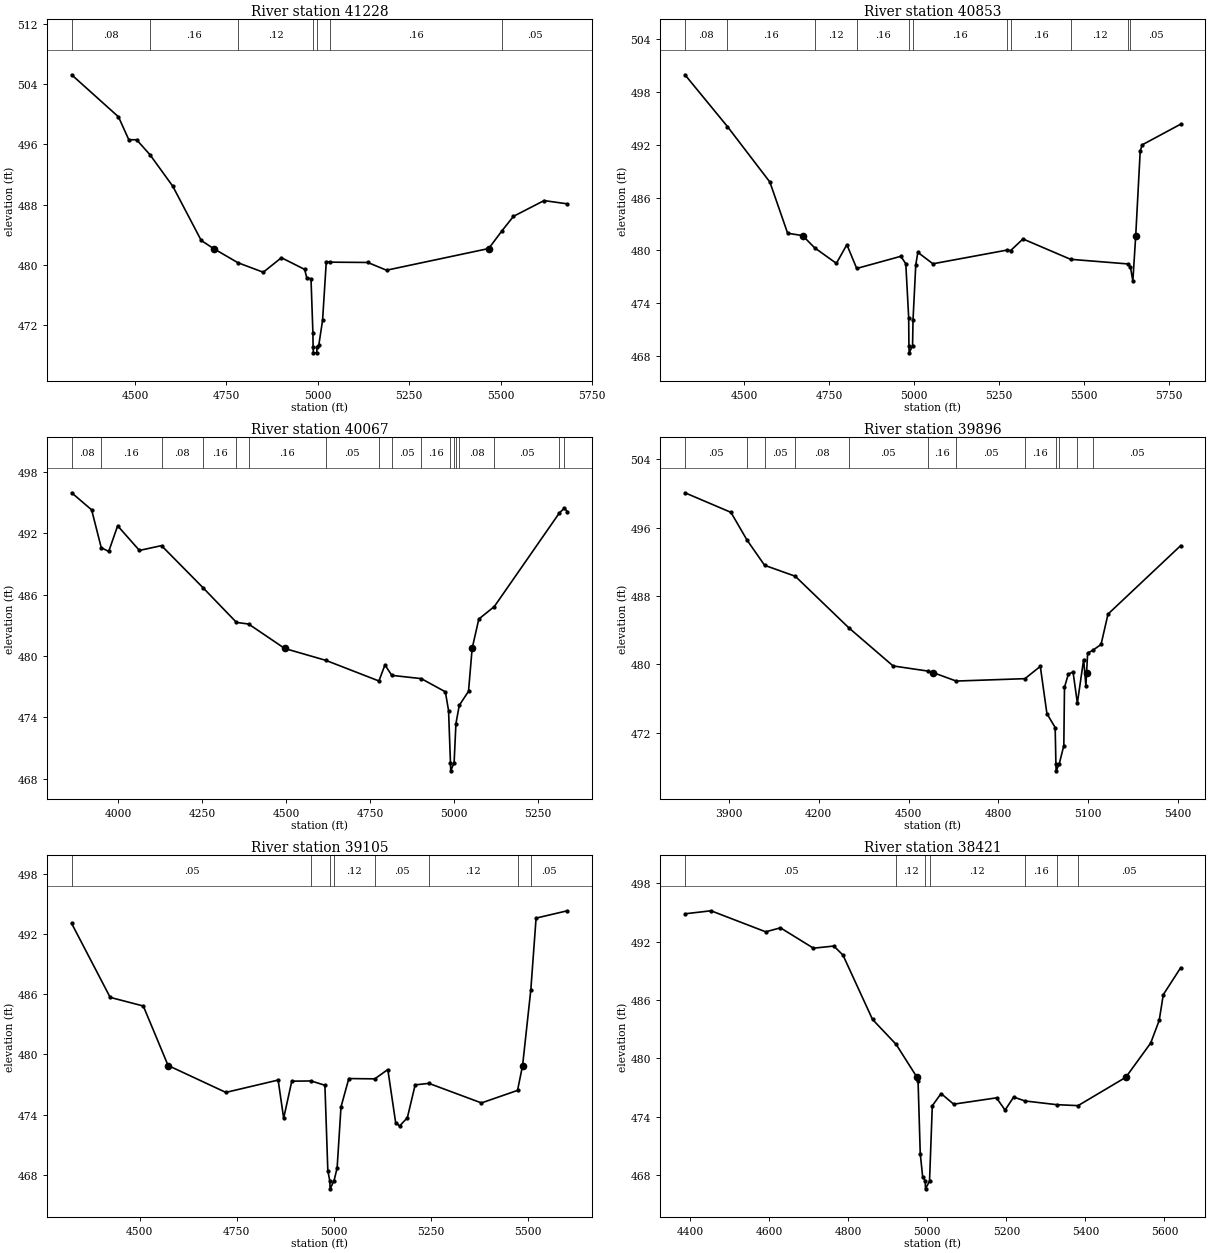
Type RM Length L Ch R = 1,41228,375,375,375
BEGIN DESCRIPTION:
XS2976A
END DESCRIPTION:
XS GIS Cut Line= 3
      2801680.30      7073010.87      2801222.00      7072552.57
      2800534.55      7072385.91
#Sta/Elev= 30
  4326.8  505.24  4454.9  499.65  4483.2  496.60  4504.4  496.61  4540.8  494.63
  4603.4  490.43  4681.2  483.22  4714.8  482.15  4781.7  480.26  4850.9  479.00
  4900.4  480.93  4964.0  479.38  4969.7  478.29  4981.4  478.12  4986.6  470.96
  4987.1  469.09  4987.9  468.29  4997.0  468.29  4997.8  469.09  5002.7  469.32
  5013.0  472.59  5023.2  480.42  5032.5  480.34  5136.5  480.30  5187.9  479.27
  5467.3  482.15  5503.4  484.49  5535.1  486.43  5618.7  488.52  5682.3  488.09
#Mann=7,-1,0
  4326.8    0.08       0  4540.8    0.16       0  4781.7    0.12       0
  4987.1    0.07       0  4997.8    0.12       0  5032.5    0.16       0
  5503.4    0.05       0
Bank Sta=4714.8,5467.3
Exp/Cntr=0.3,0.1

Type RM Length L Ch R = 1,40853,786,786,786
BEGIN DESCRIPTION:
XS2979A
END DESCRIPTION:
XS GIS Cut Line= 3
      2801659.48      7072844.21      2801320.96      7072286.94
      2800659.78      7071823.60
#Sta/Elev= 30
  4325.9  499.94  4451.0  494.06  4575.9  487.76  4628.2  481.95  4672.4  481.68
  4707.8  480.29  4771.7  478.53  4802.6  480.65  4831.6  477.95  4961.6  479.33
  4976.1  478.48  4984.6  472.38  4985.3  469.17  4986.1  468.37  4996.0  469.17
  4997.4  472.13  5005.5  478.38  5011.6  479.78  5056.0  478.48  5274.6  480.04
  5284.8  479.98  5321.1  481.30  5461.2  478.99  5631.6  478.46  5637.6  478.08
  5644.6  476.52  5653.1  481.68  5666.3  491.30  5672.4  491.99  5785.3  494.33
#Mann=11,-1,0
  4325.9    0.08       0  4451.0    0.16       0  4707.8    0.12       0
  4831.6    0.16       0  4985.3    0.07       0  4996.0    0.16       0
  5274.6    0.05       0  5284.8    0.16       0  5461.2    0.12       0
  5631.6    0.16       0  5637.6    0.05       0
Bank Sta=4672.4,5653.1
Exp/Cntr=0.3,0.1

Type RM Length L Ch R = 1,40067,171,171,171
BEGIN DESCRIPTION:
XS2977A
END DESCRIPTION:
XS GIS Cut Line= 6
      2801675.13      7072703.63      2801586.58      7072224.44
      2801492.83      7071990.07      2801352.21      7071818.19
      2801201.17      7071724.44      2800883.66      7071609.93
#Sta/Elev= 30
  3860.6  495.97  3920.2  494.30  3948.8  490.60  3971.1  490.23  3997.7  492.74
  4062.6  490.33  4128.4  490.80  4251.6  486.70  4351.8  483.29  4388.0  483.13
  4495.6  480.74  4617.9  479.58  4776.3  477.56  4794.3  479.13  4814.7  478.11
  4902.5  477.79  4974.3  476.50  4983.8  474.67  4989.5  469.57  4990.3  468.77
  5000.4  469.57  5005.8  473.39  5015.8  475.18  5043.3  476.55  5054.1  480.74
  5074.0  483.62  5120.2  484.84  5314.3  494.01  5329.1  494.47  5337.7  494.13
#Mann=17,-1,0
  3860.6    0.08       0  3948.8    0.16       0  4128.4    0.08       0
  4251.6    0.16       0  4351.8    0.08       0  4388.0    0.16       0
  4617.9    0.05       0  4776.3    0.12       0  4814.7    0.05       0
  4902.5    0.16       0  4989.5    0.07       0  5000.4    0.16       0
  5005.8    0.05       0  5015.8    0.08       0  5120.2    0.05       0
  5314.3    0.08       0  5329.1    0.05       0
Bank Sta=4495.6,5054.1
Exp/Cntr=0.3,0.1

Type RM Length L Ch R = 1,39896,791,791,791
BEGIN DESCRIPTION:
XS2978A
END DESCRIPTION:
XS GIS Cut Line= 6
      2801820.96      7072578.62      2801669.92      7072036.94
      2801456.37      7071771.32      2801248.04      7071604.65
      2801169.92      7071547.36      2800836.58      7071349.44
#Sta/Elev= 30
  3753.7  500.10  3907.1  497.81  3960.9  494.56  4019.6  491.61  4121.8  490.33
  4301.0  484.28  4448.4  479.83  4564.1  479.23  4581.1  479.06  4659.1  478.06
  4888.5  478.34  4939.8  479.78  4961.9  474.24  4989.4  472.62  4991.9  468.35
  4992.7  467.55  5002.8  468.35  5018.3  470.50  5020.5  477.33  5033.5  478.88
  5049.1  479.12  5063.5  475.48  5084.4  480.58  5092.0  477.52  5094.3  479.06
  5097.8  481.34  5114.2  481.64  5142.6  482.35  5165.8  485.90  5408.2  493.91
#Mann=12,-1,0
  3753.7    0.05       0  3960.9    0.08       0  4019.6    0.05       0
  4121.8    0.08       0  4301.0    0.05       0  4564.1    0.16       0
  4659.1    0.05       0  4888.5    0.16       0  4991.9    0.04       0
  5002.8    0.16       0  5063.5    0.16       0  5114.2    0.05       0
Bank Sta=4581.1,5094.3
Exp/Cntr=0.3,0.1

Type RM Length L Ch R = 1,39105,684,684,684
BEGIN DESCRIPTION:
SCHOOLEY CREEK 33.0
END DESCRIPTION:
XS GIS Cut Line= 3
      2801975.03      7071525.03      2801475.00      7071075.00
      2800875.01      7071125.00
#Sta/Elev= 30
  4325.4  493.06  4424.5  485.69  4509.7  484.83  4573.5  478.90  4722.0  476.22
  4856.5  477.45  4870.7  473.65  4891.6  477.34  4941.6  477.36  4976.8  476.93
  4984.3  468.42  4989.3  467.41  4990.1  466.61  5000.2  467.41  5008.2  468.69
  5018.2  474.78  5038.3  477.60  5105.1  477.57  5138.6  478.50  5158.7  473.22
  5168.7  472.87  5188.8  473.69  5208.9  476.97  5244.2  477.12  5379.4  475.17
  5472.2  476.42  5485.2  478.90  5506.3  486.42  5519.9  493.59  5600.2  494.32
#Mann=8,-1,0
  4325.4    0.05       0  4941.6    0.12       0  4989.3    0.07       0
  5000.2    0.12       0  5105.1    0.05       0  5244.2    0.12       0
  5472.2    0.16       0  5506.3    0.05       0
Bank Sta=4573.5,5485.2
Exp/Cntr=0.3,0.1

Type RM Length L Ch R = 1,38421,782,782,782
BEGIN DESCRIPTION:
SCHOOLEY CREEK 32.0
END DESCRIPTION:
XS GIS Cut Line= 3
      2802274.98      7071474.97      2802025.00      7070925.00
      2801425.01      7070675.01
#Sta/Elev= 30
  4386.8  494.85  4452.7  495.16  4591.1  493.00  4628.4  493.41  4711.9  491.32
  4763.5  491.54  4786.6  490.61  4861.3  484.01  4921.2  481.44  4973.9  478.07
  4976.6  477.65  4982.1  470.23  4988.2  467.86  4994.7  467.42  4995.4  466.62
  5005.6  467.42  5012.6  475.15  5034.8  476.40  5066.7  475.31  5175.1  475.96
  5196.7  474.70  5218.4  476.04  5247.1  475.64  5327.1  475.26  5381.4  475.16
  5502.2  478.07  5565.1  481.58  5586.7  483.91  5597.0  486.55  5640.9  489.31
#Mann=7,-1,0
  4386.8    0.05       0  4921.2    0.12       0  4994.7    0.07       0
  5005.6    0.12       0  5247.1    0.16       0  5327.1    0.12       0
  5381.4    0.05       0
Bank Sta=4973.9,5502.2
Exp/Cntr=0.3,0.1

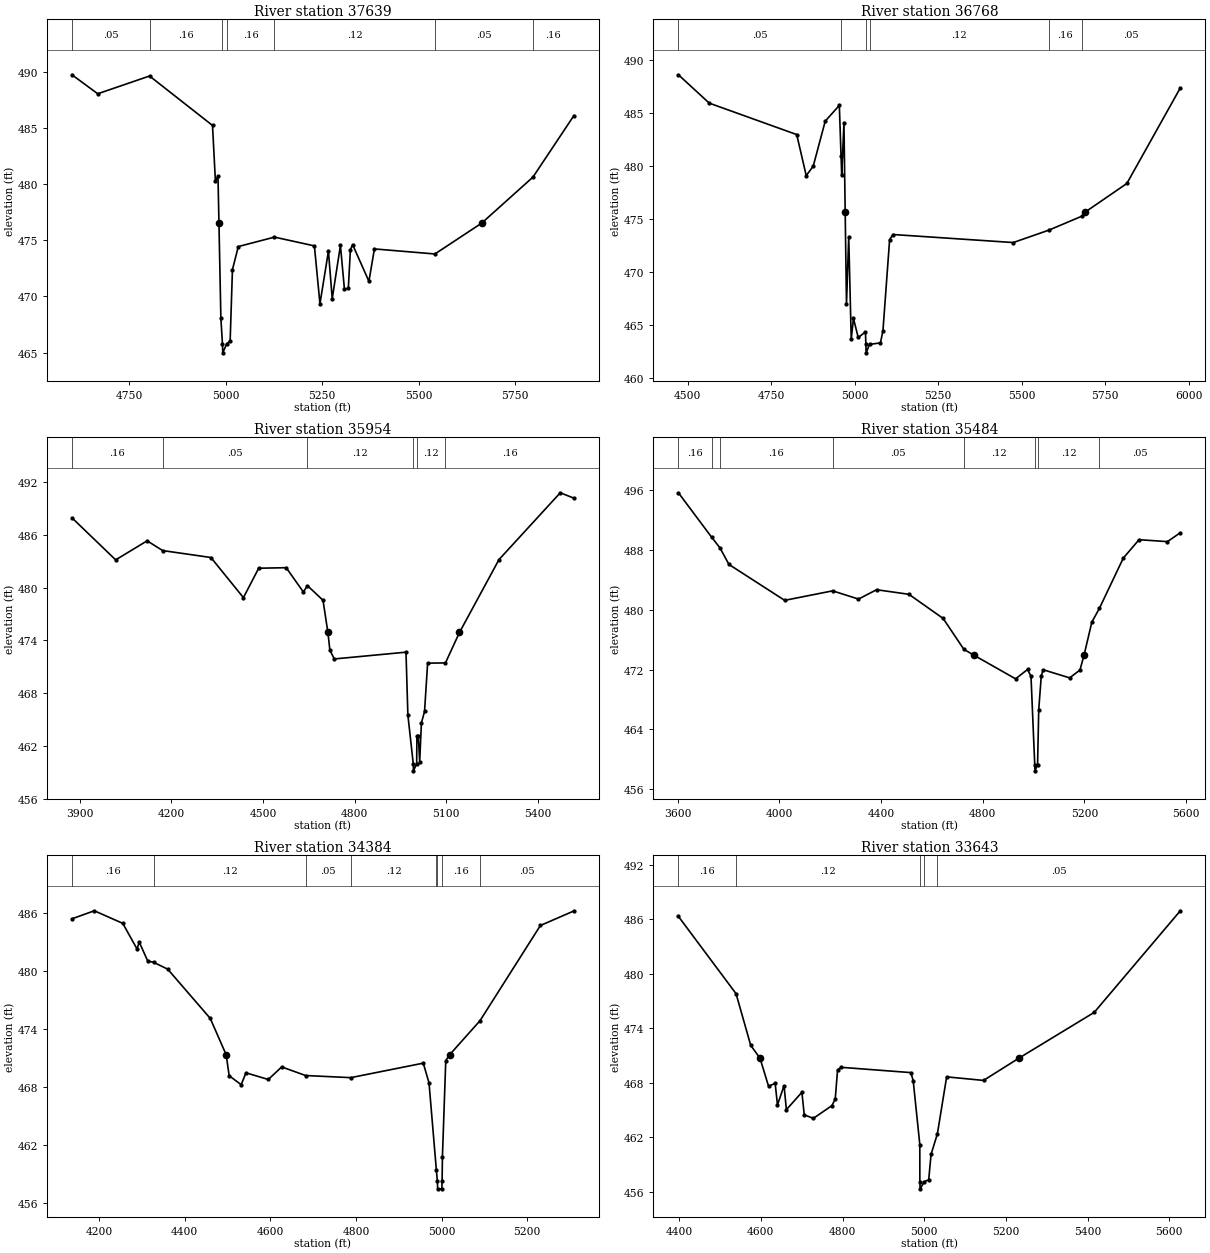
Type RM Length L Ch R = 1,37639,871,871,871
BEGIN DESCRIPTION:
XS2980A
END DESCRIPTION:
XS GIS Cut Line= 3
      2802623.04      7070781.74      2802326.17      7070516.11
      2801473.09      7070219.61
#Sta/Elev= 30
  4600.8  489.72  4667.7  488.03  4802.0  489.61  4965.3  485.21  4972.8  480.26
  4979.5  480.71  4982.0  476.51  4987.0  468.03  4991.1  465.77  4991.9  464.97
  5002.1  465.77  5011.0  466.01  5017.0  472.38  5032.2  474.43  5125.9  475.27
  5229.5  474.49  5243.9  469.34  5265.9  474.02  5275.7  469.79  5297.0  474.53
  5307.4  470.63  5317.5  470.72  5322.8  474.14  5328.6  474.60  5370.9  471.34
  5385.1  474.22  5542.0  473.77  5663.1  476.51  5796.2  480.61  5902.3  486.08
#Mann=7,-1,0
  4600.8    0.05       0  4802.0    0.16       0  4991.1    0.07       0
  5002.1    0.16       0  5125.9    0.12       0  5542.0    0.05       0
  5796.2    0.16       0
Bank Sta=4982,5663.1
Exp/Cntr=0.3,0.1

Type RM Length L Ch R = 1,36768,814,814,814
BEGIN DESCRIPTION:
SCHOOLEY CREEK 30.0
END DESCRIPTION:
XS GIS Cut Line= 3
      2802874.98      7070474.98      2802425.00      7070075.00
      2801524.95      7070075.00
#Sta/Elev= 30
  4472.2  488.65  4564.6  485.97  4826.3  483.00  4854.7  479.12  4875.7  480.02
  4911.6  484.27  4953.8  485.76  4958.9  481.00  4960.9  479.14  4967.6  484.12
  4971.3  475.68  4975.2  466.95  4981.9  473.36  4989.4  463.67  4996.1  465.63
  5010.3  463.83  5032.0  464.35  5033.2  463.18  5034.0  462.38  5044.2  463.18
  5076.8  463.32  5084.3  464.46  5104.3  473.08  5114.3  473.56  5474.3  472.80
  5580.6  473.97  5679.7  475.29  5689.7  475.68  5814.3  478.38  5974.3  487.41
#Mann=6,-1,0
  4472.2    0.05       0  4958.9    0.12       0  5033.2    0.07       0
  5044.2    0.12       0  5580.6    0.16       0  5679.7    0.05       0
Bank Sta=4971.3,5689.7
Exp/Cntr=0.3,0.1

Type RM Length L Ch R = 1,35954,470,470,470
BEGIN DESCRIPTION:
XS2981A
END DESCRIPTION:
XS GIS Cut Line= 5
      2803263.63      7069995.25      2802826.17      7069714.02
      2802597.00      7069714.02      2802268.87      7069521.32
      2801763.63      7069432.77
#Sta/Elev= 30
  3874.8  487.96  4017.9  483.17  4120.9  485.34  4171.6  484.23  4329.6  483.44
  4436.0  478.87  4486.0  482.22  4576.0  482.28  4632.1  479.52  4645.7  480.23
  4696.5  478.57  4712.5  474.91  4719.1  472.87  4733.6  471.89  4968.1  472.66
  4974.3  465.49  4991.9  459.95  4992.6  459.15  5003.0  459.95  5003.9  463.13
  5008.4  463.13  5012.9  460.19  5018.6  464.61  5028.8  465.91  5038.9  471.41
  5097.3  471.44  5143.2  474.91  5272.4  483.20  5473.0  490.81  5517.5  490.20
#Mann=6,-1,0
  3874.8    0.16       0  4171.6    0.05       0  4645.7    0.12       0
  4991.9    0.07       0  5003.0    0.12       0  5097.3    0.16       0
Bank Sta=4712.5,5143.2
Exp/Cntr=0.3,0.1

Type RM Length L Ch R = 1,35484,1100,1100,1100
BEGIN DESCRIPTION:
SCHOOLEY CREEK 28.0
END DESCRIPTION:
XS GIS Cut Line= 3
      2803475.00      7070025.00      2802518.83      7069186.36
      2801825.04      7069075.01
#Sta/Elev= 30
  3602.8  495.64  3733.0  489.72  3766.0  488.29  3801.6  486.06  4020.8  481.26
  4209.4  482.53  4311.2  481.43  4382.4  482.68  4509.5  482.07  4644.3  478.84
  4725.8  474.71  4766.2  473.91  4929.2  470.77  4976.3  472.02  4989.9  471.10
  5004.6  459.27  5005.3  458.47  5015.7  459.27  5020.3  466.65  5030.4  471.21
  5038.2  471.98  5141.8  470.90  5182.4  471.94  5198.4  473.91  5229.1  478.34
  5259.2  480.21  5353.0  486.91  5414.9  489.37  5526.7  489.11  5577.3  490.30
#Mann=8,-1,0
  3602.8    0.16       0  3733.0    0.05       0  3766.0    0.16       0
  4209.4    0.05       0  4725.8    0.12       0  5004.6    0.07       0
  5015.7    0.12       0  5259.2    0.05       0
Bank Sta=4766.2,5198.4
Exp/Cntr=0.3,0.1

Type RM Length L Ch R = 1,34384,741,741,741
BEGIN DESCRIPTION:
SCHOOLEY CREEK 27.0
END DESCRIPTION:
XS GIS Cut Line= 3
      2803164.74      7068823.41      2802325.00      7068575.00
      2802039.88      7068656.68
#Sta/Elev= 30
  4136.6  485.38  4188.8  486.21  4255.3  484.91  4288.6  482.26  4293.8  482.97
  4313.6  481.01  4327.3  480.88  4360.3  480.17  4459.6  475.08  4496.8  471.32
  4503.8  469.15  4531.9  468.22  4543.0  469.45  4595.2  468.76  4626.5  470.06
  4682.4  469.17  4787.9  468.95  4957.2  470.45  4970.6  468.41  4987.8  459.37
  4990.1  458.25  4990.8  457.45  5000.5  457.45  5001.2  458.25  5001.9  460.73
  5009.7  470.71  5018.8  471.32  5089.7  474.84  5230.8  484.69  5308.9  486.19
#Mann=8,-1,0
  4136.6    0.16       0  4327.3    0.12       0  4682.4    0.05       0
  4787.9    0.12       0  4987.8    0.16       0  4990.1    0.07       0
  5001.2    0.16       0  5089.7    0.05       0
Bank Sta=4496.8,5018.8
Exp/Cntr=0.3,0.1

Type RM Length L Ch R = 1,33643,470,470,470
BEGIN DESCRIPTION:
SCHOOLEY CREEK 26.0
END DESCRIPTION:
XS GIS Cut Line= 3
      2803174.98      7068324.99      2802625.00      7068025.00
      2802024.95      7067975.00
#Sta/Elev= 30
  4398.3  486.31  4539.4  477.80  4575.3  472.11  4598.1  470.69  4619.0  467.60
  4635.1  467.93  4640.8  465.55  4656.9  467.68  4662.6  465.03  4700.6  466.94
  4706.3  464.46  4728.6  464.07  4774.2  465.48  4782.2  466.21  4787.9  469.41
  4797.0  469.69  4967.3  469.11  4973.0  468.22  4989.2  461.19  4989.3  457.11
  4990.0  456.31  5000.5  457.11  5011.0  457.31  5016.7  460.10  5032.2  462.36
  5054.9  468.64  5145.2  468.25  5231.4  470.69  5416.1  475.74  5626.9  486.93
#Mann=5,-1,0
  4398.3    0.16       0  4539.4    0.12       0  4989.3    0.07       0
  5000.5    0.12       0  5032.2    0.05       0
Bank Sta=4598.1,5231.4
Exp/Cntr=0.3,0.1

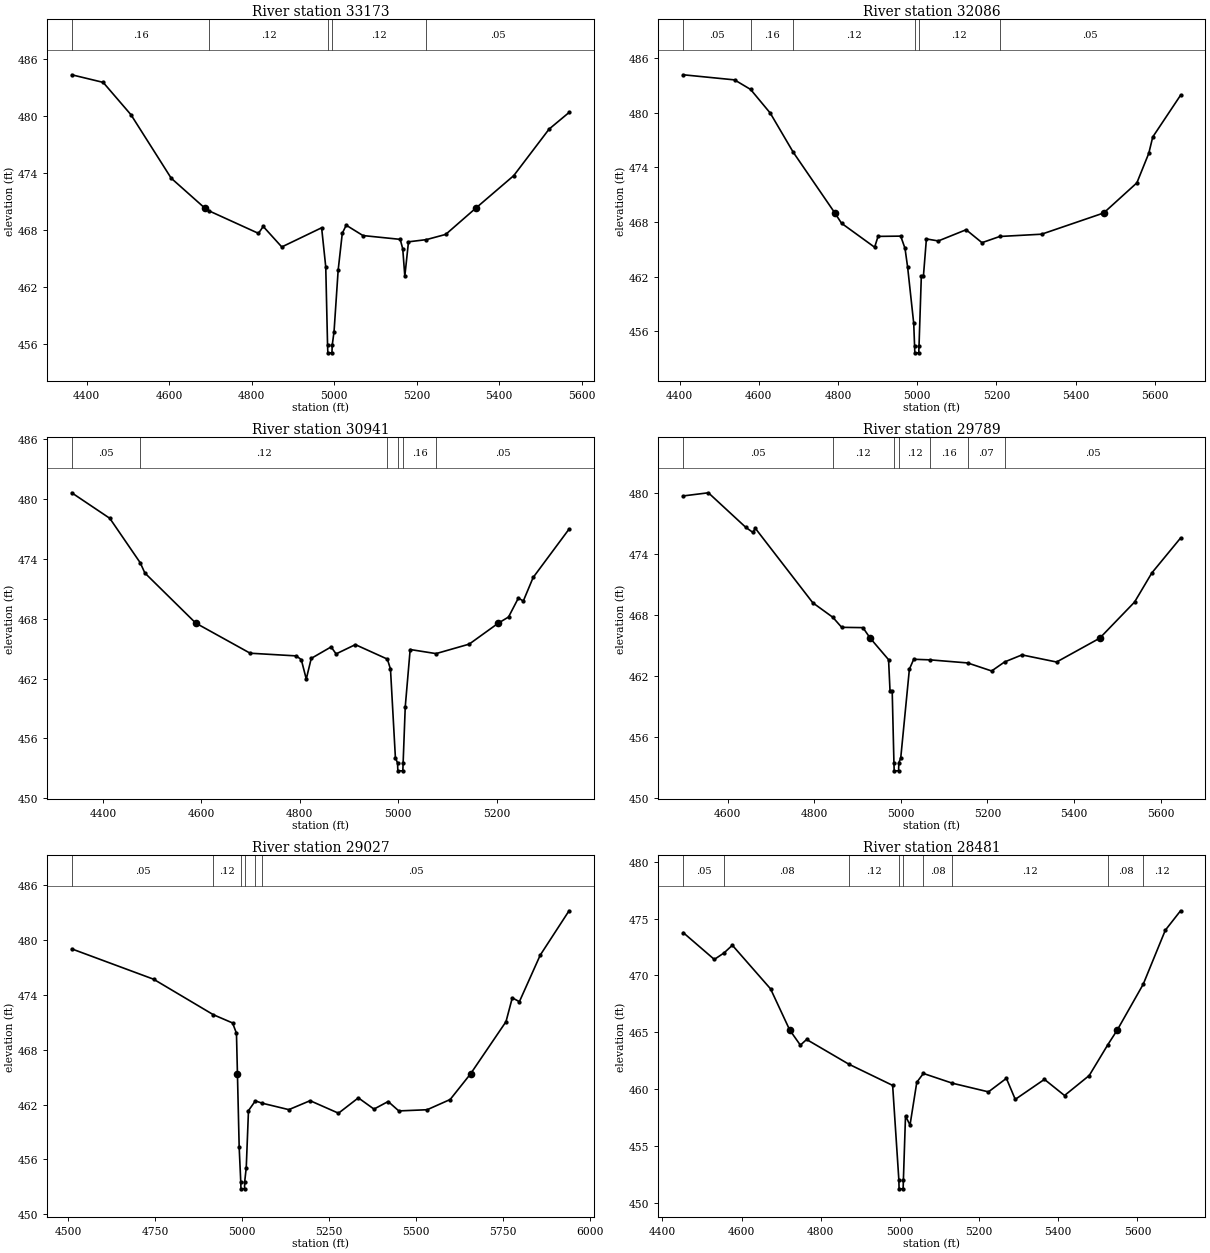
Type RM Length L Ch R = 1,33173,1087,1087,1087
BEGIN DESCRIPTION:
XS2982A
END DESCRIPTION:
XS GIS Cut Line= 3
      2803461.63      7067911.96      2802940.75      7067656.73
      2802316.75      7067609.93
#Sta/Elev= 30
  4363.5  484.33  4439.7  483.53  4507.2  480.12  4604.7  473.44  4687.0  470.26
  4697.4  469.98  4816.3  467.63  4827.8  468.36  4872.8  466.20  4969.4  468.22
  4979.4  464.10  4983.8  455.85  4984.5  455.05  4994.4  455.05  4995.1  455.85
  4999.5  457.28  5009.5  463.76  5019.5  467.64  5029.0  468.49  5069.6  467.40
  5159.9  467.00  5166.1  466.00  5171.1  463.12  5180.0  466.74  5223.2  466.97
  5270.2  467.52  5342.5  470.26  5435.2  473.71  5520.9  478.61  5569.3  480.36
#Mann=5,-1,0
  4363.5    0.16       0  4697.4    0.12       0  4983.8    0.07       0
  4995.1    0.12       0  5223.2    0.05       0
Bank Sta=4687,5342.5
Exp/Cntr=0.3,0.1

Type RM Length L Ch R = 1,32086,1145,1145,1145
BEGIN DESCRIPTION:
SCHOOLEY CREEK 24.0
END DESCRIPTION:
XS GIS Cut Line= 3
      2803725.03      7067325.01      2803175.00      7067075.00
      2802525.00      7067025.00
#Sta/Elev= 30
  4409.0  484.18  4538.6  483.62  4579.2  482.57  4628.7  479.98  4686.9  475.67
  4792.0  469.00  4808.9  467.87  4892.4  465.24  4901.1  466.43  4958.3  466.46
  4969.2  465.11  4975.8  463.05  4991.2  456.87  4993.3  454.44  4994.0  453.64
  5003.9  453.64  5004.6  454.44  5010.4  462.07  5015.7  462.07  5023.2  466.15
  5053.3  465.93  5123.5  467.16  5163.6  465.74  5208.5  466.42  5314.1  466.67
  5470.9  469.00  5554.8  472.31  5584.9  475.56  5594.9  477.35  5665.1  481.93
#Mann=6,-1,0
  4409.0    0.05       0  4579.2    0.16       0  4686.9    0.12       0
  4993.3    0.07       0  5004.6    0.12       0  5208.5    0.05       0
Bank Sta=4792,5470.9
Exp/Cntr=0.3,0.1

Type RM Length L Ch R = 1,30941,1152,1152,1152
BEGIN DESCRIPTION:
XS2983A
END DESCRIPTION:
XS GIS Cut Line= 3
      2803727.18      7066630.69      2803133.46      7066547.36
      2802722.03      7066542.15
#Sta/Elev= 30
  4336.4  480.62  4413.8  478.06  4475.6  473.61  4485.1  472.58  4588.5  467.56
  4699.1  464.54  4793.0  464.27  4803.1  463.89  4813.2  461.95  4823.3  464.02
  4863.7  465.17  4873.8  464.47  4913.0  465.40  4978.0  463.95  4984.4  462.95
  4994.4  454.05  4998.7  453.55  4999.4  452.75  5009.5  452.75  5010.1  453.55
  5014.4  459.16  5024.4  464.91  5077.0  464.50  5144.4  465.45  5203.8  467.56
  5224.4  468.17  5244.4  470.07  5254.4  469.77  5274.4  472.13  5347.4  476.98
#Mann=6,-1,0
  4336.4    0.05       0  4475.6    0.12       0  4978.0    0.16       0
  4998.7    0.07       0  5010.1    0.16       0  5077.0    0.05       0
Bank Sta=4588.5,5203.8
Exp/Cntr=0.3,0.1

Type RM Length L Ch R = 1,29789,762,762,762
BEGIN DESCRIPTION:
XS2984A
END DESCRIPTION:
XS GIS Cut Line= 3
      2803695.97      7066391.12      2803279.29      7066156.73
      2802608.67      7066156.73
#Sta/Elev= 30
  4497.2  479.70  4555.3  480.01  4642.0  476.60  4657.9  476.12  4663.7  476.52
  4796.6  469.19  4842.7  467.77  4863.2  466.78  4912.3  466.75  4929.2  465.71
  4971.5  463.60  4974.9  460.50  4979.9  460.50  4983.9  453.47  4984.5  452.67
  4994.6  452.67  4995.3  453.47  4999.6  453.93  5019.6  462.67  5029.6  463.64
  5068.1  463.58  5154.0  463.28  5209.6  462.49  5239.6  463.38  5279.6  464.07
  5359.6  463.37  5459.1  465.71  5539.6  469.26  5579.6  472.13  5645.9  475.56
#Mann=7,-1,0
  4497.2    0.05       0  4842.7    0.12       0  4983.9    0.07       0
  4995.3    0.12       0  5068.1    0.16       0  5154.0    0.07       0
  5239.6    0.05       0
Bank Sta=4929.2,5459.1
Exp/Cntr=0.3,0.1

Type RM Length L Ch R = 1,29027,546,546,546
BEGIN DESCRIPTION:
SCHOOLEY CREEK 21.0
END DESCRIPTION:
XS GIS Cut Line= 3
      2803775.04      7065925.02      2803362.62      7065693.19
      2802425.00      7065875.00
#Sta/Elev= 30
  4511.0  479.05  4746.0  475.73  4917.8  471.84  4972.9  470.94  4984.1  469.81
  4986.9  465.36  4991.9  457.32  4996.4  453.58  4997.0  452.78  5007.2  452.78
  5007.8  453.58  5012.2  455.10  5018.6  461.34  5038.3  462.41  5057.4  462.16
  5134.5  461.45  5195.6  462.43  5277.1  461.06  5334.1  462.74  5379.0  461.51
  5419.7  462.34  5450.3  461.31  5531.7  461.44  5597.8  462.56  5656.2  465.36
  5758.1  471.08  5776.2  473.69  5796.6  473.27  5856.5  478.37  5939.2  483.22
#Mann=6,-1,0
  4511.0    0.05       0  4917.8    0.12       0  4996.4    0.07       0
  5007.8    0.12       0  5038.3    0.07       0  5057.4    0.05       0
Bank Sta=4986.9,5656.2
Exp/Cntr=0.3,0.1

Type RM Length L Ch R = 1,28481,161,161,161
BEGIN DESCRIPTION:
XS2985A
END DESCRIPTION:
XS GIS Cut Line= 3
      2803862.66      7065432.79      2803388.67      7065208.82
      2802728.60      7064891.78
#Sta/Elev= 30
  4452.4  473.77  4531.0  471.41  4555.8  471.99  4576.5  472.66  4673.1  468.82
  4721.5  465.20  4748.4  463.87  4764.1  464.37  4870.6  462.20  4981.5  460.33
  4997.2  452.03  4997.8  451.23  5008.0  451.23  5008.7  452.03  5014.0  457.64
  5025.4  456.84  5042.5  460.60  5059.1  461.38  5132.6  460.52  5223.6  459.76
  5268.9  460.95  5291.3  459.10  5365.0  460.86  5415.8  459.44  5478.2  461.20
  5525.2  463.91  5549.0  465.20  5614.6  469.23  5670.4  473.98  5708.9  475.69
#Mann=9,-1,0
  4452.4    0.05       0  4555.8    0.08       0  4870.6    0.12       0
  4997.2    0.07       0  5008.7    0.12       0  5059.1    0.08       0
  5132.6    0.12       0  5525.2    0.08       0  5614.6    0.12       0
Bank Sta=4721.5,5549
Exp/Cntr=0.3,0.1

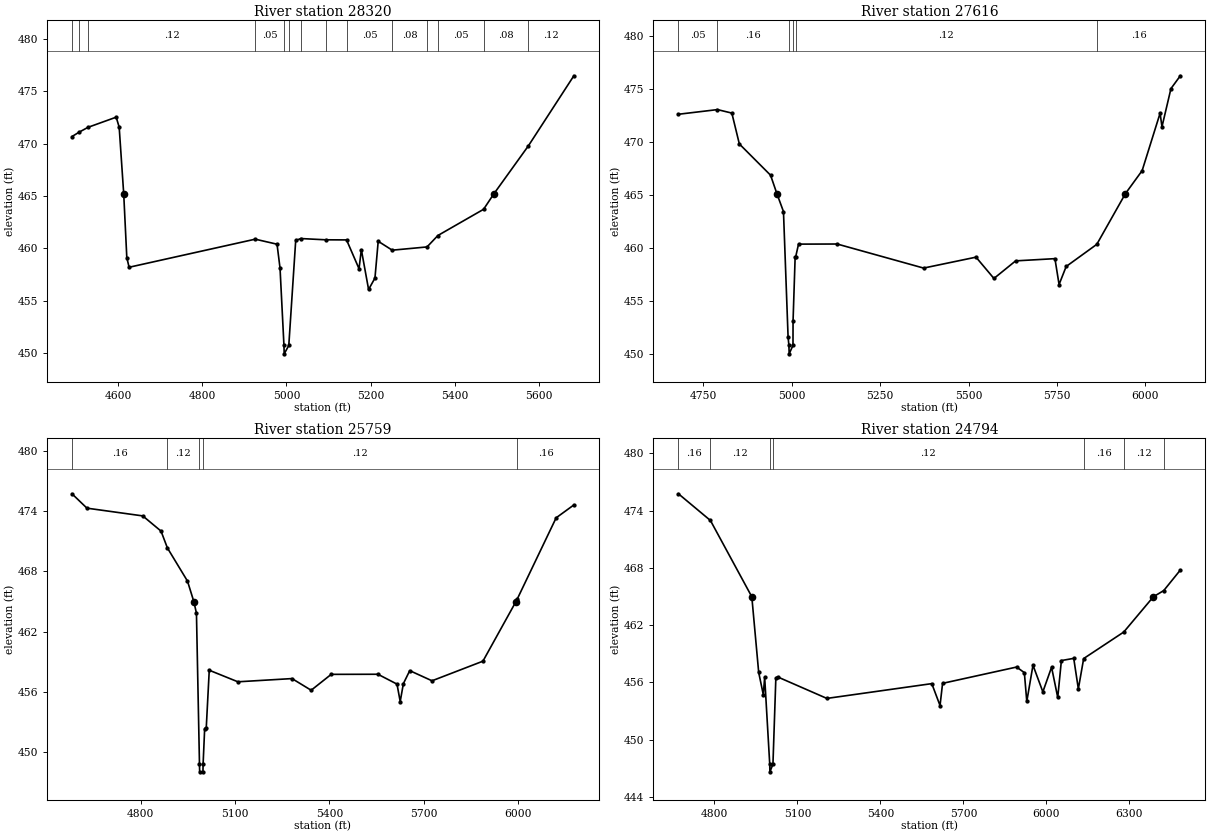
Type RM Length L Ch R = 1,28320,704,704,704
BEGIN DESCRIPTION:
XS2986A
END DESCRIPTION:
XS GIS Cut Line= 3
      2803930.32      7065245.27      2803529.29      7065099.44
      2802838.31      7064772.13
#Sta/Elev= 30
  4490.9  470.67  4507.5  471.08  4528.9  471.55  4595.9  472.52  4603.0  471.57
  4613.8  465.18  4621.1  459.13  4626.5  458.20  4925.9  460.88  4977.7  460.40
  4984.8  458.12  4994.1  450.74  4994.7  449.94  5005.6  450.74  5022.0  460.76
  5034.3  460.94  5093.2  460.82  5142.7  460.81  5172.3  458.06  5177.8  459.88
  5195.0  456.08  5210.1  457.17  5217.8  460.68  5251.1  459.83  5333.7  460.14
  5359.5  461.23  5467.9  463.73  5491.9  465.18  5574.2  469.78  5682.2  476.47
#Mann=14,-1,0
  4490.9    0.08       0  4507.5    0.05       0  4528.9    0.12       0
  4925.9    0.05       0  4994.1    0.04       0  5005.6    0.05       0
  5034.3    0.08       0  5093.2    0.12       0  5142.7    0.05       0
  5251.1    0.08       0  5333.7    0.12       0  5359.5    0.05       0
  5467.9    0.08       0  5574.2    0.12       0
Bank Sta=4613.8,5491.9
Exp/Cntr=0.3,0.1

Type RM Length L Ch R = 1,27616,1857,1857,1857
BEGIN DESCRIPTION:
XS2987A
END DESCRIPTION:
XS GIS Cut Line= 4
      2804190.72      7065177.53      2804013.67      7064896.32
      2803919.92      7064724.44      2803081.36      7064422.35
#Sta/Elev= 30
  4679.6  472.61  4790.1  473.05  4830.7  472.72  4851.9  469.81  4940.2  466.86
  4958.1  465.12  4976.7  463.43  4989.8  451.56  4992.1  450.81  4992.8  450.01
  5003.6  450.81  5003.8  453.10  5009.7  459.13  5011.0  459.13  5019.3  460.36
  5128.5  460.37  5373.0  458.10  5521.2  459.13  5571.9  457.12  5633.3  458.78
  5744.4  458.99  5756.1  456.55  5776.2  458.25  5862.8  460.34  5943.7  465.12
  5991.0  467.29  6041.8  472.71  6047.1  471.43  6072.5  475.03  6099.0  476.24
#Mann=6,-1,0
  4679.6    0.05       0  4790.1    0.16       0  4992.1    0.07       0
  5003.6    0.16       0  5011.0    0.12       0  5862.8    0.16       0
Bank Sta=4958.1,5943.7
Exp/Cntr=0.3,0.1

Type RM Length L Ch R = 1,25759,965,965,965
BEGIN DESCRIPTION:
XS2988A
END DESCRIPTION:
XS GIS Cut Line= 3
      2804711.61      7064177.57      2804305.33      7064089.02
      2803139.31      7064266.01
#Sta/Elev= 30
  4581.5  475.71  4629.2  474.28  4806.6  473.51  4864.6  472.00  4884.8  470.33
  4948.7  467.03  4968.9  464.99  4977.2  463.84  4986.8  448.87  4987.4  448.07
  4997.8  448.07  4998.4  448.87  5003.3  452.37  5008.3  452.40  5017.9  458.17
  5108.9  457.02  5280.9  457.34  5341.8  456.18  5405.5  457.76  5554.0  457.77
  5614.6  456.79  5624.8  455.06  5634.9  456.84  5655.1  458.13  5725.9  457.12
  5887.7  459.07  5992.6  464.99  5997.3  465.28  6120.4  473.32  6176.7  474.60
#Mann=5,-1,0
  4581.5    0.16       0  4884.8    0.12       0  4986.8    0.07       0
  4998.4    0.12       0  5997.3    0.16       0
Bank Sta=4968.9,5992.6
Exp/Cntr=0.3,0.1

Type RM Length L Ch R = 1,24794,768,768,768
BEGIN DESCRIPTION:
XS2989A
END DESCRIPTION:
XS GIS Cut Line= 3
      2804794.88      7063474.44      2804461.58      7063458.82
      2803139.35      7064125.14
#Sta/Elev= 30
  4669.8  475.77  4785.5  472.97  4935.1  464.97  4960.0  457.03  4976.6  454.71
  4981.6  456.52  4999.9  447.41  5000.5  446.61  5011.5  447.41  5022.0  456.44
  5028.0  456.57  5206.4  454.31  5585.7  455.86  5615.5  453.56  5624.7  455.89
  5892.4  457.60  5920.3  457.01  5929.1  453.99  5951.5  457.79  5987.2  455.00
  6018.7  457.58  6041.0  454.41  6054.2  458.28  6098.8  458.51  6115.5  455.31
  6134.7  458.49  6279.6  461.27  6386.7  464.97  6424.2  465.62  6484.1  467.77
#Mann=7,-1,0
  4669.8    0.16       0  4785.5    0.12       0  4999.9    0.07       0
  5011.5    0.12       0  6134.7    0.16       0  6279.6    0.12       0
  6424.2    0.16       0
Bank Sta=4935.1,6386.7
Exp/Cntr=0.3,0.1