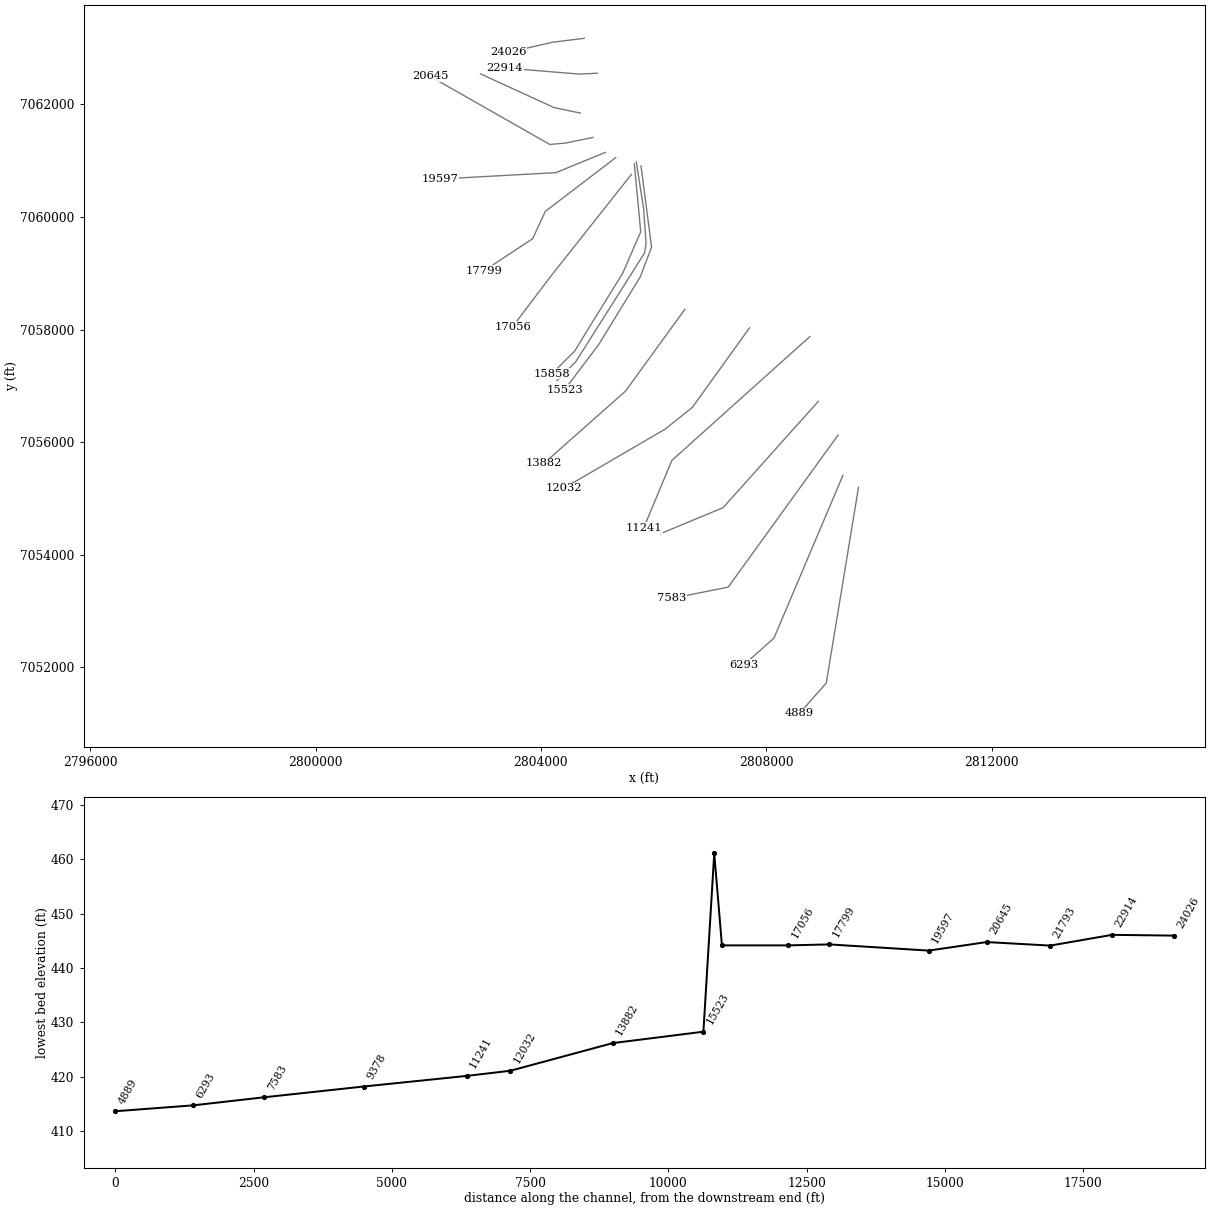
HEC-RAS study SCHOOLEY CREEK.prj: SCHOOLEY CREEK Base Level Engineering

--- SCHOOLEY CREEK.g01 (geometry) --- (continued)

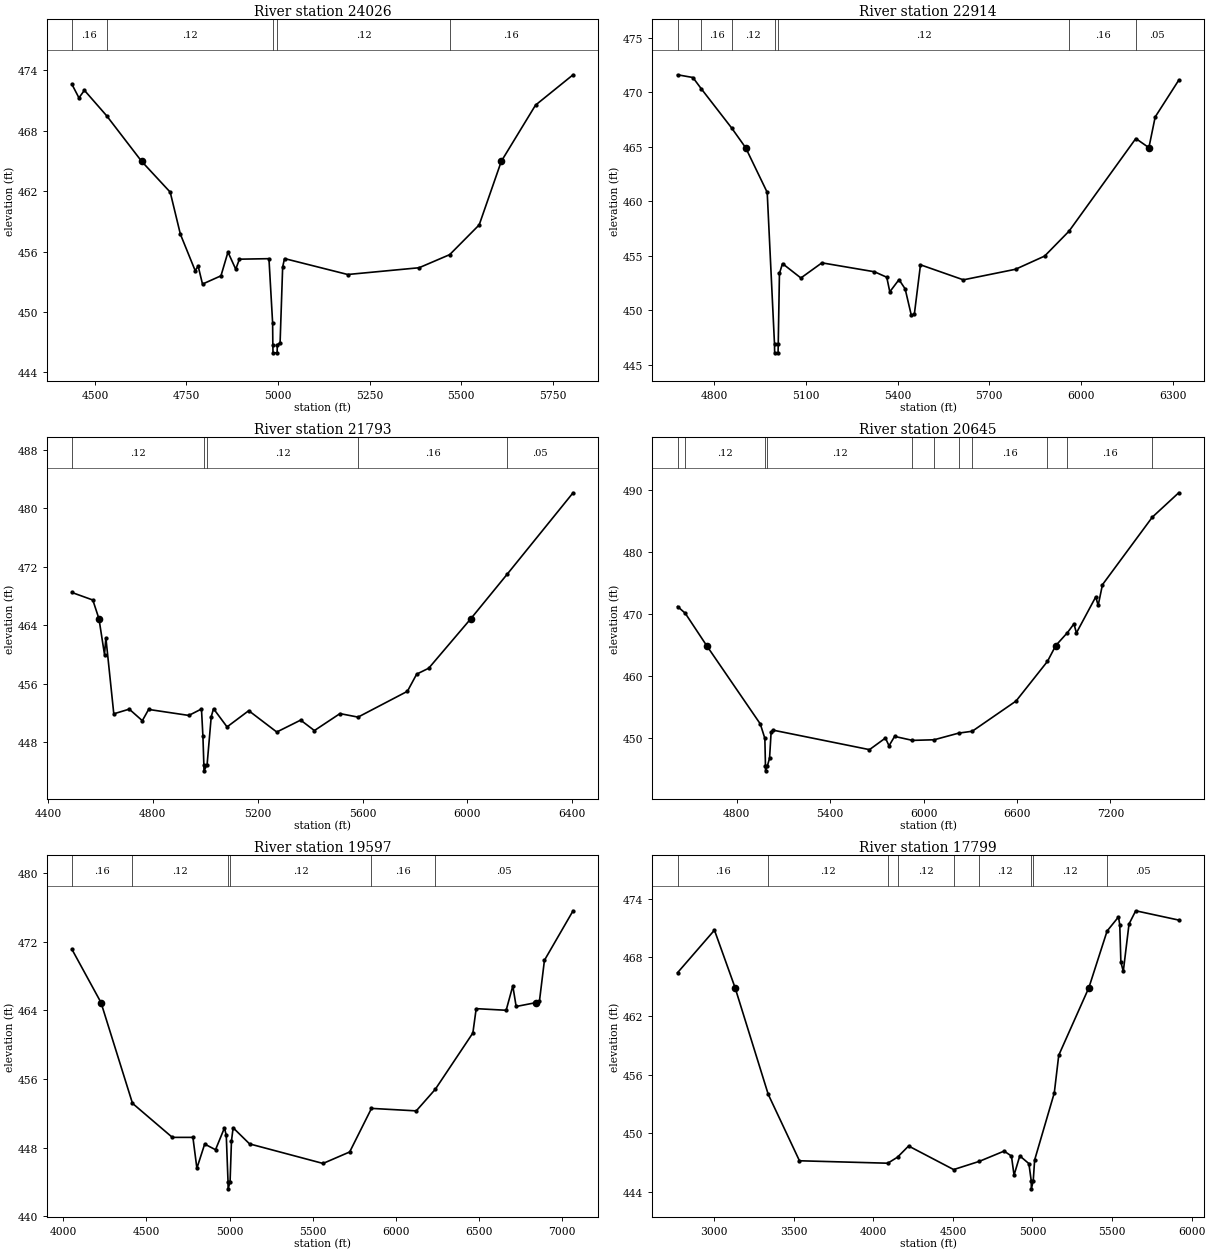
Type RM Length L Ch R = 1,24026,1112,1112,1112
BEGIN DESCRIPTION:
SCHOOLEY CREEK 16.0
END DESCRIPTION:
XS GIS Cut Line= 3
      2804768.85      7063172.35      2804216.79      7063104.65
      2803425.01      7062925.00
#Sta/Elev= 30
  4437.3  472.59  4456.5  471.24  4471.4  471.99  4531.8  469.48  4627.5  464.95
  4705.6  461.89  4733.4  457.72  4773.7  454.11  4782.0  454.54  4793.8  452.77
  4844.2  453.59  4863.3  455.94  4884.5  454.25  4894.6  455.24  4975.2  455.29
  4985.2  448.93  4985.8  446.75  4986.3  445.95  4997.5  445.95  4998.0  446.75
  5005.6  446.95  5012.6  454.46  5017.7  455.30  5190.2  453.72  5385.0  454.39
  5468.6  455.69  5549.1  458.64  5609.5  464.95  5702.9  470.52  5805.4  473.53
#Mann=5,-1,0
  4437.3    0.16       0  4531.8    0.12       0  4985.8    0.07       0
  4998.0    0.12       0  5468.6    0.16       0
Bank Sta=4627.5,5609.5
Exp/Cntr=0.3,0.1

Type RM Length L Ch R = 1,22914,1121,1121,1121
BEGIN DESCRIPTION:
SCHOOLEY CREEK 15.0
END DESCRIPTION:
XS GIS Cut Line= 3
      2804998.04      7062552.57      2804680.33      7062536.94
      2803362.66      7062646.31
#Sta/Elev= 30
  4679.9  471.61  4730.1  471.36  4757.7  470.32  4857.4  466.71  4902.7  464.92
  4973.3  460.82  4997.2  446.89  4997.7  446.09  5008.9  446.09  5009.4  446.89
  5013.4  453.38  5023.4  454.28  5083.6  452.96  5152.4  454.35  5324.4  453.53
  5364.6  453.03  5374.6  451.69  5404.7  452.81  5424.8  451.96  5444.9  449.55
  5454.9  449.63  5475.0  454.17  5615.4  452.79  5786.0  453.76  5881.3  454.97
  5961.3  457.26  6179.8  465.76  6222.6  464.92  6243.2  467.74  6320.2  471.11
#Mann=7,-1,0
  4679.9    0.12       0  4757.7    0.16       0  4857.4    0.12       0
  4997.2    0.07       0  5009.4    0.12       0  5961.3    0.16       0
  6179.8    0.05       0
Bank Sta=4902.7,6222.6
Exp/Cntr=0.3,0.1

Type RM Length L Ch R = 1,21793,1148,1148,1148
BEGIN DESCRIPTION:
XS2990A
END DESCRIPTION:
XS GIS Cut Line= 3
      2804701.21      7061844.22      2804232.42      7061943.19
      2802930.59      7062539.67
#Sta/Elev= 30
  4491.5  468.51  4571.2  467.48  4594.7  464.91  4615.8  460.02  4621.0  462.31
  4651.2  451.91  4710.2  452.55  4760.0  450.97  4784.0  452.51  4937.3  451.69
  4985.6  452.57  4991.1  448.82  4994.7  444.91  4995.2  444.11  5006.9  444.91
  5022.8  451.53  5031.6  452.61  5083.1  450.12  5165.8  452.34  5272.7  449.42
  5363.8  451.05  5416.2  449.62  5513.7  451.94  5582.6  451.46  5770.8  454.99
  5806.2  457.34  5852.2  458.15  6012.4  464.91  6152.5  471.06  6402.6  482.15
#Mann=5,-1,0
  4491.5    0.12       0  4994.7    0.07       0  5006.9    0.12       0
  5582.6    0.16       0  6152.5    0.05       0
Bank Sta=4594.7,6012.4
Exp/Cntr=0.3,0.1

Type RM Length L Ch R = 1,20645,1048,1048,1048
BEGIN DESCRIPTION:
XS2991A
END DESCRIPTION:
XS GIS Cut Line= 4
      2804925.08      7061411.93      2804440.75      7061312.98
      2804159.50      7061286.94      2802039.30      7062494.99
#Sta/Elev= 30
  4421.1  471.20  4470.0  470.13  4607.8  464.91  4952.1  452.31  4981.5  449.98
  4985.4  445.56  4985.9  444.76  4997.6  445.56  5011.6  446.78  5021.6  450.94
  5031.7  451.32  5653.1  448.17  5755.5  450.04  5778.5  448.79  5814.4  450.30
  5929.1  449.66  6068.3  449.76  6225.9  450.83  6312.7  451.13  6593.9  455.99
  6795.5  462.37  6848.7  464.91  6923.9  467.00  6965.6  468.41  6981.4  466.95
  7105.3  472.74  7121.2  471.39  7148.6  474.71  7468.7  485.58  7638.1  489.50
#Mann=11,-1,0
  4421.1    0.16       0  4470.0    0.12       0  4985.4    0.07       0
  4997.6    0.12       0  5929.1    0.16       0  6068.3    0.07       0
  6225.9    0.12       0  6312.7    0.16       0  6795.5    0.05       0
  6923.9    0.16       0  7468.7    0.05       0
Bank Sta=4607.8,6848.7
Exp/Cntr=0.3,0.1

Type RM Length L Ch R = 1,19597,1798,1798,1798
BEGIN DESCRIPTION:
XS2992A
END DESCRIPTION:
XS GIS Cut Line= 3
      2805143.85      7061146.30      2804268.87      7060786.94
      2802203.08      7060673.49
#Sta/Elev= 30
  4051.7  471.12  4226.7  464.91  4416.1  453.16  4655.8  449.19  4779.6  449.19
  4803.5  445.59  4850.4  448.41  4915.6  447.75  4969.4  450.30  4980.2  449.43
  4990.9  443.99  4991.4  443.19  5003.1  443.99  5011.5  448.76  5021.5  450.31
  5120.4  448.43  5562.3  446.15  5722.6  447.49  5853.8  452.57  6123.2  452.28
  6237.8  454.80  6463.7  461.36  6483.7  464.20  6664.0  464.01  6704.0  466.85
  6724.1  464.45  6845.7  464.91  6864.3  465.09  6894.3  469.84  7066.5  475.61
#Mann=6,-1,0
  4051.7    0.16       0  4416.1    0.12       0  4990.9    0.07       0
  5003.1    0.12       0  5853.8    0.16       0  6237.8    0.05       0
Bank Sta=4226.7,6845.7
Exp/Cntr=0.3,0.1

Type RM Length L Ch R = 1,17799,743,743,743
BEGIN DESCRIPTION:
XS2993A
END DESCRIPTION:
XS GIS Cut Line= 4
      2805329.60      7061054.27      2804079.64      7060099.44
      2803853.94      7059613.33      2802985.85      7059040.39
#Sta/Elev= 30
  2769.8  466.43  3001.6  470.78  3131.2  464.90  3339.6  453.99  3535.8  447.20
  4090.7  446.95  4152.1  447.57  4221.5  448.71  4504.6  446.30  4665.9  447.14
  4822.0  448.19  4867.8  447.68  4884.1  445.73  4920.2  447.70  4977.4  446.91
  4992.3  445.13  4992.8  444.33  5004.6  445.13  5013.5  447.28  5137.0  454.14
  5165.0  457.99  5354.3  464.90  5468.8  470.69  5540.3  472.13  5548.4  471.33
  5555.4  467.52  5570.5  466.56  5606.6  471.41  5648.7  472.76  5918.8  471.81
#Mann=9,-1,0
  2769.8    0.16       0  3339.6    0.12       0  4090.7    0.07       0
  4152.1    0.12       0  4504.6    0.05       0  4665.9    0.12       0
  4992.3    0.07       0  5004.6    0.12       0  5468.8    0.05       0
Bank Sta=3131.2,5354.3
Exp/Cntr=0.3,0.1

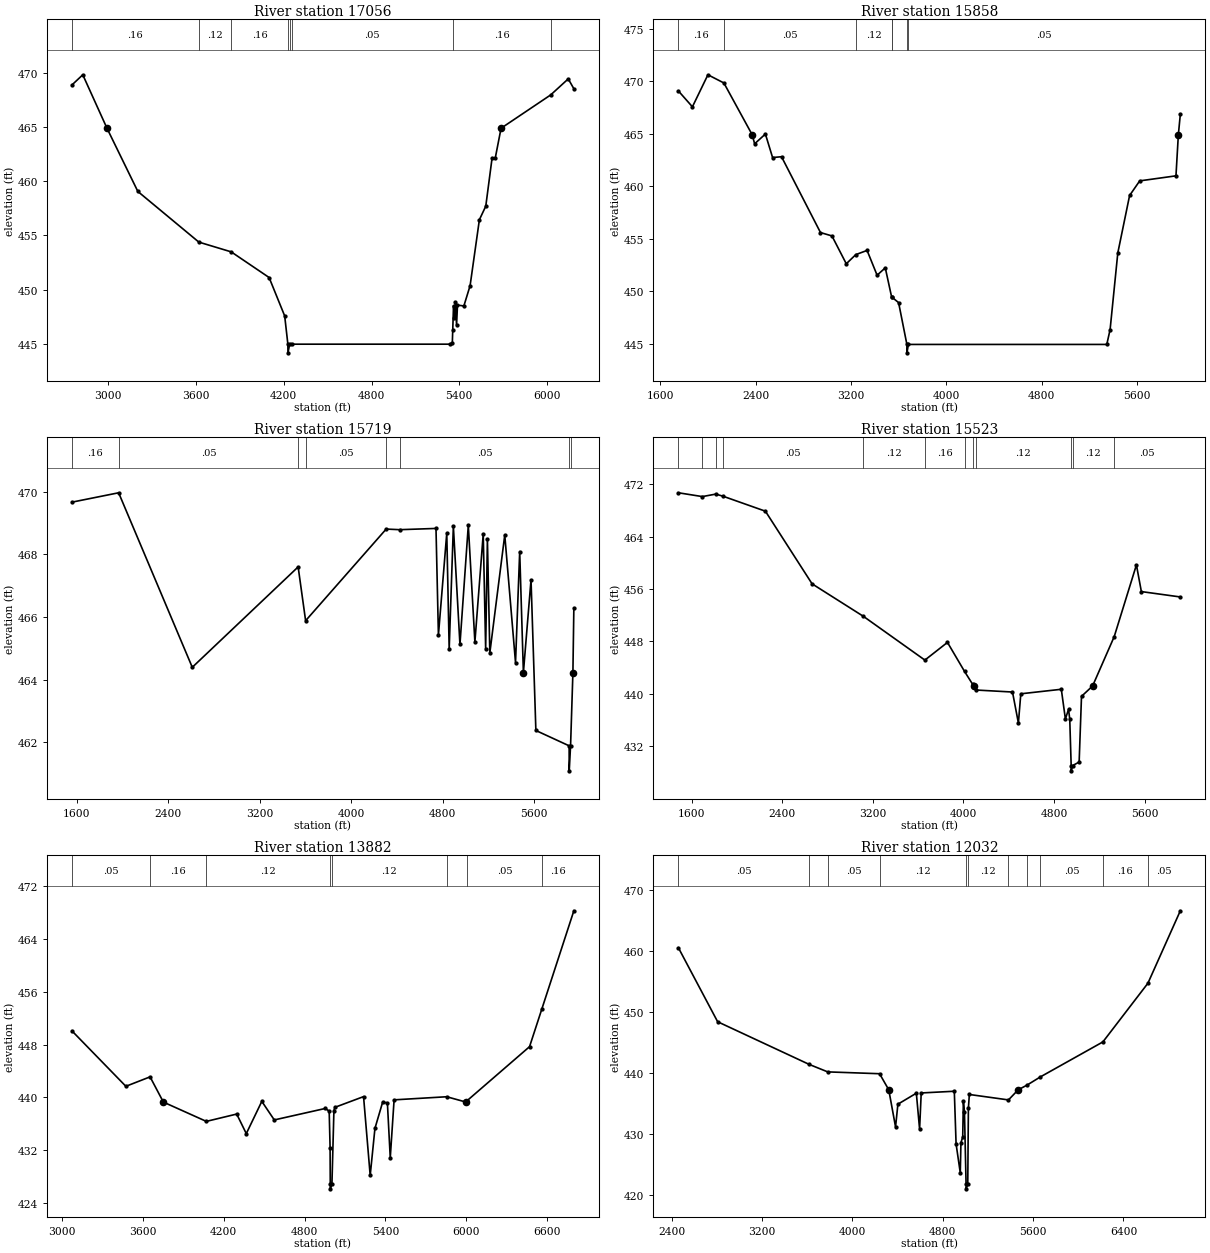
Type RM Length L Ch R = 1,17056,1198,1198,1198
BEGIN DESCRIPTION:
Mapping XS 6bc34c10
END DESCRIPTION:
XS GIS Cut Line= 3
      2805607.50      7060756.20      2804163.06      7058929.81
      2803497.18      7058048.91
#Sta/Elev= 30
  2751.0  468.90  2825.1  469.84  2990.6  464.90  3201.7  459.06  3619.0  454.38
  3840.1  453.48  4099.4  451.11  4206.0  447.56  4227.8  444.95  4228.3  444.15
  4240.2  444.95  4254.4  444.95  5338.0  444.95  5352.5  445.02  5355.4  446.24
  5360.8  448.51  5367.1  447.39  5373.9  448.87  5381.6  446.72  5387.9  448.56
  5431.6  448.48  5474.2  450.36  5537.7  456.45  5581.4  457.70  5624.6  462.16
  5645.9  462.12  5685.9  464.90  6025.4  467.98  6145.4  469.46  6183.8  468.55
#Mann=8,-1,0
  2751.0    0.16       0  3619.0    0.12       0  3840.1    0.16       0
  4227.8   0.033       0  4240.2    0.16       0  4254.4    0.05       0
  5355.4    0.16       0  6025.4    0.05       0
Bank Sta=2990.6,5685.9
Exp/Cntr=0.3,0.1

Type RM Length L Ch R = 1,15858,139,139,139
BEGIN DESCRIPTION:
XS2994A
END DESCRIPTION:
XS GIS Cut Line= 6
      2805659.50      7060941.45      2805772.35      7059734.86
      2805451.17      7058997.01      2804843.53      7058016.11
      2804600.47      7057616.80      2804195.69      7057212.65
#Sta/Elev= 30
  1752.3  469.08  1869.7  467.57  1999.8  470.62  2133.7  469.84  2371.6  464.90
  2391.5  464.05  2481.9  464.98  2542.2  462.74  2617.1  462.82  2944.0  455.60
  3040.0  455.28  3160.3  452.63  3240.1  453.50  3334.8  453.90  3418.8  451.54
  3487.5  452.24  3539.8  449.51  3540.8  449.47  3599.2  448.93  3668.7  444.95
  3669.2  444.15  3681.2  444.95  5345.5  444.95  5373.3  446.37  5437.8  453.66
  5536.8  459.13  5621.6  460.52  5925.7  461.00  5945.6  464.90  5962.2  466.86
#Mann=7,-1,0
  1752.3    0.16       0  2133.7    0.05       0  3240.1    0.12       0
  3539.8    0.07       0  3540.8    0.05       0  3668.7   0.033       0
  3681.2    0.05       0
Bank Sta=2371.6,5945.6
Exp/Cntr=0.3,0.1

Type RM Length L Ch R = 1,15719,196,196,196
BEGIN DESCRIPTION:
XS2995A
END DESCRIPTION:
XS GIS Cut Line= 6
      2805694.23      7060976.14      2805824.43      7060142.84
      2805867.83      7059526.52      2805841.79      7059361.59
      2804617.83      7057425.83      2804285.94      7057094.57
#Sta/Elev= 30
  1557.8  469.67  1965.9  469.97  2609.6  464.39  3535.1  467.60  3600.4  465.88
  4304.7  468.81  4422.1  468.79  4740.1  468.83  4761.3  465.42  4834.3  468.68
  4855.4  464.97  4891.9  468.90  4949.5  465.12  5022.5  468.93  5080.1  465.20
  5153.0  468.65  5174.2  464.98  5189.5  468.49  5210.7  464.85  5341.2  468.62
  5435.3  464.54  5471.8  468.09  5504.1  464.22  5570.8  467.19  5613.2  462.37
  5904.0  461.88  5904.5  461.08  5916.5  461.88  5936.9  464.22  5945.2  466.29
#Mann=8,-1,0
  1557.8    0.16       0  1965.9    0.05       0  3535.1    0.12       0
  3600.4    0.05       0  4304.7    0.12       0  4422.1    0.05       0
  5904.0   0.035       0  5916.5    0.05       0
Bank Sta=5504.1,5936.9
Exp/Cntr=0.3,0.1

Type RM Length L Ch R = 1,15523,1641,1641,1641
BEGIN DESCRIPTION:
XS2996A
END DESCRIPTION:
XS GIS Cut Line= 6
      2805777.55      7060906.77      2805965.05      7059462.29
      2805763.67      7058934.51      2805013.67      7057712.29
      2804937.28      7057615.07      2804423.39      7056934.52
#Sta/Elev= 30
  1484.0  470.67  1695.0  470.09  1814.8  470.47  1880.3  470.13  2252.2  467.86
  2664.4  456.78  3117.8  451.82  3660.3  445.15  3859.7  447.85  4010.6  443.42
  4083.1  441.43  4092.7  441.20  4107.6  440.59  4434.0  440.28  4486.1  435.55
  4507.4  440.01  4865.0  440.70  4901.1  436.17  4928.9  437.65  4939.5  436.17
  4952.1  429.06  4952.6  428.26  4964.6  429.06  5022.5  429.60  5043.3  439.62
  5141.2  441.20  5332.2  448.73  5528.2  459.67  5571.9  455.60  5915.9  454.78
#Mann=12,-1,0
  1484.0    0.16       0  1695.0    0.05       0  1814.8    0.16       0
  1880.3    0.05       0  3117.8    0.12       0  3660.3    0.16       0
  4010.6    0.12       0  4083.1    0.16       0  4107.6    0.12       0
  4952.1    0.07       0  4964.6    0.12       0  5332.2    0.05       0
Bank Sta=4092.7,5141.2
Exp/Cntr=0.3,0.1

Type RM Length L Ch R = 1,13882,1850,1850,1850
BEGIN DESCRIPTION:
double SCHOOLEY CREEK 7.0
END DESCRIPTION:
XS GIS Cut Line= 3
      2806557.50      7058360.72      2805501.74      7056905.21
      2804058.74      7055627.45
#Sta/Elev= 30
  3073.8  450.07  3474.1  441.68  3653.6  443.11  3752.5  439.29  4071.3  436.37
  4296.7  437.48  4367.9  434.52  4483.1  439.40  4575.7  436.59  4954.8  438.33
  4983.2  437.91  4989.9  432.41  4991.2  426.96  4991.7  426.16  5003.7  426.96
  5018.3  437.99  5025.9  438.50  5238.3  440.12  5287.6  428.19  5322.8  435.31
  5379.7  439.26  5415.2  439.19  5436.5  430.86  5465.0  439.63  5855.6  440.10
  5999.3  439.29  6007.2  439.51  6470.4  447.68  6562.1  453.41  6799.3  468.25
#Mann=8,-1,0
  3073.8    0.05       0  3653.6    0.16       0  4071.3    0.12       0
  4991.2    0.07       0  5003.7    0.12       0  5855.6    0.16       0
  6007.2    0.05       0  6562.1    0.16       0
Bank Sta=3752.5,5999.3
Exp/Cntr=0.3,0.1

Type RM Length L Ch R = 1,12032,791,791,791
BEGIN DESCRIPTION:
SCHOOLEY CREEK 6.0
END DESCRIPTION:
XS GIS Cut Line= 4
      2807704.10      7058030.10      2806687.71      7056615.93
      2806204.08      7056230.07      2804404.08      7055180.07
#Sta/Elev= 30
  2459.1  460.54  2806.4  448.43  3617.6  441.44  3781.0  440.22  4240.3  439.92
  4321.7  437.28  4381.7  431.21  4402.5  434.93  4565.8  436.73  4594.6  430.85
  4609.0  436.77  4902.0  437.05  4917.7  428.44  4954.9  423.68  4960.7  428.63
  4976.4  429.53  4982.2  435.43  4991.9  433.62  5006.1  421.87  5007.4  421.07
  5021.1  421.87  5026.7  434.27  5035.1  436.52  5381.6  435.63  5467.2  437.28
  5548.2  438.08  5664.2  439.40  6217.8  445.13  6616.4  454.74  6903.2  466.60
#Mann=11,-1,0
  2459.1    0.05       0  3617.6    0.16       0  3781.0    0.05       0
  4240.3    0.12       0  5006.1    0.07       0  5021.1    0.12       0
  5381.6    0.05       0  5548.2    0.16       0  5664.2    0.05       0
  6217.8    0.16       0  6616.4    0.05       0
Bank Sta=4321.7,5467.2
Exp/Cntr=0.3,0.1

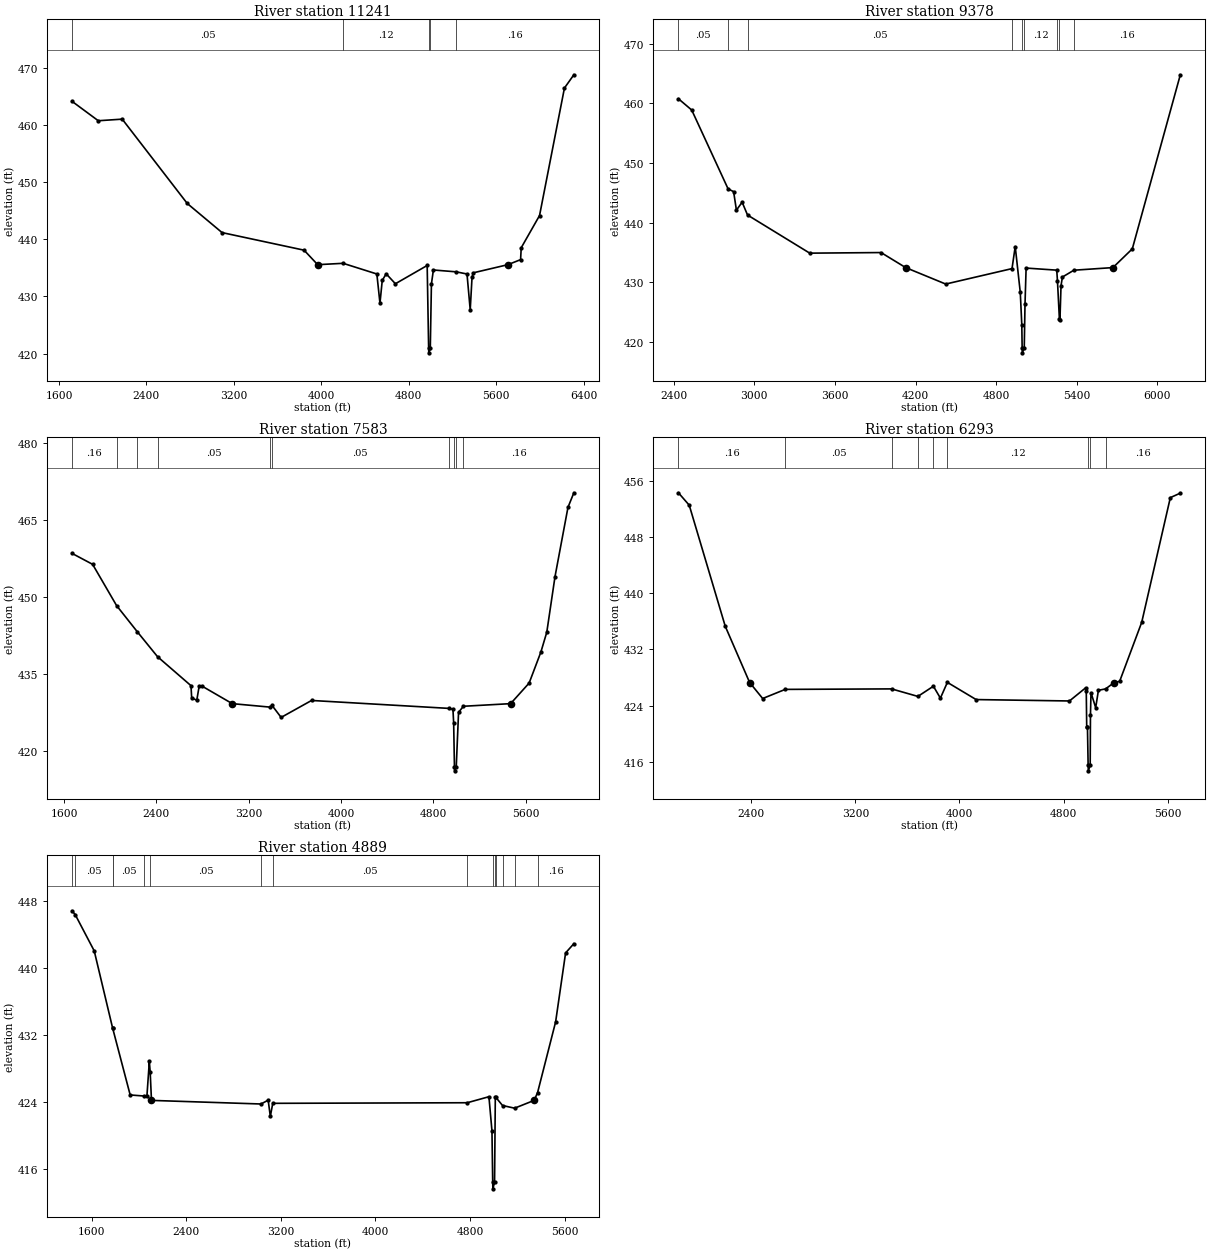
Type RM Length L Ch R = 1,11241,1863,1863,1863
BEGIN DESCRIPTION:
SCHOOLEY CREEK 5.0
END DESCRIPTION:
XS GIS Cut Line= 3
      2808774.96      7057874.97      2806325.00      7055675.00
      2805825.02      7054475.04
#Sta/Elev= 30
  1718.6  464.18  1959.6  460.77  2178.6  461.05  2773.7  446.28  3092.1  441.18
  3842.6  438.10  3967.2  435.56  4199.8  435.80  4508.6  433.93  4537.1  428.81
  4558.0  432.80  4593.9  433.96  4678.3  432.22  4969.1  435.42  4982.5  420.92
  4983.8  420.12  4997.6  420.92  5008.0  432.19  5026.0  434.63  5233.0  434.31
  5333.6  433.93  5362.9  427.65  5379.7  433.37  5392.1  434.14  5707.2  435.56
  5823.8  436.44  5829.8  438.53  5997.2  444.16  6225.2  466.50  6311.3  468.82
#Mann=5,-1,0
  1718.6    0.05       0  4199.8    0.12       0  4982.5    0.07       0
  4997.6    0.12       0  5233.0    0.16       0
Bank Sta=3967.2,5707.2
Exp/Cntr=0.3,0.1

Type RM Length L Ch R = 1,9378,1795,1795,1795
BEGIN DESCRIPTION:
SCHOOLEY CREEK 4.0
END DESCRIPTION:
XS GIS Cut Line= 3
      2808925.03      7056725.03      2807234.59      7054836.42
      2806124.96      7054374.98
#Sta/Elev= 30
  2434.8  460.76  2533.9  458.87  2804.7  445.65  2845.7  445.19  2866.6  442.09
  2909.2  443.42  2949.4  441.27  3412.4  434.88  3943.2  434.98  4126.6  432.46
  4424.7  429.70  4918.3  432.29  4942.1  435.99  4979.8  428.30  4991.1  422.87
  4993.7  418.97  4995.2  418.17  5009.3  418.97  5015.0  426.34  5023.2  432.38
  5251.3  432.03  5256.7  430.19  5271.1  423.81  5275.2  423.72  5283.1  429.45
  5293.6  430.88  5378.8  432.02  5669.5  432.46  5813.8  435.60  6171.2  464.78
#Mann=9,-1,0
  2434.8    0.05       0  2804.7    0.08       0  2949.4    0.05       0
  4918.3    0.12       0  4993.7    0.07       0  5009.3    0.12       0
  5256.7    0.16       0  5271.1    0.12       0  5378.8    0.16       0
Bank Sta=4126.6,5669.5
Exp/Cntr=0.3,0.1

Type RM Length L Ch R = 1,7583,1290,1290,1290
BEGIN DESCRIPTION:
SCHOOLEY CREEK 3.0
END DESCRIPTION:
XS GIS Cut Line= 3
      2809275.02      7056125.03      2807325.00      7053425.00
      2806324.98      7053225.00
#Sta/Elev= 30
  1668.1  458.53  1847.2  456.39  2055.0  448.36  2232.9  443.31  2410.0  438.41
  2699.8  432.77  2706.0  430.37  2750.1  429.94  2771.0  432.69  2791.8  432.73
  3057.8  429.27  3387.6  428.59  3402.2  428.93  3481.2  426.59  3745.0  429.89
  4934.0  428.35  4970.5  428.17  4976.6  425.54  4983.5  416.99  4985.1  416.19
  4999.2  416.99  5019.1  427.57  5061.0  428.76  5470.3  429.27  5631.0  433.28
  5732.9  439.33  5783.9  443.18  5855.3  454.02  5967.5  467.48  6018.5  470.32
#Mann=10,-1,0
  1668.1    0.16       0  2055.0    0.05       0  2232.9    0.16       0
  2410.0    0.05       0  3387.6    0.12       0  3402.2    0.05       0
  4934.0    0.12       0  4983.5    0.07       0  4999.2    0.12       0
  5061.0    0.16       0
Bank Sta=3057.8,5470.3
Exp/Cntr=0.3,0.1

Type RM Length L Ch R = 1,6293,1404,1404,1404
BEGIN DESCRIPTION:
SCHOOLEY CREEK 2.0
END DESCRIPTION:
XS GIS Cut Line= 3
      2809361.30      7055409.29      2808137.36      7052518.71
      2807599.59      7052041.66
#Sta/Elev= 30
  1840.0  454.30  1923.2  452.53  2200.0  435.29  2387.4  427.28  2487.7  425.00
  2661.0  426.30  3478.1  426.37  3680.6  425.30  3800.0  426.75  3853.7  425.05
  3907.3  427.30  4128.3  424.85  4845.7  424.65  4969.5  426.51  4974.9  426.07
  4978.3  421.01  4984.0  421.01  4989.3  415.50  4990.9  414.70  5005.1  415.50
  5007.2  422.66  5011.4  425.83  5047.4  423.69  5068.3  426.17  5123.5  426.37
  5189.6  427.28  5231.4  427.44  5401.1  435.85  5621.1  453.61  5697.9  454.25
#Mann=9,-1,0
  1840.0    0.16       0  2661.0    0.05       0  3478.1    0.08       0
  3680.6    0.05       0  3800.0    0.08       0  3907.3    0.12       0
  4989.3    0.07       0  5005.1    0.12       0  5123.5    0.16       0
Bank Sta=2387.4,5189.6
Exp/Cntr=0.3,0.1

Type RM Length L Ch R = 1,4889,0,0,0
BEGIN DESCRIPTION:
SCHOOLEY CREEK 1.0
END DESCRIPTION:
XS GIS Cut Line= 3
      2809639.10      7055201.03      2809066.18      7051720.10
      2808589.35      7051182.58
#Sta/Elev= 30
  1432.2  446.82  1459.5  446.37  1620.7  442.03  1775.3  432.87  1775.7  432.85
  1924.8  424.83  2043.5  424.70  2066.7  424.74  2086.9  428.83  2094.0  427.60
  2105.0  424.18  3031.6  423.75  3092.3  424.21  3110.5  422.27  3131.2  423.83
  4776.4  423.90  4960.0  424.62  4985.6  420.55  4991.9  414.42  4993.5  413.62
  5007.7  414.42  5014.0  424.55  5016.9  424.57  5075.1  423.57  5177.1  423.25
  5342.6  424.18  5371.5  425.11  5524.2  433.55  5608.6  441.79  5678.5  442.89
#Mann=15,-1,0
  1432.2    0.16       0  1459.5    0.05       0  1775.3    0.16       0
  1775.7    0.05       0  2043.5    0.16       0  2094.0    0.05       0
  3031.6    0.08       0  3131.2    0.05       0  4776.4    0.12       0
  4991.9    0.07       0  5007.7    0.12       0  5016.9    0.05       0
  5075.1    0.07       0  5177.1    0.05       0  5371.5    0.16       0
Bank Sta=2105,5342.6
Exp/Cntr=0.3,0.1

Chan Stop Cuts=-1