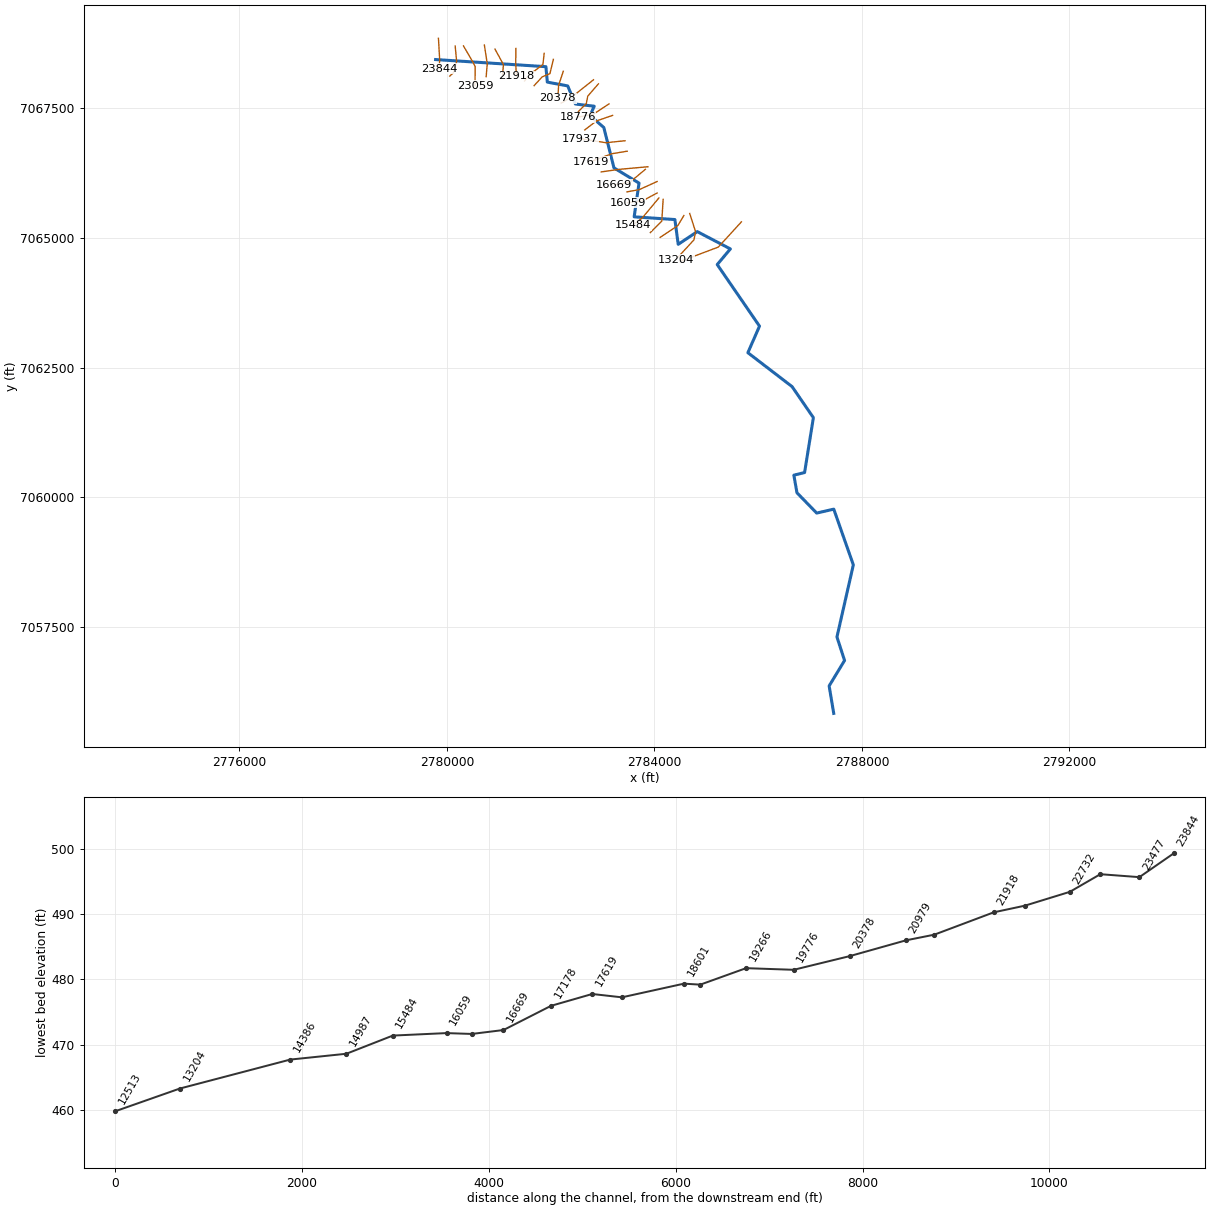
--- SLOUGH CREEK.prj (project) ---

Proj Title=SLOUGH CREEK Base Level Engineering
Current Plan=p01
Default Exp/Contr=0.3,0.1
English Units
Geom File=g01
Flow File=f01
Plan File=p01
BEGIN DESCRIPTION:
SLOUGH CREEK
END DESCRIPTION:

--- SLOUGH CREEK.p01 (plan) ---

Plan Title=Multiple Run
Short Identifier=Multiple
Geom File=g01
Flow File=f01
Subcritical Flow
K Sum by GR= 0
Std Step Tol= 0.01
Critical Tol= 0.01
Num of Std Step Trials= 20
Max Error Tol= 0.3
Flow Tol Ratio= 0.001
Split Flow NTrial= 30
Split Flow Tol= 0.02
Split Flow Ratio= 0.02
Log Output Level= 0
Friction Slope Method= 1
Unsteady Friction Slope Method= 2
Unsteady Bridges Friction Slope Method= 1
Parabolic Critical Depth
Global Vel Dist=  1 , 1 , 1
Global Log Level= 0
CheckData=True
Encroach Param= -1, 0, 0, 0
BEGIN DESCRIPTION:
Multiple Run
END DESCRIPTION:

--- SLOUGH CREEK.f01 (steady flow) ---

Flow Title=Multiple
Number of Profiles=7
Profile Names=10-year,25-year,50-year,1pct_min,100-year,1pct_plu,500-year
River Rch & RM= SLOUGH CREEK,Reach-1,23844
     460     600     710     418     833    1662    1143
River Rch & RM= SLOUGH CREEK,Reach-1,19266
     744     999    1206     721    1439    2871    2045
River Rch & RM= SLOUGH CREEK,Reach-1,13204
     895    1206    1457     872    1739    3470    2474
Boundary for River Rch & Prof#=SLOUGH CREEK,Reach-1,1
Up Type=0
Dn Type=3
Dn Slope=0.005
Boundary for River Rch & Prof#=SLOUGH CREEK,Reach-1,2
Up Type=0
Dn Type=3
Dn Slope=0.005
Boundary for River Rch & Prof#=SLOUGH CREEK,Reach-1,3
Up Type=0
Dn Type=3
Dn Slope=0.005
Boundary for River Rch & Prof#=SLOUGH CREEK,Reach-1,4
Up Type=0
Dn Type=3
Dn Slope=0.005
Boundary for River Rch & Prof#=SLOUGH CREEK,Reach-1,5
Up Type=0
Dn Type=3
Dn Slope=0.005
Boundary for River Rch & Prof#=SLOUGH CREEK,Reach-1,6
Up Type=0
Dn Type=3
Dn Slope=0.005
Boundary for River Rch & Prof#=SLOUGH CREEK,Reach-1,7
Up Type=0
Dn Type=3
Dn Slope=0.005

--- SLOUGH CREEK.g01 (geometry) ---

Geom Title=Existing Conditions

River Reach=SLOUGH CREEK,Reach-1
Reach XY= 30
      2779781.64      7068442.53      2781907.85      7068304.79
      2781934.52      7068007.30      2782327.16      7067934.38
      2782476.46      7067584.29      2782838.81      7067542.53
      2782759.50      7067362.97      2783024.15      7067130.78
      2783219.39      7066352.72      2783702.47      7066059.49
      2783608.85      7065408.59      2784393.85      7065356.29
      2784457.73      7064878.42      2784825.99      7065123.12
      2785463.42      7064789.80      2785209.76      7064487.84
      2786024.96      7063299.97      2785800.60      7062788.08
      2786652.16      7062134.33      2787063.39      7061534.95
      2786893.90      7060476.12      2786687.03      7060425.55
      2786746.86      7060086.25      2787127.35      7059694.14
      2787456.35      7059770.18      2787833.63      7058694.86
      2787517.65      7057304.68      2787664.48      7056850.90
      2787367.05      7056360.31      2787455.59      7055830.71

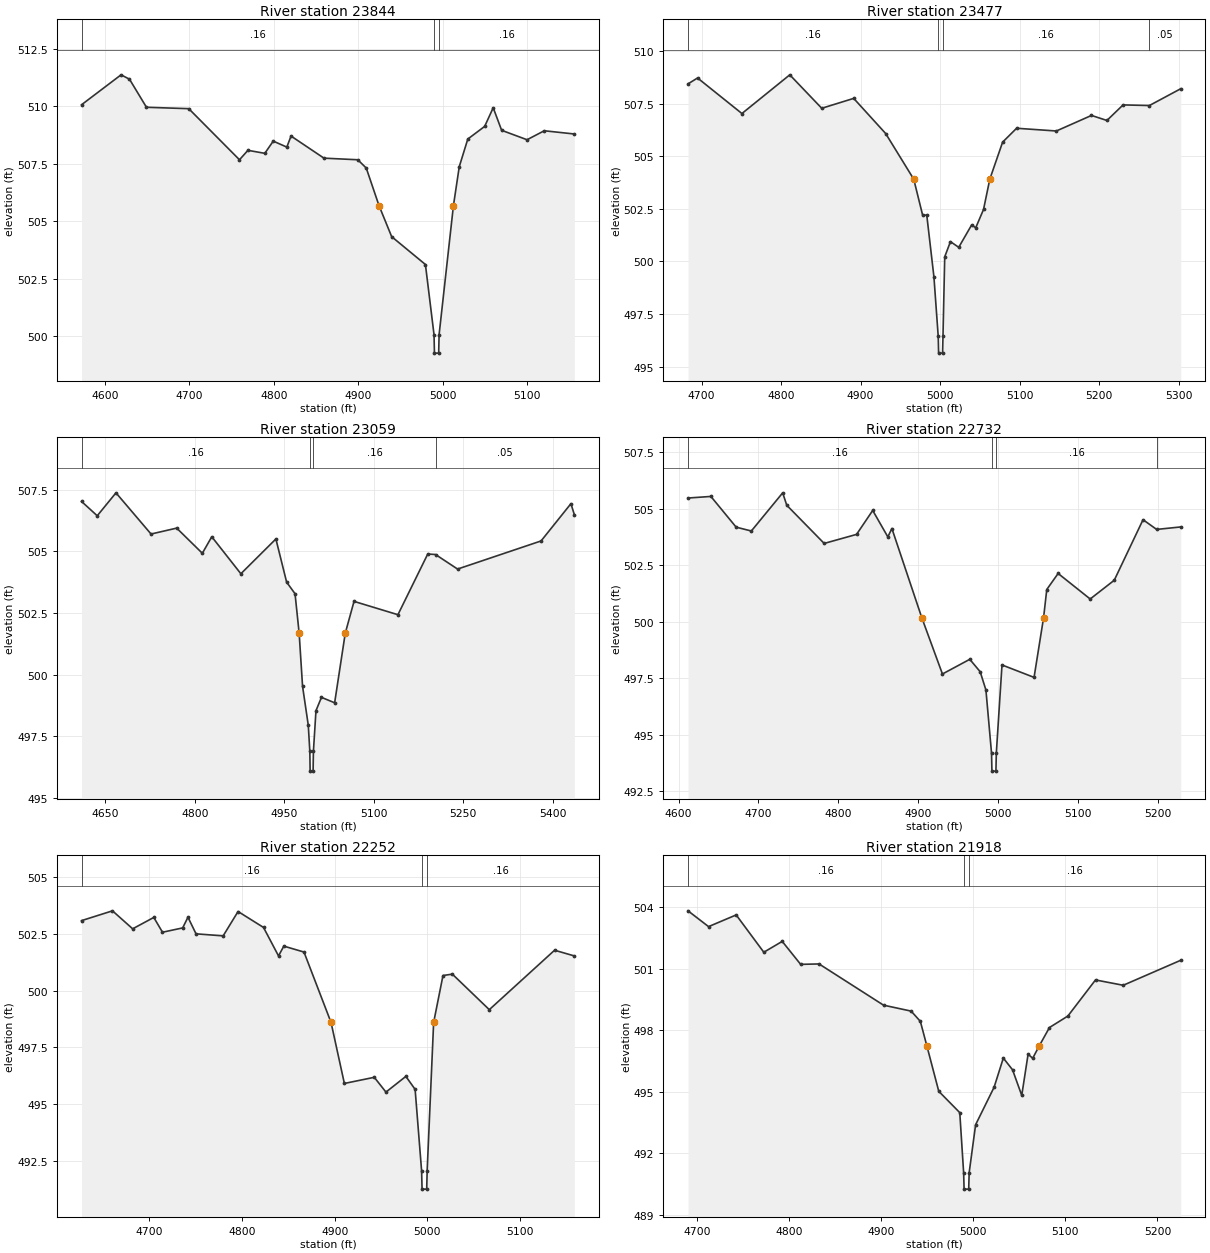
Type RM Length L Ch R = 1,23844,367,367,367
BEGIN DESCRIPTION:
SLOUGH CREEK 10.0
END DESCRIPTION:
XS GIS Cut Line= 3
      2779836.01      7068851.75      2779860.32      7068428.14
      2779846.50      7068269.24
#Sta/Elev= 30
  4572.2  510.06  4619.0  511.36  4629.0  511.17  4649.1  509.95  4699.2  509.89
  4759.3  507.67  4769.3  508.08  4789.3  507.95  4799.3  508.48  4815.4  508.22
  4820.4  508.70  4859.4  507.74  4899.5  507.67  4909.5  507.31  4924.6  505.68
  4939.6  504.33  4979.6  503.12  4989.8  500.07  4990.3  499.27  4995.3  499.27
  4995.8  500.07  5012.8  505.68  5019.7  507.37  5029.8  508.57  5049.8  509.12
  5059.9  509.93  5069.9  508.95  5100.0  508.54  5120.4  508.93  5156.0  508.79
#Mann=3,-1,0
  4572.2    0.16       0  4989.8    0.07       0  4995.8    0.16       0
Bank Sta=4924.6,5012.8
Exp/Cntr=0.3,0.1

Type RM Length L Ch R = 1,23477,418,418,418
BEGIN DESCRIPTION:
XS2997A
END DESCRIPTION:
XS GIS Cut Line= 4
      2780158.93      7068702.47      2780186.71      7068407.31
      2780124.21      7068188.56      2780054.73      7068122.55
#Sta/Elev= 30
  4683.0  508.44  4695.0  508.72  4750.8  507.03  4811.0  508.87  4851.2  507.28
  4891.4  507.75  4931.6  506.08  4966.9  503.91  4978.1  502.20  4983.3  502.20
  4992.3  499.27  4997.7  496.44  4998.2  495.64  5003.2  495.64  5003.7  496.44
  5005.9  500.22  5013.1  500.94  5023.5  500.67  5039.7  501.73  5044.9  501.60
  5054.7  502.47  5062.6  503.91  5078.7  505.67  5096.3  506.33  5146.3  506.20
  5190.5  506.94  5209.9  506.70  5230.2  507.44  5263.3  507.41  5302.8  508.21
#Mann=4,-1,0
  4683.0    0.16       0  4997.7    0.07       0  5003.7    0.16       0
  5263.3    0.05       0
Bank Sta=4966.9,5062.6
Exp/Cntr=0.3,0.1

Type RM Length L Ch R = 1,23059,327,327,327
BEGIN DESCRIPTION:
XS2998A
END DESCRIPTION:
XS GIS Cut Line= 4
      2780318.66      7068705.90      2780492.26      7068407.31
      2780544.34      7068306.61      2780540.88      7067939.28
#Sta/Elev= 30
  4609.9  507.02  4636.2  506.44  4667.6  507.37  4726.4  505.70  4769.4  505.94
  4812.4  504.92  4828.2  505.59  4877.0  504.09  4935.7  505.50  4953.7  503.75
  4967.8  503.28  4974.7  501.68  4980.4  499.53  4990.0  497.95  4992.6  496.89
  4993.1  496.09  4998.1  496.09  4998.6  496.89  5002.9  498.54  5012.1  499.08
  5034.2  498.86  5052.0  501.68  5066.7  502.97  5140.3  502.43  5190.3  504.89
  5203.3  504.87  5240.3  504.28  5380.3  505.42  5430.3  506.93  5436.0  506.49
#Mann=4,-1,0
  4609.9    0.16       0  4992.6    0.07       0  4998.6    0.16       0
  5203.3    0.05       0
Bank Sta=4974.7,5052
Exp/Cntr=0.3,0.1

Type RM Length L Ch R = 1,22732,480,480,480
BEGIN DESCRIPTION:
XS2999A
END DESCRIPTION:
XS GIS Cut Line= 3
      2780721.42      7068723.31      2780776.98      7068362.17
      2780756.15      7068112.13
#Sta/Elev= 30
  4611.9  505.48  4640.5  505.55  4672.1  504.19  4691.1  504.02  4730.3  505.71
  4735.4  505.16  4782.2  503.47  4822.7  503.87  4842.9  504.93  4861.8  503.76
  4866.9  504.13  4904.3  500.18  4930.1  497.69  4964.3  498.34  4977.3  497.79
  4984.5  496.98  4991.5  494.19  4992.0  493.39  4997.0  493.39  4997.5  494.19
  5004.6  498.09  5044.7  497.54  5056.6  500.18  5060.6  501.43  5074.8  502.14
  5114.9  501.01  5145.0  501.84  5181.0  504.52  5198.0  504.09  5228.2  504.20
#Mann=4,-1,0
  4611.9    0.16       0  4991.5    0.07       0  4997.5    0.16       0
  5198.0    0.05       0
Bank Sta=4904.3,5056.6
Exp/Cntr=0.3,0.1

Type RM Length L Ch R = 1,22252,334,334,334
BEGIN DESCRIPTION:
XS3000A
END DESCRIPTION:
XS GIS Cut Line= 3
      2780926.28      7068643.43      2781089.48      7068344.81
      2781072.12      7068153.81
#Sta/Elev= 30
  4626.7  503.07  4660.1  503.50  4681.9  502.71  4704.7  503.21  4714.1  502.56
  4735.9  502.75  4741.6  503.22  4750.3  502.49  4779.6  502.40  4795.7  503.47
  4823.2  502.77  4839.4  501.52  4845.1  501.95  4866.9  501.69  4896.1  498.60
  4910.5  495.92  4942.8  496.19  4955.4  495.54  4976.9  496.23  4986.9  495.66
  4993.9  492.08  4994.4  491.28  4999.4  491.28  4999.9  492.08  5006.9  498.60
  5017.0  500.66  5027.1  500.72  5067.0  499.16  5137.5  501.77  5158.8  501.52
#Mann=3,-1,0
  4626.7    0.16       0  4993.9    0.07       0  4999.9    0.16       0
Bank Sta=4896.1,5006.9
Exp/Cntr=0.3,0.1

Type RM Length L Ch R = 1,21918,637,637,637
BEGIN DESCRIPTION:
XS3001A
END DESCRIPTION:
XS GIS Cut Line= 3
      2781329.07      7068657.28      2781325.59      7068362.17
      2781339.48      7068122.60
#Sta/Elev= 30
  4690.3  503.83  4712.6  503.06  4742.6  503.63  4772.6  501.81  4792.6  502.34
  4812.6  501.22  4832.6  501.24  4902.6  499.23  4932.6  498.94  4942.6  498.44
  4949.8  497.22  4962.6  495.03  4985.4  493.99  4989.6  491.06  4990.1  490.26
  4995.1  490.26  4995.6  491.06  5002.6  493.40  5022.7  495.23  5032.7  496.65
  5042.7  496.08  5052.7  494.83  5059.6  496.84  5064.6  496.64  5071.4  497.22
  5082.8  498.14  5102.8  498.70  5132.8  500.46  5162.9  500.20  5225.4  501.42
#Mann=3,-1,0
  4690.3    0.16       0  4989.6    0.07       0  4995.6    0.16       0
Bank Sta=4949.8,5071.4
Exp/Cntr=0.3,0.1

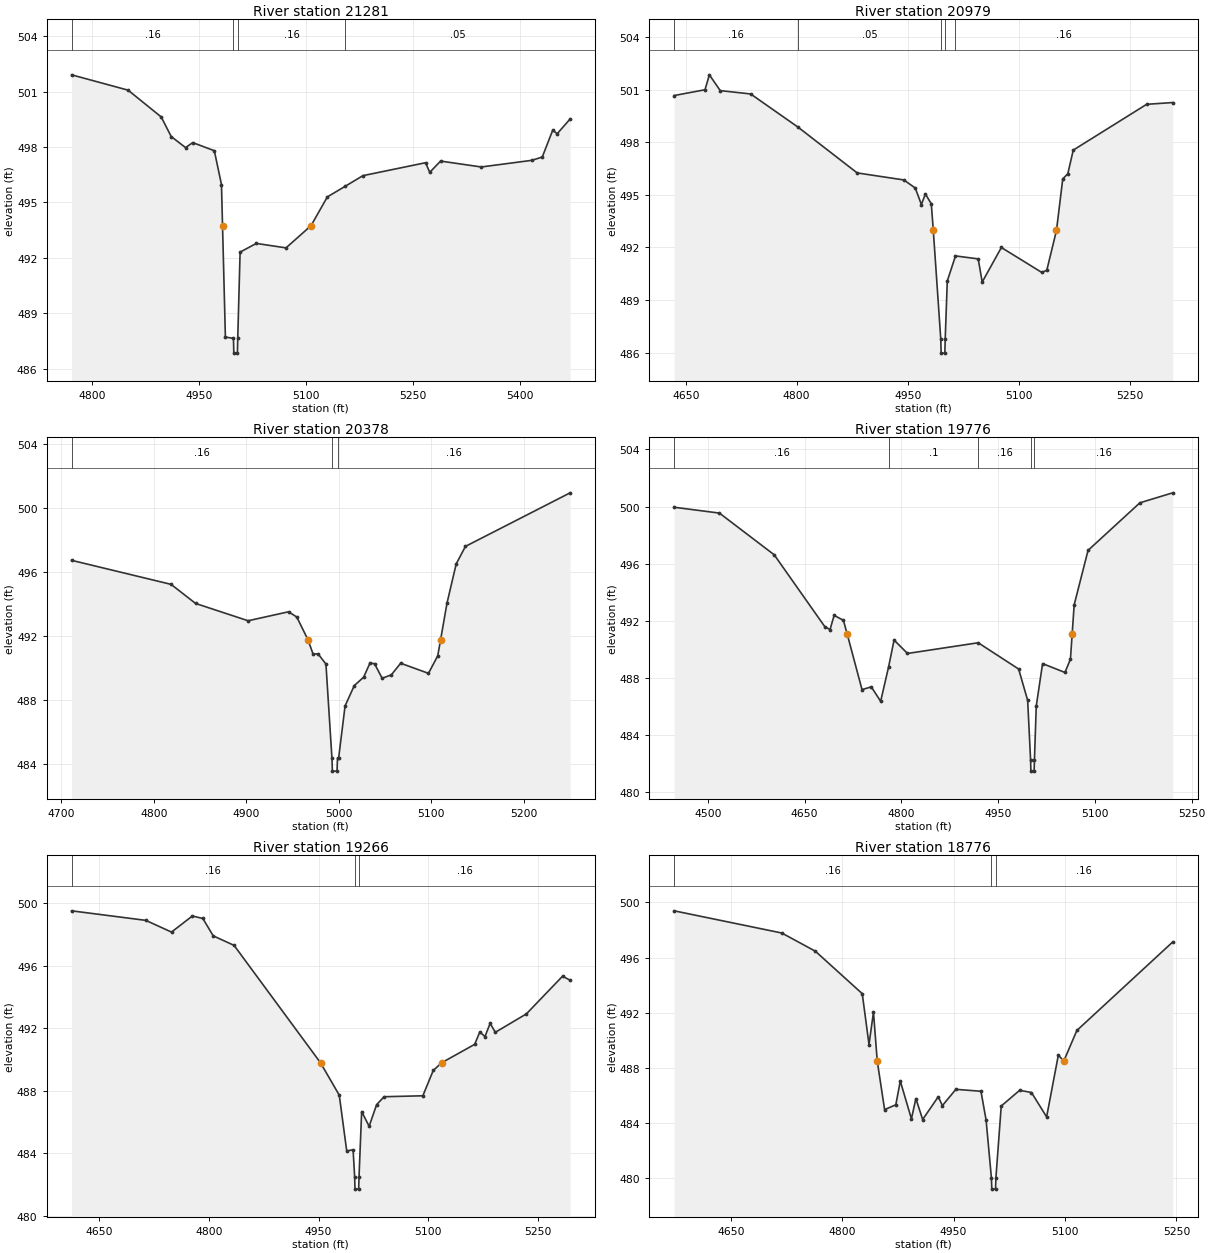
Type RM Length L Ch R = 1,21281,302,302,302
BEGIN DESCRIPTION:
XS3002A
END DESCRIPTION:
XS GIS Cut Line= 5
      2781874.21      7068563.60      2781849.90      7068348.28
      2781693.65      7068226.75      2781596.43      7068164.25
      2781496.19      7068029.45
#Sta/Elev= 30
  4771.5  501.91  4850.6  501.08  4897.0  499.63  4911.0  498.57  4931.1  497.97
  4941.2  498.24  4971.4  497.80  4981.4  495.97  4982.9  493.74  4986.9  487.71
  4998.2  487.64  4998.7  486.84  5003.7  486.84  5004.2  487.64  5007.5  492.31
  5030.2  492.78  5071.8  492.54  5106.8  493.74  5129.7  495.30  5154.5  495.87
  5179.5  496.45  5267.2  497.15  5273.1  496.63  5288.3  497.24  5345.2  496.92
  5416.1  497.28  5430.7  497.46  5445.3  498.91  5451.6  498.72  5469.7  499.52
#Mann=4,-1,0
  4771.5    0.16       0  4998.2    0.07       0  5004.2    0.16       0
  5154.5    0.05       0
Bank Sta=4982.9,5106.8
Exp/Cntr=0.3,0.1

Type RM Length L Ch R = 1,20979,601,601,601
BEGIN DESCRIPTION:
XS3003A
END DESCRIPTION:
XS GIS Cut Line= 4
      2782051.30      7068445.55      2781985.32      7068171.20
      2781836.01      7068108.70      2781680.53      7067939.39
#Sta/Elev= 30
  4634.4  500.66  4676.1  500.99  4682.0  501.84  4696.7  500.94  4737.8  500.75
  4801.8  498.86  4881.8  496.25  4944.8  495.85  4960.3  495.39  4968.6  494.45
  4974.0  495.05  4982.0  494.49  4984.7  492.97  4994.8  486.78  4995.3  485.98
  5000.3  485.98  5000.8  486.78  5003.6  490.09  5014.7  491.52  5045.4  491.35
  5050.8  490.03  5076.7  492.00  5131.3  490.58  5138.1  490.70  5151.2  492.97
  5159.7  495.91  5166.5  496.20  5173.9  497.55  5273.1  500.16  5308.3  500.26
#Mann=5,-1,0
  4634.4    0.16       0  4801.8    0.05       0  4994.8    0.04       0
  5000.8    0.05       0  5014.7    0.16       0
Bank Sta=4984.7,5151.2
Exp/Cntr=0.3,0.1

Type RM Length L Ch R = 1,20378,602,602,602
BEGIN DESCRIPTION:
XS3004A
END DESCRIPTION:
XS GIS Cut Line= 3
      2782242.27      7068216.35      2782151.98      7067942.03
      2782138.09      7067692.01
#Sta/Elev= 30
  4711.2  496.72  4818.8  495.22  4845.3  494.03  4902.1  492.95  4945.9  493.51
  4954.8  493.18  4966.9  491.76  4972.4  490.87  4977.7  490.89  4986.3  490.25
  4992.8  484.37  4993.3  483.57  4998.3  483.57  4998.8  484.37  5000.0  484.37
  5007.0  487.64  5017.0  488.91  5027.1  489.43  5033.9  490.31  5038.9  490.27
  5047.1  489.36  5057.1  489.58  5067.1  490.30  5097.2  489.67  5107.2  490.76
  5110.3  491.76  5117.2  494.04  5127.2  496.50  5137.2  497.59  5250.4  500.93
#Mann=3,-1,0
  4711.2    0.16       0  4992.8    0.07       0  4998.8    0.16       0
Bank Sta=4966.9,5110.3
Exp/Cntr=0.3,0.1

Type RM Length L Ch R = 1,19776,510,510,510
BEGIN DESCRIPTION:
XS3005A
END DESCRIPTION:
XS GIS Cut Line= 3
      2782825.62      7068053.17      2782415.87      7067726.75
      2782200.60      7067601.76
#Sta/Elev= 30
  4447.7  499.95  4517.9  499.54  4602.8  496.62  4681.2  491.59  4689.3  491.38
  4695.7  492.38  4710.1  492.03  4716.1  491.04  4738.9  487.18  4753.3  487.37
  4767.8  486.36  4780.2  488.79  4788.6  490.65  4809.4  489.71  4919.0  490.46
  4981.7  488.62  4995.7  486.42  5000.2  482.27  5000.7  481.47  5005.7  481.47
  5006.2  482.27  5009.0  486.02  5018.8  489.00  5053.5  488.38  5062.0  489.31
  5064.6  491.04  5067.8  493.12  5089.3  496.93  5169.6  500.26  5220.5  500.96
#Mann=5,-1,0
  4447.7    0.16       0  4780.2     0.1       0  4919.0    0.16       0
  5000.2    0.07       0  5006.2    0.16       0
Bank Sta=4716.1,5064.6
Exp/Cntr=0.3,0.1

Type RM Length L Ch R = 1,19266,490,490,490
BEGIN DESCRIPTION:
XS3006A
END DESCRIPTION:
XS GIS Cut Line= 4
      2782919.34      7067973.27      2782714.48      7067737.17
      2782686.71      7067594.81      2782530.43      7067435.07
#Sta/Elev= 30
  4612.6  499.52  4714.0  498.91  4749.1  498.16  4777.6  499.19  4791.9  499.03
  4806.1  497.92  4834.6  497.31  4952.7  489.80  4978.3  487.73  4988.5  484.16
  4997.2  484.24  4999.3  482.52  4999.8  481.72  5004.8  481.72  5005.3  482.52
  5008.9  486.68  5019.1  485.74  5029.3  487.12  5039.5  487.63  5092.5  487.69
  5106.7  489.31  5118.1  489.80  5163.3  490.98  5170.3  491.77  5177.4  491.48
  5184.4  492.32  5191.5  491.75  5234.0  492.93  5283.4  495.34  5293.7  495.08
#Mann=3,-1,0
  4612.6    0.16       0  4999.3    0.07       0  5005.3    0.16       0
Bank Sta=4952.7,5118.1
Exp/Cntr=0.3,0.1

Type RM Length L Ch R = 1,18776,175,175,175
BEGIN DESCRIPTION:
XS3007A
END DESCRIPTION:
XS GIS Cut Line= 3
      2783124.18      7067587.85      2782825.59      7067389.95
      2782518.27      7067331.24
#Sta/Elev= 30
  4573.8  499.39  4718.7  497.78  4763.9  496.46  4827.0  493.38  4836.1  489.69
  4842.1  492.04  4847.2  488.48  4857.1  484.97  4872.2  485.32  4878.2  487.04
  4893.2  484.30  4899.2  485.77  4908.3  484.25  4929.3  485.90  4934.9  485.26
  4953.0  486.44  4986.8  486.30  4993.7  484.22  5000.9  480.00  5001.4  479.20
  5006.4  479.20  5006.9  480.00  5014.1  485.23  5038.9  486.37  5054.8  486.21
  5075.2  484.44  5091.0  488.93  5098.2  488.48  5115.9  490.71  5244.9  497.13
#Mann=3,-1,0
  4573.8    0.16       0  5000.9    0.07       0  5006.9    0.16       0
Bank Sta=4847.2,5098.2
Exp/Cntr=0.3,0.1

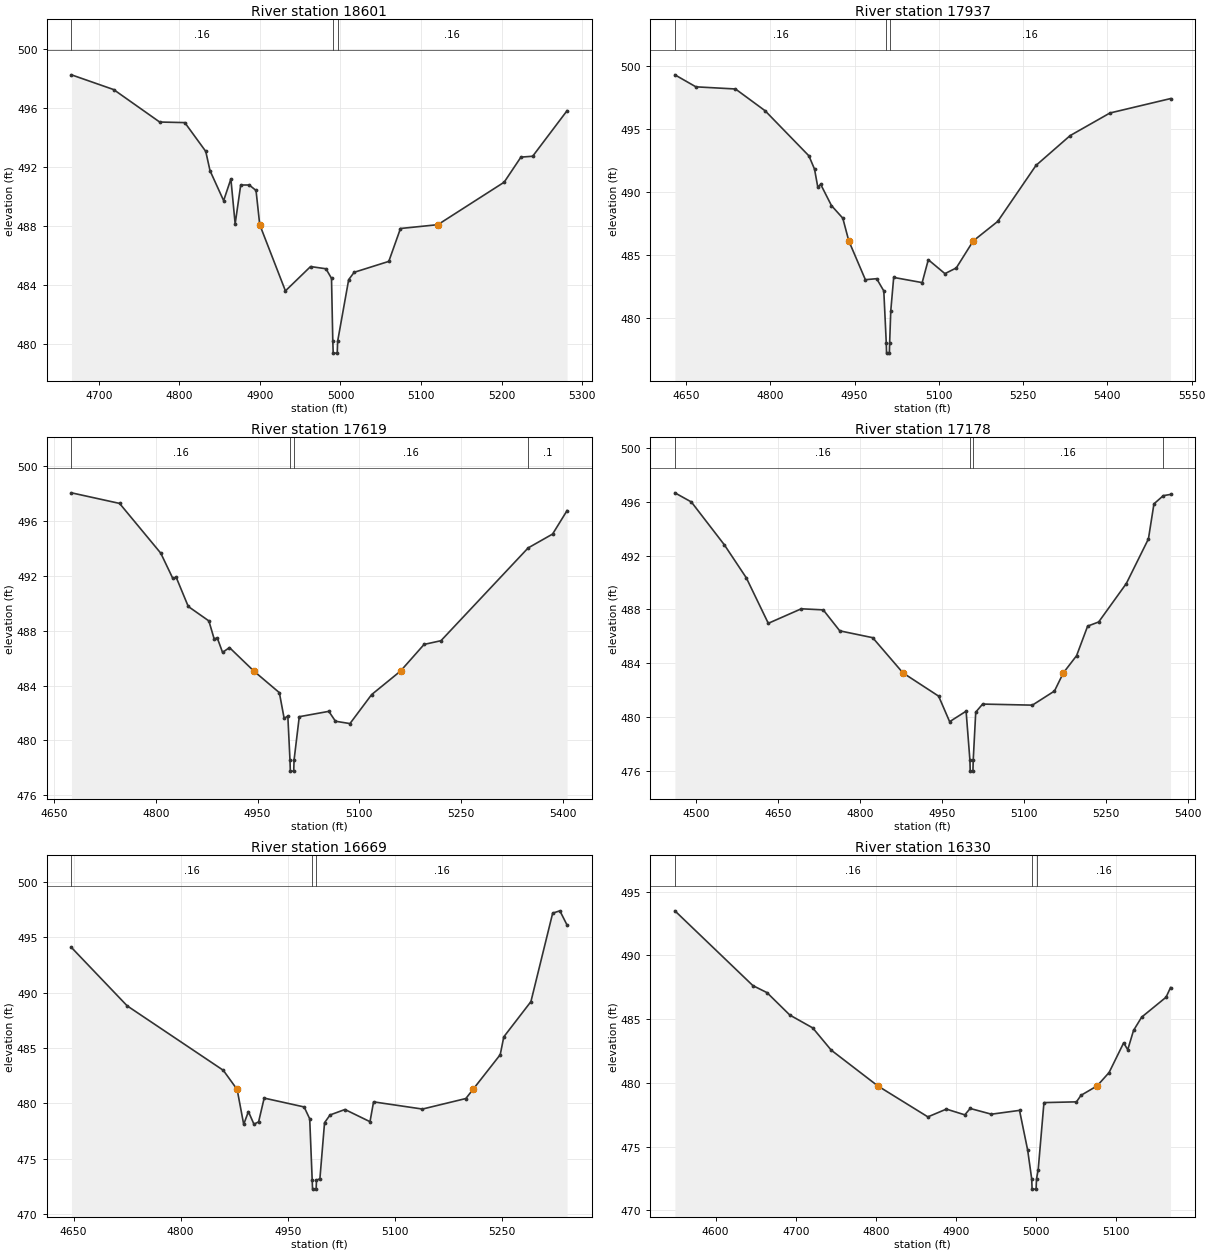
Type RM Length L Ch R = 1,18601,664,664,664
BEGIN DESCRIPTION:
XS3008A
END DESCRIPTION:
XS GIS Cut Line= 3
      2783193.63      7067365.64      2782881.15      7067258.00
      2782655.49      7067084.42
#Sta/Elev= 30
  4666.1  498.22  4718.5  497.22  4775.6  495.02  4806.8  494.98  4832.8  493.03
  4838.1  491.72  4855.0  489.69  4864.0  491.16  4869.3  488.11  4876.2  490.75
  4886.8  490.75  4895.2  490.38  4899.8  488.06  4931.7  483.57  4962.9  485.22
  4982.0  485.07  4988.9  484.42  4990.5  480.15  4991.0  479.35  4996.0  479.35
  4996.5  480.15  5010.2  484.33  5017.0  484.83  5060.0  485.57  5074.5  487.80
  5120.9  488.06  5203.2  490.94  5224.0  492.64  5238.6  492.70  5281.3  495.79
#Mann=3,-1,0
  4666.1    0.16       0  4990.5    0.07       0  4996.5    0.16       0
Bank Sta=4899.8,5120.9
Exp/Cntr=0.3,0.1

Type RM Length L Ch R = 1,17937,318,318,318
BEGIN DESCRIPTION:
SLOUGH CREEK 4.0
END DESCRIPTION:
XS GIS Cut Line= 3
      2783432.21      7066876.22      2783062.42      7066838.03
      2782558.61      7066919.40
#Sta/Elev= 30
  4630.3  499.28  4667.7  498.33  4738.1  498.16  4790.8  496.44  4868.8  492.87
  4878.8  491.82  4884.7  490.38  4889.7  490.62  4909.0  488.93  4929.1  487.94
  4939.8  486.14  4969.3  483.07  4989.4  483.15  5002.1  482.18  5006.5  478.06
  5007.0  477.26  5012.0  477.26  5012.5  478.06  5014.5  480.60  5019.7  483.25
  5070.4  482.84  5081.3  484.65  5110.9  483.55  5131.1  484.00  5161.3  486.14
  5204.8  487.68  5272.9  492.11  5333.7  494.47  5404.6  496.26  5512.4  497.40
#Mann=3,-1,0
  4630.3    0.16       0  5006.5    0.07       0  5012.5    0.16       0
Bank Sta=4939.8,5161.3
Exp/Cntr=0.3,0.1

Type RM Length L Ch R = 1,17619,441,441,441
BEGIN DESCRIPTION:
SLOUGH CREEK 3.0
END DESCRIPTION:
XS GIS Cut Line= 3
      2783475.01      7066675.00      2783175.00      7066625.00
      2782774.95      7066474.98
#Sta/Elev= 30
  4675.3  498.02  4746.3  497.25  4807.1  493.63  4824.8  491.80  4829.9  491.87
  4847.7  489.75  4878.1  488.70  4885.7  487.42  4890.7  487.43  4898.3  486.41
  4908.5  486.76  4944.5  485.05  4982.1  483.48  4989.2  481.60  4994.6  481.78
  4997.8  478.57  4998.3  477.77  5003.3  477.77  5003.8  478.57  5011.5  481.73
  5055.1  482.12  5064.9  481.40  5086.3  481.23  5118.3  483.34  5160.9  485.05
  5195.7  486.99  5220.6  487.26  5349.2  494.01  5385.3  495.02  5406.7  496.73
#Mann=4,-1,0
  4675.3    0.16       0  4997.8    0.07       0  5003.8    0.16       0
  5349.2     0.1       0
Bank Sta=4944.5,5160.9
Exp/Cntr=0.3,0.1

Type RM Length L Ch R = 1,17178,509,509,509
BEGIN DESCRIPTION:
SLOUGH CREEK 2.0
END DESCRIPTION:
XS GIS Cut Line= 3
      2783875.02      7066375.00      2783325.00      7066325.00
      2782975.04      7066275.01
#Sta/Elev= 30
  4461.5  496.67  4491.6  495.99  4551.9  492.80  4592.1  490.34  4632.2  486.96
  4692.5  488.04  4732.6  487.96  4762.8  486.40  4823.0  485.89  4878.3  483.27
  4943.5  481.54  4963.6  479.64  4993.7  480.42  5000.7  476.76  5001.2  475.96
  5006.2  475.96  5006.7  476.76  5011.3  480.35  5023.9  480.95  5114.8  480.87
  5155.2  481.92  5171.4  483.27  5195.6  484.55  5215.8  486.75  5236.0  487.06
  5286.5  489.92  5326.9  493.24  5337.0  495.85  5354.1  496.46  5367.3  496.55
#Mann=4,-1,0
  4461.5    0.16       0  5000.7    0.07       0  5006.7    0.16       0
  5354.1     0.1       0
Bank Sta=4878.3,5171.4
Exp/Cntr=0.3,0.1

Type RM Length L Ch R = 1,16669,339,339,339
BEGIN DESCRIPTION:
SLOUGH CREEK 1.0
END DESCRIPTION:
XS GIS Cut Line= 3
      2783824.98      7066324.98      2783525.00      7066075.00
      2783225.03      7066025.00
#Sta/Elev= 30
  4647.0  494.08  4725.1  488.81  4859.8  482.99  4879.2  481.26  4888.4  478.11
  4895.0  479.26  4902.8  478.12  4909.3  478.34  4917.1  480.48  4973.1  479.68
  4980.9  478.61  4984.4  473.06  4984.9  472.26  4989.9  472.26  4990.4  473.06
  4995.2  473.20  5001.7  478.26  5009.5  478.96  5030.3  479.45  5065.4  478.35
  5070.4  480.14  5138.9  479.49  5199.7  480.44  5209.7  481.26  5247.9  484.40
  5252.9  486.01  5290.9  489.19  5321.4  497.18  5331.5  497.39  5341.6  496.10
#Mann=3,-1,0
  4647.0    0.16       0  4984.4    0.07       0  4990.4    0.16       0
Bank Sta=4879.2,5209.7
Exp/Cntr=0.3,0.1

Type RM Length L Ch R = 1,16330,271,271,271
BEGIN DESCRIPTION:
XS3015A
END DESCRIPTION:
XS GIS Cut Line= 3
      2784050.41      7066089.60      2783707.54      7065933.35
      2783469.54      7065890.08
#Sta/Elev= 30
  4549.2  493.50  4646.6  487.63  4664.2  487.08  4692.7  485.32  4721.3  484.31
  4744.3  482.57  4802.5  479.76  4865.0  477.33  4888.1  477.94  4911.1  477.49
  4917.8  477.99  4944.3  477.54  4979.4  477.84  4989.6  474.71  4994.6  472.46
  4995.1  471.66  5000.1  471.66  5000.6  472.46  5002.7  473.18  5009.9  478.45
  5050.5  478.51  5056.1  479.02  5076.2  479.76  5091.2  480.81  5109.4  483.14
  5114.5  482.60  5121.7  484.11  5131.9  485.16  5162.3  486.72  5167.9  487.48
#Mann=3,-1,0
  4549.2    0.16       0  4994.6    0.07       0  5000.6    0.16       0
Bank Sta=4802.5,5076.2
Exp/Cntr=0.3,0.1

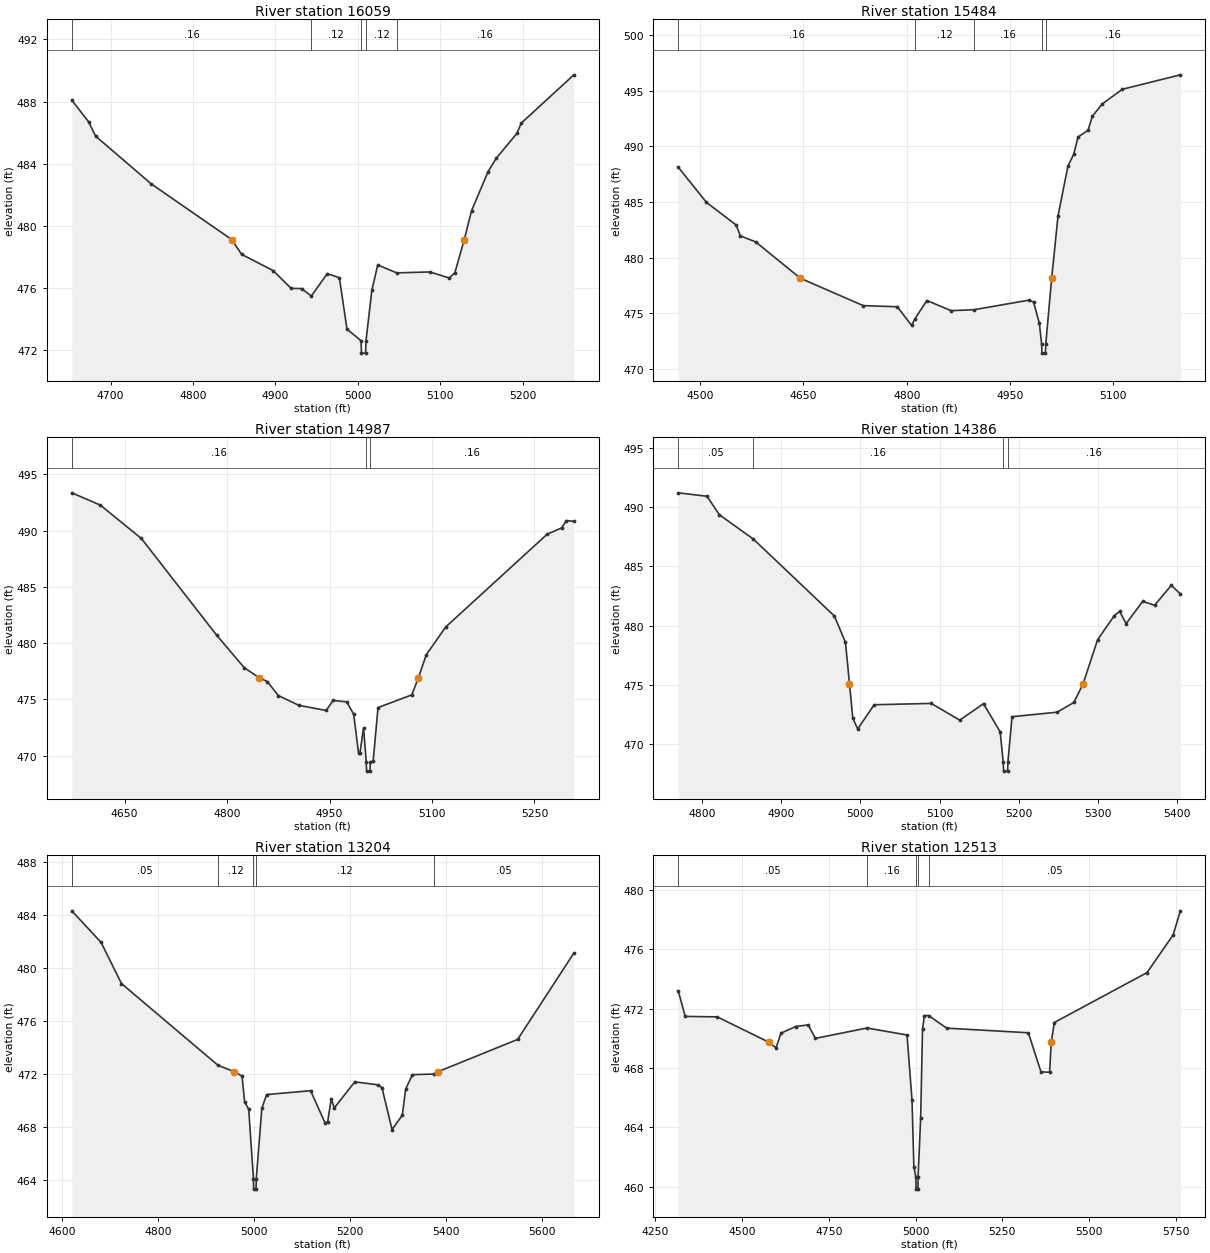
Type RM Length L Ch R = 1,16059,575,575,575
BEGIN DESCRIPTION:
XS3014A
END DESCRIPTION:
XS GIS Cut Line= 3
      2784050.40      7065868.24      2783768.30      7065716.34
      2783481.80      7065681.61
#Sta/Elev= 30
  4652.9  488.09  4673.2  486.70  4681.8  485.77  4749.4  482.69  4846.8  479.11
  4859.0  478.15  4897.1  477.11  4919.0  475.96  4931.6  475.95  4943.5  475.47
  4962.8  476.91  4977.5  476.65  4986.7  473.34  5003.8  472.59  5004.3  471.79
  5009.3  471.79  5009.8  472.59  5016.9  475.84  5024.0  477.47  5047.1  476.96
  5087.4  477.02  5110.8  476.63  5117.6  476.97  5129.0  479.11  5137.8  480.96
  5157.9  483.49  5168.0  484.36  5192.7  485.94  5198.2  486.61  5261.9  489.72
#Mann=5,-1,0
  4652.9    0.16       0  4943.5    0.12       0  5003.8    0.07       0
  5009.8    0.12       0  5047.1    0.16       0
Bank Sta=4846.8,5129
Exp/Cntr=0.3,0.1

Type RM Length L Ch R = 1,15484,497,497,497
BEGIN DESCRIPTION:
XS3013A
END DESCRIPTION:
XS GIS Cut Line= 3
      2784085.12      7065772.73      2783763.96      7065386.48
      2783583.26      7065248.80
#Sta/Elev= 30
  4468.0  488.13  4508.9  484.97  4551.9  482.94  4558.4  481.95  4580.5  481.41
  4645.5  478.14  4736.8  475.68  4786.3  475.58  4807.1  473.90  4811.9  474.49
  4829.2  476.14  4864.4  475.23  4897.6  475.31  4978.2  476.18  4984.4  475.98
  4992.7  474.09  4996.0  472.21  4996.5  471.41  5001.5  471.41  5002.0  472.21
  5010.6  478.14  5019.8  483.75  5034.3  488.24  5042.6  489.28  5048.9  490.84
  5063.4  491.44  5069.7  492.71  5084.2  493.82  5113.3  495.13  5197.5  496.43
#Mann=5,-1,0
  4468.0    0.16       0  4811.9    0.12       0  4897.6    0.16       0
  4996.0    0.07       0  5002.0    0.16       0
Bank Sta=4645.5,5010.6
Exp/Cntr=0.3,0.1

Type RM Length L Ch R = 1,14987,601,601,601
BEGIN DESCRIPTION:
XS3012A
END DESCRIPTION:
XS GIS Cut Line= 3
      2784167.61      7065746.71      2784141.57      7065325.71
      2783920.25      7065104.39
#Sta/Elev= 30
  4572.8  493.37  4614.6  492.28  4674.7  489.31  4784.9  480.71  4825.0  477.84
  4846.8  476.94  4859.0  476.59  4875.1  475.35  4905.1  474.48  4945.2  474.02
  4955.2  474.91  4975.3  474.79  4985.3  473.69  4992.5  470.25  4994.6  470.25
  4999.8  472.47  5003.8  469.43  5004.3  468.63  5009.3  468.63  5009.8  469.43
  5013.9  469.53  5021.0  474.28  5070.5  475.41  5080.1  476.94  5091.7  478.98
  5120.0  481.44  5268.5  489.69  5289.7  490.25  5296.7  490.90  5307.6  490.84
#Mann=3,-1,0
  4572.8    0.16       0  5003.8    0.07       0  5009.8    0.16       0
Bank Sta=4846.8,5080.1
Exp/Cntr=0.3,0.1

Type RM Length L Ch R = 1,14386,1182,1182,1182
BEGIN DESCRIPTION:
XS3011A
END DESCRIPTION:
XS GIS Cut Line= 3
      2784566.93      7065434.25      2784449.73      7065238.91
      2784111.17      7065013.20
#Sta/Elev= 30
  4769.7  491.21  4806.1  490.92  4821.7  489.36  4864.7  487.31  4967.1  480.82
  4981.1  478.60  4986.2  475.10  4990.4  472.19  4996.6  471.30  5017.4  473.34
  5089.5  473.45  5125.6  472.04  5155.6  473.43  5176.6  471.06  5180.5  468.54
  5181.0  467.74  5186.0  467.74  5186.5  468.54  5191.7  472.33  5248.7  472.71
  5269.8  473.53  5281.5  475.10  5299.8  478.82  5320.9  480.85  5327.7  481.21
  5335.9  480.18  5356.9  482.06  5371.9  481.73  5393.0  483.41  5404.4  482.69
#Mann=4,-1,0
  4769.7    0.05       0  4864.7    0.16       0  5180.5    0.07       0
  5186.5    0.16       0
Bank Sta=4986.2,5281.5
Exp/Cntr=0.3,0.1

Type RM Length L Ch R = 1,13204,691,691,691
BEGIN DESCRIPTION:
XS3010A
END DESCRIPTION:
XS GIS Cut Line= 4
      2784679.76      7065473.28      2784792.61      7065121.72
      2784762.23      7064965.47      2784410.68      7064583.54
#Sta/Elev= 30
  4619.4  484.32  4680.5  481.94  4723.1  478.83  4924.4  472.66  4958.8  472.17
  4974.7  471.84  4980.0  469.90  4988.6  469.33  4998.4  464.11  4998.9  463.31
  5003.9  463.31  5004.4  464.11  5015.9  469.41  5026.0  470.45  5117.7  470.74
  5147.8  468.31  5153.2  468.37  5160.6  470.10  5167.3  469.45  5209.9  471.41
  5259.2  471.18  5266.6  470.96  5287.6  467.81  5309.1  468.89  5315.9  470.85
  5330.1  471.95  5375.5  472.00  5383.0  472.17  5549.6  474.61  5666.9  481.13
#Mann=5,-1,0
  4619.4    0.05       0  4924.4    0.12       0  4998.4    0.07       0
  5004.4    0.12       0  5375.5    0.05       0
Bank Sta=4958.8,5383
Exp/Cntr=0.3,0.1

Type RM Length L Ch R = 1,12513,0,0,0
BEGIN DESCRIPTION:
XS3009A
END DESCRIPTION:
XS GIS Cut Line= 3
      2785676.30      7065311.84      2785231.84      7064825.71
      2784495.70      7064547.92
#Sta/Elev= 30
  4316.8  473.20  4336.9  471.47  4428.8  471.44  4577.3  469.74  4598.4  469.35
  4612.6  470.34  4655.1  470.79  4690.9  470.90  4711.8  469.99  4860.3  470.69
  4975.5  470.22  4989.9  465.82  4995.2  461.35  5001.0  460.64  5001.5  459.84
  5006.8  459.84  5007.3  460.64  5014.8  464.66  5020.1  470.62  5025.6  471.53
  5037.5  471.53  5089.7  470.68  5324.8  470.37  5361.1  467.74  5385.9  467.71
  5390.8  469.74  5399.6  471.06  5666.5  474.42  5741.7  476.96  5762.3  478.58
#Mann=5,-1,0
  4316.8    0.05       0  4860.3    0.16       0  5001.0    0.07       0
  5007.3    0.16       0  5037.5    0.05       0
Bank Sta=4577.3,5390.8
Exp/Cntr=0.3,0.1

Chan Stop Cuts=-1