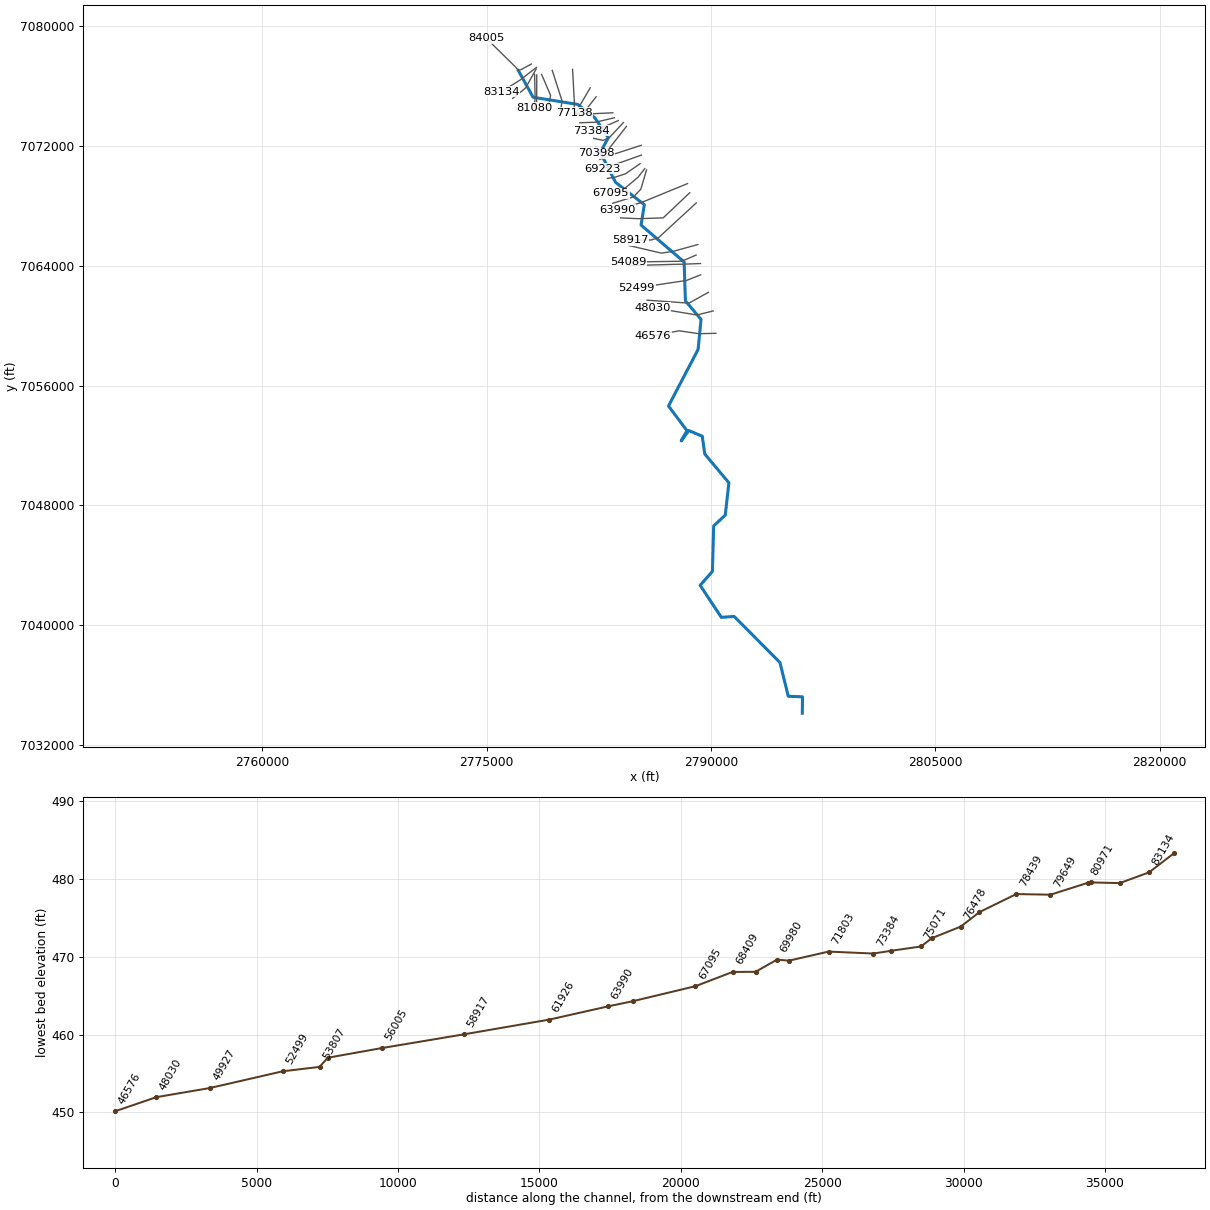
--- TURKEY CREEK.prj (project) ---

Proj Title=TURKEY CREEK Base Level Engineering
Current Plan=p01
Default Exp/Contr=0.3,0.1
English Units
Geom File=g01
Flow File=f01
Plan File=p01
BEGIN DESCRIPTION:
TURKEY CREEK
END DESCRIPTION:

--- TURKEY CREEK.p01 (plan) ---

Plan Title=Multiple Run
Short Identifier=Multiple
Geom File=g01
Flow File=f01
Subcritical Flow
K Sum by GR= 0
Std Step Tol= 0.01
Critical Tol= 0.01
Num of Std Step Trials= 20
Max Error Tol= 0.3
Flow Tol Ratio= 0.001
Split Flow NTrial= 30
Split Flow Tol= 0.02
Split Flow Ratio= 0.02
Log Output Level= 0
Friction Slope Method= 1
Unsteady Friction Slope Method= 2
Unsteady Bridges Friction Slope Method= 1
Parabolic Critical Depth
Global Vel Dist=  1 , 1 , 1
Global Log Level= 0
CheckData=True
Encroach Param= -1, 0, 0, 0
BEGIN DESCRIPTION:
Multiple Run
END DESCRIPTION:

--- TURKEY CREEK.f01 (steady flow) ---

Flow Title=Multiple
Program Version=5.07
Number of Profiles= 7
Profile Names=10-year,25-year,50-year,1pct_min,100-year,1pct_plu,500-year
River Rch & RM=TURKEY CREEK,Reach-1         ,84005
    5010    7225    9140    5691   11355   22657   17515
River Rch & RM=TURKEY CREEK,Reach-1         ,77138
    4975    7150    9023    5604   11181   22309   17156
River Rch & RM=TURKEY CREEK,Reach-1         ,70398
    5138    7367    9283    5754   11482   22909   17552
River Rch & RM=TURKEY CREEK,Reach-1         ,64896
    5285    7579    9550    5920   11812   23567   18053
River Rch & RM=TURKEY CREEK,Reach-1         ,58917
    6537    9437   11949    7439   14844   29617   22884
River Rch & RM=TURKEY CREEK,Reach-1         ,53807
    6664    9616   12170    7573   15111   30151   23273
River Rch & RM=TURKEY CREEK,Reach-1         ,48030
    6769    9759   12344    7677   15317   30562   23559
River Rch & RM=TURKEY CREEK,Reach-1         ,37938
    7075   10218   12942    8059   16080   32084   24794
River Rch & RM=TURKEY CREEK,Reach-1         ,37101
    7287   10500   13278    8254   16468   32859   25305
River Rch & RM=TURKEY CREEK,Reach-1         ,28491
    7326   10542   13319    8272   16504   32930   25317
River Rch & RM=TURKEY CREEK,Reach-1         ,22579
    7428   10692   13512    8395   16750   33420   25713
River Rch & RM=TURKEY CREEK,Reach-1         ,14557
    7443   10701   13512    8388   16736   33393   25653
Boundary for River Rch & Prof#=TURKEY CREEK,Reach-1         , 1
Up Type= 0
Dn Type= 3
Dn Slope=0.00091
Boundary for River Rch & Prof#=TURKEY CREEK,Reach-1         , 2
Up Type= 0
Dn Type= 3
Dn Slope=0.00091
Boundary for River Rch & Prof#=TURKEY CREEK,Reach-1         , 3
Up Type= 0
Dn Type= 3
Dn Slope=0.00091
Boundary for River Rch & Prof#=TURKEY CREEK,Reach-1         , 4
Up Type= 0
Dn Type= 3
Dn Slope=0.00091
Boundary for River Rch & Prof#=TURKEY CREEK,Reach-1         , 5
Up Type= 0
Dn Type= 3
Dn Slope=0.00091
Boundary for River Rch & Prof#=TURKEY CREEK,Reach-1         , 6
Up Type= 0
Dn Type= 3
Dn Slope=0.00091
Boundary for River Rch & Prof#=TURKEY CREEK,Reach-1         , 7
Up Type= 0
Dn Type= 3
Dn Slope=0.00091
DSS Import GetInterval= 0
DSS Import GetPeak= 0
DSS Import FillOption= 0

--- TURKEY CREEK.g01 (geometry) ---

Geom Title=Existing Conditions

River Reach=TURKEY CREEK,Reach-1
Reach XY= 30
      2777115.59      7077040.71      2778102.89      7075255.56
      2781084.40      7074777.53      2782227.70      7073887.03
      2783132.58      7072549.47      2782596.37      7071570.10
      2783617.86      7069571.43      2785542.67      7068078.79
      2785321.68      7066717.72      2788201.91      7064252.72
      2788287.47      7061656.13      2789334.03      7060415.41
      2789135.17      7058404.89      2787156.63      7054630.82
      2788392.97      7052980.09      2788005.75      7052300.55
      2788510.90      7052989.46      2789415.59      7052610.71
      2789580.61      7051428.28      2791195.85      7049500.59
      2790952.95      7047341.75      2790177.11      7046615.06
      2790093.28      7043578.04      2789272.27      7042651.46
      2790691.72      7040513.34      2791550.75      7040572.70
      2794609.53      7037495.17      2795167.00      7035240.15
      2796118.70      7035204.10      2796105.59      7034110.71

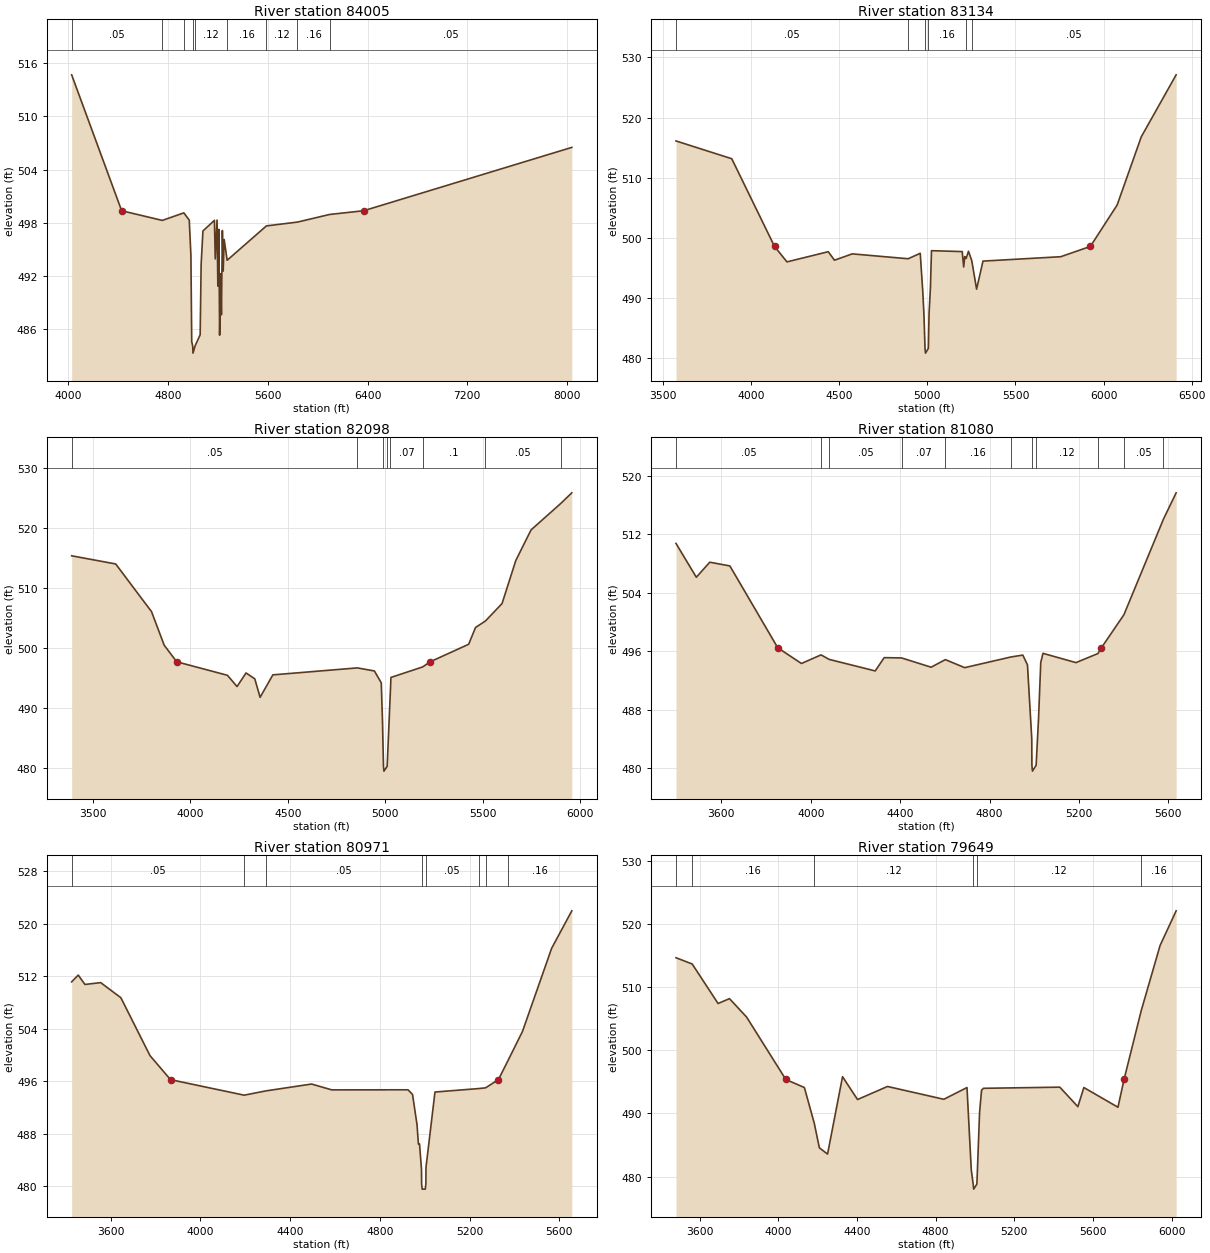
Type RM Length L Ch R = 1,84005,871,871,871
BEGIN DESCRIPTION:
XS3018A
END DESCRIPTION:
XS GIS Cut Line= 6
      2777984.02      7077474.71      2777324.34      7077113.62
      2777115.57      7077038.72      2777110.97      7077058.06
      2776927.81      7077277.29      2774975.84      7079191.23
#Sta/Elev= 30
  4025.9  514.68  4427.0  499.36  4753.2  498.27  4926.1  499.12  4969.5  498.30
  4982.8  494.32  4989.3  484.60  4997.1  484.11  4999.6  483.31  5015.9  484.11
  5057.0  485.38  5064.8  493.32  5079.2  497.08  5171.6  498.28  5178.1  493.93
  5192.4  498.31  5198.9  490.87  5206.7  497.26  5213.2  485.34  5221.0  492.27
  5227.5  487.63  5235.3  497.13  5241.8  492.56  5249.6  496.12  5273.6  493.78
  5588.6  497.65  5837.4  498.08  6095.8  498.94  6369.1  499.36  8039.3  506.50
#Mann=9,-1,0
  4025.9    0.05       0  4753.2    0.07       0  4926.1    0.12       0
  4997.1    0.07       0  5015.9    0.12       0  5273.6    0.16       0
  5588.6    0.12       0  5837.4    0.16       0  6095.8    0.05       0
Bank Sta=4427,6369.1
Exp/Cntr=0.3,0.1

Type RM Length L Ch R = 1,83134,1036,1036,1036
BEGIN DESCRIPTION:
Mapping XS 9903ad90
END DESCRIPTION:
XS GIS Cut Line= 3
      2778324.85      7077248.59      2777270.13      7076428.26
      2775994.11      7075634.00
#Sta/Elev= 30
  3572.8  516.11  3889.3  513.16  4132.0  498.60  4202.7  496.03  4437.1  497.72
  4472.4  496.31  4573.4  497.36  4890.9  496.55  4959.3  497.46  4973.9  491.03
  4980.6  487.09  4986.5  481.68  4989.0  480.88  5005.4  481.68  5009.3  487.40
  5017.2  491.77  5023.1  497.89  5197.7  497.74  5206.0  495.19  5211.9  496.91
  5219.7  496.59  5233.2  497.80  5251.8  496.24  5279.2  491.50  5315.5  496.16
  5757.2  496.89  5925.2  498.60  6077.1  505.47  6214.0  516.79  6412.0  527.09
#Mann=6,-1,0
  3572.8    0.05       0  4890.9    0.16       0  4986.5    0.07       0
  5005.4    0.16       0  5219.7    0.16       0  5251.8    0.05       0
Bank Sta=4132,5925.2
Exp/Cntr=0.3,0.1

Type RM Length L Ch R = 1,82098,1018,1018,1018
BEGIN DESCRIPTION:
Mapping XS 9a3d250e
END DESCRIPTION:
XS GIS Cut Line= 3
      2778311.80      7077144.40      2777595.65      7075868.36
      2776737.39      7075179.15
#Sta/Elev= 30
  3392.5  515.40  3618.2  514.04  3801.9  506.09  3866.9  500.49  3931.0  497.73
  4190.9  495.48  4240.4  493.60  4286.3  495.87  4331.2  494.89  4358.6  491.81
  4423.9  495.55  4857.2  496.71  4944.5  496.20  4979.7  494.22  4986.1  487.70
  4991.0  480.30  4993.5  479.50  5009.9  480.30  5026.9  493.19  5029.3  495.12
  5191.8  496.87  5230.6  497.73  5427.7  500.65  5462.9  503.45  5513.7  504.53
  5598.9  507.44  5669.3  514.61  5747.7  519.72  5901.0  524.16  5956.5  525.90
#Mann=8,-1,0
  3392.5    0.05       0  4857.2    0.12       0  4991.0    0.07       0
  5009.9    0.12       0  5026.9    0.07       0  5191.8     0.1       0
  5513.7    0.05       0  5901.0    0.16       0
Bank Sta=3931,5230.6
Exp/Cntr=0.3,0.1

Type RM Length L Ch R = 1,81080,109,109,109
BEGIN DESCRIPTION:
XS3017A
END DESCRIPTION:
XS GIS Cut Line= 3
      2778202.64      7076785.92      2778239.10      7075218.25
      2778181.81      7074551.60
#Sta/Elev= 30
  3397.4  510.77  3488.3  506.14  3548.4  508.20  3638.4  507.69  3852.6  496.48
  3958.5  494.33  4046.1  495.51  4082.7  494.89  4288.6  493.31  4328.6  495.13
  4406.7  495.09  4538.6  493.82  4602.3  494.86  4688.7  493.76  4895.6  495.22
  4948.7  495.48  4969.6  494.14  4988.8  484.03  4989.4  480.39  4991.9  479.59
  5008.3  480.39  5018.9  486.65  5029.0  494.46  5039.0  495.72  5186.6  494.45
  5284.7  495.69  5300.3  496.48  5401.1  501.01  5577.9  514.10  5634.6  517.70
#Mann=11,-1,0
  3397.4    0.05       0  4046.1    0.16       0  4082.7    0.05       0
  4406.7    0.07       0  4602.3    0.16       0  4895.6    0.12       0
  4989.4    0.07       0  5008.3    0.12       0  5284.7    0.16       0
  5401.1    0.05       0  5577.9    0.16       0
Bank Sta=3852.6,5300.3
Exp/Cntr=0.3,0.1

Type RM Length L Ch R = 1,80971,1322,1322,1322
BEGIN DESCRIPTION:
XS3016A
END DESCRIPTION:
XS GIS Cut Line= 3
      2778348.48      7076744.25      2778343.27      7075197.41
      2778338.06      7074515.08
#Sta/Elev= 30
  3426.2  511.16  3455.4  512.19  3485.4  510.76  3555.4  511.04  3645.4  508.74
  3775.4  499.90  3866.8  496.24  4195.1  493.87  4292.9  494.53  4495.5  495.57
  4585.5  494.68  4925.5  494.69  4945.5  493.98  4965.5  489.37  4971.7  486.42
  4976.7  486.42  4985.5  482.51  4986.0  480.34  4988.5  479.54  5002.4  479.54
  5004.9  480.34  5005.5  482.87  5045.5  494.35  5240.4  494.88  5271.2  494.99
  5328.2  496.24  5369.0  499.01  5435.5  503.59  5565.5  516.27  5655.4  521.99
#Mann=8,-1,0
  3426.2    0.05       0  4195.1    0.08       0  4292.9    0.05       0
  4986.0    0.04       0  5004.9    0.05       0  5240.4    0.12       0
  5271.2     0.1       0  5369.0    0.16       0
Bank Sta=3866.8,5328.2
Exp/Cntr=0.3,0.1

Type RM Length L Ch R = 1,79649,1210,1210,1210
BEGIN DESCRIPTION:
TURKEY CREEK 51.0
END DESCRIPTION:
XS GIS Cut Line= 3
      2778675.00      7076775.00      2779275.00      7075375.00
      2779074.99      7074374.96
#Sta/Elev= 30
  3479.8  514.66  3562.1  513.67  3693.8  507.41  3751.8  508.18  3838.8  505.26
  4038.2  495.38  4132.6  494.10  4182.8  488.45  4208.7  484.56  4250.4  483.56
  4326.6  495.82  4402.8  492.20  4555.1  494.27  4841.6  492.24  4959.4  494.10
  4981.2  481.05  4990.8  478.81  4993.3  478.01  5009.7  478.81  5023.4  490.16
  5033.5  493.70  5043.7  493.98  5431.3  494.16  5523.1  491.07  5553.6  494.10
  5727.0  490.98  5758.1  495.39  5845.2  506.27  5941.2  516.60  6022.8  522.09
#Mann=6,-1,0
  3479.8    0.05       0  3562.1    0.16       0  4182.8    0.12       0
  4990.8    0.07       0  5009.7    0.12       0  5845.2    0.16       0
Bank Sta=4038.2,5758.1
Exp/Cntr=0.3,0.1

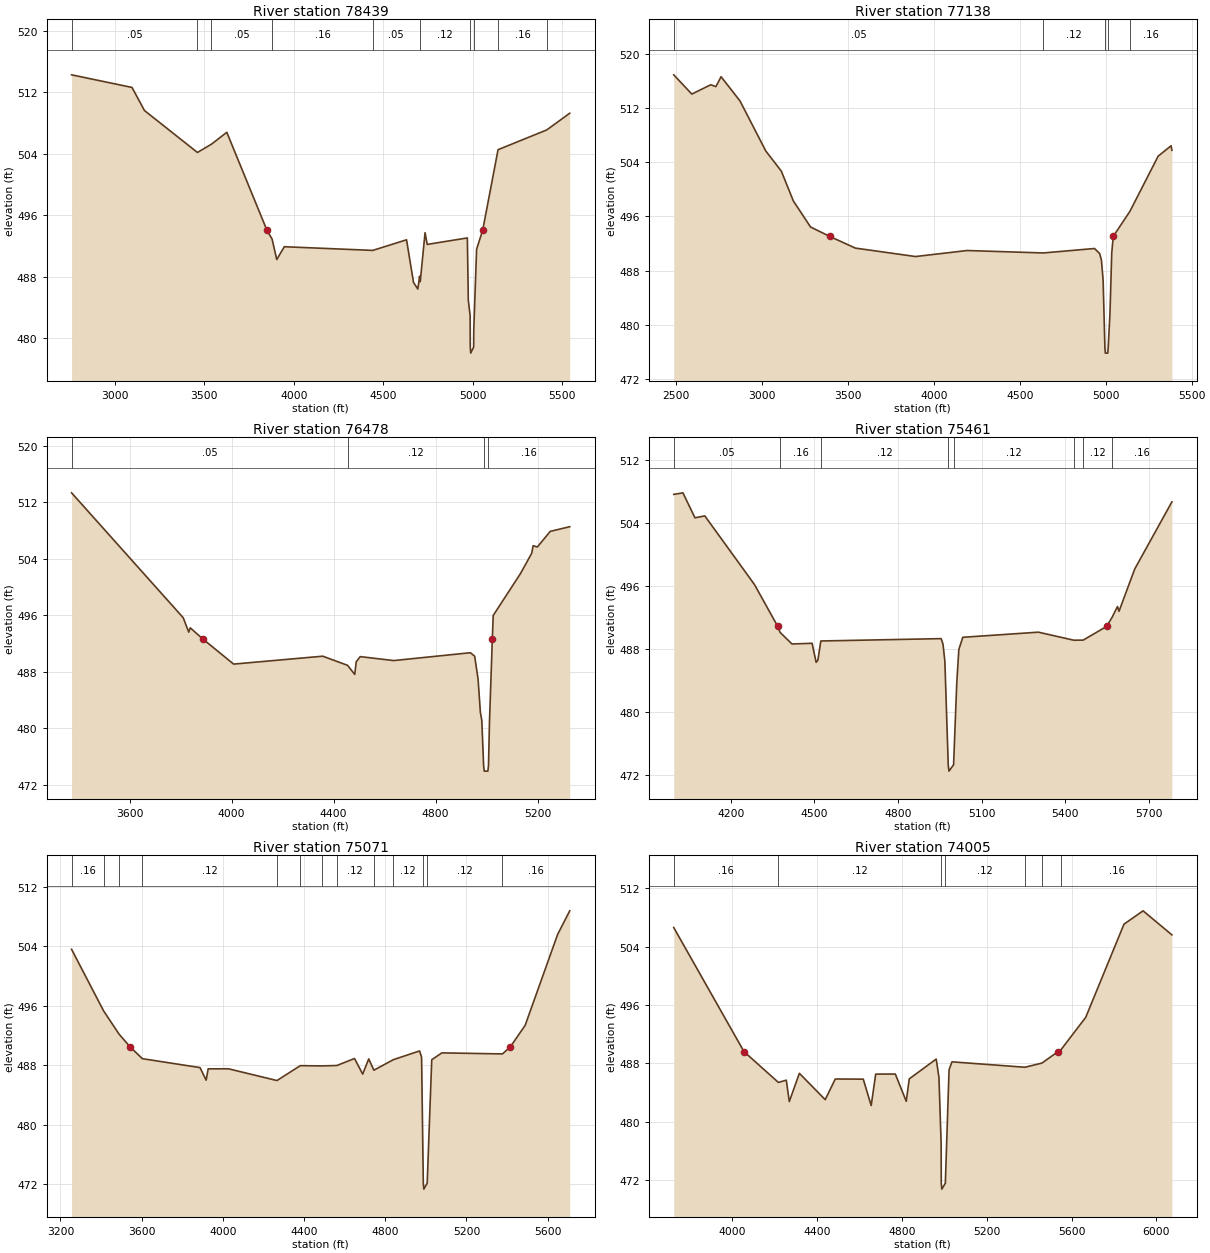
Type RM Length L Ch R = 1,78439,1301,1301,1301
BEGIN DESCRIPTION:
XS3019A
END DESCRIPTION:
XS GIS Cut Line= 3
      2779385.07      7077046.41      2780048.13      7074982.14
      2779930.27      7074378.99
#Sta/Elev= 30
  2758.3  514.26  3095.9  512.62  3165.5  509.62  3461.4  504.17  3539.9  505.25
  3625.4  506.79  3849.1  494.09  3878.4  492.91  3904.6  490.25  3946.5  491.92
  4440.8  491.44  4629.4  492.82  4668.5  487.27  4692.4  486.42  4702.4  488.09
  4705.9  487.37  4732.8  493.74  4744.9  492.22  4969.1  493.06  4974.5  484.95
  4984.7  482.96  4985.4  478.89  4987.9  478.09  5004.3  478.89  5005.0  481.11
  5020.7  491.58  5055.1  494.09  5140.6  504.53  5412.8  507.10  5541.0  509.27
#Mann=10,-1,0
  2758.3    0.05       0  3461.4    0.16       0  3539.9    0.05       0
  3878.4    0.16       0  4440.8    0.05       0  4702.4    0.12       0
  4985.4    0.07       0  5004.3    0.12       0  5140.6    0.16       0
  5412.8    0.05       0
Bank Sta=3849.1,5055.1
Exp/Cntr=0.3,0.1

Type RM Length L Ch R = 1,77138,660,660,660
BEGIN DESCRIPTION:
XS3020A
END DESCRIPTION:
XS GIS Cut Line= 3
      2780743.13      7077120.09      2780867.57      7074822.41
      2780839.80      7074225.20
#Sta/Elev= 30
  2486.1  516.97  2591.3  514.12  2701.5  515.50  2731.5  515.23  2761.6  516.69
  2871.8  513.10  3022.0  505.69  3112.1  502.72  3182.2  498.30  3282.4  494.44
  3393.1  493.06  3542.7  491.32  3893.2  490.07  4193.7  490.96  4636.4  490.60
  4934.7  491.26  4964.7  490.51  4974.8  489.55  4984.8  486.58  4995.2  476.57
  4997.7  475.77  5011.8  475.77  5014.3  476.57  5024.8  481.73  5034.8  490.54
  5043.8  493.06  5140.3  496.74  5305.1  504.93  5380.4  506.47  5385.0  505.80
#Mann=5,-1,0
  2486.1    0.05       0  4636.4    0.12       0  4995.2    0.07       0
  5014.3    0.12       0  5140.3    0.16       0
Bank Sta=3393.1,5043.8
Exp/Cntr=0.3,0.1

Type RM Length L Ch R = 1,76478,1017,1017,1017
BEGIN DESCRIPTION:
XS3021A
END DESCRIPTION:
XS GIS Cut Line= 3
      2781923.15      7075884.95      2781187.02      7074627.97
      2780964.79      7074183.50
#Sta/Elev= 30
  3372.3  513.33  3810.3  495.63  3831.8  493.60  3837.6  494.21  3887.6  492.61
  4007.8  489.07  4357.3  490.19  4454.5  488.90  4482.8  487.61  4488.6  489.40
  4504.3  490.13  4635.4  489.57  4936.3  490.68  4953.1  490.19  4966.5  486.94
  4975.4  482.26  4981.0  481.12  4988.2  474.71  4990.7  473.91  5004.8  473.91
  5007.3  474.71  5011.2  480.91  5022.3  492.61  5025.8  495.96  5132.0  501.85
  5176.7  504.76  5182.3  505.84  5199.0  505.66  5249.4  507.87  5325.9  508.53
#Mann=4,-1,0
  3372.3    0.05       0  4454.5    0.12       0  4988.2    0.07       0
  5007.3    0.16       0
Bank Sta=3887.6,5022.3
Exp/Cntr=0.3,0.1

Type RM Length L Ch R = 1,75461,390,390,390
BEGIN DESCRIPTION:
XS3023A
END DESCRIPTION:
XS GIS Cut Line= 4
      2782318.93      7075287.66      2781728.68      7074537.69
      2781562.02      7074350.19      2781013.40      7074155.75
#Sta/Elev= 30
  3995.5  507.58  4028.4  507.78  4071.7  504.61  4107.0  504.85  4285.0  496.14
  4368.7  490.81  4377.0  490.06  4419.7  488.58  4491.9  488.67  4506.4  486.25
  4512.7  486.52  4523.3  488.96  4955.0  489.26  4961.6  488.55  4968.3  486.37
  4980.4  473.23  4982.9  472.43  4999.5  473.23  5010.9  483.59  5018.4  487.88
  5032.6  489.43  5303.7  490.08  5430.8  489.06  5464.4  489.07  5548.7  490.81
  5568.6  491.99  5587.6  493.34  5593.0  492.73  5649.4  498.10  5782.8  506.63
#Mann=8,-1,0
  3995.5    0.05       0  4377.0    0.16       0  4523.3    0.12       0
  4980.4    0.07       0  4999.5    0.12       0  5430.8    0.16       0
  5464.4    0.12       0  5568.6    0.16       0
Bank Sta=4368.7,5548.7
Exp/Cntr=0.3,0.1

Type RM Length L Ch R = 1,75071,1066,1066,1066
BEGIN DESCRIPTION:
XS3022A
END DESCRIPTION:
XS GIS Cut Line= 3
      2783437.05      7074218.25      2781693.96      7074134.91
      2780985.64      7074114.08
#Sta/Elev= 30
  3254.9  503.60  3412.6  495.32  3488.1  492.22  3542.3  490.50  3603.7  488.89
  3887.7  487.69  3917.7  486.00  3927.7  487.52  4027.8  487.53  4266.6  485.95
  4381.3  487.95  4486.1  487.92  4561.2  487.97  4648.5  488.91  4688.8  486.82
  4718.6  488.86  4743.9  487.34  4840.1  488.76  4968.9  489.93  4978.9  489.10
  4987.4  472.15  4989.9  471.35  5006.5  472.15  5028.9  488.75  5079.0  489.67
  5377.3  489.53  5416.6  490.50  5489.1  493.38  5649.2  505.61  5708.6  508.77
#Mann=13,-1,0
  3254.9    0.16       0  3412.6    0.12       0  3488.1    0.16       0
  3603.7    0.12       0  4266.6    0.16       0  4381.3    0.12       0
  4486.1    0.16       0  4561.2    0.12       0  4743.9    0.16       0
  4840.1    0.12       0  4987.4    0.07       0  5006.5    0.12       0
  5377.3    0.16       0
Bank Sta=3542.3,5416.6
Exp/Cntr=0.3,0.1

Type RM Length L Ch R = 1,74005,621,621,621
BEGIN DESCRIPTION:
XS3024A
END DESCRIPTION:
XS GIS Cut Line= 3
      2783541.15      7073884.91      2782277.30      7073586.30
      2781229.32      7073551.60
#Sta/Elev= 30
  3725.6  506.61  4056.7  489.62  4218.8  485.40  4256.0  485.71  4270.1  482.78
  4317.6  486.65  4439.3  483.04  4486.7  485.87  4618.7  485.85  4655.9  482.24
  4677.3  486.54  4769.7  486.55  4821.1  482.82  4835.4  485.89  4962.3  488.60
  4975.2  486.10  4985.5  477.04  4986.2  471.59  4988.7  470.79  5005.3  471.59
  5022.9  487.13  5036.6  488.22  5380.5  487.48  5460.4  488.05  5536.4  489.62
  5549.7  489.86  5666.9  494.32  5847.0  507.07  5937.0  508.90  6072.8  505.61
#Mann=7,-1,0
  3725.6    0.16       0  4218.8    0.12       0  4986.2    0.07       0
  5005.3    0.12       0  5380.5    0.16       0  5460.4    0.12       0
  5549.7    0.16       0
Bank Sta=4056.7,5536.4
Exp/Cntr=0.3,0.1

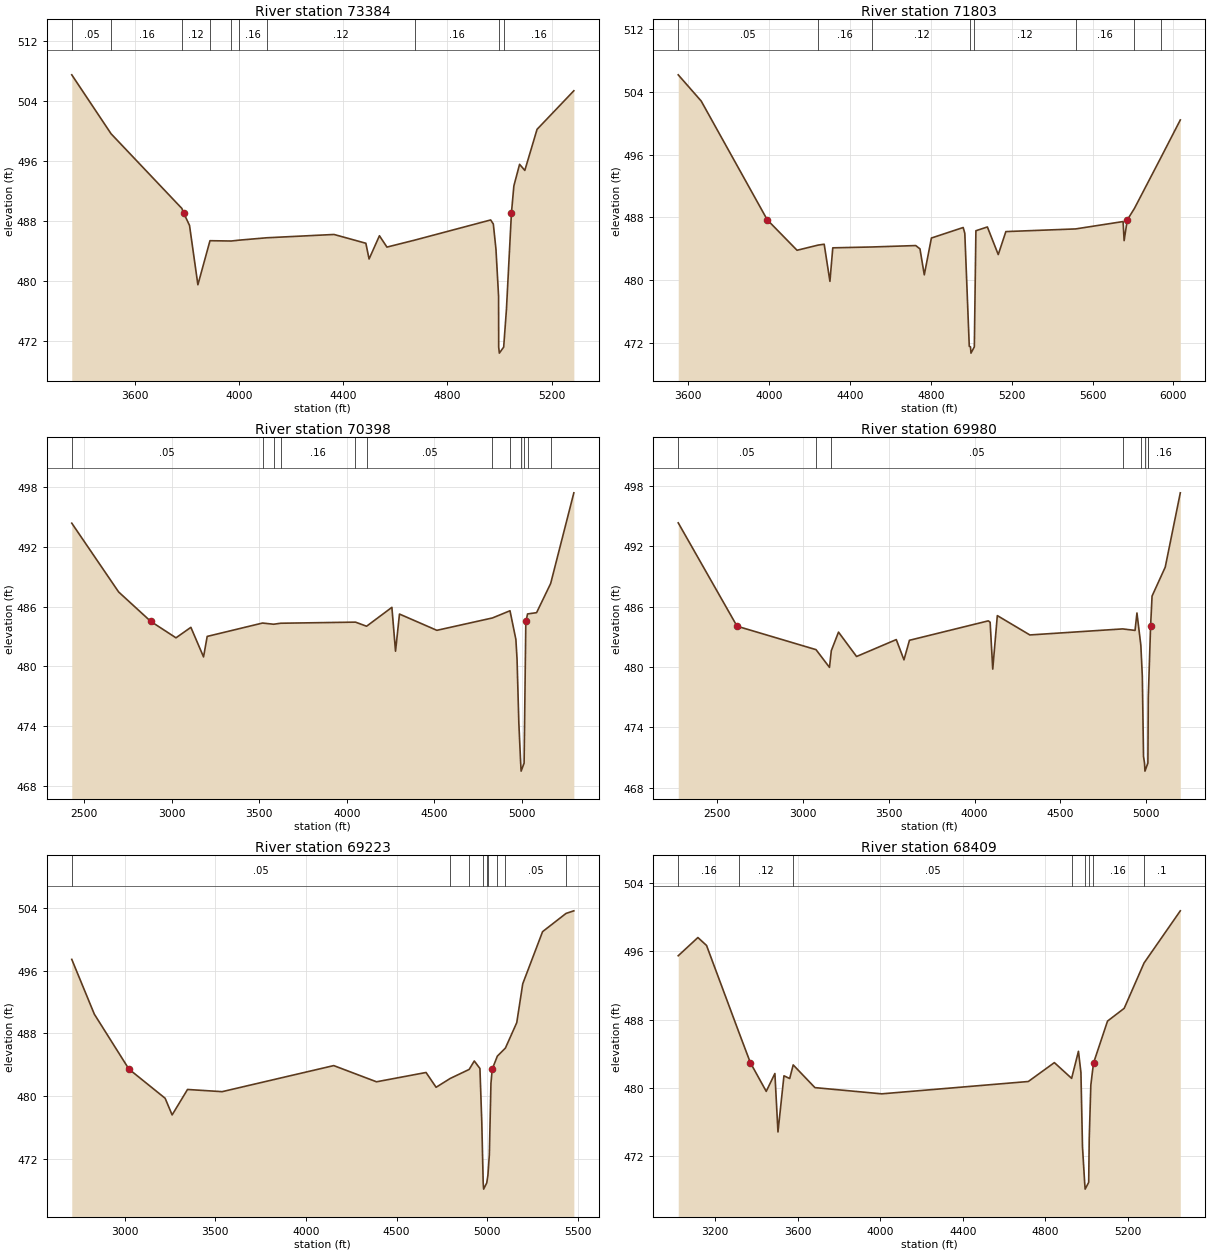
Type RM Length L Ch R = 1,73384,1581,1581,1581
BEGIN DESCRIPTION:
XS3025A
END DESCRIPTION:
XS GIS Cut Line= 3
      2783798.08      7073697.39      2782367.57      7073065.47
      2782008.23      7073024.01
#Sta/Elev= 30
  3359.3  507.45  3510.1  499.61  3781.6  489.68  3788.7  489.05  3810.9  487.43
  3843.0  479.53  3889.4  485.39  3971.3  485.35  3999.9  485.46  4107.1  485.78
  4365.2  486.22  4487.2  485.05  4499.6  482.96  4539.3  486.05  4568.1  484.54
  4677.0  485.49  4965.9  488.15  4976.1  487.61  4986.2  484.26  4996.2  478.04
  4996.7  471.24  4999.2  470.44  5015.8  471.24  5026.4  476.26  5045.5  489.05
  5054.9  492.68  5076.8  495.55  5096.9  494.74  5143.8  500.20  5284.9  505.33
#Mann=10,-1,0
  3359.3    0.05       0  3510.1    0.16       0  3781.6    0.12       0
  3889.4    0.16       0  3971.3    0.12       0  3999.9    0.16       0
  4107.1    0.12       0  4677.0    0.16       0  4996.7    0.07       0
  5015.8    0.16       0
Bank Sta=3788.7,5045.5
Exp/Cntr=0.3,0.1

Type RM Length L Ch R = 1,71803,1405,1405,1405
BEGIN DESCRIPTION:
XS3026A
END DESCRIPTION:
XS GIS Cut Line= 4
      2784145.33      7073565.45      2783207.85      7072565.47
      2782791.18      7072371.03      2782152.31      7072509.91
#Sta/Elev= 30
  3549.8  506.16  3663.4  502.82  3990.7  487.67  4137.7  483.80  4242.3  484.46
  4272.0  484.57  4300.4  479.84  4314.5  484.11  4510.6  484.22  4724.8  484.40
  4745.9  483.98  4767.3  480.67  4802.5  485.36  4959.7  486.70  4967.8  485.96
  4989.9  471.56  4995.8  471.49  4998.3  470.69  5014.9  471.49  5022.7  486.29
  5079.5  486.77  5133.3  483.25  5170.9  486.18  5516.1  486.52  5751.0  487.46
  5756.1  485.03  5771.7  487.67  5807.2  489.14  5937.2  495.57  6034.1  500.41
#Mann=8,-1,0
  3549.8    0.05       0  4242.3    0.16       0  4510.6    0.12       0
  4995.8    0.07       0  5014.9    0.12       0  5516.1    0.16       0
  5807.2    0.12       0  5937.2    0.16       0
Bank Sta=3990.7,5771.7
Exp/Cntr=0.3,0.1

Type RM Length L Ch R = 1,70398,418,418,418
BEGIN DESCRIPTION:
XS3027A
END DESCRIPTION:
XS GIS Cut Line= 3
      2784346.73      7073308.51      2783034.24      7071634.91
      2782305.10      7071516.86
#Sta/Elev= 30
  2430.8  494.35  2698.4  487.46  2882.0  484.51  3025.6  482.87  3110.6  483.92
  3182.9  480.96  3203.7  483.01  3519.6  484.35  3582.6  484.23  3623.2  484.33
  4050.1  484.44  4113.4  484.03  4257.8  485.92  4278.6  481.53  4301.1  485.25
  4514.5  483.62  4831.9  484.86  4931.9  485.58  4965.5  482.71  4972.2  480.72
  4982.4  474.32  4992.9  470.32  4995.4  469.52  5012.4  470.32  5022.1  484.27
  5023.4  484.51  5031.9  485.26  5083.7  485.39  5164.0  488.31  5296.3  497.39
#Mann=12,-1,0
  2430.8    0.05       0  3519.6    0.07       0  3582.6    0.12       0
  3623.2    0.16       0  4050.1    0.12       0  4113.4    0.05       0
  4831.9    0.07       0  4931.9    0.12       0  4992.9    0.07       0
  5012.4    0.12       0  5031.9    0.16       0  5164.0    0.05       0
Bank Sta=2882,5023.4
Exp/Cntr=0.3,0.1

Type RM Length L Ch R = 1,69980,757,757,757
BEGIN DESCRIPTION:
double XS3028A
END DESCRIPTION:
XS GIS Cut Line= 3
      2785332.89      7072044.65      2782805.07      7071225.19
      2782569.47      7071100.46
#Sta/Elev= 30
  2274.5  494.31  2617.0  484.05  3077.0  481.72  3155.3  479.96  3166.0  481.62
  3207.9  483.46  3313.0  481.04  3544.3  482.72  3589.1  480.71  3621.1  482.65
  4080.4  484.58  4090.9  484.44  4106.1  479.79  4132.8  485.10  4322.2  483.18
  4862.8  483.78  4934.7  483.63  4945.9  485.36  4968.6  482.15  4977.2  479.08
  4984.2  471.11  4990.0  470.46  4992.5  469.66  5009.6  470.46  5010.6  473.31
  5011.9  477.01  5025.3  484.05  5033.9  487.04  5110.6  489.91  5198.4  497.29
#Mann=8,-1,0
  2274.5    0.05       0  3077.0    0.07       0  3166.0    0.05       0
  4862.8    0.16       0  4968.6    0.12       0  4990.0    0.07       0
  5009.6    0.12       0  5010.6    0.16       0
Bank Sta=2617,5025.3
Exp/Cntr=0.3,0.1

Type RM Length L Ch R = 1,69223,814,814,814
BEGIN DESCRIPTION:
double XS3029A
END DESCRIPTION:
XS GIS Cut Line= 3
      2785346.77      7071391.87      2783235.63      7070641.86
      2782728.66      7070489.07
#Sta/Elev= 30
  2707.9  497.44  2832.4  490.44  3023.3  483.42  3222.9  479.70  3261.6  477.57
  3346.5  480.82  3537.5  480.54  4153.1  483.87  4389.1  481.80  4662.4  482.99
  4717.9  481.10  4796.0  482.23  4900.3  483.38  4928.5  484.46  4959.7  483.50
  4969.9  476.68  4977.7  468.89  4980.2  468.09  4997.3  468.89  5003.7  469.85
  5011.6  472.47  5020.5  481.62  5027.6  483.42  5055.8  485.08  5100.3  486.11
  5162.9  489.36  5195.9  494.32  5305.3  500.98  5434.8  503.31  5477.8  503.64
#Mann=9,-1,0
  2707.9    0.05       0  4796.0    0.16       0  4900.3    0.12       0
  4977.7    0.07       0  4997.3    0.12       0  5003.7    0.07       0
  5055.8    0.12       0  5100.3    0.05       0  5434.8     0.1       0
Bank Sta=3023.3,5027.6
Exp/Cntr=0.3,0.1

Type RM Length L Ch R = 1,68409,1314,1314,1314
BEGIN DESCRIPTION:
double XS3030A
END DESCRIPTION:
XS GIS Cut Line= 4
      2785256.49      7070815.49      2784281.71      7070142.19
      2783555.07      7069905.75      2783075.92      7069836.30
#Sta/Elev= 30
  3021.3  495.50  3116.6  497.64  3158.5  496.71  3314.7  486.54  3370.9  482.93
  3447.8  479.56  3489.7  481.66  3504.6  474.79  3533.6  481.39  3561.4  481.07
  3578.4  482.67  3683.7  480.00  4007.5  479.27  4717.8  480.72  4844.0  482.94
  4927.6  481.09  4960.7  484.27  4972.7  481.79  4980.3  473.05  4990.7  468.87
  4993.2  468.07  5010.3  468.87  5012.9  473.96  5020.7  480.29  5028.9  481.95
  5034.3  482.93  5101.6  487.82  5182.4  489.32  5278.6  494.65  5454.3  500.78
#Mann=8,-1,0
  3021.3    0.16       0  3314.7    0.12       0  3578.4    0.05       0
  4927.6     0.1       0  4990.7    0.07       0  5010.3     0.1       0
  5028.9    0.16       0  5278.6     0.1       0
Bank Sta=3370.9,5034.3
Exp/Cntr=0.3,0.1

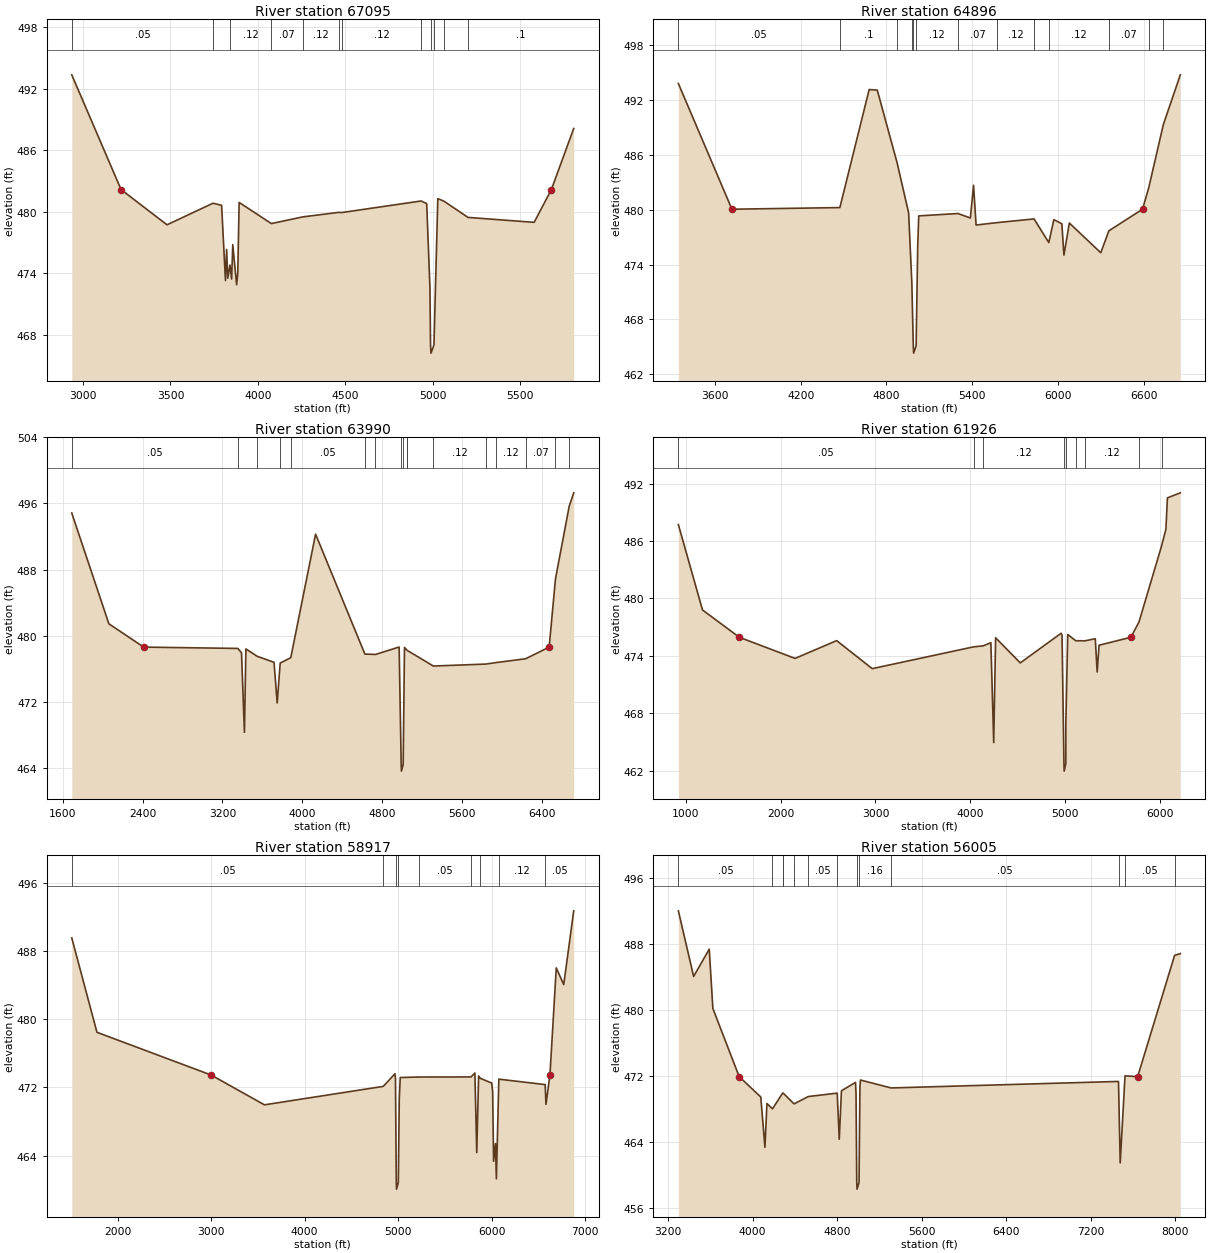
Type RM Length L Ch R = 1,67095,2199,2199,2199
BEGIN DESCRIPTION:
double XS3032A
END DESCRIPTION:
XS GIS Cut Line= 4
      2785566.37      7070486.92      2785123.65      7069913.99
      2784203.51      7069141.42      2783311.25      7068829.57
#Sta/Elev= 30
  2935.7  493.35  3217.7  482.17  3480.5  478.74  3743.2  480.84  3792.7  480.64
  3814.7  473.31  3821.3  476.34  3827.9  473.54  3840.4  474.82  3849.9  473.45
  3856.5  476.81  3878.6  472.90  3885.1  474.02  3892.9  480.92  4077.2  478.86
  4256.7  479.51  4461.5  479.95  4482.6  479.94  4933.3  481.06  4965.6  480.81
  4984.1  472.64  4987.5  467.04  4990.0  466.24  5007.1  467.04  5029.1  481.29
  5064.4  481.04  5202.1  479.46  5580.0  478.98  5678.6  482.17  5806.4  488.12
#Mann=12,-1,0
  2935.7    0.05       0  3743.2    0.16       0  3840.4    0.12       0
  4077.2    0.07       0  4256.7    0.12       0  4461.5    0.07       0
  4482.6    0.12       0  4933.3    0.07       0  4987.5    0.07       0
  5007.1    0.07       0  5064.4    0.16       0  5202.1     0.1       0
Bank Sta=3217.7,5678.6
Exp/Cntr=0.3,0.1

Type RM Length L Ch R = 1,64896,906,906,906
BEGIN DESCRIPTION:
XS3031A
END DESCRIPTION:
XS GIS Cut Line= 4
      2785687.02      7070398.81      2785312.02      7069121.03
      2784818.96      7068600.19      2783423.71      7068169.82
#Sta/Elev= 30
  3345.1  493.81  3719.6  480.06  4474.2  480.24  4679.0  493.15  4735.6  493.09
  4874.0  485.16  4954.8  479.66  4977.2  472.05  4987.4  465.12  4989.9  464.32
  5007.2  465.12  5018.4  476.07  5025.6  479.33  5299.8  479.59  5386.5  479.10
  5408.6  482.68  5426.4  478.33  5571.4  478.59  5831.6  479.00  5934.9  476.41
  5969.9  478.92  6026.0  478.47  6040.5  475.04  6078.4  478.55  6298.1  475.30
  6354.6  477.70  6590.0  480.06  6632.7  482.37  6735.6  489.33  6854.1  494.76
#Mann=13,-1,0
  3345.1    0.05       0  4474.2     0.1       0  4874.0    0.05       0
  4977.2    0.12       0  4987.4    0.07       0  5007.2    0.12       0
  5299.8    0.07       0  5571.4    0.12       0  5831.6    0.07       0
  5934.9    0.12       0  6354.6    0.07       0  6632.7     0.1       0
  6735.6    0.05       0
Bank Sta=3719.6,6590
Exp/Cntr=0.3,0.1

Type RM Length L Ch R = 1,63990,2064,2064,2064
BEGIN DESCRIPTION:
double XS3033A
END DESCRIPTION:
XS GIS Cut Line= 3
      2788428.80      7069486.49      2785358.02      7068227.80
      2783720.61      7067739.83
#Sta/Elev= 30
  1690.6  494.85  2062.2  481.45  2411.2  478.63  3353.9  478.47  3390.6  477.95
  3420.0  468.32  3434.7  478.41  3547.7  477.52  3716.3  476.79  3748.1  471.88
  3778.1  476.70  3884.1  477.35  4132.6  492.29  4626.4  477.79  4732.4  477.74
  4969.4  478.64  4990.0  464.43  4992.5  463.63  5009.8  464.43  5022.9  478.59
  5048.3  478.25  5049.6  478.24  5312.1  476.34  5839.0  476.58  5941.0  476.76
  6236.2  477.22  6472.1  478.63  6534.8  486.86  6672.3  495.64  6717.9  497.29
#Mann=17,-1,0
  1690.6    0.05       0  3353.9    0.16       0  3547.7    0.12       0
  3778.1     0.1       0  3884.1    0.05       0  4626.4    0.12       0
  4732.4    0.16       0  4990.0    0.07       0  5009.8    0.16       0
  5048.3    0.12       0  5049.6    0.05       0  5312.1    0.12       0
  5839.0    0.16       0  5941.0    0.12       0  6236.2    0.07       0
  6534.8    0.12       0  6672.3    0.05       0
Bank Sta=2411.2,6472.1
Exp/Cntr=0.3,0.1

Type RM Length L Ch R = 1,61926,3009,3009,3009
BEGIN DESCRIPTION:
double XS3035A
END DESCRIPTION:
XS GIS Cut Line= 4
      2788580.65      7068878.81      2786801.17      7067196.98
      2785151.86      7067142.73      2783959.18      7067196.94
#Sta/Elev= 30
   921.6  487.73  1176.0  478.80  1564.6  475.94  2152.2  473.73  2590.8  475.59
  2965.8  472.66  4034.7  474.94  4133.8  475.04  4216.7  475.37  4246.7  464.93
  4266.7  475.89  4526.9  473.26  4957.1  476.36  4967.1  476.17  4987.2  462.74
  4989.7  461.94  5007.0  462.74  5007.1  466.86  5027.2  476.23  5111.4  475.58
  5209.5  475.57  5317.5  475.79  5337.5  472.31  5357.5  475.11  5693.0  475.94
  5778.6  477.54  6017.8  485.54  6062.3  487.25  6078.2  490.52  6214.2  491.05
#Mann=9,-1,0
   921.6    0.05       0  4034.7    0.16       0  4133.8    0.12       0
  4987.2    0.07       0  5007.0    0.12       0  5111.4    0.05       0
  5209.5    0.12       0  5778.6    0.16       0  6017.8    0.05       0
Bank Sta=1564.6,5693
Exp/Cntr=0.3,0.1

Type RM Length L Ch R = 1,58917,2912,2912,2912
BEGIN DESCRIPTION:
XS3034A
END DESCRIPTION:
XS GIS Cut Line= 4
      2789014.74      7068195.28      2786475.65      7065862.34
      2785998.22      7065721.29      2784578.42      7065710.45
#Sta/Elev= 30
  1510.5  489.59  1779.7  478.49  3001.2  473.46  3570.1  469.96  4840.2  472.13
  4965.7  473.62  4970.9  473.04  4979.7  460.85  4982.5  460.05  5001.4  460.85
  5011.4  470.60  5021.9  473.17  5220.3  473.23  5778.7  473.24  5819.7  473.70
  5839.7  464.35  5859.7  473.35  5877.8  473.08  5999.7  472.52  6009.7  471.55
  6019.7  463.33  6039.7  465.41  6049.7  461.27  6075.9  472.98  6571.1  472.34
  6579.7  470.02  6622.1  473.46  6689.7  486.06  6769.7  484.10  6876.3  492.77
#Mann=9,-1,0
  1510.5    0.05       0  4840.2    0.12       0  4979.7    0.07       0
  5001.4    0.12       0  5220.3    0.05       0  5778.7    0.12       0
  5877.8    0.16       0  6075.9    0.12       0  6571.1    0.05       0
Bank Sta=3001.2,6622.1
Exp/Cntr=0.3,0.1

Type RM Length L Ch R = 1,56005,1916,1916,1916
BEGIN DESCRIPTION:
double XS3036A
END DESCRIPTION:
XS GIS Cut Line= 4
      2789123.19      7065417.46      2787473.91      7064961.74
      2786681.81      7064842.38      2784500.87      7065352.35
#Sta/Elev= 30
  3297.5  492.03  3442.1  484.07  3589.8  487.38  3624.2  480.19  3873.4  471.92
  4077.7  469.45  4117.2  463.35  4136.0  468.66  4188.6  468.02  4285.8  469.94
  4290.7  469.91  4392.8  468.62  4527.9  469.51  4801.2  469.92  4820.7  464.32
  4841.5  470.21  4974.4  471.22  4979.5  469.85  4986.2  459.08  4989.0  458.28
  5007.9  459.08  5016.4  470.69  5021.4  471.51  5311.6  470.55  7464.2  471.34
  7480.3  461.46  7525.9  472.02  7645.5  471.92  7995.4  486.63  8049.4  486.84
#Mann=13,-1,0
  3297.5    0.05       0  4188.6    0.07       0  4285.8    0.05       0
  4290.7    0.16       0  4392.8    0.12       0  4527.9    0.05       0
  4801.2    0.16       0  4986.2    0.07       0  5007.9    0.16       0
  5311.6    0.05       0  7464.2    0.16       0  7525.9    0.05       0
  7995.4    0.16       0
Bank Sta=3873.4,7645.5
Exp/Cntr=0.3,0.1

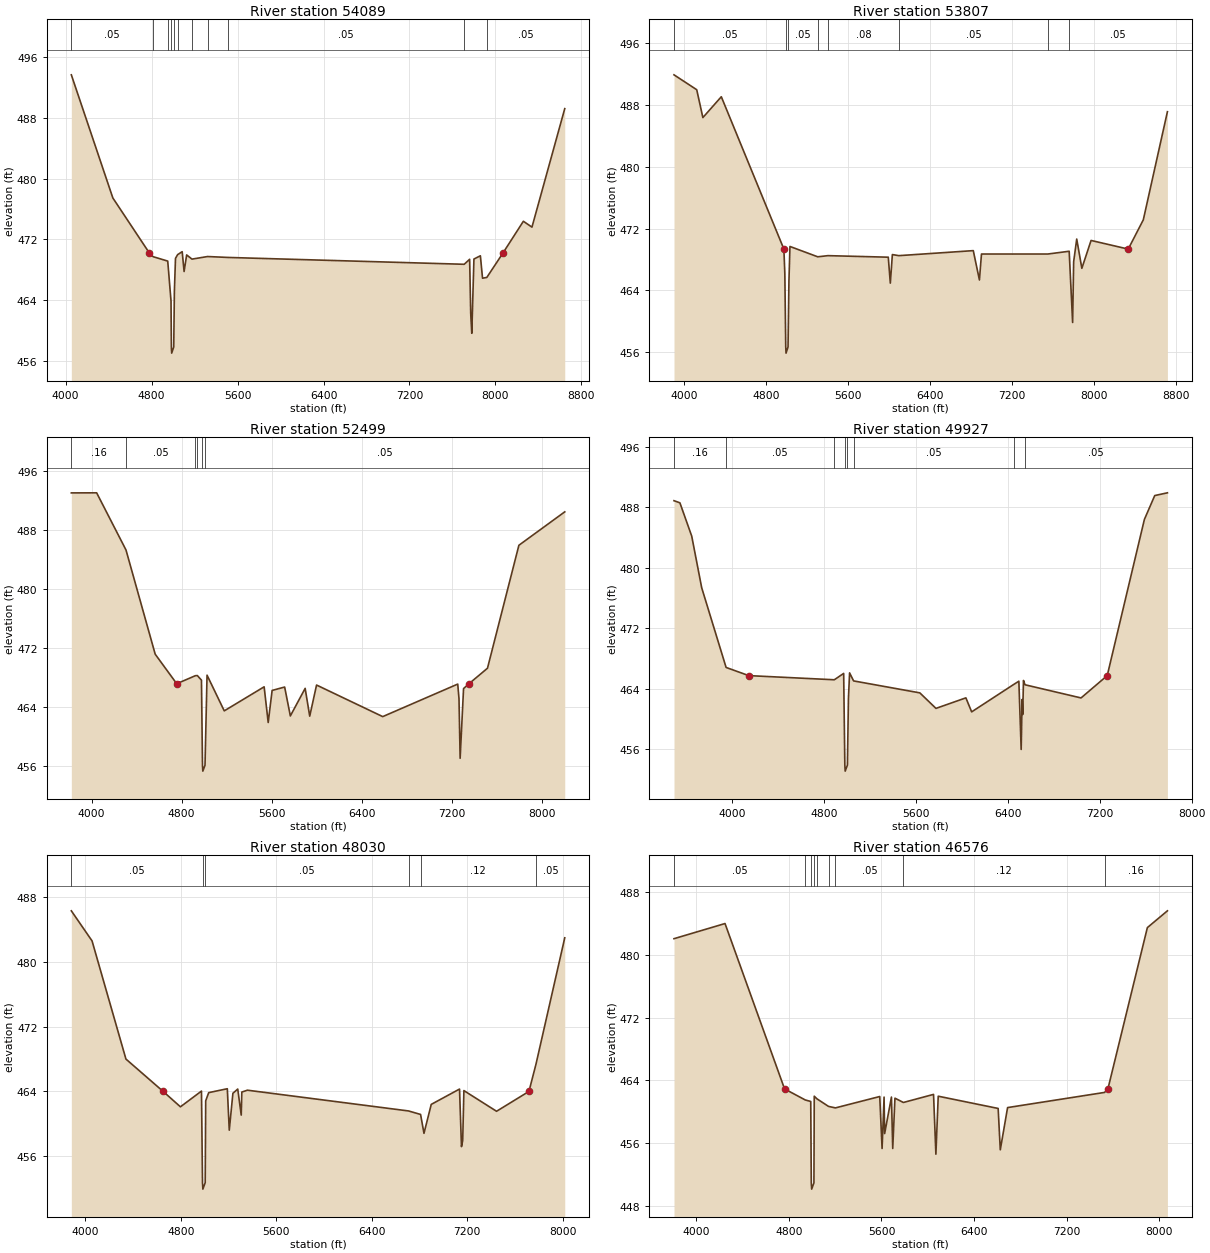
Type RM Length L Ch R = 1,54089,282,282,282
BEGIN DESCRIPTION:
double XS3037A
END DESCRIPTION:
XS GIS Cut Line= 4
      2789003.84      7064712.17      2788266.01      7064397.50
      2787918.79      7064299.84      2784489.94      7064245.59
#Sta/Elev= 30
  4053.1  493.65  4439.4  477.45  4779.4  470.20  4814.3  469.72  4950.3  469.14
  4980.9  463.88  4984.2  457.83  4987.0  457.03  5006.1  457.83  5012.1  465.12
  5022.5  469.50  5042.4  469.99  5084.8  470.38  5102.5  467.77  5126.4  469.95
  5176.0  469.40  5321.1  469.74  5512.6  469.62  7709.5  468.72  7760.0  469.38
  7770.0  462.24  7780.0  459.64  7800.0  469.41  7860.0  469.84  7880.0  466.89
  7919.9  466.99  8070.1  470.20  8260.1  474.38  8340.1  473.61  8645.2  489.20
#Mann=11,-1,0
  4053.1    0.05       0  4814.3    0.08       0  4950.3    0.05       0
  4984.2    0.03       0  5006.1    0.05       0  5042.4    0.12       0
  5176.0    0.08       0  5321.1    0.12       0  5512.6    0.05       0
  7709.5    0.12       0  7919.9    0.05       0
Bank Sta=4779.4,8070.1
Exp/Cntr=0.3,0.1

Type RM Length L Ch R = 1,53807,1308,1308,1308
BEGIN DESCRIPTION:
double XS3038A
END DESCRIPTION:
XS GIS Cut Line= 4
      2789296.78      7064147.93      2788200.91      7064104.53
      2787549.86      7064093.68      2784479.56      7064006.89
#Sta/Elev= 30
  3898.6  491.92  4120.6  489.99  4180.6  486.38  4360.7  489.08  4971.9  469.34
  4981.2  466.15  4990.0  456.66  4993.0  455.86  5012.4  456.66  5021.2  465.22
  5031.2  469.68  5302.7  468.34  5401.8  468.49  5991.5  468.29  6011.5  464.93
  6031.5  468.63  6095.0  468.49  6821.8  469.14  6881.8  465.34  6901.8  468.70
  7549.4  468.70  7758.5  469.06  7792.2  459.83  7802.2  467.70  7832.2  470.64
  7882.2  466.85  7972.3  470.46  8335.2  469.34  8482.5  473.13  8718.0  487.14
#Mann=8,-1,0
  3898.6    0.05       0  4990.0    0.03       0  5012.4    0.05       0
  5302.7    0.05       0  5401.8    0.08       0  6095.0    0.05       0
  7549.4    0.16       0  7758.5    0.05       0
Bank Sta=4971.9,8335.2
Exp/Cntr=0.3,0.1

Type RM Length L Ch R = 1,52499,2572,2572,2572
BEGIN DESCRIPTION:
double TURKEY CREEK 33.0
END DESCRIPTION:
XS GIS Cut Line= 3
      2789305.94      7063394.46      2788368.44      7063019.46
      2785036.93      7062519.74
#Sta/Elev= 30
  3820.8  493.01  4045.4  493.02  4305.9  485.27  4565.1  471.14  4756.1  467.14
  4920.2  468.22  4938.9  468.25  4975.6  467.62  4984.6  456.09  4987.6  455.29
  5007.0  456.09  5025.1  468.30  5177.8  463.46  5531.7  466.72  5567.8  461.88
  5602.5  466.23  5713.7  466.69  5764.3  462.77  5895.7  466.51  5936.2  462.74
  5996.9  466.96  6584.0  462.68  7249.7  467.09  7260.9  465.10  7271.0  457.03
  7301.3  466.48  7349.7  467.14  7513.6  469.24  7792.4  485.91  8199.3  490.44
#Mann=6,-1,0
  3820.8    0.16       0  4305.9    0.05       0  4920.2    0.07       0
  4938.9    0.05       0  4984.6    0.03       0  5007.0    0.05       0
Bank Sta=4756.1,7349.7
Exp/Cntr=0.3,0.1

Type RM Length L Ch R = 1,49927,1897,1897,1897
BEGIN DESCRIPTION:
double TURKEY CREEK 32.0
END DESCRIPTION:
XS GIS Cut Line= 3
      2789825.00      7062225.00      2788525.00      7061499.89
      2785724.99      7061699.89
#Sta/Elev= 30
  3493.2  488.87  3544.6  488.59  3647.5  484.19  3734.3  477.37  3946.7  466.84
  4143.8  465.76  4888.9  465.21  4970.3  466.05  4980.5  453.94  4983.6  453.14
  5003.0  453.94  5011.8  462.74  5021.9  466.12  5056.8  465.06  5633.4  463.48
  5773.8  461.43  6034.4  462.82  6084.6  460.97  6449.6  464.58  6495.6  465.02
  6515.7  456.01  6524.0  462.60  6529.0  460.62  6535.7  465.12  6549.1  464.55
  7037.0  462.81  7264.9  465.76  7588.4  486.39  7678.6  489.55  7788.9  489.91
#Mann=8,-1,0
  3493.2    0.16       0  3946.7    0.05       0  4888.9    0.16       0
  4980.5    0.07       0  5003.0    0.16       0  5056.8    0.05       0
  6449.6    0.16       0  6549.1    0.05       0
Bank Sta=4143.8,7264.9
Exp/Cntr=0.3,0.1

Type RM Length L Ch R = 1,48030,1454,1454,1454
BEGIN DESCRIPTION:
double TURKEY CREEK 31.0
END DESCRIPTION:
XS GIS Cut Line= 3
      2790143.64      7060979.54      2789049.86      7060710.44
      2786081.10      7061205.23
#Sta/Elev= 30
  3881.4  486.28  4055.1  482.57  4339.1  468.00  4650.9  464.01  4795.9  462.11
  4972.3  464.05  4980.9  452.76  4984.0  451.96  5003.6  452.76  5007.7  462.85
  5033.0  463.86  5188.9  464.34  5205.3  459.23  5235.8  463.78  5276.3  464.30
  5305.5  461.09  5310.5  463.93  5357.4  464.16  6708.2  461.60  6809.0  461.17
  6837.5  458.84  6898.4  462.41  7135.4  464.30  7151.8  457.20  7162.0  457.95
  7172.1  464.11  7445.8  461.56  7717.5  464.01  7776.2  467.36  8017.5  482.95
#Mann=6,-1,0
  3881.4    0.05       0  4980.9    0.03       0  5003.6    0.05       0
  6708.2    0.16       0  6809.0    0.12       0  7776.2    0.05       0
Bank Sta=4650.9,7717.5
Exp/Cntr=0.3,0.1

Type RM Length L Ch R = 1,46576,3013,3013,3013
BEGIN DESCRIPTION:
double XS3039A
END DESCRIPTION:
XS GIS Cut Line= 4
      2790325.93      7059486.48      2789193.09      7059460.44
      2787864.97      7059655.75      2786108.59      7059317.48
#Sta/Elev= 30
  3807.1  482.06  4248.1  483.99  4762.6  462.92  4941.6  461.51  4988.8  461.32
  4993.6  450.95  4996.8  450.15  5016.4  450.95  5019.2  461.99  5042.0  461.66
  5142.5  460.69  5202.3  460.50  5585.2  461.95  5605.4  455.33  5622.6  461.88
  5627.6  457.23  5686.3  461.88  5697.4  455.33  5716.6  461.74  5789.6  461.19
  6050.1  462.22  6070.4  454.60  6090.6  461.99  6608.5  460.43  6627.0  455.16
  6690.0  460.54  7527.7  462.47  7557.1  462.92  7898.0  483.47  8071.3  485.61
#Mann=9,-1,0
  3807.1    0.05       0  4941.6    0.16       0  4993.6    0.07       0
  5016.4    0.16       0  5042.0    0.12       0  5142.5    0.07       0
  5202.3    0.05       0  5789.6    0.12       0  7527.7    0.16       0
Bank Sta=4762.6,7557.1
Exp/Cntr=0.3,0.1