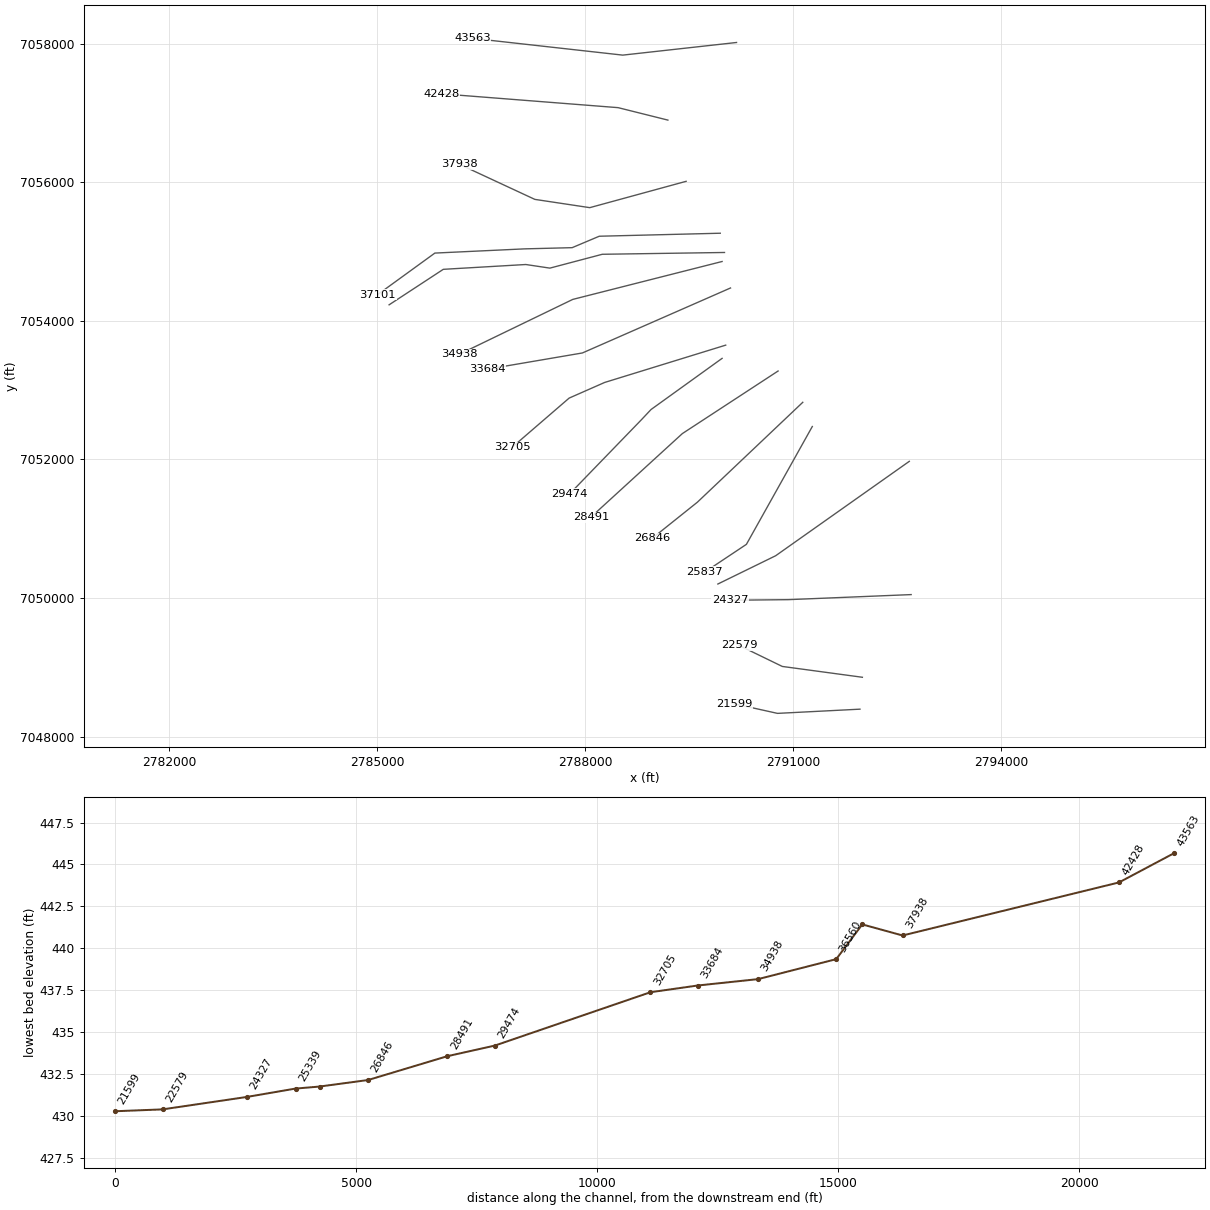
HEC-RAS study TURKEY CREEK.prj: TURKEY CREEK Base Level Engineering

--- TURKEY CREEK.g01 (geometry) --- (continued)

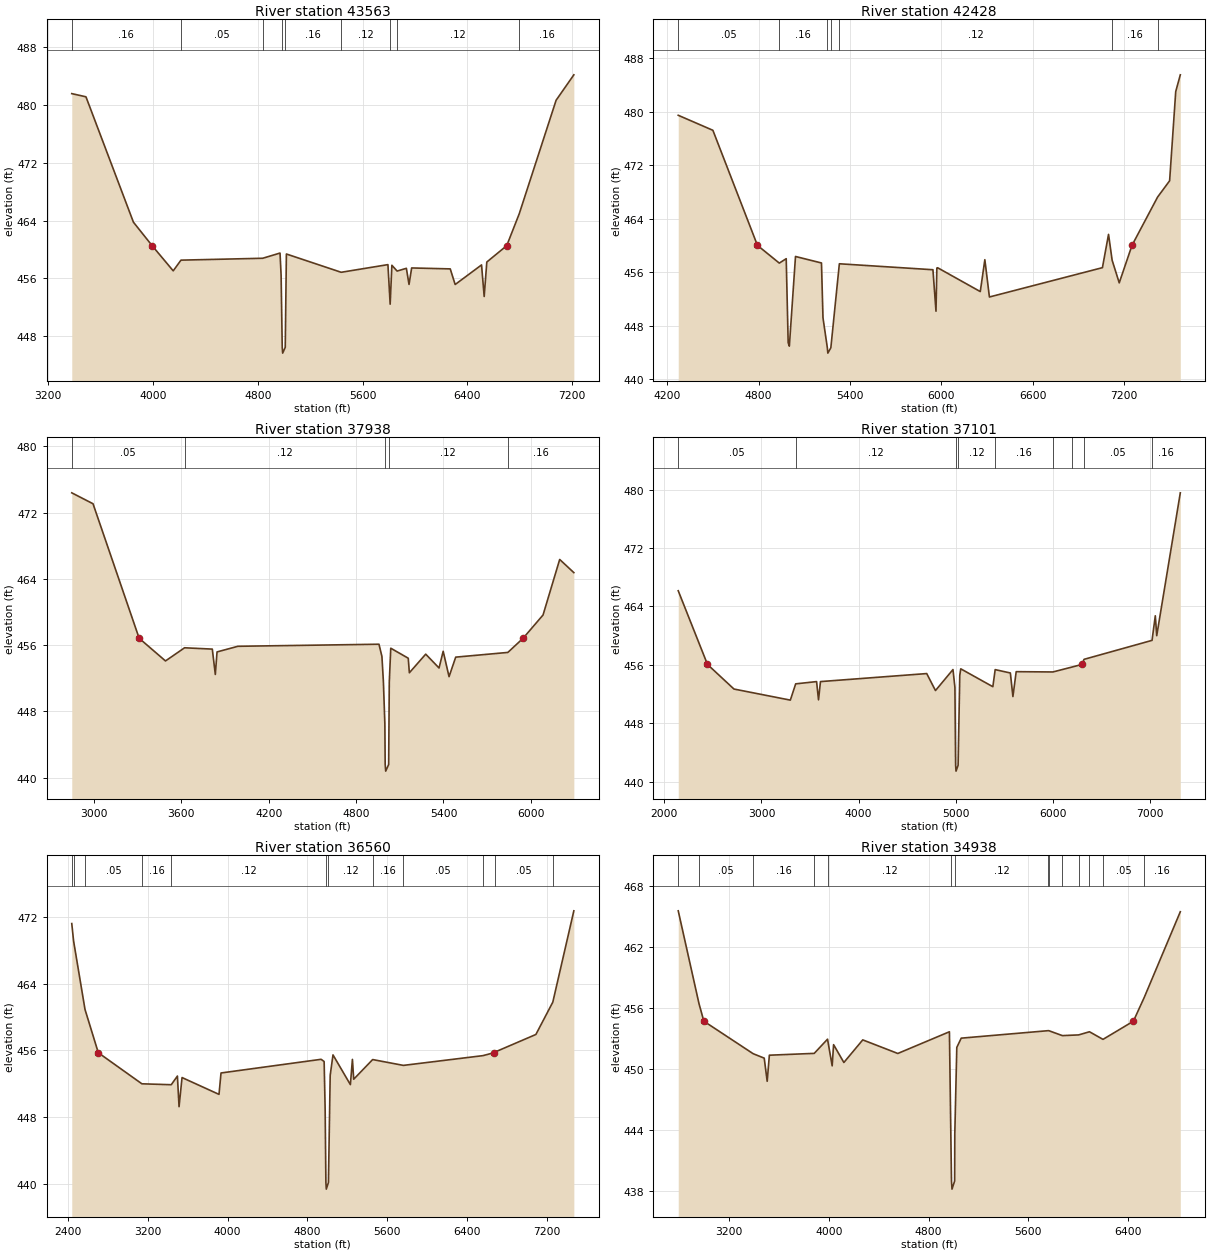
Type RM Length L Ch R = 1,43563,1135,1135,1135
BEGIN DESCRIPTION:
double TURKEY CREEK 27.0
END DESCRIPTION:
XS GIS Cut Line= 3
      2790182.65      7058015.12      2788542.05      7057832.83
      2786375.04      7058075.00
#Sta/Elev= 30
  3380.7  481.55  3489.0  481.11  3851.2  463.77  3994.0  460.52  4154.8  457.04
  4214.0  458.52  4837.9  458.78  4969.8  459.50  4978.1  456.44  4986.7  446.46
  4990.0  445.66  5009.7  446.46  5018.4  459.37  5436.5  456.84  5793.2  457.90
  5810.3  452.43  5823.3  457.81  5863.4  457.01  5934.0  457.39  5954.2  455.16
  5974.3  457.44  6268.8  457.31  6306.3  455.15  6507.6  457.86  6527.7  453.49
  6547.8  458.26  6699.7  460.52  6795.0  464.92  7076.5  480.63  7211.9  484.15
#Mann=9,-1,0
  3380.7    0.16       0  4214.0    0.05       0  4837.9    0.16       0
  4986.7    0.07       0  5009.7    0.16       0  5436.5    0.12       0
  5810.3    0.05       0  5863.4    0.12       0  6795.0    0.16       0
Bank Sta=3994,6699.7
Exp/Cntr=0.3,0.1

Type RM Length L Ch R = 1,42428,4490,4490,4490
BEGIN DESCRIPTION:
double TURKEY CREEK 26.0
END DESCRIPTION:
XS GIS Cut Line= 3
      2789193.11      7056895.33      2788475.00      7057075.00
      2785924.98      7057275.00
#Sta/Elev= 30
  4272.3  479.44  4499.9  477.20  4792.6  460.02  4936.2  457.37  4981.6  458.03
  4994.5  445.49  5002.2  444.97  5042.6  458.36  5213.2  457.39  5223.2  449.20
  5251.8  444.73  5255.1  443.93  5274.8  444.73  5330.7  457.27  5945.4  456.38
  5965.5  450.19  5971.1  456.63  5976.1  456.68  6256.4  453.12  6286.4  457.88
  6316.5  452.31  7058.8  456.69  7098.9  461.66  7122.5  457.81  7169.2  454.42
  7253.1  460.02  7421.2  467.23  7500.2  469.66  7540.3  482.98  7570.4  485.48
#Mann=7,-1,0
  4272.3    0.05       0  4936.2    0.16       0  5251.8    0.07       0
  5274.8    0.16       0  5330.7    0.12       0  7122.5    0.16       0
  7421.2    0.05       0
Bank Sta=4792.6,7253.1
Exp/Cntr=0.3,0.1

Type RM Length L Ch R = 1,37938,837,837,837
BEGIN DESCRIPTION:
XS3040A
END DESCRIPTION:
XS GIS Cut Line= 4
      2789455.71      7056012.09      2788066.79      7055632.31
      2787274.69      7055751.67      2786181.14      7056260.55
#Sta/Elev= 30
  2848.2  474.39  2994.1  473.07  3310.9  456.82  3491.7  454.08  3622.7  455.67
  3813.1  455.51  3833.8  452.45  3845.6  455.17  3988.8  455.85  4957.4  456.10
  4977.6  454.63  4987.7  451.59  4997.8  446.49  5000.0  441.57  5003.6  440.77
  5023.9  441.57  5028.2  451.52  5038.3  455.62  5158.4  454.41  5166.0  452.65
  5278.3  454.90  5369.8  453.23  5398.2  455.25  5438.5  452.18  5484.2  454.54
  5842.3  455.11  5946.9  456.82  6083.8  459.63  6198.2  466.34  6295.3  464.75
#Mann=5,-1,0
  2848.2    0.05       0  3622.7    0.12       0  5000.0    0.07       0
  5023.9    0.12       0  5842.3    0.16       0
Bank Sta=3310.9,5946.9
Exp/Cntr=0.3,0.1

Type RM Length L Ch R = 1,37101,541,541,541
BEGIN DESCRIPTION:
XS3041A
END DESCRIPTION:
XS GIS Cut Line= 6
      2789948.31      7055263.39      2788203.51      7055219.98
      2787812.89      7055055.05      2787127.12      7055037.69
      2785833.72      7054976.93      2785010.92      7054379.31
#Sta/Elev= 30
  2143.2  466.15  2444.2  456.05  2716.7  452.68  3296.9  451.16  3351.9  453.39
  3567.0  453.70  3587.0  451.20  3607.0  453.70  4700.6  454.80  4790.6  452.47
  4970.7  455.35  4990.7  452.90  4998.0  442.23  5002.1  441.43  5023.4  442.23
  5040.7  454.55  5050.7  455.45  5381.1  453.00  5405.0  455.34  5561.3  454.88
  5587.5  451.65  5621.3  455.06  5999.4  455.02  6197.5  455.70  6297.3  456.05
  6319.6  456.75  7019.4  459.35  7052.9  462.72  7067.6  459.99  7310.3  479.57
#Mann=9,-1,0
  2143.2    0.05       0  3351.9    0.12       0  4998.0    0.07       0
  5023.4    0.12       0  5405.0    0.16       0  5999.4    0.05       0
  6197.5    0.07       0  6319.6    0.05       0  7019.4    0.16       0
Bank Sta=2444.2,6297.3
Exp/Cntr=0.3,0.1

Type RM Length L Ch R = 1,36560,1622,1622,1622
BEGIN DESCRIPTION:
XS3042A
END DESCRIPTION:
XS GIS Cut Line= 6
      2790009.03      7054985.61      2788246.91      7054959.57
      2787491.71      7054759.91      2787144.48      7054812.00
      2785955.25      7054742.55      2785174.00      7054230.40
#Sta/Elev= 30
  2440.1  471.23  2458.3  469.14  2572.5  460.93  2705.7  455.73  3142.2  452.00
  3436.1  451.89  3497.8  452.93  3514.2  449.25  3544.2  452.75  3914.3  450.73
  3934.3  453.30  4936.6  454.94  4966.8  454.67  4976.9  448.90  4984.4  440.16
  4988.5  439.36  5009.8  440.16  5027.4  453.02  5055.5  455.47  5229.6  451.90
  5249.9  454.93  5262.8  452.55  5452.5  454.91  5760.0  454.21  6556.3  455.38
  6666.7  455.73  6673.0  455.79  7086.7  457.92  7256.2  461.80  7466.8  472.76
#Mann=12,-1,0
  2440.1    0.05       0  2458.3    0.16       0  2572.5    0.05       0
  3142.2    0.16       0  3436.1    0.12       0  4984.4    0.07       0
  5009.8    0.12       0  5452.5    0.16       0  5760.0    0.05       0
  6556.3    0.08       0  6673.0    0.05       0  7256.2    0.16       0
Bank Sta=2705.7,6666.7
Exp/Cntr=0.3,0.1

Type RM Length L Ch R = 1,34938,1254,1254,1254
BEGIN DESCRIPTION:
XS3043A
END DESCRIPTION:
XS GIS Cut Line= 3
      2789974.32      7054855.40      2787821.57      7054308.53
      2786191.25      7053519.38
#Sta/Elev= 30
  2789.5  465.60  2956.7  456.43  2995.3  454.72  3391.0  451.52  3480.1  451.08
  3503.9  448.80  3521.4  451.37  3881.8  451.55  3988.6  452.95  4025.8  450.32
  4037.2  452.41  4119.8  450.65  4271.5  452.88  4552.9  451.54  4967.5  453.68
  4984.1  438.97  4988.2  438.17  5009.5  438.97  5010.6  443.54  5026.8  452.14
  5062.4  453.05  5763.0  453.79  5769.5  453.77  5874.6  453.30  6005.5  453.37
  6092.2  453.68  6201.0  452.93  6445.0  454.72  6532.5  457.07  6821.9  465.51
#Mann=14,-1,0
  2789.5    0.16       0  2956.7    0.05       0  3391.0    0.16       0
  3881.8    0.07       0  3988.6    0.12       0  4984.1    0.07       0
  5009.5    0.12       0  5763.0    0.16       0  5769.5    0.05       0
  5874.6    0.07       0  6005.5    0.16       0  6092.2     0.1       0
  6201.0    0.05       0  6532.5    0.16       0
Bank Sta=2995.3,6445
Exp/Cntr=0.3,0.1

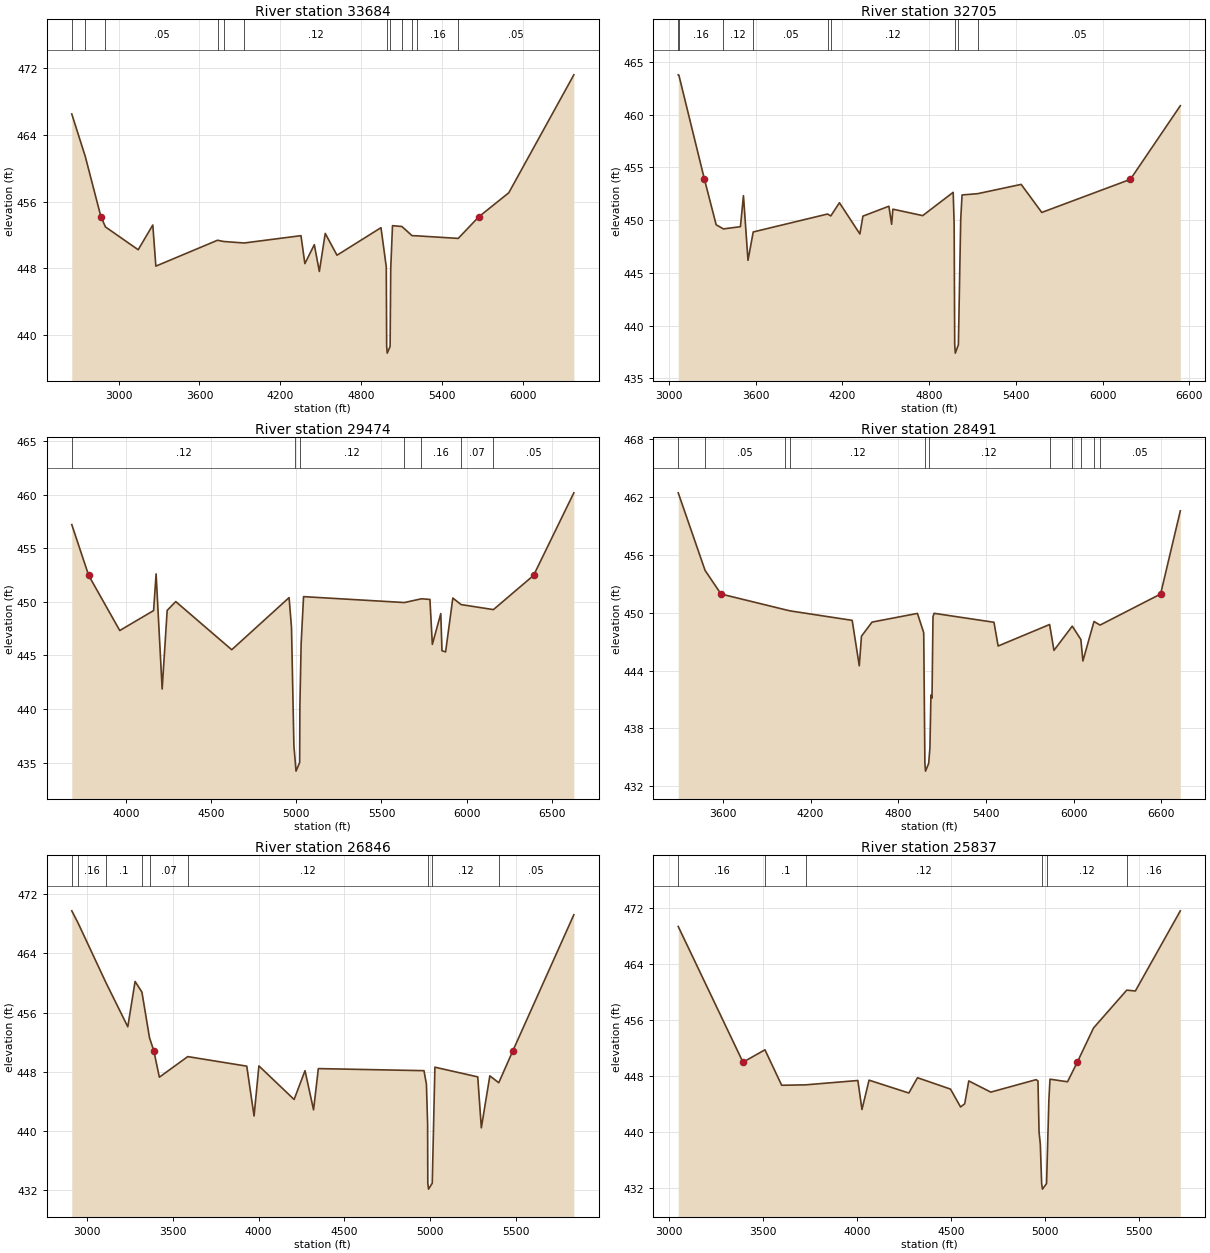
Type RM Length L Ch R = 1,33684,979,979,979
BEGIN DESCRIPTION:
XS3044A
END DESCRIPTION:
XS GIS Cut Line= 3
      2790095.91      7054473.47      2787960.46      7053535.96
      2786589.42      7053301.67
#Sta/Elev= 30
  2653.1  466.52  2753.7  461.39  2869.2  454.18  2902.8  452.95  3145.6  450.21
  3254.0  453.18  3276.6  448.24  3734.0  451.35  3780.0  451.20  3931.5  451.02
  4352.8  451.90  4381.7  448.54  4451.7  450.82  4488.9  447.60  4532.7  452.17
  4619.9  449.55  4946.2  452.86  4985.3  448.15  4988.2  438.59  4992.4  437.79
  5013.7  438.59  5018.4  447.95  5031.4  453.10  5101.2  453.00  5176.4  451.90
  5212.6  451.88  5518.9  451.57  5672.4  454.18  5893.7  457.05  6376.2  471.22
#Mann=12,-1,0
  2653.1    0.05       0  2753.7    0.16       0  2902.8    0.05       0
  3734.0    0.12       0  3780.0    0.05       0  3931.5    0.12       0
  4988.2    0.07       0  5013.7    0.12       0  5101.2    0.16       0
  5176.4    0.05       0  5212.6    0.16       0  5518.9    0.05       0
Bank Sta=2869.2,5672.4
Exp/Cntr=0.3,0.1

Type RM Length L Ch R = 1,32705,3231,3231,3231
BEGIN DESCRIPTION:
XS3045A
END DESCRIPTION:
XS GIS Cut Line= 4
      2790026.39      7053648.79      2788281.64      7053110.61
      2787769.48      7052884.91      2786944.84      7052173.12
#Sta/Elev= 30
  3063.4  463.78  3067.6  463.76  3244.9  453.87  3326.0  449.56  3376.3  449.17
  3493.9  449.38  3514.8  452.32  3546.2  446.19  3582.4  448.88  4096.7  450.58
  4119.3  450.40  4179.1  451.65  4320.6  448.69  4341.6  450.38  4521.4  451.32
  4540.4  449.61  4548.9  451.04  4755.3  450.43  4966.4  452.64  4973.0  449.66
  4976.9  438.19  4981.1  437.39  5002.4  438.19  5018.5  450.08  5027.7  452.39
  5135.6  452.51  5436.9  453.39  5579.6  450.73  6192.8  453.87  6538.3  460.85
#Mann=9,-1,0
  3063.4    0.05       0  3067.6    0.16       0  3376.3    0.12       0
  3582.4    0.05       0  4096.7    0.07       0  4119.3    0.12       0
  4976.9    0.07       0  5002.4    0.12       0  5135.6    0.05       0
Bank Sta=3244.9,6192.8
Exp/Cntr=0.3,0.1

Type RM Length L Ch R = 1,29474,983,983,983
BEGIN DESCRIPTION:
XS3046A
END DESCRIPTION:
XS GIS Cut Line= 4
      2789974.38      7053457.86      2788950.04      7052719.98
      2788811.15      7052572.41      2787779.07      7051505.64
#Sta/Elev= 30
  3680.6  457.20  3779.9  452.46  3962.5  447.32  4161.3  449.18  4176.0  452.60
  4211.6  441.87  4241.1  449.20  4291.4  450.02  4620.3  445.53  4957.2  450.39
  4971.4  447.60  4985.5  436.59  4993.8  435.01  4998.0  434.21  5019.3  435.01
  5020.7  440.31  5028.0  446.08  5042.2  450.48  5634.7  449.93  5734.7  450.28
  5784.6  450.22  5798.8  446.03  5848.4  448.90  5855.4  445.44  5876.7  445.33
  5919.1  450.35  5967.5  449.74  6157.5  449.27  6393.4  452.46  6630.0  460.16
#Mann=7,-1,0
  3680.6    0.12       0  4993.8    0.07       0  5019.3    0.12       0
  5634.7    0.07       0  5734.7    0.16       0  5967.5    0.07       0
  6157.5    0.05       0
Bank Sta=3779.9,6393.4
Exp/Cntr=0.3,0.1

Type RM Length L Ch R = 1,28491,1645,1645,1645
BEGIN DESCRIPTION:
XS3047A
END DESCRIPTION:
XS GIS Cut Line= 3
      2790781.61      7053275.52      2789401.43      7052372.76
      2788081.96      7051166.15
#Sta/Elev= 30
  3293.7  462.43  3477.4  454.39  3586.6  451.94  4024.1  450.32  4060.2  450.19
  4484.6  449.21  4533.1  444.50  4548.2  447.57  4620.6  449.03  4931.2  449.93
  4974.3  447.93  4982.3  434.38  4986.6  433.58  5008.2  434.38  5016.8  436.01
  5023.6  441.47  5031.0  441.15  5037.8  449.58  5045.2  449.94  5455.3  449.01
  5483.7  446.55  5836.1  448.78  5866.0  446.10  5991.2  448.61  6050.3  447.22
  6064.0  445.00  6140.0  449.09  6181.7  448.72  6595.9  451.94  6730.9  460.56
#Mann=11,-1,0
  3293.7    0.16       0  3477.4    0.05       0  4024.1    0.16       0
  4060.2    0.12       0  4982.3    0.07       0  5008.2    0.12       0
  5836.1    0.07       0  5991.2    0.16       0  6050.3    0.12       0
  6140.0    0.07       0  6181.7    0.05       0
Bank Sta=3586.6,6595.9
Exp/Cntr=0.3,0.1

Type RM Length L Ch R = 1,26846,1009,1009,1009
BEGIN DESCRIPTION:
TURKEY CREEK 19.0
END DESCRIPTION:
XS GIS Cut Line= 3
      2791137.50      7052824.12      2789618.44      7051383.18
      2788968.73      7050863.41
#Sta/Elev= 30
  2910.9  469.75  2945.7  468.20  3110.9  460.01  3237.4  454.09  3279.9  460.21
  3319.7  458.78  3364.1  452.59  3388.7  450.88  3421.4  447.28  3586.8  450.06
  3930.7  448.77  3973.2  442.04  4001.5  448.80  4206.6  444.27  4270.1  448.16
  4319.9  442.87  4347.8  448.44  4963.4  448.16  4977.6  446.34  4984.5  441.06
  4985.7  432.96  4990.0  432.16  5011.6  432.96  5027.0  448.63  5276.7  447.32
  5297.6  440.44  5347.2  447.46  5399.2  446.53  5481.9  450.88  5836.7  469.22
#Mann=9,-1,0
  2910.9    0.05       0  2945.7    0.16       0  3110.9     0.1       0
  3319.7    0.05       0  3364.1    0.07       0  3586.8    0.12       0
  4985.7    0.07       0  5011.6    0.12       0  5399.2    0.05       0
Bank Sta=3388.7,5481.9
Exp/Cntr=0.3,0.1

Type RM Length L Ch R = 1,25837,498,498,498
BEGIN DESCRIPTION:
TURKEY CREEK 18.0
END DESCRIPTION:
XS GIS Cut Line= 3
      2791274.98      7052474.96      2790325.00      7050775.00
      2789725.00      7050375.00
#Sta/Elev= 30
  3050.0  469.32  3394.1  449.92  3511.0  451.69  3599.8  446.62  3727.8  446.68
  4004.8  447.30  4026.5  443.15  4064.2  447.35  4275.7  445.51  4321.5  447.70
  4497.1  446.07  4550.6  443.52  4572.5  443.97  4594.2  447.24  4711.0  445.64
  4951.7  447.42  4962.0  447.25  4967.7  439.95  4974.5  438.19  4981.5  432.57
  4985.8  431.77  5007.6  432.57  5019.9  444.48  5025.9  447.49  5119.1  447.12
  5170.9  449.92  5257.3  454.81  5433.8  460.22  5479.6  460.10  5718.5  471.56
#Mann=6,-1,0
  3050.0    0.16       0  3511.0     0.1       0  3727.8    0.12       0
  4981.5    0.07       0  5007.6    0.12       0  5433.8    0.16       0
Bank Sta=3394.1,5170.9
Exp/Cntr=0.3,0.1

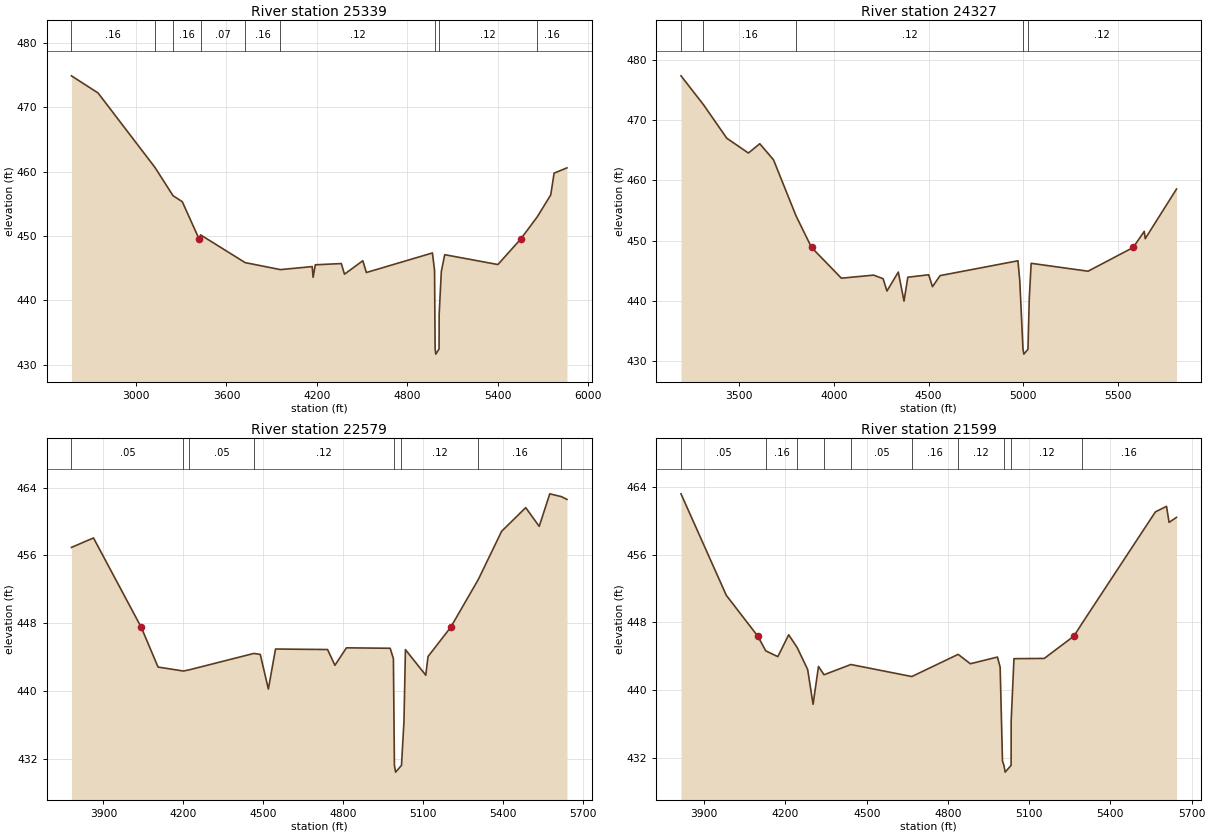
Type RM Length L Ch R = 1,25339,1012,1012,1012
BEGIN DESCRIPTION:
XS3048A
END DESCRIPTION:
XS GIS Cut Line= 3
      2792673.30      7051972.40      2790746.91      7050610.61
      2789913.55      7050202.61
#Sta/Elev= 30
  2571.5  474.92  2747.9  472.26  3125.8  460.67  3245.6  456.28  3306.8  455.35
  3418.5  449.54  3428.3  450.19  3723.6  445.88  3958.0  444.79  4168.5  445.26
  4174.6  443.59  4189.4  445.54  4361.8  445.73  4382.7  444.08  4504.5  446.17
  4528.0  444.34  4966.2  447.38  4980.2  444.68  4984.1  432.45  4988.4  431.65
  5010.2  432.45  5010.7  437.78  5025.2  444.50  5047.7  447.11  5400.4  445.58
  5551.9  449.54  5662.2  453.02  5750.9  456.40  5773.4  459.79  5858.5  460.61
#Mann=9,-1,0
  2571.5    0.16       0  3125.8    0.12       0  3245.6    0.16       0
  3428.3    0.07       0  3723.6    0.16       0  3958.0    0.12       0
  4984.1    0.07       0  5010.2    0.12       0  5662.2    0.16       0
Bank Sta=3418.5,5551.9
Exp/Cntr=0.3,0.1

Type RM Length L Ch R = 1,24327,1748,1748,1748
BEGIN DESCRIPTION:
double XS3049A
END DESCRIPTION:
XS GIS Cut Line= 3
      2792700.04      7050050.00      2790929.21      7049976.93
      2790088.60      7049968.26
#Sta/Elev= 30
  3194.8  477.33  3313.4  472.54  3436.2  466.98  3550.1  464.52  3610.2  466.06
  3682.6  463.40  3801.5  454.09  3883.4  448.85  4040.6  443.75  4210.7  444.26
  4260.8  443.66  4280.8  441.62  4340.8  444.77  4370.8  439.95  4390.9  443.91
  4501.0  444.32  4521.0  442.34  4561.0  444.18  4971.7  446.64  4981.4  443.30
  4998.3  431.95  5002.7  431.15  5024.4  431.95  5031.4  440.42  5041.4  446.22
  5341.4  444.91  5579.5  448.85  5637.8  451.52  5642.8  450.31  5807.8  458.54
#Mann=5,-1,0
  3194.8    0.05       0  3313.4    0.16       0  3801.5    0.12       0
  4998.3    0.07       0  5024.4    0.12       0
Bank Sta=3883.4,5579.5
Exp/Cntr=0.3,0.1

Type RM Length L Ch R = 1,22579,980,980,980
BEGIN DESCRIPTION:
XS3050A
END DESCRIPTION:
XS GIS Cut Line= 3
      2791996.94      7048857.13      2790842.40      7049013.39
      2790218.74      7049316.55
#Sta/Elev= 30
  3779.8  456.95  3862.5  458.07  4041.7  447.51  4104.7  442.82  4199.9  442.35
  4221.4  442.49  4464.1  444.43  4488.1  444.31  4518.4  440.22  4545.2  444.95
  4740.4  444.89  4768.1  443.03  4811.1  445.09  4975.3  445.04  4987.4  443.81
  4991.2  431.21  4995.7  430.41  5017.7  431.21  5027.0  436.38  5032.5  444.88
  5108.8  441.86  5117.2  444.06  5202.1  447.51  5305.6  453.15  5393.4  458.86
  5483.7  461.65  5534.3  459.44  5573.9  463.28  5617.4  462.95  5638.3  462.62
#Mann=8,-1,0
  3779.8    0.05       0  4199.9    0.16       0  4221.4    0.05       0
  4464.1    0.12       0  4991.2    0.07       0  5017.7    0.12       0
  5305.6    0.16       0  5617.4    0.12       0
Bank Sta=4041.7,5202.1
Exp/Cntr=0.3,0.1

Type RM Length L Ch R = 1,21599,778,778,778
BEGIN DESCRIPTION:
XS3051A
END DESCRIPTION:
XS GIS Cut Line= 3
      2791962.18      7048397.07      2790772.96      7048336.30
      2790148.96      7048474.97
#Sta/Elev= 30
  3814.1  463.17  3981.5  451.18  4097.5  446.37  4127.2  444.62  4171.7  443.94
  4211.8  446.52  4243.3  445.01  4281.9  442.42  4301.9  438.31  4321.9  442.78
  4342.3  441.80  4441.4  443.01  4666.6  441.59  4837.7  444.21  4882.7  443.10
  4982.8  443.89  4992.8  442.69  5001.4  431.61  5006.8  431.10  5011.3  430.30
  5033.3  431.10  5033.5  436.36  5043.8  443.70  5155.8  443.73  5265.3  446.37
  5294.3  447.82  5566.2  461.04  5607.2  461.69  5616.7  459.80  5644.1  460.39
#Mann=10,-1,0
  3814.1    0.05       0  4127.2    0.16       0  4243.3    0.12       0
  4342.3    0.07       0  4441.4    0.05       0  4666.6    0.16       0
  4837.7    0.12       0  5006.8    0.07       0  5033.3    0.12       0
  5294.3    0.16       0
Bank Sta=4097.5,5265.3
Exp/Cntr=0.3,0.1