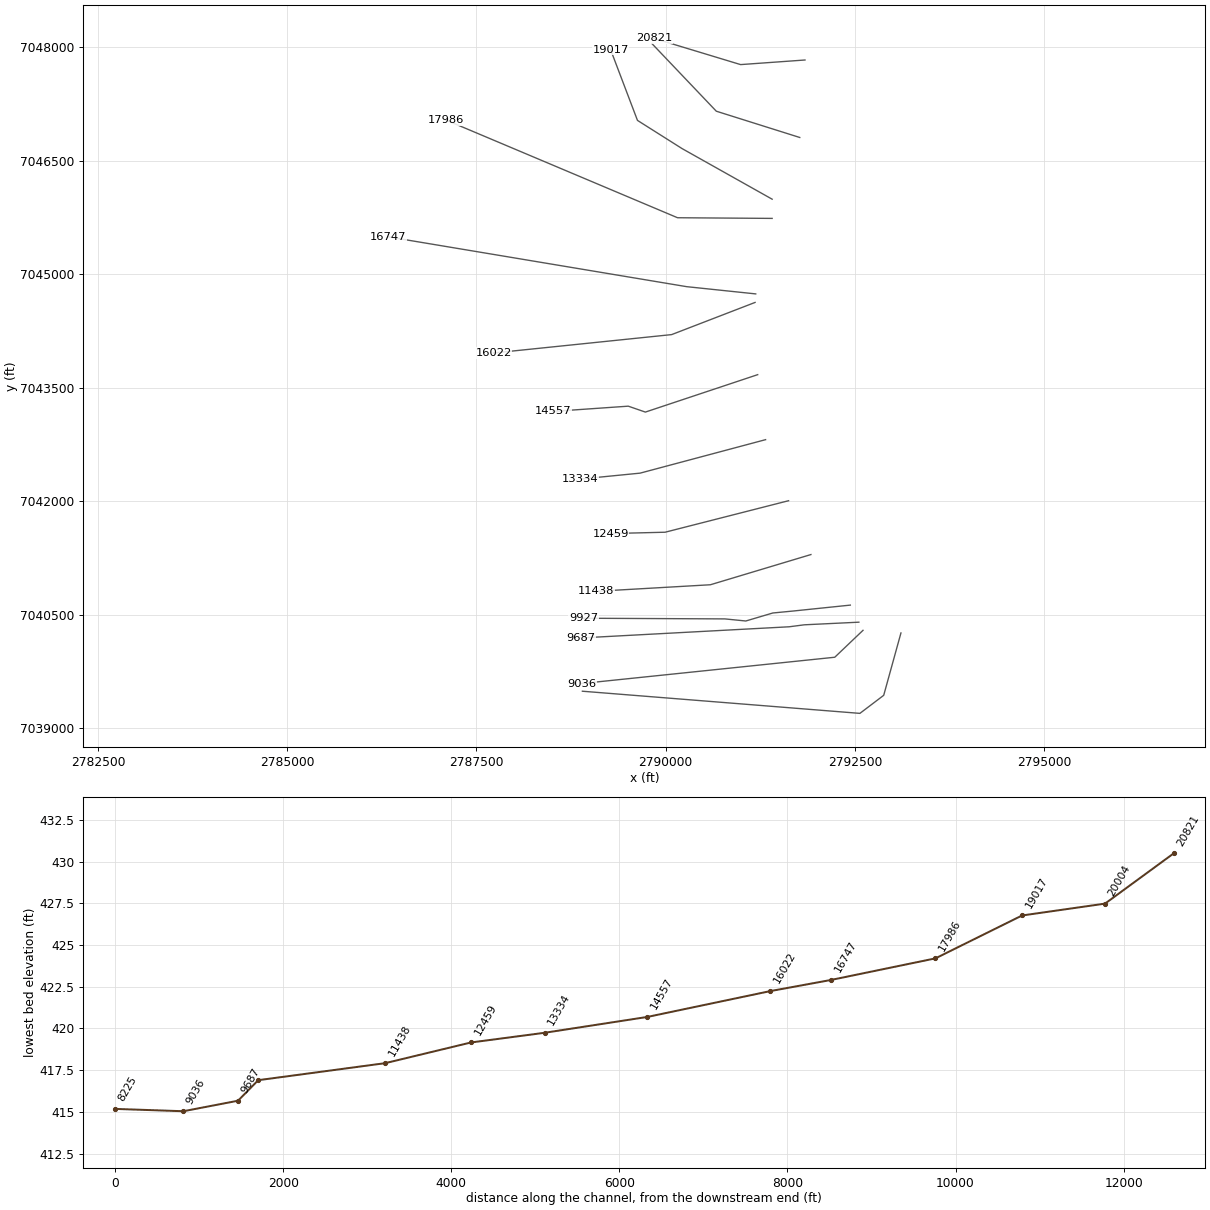
HEC-RAS study TURKEY CREEK.prj: TURKEY CREEK Base Level Engineering

--- TURKEY CREEK.g01 (geometry) --- (continued)

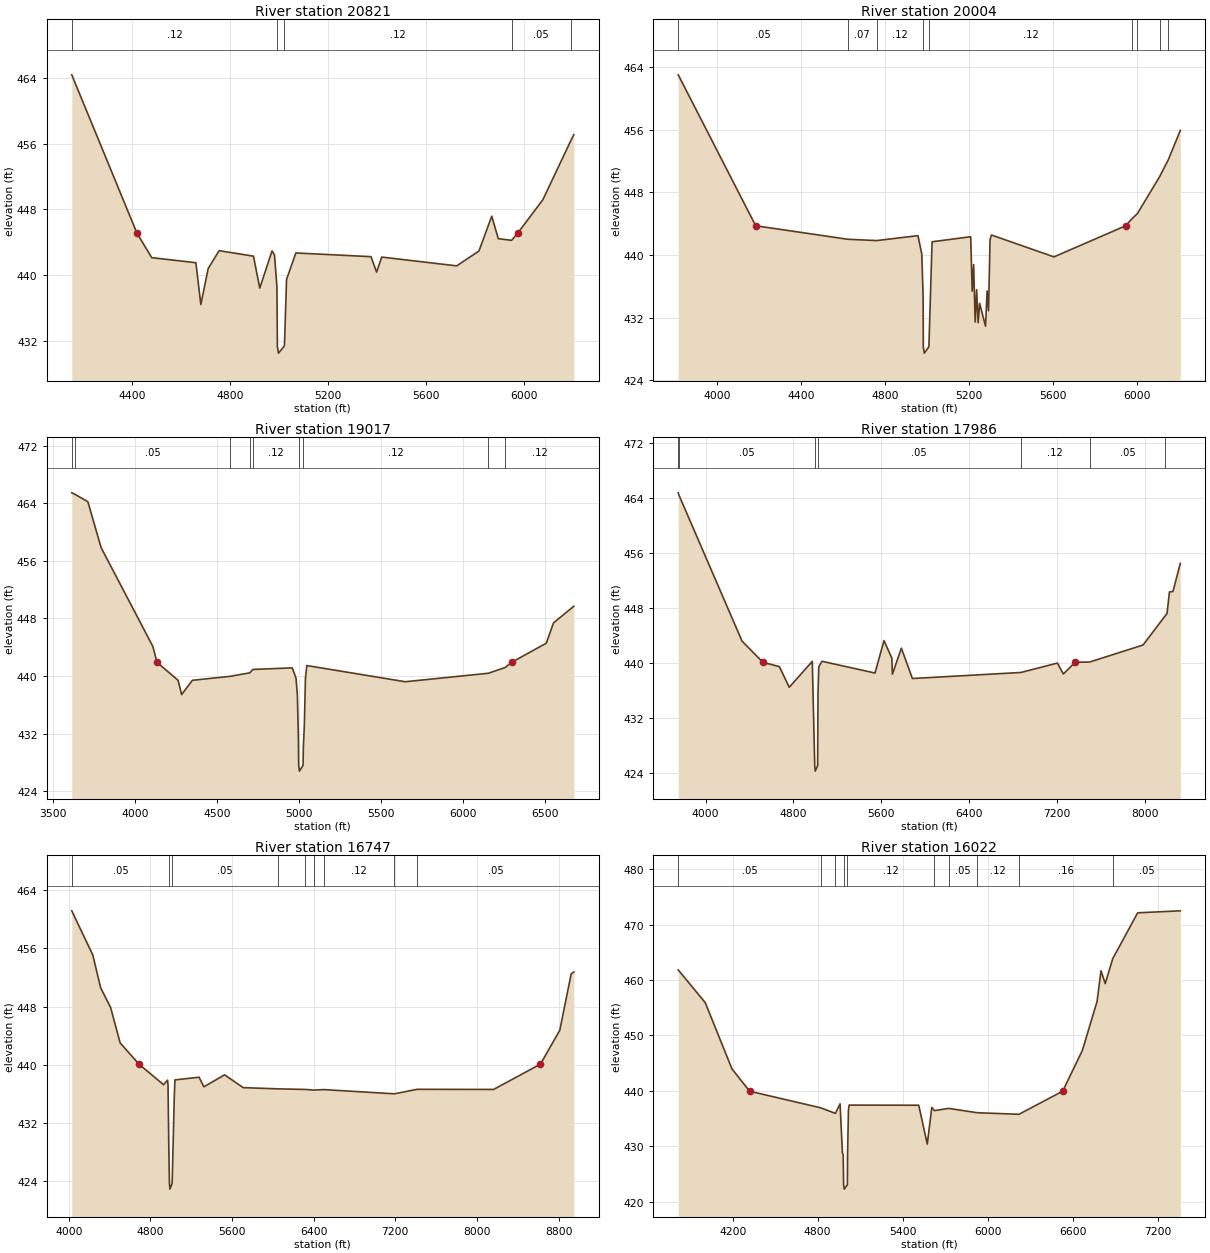
Type RM Length L Ch R = 1,20821,817,817,817
BEGIN DESCRIPTION:
XS3052A
END DESCRIPTION:
XS GIS Cut Line= 3
      2791840.66      7047832.83      2790989.97      7047772.07
      2789844.18      7048119.28
#Sta/Elev= 30
  4152.8  464.39  4418.9  445.11  4479.3  442.12  4659.7  441.50  4679.8  436.41
  4709.9  440.80  4754.5  442.97  4894.8  442.30  4920.4  438.41  4970.5  442.94
  4980.6  442.45  4990.6  438.54  4992.4  431.29  4996.9  430.49  5018.9  431.29
  5021.3  431.47  5029.8  439.47  5067.9  442.69  5374.6  442.24  5397.5  440.36
  5418.4  442.19  5724.6  441.12  5815.4  442.93  5867.7  447.17  5894.4  444.43
  5948.7  444.23  5973.9  445.11  6076.7  449.19  6190.8  456.39  6202.9  457.10
#Mann=5,-1,0
  4152.8    0.12       0  4992.4    0.07       0  5018.9    0.12       0
  5948.7    0.05       0  6190.8    0.12       0
Bank Sta=4418.9,5973.9
Exp/Cntr=0.3,0.1

Type RM Length L Ch R = 1,20004,987,987,987
BEGIN DESCRIPTION:
XS3053A
END DESCRIPTION:
XS GIS Cut Line= 3
      2791771.22      7046808.53      2790668.79      7047155.75
      2789819.03      7048048.87
#Sta/Elev= 30
  3816.4  462.99  4185.0  443.73  4622.1  442.01  4760.8  441.84  4956.8  442.47
  4975.2  440.11  4981.5  434.55  4982.4  428.28  4986.9  427.48  5008.9  428.28
  5024.0  441.69  5207.7  442.33  5214.9  435.39  5221.8  438.78  5229.1  431.45
  5236.0  435.57  5243.2  431.36  5250.1  433.84  5278.4  430.92  5285.7  435.41
  5292.6  432.89  5299.8  441.95  5306.7  442.55  5604.0  439.76  5944.9  443.73
  5974.6  444.62  6000.7  445.28  6106.7  450.00  6148.0  452.16  6205.0  455.90
#Mann=9,-1,0
  3816.4    0.05       0  4622.1    0.07       0  4760.8    0.12       0
  4982.4    0.07       0  5008.9    0.12       0  5974.6    0.16       0
  6000.7    0.05       0  6106.7    0.07       0  6148.0    0.12       0
Bank Sta=4185,5944.9
Exp/Cntr=0.3,0.1

Type RM Length L Ch R = 1,19017,1031,1031,1031
BEGIN DESCRIPTION:
XS3054A
END DESCRIPTION:
XS GIS Cut Line= 4
      2791406.63      7045992.56      2790217.40      7046660.96
      2789627.12      7047034.22      2789271.56      7047970.82
#Sta/Elev= 30
  3612.9  465.47  3630.3  465.29  3711.0  464.24  3792.0  457.85  4108.0  444.10
  4133.1  441.90  4261.8  439.40  4283.5  437.41  4348.9  439.40  4578.7  439.95
  4699.4  440.44  4718.5  440.91  4958.7  441.13  4981.5  439.71  4989.9  437.37
  4995.8  431.81  4997.9  427.57  5002.4  426.77  5024.4  427.57  5026.4  430.17
  5032.3  433.05  5039.1  439.67  5047.6  441.45  5648.6  439.20  6155.8  440.38
  6258.2  441.18  6297.9  441.90  6509.0  444.56  6553.4  447.39  6677.3  449.70
#Mann=9,-1,0
  3612.9    0.16       0  3630.3    0.05       0  4578.7    0.12       0
  4699.4    0.07       0  4718.5    0.12       0  4997.9    0.07       0
  5024.4    0.12       0  6155.8    0.07       0  6258.2    0.12       0
Bank Sta=4133.1,6297.9
Exp/Cntr=0.3,0.1

Type RM Length L Ch R = 1,17986,1239,1239,1239
BEGIN DESCRIPTION:
double XS3055A
END DESCRIPTION:
XS GIS Cut Line= 3
      2791406.60      7045738.65      2790156.64      7045747.33
      2787093.24      7047040.37
#Sta/Elev= 30
  3751.0  464.71  3759.9  464.29  4332.6  443.12  4522.1  440.05  4672.6  439.41
  4762.6  436.41  4972.6  440.18  4994.8  425.00  4999.3  424.20  5021.3  425.00
  5024.5  435.43  5031.7  439.38  5060.9  440.19  5544.0  438.48  5626.0  443.20
  5697.1  440.66  5702.5  438.31  5784.5  442.10  5884.8  437.68  6873.9  438.56
  7206.2  439.93  7260.5  438.34  7367.9  440.05  7500.2  440.08  7986.6  442.56
  8186.7  446.77  8204.8  447.12  8227.1  450.28  8259.1  450.35  8326.1  454.44
#Mann=7,-1,0
  3751.0    0.16       0  3759.9    0.05       0  4994.8    0.03       0
  5021.3    0.05       0  6873.9    0.12       0  7500.2    0.05       0
  8186.7    0.16       0
Bank Sta=4522.1,7367.9
Exp/Cntr=0.3,0.1

Type RM Length L Ch R = 1,16747,725,725,725
BEGIN DESCRIPTION:
double XS3056A
END DESCRIPTION:
XS GIS Cut Line= 3
      2791189.65      7044740.38      2790278.16      7044835.87
      2786329.25      7045495.47
#Sta/Elev= 30
  4029.9  461.16  4235.7  455.10  4312.6  450.60  4410.9  447.86  4504.1  443.01
  4688.5  440.09  4929.4  437.26  4968.1  437.89  4973.2  437.21  4980.0  429.55
  4987.0  423.71  4991.5  422.91  5013.6  423.71  5034.0  435.37  5040.8  437.92
  5277.0  438.29  5324.7  436.97  5527.5  438.62  5710.0  436.86  6050.4  436.69
  6317.9  436.61  6403.6  436.52  6497.4  436.59  7192.1  436.01  7414.9  436.63
  8163.5  436.61  8622.9  440.09  8812.4  444.75  8923.9  452.50  8950.0  452.76
#Mann=9,-1,0
  4029.9    0.05       0  4987.0    0.03       0  5013.6    0.05       0
  6050.4    0.16       0  6317.9    0.12       0  6403.6    0.16       0
  6497.4    0.12       0  7192.1    0.16       0  7414.9    0.05       0
Bank Sta=4688.5,8622.9
Exp/Cntr=0.3,0.1

Type RM Length L Ch R = 1,16022,1465,1465,1465
BEGIN DESCRIPTION:
double XS3057A
END DESCRIPTION:
XS GIS Cut Line= 3
      2791180.98      7044627.55      2790078.51      7044202.19
      2787728.00      7043959.33
#Sta/Elev= 30
  3815.7  461.83  4006.5  455.91  4194.9  443.96  4319.8  439.92  4820.3  436.93
  4925.5  435.92  4958.3  437.64  4975.0  428.77  4980.4  428.44  4983.3  423.04
  4987.8  422.24  5009.9  423.04  5011.0  428.10  5017.3  436.49  5022.4  437.41
  5513.6  437.39  5573.9  430.37  5605.8  436.99  5624.9  436.41  5724.2  436.82
  5924.7  436.04  6220.9  435.75  6529.8  439.92  6668.8  447.28  6772.7  456.12
  6800.4  461.67  6830.6  459.35  6883.1  463.84  7059.4  472.13  7360.4  472.49
#Mann=10,-1,0
  3815.7    0.05       0  4820.3    0.16       0  4925.5    0.12       0
  4983.3    0.07       0  5009.9    0.12       0  5624.9     0.1       0
  5724.2    0.05       0  5924.7    0.12       0  6220.9    0.16       0
  6883.1    0.05       0
Bank Sta=4319.8,6529.8
Exp/Cntr=0.3,0.1

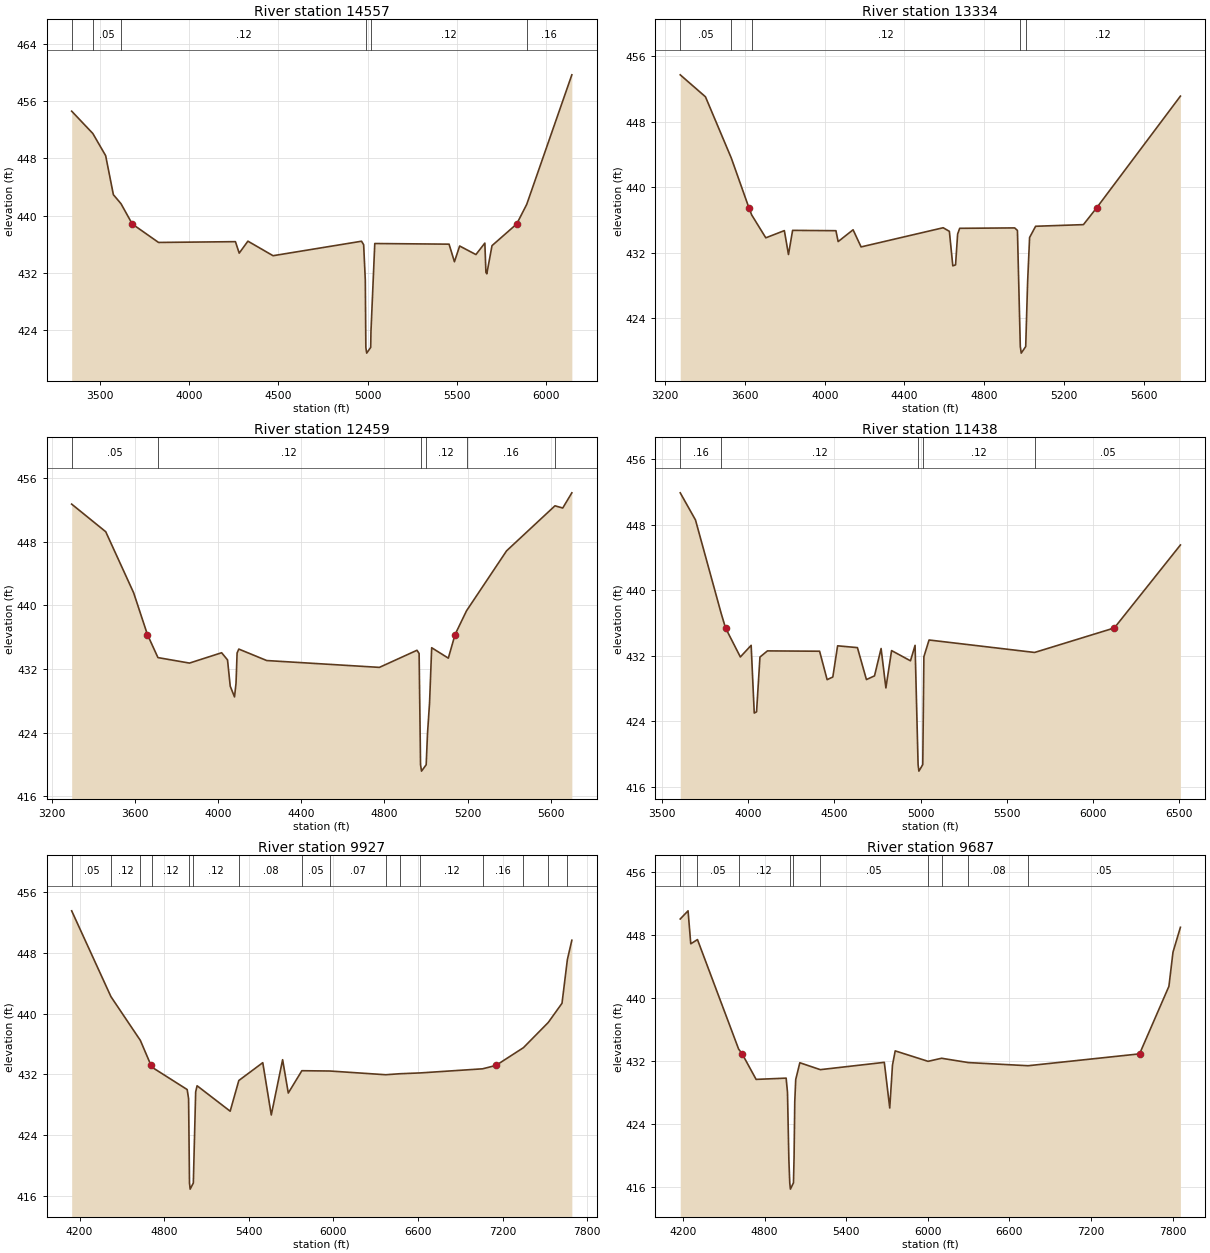
Type RM Length L Ch R = 1,14557,1223,1223,1223
BEGIN DESCRIPTION:
XS3058A
END DESCRIPTION:
XS GIS Cut Line= 4
      2791215.62      7043672.66      2789731.29      7043177.88
      2789505.59      7043256.01      2788508.66      7043186.66
#Sta/Elev= 30
  3341.9  454.64  3460.4  451.51  3532.3  448.40  3575.7  442.92  3618.5  441.65
  3681.4  438.81  3828.7  436.22  4259.6  436.33  4280.7  434.72  4329.4  436.40
  4470.4  434.36  4966.1  436.39  4978.1  435.90  4987.3  430.93  4990.4  421.49
  4995.1  420.69  5017.5  421.49  5019.0  423.71  5040.4  436.07  5456.7  435.98
  5486.8  433.51  5516.0  435.72  5607.1  434.52  5657.2  436.13  5663.2  432.02
  5668.2  431.82  5697.3  435.77  5835.6  438.81  5891.8  441.56  6144.7  459.74
#Mann=6,-1,0
  3341.9    0.16       0  3460.4    0.05       0  3618.5    0.12       0
  4990.4    0.07       0  5017.5    0.12       0  5891.8    0.16       0
Bank Sta=3681.4,5835.6
Exp/Cntr=0.3,0.1

Type RM Length L Ch R = 1,13334,875,875,875
BEGIN DESCRIPTION:
XS3059A
END DESCRIPTION:
XS GIS Cut Line= 3
      2791319.84      7042813.30      2789661.84      7042370.59
      2788871.88      7042292.46
#Sta/Elev= 30
  3275.1  453.70  3401.7  451.02  3531.6  443.53  3619.6  437.49  3633.5  436.61
  3704.5  433.81  3797.6  434.69  3818.3  431.77  3839.0  434.72  4056.4  434.68
  4067.5  433.35  4142.5  434.79  4182.6  432.70  4594.6  435.04  4625.7  434.60
  4642.9  430.39  4656.7  430.51  4667.1  434.27  4677.4  434.97  4953.2  435.02
  4967.2  434.71  4981.6  420.54  4986.3  419.74  5008.7  420.54  5018.2  428.36
  5028.2  433.85  5058.4  435.22  5298.3  435.42  5365.4  437.49  5785.0  451.10
#Mann=5,-1,0
  3275.1    0.05       0  3531.6    0.16       0  3633.5    0.12       0
  4981.6    0.07       0  5008.7    0.12       0
Bank Sta=3619.6,5365.4
Exp/Cntr=0.3,0.1

Type RM Length L Ch R = 1,12459,1021,1021,1021
BEGIN DESCRIPTION:
XS3060A
END DESCRIPTION:
XS GIS Cut Line= 3
      2791623.68      7042006.02      2789991.71      7041589.34
      2789271.24      7041571.98
#Sta/Elev= 30
  3296.3  452.72  3460.1  449.25  3594.2  441.58  3660.5  436.33  3711.1  433.43
  3862.6  432.74  4017.4  434.04  4045.7  433.14  4058.7  429.84  4079.3  428.49
  4086.6  430.22  4091.7  434.01  4100.0  434.50  4234.1  433.06  4775.9  432.20
  4956.6  434.35  4966.9  433.95  4973.8  419.96  4978.5  419.16  5000.9  419.96
  5007.3  423.90  5017.3  427.83  5027.3  434.67  5107.4  433.36  5139.8  436.33
  5194.8  439.31  5387.5  446.85  5620.2  452.51  5657.5  452.23  5701.3  454.14
#Mann=6,-1,0
  3296.3    0.05       0  3711.1    0.12       0  4973.8    0.07       0
  5000.9    0.12       0  5194.8    0.16       0  5620.2    0.05       0
Bank Sta=3660.5,5139.8
Exp/Cntr=0.3,0.1

Type RM Length L Ch R = 1,11438,1511,1511,1511
BEGIN DESCRIPTION:
XS3061A
END DESCRIPTION:
XS GIS Cut Line= 3
      2791918.80      7041294.21      2790590.66      7040894.90
      2789080.22      7040808.09
#Sta/Elev= 30
  3606.3  451.90  3694.7  448.59  3844.3  437.13  3869.0  435.40  3954.9  431.86
  4017.5  433.28  4035.4  425.01  4048.8  425.16  4068.5  431.85  4111.9  432.60
  4414.3  432.56  4457.9  429.09  4490.9  429.41  4518.7  433.22  4633.6  433.00
  4685.8  429.10  4732.6  429.55  4770.8  432.89  4798.6  428.08  4831.6  432.64
  4941.2  431.39  4967.8  433.28  4985.3  418.72  4990.0  417.92  5012.4  418.72
  5018.9  431.89  5048.9  433.93  5660.9  432.41  6122.9  435.40  6506.1  445.53
#Mann=5,-1,0
  3606.3    0.16       0  3844.3    0.12       0  4985.3    0.07       0
  5012.4    0.12       0  5660.9    0.05       0
Bank Sta=3869,6122.9
Exp/Cntr=0.3,0.1

Type RM Length L Ch R = 1,9927,240,240,240
BEGIN DESCRIPTION:
XS3063A
END DESCRIPTION:
XS GIS Cut Line= 6
      2792439.60      7040625.80      2791684.41      7040547.67
      2791415.32      7040521.63      2791058.55      7040415.73
      2790781.64      7040443.51      2788915.28      7040452.19
#Sta/Elev= 30
  4144.2  453.54  4422.7  442.24  4631.2  436.48  4706.8  433.19  4715.3  432.93
  4963.1  430.01  4973.2  428.81  4979.6  417.70  4984.4  416.90  5006.8  417.70
  5023.4  429.70  5033.4  430.51  5268.0  427.16  5329.3  431.20  5499.2  433.55
  5559.5  426.66  5639.9  433.94  5680.1  429.55  5776.3  432.49  5974.8  432.45
  6371.0  431.96  6470.1  432.09  6616.3  432.20  7058.1  432.74  7152.8  433.19
  7347.2  435.52  7523.3  438.84  7620.9  441.37  7658.9  447.12  7690.6  449.67
#Mann=16,-1,0
  4144.2    0.05       0  4422.7    0.12       0  4631.2    0.05       0
  4715.3    0.12       0  4979.6    0.07       0  5006.8    0.12       0
  5329.3    0.08       0  5776.3    0.05       0  5974.8    0.07       0
  6371.0    0.12       0  6470.1    0.05       0  6616.3    0.12       0
  7058.1    0.16       0  7347.2    0.05       0  7523.3    0.08       0
  7658.9    0.05       0
Bank Sta=4706.8,7152.8
Exp/Cntr=0.3,0.1

Type RM Length L Ch R = 1,9687,651,651,651
BEGIN DESCRIPTION:
XS3062A
END DESCRIPTION:
XS GIS Cut Line= 4
      2792552.44      7040400.10      2791831.98      7040365.38
      2791632.33      7040339.34      2788880.62      7040191.77
#Sta/Elev= 30
  4179.5  450.06  4237.0  451.10  4257.0  446.90  4306.3  447.44  4608.7  433.51
  4634.9  432.89  4737.6  429.64  4958.3  429.80  4968.3  427.99  4978.4  419.42
  4985.0  416.47  4989.7  415.67  5012.2  416.47  5016.7  419.74  5021.8  426.79
  5028.8  429.62  5059.1  431.76  5209.4  430.88  5680.3  431.81  5720.3  426.00
  5740.4  431.46  5760.4  433.27  6002.0  431.94  6101.1  432.33  6299.2  431.78
  6737.7  431.38  7557.4  432.89  7773.3  441.49  7803.3  445.84  7857.8  449.00
#Mann=10,-1,0
  4179.5    0.08       0  4306.3    0.05       0  4608.7    0.12       0
  4985.0    0.07       0  5012.2    0.12       0  5209.4    0.05       0
  6002.0    0.08       0  6101.1    0.05       0  6299.2    0.08       0
  6737.7    0.05       0
Bank Sta=4634.9,7557.4
Exp/Cntr=0.3,0.1

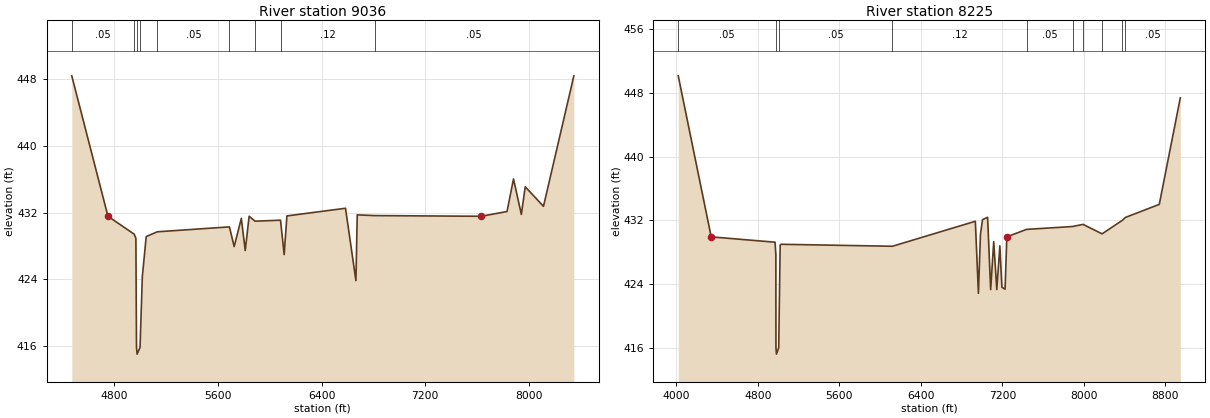
Type RM Length L Ch R = 1,9036,811,811,811
BEGIN DESCRIPTION:
XS3064A
END DESCRIPTION:
XS GIS Cut Line= 3
      2792607.16      7040292.47      2792233.89      7039936.56
      2788891.83      7039589.34
#Sta/Elev= 30
  4471.1  448.37  4750.5  431.55  4952.7  429.41  4966.0  428.92  4970.8  415.84
  4975.5  415.04  4998.0  415.84  5015.9  424.34  5045.7  429.12  5131.2  429.69
  5688.2  430.28  5724.7  427.92  5780.0  431.30  5810.1  427.45  5840.3  431.55
  5886.9  430.96  6082.5  431.08  6110.8  426.96  6131.9  431.59  6584.3  432.51
  6664.7  423.84  6674.8  431.72  6809.4  431.63  7632.8  431.55  7831.0  432.12
  7881.2  436.02  7941.6  431.77  7971.7  435.08  8112.5  432.74  8346.9  448.36
#Mann=9,-1,0
  4471.1    0.05       0  4952.7    0.12       0  4970.8    0.07       0
  4998.0    0.12       0  5131.2    0.05       0  5688.2    0.16       0
  5886.9    0.05       0  6082.5    0.12       0  6809.4    0.05       0
Bank Sta=4750.5,7632.8
Exp/Cntr=0.3,0.1

Type RM Length L Ch R = 1,8225,0,0,0
BEGIN DESCRIPTION:
XS3065A
END DESCRIPTION:
XS GIS Cut Line= 4
      2793108.47      7040257.77      2792880.59      7039433.09
      2792565.92      7039194.38      2788899.16      7039487.28
#Sta/Elev= 30
  4017.8  450.14  4341.4  429.91  4968.3  429.24  4976.2  427.69  4977.1  415.98
  4981.9  415.18  5004.3  415.98  5018.5  428.89  5026.1  428.98  6120.6  428.73
  6934.6  431.87  6964.7  422.82  6984.7  430.20  7004.8  432.07  7054.9  432.37
  7085.0  423.29  7115.1  429.31  7145.2  423.29  7175.3  428.78  7195.4  423.58
  7226.6  423.34  7243.5  429.91  7437.1  430.85  7889.7  431.21  7991.5  431.48
  8178.9  430.29  8378.0  431.99  8407.8  432.35  8740.3  433.99  8946.8  447.37
#Mann=10,-1,0
  4017.8    0.05       0  4977.1    0.03       0  5004.3    0.05       0
  6120.6    0.12       0  7437.1    0.05       0  7889.7    0.12       0
  7991.5    0.05       0  8178.9    0.16       0  8378.0    0.12       0
  8407.8    0.05       0
Bank Sta=4341.4,7243.5
Exp/Cntr=0.3,0.1

Chan Stop Cuts=-1