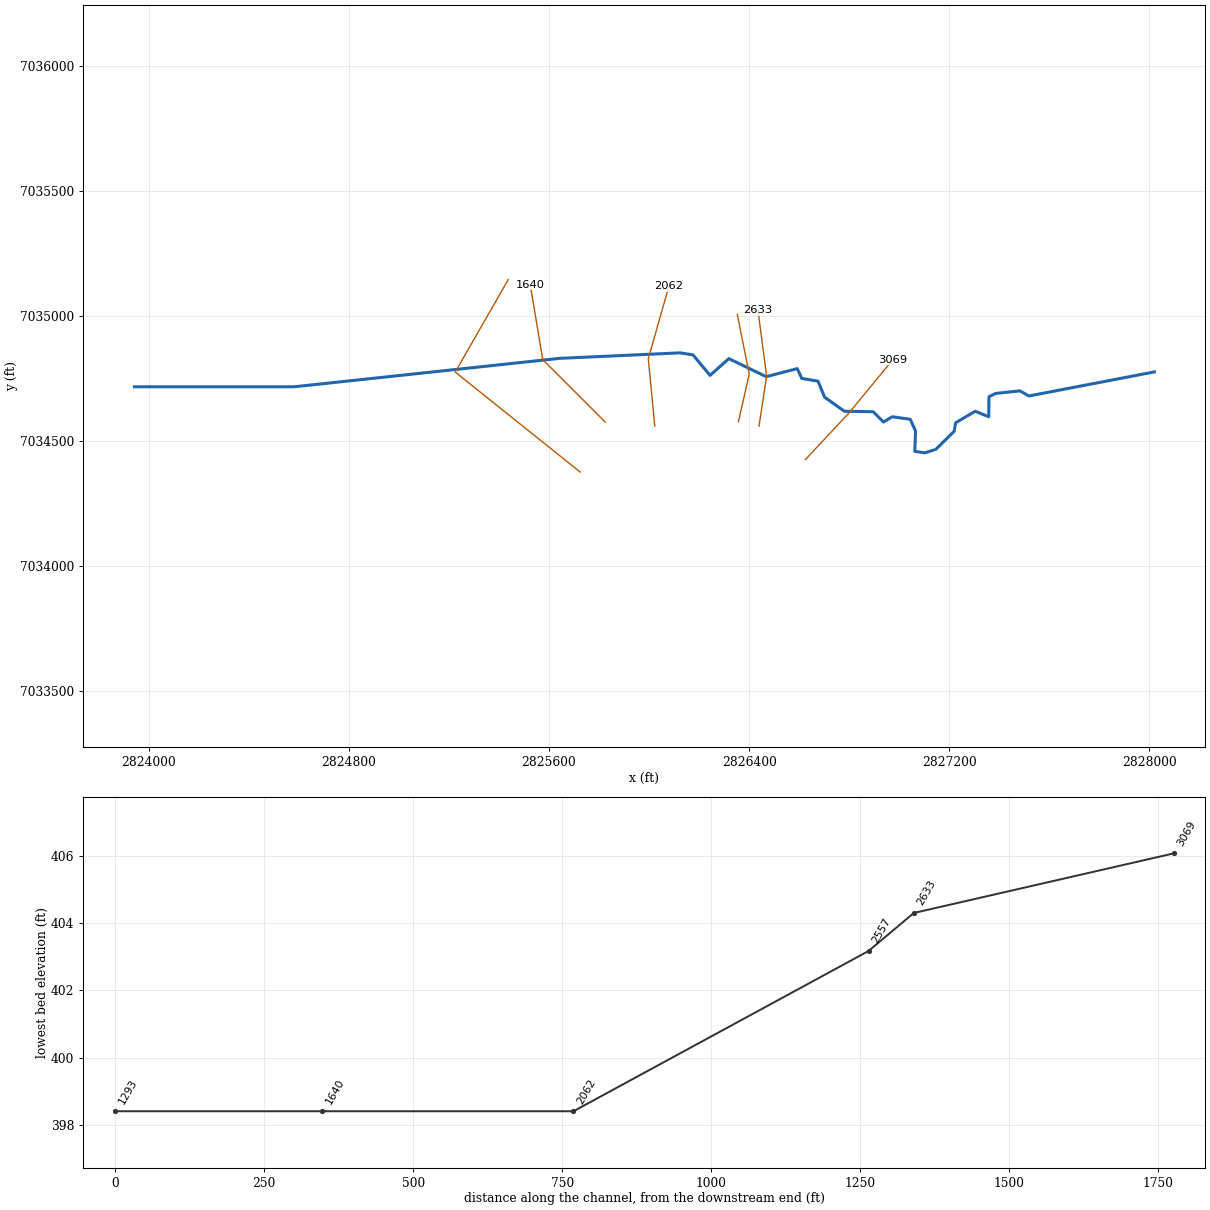
--- UNT 001 in LFCCL Watershed.prj (project) ---

Proj Title=UNT 001 in LFCCL Watershed Base Level Engineering
Current Plan=p01
Default Exp/Contr=0.3,0.1
English Units
Geom File=g01
Flow File=f01
Plan File=p01
BEGIN DESCRIPTION:
UNT 001 in LFCCL Watershed
END DESCRIPTION:

--- UNT 001 in LFCCL Watershed.p01 (plan) ---

Plan Title=Multiple Run
Short Identifier=Multiple
Geom File=g01
Flow File=f01
Subcritical Flow
K Sum by GR= 0
Std Step Tol= 0.01
Critical Tol= 0.01
Num of Std Step Trials= 20
Max Error Tol= 0.3
Flow Tol Ratio= 0.001
Split Flow NTrial= 30
Split Flow Tol= 0.02
Split Flow Ratio= 0.02
Log Output Level= 0
Friction Slope Method= 1
Unsteady Friction Slope Method= 2
Unsteady Bridges Friction Slope Method= 1
Parabolic Critical Depth
Global Vel Dist=  1 , 1 , 1
Global Log Level= 0
CheckData=True
Encroach Param= -1, 0, 0, 0
BEGIN DESCRIPTION:
Multiple Run
END DESCRIPTION:

--- UNT 001 in LFCCL Watershed.f01 (steady flow) ---

Flow Title=Multiple
Number of Profiles=7
Profile Names=10-year,25-year,50-year,1pct_min,100-year,1pct_plu,500-year
River Rch & RM= UNT 001 in LFCCL,Reach-1,3069
     224     278     318     181     362     722     467
Boundary for River Rch & Prof#=UNT 001 in LFCCL,Reach-1,1
Up Type=0
Dn Type=3
Dn Slope=0.005
Boundary for River Rch & Prof#=UNT 001 in LFCCL,Reach-1,2
Up Type=0
Dn Type=3
Dn Slope=0.005
Boundary for River Rch & Prof#=UNT 001 in LFCCL,Reach-1,3
Up Type=0
Dn Type=3
Dn Slope=0.005
Boundary for River Rch & Prof#=UNT 001 in LFCCL,Reach-1,4
Up Type=0
Dn Type=3
Dn Slope=0.005
Boundary for River Rch & Prof#=UNT 001 in LFCCL,Reach-1,5
Up Type=0
Dn Type=3
Dn Slope=0.005
Boundary for River Rch & Prof#=UNT 001 in LFCCL,Reach-1,6
Up Type=0
Dn Type=3
Dn Slope=0.005
Boundary for River Rch & Prof#=UNT 001 in LFCCL,Reach-1,7
Up Type=0
Dn Type=3
Dn Slope=0.005

--- UNT 001 in LFCCL Watershed.g01 (geometry) ---

Geom Title=Existing Conditions

River Reach=UNT 001 in LFCCL,Reach-1
Reach XY= 30
      2828020.59      7034775.71      2827518.68      7034679.45
      2827482.32      7034700.04      2827385.86      7034689.48
      2827359.12      7034676.52      2827358.11      7034596.37
      2827304.01      7034618.41      2827225.86      7034572.32
      2827219.84      7034538.25      2827146.70      7034466.11
      2827102.62      7034452.09      2827062.54      7034458.10
      2827065.54      7034539.26      2827044.50      7034586.35
      2826972.36      7034596.37      2826937.29      7034575.33
      2826896.21      7034616.41      2826780.99      7034618.41
      2826701.84      7034674.52      2826675.78      7034738.64
      2826610.66      7034749.67      2826592.62      7034788.74
      2826468.38      7034756.68      2826319.09      7034828.82
      2826243.94      7034761.69      2826175.81      7034843.85
      2826123.71      7034851.87      2825641.77      7034829.82
      2824581.17      7034716.21      2823942.44      7034716.21

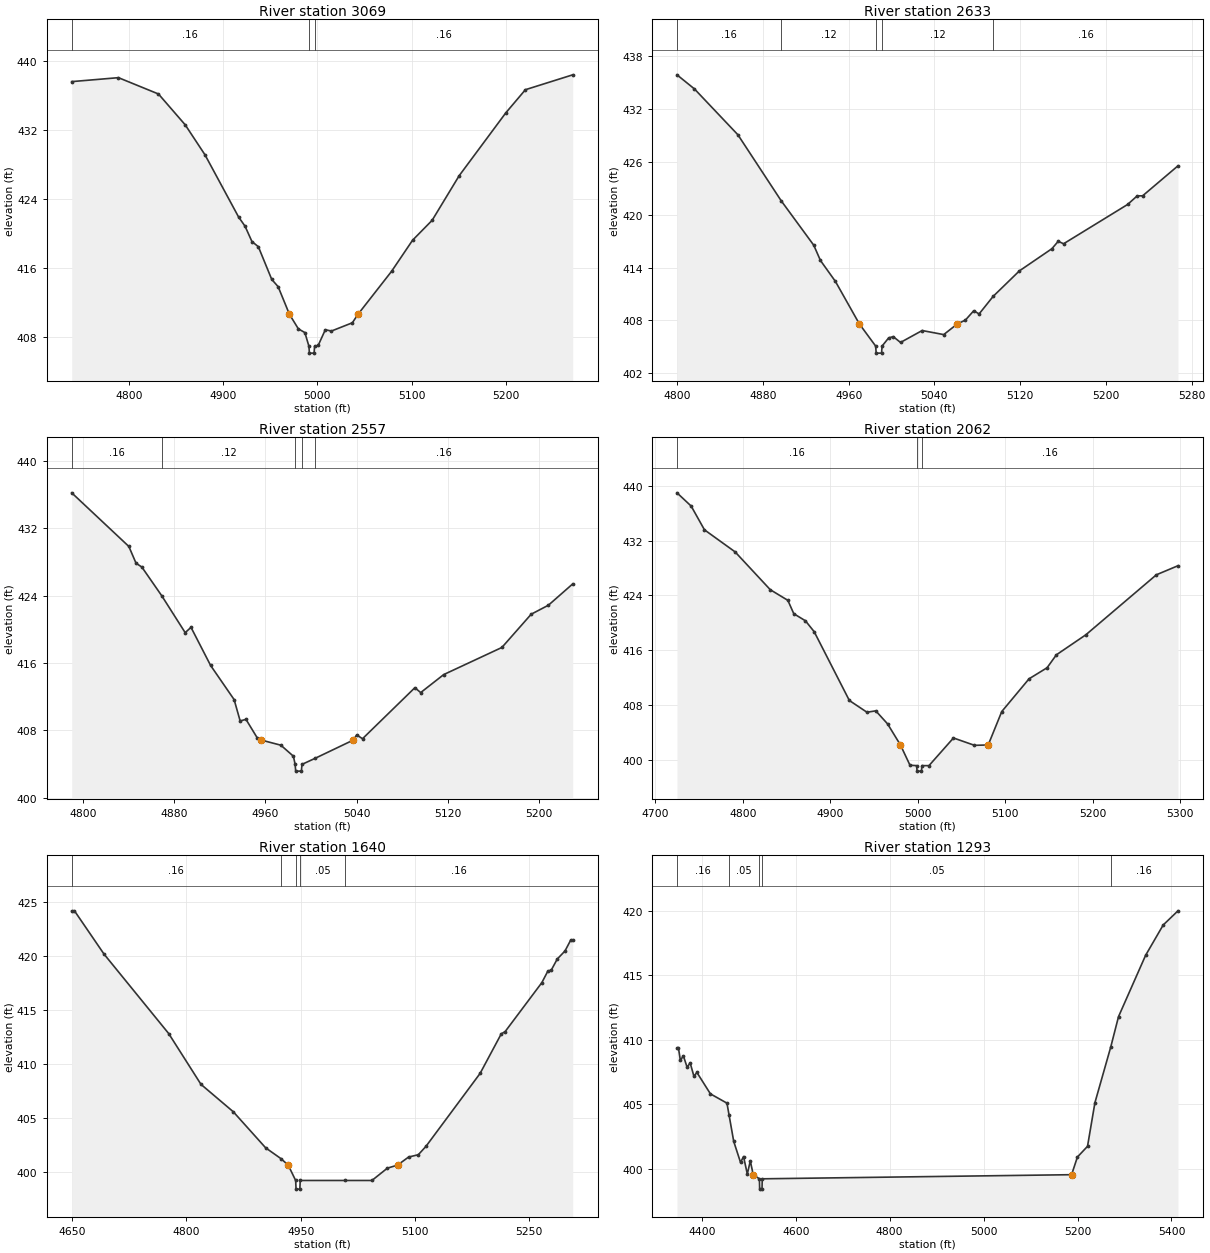
Type RM Length L Ch R = 1,3069,436,436,436
BEGIN DESCRIPTION:
UNT 001 in LFCCL Watershed 3.0
END DESCRIPTION:
XS GIS Cut Line= 3
      2826624.97      7034424.97      2826800.38      7034612.66
      2826974.99      7034824.99
#Sta/Elev= 30
  4739.2  437.65  4788.8  438.11  4831.3  436.21  4859.7  432.62  4880.7  429.13
  4916.3  421.91  4923.2  420.83  4930.5  419.05  4937.3  418.45  4951.5  414.65
  4958.3  413.80  4970.3  410.59  4979.8  408.89  4986.7  408.46  4991.0  406.87
  4991.5  406.07  4996.5  406.07  4997.0  406.87  5000.8  406.96  5008.4  408.79
  5014.9  408.64  5037.1  409.60  5043.1  410.59  5078.7  415.58  5101.0  419.20
  5121.8  421.52  5150.5  426.71  5200.0  434.02  5220.8  436.71  5271.0  438.44
#Mann=3,-1,0
  4739.2    0.16       0  4991.0    0.07       0  4997.0    0.16       0
Bank Sta=4970.3,5043.1
Exp/Cntr=0.3,0.1

Type RM Length L Ch R = 1,2633,76,76,76
BEGIN DESCRIPTION:
XS3068A
END DESCRIPTION:
XS GIS Cut Line= 3
      2826439.70      7034558.86      2826470.08      7034758.49
      2826435.58      7035021.61
#Sta/Elev= 30
  4799.9  435.83  4816.2  434.23  4856.7  429.04  4897.1  421.56  4927.5  416.52
  4933.7  414.80  4947.7  412.42  4970.0  407.61  4985.2  405.10  4985.7  404.30
  4990.7  404.30  4991.2  405.10  4997.3  406.02  5001.6  406.17  5008.4  405.51
  5028.6  406.86  5048.7  406.40  5061.4  407.61  5068.9  408.04  5076.7  409.10
  5081.7  408.74  5094.8  410.73  5119.3  413.62  5149.6  416.13  5155.5  416.97
  5160.5  416.69  5220.2  421.14  5229.2  422.12  5234.2  422.12  5267.2  425.52
#Mann=5,-1,0
  4799.9    0.16       0  4897.1    0.12       0  4985.2    0.07       0
  4991.2    0.12       0  5094.8    0.16       0
Bank Sta=4970,5061.4
Exp/Cntr=0.3,0.1

Type RM Length L Ch R = 1,2557,495,495,495
BEGIN DESCRIPTION:
XS3067A
END DESCRIPTION:
XS GIS Cut Line= 3
      2826357.23      7034576.19      2826400.64      7034767.17
      2826352.89      7035005.89
#Sta/Elev= 30
  4790.1  436.23  4840.2  429.86  4846.5  427.87  4851.6  427.41  4869.0  424.01
  4889.6  419.62  4894.7  420.25  4911.9  415.72  4932.5  411.67  4937.8  409.13
  4942.9  409.32  4953.0  407.07  4956.3  406.86  4973.5  406.25  4984.5  404.94
  4986.0  403.97  4986.5  403.17  4991.5  403.17  4992.0  403.97  5003.5  404.69
  5037.0  406.86  5040.0  407.47  5045.1  407.02  5091.0  413.08  5096.1  412.50
  5116.3  414.64  5167.3  417.86  5193.0  421.81  5208.1  422.88  5229.4  425.41
#Mann=5,-1,0
  4790.1    0.16       0  4869.0    0.12       0  4986.0    0.07       0
  4992.0    0.12       0  5003.5    0.16       0
Bank Sta=4956.3,5037
Exp/Cntr=0.3,0.1

Type RM Length L Ch R = 1,2062,422,422,422
BEGIN DESCRIPTION:
XS3066A
END DESCRIPTION:
XS GIS Cut Line= 3
      2826023.03      7034558.89      2825996.99      7034827.94
      2826079.47      7035118.76
#Sta/Elev= 30
  4724.7  438.95  4740.9  437.02  4756.1  433.56  4791.1  430.35  4831.3  424.84
  4851.4  423.29  4858.2  421.34  4871.5  420.31  4881.5  418.72  4921.7  408.70
  4941.8  406.99  4951.9  407.19  4965.4  405.29  4980.1  402.22  4991.0  399.27
  4998.6  399.21  4999.1  398.41  5004.1  398.41  5004.6  399.21  5012.7  399.21
  5040.7  403.24  5064.7  402.17  5080.4  402.22  5095.9  407.09  5127.1  411.86
  5147.7  413.47  5158.3  415.35  5192.0  418.27  5272.6  427.01  5297.3  428.33
#Mann=3,-1,0
  4724.7    0.16       0  4998.6    0.07       0  5004.6    0.16       0
Bank Sta=4980.1,5080.4
Exp/Cntr=0.3,0.1

Type RM Length L Ch R = 1,1640,347,347,347
BEGIN DESCRIPTION:
UNT 001 in LFCCL Watershed 2.0
END DESCRIPTION:
XS GIS Cut Line= 3
      2825825.02      7034574.98      2825575.00      7034825.00
      2825525.00      7035124.99
#Sta/Elev= 30
  4649.4  424.15  4653.0  424.15  4691.8  420.15  4776.7  412.80  4819.1  408.10
  4861.6  405.56  4904.0  402.23  4924.1  401.23  4933.6  400.63  4943.4  399.21
  4943.9  398.41  4948.9  398.41  4949.4  399.21  5007.9  399.21  5043.5  399.21
  5063.8  400.35  5077.1  400.63  5091.7  401.38  5104.4  401.59  5114.5  402.37
  5185.5  409.11  5213.3  412.77  5218.4  412.98  5266.6  417.51  5274.2  418.54
  5279.2  418.70  5286.8  419.69  5297.0  420.44  5304.6  421.46  5307.1  421.46
#Mann=5,-1,0
  4649.4    0.16       0  4924.1    0.05       0  4943.4   0.035       0
  4949.4    0.05       0  5007.9    0.16       0
Bank Sta=4933.6,5077.1
Exp/Cntr=0.3,0.1

Type RM Length L Ch R = 1,1293,0,0,0
BEGIN DESCRIPTION:
UNT 001 in LFCCL Watershed 1.0
END DESCRIPTION:
XS GIS Cut Line= 3
      2825724.99      7034375.01      2825225.00      7034775.00
      2825437.10      7035144.79
#Sta/Elev= 30
  4347.2  409.34  4350.4  409.34  4354.4  408.40  4360.8  408.75  4368.8  407.86
  4375.2  408.21  4383.2  407.17  4389.6  407.46  4418.4  405.80  4453.6  405.08
  4458.1  404.15  4468.0  402.11  4482.5  400.48  4488.9  400.94  4496.9  399.58
  4503.3  400.60  4509.5  399.53  4522.7  399.21  4523.2  398.41  4528.2  398.41
  4528.7  399.21  5187.3  399.53  5199.7  400.90  5221.2  401.73  5237.0  405.12
  5270.7  409.44  5287.2  411.79  5344.9  416.55  5382.3  418.90  5413.8  420.00
#Mann=5,-1,0
  4347.2    0.16       0  4458.1    0.05       0  4522.7   0.033       0
  4528.7    0.05       0  5270.7    0.16       0
Bank Sta=4509.5,5187.3
Exp/Cntr=0.3,0.1

Chan Stop Cuts=-1