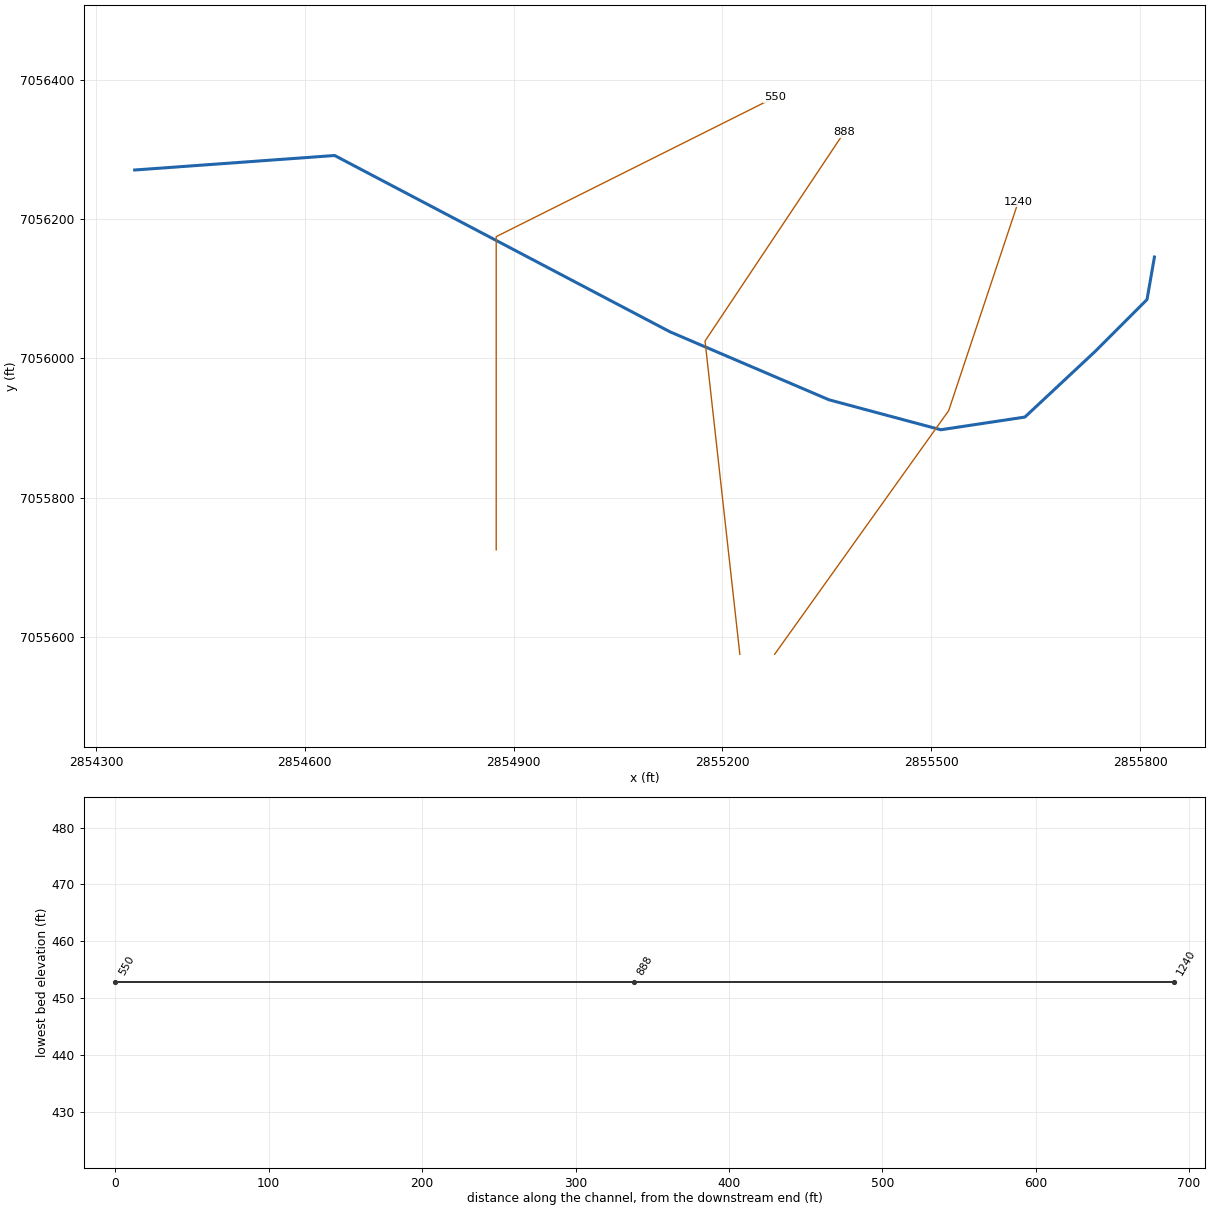
--- UNT 002 in LFCCL Watershed.prj (project) ---

Proj Title=UNT 002 in LFCCL Watershed Base Level Engineering
Current Plan=p01
Default Exp/Contr=0.3,0.1
English Units
Geom File=g01
Flow File=f01
Plan File=p01
BEGIN DESCRIPTION:
UNT 002 in LFCCL Watershed
END DESCRIPTION:

--- UNT 002 in LFCCL Watershed.p01 (plan) ---

Plan Title=Multiple Run
Short Identifier=Multiple
Geom File=g01
Flow File=f01
Subcritical Flow
K Sum by GR= 0
Std Step Tol= 0.01
Critical Tol= 0.01
Num of Std Step Trials= 20
Max Error Tol= 0.3
Flow Tol Ratio= 0.001
Split Flow NTrial= 30
Split Flow Tol= 0.02
Split Flow Ratio= 0.02
Log Output Level= 0
Friction Slope Method= 1
Unsteady Friction Slope Method= 2
Unsteady Bridges Friction Slope Method= 1
Parabolic Critical Depth
Global Vel Dist=  1 , 1 , 1
Global Log Level= 0
CheckData=True
Encroach Param= -1, 0, 0, 0
BEGIN DESCRIPTION:
Multiple Run
END DESCRIPTION:

--- UNT 002 in LFCCL Watershed.f01 (steady flow) ---

Flow Title=Multiple
Number of Profiles=7
Profile Names=10-year,25-year,50-year,1pct_min,100-year,1pct_plu,500-year
River Rch & RM= UNT 002 in LFCCL,Reach-1,1240
     191     239     276     159     317     632     418
Boundary for River Rch & Prof#=UNT 002 in LFCCL,Reach-1,1
Up Type=0
Dn Type=3
Dn Slope=0.005
Boundary for River Rch & Prof#=UNT 002 in LFCCL,Reach-1,2
Up Type=0
Dn Type=3
Dn Slope=0.005
Boundary for River Rch & Prof#=UNT 002 in LFCCL,Reach-1,3
Up Type=0
Dn Type=3
Dn Slope=0.005
Boundary for River Rch & Prof#=UNT 002 in LFCCL,Reach-1,4
Up Type=0
Dn Type=3
Dn Slope=0.005
Boundary for River Rch & Prof#=UNT 002 in LFCCL,Reach-1,5
Up Type=0
Dn Type=3
Dn Slope=0.005
Boundary for River Rch & Prof#=UNT 002 in LFCCL,Reach-1,6
Up Type=0
Dn Type=3
Dn Slope=0.005
Boundary for River Rch & Prof#=UNT 002 in LFCCL,Reach-1,7
Up Type=0
Dn Type=3
Dn Slope=0.005

--- UNT 002 in LFCCL Watershed.g01 (geometry) ---

Geom Title=Existing Conditions

River Reach=UNT 002 in LFCCL,Reach-1
Reach XY= 9
      2855820.59      7056145.71      2855809.94      7056084.62
      2855735.45      7056010.12      2855634.47      7055915.77
      2855513.63      7055897.56      2855353.06      7055940.60
      2855124.62      7056038.27      2854642.91      7056291.54
      2854355.59      7056270.71

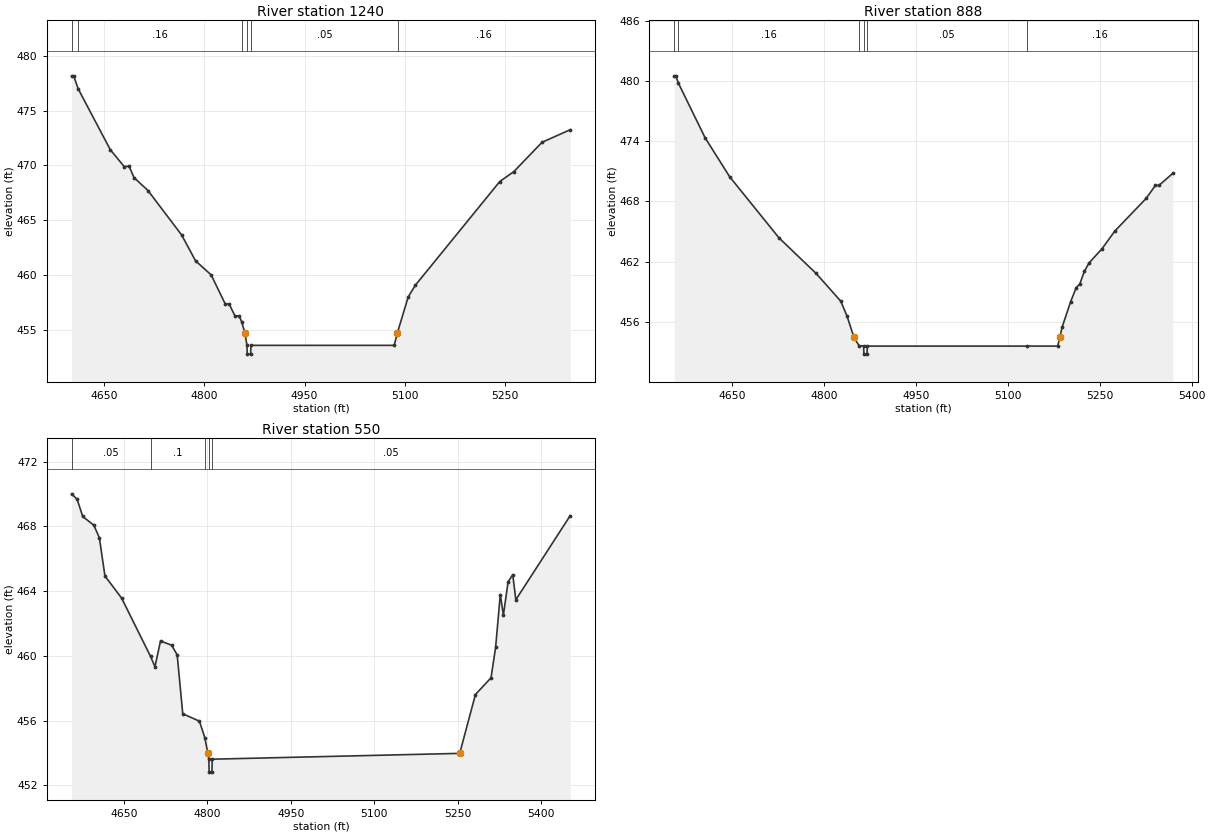
Type RM Length L Ch R = 1,1240,352,352,352
BEGIN DESCRIPTION:
UNT 002 in LFCCL Watershed 3.0
END DESCRIPTION:
XS GIS Cut Line= 3
      2855274.98      7055574.98      2855525.00      7055925.00
      2855625.01      7056225.02
#Sta/Elev= 30
  4601.3  478.17  4604.4  478.17  4611.2  476.98  4659.1  471.45  4680.0  469.90
  4687.4  469.93  4694.7  468.90  4715.6  467.72  4766.0  463.67  4786.9  461.31
  4810.2  460.03  4831.1  457.41  4837.3  457.36  4845.9  456.28  4852.0  456.31
  4855.8  455.78  4860.9  454.70  4863.8  453.61  4864.3  452.81  4869.3  452.81
  4869.8  453.61  5084.2  453.61  5088.9  454.70  5090.0  454.95  5105.2  458.02
  5115.8  459.08  5242.3  468.54  5263.3  469.44  5305.5  472.11  5347.7  473.26
#Mann=6,-1,0
  4601.3    0.08       0  4611.2    0.16       0  4855.8    0.05       0
  4863.8   0.035       0  4869.8    0.05       0  5090.0    0.16       0
Bank Sta=4860.9,5088.9
Exp/Cntr=0.3,0.1

Type RM Length L Ch R = 1,888,338,338,338
BEGIN DESCRIPTION:
UNT 002 in LFCCL Watershed 2.0
END DESCRIPTION:
XS GIS Cut Line= 3
      2855225.00      7055575.03      2855175.00      7056025.00
      2855375.00      7056325.00
#Sta/Elev= 30
  4556.0  480.50  4558.5  480.50  4562.8  479.77  4606.3  474.34  4646.5  470.45
  4727.0  464.37  4787.4  460.84  4827.6  458.08  4837.7  456.62  4849.1  454.49
  4857.3  453.66  4864.9  453.61  4865.4  452.81  4870.4  452.81  4870.9  453.61
  5131.6  453.61  5181.5  453.61  5184.9  454.49  5189.0  455.55  5202.5  458.01
  5211.6  459.41  5217.6  459.80  5225.1  461.06  5232.6  461.88  5253.6  463.28
  5274.6  465.05  5325.7  468.30  5340.8  469.59  5346.8  469.60  5369.3  470.80
#Mann=6,-1,0
  4556.0    0.08       0  4562.8    0.16       0  4857.3    0.05       0
  4864.9   0.033       0  4870.9    0.05       0  5131.6    0.16       0
Bank Sta=4849.1,5184.9
Exp/Cntr=0.3,0.1

Type RM Length L Ch R = 1,550,0,0,0
BEGIN DESCRIPTION:
UNT 002 in LFCCL Watershed 1.0
END DESCRIPTION:
XS GIS Cut Line= 3
      2854875.00      7055725.01      2854875.00      7056175.00
      2855275.00      7056375.00
#Sta/Elev= 30
  4555.5  470.02  4565.5  469.68  4575.5  468.62  4595.5  468.08  4605.5  467.30
  4615.5  464.94  4645.5  463.57  4697.5  459.97  4705.5  459.33  4715.5  460.92
  4735.5  460.66  4745.5  460.06  4755.5  456.42  4785.5  455.96  4795.3  454.93
  4800.6  453.97  4802.5  453.61  4803.0  452.81  4808.0  452.81  4808.5  453.61
  5253.9  453.97  5282.2  457.61  5310.2  458.64  5318.5  460.52  5326.9  463.79
  5332.5  462.52  5340.9  464.57  5349.3  465.02  5354.9  463.47  5452.7  468.67
#Mann=5,-1,0
  4555.5    0.05       0  4697.5     0.1       0  4795.3    0.05       0
  4802.5   0.033       0  4808.5    0.05       0
Bank Sta=4800.6,5253.9
Exp/Cntr=0.3,0.1

Chan Stop Cuts=-1