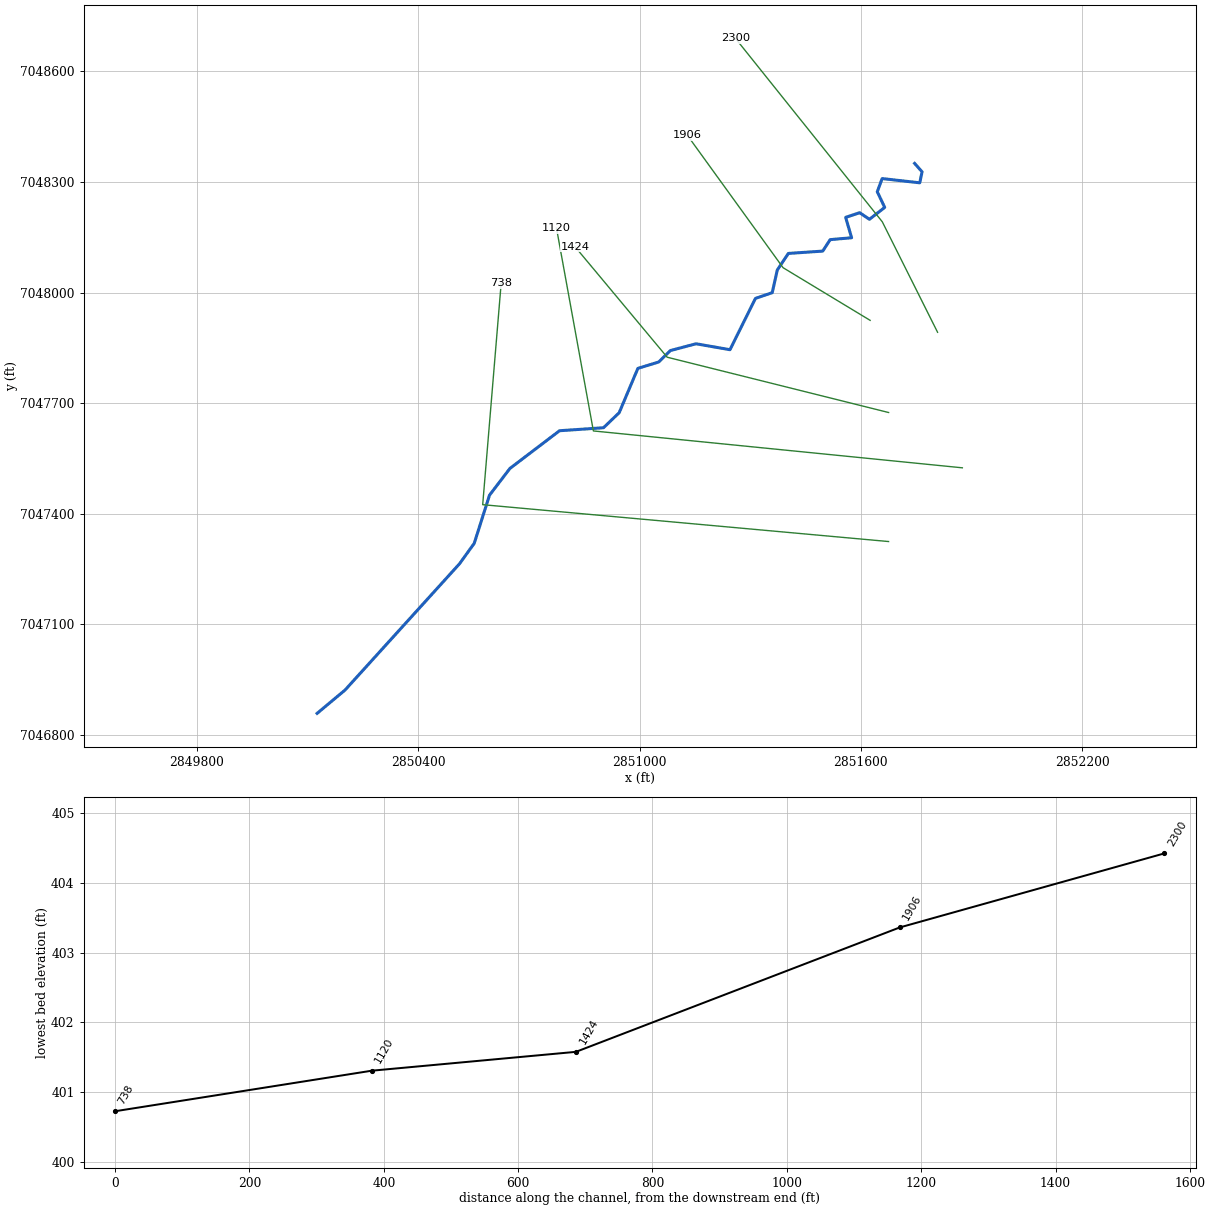
--- UNT 003 in LFCCL Watershed.prj (project) ---

Proj Title=UNT 003 in LFCCL Watershed Base Level Engineering
Current Plan=p01
Default Exp/Contr=0.3,0.1
English Units
Geom File=g01
Flow File=f01
Plan File=p01
BEGIN DESCRIPTION:
UNT 003 in LFCCL Watershed
END DESCRIPTION:

--- UNT 003 in LFCCL Watershed.p01 (plan) ---

Plan Title=Multiple Run
Short Identifier=Multiple
Geom File=g01
Flow File=f01
Subcritical Flow
K Sum by GR= 0
Std Step Tol= 0.01
Critical Tol= 0.01
Num of Std Step Trials= 20
Max Error Tol= 0.3
Flow Tol Ratio= 0.001
Split Flow NTrial= 30
Split Flow Tol= 0.02
Split Flow Ratio= 0.02
Log Output Level= 0
Friction Slope Method= 1
Unsteady Friction Slope Method= 2
Unsteady Bridges Friction Slope Method= 1
Parabolic Critical Depth
Global Vel Dist=  1 , 1 , 1
Global Log Level= 0
CheckData=True
Encroach Param= -1, 0, 0, 0
BEGIN DESCRIPTION:
Multiple Run
END DESCRIPTION:

--- UNT 003 in LFCCL Watershed.f01 (steady flow) ---

Flow Title=Multiple
Number of Profiles=7
Profile Names=10-year,25-year,50-year,1pct_min,100-year,1pct_plu,500-year
River Rch & RM= UNT 003 in LFCCL,Reach-1,2300
     435     573     683     406     810    1615    1138
Boundary for River Rch & Prof#=UNT 003 in LFCCL,Reach-1,1
Up Type=0
Dn Type=3
Dn Slope=0.005
Boundary for River Rch & Prof#=UNT 003 in LFCCL,Reach-1,2
Up Type=0
Dn Type=3
Dn Slope=0.005
Boundary for River Rch & Prof#=UNT 003 in LFCCL,Reach-1,3
Up Type=0
Dn Type=3
Dn Slope=0.005
Boundary for River Rch & Prof#=UNT 003 in LFCCL,Reach-1,4
Up Type=0
Dn Type=3
Dn Slope=0.005
Boundary for River Rch & Prof#=UNT 003 in LFCCL,Reach-1,5
Up Type=0
Dn Type=3
Dn Slope=0.005
Boundary for River Rch & Prof#=UNT 003 in LFCCL,Reach-1,6
Up Type=0
Dn Type=3
Dn Slope=0.005
Boundary for River Rch & Prof#=UNT 003 in LFCCL,Reach-1,7
Up Type=0
Dn Type=3
Dn Slope=0.005

--- UNT 003 in LFCCL Watershed.g01 (geometry) ---

Geom Title=Existing Conditions

River Reach=UNT 003 in LFCCL,Reach-1
Reach XY= 30
      2851745.59      7048350.71      2851765.78      7048327.95
      2851759.46      7048298.04      2851657.64      7048309.55
      2851644.41      7048273.88      2851664.54      7048231.31
      2851623.13      7048199.10      2851596.67      7048216.93
      2851558.70      7048204.28      2851574.81      7048149.06
      2851516.71      7048143.88      2851496.57      7048112.82
      2851403.39      7048106.49      2851373.47      7048061.62
      2851359.67      7048000.07      2851314.23      7047984.54
      2851245.20      7047845.33      2851153.16      7047861.44
      2851083.56      7047843.03      2851051.92      7047811.97
      2850995.55      7047794.71      2850944.93      7047674.49
      2850902.36      7047633.65      2850783.28      7047625.59
      2850648.68      7047523.20      2850593.46      7047450.72
      2850552.04      7047320.14      2850512.35      7047264.92
      2850201.90      7046922.14      2850126.20      7046858.91

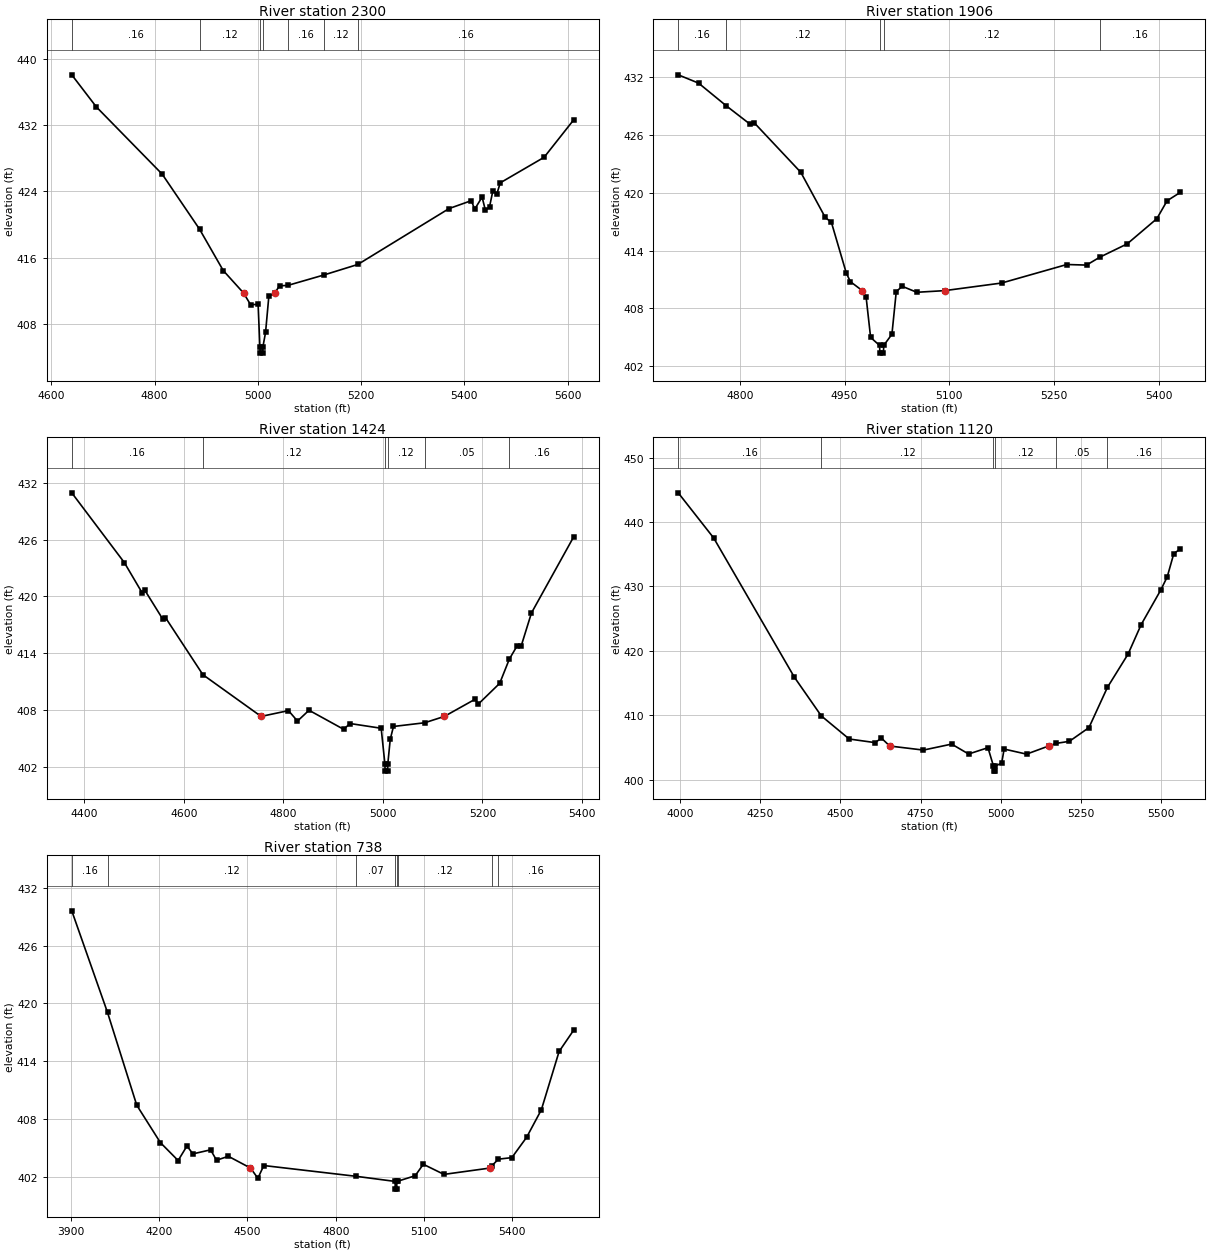
Type RM Length L Ch R = 1,2300,394,394,394
BEGIN DESCRIPTION:
UNT 003 in LFCCL Watershed 5.0
END DESCRIPTION:
XS GIS Cut Line= 3
      2851807.85      7047892.54      2851657.86      7048192.52
      2851259.92      7048689.94
#Sta/Elev= 30
  4639.6  438.13  4687.1  434.25  4814.7  426.10  4887.0  419.44  4933.0  414.42
  4972.2  411.71  4986.1  410.27  5000.5  410.34  5003.9  405.22  5004.4  404.42
  5009.4  404.42  5009.9  405.22  5014.9  406.92  5021.3  411.32  5032.5  411.71
  5042.2  412.57  5058.4  412.63  5127.6  413.88  5193.6  415.16  5370.3  421.93
  5413.5  422.89  5419.9  421.85  5434.3  423.32  5440.7  421.72  5448.7  422.14
  5455.1  424.06  5463.1  423.75  5469.5  425.05  5554.4  428.14  5612.0  432.70
#Mann=7,-1,0
  4639.6    0.16       0  4887.0    0.12       0  5003.9    0.07       0
  5009.9    0.12       0  5058.4    0.16       0  5127.6    0.12       0
  5193.6    0.16       0
Bank Sta=4972.2,5032.5
Exp/Cntr=0.3,0.1

Type RM Length L Ch R = 1,1906,482,482,482
BEGIN DESCRIPTION:
UNT 003 in LFCCL Watershed 4.0
END DESCRIPTION:
XS GIS Cut Line= 3
      2851625.04      7047924.98      2851389.04      7048067.81
      2851129.88      7048426.65
#Sta/Elev= 30
  4711.9  432.22  4741.0  431.36  4780.6  429.01  4814.7  427.10  4820.6  427.25
  4887.3  422.11  4922.3  417.43  4931.1  416.92  4952.5  411.64  4958.3  410.77
  4975.3  409.84  4980.8  409.15  4987.2  404.99  5000.0  404.16  5000.5  403.36
  5005.5  403.36  5006.0  404.16  5017.7  405.32  5023.9  409.74  5032.4  410.29
  5053.3  409.67  5093.1  409.84  5174.7  410.63  5268.0  412.55  5296.2  412.49
  5315.2  413.31  5354.4  414.69  5396.8  417.30  5411.5  419.16  5430.4  420.03
#Mann=5,-1,0
  4711.9    0.16       0  4780.6    0.12       0  5000.0    0.07       0
  5006.0    0.12       0  5315.2    0.16       0
Bank Sta=4975.3,5093.1
Exp/Cntr=0.3,0.1

Type RM Length L Ch R = 1,1424,304,304,304
BEGIN DESCRIPTION:
UNT 003 in LFCCL Watershed 3.0
END DESCRIPTION:
XS GIS Cut Line= 3
      2851675.04      7047674.99      2851075.00      7047825.00
      2850825.01      7048124.99
#Sta/Elev= 30
  4374.6  430.93  4480.3  423.57  4516.4  420.35  4521.5  420.65  4557.6  417.60
  4562.8  417.78  4638.1  411.75  4755.1  407.35  4810.1  407.96  4828.2  406.86
  4851.4  408.00  4921.0  405.99  4933.8  406.60  4996.4  406.10  5003.8  402.38
  5004.3  401.58  5009.3  401.58  5009.8  402.38  5014.6  404.93  5021.1  406.29
  5083.8  406.68  5123.4  407.35  5185.1  409.16  5191.6  408.65  5234.6  410.84
  5254.0  413.40  5269.7  414.80  5277.5  414.73  5298.4  418.26  5383.6  426.32
#Mann=6,-1,0
  4374.6    0.16       0  4638.1    0.12       0  5003.8    0.07       0
  5009.8    0.12       0  5083.8    0.05       0  5254.0    0.16       0
Bank Sta=4755.1,5123.4
Exp/Cntr=0.3,0.1

Type RM Length L Ch R = 1,1120,382,382,382
BEGIN DESCRIPTION:
UNT 003 in LFCCL Watershed 2.0
END DESCRIPTION:
XS GIS Cut Line= 3
      2851875.00      7047525.00      2850875.00      7047625.00
      2850775.00      7048175.00
#Sta/Elev= 30
  3995.0  444.55  4105.5  437.53  4356.8  415.90  4440.7  409.89  4527.6  406.30
  4608.0  405.74  4628.1  406.43  4653.9  405.21  4758.8  404.58  4846.7  405.51
  4899.5  403.97  4959.8  404.95  4976.9  402.11  4977.4  401.31  4982.4  401.31
  4982.9  402.11  5002.5  402.55  5010.2  404.74  5080.0  403.95  5148.7  405.21
  5172.0  405.62  5213.4  405.94  5274.4  408.07  5331.9  414.32  5396.4  419.51
  5437.0  424.07  5498.0  429.44  5518.3  431.50  5538.7  435.11  5559.0  435.83
#Mann=6,-1,0
  3995.0    0.16       0  4440.7    0.12       0  4976.9    0.07       0
  4982.9    0.12       0  5172.0    0.05       0  5331.9    0.16       0
Bank Sta=4653.9,5148.7
Exp/Cntr=0.3,0.1

Type RM Length L Ch R = 1,738,0,0,0
BEGIN DESCRIPTION:
UNT 003 in LFCCL Watershed 1.0
END DESCRIPTION:
XS GIS Cut Line= 3
      2851675.01      7047325.00      2850575.00      7047425.00
      2850625.00      7048024.97
#Sta/Elev= 30
  3902.8  429.62  4024.3  419.07  4123.7  409.44  4204.0  405.56  4264.3  403.70
  4294.4  405.21  4314.5  404.39  4374.7  404.81  4394.8  403.73  4435.0  404.14
  4510.3  402.92  4535.4  401.86  4555.5  403.18  4869.6  402.06  5001.8  401.53
  5002.3  400.73  5007.3  400.73  5007.8  401.53  5010.7  401.55  5070.1  402.12
  5097.7  403.31  5167.9  402.26  5324.6  402.92  5331.2  403.17  5352.9  403.84
  5398.7  404.00  5448.9  406.11  5499.0  408.97  5559.3  415.02  5609.4  417.26
#Mann=8,-1,0
  3902.8    0.16       0  4024.3    0.12       0  4869.6    0.07       0
  5001.8    0.07       0  5007.8    0.07       0  5010.7    0.12       0
  5331.2    0.05       0  5352.9    0.16       0
Bank Sta=4510.3,5324.6
Exp/Cntr=0.3,0.1

Chan Stop Cuts=-1