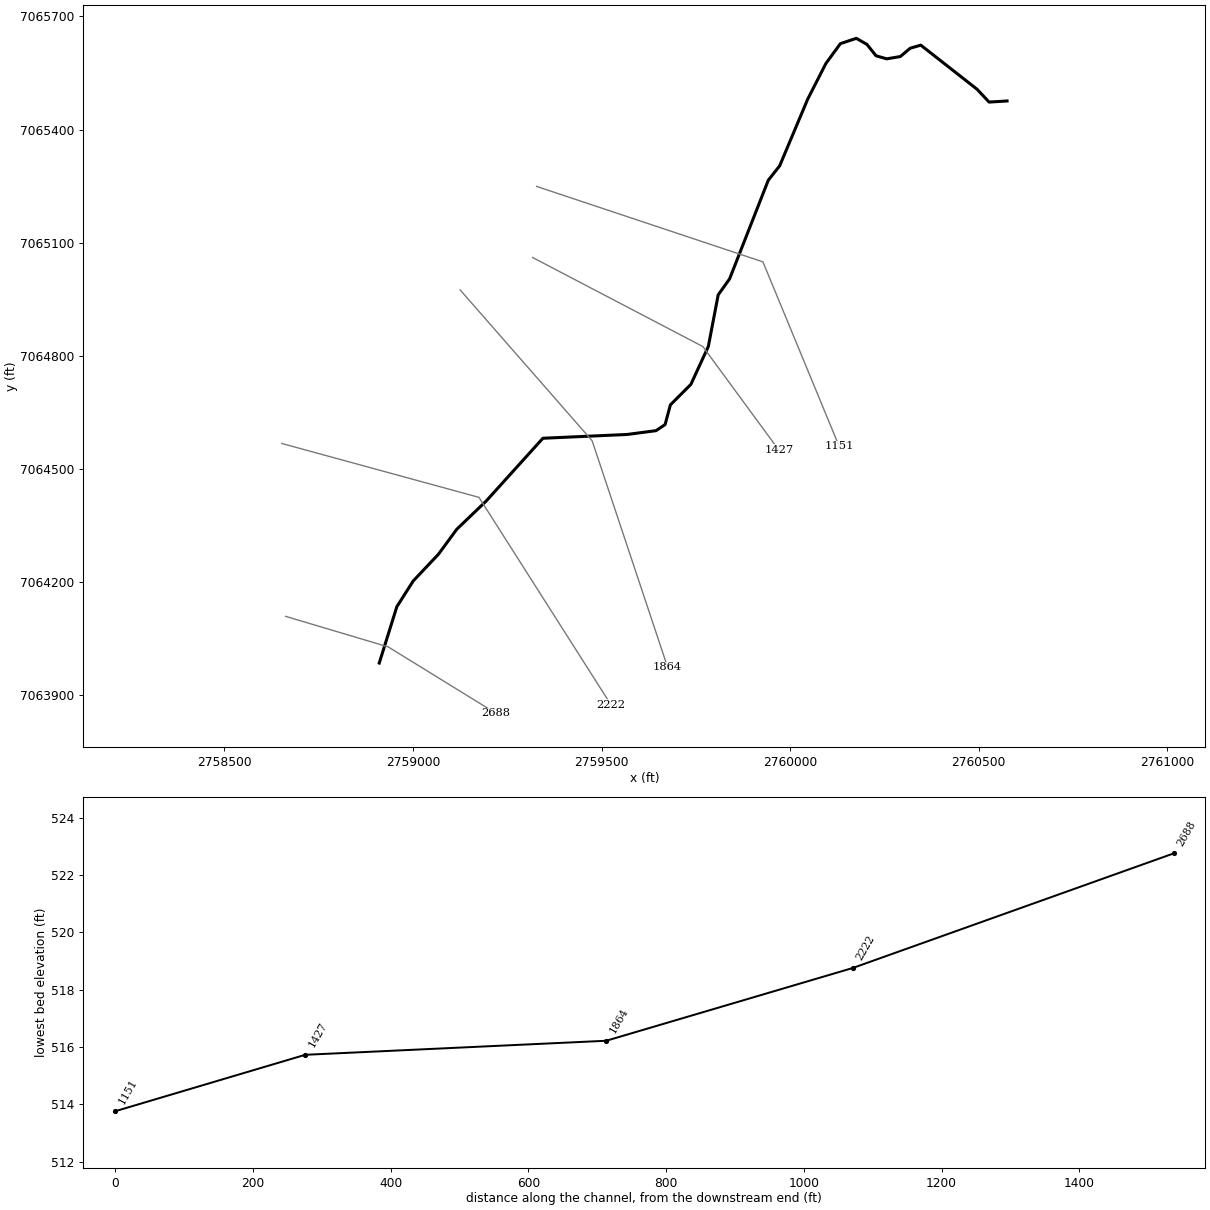
--- UNT 004 in LFCCL Watershed.prj (project) ---

Proj Title=UNT 004 in LFCCL Watershed Base Level Engineering
Current Plan=p01
Default Exp/Contr=0.3,0.1
English Units
Geom File=g01
Flow File=f01
Plan File=p01
BEGIN DESCRIPTION:
UNT 004 in LFCCL Watershed
END DESCRIPTION:

--- UNT 004 in LFCCL Watershed.p01 (plan) ---

Plan Title=Multiple Run
Short Identifier=Multiple
Geom File=g01
Flow File=f01
Subcritical Flow
K Sum by GR= 0
Std Step Tol= 0.01
Critical Tol= 0.01
Num of Std Step Trials= 20
Max Error Tol= 0.3
Flow Tol Ratio= 0.001
Split Flow NTrial= 30
Split Flow Tol= 0.02
Split Flow Ratio= 0.02
Log Output Level= 0
Friction Slope Method= 1
Unsteady Friction Slope Method= 2
Unsteady Bridges Friction Slope Method= 1
Parabolic Critical Depth
Global Vel Dist=  1 , 1 , 1
Global Log Level= 0
CheckData=True
Encroach Param= -1, 0, 0, 0
BEGIN DESCRIPTION:
Multiple Run
END DESCRIPTION:

--- UNT 004 in LFCCL Watershed.f01 (steady flow) ---

Flow Title=Multiple
Number of Profiles=7
Profile Names=10-year,25-year,50-year,1pct_min,100-year,1pct_plu,500-year
River Rch & RM= UNT 004 in LFCCL,Reach-1,2688
     370     479     564     330     659    1315     897
Boundary for River Rch & Prof#=UNT 004 in LFCCL,Reach-1,1
Up Type=0
Dn Type=3
Dn Slope=0.005
Boundary for River Rch & Prof#=UNT 004 in LFCCL,Reach-1,2
Up Type=0
Dn Type=3
Dn Slope=0.005
Boundary for River Rch & Prof#=UNT 004 in LFCCL,Reach-1,3
Up Type=0
Dn Type=3
Dn Slope=0.005
Boundary for River Rch & Prof#=UNT 004 in LFCCL,Reach-1,4
Up Type=0
Dn Type=3
Dn Slope=0.005
Boundary for River Rch & Prof#=UNT 004 in LFCCL,Reach-1,5
Up Type=0
Dn Type=3
Dn Slope=0.005
Boundary for River Rch & Prof#=UNT 004 in LFCCL,Reach-1,6
Up Type=0
Dn Type=3
Dn Slope=0.005
Boundary for River Rch & Prof#=UNT 004 in LFCCL,Reach-1,7
Up Type=0
Dn Type=3
Dn Slope=0.005

--- UNT 004 in LFCCL Watershed.g01 (geometry) ---

Geom Title=Existing Conditions

River Reach=UNT 004 in LFCCL,Reach-1
Reach XY= 30
      2758910.59      7063985.71      2758957.21      7064135.04
      2759000.74      7064203.49      2759067.57      7064274.21
      2759116.20      7064340.54      2759193.55      7064414.67
      2759344.44      7064581.66      2759567.76      7064591.72
      2759644.21      7064601.78      2759668.35      7064617.87
      2759682.43      7064670.18      2759736.75      7064724.50
      2759783.02      7064825.09      2759809.18      7064961.89
      2759839.35      7065004.14      2759941.96      7065265.68
      2759972.14      7065303.91      2760046.57      7065480.95
      2760094.86      7065575.51      2760133.08      7065627.81
      2760175.33      7065641.90      2760203.50      7065625.80
      2760227.64      7065595.62      2760255.80      7065587.58
      2760292.02      7065593.61      2760318.17      7065615.74
      2760346.34      7065623.79      2760495.21      7065507.10
      2760527.40      7065472.90      2760575.03      7065475.87

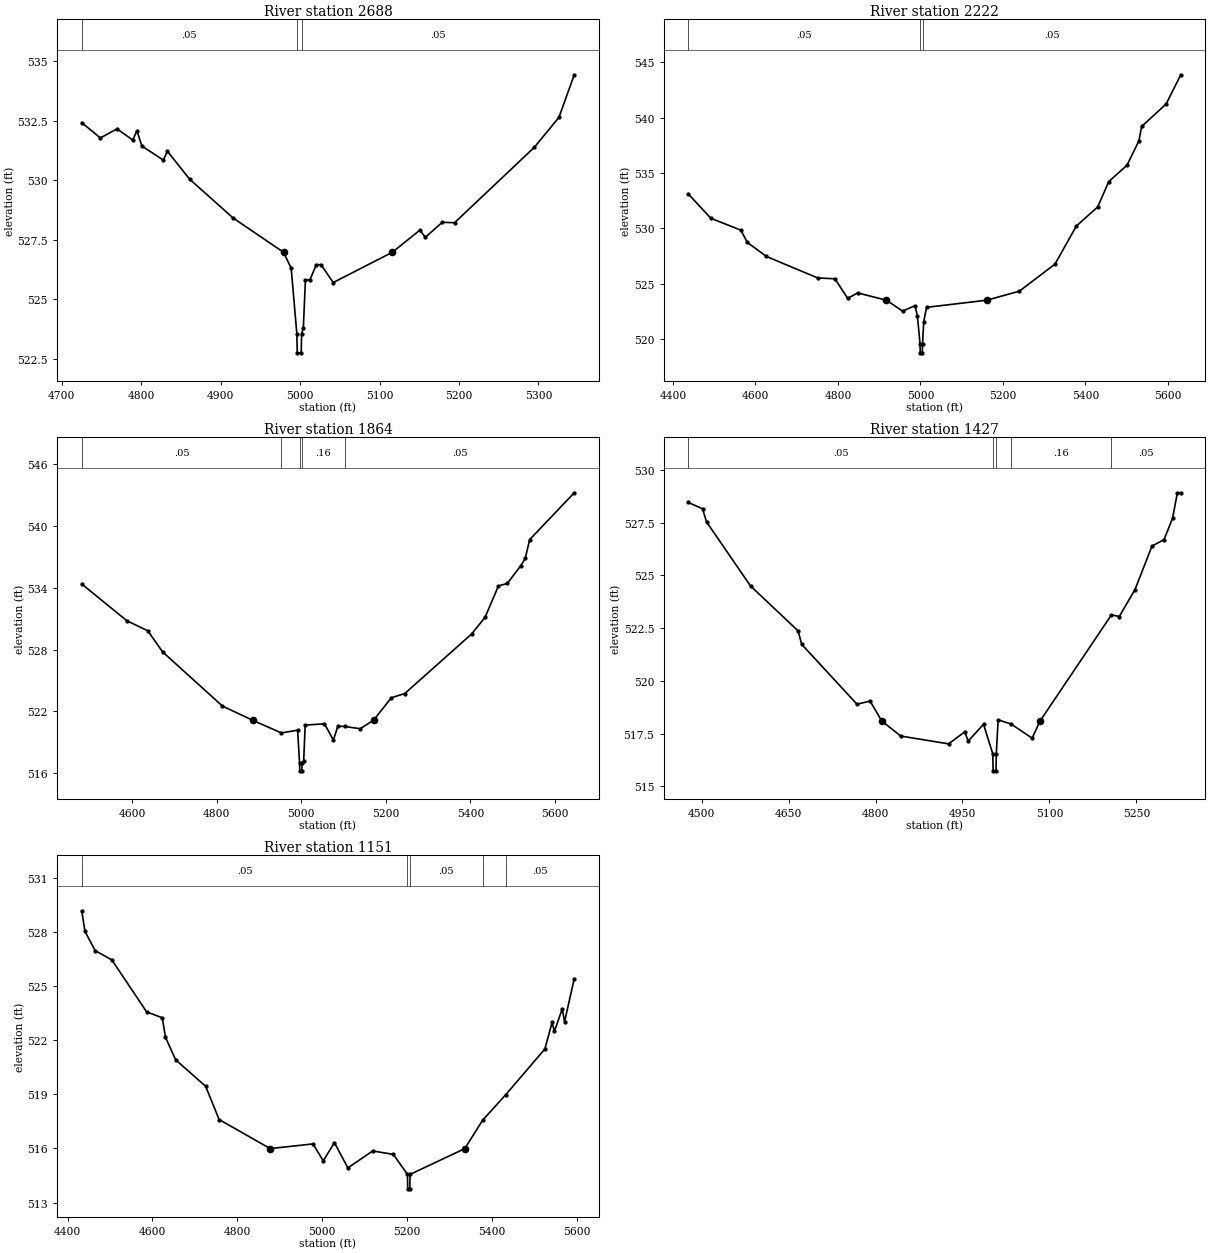
Type RM Length L Ch R = 1,2688,466,466,466
BEGIN DESCRIPTION:
UNT 004 in LFCCL Watershed 4.0
END DESCRIPTION:
XS GIS Cut Line= 3
      2758662.49      7064109.51      2758934.39      7064028.52
      2759220.36      7063852.31
#Sta/Elev= 30
  4725.4  532.42  4748.9  531.78  4769.8  532.16  4789.6  531.69  4794.8  532.08
  4801.1  531.44  4828.0  530.85  4833.2  531.22  4861.1  530.05  4915.8  528.42
  4979.3  526.98  4988.9  526.31  4996.0  523.56  4996.5  522.76  5001.5  522.76
  5002.0  523.56  5004.2  523.81  5006.8  525.82  5012.4  525.82  5020.5  526.46
  5026.4  526.46  5041.8  525.71  5116.1  526.98  5150.8  527.91  5157.7  527.61
  5179.0  528.24  5194.4  528.22  5294.9  531.39  5325.7  532.64  5345.0  534.43
#Mann=3,-1,0
  4725.4    0.05       0  4996.0    0.03       0  5002.0    0.05       0
Bank Sta=4979.3,5116.1
Exp/Cntr=0.3,0.1

Type RM Length L Ch R = 1,2222,358,358,358
BEGIN DESCRIPTION:
UNT 004 in LFCCL Watershed 3.0
END DESCRIPTION:
XS GIS Cut Line= 3
      2758652.13      7064567.86      2759175.00      7064425.00
      2759525.02      7063874.97
#Sta/Elev= 30
  4437.3  533.11  4492.1  530.91  4564.7  529.84  4580.6  528.73  4626.9  527.46
  4751.3  525.52  4792.7  525.45  4823.8  523.68  4848.2  524.17  4917.7  523.51
  4956.9  522.53  4987.0  523.02  4992.9  522.06  4999.2  519.56  4999.7  518.76
  5004.7  518.76  5005.2  519.56  5008.1  521.56  5014.9  522.87  5160.7  523.51
  5240.1  524.33  5326.5  526.78  5378.1  530.21  5429.8  531.93  5456.8  534.23
  5500.9  535.70  5529.7  537.90  5536.4  539.20  5595.7  541.23  5631.3  543.87
#Mann=3,-1,0
  4437.3    0.05       0  4999.2    0.03       0  5005.2    0.05       0
Bank Sta=4917.7,5160.7
Exp/Cntr=0.3,0.1

Type RM Length L Ch R = 1,1864,437,437,437
BEGIN DESCRIPTION:
UNT 004 in LFCCL Watershed 2.0
END DESCRIPTION:
XS GIS Cut Line= 3
      2759125.02      7064974.97      2759475.00      7064575.00
      2759674.99      7063975.02
#Sta/Elev= 30
  4481.4  534.37  4587.7  530.81  4637.5  529.82  4672.6  527.77  4814.0  522.51
  4885.0  521.14  4953.3  519.90  4991.5  520.17  4996.1  517.02  4996.6  516.22
  5001.6  516.22  5002.1  517.02  5005.8  517.15  5009.5  520.66  5055.0  520.79
  5076.1  519.21  5086.7  520.56  5103.0  520.53  5139.4  520.31  5171.1  521.14
  5213.1  523.32  5244.8  523.73  5402.9  529.52  5434.5  531.13  5466.1  534.18
  5487.2  534.43  5518.8  536.14  5529.4  536.85  5539.9  538.68  5645.3  543.23
#Mann=5,-1,0
  4481.4    0.05       0  4953.3    0.16       0  4996.1    0.07       0
  5002.1    0.16       0  5103.0    0.05       0
Bank Sta=4885,5171.1
Exp/Cntr=0.3,0.1

Type RM Length L Ch R = 1,1427,276,276,276
BEGIN DESCRIPTION:
XS3069A
END DESCRIPTION:
XS GIS Cut Line= 3
      2759317.07      7065060.92      2759768.48      7064824.80
      2759969.85      7064550.52
#Sta/Elev= 30
  4476.9  528.46  4501.6  528.16  4508.4  527.54  4584.3  524.50  4666.4  522.37
  4672.6  521.73  4768.0  518.89  4790.6  519.04  4810.6  518.10  4843.5  517.38
  4926.0  517.01  4953.9  517.58  4959.8  517.14  4986.3  517.94  5002.3  516.53
  5002.8  515.73  5007.8  515.73  5008.3  516.53  5011.5  518.15  5033.9  517.95
  5070.1  517.28  5084.0  518.10  5207.0  523.13  5220.5  523.05  5247.6  524.33
  5276.9  526.39  5297.7  526.70  5312.4  527.71  5320.7  528.92  5326.6  528.92
#Mann=5,-1,0
  4476.9    0.05       0  5002.3    0.03       0  5008.3    0.05       0
  5033.9    0.16       0  5207.0    0.05       0
Bank Sta=4810.6,5084
Exp/Cntr=0.3,0.1

Type RM Length L Ch R = 1,1151,0,0,0
BEGIN DESCRIPTION:
UNT 004 in LFCCL Watershed 1.0
END DESCRIPTION:
XS GIS Cut Line= 3
      2759327.77      7065249.31      2759927.78      7065049.31
      2760129.58      7064560.92
#Sta/Elev= 30
  4433.3  529.17  4440.9  528.03  4465.0  526.96  4504.2  526.45  4586.2  523.57
  4623.1  523.24  4630.7  522.16  4654.7  520.91  4725.5  519.44  4757.1  517.60
  4877.7  515.99  4978.5  516.25  5002.6  515.31  5028.9  516.32  5060.6  514.92
  5119.1  515.86  5167.8  515.67  5201.1  514.56  5201.6  513.76  5206.6  513.76
  5207.1  514.56  5336.3  515.99  5378.1  517.56  5432.8  518.98  5524.9  521.51
  5542.0  522.98  5547.4  522.49  5565.9  523.73  5571.3  523.02  5594.2  525.41
#Mann=5,-1,0
  4433.3    0.05       0  5201.1    0.03       0  5207.1    0.05       0
  5378.1    0.16       0  5432.8    0.05       0
Bank Sta=4877.7,5336.3
Exp/Cntr=0.3,0.1

Chan Stop Cuts=-1