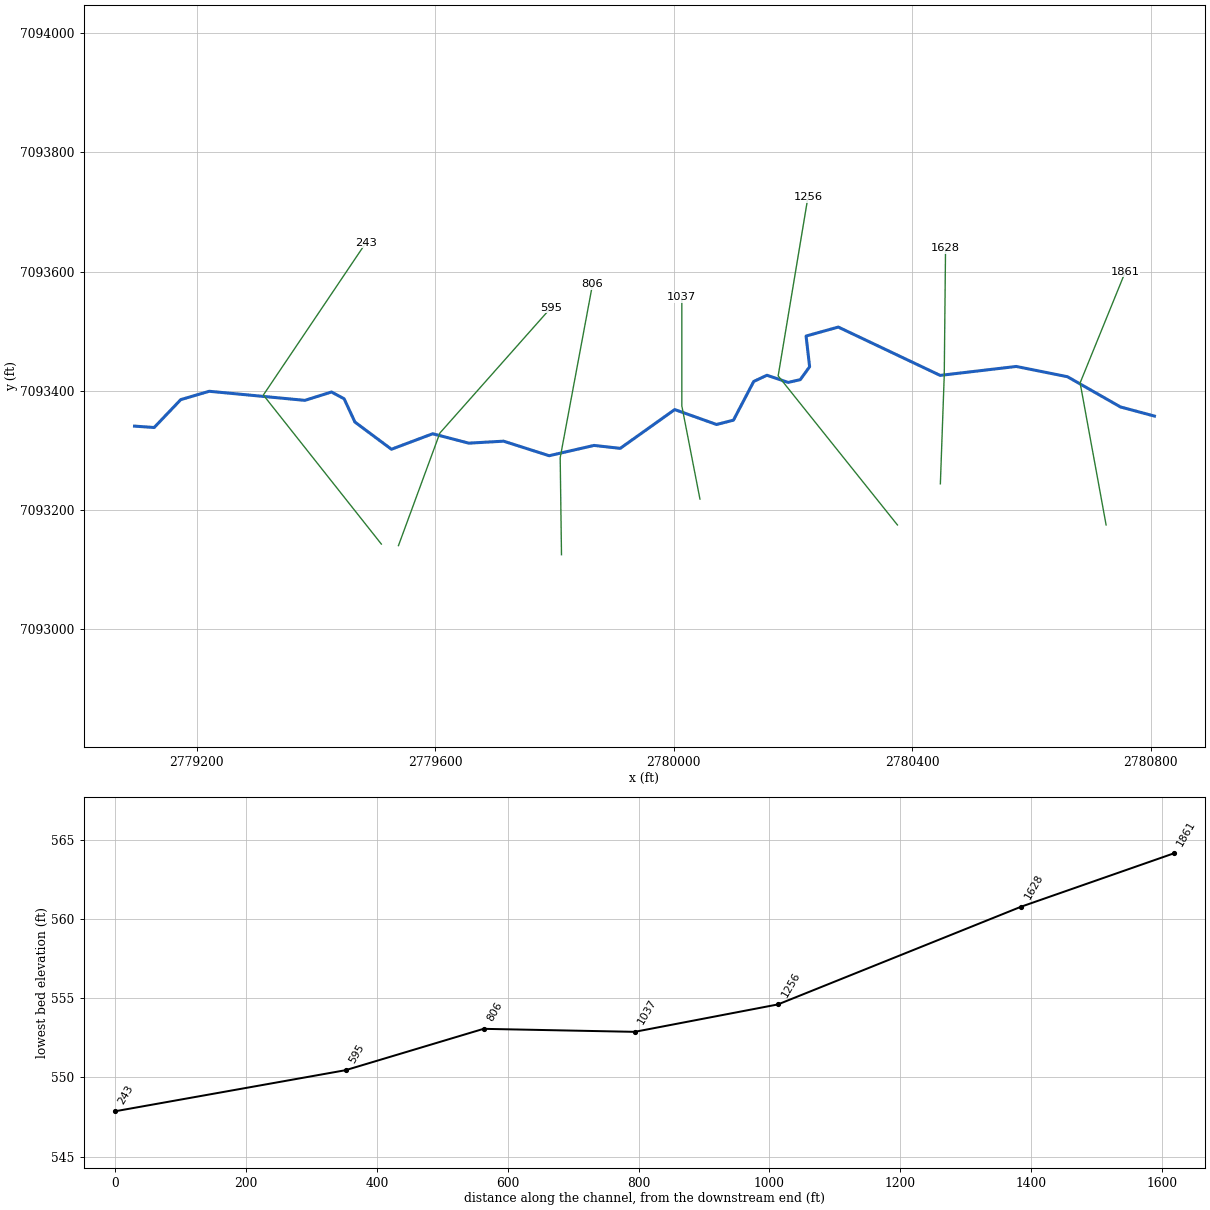
--- UNT 005 in LFCCL Watershed.prj (project) ---

Proj Title=UNT 005 in LFCCL Watershed Base Level Engineering
Current Plan=p01
Default Exp/Contr=0.3,0.1
English Units
Geom File=g01
Flow File=f01
Plan File=p01
BEGIN DESCRIPTION:
UNT 005 in LFCCL Watershed
END DESCRIPTION:

--- UNT 005 in LFCCL Watershed.p01 (plan) ---

Plan Title=Multiple Run
Short Identifier=Multiple
Geom File=g01
Flow File=f01
Subcritical Flow
K Sum by GR= 0
Std Step Tol= 0.01
Critical Tol= 0.01
Num of Std Step Trials= 20
Max Error Tol= 0.3
Flow Tol Ratio= 0.001
Split Flow NTrial= 30
Split Flow Tol= 0.02
Split Flow Ratio= 0.02
Log Output Level= 0
Friction Slope Method= 1
Unsteady Friction Slope Method= 2
Unsteady Bridges Friction Slope Method= 1
Parabolic Critical Depth
Global Vel Dist=  1 , 1 , 1
Global Log Level= 0
CheckData=True
Encroach Param= -1, 0, 0, 0
BEGIN DESCRIPTION:
Multiple Run
END DESCRIPTION:

--- UNT 005 in LFCCL Watershed.f01 (steady flow) ---

Flow Title=Multiple
Number of Profiles=7
Profile Names=10-year,25-year,50-year,1pct_min,100-year,1pct_plu,500-year
River Rch & RM= UNT 005 in LFCCL,Reach-1,1861
     240     301     347     200     399     796     523
Boundary for River Rch & Prof#=UNT 005 in LFCCL,Reach-1,1
Up Type=0
Dn Type=3
Dn Slope=0.005
Boundary for River Rch & Prof#=UNT 005 in LFCCL,Reach-1,2
Up Type=0
Dn Type=3
Dn Slope=0.005
Boundary for River Rch & Prof#=UNT 005 in LFCCL,Reach-1,3
Up Type=0
Dn Type=3
Dn Slope=0.005
Boundary for River Rch & Prof#=UNT 005 in LFCCL,Reach-1,4
Up Type=0
Dn Type=3
Dn Slope=0.005
Boundary for River Rch & Prof#=UNT 005 in LFCCL,Reach-1,5
Up Type=0
Dn Type=3
Dn Slope=0.005
Boundary for River Rch & Prof#=UNT 005 in LFCCL,Reach-1,6
Up Type=0
Dn Type=3
Dn Slope=0.005
Boundary for River Rch & Prof#=UNT 005 in LFCCL,Reach-1,7
Up Type=0
Dn Type=3
Dn Slope=0.005

--- UNT 005 in LFCCL Watershed.g01 (geometry) ---

Geom Title=Existing Conditions

River Reach=UNT 005 in LFCCL,Reach-1
Reach XY= 30
      2780806.03      7093357.59      2780749.09      7093372.87
      2780660.20      7093423.57      2780574.35      7093440.79
      2780446.68      7093425.80      2780275.86      7093506.85
      2780221.82      7093491.81      2780227.77      7093440.29
      2780212.11      7093418.67      2780191.77      7093414.03
      2780156.14      7093426.06      2780134.00      7093415.60
      2780100.04      7093350.71      2780071.69      7093343.45
      2780001.49      7093368.49      2779910.19      7093303.43
      2779866.19      7093308.35      2779790.93      7093291.09
      2779714.51      7093315.48      2779656.14      7093312.16
      2779595.64      7093327.93      2779526.40      7093301.92
      2779465.19      7093347.59      2779447.08      7093386.57
      2779425.94      7093397.96      2779381.27      7093383.93
      2779220.84      7093399.17      2779173.07      7093385.14
      2779128.52      7093338.39      2779095.59      7093340.71

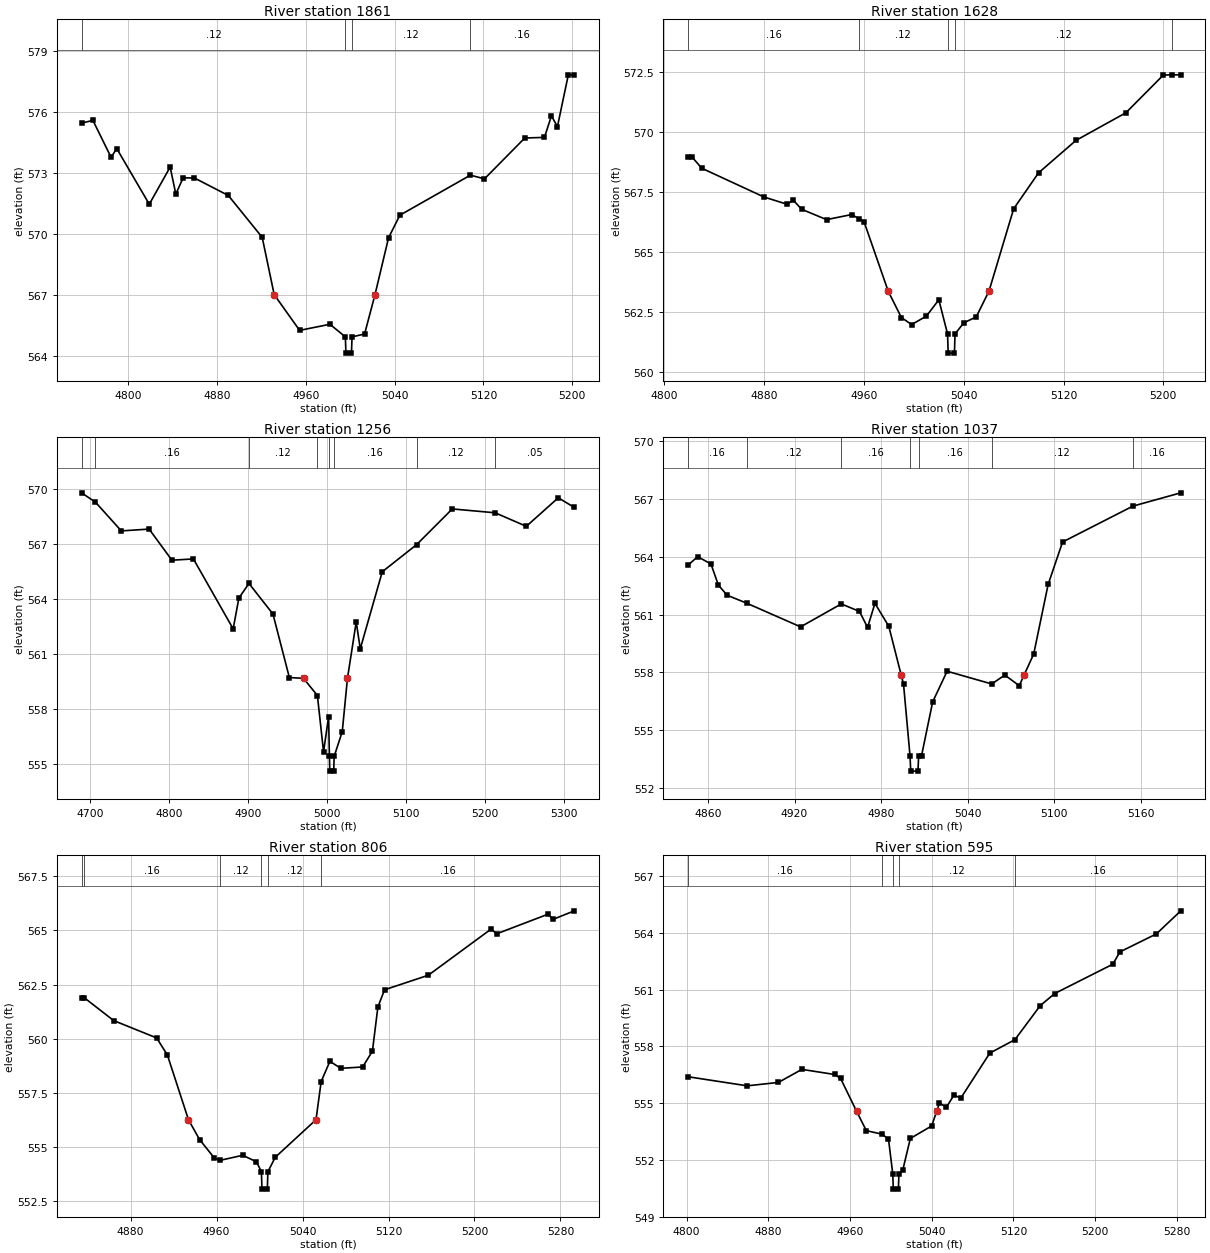
Type RM Length L Ch R = 1,1861,233,233,233
BEGIN DESCRIPTION:
UNT 005 in LFCCL Watershed 3.0
END DESCRIPTION:
XS GIS Cut Line= 3
      2780725.01      7093174.97      2780681.42      7093413.27
      2780757.40      7093599.95
#Sta/Elev= 30
  4758.0  575.46  4768.2  575.60  4784.6  573.78  4789.7  574.21  4819.0  571.47
  4837.8  573.30  4842.9  571.97  4849.5  572.77  4859.7  572.76  4890.2  571.90
  4920.7  569.84  4931.5  567.02  4954.4  565.26  4981.7  565.56  4995.6  564.94
  4996.1  564.14  5001.1  564.14  5001.6  564.94  5012.9  565.08  5022.3  567.02
  5034.5  569.82  5044.7  570.93  5108.2  572.90  5120.9  572.72  5157.2  574.73
  5174.9  574.76  5181.2  575.82  5186.6  575.29  5196.4  577.84  5201.8  577.84
#Mann=4,-1,0
  4758.0    0.12       0  4995.6    0.07       0  5001.6    0.12       0
  5108.2    0.16       0
Bank Sta=4931.5,5022.3
Exp/Cntr=0.3,0.1

Type RM Length L Ch R = 1,1628,372,372,372
BEGIN DESCRIPTION:
XS3070A
END DESCRIPTION:
XS GIS Cut Line= 3
      2780447.05      7093244.01      2780453.56      7093426.29
      2780455.73      7093638.98
#Sta/Elev= 30
  4818.9  568.96  4821.9  568.96  4829.9  568.48  4879.9  567.28  4898.3  566.98
  4903.3  567.15  4910.0  566.77  4930.0  566.34  4950.0  566.55  4956.0  566.38
  4960.0  566.26  4979.4  563.36  4990.0  562.26  4998.2  561.97  5010.0  562.32
  5020.0  563.00  5027.0  561.58  5027.5  560.78  5032.5  560.78  5033.0  561.58
  5040.0  562.04  5050.0  562.29  5060.2  563.36  5080.0  566.79  5100.0  568.29
  5130.0  569.64  5170.0  570.79  5200.0  572.36  5207.0  572.37  5214.0  572.37
#Mann=5,-1,0
  4818.9    0.16       0  4956.0    0.12       0  5027.0    0.07       0
  5033.0    0.12       0  5207.0    0.16       0
Bank Sta=4979.4,5060.2
Exp/Cntr=0.3,0.1

Type RM Length L Ch R = 1,1256,219,219,219
BEGIN DESCRIPTION:
UNT 005 in LFCCL Watershed 2.0
END DESCRIPTION:
XS GIS Cut Line= 3
      2780375.00      7093175.00      2780175.00      7093425.00
      2780225.00      7093725.00
#Sta/Elev= 30
  4688.9  569.81  4706.5  569.30  4739.3  567.73  4774.5  567.83  4803.4  566.13
  4830.6  566.20  4881.0  562.38  4888.2  564.06  4901.0  564.86  4931.4  563.19
  4952.2  559.72  4970.1  559.68  4987.7  558.74  4995.5  555.66  5001.9  557.59
  5002.9  555.41  5003.4  554.61  5008.4  554.61  5008.9  555.41  5019.2  556.77
  5025.8  559.68  5036.9  562.76  5042.0  561.29  5069.9  565.50  5113.4  566.98
  5158.6  568.93  5212.9  568.72  5252.4  567.98  5292.9  569.54  5313.2  569.01
#Mann=8,-1,0
  4688.9    0.05       0  4706.5    0.16       0  4901.0    0.12       0
  4987.7    0.16       0  5002.9    0.07       0  5008.9    0.16       0
  5113.4    0.12       0  5212.9    0.05       0
Bank Sta=4970.1,5025.8
Exp/Cntr=0.3,0.1

Type RM Length L Ch R = 1,1037,231,231,231
BEGIN DESCRIPTION:
XS3073A
END DESCRIPTION:
XS GIS Cut Line= 3
      2780043.83      7093218.41      2780013.45      7093374.64
      2780013.45      7093556.89
#Sta/Elev= 30
  4846.2  563.56  4852.9  564.00  4862.1  563.62  4867.2  562.53  4873.3  562.00
  4886.8  561.59  4924.2  560.36  4952.4  561.55  4965.0  561.16  4970.6  560.33
  4975.7  561.58  4985.3  560.39  4993.8  557.89  4995.5  557.40  5000.0  553.68
  5000.5  552.88  5005.5  552.88  5006.0  553.68  5008.0  553.68  5015.7  556.47
  5025.7  558.06  5056.6  557.40  5065.7  557.86  5075.7  557.31  5079.2  557.89
  5085.7  558.95  5095.7  562.56  5105.7  564.76  5154.4  566.62  5187.6  567.31
#Mann=7,-1,0
  4846.2    0.16       0  4886.8    0.12       0  4952.4    0.16       0
  5000.0    0.07       0  5006.0    0.16       0  5056.6    0.12       0
  5154.4    0.16       0
Bank Sta=4993.8,5079.2
Exp/Cntr=0.3,0.1

Type RM Length L Ch R = 1,806,211,211,211
BEGIN DESCRIPTION:
XS3072A
END DESCRIPTION:
XS GIS Cut Line= 3
      2779811.63      7093125.06      2779809.46      7093287.84
      2779863.71      7093578.63
#Sta/Elev= 30
  4834.3  561.89  4836.9  561.89  4864.2  560.84  4904.2  560.04  4914.2  559.25
  4933.8  556.27  4944.2  555.35  4958.0  554.50  4963.5  554.40  4984.3  554.63
  4997.1  554.33  5001.7  553.87  5002.2  553.07  5007.2  553.07  5007.7  553.87
  5014.6  554.54  5052.5  556.27  5057.3  558.03  5065.4  558.96  5075.6  558.64
  5095.9  558.70  5105.0  559.43  5110.1  561.47  5116.3  562.26  5157.0  562.93
  5215.5  565.06  5220.6  564.84  5268.2  565.74  5273.3  565.51  5292.9  565.90
#Mann=6,-1,0
  4834.3    0.05       0  4836.9    0.16       0  4963.5    0.12       0
  5001.7    0.07       0  5007.7    0.12       0  5057.3    0.16       0
Bank Sta=4933.8,5052.5
Exp/Cntr=0.3,0.1

Type RM Length L Ch R = 1,595,352,352,352
BEGIN DESCRIPTION:
XS3071A
END DESCRIPTION:
XS GIS Cut Line= 3
      2779538.21      7093140.31      2779607.64      7093329.07
      2779794.30      7093539.61
#Sta/Elev= 30
  4801.4  556.40  4859.4  555.92  4889.9  556.10  4912.9  556.79  4944.9  556.52
  4950.8  556.31  4966.4  554.58  4976.0  553.55  4991.1  553.37  4997.7  553.11
  5001.9  551.26  5002.4  550.46  5007.4  550.46  5007.9  551.26  5011.6  551.45
  5019.1  553.14  5040.0  553.80  5044.9  554.58  5047.6  555.02  5054.3  554.78
  5061.8  555.43  5068.5  555.27  5096.9  557.65  5121.5  558.36  5146.3  560.16
  5160.5  560.80  5217.4  562.35  5224.3  563.00  5260.0  563.95  5283.9  565.17
#Mann=5,-1,0
  4801.4    0.16       0  4991.1    0.12       0  5001.9    0.07       0
  5007.9    0.12       0  5121.5    0.16       0
Bank Sta=4966.4,5044.9
Exp/Cntr=0.3,0.1

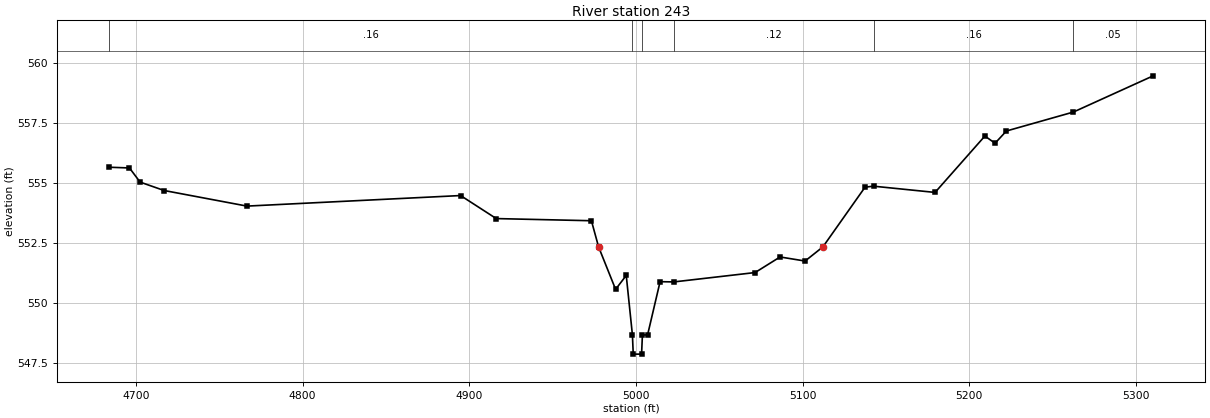
Type RM Length L Ch R = 1,243,0,0,0
BEGIN DESCRIPTION:
UNT 005 in LFCCL Watershed 1.0
END DESCRIPTION:
XS GIS Cut Line= 3
      2779509.53      7093142.90      2779311.63      7093392.87
      2779483.50      7093648.07
#Sta/Elev= 30
  4683.9  555.66  4696.1  555.63  4702.5  555.04  4716.9  554.69  4766.6  554.04
  4894.8  554.48  4916.2  553.52  4973.3  553.43  4977.6  552.34  4987.8  550.57
  4994.2  551.15  4997.9  548.67  4998.4  547.87  5003.4  547.87  5003.9  548.67
  5007.0  548.67  5014.5  550.89  5022.8  550.88  5071.5  551.27  5086.5  551.92
  5101.5  551.75  5112.2  552.34  5137.5  554.83  5142.6  554.87  5179.5  554.61
  5209.4  556.96  5215.5  556.66  5222.3  557.17  5262.5  557.96  5310.4  559.47
#Mann=6,-1,0
  4683.9    0.16       0  4997.9    0.07       0  5003.9    0.16       0
  5022.8    0.12       0  5142.6    0.16       0  5262.5    0.05       0
Bank Sta=4977.6,5112.2
Exp/Cntr=0.3,0.1

Chan Stop Cuts=-1