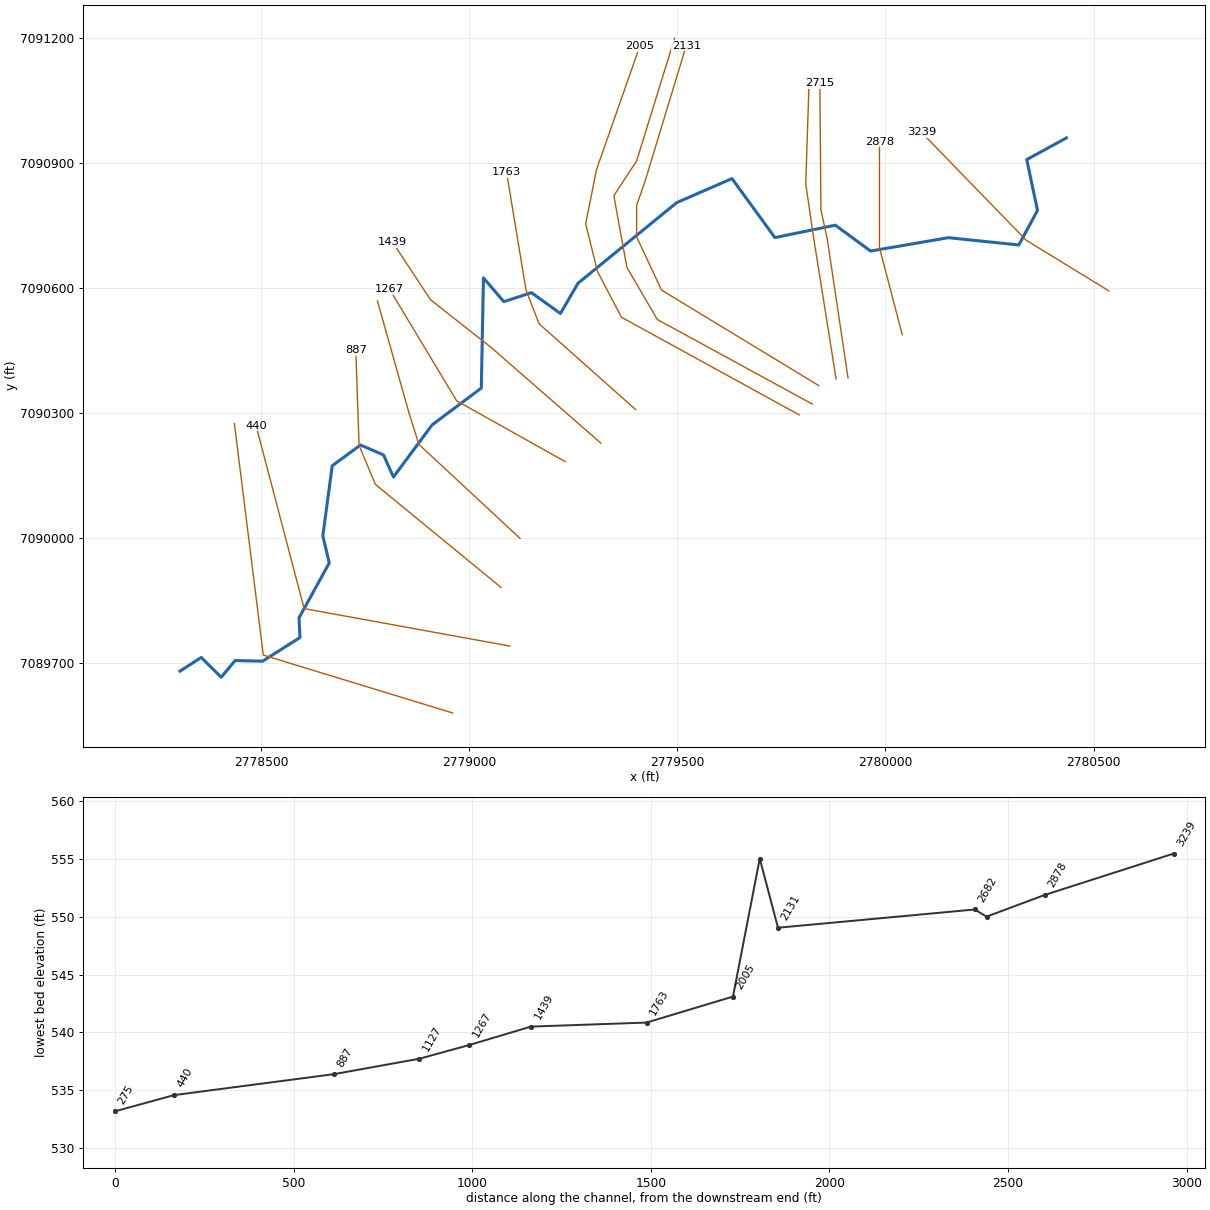
--- UNT 006 in LFCCL Watershed.prj (project) ---

Proj Title=UNT 006 in LFCCL Watershed Base Level Engineering
Current Plan=p01
Default Exp/Contr=0.3,0.1
English Units
Geom File=g01
Flow File=f01
Plan File=p01
BEGIN DESCRIPTION:
UNT 006 in LFCCL Watershed
END DESCRIPTION:

--- UNT 006 in LFCCL Watershed.p01 (plan) ---

Plan Title=Multiple Run
Short Identifier=Multiple
Geom File=g01
Flow File=f01
Subcritical Flow
K Sum by GR= 0
Std Step Tol= 0.01
Critical Tol= 0.01
Num of Std Step Trials= 20
Max Error Tol= 0.3
Flow Tol Ratio= 0.001
Split Flow NTrial= 30
Split Flow Tol= 0.02
Split Flow Ratio= 0.02
Log Output Level= 0
Friction Slope Method= 1
Unsteady Friction Slope Method= 2
Unsteady Bridges Friction Slope Method= 1
Parabolic Critical Depth
Global Vel Dist=  1 , 1 , 1
Global Log Level= 0
CheckData=True
Encroach Param= -1, 0, 0, 0
BEGIN DESCRIPTION:
Multiple Run
END DESCRIPTION:

--- UNT 006 in LFCCL Watershed.f01 (steady flow) ---

Flow Title=Multiple
Number of Profiles=7
Profile Names=10-year,25-year,50-year,1pct_min,100-year,1pct_plu,500-year
River Rch & RM= UNT 006 in LFCCL,Reach-1,3239
     259     325     375     216     431     859     564
Boundary for River Rch & Prof#=UNT 006 in LFCCL,Reach-1,1
Up Type=0
Dn Type=3
Dn Slope=0.005
Boundary for River Rch & Prof#=UNT 006 in LFCCL,Reach-1,2
Up Type=0
Dn Type=3
Dn Slope=0.005
Boundary for River Rch & Prof#=UNT 006 in LFCCL,Reach-1,3
Up Type=0
Dn Type=3
Dn Slope=0.005
Boundary for River Rch & Prof#=UNT 006 in LFCCL,Reach-1,4
Up Type=0
Dn Type=3
Dn Slope=0.005
Boundary for River Rch & Prof#=UNT 006 in LFCCL,Reach-1,5
Up Type=0
Dn Type=3
Dn Slope=0.005
Boundary for River Rch & Prof#=UNT 006 in LFCCL,Reach-1,6
Up Type=0
Dn Type=3
Dn Slope=0.005
Boundary for River Rch & Prof#=UNT 006 in LFCCL,Reach-1,7
Up Type=0
Dn Type=3
Dn Slope=0.005

--- UNT 006 in LFCCL Watershed.g01 (geometry) ---

Geom Title=Existing Conditions

River Reach=UNT 006 in LFCCL,Reach-1
Reach XY= 30
      2780434.92      7090960.30      2780339.44      7090908.20
      2780365.26      7090786.11      2780320.33      7090703.25
      2780151.17      7090720.77      2779964.33      7090688.69
      2779879.58      7090750.73      2779734.53      7090721.02
      2779631.43      7090862.57      2779498.61      7090804.90
      2779261.75      7090611.60      2779219.31      7090538.76
      2779149.85      7090588.75      2779083.32      7090567.25
      2779034.45      7090624.26      2779029.28      7090359.86
      2778911.37      7090271.68      2778818.20      7090146.51
      2778794.37      7090199.44      2778739.12      7090223.25
      2778671.16      7090173.36      2778648.61      7090005.18
      2778664.11      7089940.29      2778591.53      7089808.63
      2778593.78      7089761.31      2778504.02      7089704.50
      2778438.02      7089705.99      2778404.59      7089665.94
      2778356.50      7089713.40      2778305.59      7089680.71

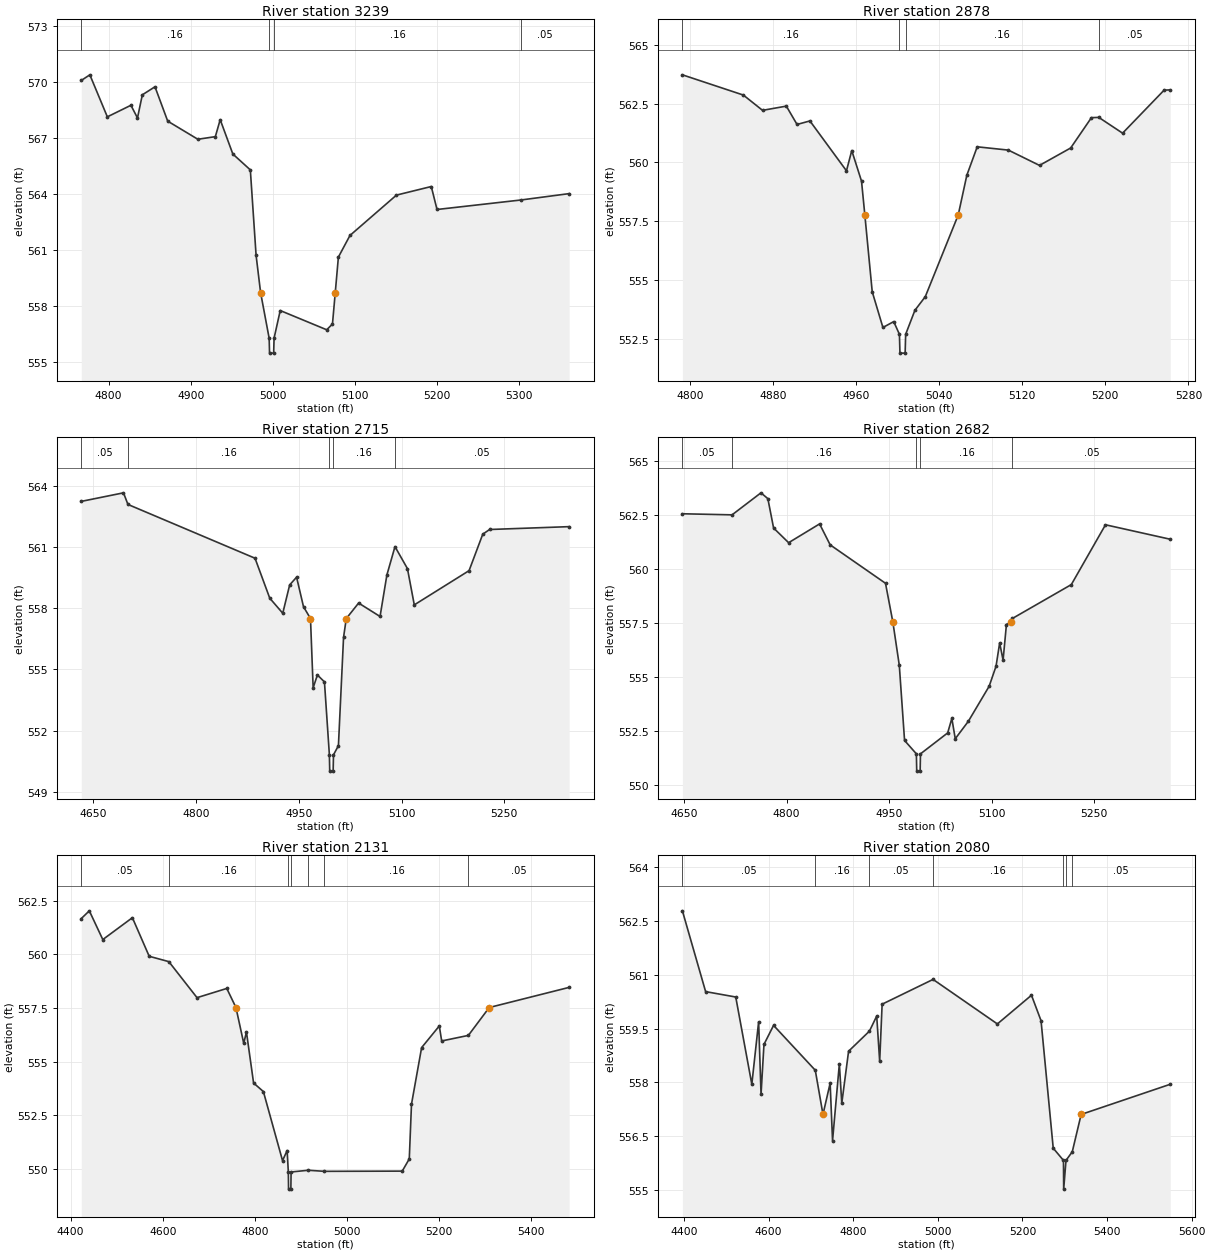
Type RM Length L Ch R = 1,3239,361,361,361
BEGIN DESCRIPTION:
UNT 006 in LFCCL Watershed 2.0
END DESCRIPTION:
XS GIS Cut Line= 3
      2780536.54      7090593.17      2780337.87      7090714.76
      2780086.27      7090973.75
#Sta/Elev= 30
  4766.8  570.07  4777.2  570.37  4798.5  568.12  4827.2  568.74  4835.2  568.06
  4841.1  569.30  4856.5  569.73  4872.0  567.89  4908.7  566.92  4930.0  567.06
  4935.9  567.97  4951.3  566.13  4972.6  565.28  4979.6  560.71  4985.1  558.71
  4995.5  556.27  4996.0  555.47  5001.0  555.47  5001.5  556.27  5009.0  557.75
  5065.6  556.72  5072.6  557.03  5076.0  558.71  5079.8  560.61  5093.9  561.77
  5150.5  563.93  5192.9  564.39  5199.9  563.16  5302.3  563.67  5360.8  564.01
#Mann=4,-1,0
  4766.8    0.16       0  4995.5    0.07       0  5001.5    0.16       0
  5302.3    0.05       0
Bank Sta=4985.1,5076
Exp/Cntr=0.3,0.1

Type RM Length L Ch R = 1,2878,163,163,163
BEGIN DESCRIPTION:
XS3074A
END DESCRIPTION:
XS GIS Cut Line= 3
      2780040.37      7090488.18      2779985.67      7090696.54
      2779985.67      7090950.92
#Sta/Elev= 30
  4792.7  563.72  4851.4  562.86  4869.9  562.21  4892.8  562.39  4903.1  561.61
  4915.5  561.76  4950.7  559.64  4955.8  560.50  4965.2  559.20  4968.4  557.76
  4975.5  554.50  4985.8  552.98  4996.2  553.23  5001.7  552.69  5002.2  551.89
  5007.2  551.89  5007.7  552.69  5016.6  553.71  5026.6  554.29  5058.3  557.76
  5066.6  559.45  5076.6  560.66  5106.6  560.52  5136.6  559.87  5166.6  560.61
  5186.6  561.90  5193.7  561.91  5216.6  561.24  5256.6  563.07  5262.5  563.08
#Mann=4,-1,0
  4792.7    0.16       0  5001.7    0.07       0  5007.7    0.16       0
  5193.7    0.05       0
Bank Sta=4968.4,5058.3
Exp/Cntr=0.3,0.1

Type RM Length L Ch R = 1,2715,33,33,33
BEGIN DESCRIPTION:
XS3076A
END DESCRIPTION:
XS GIS Cut Line= 4
      2779910.14      7090384.08      2779860.67      7090714.77
      2779845.05      7090787.69      2779842.45      7091091.23
#Sta/Elev= 30
  4632.2  563.25  4693.8  563.67  4700.3  563.10  4885.9  560.46  4907.4  558.50
  4926.4  557.76  4936.5  559.15  4946.6  559.53  4956.7  558.08  4966.9  557.50
  4970.8  554.10  4977.0  554.73  4987.3  554.39  4994.5  550.81  4995.0  550.01
  5000.0  550.01  5000.5  550.81  5007.7  551.26  5015.2  556.58  5019.2  557.50
  5037.2  558.26  5068.5  557.60  5078.5  559.64  5090.3  561.03  5108.5  559.95
  5118.5  558.17  5198.5  559.85  5218.5  561.64  5228.5  561.87  5344.7  562.01
#Mann=5,-1,0
  4632.2    0.05       0  4700.3    0.16       0  4994.5    0.07       0
  5000.5    0.16       0  5090.3    0.05       0
Bank Sta=4966.9,5019.2
Exp/Cntr=0.3,0.1

Type RM Length L Ch R = 1,2682,551,551,551
BEGIN DESCRIPTION:
XS3077A
END DESCRIPTION:
XS GIS Cut Line= 4
      2779881.51      7090381.42      2779826.82      7090725.19
      2779808.59      7090850.19      2779816.40      7091089.75
#Sta/Elev= 30
  4647.5  562.55  4720.2  562.50  4762.5  563.52  4772.6  563.25  4781.0  561.89
  4803.0  561.21  4848.3  562.08  4863.8  561.11  4944.8  559.33  4955.6  557.53
  4965.0  555.53  4972.7  552.05  4990.0  551.43  4990.5  550.63  4995.5  550.63
  4996.0  551.43  5035.8  552.40  5041.9  553.07  5046.9  552.13  5066.1  552.94
  5096.5  554.56  5106.6  555.49  5111.9  556.57  5116.9  555.77  5121.8  557.42
  5128.3  557.53  5130.5  557.70  5216.8  559.27  5266.8  562.04  5361.6  561.37
#Mann=5,-1,0
  4647.5    0.05       0  4720.2    0.16       0  4990.0    0.07       0
  4996.0    0.16       0  5130.5    0.05       0
Bank Sta=4955.6,5128.3
Exp/Cntr=0.3,0.1

Type RM Length L Ch R = 1,2131,51,51,51
BEGIN DESCRIPTION:
XS3075A
END DESCRIPTION:
XS GIS Cut Line= 6
      2779839.88      7090365.79      2779462.23      7090594.98
      2779402.34      7090722.58      2779402.34      7090798.10
      2779423.17      7090858.00      2779521.58      7091181.72
#Sta/Elev= 30
  4423.1  561.67  4440.5  562.03  4469.8  560.69  4534.1  561.71  4570.6  559.91
  4613.3  559.66  4674.5  557.98  4739.2  558.41  4759.1  557.52  4776.0  555.85
  4781.9  556.38  4797.4  554.00  4818.7  553.60  4860.3  550.38  4870.3  550.85
  4872.9  549.85  4873.4  549.05  4878.4  549.05  4878.9  549.85  4916.2  549.93
  4951.3  549.88  5120.4  549.89  5135.7  550.46  5140.5  553.01  5162.5  555.65
  5200.9  556.66  5206.1  555.96  5264.1  556.22  5309.4  557.52  5483.1  558.46
#Mann=7,-1,0
  4423.1    0.05       0  4613.3    0.16       0  4872.9    0.07       0
  4878.9    0.16       0  4916.2    0.05       0  4951.3    0.16       0
  5264.1    0.05       0
Bank Sta=4759.1,5309.4
Exp/Cntr=0.3,0.1

Type RM Length L Ch R = 1,2080,75,75,75
BEGIN DESCRIPTION:
XS3078A
END DESCRIPTION:
XS GIS Cut Line= 6
      2779824.23      7090321.53      2779451.82      7090524.66
      2779378.90      7090649.66      2779347.65      7090821.54
      2779402.34      7090904.87      2779493.50      7091199.18
#Sta/Elev= 30
  4396.3  562.78  4451.2  560.53  4522.4  560.38  4560.4  557.95  4576.5  559.69
  4582.2  557.67  4589.1  559.06  4611.8  559.59  4710.4  558.34  4728.6  557.11
  4745.5  557.98  4751.2  556.38  4767.3  558.52  4773.0  557.42  4789.1  558.87
  4838.4  559.43  4855.6  559.85  4862.6  558.59  4868.4  560.18  4988.8  560.87
  5140.8  559.63  5221.4  560.43  5244.0  559.72  5272.8  556.17  5297.0  555.83
  5297.5  555.03  5303.0  555.83  5317.8  556.07  5338.8  557.11  5549.4  557.95
#Mann=7,-1,0
  4396.3    0.05       0  4710.4    0.16       0  4838.4    0.05       0
  4988.8    0.16       0  5297.0    0.07       0  5303.0    0.16       0
  5317.8    0.05       0
Bank Sta=4728.6,5338.8
Exp/Cntr=0.3,0.1

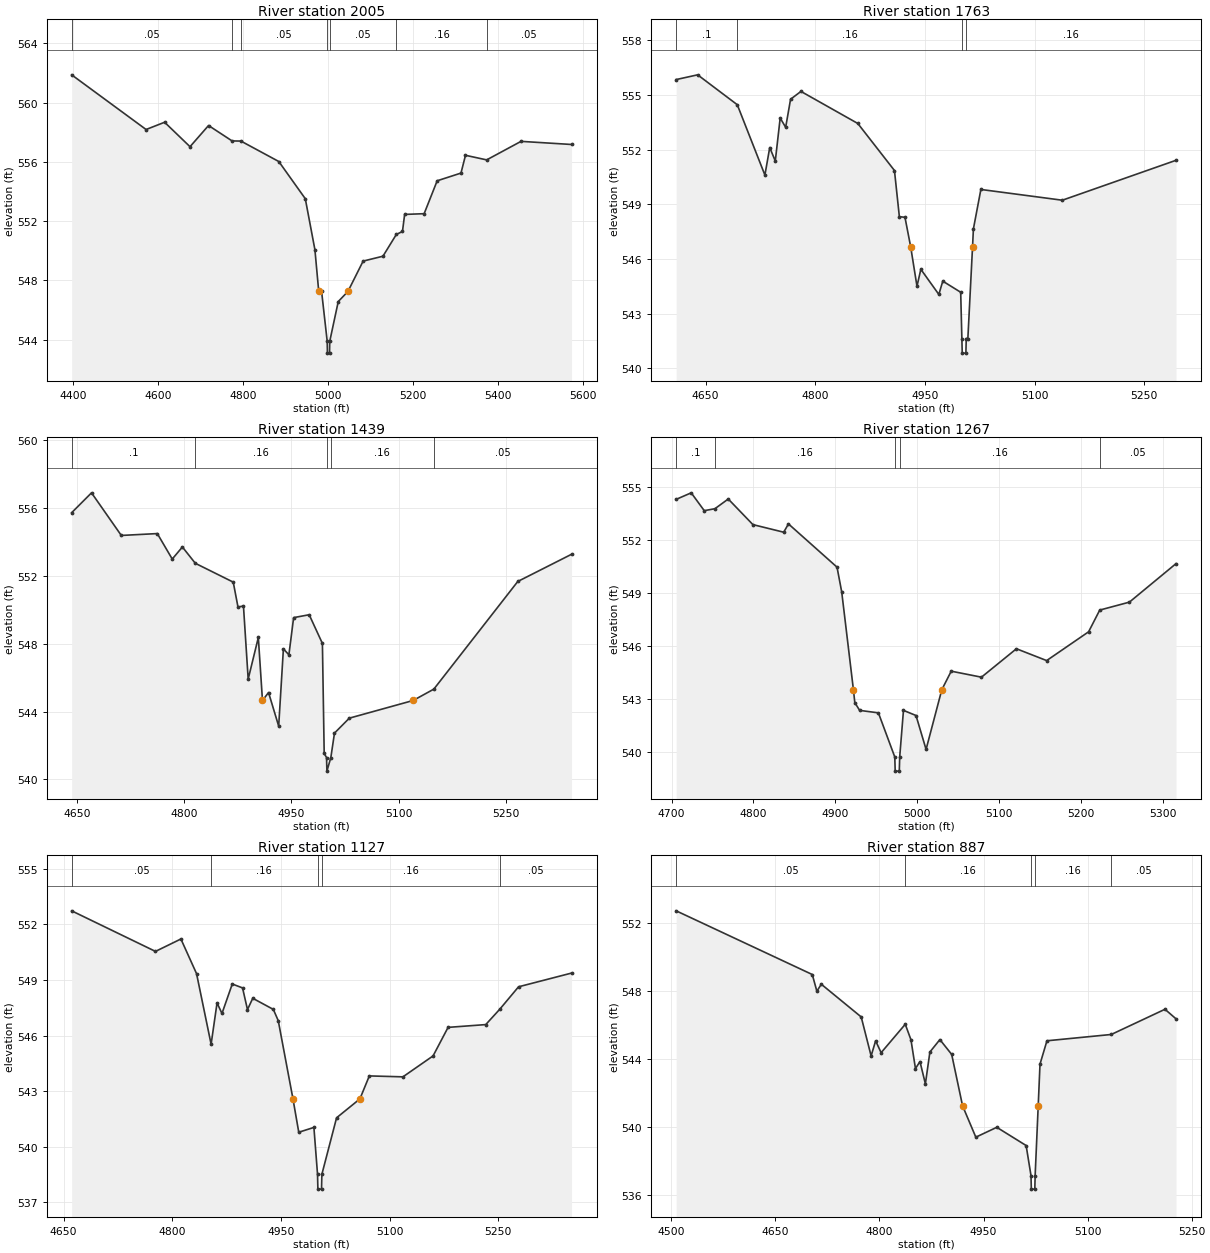
Type RM Length L Ch R = 1,2005,242,242,242
BEGIN DESCRIPTION:
XS3079A
END DESCRIPTION:
XS GIS Cut Line= 6
      2779792.94      7090295.51      2779365.88      7090529.87
      2779308.59      7090639.25      2779279.94      7090753.83
      2779305.98      7090884.04      2779409.91      7091180.22
#Sta/Elev= 30
  4397.2  561.87  4572.2  558.18  4615.8  558.67  4675.5  557.02  4719.1  558.45
  4774.4  557.41  4795.2  557.40  4884.3  556.02  4946.6  553.51  4969.2  550.07
  4978.2  547.25  4984.7  547.31  4998.1  543.89  4998.6  543.09  5003.6  543.09
  5004.1  543.89  5024.1  546.57  5046.8  547.25  5082.6  549.30  5129.2  549.63
  5160.7  551.10  5175.1  551.30  5180.2  552.45  5226.1  552.50  5256.7  554.72
  5312.7  555.24  5323.3  556.44  5373.1  556.13  5453.9  557.38  5572.6  557.17
#Mann=7,-1,0
  4397.2    0.05       0  4774.4    0.16       0  4795.2    0.05       0
  4998.1   0.035       0  5004.1    0.05       0  5160.7    0.16       0
  5373.1    0.05       0
Bank Sta=4978.2,5046.8
Exp/Cntr=0.3,0.1

Type RM Length L Ch R = 1,1763,324,324,324
BEGIN DESCRIPTION:
XS3082A
END DESCRIPTION:
XS GIS Cut Line= 4
      2779399.72      7090308.53      2779167.96      7090514.25
      2779136.71      7090594.98      2779089.91      7090878.38
#Sta/Elev= 30
  4609.8  555.85  4639.2  556.11  4693.4  554.47  4731.2  550.61  4737.8  552.12
  4745.4  551.38  4752.1  553.74  4759.6  553.23  4766.3  554.77  4780.5  555.20
  4858.3  553.44  4908.4  550.86  4915.1  548.33  4922.8  548.29  4930.6  546.67
  4939.2  544.51  4944.5  545.44  4969.1  544.06  4974.5  544.79  4999.0  544.18
  5000.6  541.64  5001.1  540.84  5006.1  540.84  5006.6  541.64  5008.8  541.64
  5015.2  546.67  5016.4  547.66  5026.6  549.82  5138.0  549.23  5293.5  551.42
#Mann=4,-1,0
  4609.8     0.1       0  4693.4    0.16       0  5000.6    0.07       0
  5006.6    0.16       0
Bank Sta=4930.6,5015.2
Exp/Cntr=0.3,0.1

Type RM Length L Ch R = 1,1439,172,172,172
BEGIN DESCRIPTION:
XS3083A
END DESCRIPTION:
XS GIS Cut Line= 4
      2779316.41      7090227.78      2779053.38      7090456.96
      2778907.55      7090571.54      2778816.42      7090709.54
#Sta/Elev= 30
  4642.4  555.71  4670.2  556.88  4711.9  554.37  4762.3  554.48  4783.2  552.98
  4797.4  553.69  4815.5  552.73  4868.6  551.62  4875.2  550.16  4882.9  550.21
  4889.5  545.91  4903.7  548.36  4909.5  544.65  4918.0  545.12  4932.2  543.14
  4938.8  547.69  4946.5  547.34  4953.1  549.53  4974.9  549.70  4993.4  548.01
  4995.9  541.53  4999.2  541.29  4999.7  540.49  5005.2  541.29  5010.3  542.73
  5031.1  543.61  5120.4  544.65  5149.4  545.32  5266.9  551.66  5342.1  553.26
#Mann=5,-1,0
  4642.4     0.1       0  4815.5    0.16       0  4999.2    0.07       0
  5005.2    0.16       0  5149.4    0.05       0
Bank Sta=4909.5,5120.4
Exp/Cntr=0.3,0.1

Type RM Length L Ch R = 1,1267,140,140,140
BEGIN DESCRIPTION:
XS3081A
END DESCRIPTION:
XS GIS Cut Line= 3
      2779230.46      7090183.52      2778970.05      7090329.35
      2778809.28      7090596.43
#Sta/Elev= 30
  4705.6  554.29  4724.0  554.66  4739.9  553.65  4752.9  553.76  4769.2  554.31
  4799.3  552.86  4836.9  552.43  4842.7  552.90  4902.0  550.45  4907.7  549.05
  4922.0  543.51  4923.7  542.78  4929.6  542.34  4952.5  542.20  4972.5  539.70
  4973.0  538.90  4978.0  538.90  4978.5  539.70  4983.1  542.34  4998.4  542.05
  5010.7  540.13  5029.9  543.51  5041.4  544.56  5078.3  544.22  5121.0  545.83
  5157.9  545.16  5209.1  546.79  5222.7  548.02  5258.9  548.47  5315.8  550.65
#Mann=5,-1,0
  4705.6     0.1       0  4752.9    0.16       0  4972.5    0.07       0
  4978.5    0.16       0  5222.7    0.05       0
Bank Sta=4922,5029.9
Exp/Cntr=0.3,0.1

Type RM Length L Ch R = 1,1127,240,240,240
BEGIN DESCRIPTION:
XS3085A
END DESCRIPTION:
XS GIS Cut Line= 4
      2779122.37      7089999.07      2778879.33      7090224.75
      2778855.46      7090300.71      2778779.75      7090568.95
#Sta/Elev= 30
  4661.1  552.73  4776.8  550.54  4811.9  551.21  4833.5  549.34  4853.6  545.53
  4861.8  547.76  4868.6  547.19  4882.8  548.78  4897.0  548.57  4903.8  547.40
  4911.1  548.01  4939.5  547.41  4946.3  546.80  4966.6  542.58  4974.6  540.78
  4995.5  541.04  5000.5  538.51  5001.0  537.71  5006.0  537.71  5006.5  538.51
  5026.8  541.56  5059.0  542.58  5072.0  543.82  5118.4  543.77  5160.0  544.90
  5180.7  546.44  5232.7  546.59  5252.3  547.43  5278.0  548.63  5351.1  549.37
#Mann=5,-1,0
  4661.1    0.05       0  4853.6    0.16       0  5000.5    0.07       0
  5006.5    0.16       0  5252.3    0.05       0
Bank Sta=4966.6,5059
Exp/Cntr=0.3,0.1

Type RM Length L Ch R = 1,887,447,447,447
BEGIN DESCRIPTION:
XS3080A
END DESCRIPTION:
XS GIS Cut Line= 4
      2779076.80      7089881.45      2778774.73      7090128.83
      2778735.67      7090222.58      2778727.89      7090450.85
#Sta/Elev= 30
  4507.0  552.71  4703.2  548.97  4709.8  547.99  4716.2  548.40  4773.7  546.48
  4788.0  544.19  4794.5  545.08  4802.4  544.38  4837.2  546.05  4845.4  545.14
  4851.9  543.45  4858.4  543.86  4866.2  542.55  4872.7  544.42  4887.1  545.15
  4904.1  544.28  4919.8  541.26  4938.9  539.42  4969.1  540.00  5011.4  538.93
  5018.4  537.17  5018.9  536.37  5023.9  536.37  5024.4  537.17  5028.8  541.26
  5031.4  543.71  5041.4  545.08  5134.1  545.45  5211.5  546.93  5227.4  546.37
#Mann=5,-1,0
  4507.0    0.05       0  4837.2    0.16       0  5018.4    0.07       0
  5024.4    0.16       0  5134.1    0.05       0
Bank Sta=4919.8,5028.8
Exp/Cntr=0.3,0.1

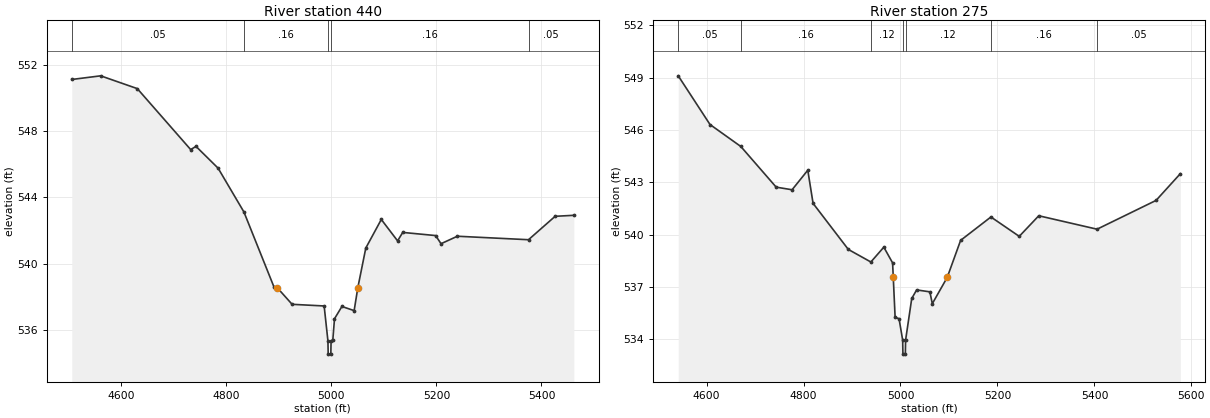
Type RM Length L Ch R = 1,440,165,165,165
BEGIN DESCRIPTION:
UNT 006 in LFCCL Watershed 1.0
END DESCRIPTION:
XS GIS Cut Line= 3
      2779097.64      7089740.81      2778603.74      7089830.67
      2778488.28      7090269.43
#Sta/Elev= 30
  4505.9  551.10  4560.9  551.32  4630.6  550.55  4732.2  546.88  4742.4  547.07
  4784.4  545.76  4833.6  543.12  4891.1  538.58  4897.0  538.56  4925.3  537.56
  4986.3  537.46  4993.5  535.36  4994.0  534.56  4999.0  534.56  4999.5  535.36
  5002.8  535.41  5006.0  536.69  5020.1  537.43  5043.4  537.18  5050.4  538.56
  5065.6  540.95  5095.1  542.67  5126.1  541.38  5135.9  541.89  5198.5  541.70
  5208.8  541.21  5239.9  541.66  5375.3  541.45  5426.0  542.86  5461.6  542.92
#Mann=5,-1,0
  4505.9    0.05       0  4833.6    0.16       0  4993.5    0.07       0
  4999.5    0.16       0  5375.3    0.05       0
Bank Sta=4897,5050.4
Exp/Cntr=0.3,0.1

Type RM Length L Ch R = 1,275,0,0,0
BEGIN DESCRIPTION:
XS3084A
END DESCRIPTION:
XS GIS Cut Line= 3
      2778960.54      7089580.21      2778505.64      7089719.11
      2778436.19      7090274.65
#Sta/Elev= 30
  4541.6  549.11  4607.1  546.32  4670.7  545.06  4743.6  542.73  4776.4  542.58
  4808.8  543.70  4819.7  541.80  4892.4  539.16  4938.9  538.44  4965.6  539.29
  4983.7  538.39  4985.1  537.56  4988.9  535.27  4997.0  535.19  5004.5  533.96
  5005.0  533.16  5010.0  533.16  5010.5  533.96  5023.2  536.35  5033.3  536.84
  5060.6  536.73  5065.6  536.05  5096.4  537.56  5124.0  539.68  5186.5  541.02
  5244.9  539.91  5285.2  541.09  5405.4  540.32  5527.1  541.97  5577.1  543.50
#Mann=7,-1,0
  4541.6    0.05       0  4670.7    0.16       0  4938.9    0.12       0
  5004.5    0.07       0  5010.5    0.12       0  5186.5    0.16       0
  5405.4    0.05       0
Bank Sta=4985.1,5096.4
Exp/Cntr=0.3,0.1

Chan Stop Cuts=-1