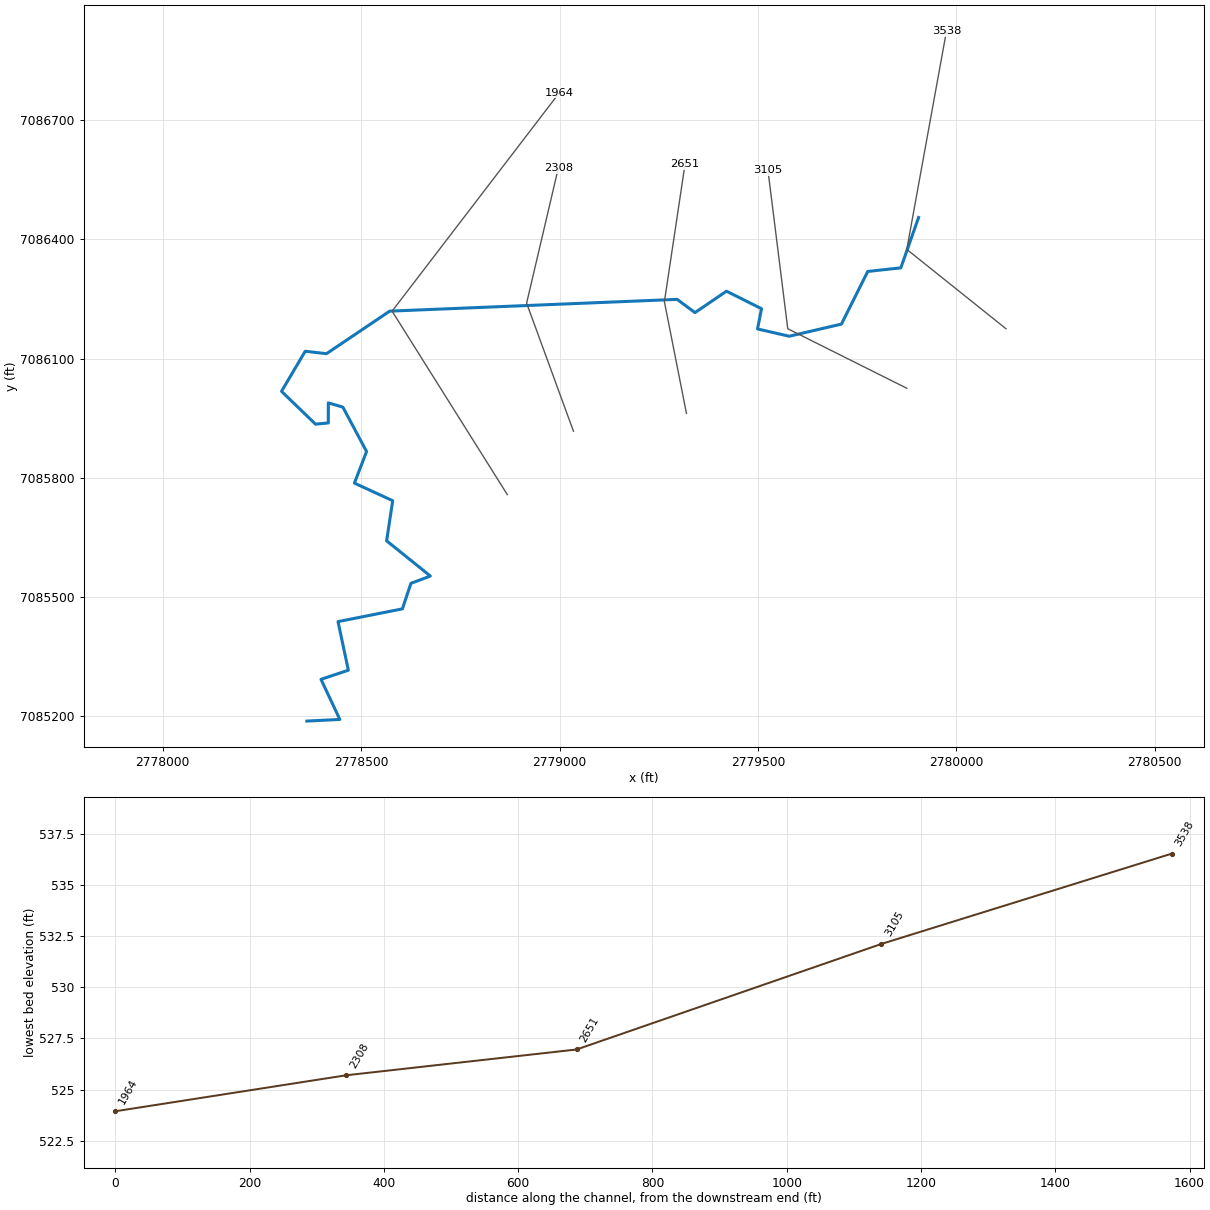
--- UNT 007 in LFCCL Watershed.prj (project) ---

Proj Title=UNT 007 in LFCCL Watershed Base Level Engineering
Current Plan=p01
Default Exp/Contr=0.3,0.1
English Units
Geom File=g01
Flow File=f01
Plan File=p01
BEGIN DESCRIPTION:
UNT 007 in LFCCL Watershed
END DESCRIPTION:

--- UNT 007 in LFCCL Watershed.p01 (plan) ---

Plan Title=Multiple Run
Short Identifier=Multiple
Geom File=g01
Flow File=f01
Subcritical Flow
K Sum by GR= 0
Std Step Tol= 0.01
Critical Tol= 0.01
Num of Std Step Trials= 20
Max Error Tol= 0.3
Flow Tol Ratio= 0.001
Split Flow NTrial= 30
Split Flow Tol= 0.02
Split Flow Ratio= 0.02
Log Output Level= 0
Friction Slope Method= 1
Unsteady Friction Slope Method= 2
Unsteady Bridges Friction Slope Method= 1
Parabolic Critical Depth
Global Vel Dist=  1 , 1 , 1
Global Log Level= 0
CheckData=True
Encroach Param= -1, 0, 0, 0
BEGIN DESCRIPTION:
Multiple Run
END DESCRIPTION:

--- UNT 007 in LFCCL Watershed.f01 (steady flow) ---

Flow Title=Multiple
Number of Profiles=7
Profile Names=10-year,25-year,50-year,1pct_min,100-year,1pct_plu,500-year
River Rch & RM= UNT 007 in LFCCL,Reach-1,3538
     398     516     609     357     712    1420     970
Boundary for River Rch & Prof#=UNT 007 in LFCCL,Reach-1,1
Up Type=0
Dn Type=3
Dn Slope=0.005
Boundary for River Rch & Prof#=UNT 007 in LFCCL,Reach-1,2
Up Type=0
Dn Type=3
Dn Slope=0.005
Boundary for River Rch & Prof#=UNT 007 in LFCCL,Reach-1,3
Up Type=0
Dn Type=3
Dn Slope=0.005
Boundary for River Rch & Prof#=UNT 007 in LFCCL,Reach-1,4
Up Type=0
Dn Type=3
Dn Slope=0.005
Boundary for River Rch & Prof#=UNT 007 in LFCCL,Reach-1,5
Up Type=0
Dn Type=3
Dn Slope=0.005
Boundary for River Rch & Prof#=UNT 007 in LFCCL,Reach-1,6
Up Type=0
Dn Type=3
Dn Slope=0.005
Boundary for River Rch & Prof#=UNT 007 in LFCCL,Reach-1,7
Up Type=0
Dn Type=3
Dn Slope=0.005

--- UNT 007 in LFCCL Watershed.g01 (geometry) ---

Geom Title=Existing Conditions

River Reach=UNT 007 in LFCCL,Reach-1
Reach XY= 30
      2779904.70      7086455.36      2779859.87      7086328.41
      2779776.65      7086319.44      2779710.23      7086186.71
      2779578.68      7086156.12      2779498.77      7086174.51
      2779508.87      7086225.48      2779420.57      7086269.63
      2779341.21      7086215.66      2779296.20      7086249.03
      2778571.74      7086219.33      2778412.50      7086112.15
      2778358.91      7086118.27      2778299.19      7086017.22
      2778384.94      7085934.53      2778417.09      7085937.60
      2778417.09      7085988.12      2778453.84      7085977.41
      2778513.55      7085865.63      2778482.93      7085786.01
      2778579.39      7085741.61      2778564.08      7085640.55
      2778674.32      7085551.75      2778625.33      7085533.37
      2778603.89      7085469.07      2778441.59      7085436.91
      2778467.62      7085314.42      2778398.72      7085291.45
      2778446.18      7085190.40      2778363.07      7085186.27

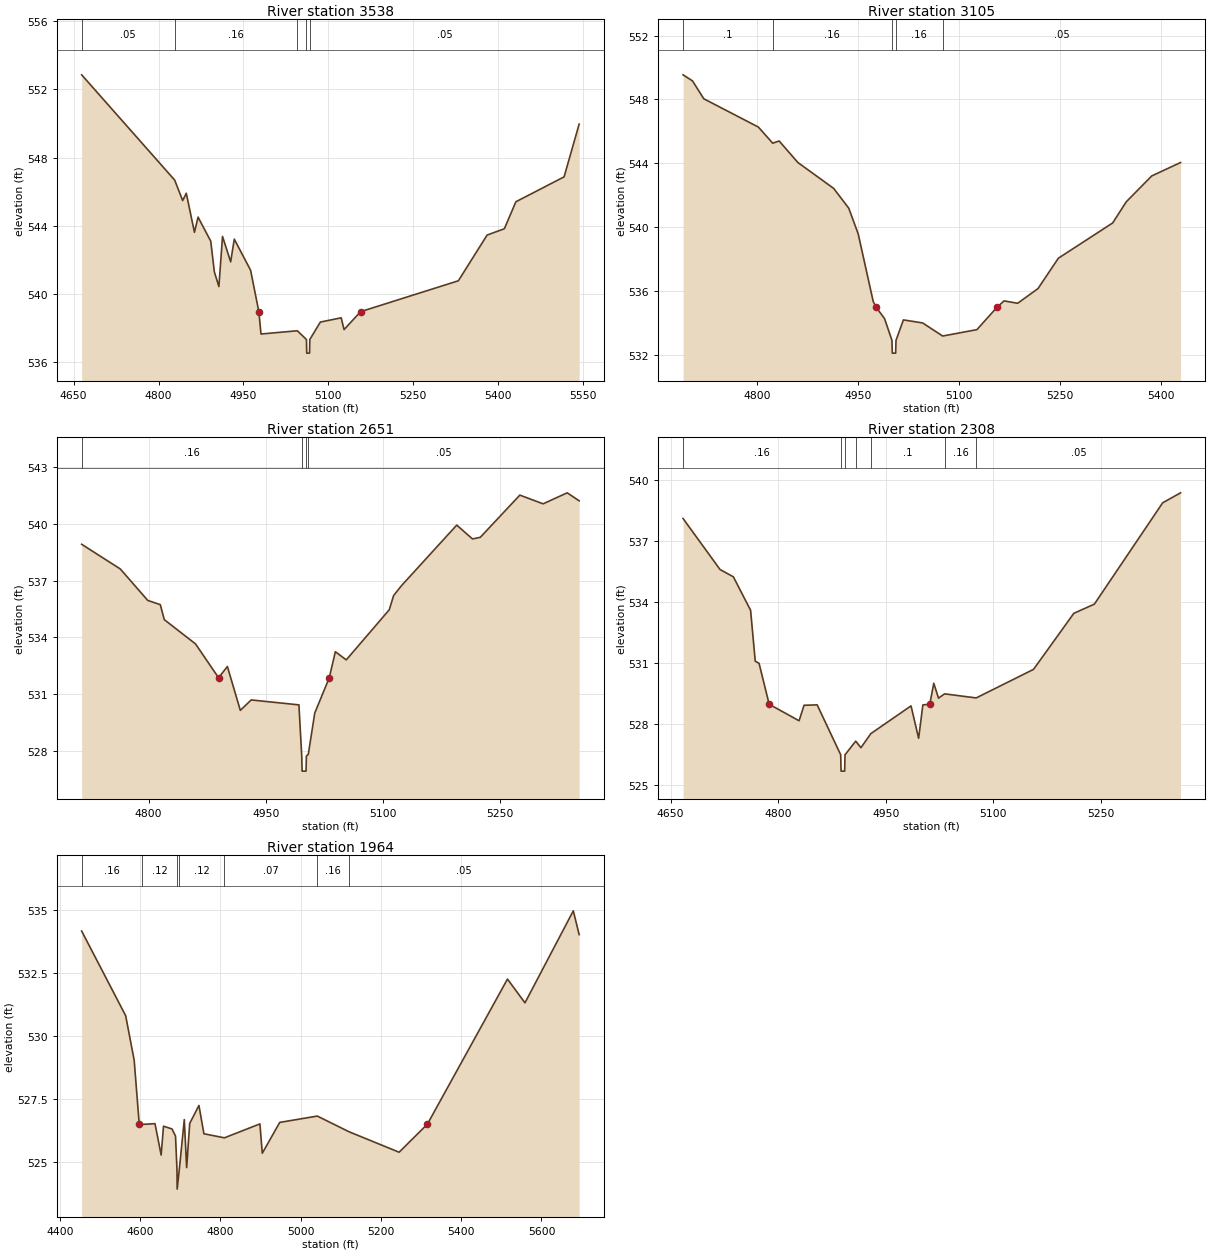
Type RM Length L Ch R = 1,3538,433,433,433
BEGIN DESCRIPTION:
UNT 007 in LFCCL Watershed 3.0
END DESCRIPTION:
XS GIS Cut Line= 3
      2780124.98      7086175.01      2779875.00      7086375.00
      2779974.99      7086924.95
#Sta/Elev= 30
  4664.1  552.85  4828.5  546.68  4842.6  545.48  4849.0  545.91  4863.4  543.62
  4869.8  544.51  4892.2  543.10  4898.6  541.30  4906.6  540.44  4913.0  543.38
  4927.4  541.89  4933.8  543.22  4962.6  541.40  4977.2  538.97  4981.0  537.66
  5045.2  537.85  5061.3  537.34  5061.8  536.54  5066.8  536.54  5067.3  537.34
  5085.9  538.36  5122.7  538.61  5127.8  537.92  5157.0  538.97  5329.8  540.78
  5380.6  543.46  5411.1  543.83  5431.4  545.41  5516.6  546.87  5543.2  549.96
#Mann=5,-1,0
  4664.1    0.05       0  4828.5    0.16       0  5045.2    0.05       0
  5061.3    0.07       0  5067.3    0.05       0
Bank Sta=4977.2,5157
Exp/Cntr=0.3,0.1

Type RM Length L Ch R = 1,3105,454,454,454
BEGIN DESCRIPTION:
UNT 007 in LFCCL Watershed 2.0
END DESCRIPTION:
XS GIS Cut Line= 3
      2779875.02      7086024.99      2779575.00      7086175.00
      2779525.01      7086574.95
#Sta/Elev= 30
  4690.6  549.54  4704.6  549.16  4721.4  548.04  4802.4  546.27  4823.7  545.26
  4833.2  545.40  4861.1  544.05  4914.2  542.43  4936.6  541.19  4950.6  539.58
  4972.9  535.35  4977.4  534.98  4989.7  534.28  5000.7  532.92  5001.2  532.12
  5006.2  532.12  5006.7  532.92  5017.7  534.20  5046.2  534.01  5076.0  533.19
  5126.8  533.59  5156.4  534.98  5167.1  535.39  5187.3  535.24  5217.5  536.16
  5247.7  538.06  5328.4  540.27  5348.5  541.59  5386.3  543.21  5429.1  544.05
#Mann=5,-1,0
  4690.6     0.1       0  4823.7    0.16       0  5000.7    0.07       0
  5006.7    0.16       0  5076.0    0.05       0
Bank Sta=4977.4,5156.4
Exp/Cntr=0.3,0.1

Type RM Length L Ch R = 1,2651,343,343,343
BEGIN DESCRIPTION:
XS3087A
END DESCRIPTION:
XS GIS Cut Line= 3
      2779319.67      7085961.79      2779264.12      7086243.03
      2779316.19      7086590.17
#Sta/Elev= 30
  4714.1  538.91  4763.6  537.61  4798.9  535.95  4814.9  535.73  4820.0  534.94
  4860.1  533.66  4889.6  531.88  4900.9  532.47  4917.5  530.16  4931.4  530.71
  4992.6  530.45  4996.2  527.76  4996.7  526.96  5001.7  526.96  5002.2  527.76
  5004.6  527.84  5012.9  530.02  5031.5  531.88  5039.3  533.25  5053.3  532.82
  5108.4  535.46  5114.0  536.21  5124.1  536.73  5194.9  539.92  5215.1  539.19
  5225.2  539.28  5275.8  541.50  5305.6  541.04  5336.5  541.62  5351.8  541.20
#Mann=4,-1,0
  4714.1    0.16       0  4996.2    0.07       0  5002.2    0.16       0
  5004.6    0.05       0
Bank Sta=4889.6,5031.5
Exp/Cntr=0.3,0.1

Type RM Length L Ch R = 1,2308,344,344,344
BEGIN DESCRIPTION:
XS3086A
END DESCRIPTION:
XS GIS Cut Line= 3
      2779034.95      7085916.64      2778916.89      7086239.56
      2778996.75      7086579.80
#Sta/Elev= 30
  4667.5  538.09  4719.0  535.59  4737.6  535.23  4761.6  533.59  4768.1  531.09
  4773.4  530.99  4787.5  528.98  4829.2  528.17  4836.1  528.93  4854.4  528.95
  4887.2  526.50  4887.7  525.70  4892.7  525.70  4893.2  526.50  4908.1  527.17
  4915.4  526.85  4929.2  527.54  4985.2  528.90  4995.8  527.31  5001.7  528.95
  5011.3  528.98  5016.9  530.01  5023.5  529.28  5032.0  529.49  5076.0  529.29
  5155.9  530.69  5212.1  533.44  5240.7  533.89  5335.9  538.86  5360.8  539.35
#Mann=7,-1,0
  4667.5    0.16       0  4887.2    0.07       0  4893.2    0.16       0
  4908.1    0.07       0  4929.2     0.1       0  5032.0    0.16       0
  5076.0    0.05       0
Bank Sta=4787.5,5011.3
Exp/Cntr=0.3,0.1

Type RM Length L Ch R = 1,1964,0,0,0
BEGIN DESCRIPTION:
UNT 007 in LFCCL Watershed 1.0
END DESCRIPTION:
XS GIS Cut Line= 3
      2778868.27      7085756.94      2778577.89      7086219.33
      2778999.79      7086770.23
#Sta/Elev= 30
  4454.0  534.15  4563.7  530.80  4584.9  529.04  4597.5  526.51  4604.4  526.50
  4636.8  526.53  4652.1  525.29  4658.0  526.43  4679.2  526.32  4687.9  526.04
  4691.5  524.74  4692.0  523.94  4697.5  524.74  4709.8  526.69  4715.7  524.79
  4723.3  526.54  4746.3  527.25  4758.7  526.13  4809.9  525.97  4898.3  526.52
  4904.2  525.36  4947.7  526.58  5041.3  526.83  5120.3  526.21  5245.2  525.40
  5315.7  526.51  5515.3  532.25  5558.9  531.31  5679.4  534.95  5693.9  534.01
#Mann=7,-1,0
  4454.0    0.16       0  4604.4    0.12       0  4691.5    0.07       0
  4697.5    0.12       0  4809.9    0.07       0  5041.3    0.16       0
  5120.3    0.05       0
Bank Sta=4597.5,5315.7
Exp/Cntr=0.3,0.1

Chan Stop Cuts=-1