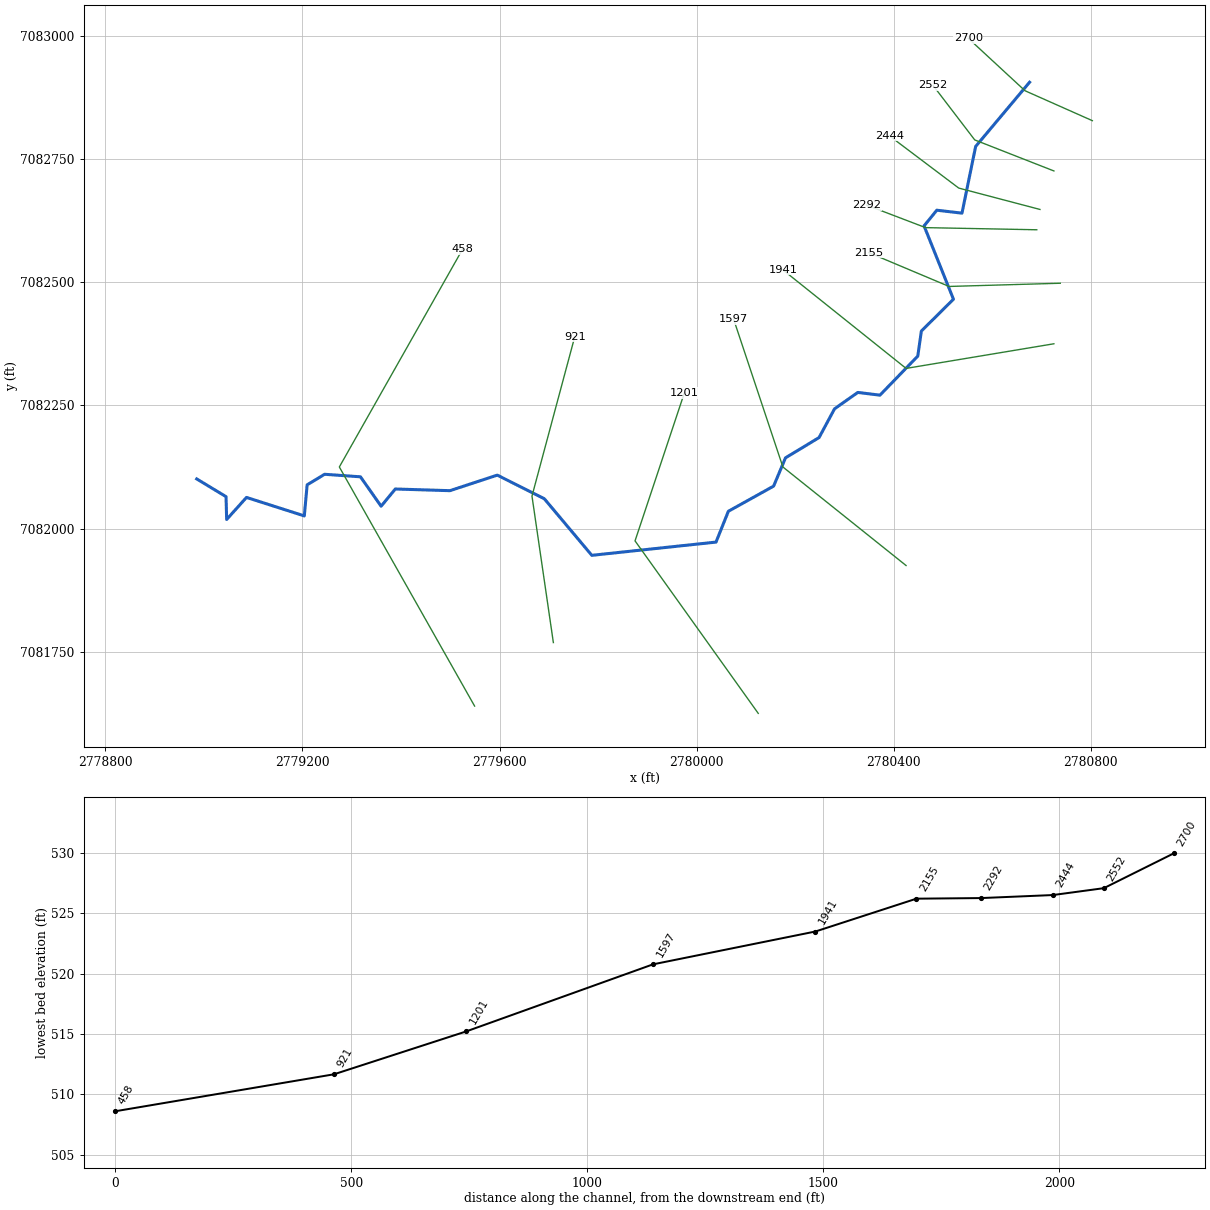
--- UNT 008 in LFCCL Watershed.prj (project) ---

Proj Title=UNT 008 in LFCCL Watershed Base Level Engineering
Current Plan=p01
Default Exp/Contr=0.3,0.1
English Units
Geom File=g01
Flow File=f01
Plan File=p01
BEGIN DESCRIPTION:
UNT 008 in LFCCL Watershed
END DESCRIPTION:

--- UNT 008 in LFCCL Watershed.p01 (plan) ---

Plan Title=Multiple Run
Short Identifier=Multiple
Geom File=g01
Flow File=f01
Subcritical Flow
K Sum by GR= 0
Std Step Tol= 0.01
Critical Tol= 0.01
Num of Std Step Trials= 20
Max Error Tol= 0.3
Flow Tol Ratio= 0.001
Split Flow NTrial= 30
Split Flow Tol= 0.02
Split Flow Ratio= 0.02
Log Output Level= 0
Friction Slope Method= 1
Unsteady Friction Slope Method= 2
Unsteady Bridges Friction Slope Method= 1
Parabolic Critical Depth
Global Vel Dist=  1 , 1 , 1
Global Log Level= 0
CheckData=True
Encroach Param= -1, 0, 0, 0
BEGIN DESCRIPTION:
Multiple Run
END DESCRIPTION:

--- UNT 008 in LFCCL Watershed.f01 (steady flow) ---

Flow Title=Multiple
Number of Profiles=7
Profile Names=10-year,25-year,50-year,1pct_min,100-year,1pct_plu,500-year
River Rch & RM= UNT 008 in LFCCL,Reach-1,2700
     219     272     312     179     356     711     461
Boundary for River Rch & Prof#=UNT 008 in LFCCL,Reach-1,1
Up Type=0
Dn Type=3
Dn Slope=0.005
Boundary for River Rch & Prof#=UNT 008 in LFCCL,Reach-1,2
Up Type=0
Dn Type=3
Dn Slope=0.005
Boundary for River Rch & Prof#=UNT 008 in LFCCL,Reach-1,3
Up Type=0
Dn Type=3
Dn Slope=0.005
Boundary for River Rch & Prof#=UNT 008 in LFCCL,Reach-1,4
Up Type=0
Dn Type=3
Dn Slope=0.005
Boundary for River Rch & Prof#=UNT 008 in LFCCL,Reach-1,5
Up Type=0
Dn Type=3
Dn Slope=0.005
Boundary for River Rch & Prof#=UNT 008 in LFCCL,Reach-1,6
Up Type=0
Dn Type=3
Dn Slope=0.005
Boundary for River Rch & Prof#=UNT 008 in LFCCL,Reach-1,7
Up Type=0
Dn Type=3
Dn Slope=0.005

--- UNT 008 in LFCCL Watershed.g01 (geometry) ---

Geom Title=Existing Conditions

River Reach=UNT 008 in LFCCL,Reach-1
Reach XY= 30
      2780675.59      7082905.71      2780566.16      7082775.35
      2780538.44      7082640.03      2780487.35      7082646.02
      2780461.48      7082614.16      2780521.13      7082465.42
      2780456.01      7082400.78      2780448.75      7082349.95
      2780371.94      7082270.71      2780327.05      7082276.25
      2780279.85      7082243.00      2780248.46      7082184.69
      2780180.29      7082143.49      2780156.20      7082086.15
      2780064.44      7082035.11      2780039.33      7081972.56
      2779787.27      7081945.71      2779690.88      7082060.55
      2779595.48      7082108.46      2779499.36      7082076.89
      2779388.56      7082080.30      2779359.77      7082045.37
      2779317.85      7082105.04      2779245.05      7082110.17
      2779209.65      7082088.68      2779203.90      7082025.71
      2779086.59      7082063.21      2779046.35      7082018.48
      2779045.09      7082064.76      2778985.59      7082100.71

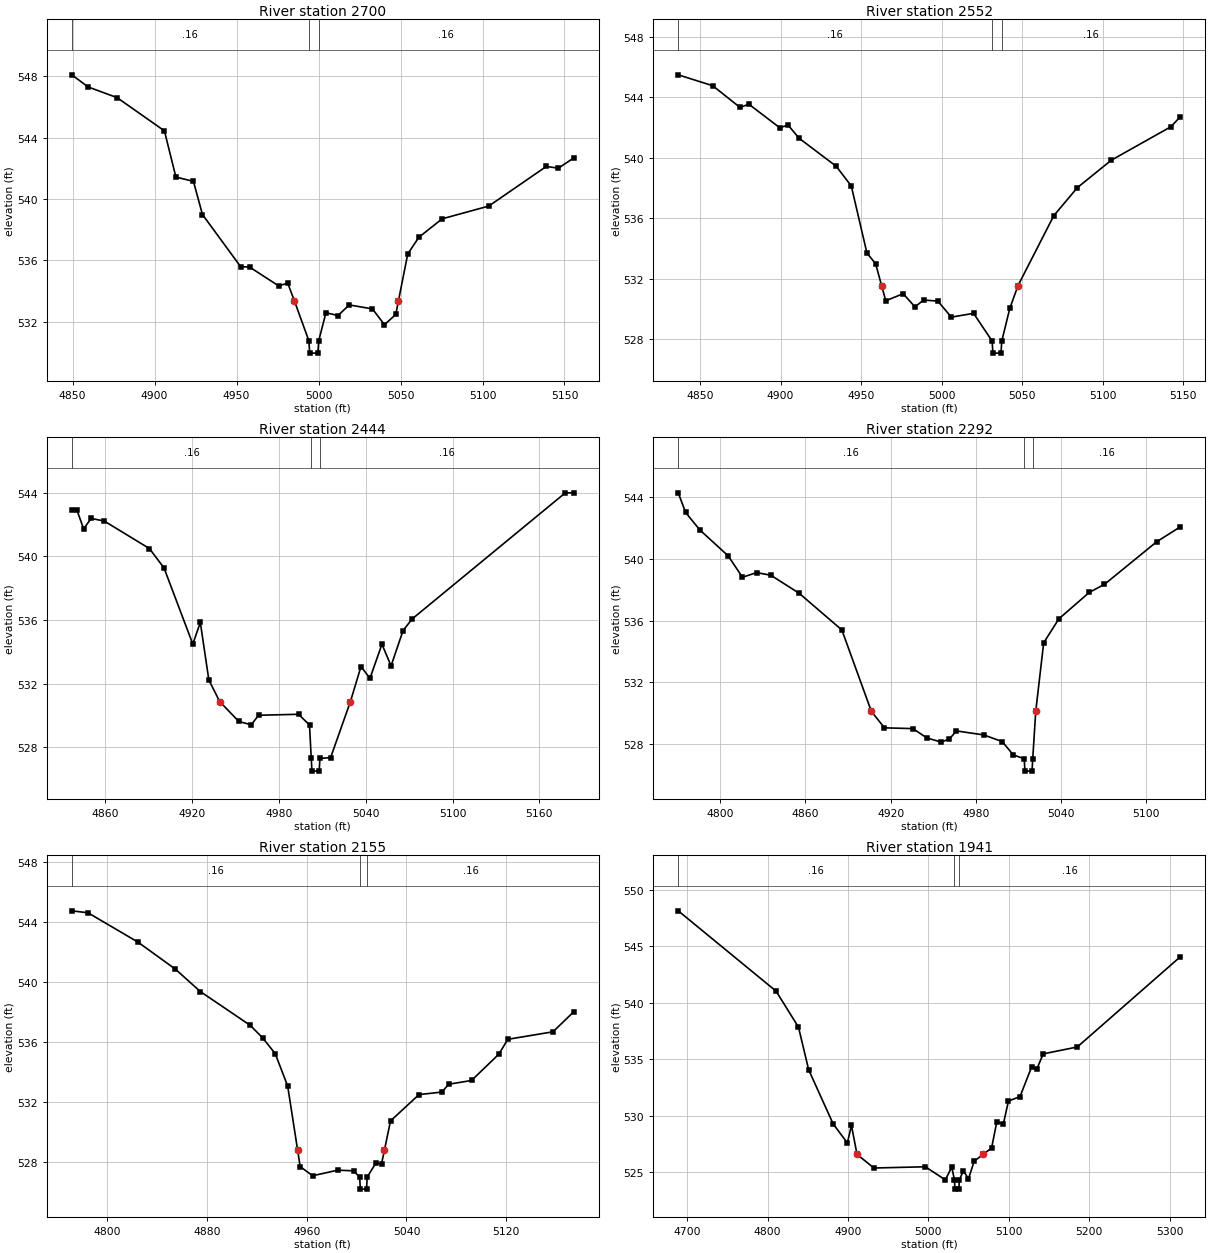
Type RM Length L Ch R = 1,2700,148,148,148
BEGIN DESCRIPTION:
UNT 008 in LFCCL Watershed 5.0
END DESCRIPTION:
XS GIS Cut Line= 3
      2780803.00      7082827.69      2780666.32      7082888.43
      2780551.31      7082994.76
#Sta/Elev= 30
  4849.5  548.09  4859.5  547.30  4877.2  546.60  4906.0  544.44  4913.0  541.43
  4923.7  541.15  4929.2  538.99  4952.5  535.59  4957.9  535.57  4975.7  534.34
  4981.2  534.52  4985.3  533.36  4994.1  530.76  4994.6  529.96  4999.6  529.96
  5000.1  530.76  5004.5  532.59  5011.9  532.41  5018.7  533.10  5032.9  532.84
  5040.2  531.81  5047.1  532.48  5048.7  533.35  5054.4  536.42  5061.2  537.51
  5075.4  538.71  5103.8  539.54  5138.9  542.12  5146.3  542.01  5155.7  542.68
#Mann=3,-1,0
  4849.5    0.16       0  4994.1    0.07       0  5000.1    0.16       0
Bank Sta=4985.3,5048.7
Exp/Cntr=0.3,0.1

Type RM Length L Ch R = 1,2552,108,108,108
BEGIN DESCRIPTION:
XS3088A
END DESCRIPTION:
XS GIS Cut Line= 3
      2780724.96      7082725.66      2780564.33      7082788.61
      2780479.85      7082899.08
#Sta/Elev= 30
  4836.5  545.48  4857.9  544.76  4874.9  543.32  4880.3  543.54  4899.4  541.99
  4904.7  542.15  4911.6  541.28  4934.6  539.43  4943.9  538.13  4953.6  533.70
  4959.0  532.99  4962.7  531.55  4965.3  530.54  4976.1  531.01  4983.4  530.14
  4988.8  530.59  4997.6  530.52  5006.0  529.46  5019.8  529.71  5031.3  527.88
  5031.8  527.08  5036.8  527.08  5037.3  527.88  5042.3  530.05  5047.4  531.55
  5069.6  536.17  5084.2  538.02  5105.2  539.83  5142.3  542.05  5148.1  542.71
#Mann=3,-1,0
  4836.5    0.16       0  5031.3    0.07       0  5037.3    0.16       0
Bank Sta=4962.7,5047.4
Exp/Cntr=0.3,0.1

Type RM Length L Ch R = 1,2444,152,152,152
BEGIN DESCRIPTION:
XS3089A
END DESCRIPTION:
XS GIS Cut Line= 3
      2780696.66      7082647.56      2780531.78      7082690.95
      2780390.68      7082797.32
#Sta/Elev= 30
  4836.7  542.94  4840.1  542.94  4844.9  541.73  4850.1  542.38  4859.1  542.22
  4890.4  540.49  4900.5  539.27  4920.4  534.49  4925.6  535.85  4931.5  532.23
  4939.0  530.88  4952.2  529.63  4960.8  529.42  4965.9  530.02  4993.5  530.08
  5001.1  529.41  5002.3  527.31  5002.8  526.51  5007.8  526.51  5008.3  527.31
  5015.7  527.36  5029.4  530.88  5036.7  533.08  5042.9  532.34  5051.2  534.48
  5057.5  533.12  5065.8  535.34  5072.1  536.07  5178.0  543.99  5183.9  543.99
#Mann=3,-1,0
  4836.7    0.16       0  5002.3    0.07       0  5008.3    0.16       0
Bank Sta=4939,5029.4
Exp/Cntr=0.3,0.1

Type RM Length L Ch R = 1,2292,137,137,137
BEGIN DESCRIPTION:
XS3091A
END DESCRIPTION:
XS GIS Cut Line= 3
      2780690.16      7082606.32      2780464.50      7082610.66
      2780345.11      7082656.24
#Sta/Elev= 30
  4770.4  544.26  4775.6  542.99  4785.6  541.86  4805.6  540.18  4815.6  538.80
  4825.6  539.10  4835.6  538.93  4855.6  537.76  4885.6  535.39  4906.4  530.12
  4915.6  529.06  4935.6  529.01  4945.6  528.40  4955.6  528.14  4961.3  528.34
  4966.3  528.86  4985.6  528.60  4998.5  528.17  5006.3  527.31  5014.0  527.06
  5014.5  526.26  5019.5  526.26  5020.0  527.06  5022.1  530.12  5027.7  534.56
  5038.4  536.11  5059.8  537.82  5070.5  538.34  5107.2  541.09  5123.9  542.06
#Mann=3,-1,0
  4770.4    0.16       0  5014.0    0.07       0  5020.0    0.16       0
Bank Sta=4906.4,5022.1
Exp/Cntr=0.3,0.1

Type RM Length L Ch R = 1,2155,214,214,214
BEGIN DESCRIPTION:
XS3090A
END DESCRIPTION:
XS GIS Cut Line= 3
      2780737.95      7082497.81      2780512.24      7082491.30
      2780349.58      7082559.79
#Sta/Elev= 30
  4771.8  544.73  4784.8  544.60  4824.8  542.65  4854.8  540.85  4874.8  539.36
  4914.8  537.11  4924.8  536.27  4934.8  535.23  4944.8  533.07  4952.8  528.79
  4954.8  527.71  4964.8  527.10  4984.8  527.47  4997.6  527.43  5002.5  527.01
  5003.0  526.21  5008.0  526.21  5008.5  527.01  5015.5  527.95  5020.0  527.89
  5022.3  528.79  5027.2  530.75  5050.0  532.50  5068.4  532.67  5073.8  533.19
  5092.1  533.44  5114.0  535.19  5121.2  536.18  5157.4  536.68  5174.1  538.02
#Mann=3,-1,0
  4771.8    0.16       0  5002.5    0.07       0  5008.5    0.16       0
Bank Sta=4952.8,5022.3
Exp/Cntr=0.3,0.1

Type RM Length L Ch R = 1,1941,344,344,344
BEGIN DESCRIPTION:
UNT 008 in LFCCL Watershed 4.0
END DESCRIPTION:
XS GIS Cut Line= 3
      2780724.97      7082374.99      2780425.00      7082325.00
      2780174.97      7082525.03
#Sta/Elev= 30
  4689.0  548.14  4810.6  541.03  4838.5  537.84  4851.2  534.06  4881.6  529.27
  4899.3  527.58  4904.4  529.13  4911.3  526.57  4932.3  525.36  4996.3  525.47
  5021.1  524.31  5029.1  525.44  5032.5  524.29  5033.0  523.49  5038.0  523.49
  5038.5  524.29  5043.5  525.12  5049.9  524.41  5057.1  525.98  5068.4  526.57
  5078.7  527.15  5085.1  529.45  5093.2  529.24  5099.6  531.29  5114.0  531.69
  5128.4  534.31  5134.8  534.11  5142.8  535.47  5185.2  536.08  5313.3  544.07
#Mann=3,-1,0
  4689.0    0.16       0  5032.5    0.07       0  5038.5    0.16       0
Bank Sta=4911.3,5068.4
Exp/Cntr=0.3,0.1

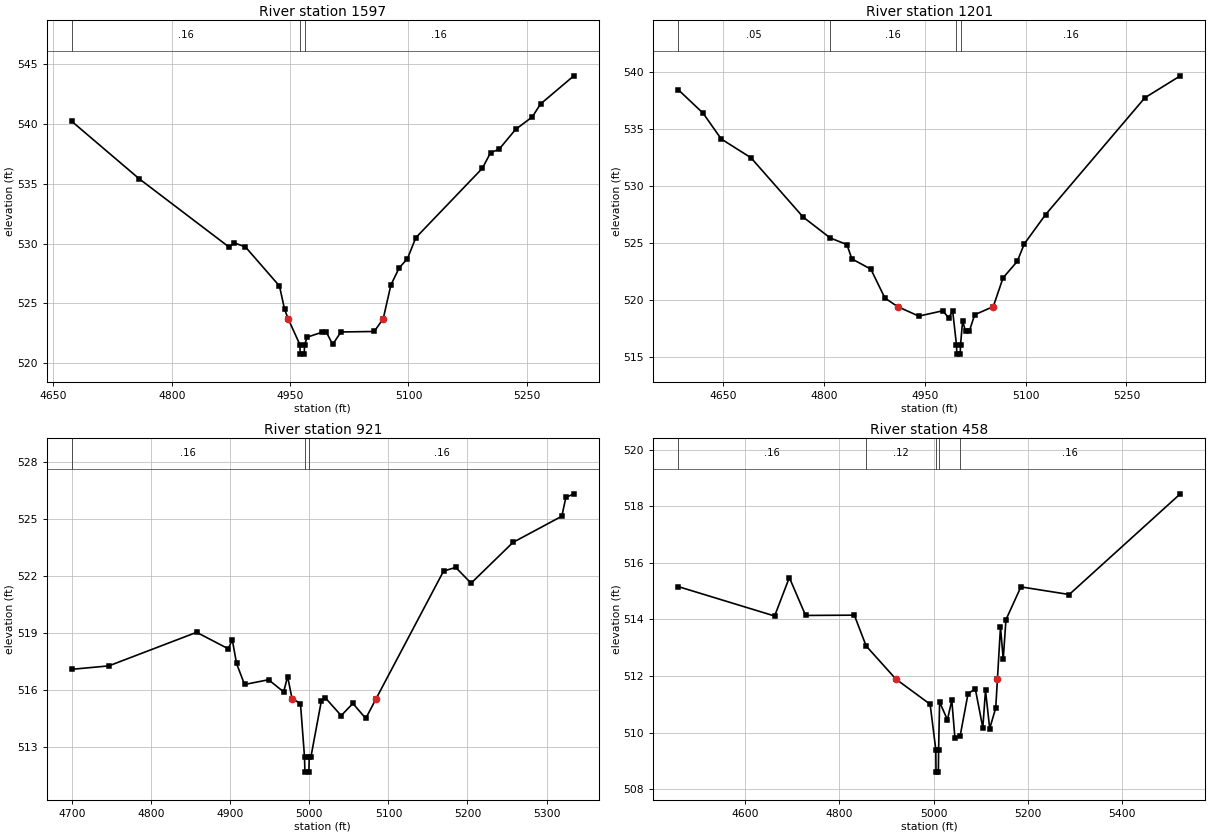
Type RM Length L Ch R = 1,1597,396,396,396
BEGIN DESCRIPTION:
UNT 008 in LFCCL Watershed 3.0
END DESCRIPTION:
XS GIS Cut Line= 3
      2780424.98      7081925.02      2780175.00      7082125.00
      2780074.99      7082425.04
#Sta/Elev= 30
  4673.2  540.20  4758.8  535.40  4872.5  529.71  4878.9  530.06  4893.3  529.72
  4936.5  526.45  4942.9  524.52  4947.4  523.73  4962.3  521.57  4962.8  520.77
  4967.8  520.77  4968.3  521.57  4971.7  522.19  4990.1  522.59  4996.0  522.59
  5003.9  521.58  5014.4  522.62  5056.6  522.66  5068.0  523.73  5077.7  526.54
  5088.2  527.97  5098.7  528.74  5109.3  530.49  5193.6  536.28  5204.1  537.59
  5214.7  537.86  5235.8  539.53  5256.9  540.57  5267.4  541.65  5309.6  544.00
#Mann=3,-1,0
  4673.2    0.16       0  4962.3    0.07       0  4968.3    0.16       0
Bank Sta=4947.4,5068
Exp/Cntr=0.3,0.1

Type RM Length L Ch R = 1,1201,280,280,280
BEGIN DESCRIPTION:
UNT 008 in LFCCL Watershed 2.0
END DESCRIPTION:
XS GIS Cut Line= 3
      2780125.00      7081625.01      2779875.00      7081975.00
      2779974.99      7082274.97
#Sta/Elev= 30
  4583.7  538.45  4620.6  536.39  4647.6  534.12  4691.8  532.47  4769.3  527.26
  4809.6  525.42  4834.4  524.84  4841.8  523.58  4870.0  522.68  4890.9  520.14
  4909.7  519.39  4941.3  518.55  4976.9  519.02  4985.5  518.41  4991.7  518.97
  4997.3  516.01  4997.8  515.21  5002.8  515.21  5003.3  516.01  5006.4  518.12
  5010.7  517.23  5016.4  517.23  5024.3  518.67  5052.0  519.39  5066.5  521.91
  5087.6  523.36  5098.1  524.90  5129.8  527.48  5277.3  537.74  5330.0  539.67
#Mann=4,-1,0
  4583.7    0.05       0  4809.6    0.16       0  4997.3    0.07       0
  5003.3    0.16       0
Bank Sta=4909.7,5052
Exp/Cntr=0.3,0.1

Type RM Length L Ch R = 1,921,463,463,463
BEGIN DESCRIPTION:
XS3092A
END DESCRIPTION:
XS GIS Cut Line= 3
      2779709.29      7081768.64      2779665.89      7082065.95
      2779752.71      7082389.34
#Sta/Elev= 30
  4699.3  517.08  4746.1  517.26  4857.3  519.03  4897.4  518.16  4902.4  518.64
  4907.8  517.39  4917.9  516.28  4948.3  516.53  4967.4  515.89  4972.4  516.70
  4978.0  515.54  4988.7  515.27  4993.8  512.46  4994.3  511.66  4999.3  511.66
  4999.8  512.46  5001.9  512.46  5015.0  515.39  5020.1  515.58  5040.2  514.64
  5055.0  515.28  5071.3  514.49  5084.5  515.54  5169.8  522.26  5185.1  522.45
  5204.6  521.62  5257.6  523.77  5319.4  525.15  5324.5  526.14  5334.6  526.33
#Mann=3,-1,0
  4699.3    0.16       0  4993.8    0.07       0  4999.8    0.16       0
Bank Sta=4978,5084.5
Exp/Cntr=0.3,0.1

Type RM Length L Ch R = 1,458,0,0,0
BEGIN DESCRIPTION:
UNT 008 in LFCCL Watershed 1.0
END DESCRIPTION:
XS GIS Cut Line= 3
      2779549.44      7081639.85      2779275.00      7082125.00
      2779525.11      7082566.94
#Sta/Elev= 30
  4458.0  515.16  4662.5  514.12  4693.7  515.48  4728.2  514.14  4831.6  514.15
  4856.7  513.06  4919.8  511.89  4992.4  511.00  5004.4  509.40  5004.9  508.60
  5009.9  508.60  5010.4  509.40  5012.5  511.08  5029.1  510.45  5038.4  511.14
  5045.0  509.81  5056.0  509.87  5072.9  511.38  5088.3  511.54  5104.2  510.17
  5109.9  511.49  5118.8  510.14  5131.6  510.87  5135.2  511.89  5141.7  513.73
  5147.5  512.59  5153.3  513.99  5185.0  515.15  5287.5  514.88  5523.2  518.44
#Mann=5,-1,0
  4458.0    0.16       0  4856.7    0.12       0  5004.4    0.07       0
  5010.4    0.12       0  5056.0    0.16       0
Bank Sta=4919.8,5135.2
Exp/Cntr=0.3,0.1

Chan Stop Cuts=-1