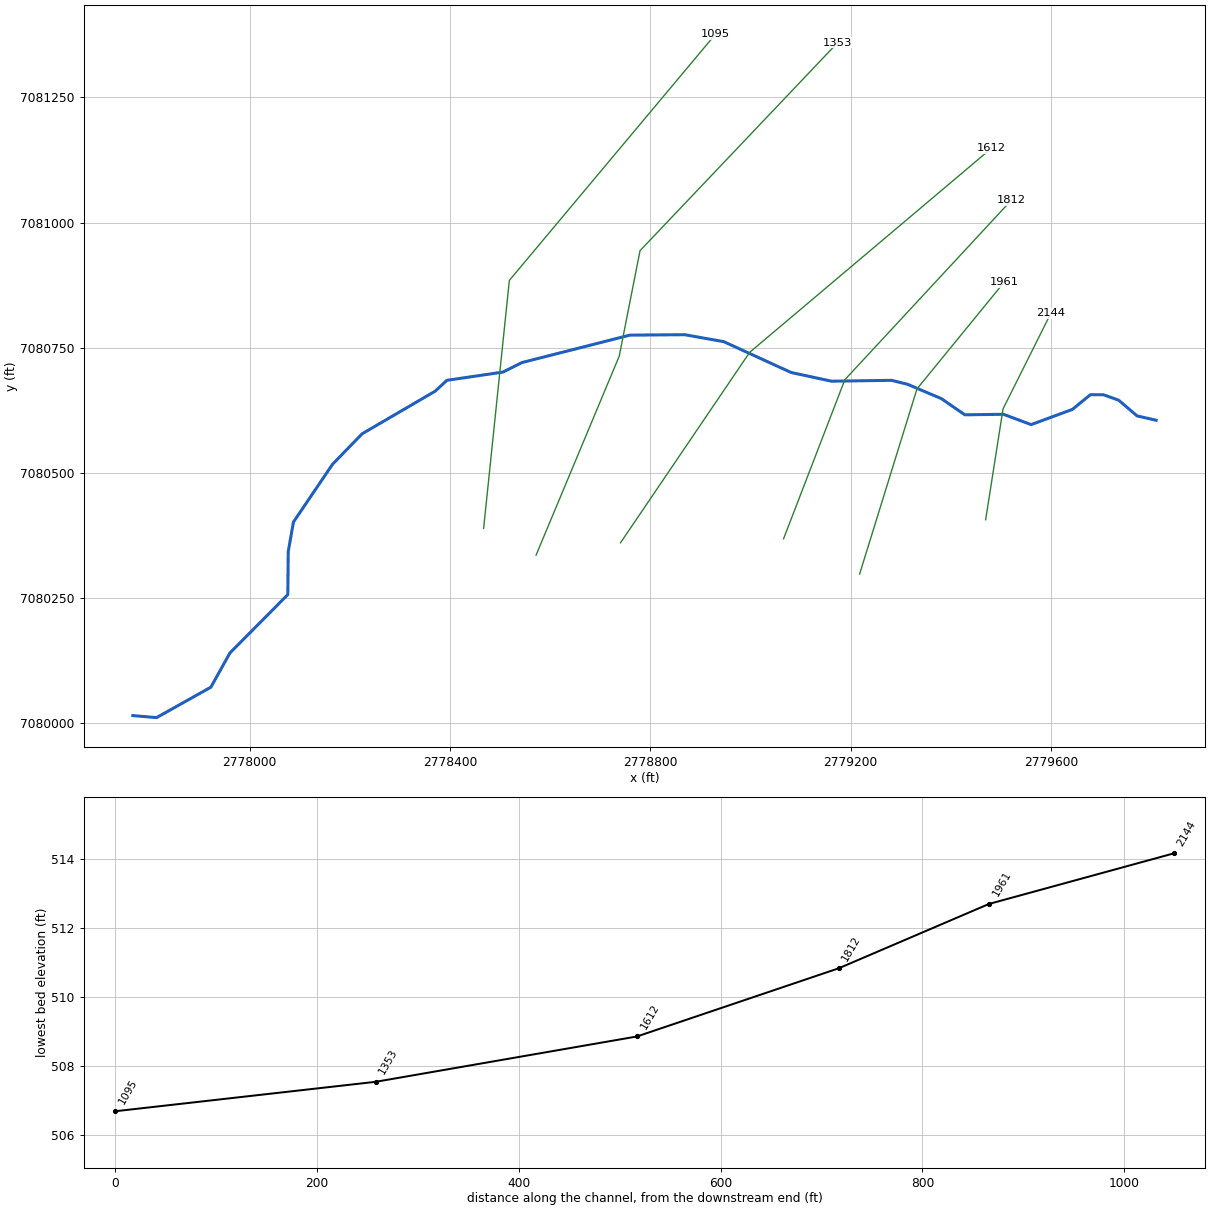
--- UNT 009 in LFCCL Watershed.prj (project) ---

Proj Title=UNT 009 in LFCCL Watershed Base Level Engineering
Current Plan=p01
Default Exp/Contr=0.3,0.1
English Units
Geom File=g01
Flow File=f01
Plan File=p01
BEGIN DESCRIPTION:
UNT 009 in LFCCL Watershed
END DESCRIPTION:

--- UNT 009 in LFCCL Watershed.p01 (plan) ---

Plan Title=Multiple Run
Short Identifier=Multiple
Geom File=g01
Flow File=f01
Subcritical Flow
K Sum by GR= 0
Std Step Tol= 0.01
Critical Tol= 0.01
Num of Std Step Trials= 20
Max Error Tol= 0.3
Flow Tol Ratio= 0.001
Split Flow NTrial= 30
Split Flow Tol= 0.02
Split Flow Ratio= 0.02
Log Output Level= 0
Friction Slope Method= 1
Unsteady Friction Slope Method= 2
Unsteady Bridges Friction Slope Method= 1
Parabolic Critical Depth
Global Vel Dist=  1 , 1 , 1
Global Log Level= 0
CheckData=True
Encroach Param= -1, 0, 0, 0
BEGIN DESCRIPTION:
Multiple Run
END DESCRIPTION:

--- UNT 009 in LFCCL Watershed.f01 (steady flow) ---

Flow Title=Multiple
Number of Profiles=7
Profile Names=10-year,25-year,50-year,1pct_min,100-year,1pct_plu,500-year
River Rch & RM= UNT 009 in LFCCL,Reach-1,2144
     148     178     199     112     223     445     277
Boundary for River Rch & Prof#=UNT 009 in LFCCL,Reach-1,1
Up Type=0
Dn Type=3
Dn Slope=0.005
Boundary for River Rch & Prof#=UNT 009 in LFCCL,Reach-1,2
Up Type=0
Dn Type=3
Dn Slope=0.005
Boundary for River Rch & Prof#=UNT 009 in LFCCL,Reach-1,3
Up Type=0
Dn Type=3
Dn Slope=0.005
Boundary for River Rch & Prof#=UNT 009 in LFCCL,Reach-1,4
Up Type=0
Dn Type=3
Dn Slope=0.005
Boundary for River Rch & Prof#=UNT 009 in LFCCL,Reach-1,5
Up Type=0
Dn Type=3
Dn Slope=0.005
Boundary for River Rch & Prof#=UNT 009 in LFCCL,Reach-1,6
Up Type=0
Dn Type=3
Dn Slope=0.005
Boundary for River Rch & Prof#=UNT 009 in LFCCL,Reach-1,7
Up Type=0
Dn Type=3
Dn Slope=0.005

--- UNT 009 in LFCCL Watershed.g01 (geometry) ---

Geom Title=Existing Conditions

River Reach=UNT 009 in LFCCL,Reach-1
Reach XY= 30
      2779810.11      7080605.13      2779772.14      7080613.81
      2779735.24      7080645.28      2779704.86      7080656.13
      2779678.82      7080656.13      2779643.01      7080626.84
      2779560.55      7080596.45      2779505.21      7080617.07
      2779428.17      7080615.98      2779381.29      7080648.32
      2779313.59      7080676.97      2779281.73      7080684.86
      2779161.94      7080683.13      2779081.21      7080700.49
      2778946.66      7080762.12      2778868.53      7080776.01
      2778759.16      7080775.14      2778543.88      7080720.45
      2778505.69      7080701.36      2778393.71      7080684.86
      2778370.27      7080663.16      2778224.44      7080578.09
      2778165.41      7080517.33      2778087.28      7080401.88
      2778076.87      7080342.85      2778076.00      7080256.91
      2777960.55      7080140.59      2777922.35      7080072.02
      2777813.85      7080011.25      2777766.53      7080015.32

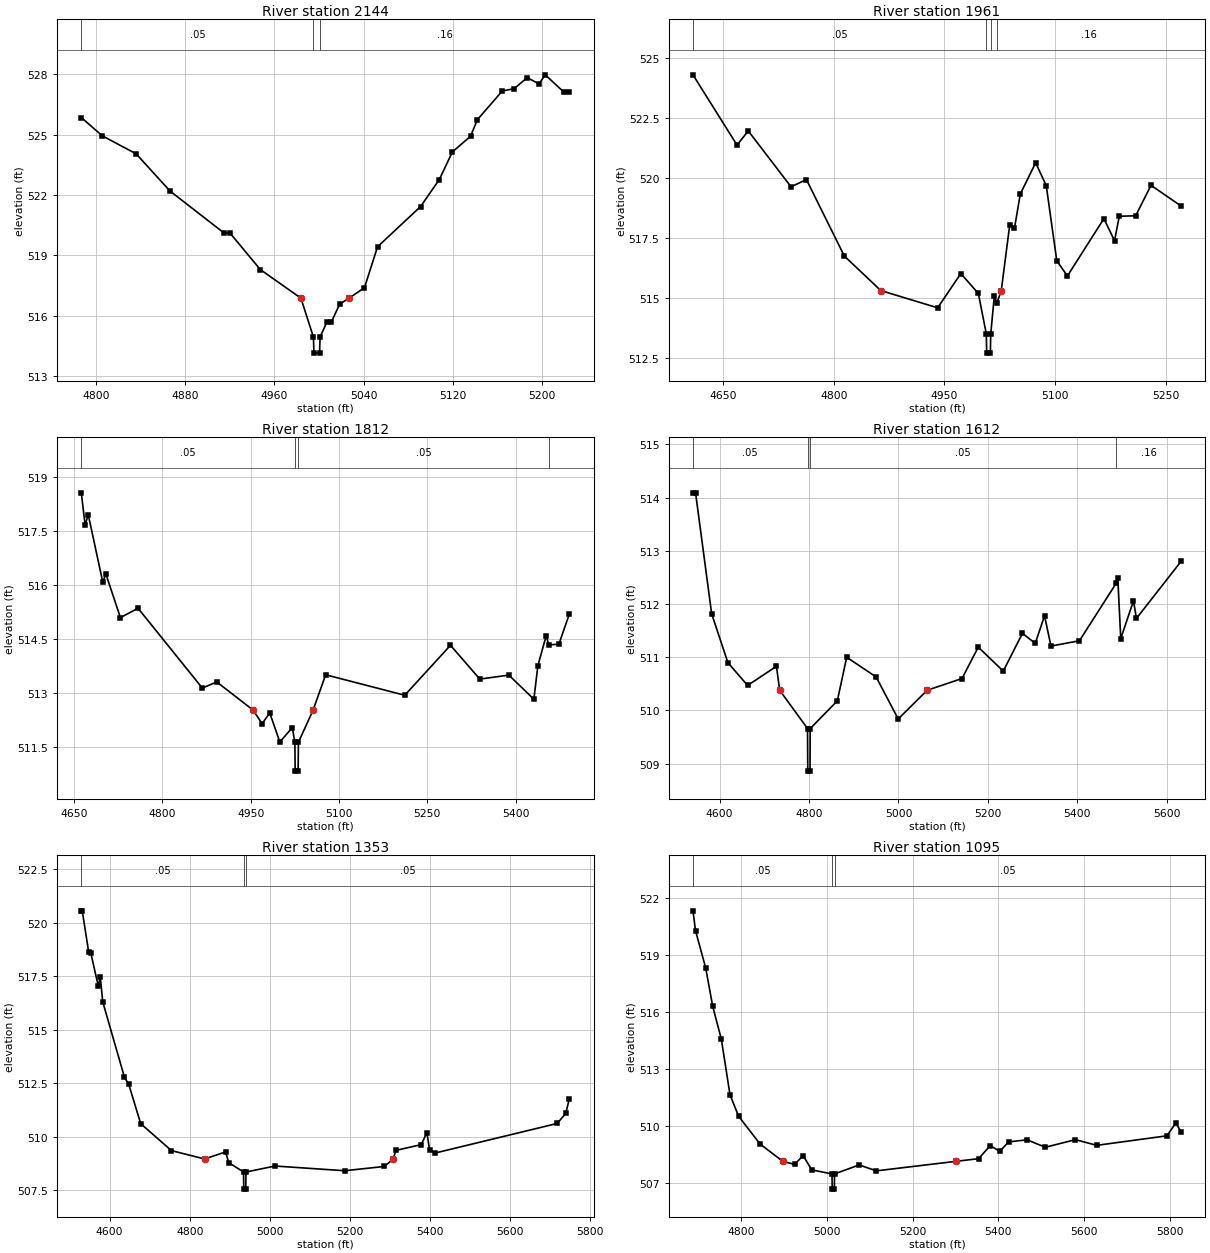
Type RM Length L Ch R = 1,2144,183,183,183
BEGIN DESCRIPTION:
XS3093A
END DESCRIPTION:
XS GIS Cut Line= 3
      2779469.68      7080406.45      2779504.40      7080627.83
      2779599.89      7080818.80
#Sta/Elev= 30
  4786.8  525.85  4805.6  524.94  4835.9  524.05  4866.3  522.20  4914.9  520.11
  4920.0  520.12  4947.3  518.30  4983.7  516.88  4994.9  514.95  4995.4  514.15
  5000.4  514.15  5000.9  514.95  5006.9  515.68  5010.9  515.68  5018.4  516.58
  5026.9  516.88  5040.7  517.40  5052.4  519.43  5091.0  521.43  5107.8  522.77
  5119.5  524.14  5135.8  524.92  5141.9  525.74  5164.3  527.17  5174.9  527.28
  5186.6  527.83  5197.2  527.52  5202.8  527.97  5219.5  527.11  5224.4  527.11
#Mann=3,-1,0
  4786.8    0.05       0  4994.9    0.07       0  5000.9    0.16       0
Bank Sta=4983.7,5026.9
Exp/Cntr=0.3,0.1

Type RM Length L Ch R = 1,1961,149,149,149
BEGIN DESCRIPTION:
UNT 009 in LFCCL Watershed 1.0
END DESCRIPTION:
XS GIS Cut Line= 3
      2779217.95      7080297.98      2779332.53      7080667.76
      2779506.45      7080880.61
#Sta/Elev= 30
  4608.9  524.30  4668.6  521.37  4683.9  521.96  4741.9  519.63  4762.8  519.93
  4814.2  516.74  4863.7  515.30  4940.8  514.58  4972.2  516.01  4996.0  515.18
  5006.8  513.49  5007.3  512.69  5012.3  512.69  5012.8  513.49  5017.7  515.09
  5021.2  514.78  5027.1  515.30  5038.6  518.05  5045.0  517.90  5052.9  519.33
  5073.7  520.63  5088.1  519.68  5102.4  516.54  5116.8  515.91  5166.3  518.30
  5180.7  517.38  5187.2  518.40  5209.4  518.42  5230.2  519.69  5270.9  518.83
#Mann=4,-1,0
  4608.9    0.05       0  5006.8    0.03       0  5012.8    0.05       0
  5021.2    0.16       0
Bank Sta=4863.7,5027.1
Exp/Cntr=0.3,0.1

Type RM Length L Ch R = 1,1812,200,200,200
BEGIN DESCRIPTION:
XS3096A
END DESCRIPTION:
XS GIS Cut Line= 3
      2779066.03      7080368.28      2779188.43      7080685.99
      2779520.86      7081044.39
#Sta/Elev= 30
  4662.2  518.57  4668.6  517.68  4674.0  517.96  4698.6  516.09  4704.0  516.31
  4728.6  515.10  4758.6  515.36  4867.8  513.14  4892.4  513.31  4953.9  512.53
  4969.5  512.15  4982.4  512.45  4999.5  511.64  5020.7  512.04  5025.1  511.63
  5025.6  510.83  5030.6  510.83  5031.1  511.63  5056.1  512.53  5077.4  513.51
  5211.8  512.94  5289.5  514.33  5339.3  513.39  5388.7  513.50  5431.2  512.83
  5438.0  513.76  5452.2  514.60  5456.4  514.34  5473.7  514.36  5491.5  515.20
#Mann=4,-1,0
  4662.2    0.05       0  5025.1    0.03       0  5031.1    0.05       0
  5456.4    0.16       0
Bank Sta=4953.9,5056.1
Exp/Cntr=0.3,0.1

Type RM Length L Ch R = 1,1612,259,259,259
BEGIN DESCRIPTION:
XS3095A
END DESCRIPTION:
XS GIS Cut Line= 3
      2778740.50      7080360.45      2778998.33      7080740.67
      2779481.36      7081148.40
#Sta/Elev= 30
  4540.4  514.09  4546.2  514.09  4582.1  511.82  4618.4  510.90  4662.5  510.47
  4727.1  510.83  4734.3  510.38  4796.6  509.66  4797.1  508.86  4802.1  508.86
  4802.6  509.66  4863.2  510.18  4884.2  511.00  4950.0  510.63  4999.4  509.84
  5064.2  510.38  5142.1  510.60  5178.4  511.19  5234.4  510.74  5277.3  511.45
  5305.9  511.26  5326.7  511.78  5341.0  511.21  5404.7  511.31  5486.9  512.39
  5490.5  512.49  5497.1  511.35  5525.6  512.06  5532.2  511.73  5631.9  512.80
#Mann=4,-1,0
  4540.4    0.05       0  4796.6    0.03       0  4802.6    0.05       0
  5486.9    0.16       0
Bank Sta=4734.3,5064.2
Exp/Cntr=0.3,0.1

Type RM Length L Ch R = 1,1353,258,258,258
BEGIN DESCRIPTION:
Mapping XS d4383e44
END DESCRIPTION:
XS GIS Cut Line= 4
      2778571.82      7080335.77      2778737.91      7080733.20
      2778779.42      7080943.76      2779173.84      7081358.93
#Sta/Elev= 30
  4529.5  520.56  4531.8  520.56  4547.8  518.64  4553.2  518.59  4571.6  517.06
  4577.0  517.45  4582.9  516.31  4637.0  512.79  4647.9  512.45  4677.7  510.61
  4754.5  509.35  4837.1  508.96  4889.8  509.29  4897.2  508.79  4934.4  508.35
  4934.9  507.55  4939.9  507.55  4940.4  508.35  5013.0  508.63  5186.8  508.41
  5285.9  508.61  5308.1  508.96  5314.2  509.36  5377.8  509.63  5391.9  510.19
  5398.8  509.37  5413.0  509.24  5717.1  510.62  5738.6  511.09  5747.5  511.78
#Mann=3,-1,0
  4529.5    0.05       0  4934.4    0.03       0  4940.4    0.05       0
Bank Sta=4837.1,5308.1
Exp/Cntr=0.3,0.1

Type RM Length L Ch R = 1,1095,0,0,0
BEGIN DESCRIPTION:
XS3094A
END DESCRIPTION:
XS GIS Cut Line= 3
      2778467.07      7080389.10      2778518.45      7080884.44
      2778930.36      7081376.36
#Sta/Elev= 30
  4686.8  521.32  4692.7  520.28  4716.5  518.32  4732.9  516.30  4753.1  514.57
  4773.2  511.66  4793.3  510.53  4843.5  509.07  4896.5  508.16  4924.0  508.00
  4944.1  508.46  4964.2  507.71  5011.4  507.50  5011.9  506.70  5016.9  506.70
  5017.4  507.50  5074.8  507.97  5115.0  507.66  5301.0  508.16  5353.6  508.30
  5381.2  508.99  5403.0  508.68  5423.8  509.18  5466.8  509.29  5509.7  508.90
  5580.0  509.30  5629.4  509.00  5793.4  509.50  5814.2  510.17  5826.4  509.72
#Mann=3,-1,0
  4686.8    0.05       0  5011.4    0.03       0  5017.4    0.05       0
Bank Sta=4896.5,5301
Exp/Cntr=0.3,0.1

Chan Stop Cuts=-1