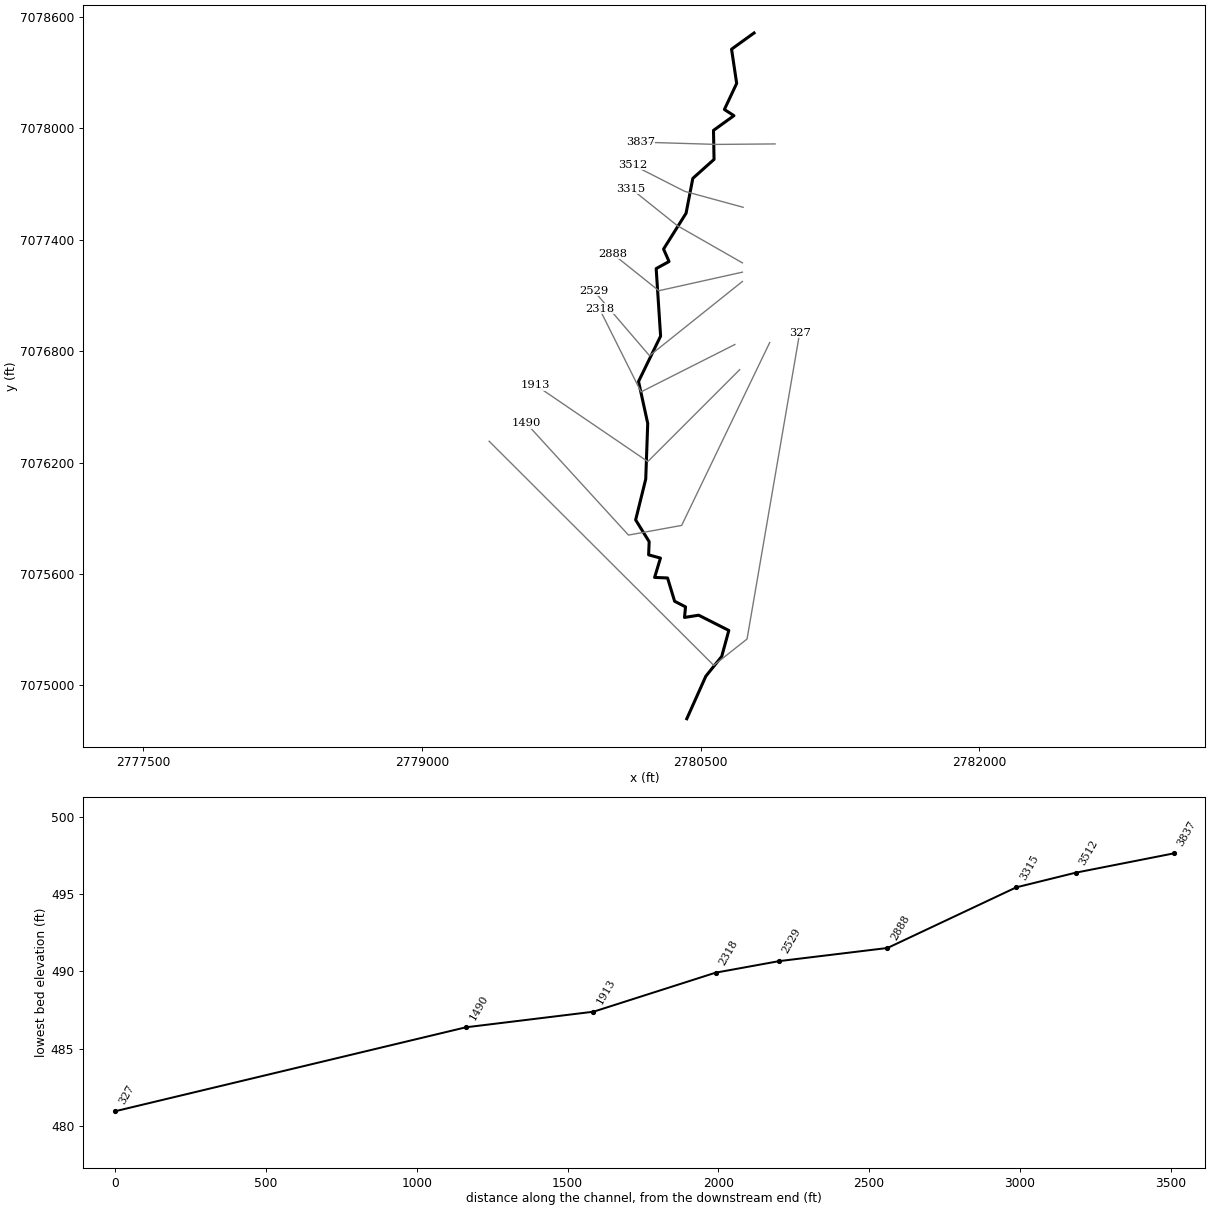
--- UNT 015 in LFCCL Watershed.prj (project) ---

Proj Title=UNT 015 in LFCCL Watershed Base Level Engineering
Current Plan=p01
Default Exp/Contr=0.3,0.1
English Units
Geom File=g01
Flow File=f01
Plan File=p01
BEGIN DESCRIPTION:
UNT 015 in LFCCL Watershed
END DESCRIPTION:

--- UNT 015 in LFCCL Watershed.p01 (plan) ---

Plan Title=Multiple Run
Short Identifier=Multiple
Geom File=g01
Flow File=f01
Subcritical Flow
K Sum by GR= 0
Std Step Tol= 0.01
Critical Tol= 0.01
Num of Std Step Trials= 20
Max Error Tol= 0.3
Flow Tol Ratio= 0.001
Split Flow NTrial= 30
Split Flow Tol= 0.02
Split Flow Ratio= 0.02
Log Output Level= 0
Friction Slope Method= 1
Unsteady Friction Slope Method= 2
Unsteady Bridges Friction Slope Method= 1
Parabolic Critical Depth
Global Vel Dist=  1 , 1 , 1
Global Log Level= 0
CheckData=True
Encroach Param= -1, 0, 0, 0
BEGIN DESCRIPTION:
Multiple Run
END DESCRIPTION:

--- UNT 015 in LFCCL Watershed.f01 (steady flow) ---

Flow Title=Multiple
Number of Profiles=7
Profile Names=10-year,25-year,50-year,1pct_min,100-year,1pct_plu,500-year
River Rch & RM= UNT 015 in LFCCL,Reach-1,3837
     463     605     716     421     840    1676    1153
River Rch & RM= UNT 015 in LFCCL,Reach-1,1490
     688     920    1108     661    1319    2632    1866
Boundary for River Rch & Prof#=UNT 015 in LFCCL,Reach-1,1
Up Type=0
Dn Type=3
Dn Slope=0.005
Boundary for River Rch & Prof#=UNT 015 in LFCCL,Reach-1,2
Up Type=0
Dn Type=3
Dn Slope=0.005
Boundary for River Rch & Prof#=UNT 015 in LFCCL,Reach-1,3
Up Type=0
Dn Type=3
Dn Slope=0.005
Boundary for River Rch & Prof#=UNT 015 in LFCCL,Reach-1,4
Up Type=0
Dn Type=3
Dn Slope=0.005
Boundary for River Rch & Prof#=UNT 015 in LFCCL,Reach-1,5
Up Type=0
Dn Type=3
Dn Slope=0.005
Boundary for River Rch & Prof#=UNT 015 in LFCCL,Reach-1,6
Up Type=0
Dn Type=3
Dn Slope=0.005
Boundary for River Rch & Prof#=UNT 015 in LFCCL,Reach-1,7
Up Type=0
Dn Type=3
Dn Slope=0.005

--- UNT 015 in LFCCL Watershed.g01 (geometry) ---

Geom Title=Existing Conditions

River Reach=UNT 015 in LFCCL,Reach-1
Reach XY= 30
      2780787.64      7078512.71      2780666.55      7078425.37
      2780694.05      7078241.20      2780627.94      7078100.66
      2780679.36      7078067.54      2780569.28      7077988.30
      2780572.26      7077832.03      2780457.99      7077729.94
      2780421.68      7077542.26      2780300.54      7077349.32
      2780330.00      7077282.23      2780260.71      7077244.16
      2780284.54      7076880.74      2780165.79      7076636.55
      2780215.23      7076410.92      2780204.52      7076110.98
      2780150.19      7075891.20      2780222.98      7075774.02
      2780220.12      7075703.10      2780283.67      7075685.60
      2780252.32      7075581.55      2780321.97      7075578.60
      2780359.99      7075453.19      2780418.73      7075423.02
      2780413.28      7075366.11      2780489.54      7075378.16
      2780651.85      7075296.05      2780613.52      7075155.97
      2780528.00      7075049.72      2780425.59      7074820.71

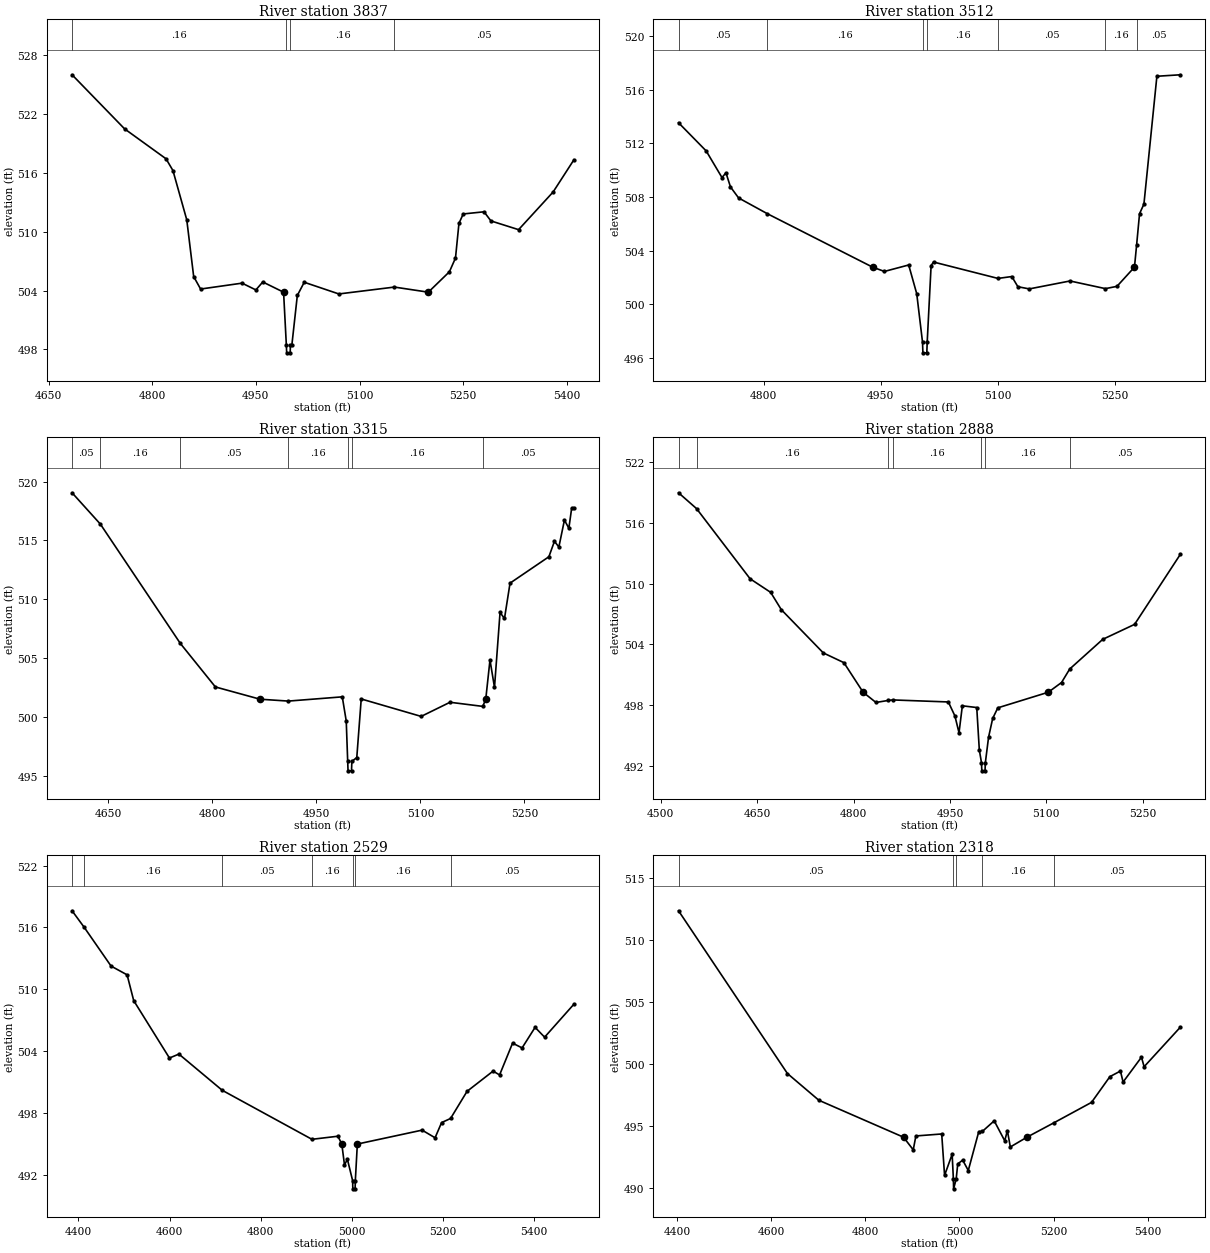
Type RM Length L Ch R = 1,3837,325,325,325
BEGIN DESCRIPTION:
UNT 015 in LFCCL Watershed 5.0
END DESCRIPTION:
XS GIS Cut Line= 3
      2780901.02      7077915.33      2780585.90      7077912.73
      2780175.01      7077925.00
#Sta/Elev= 30
  4684.0  525.98  4760.0  520.47  4820.0  517.42  4830.0  516.22  4850.0  511.20
  4860.0  505.42  4870.0  504.15  4930.0  504.75  4950.0  504.06  4960.0  504.87
  4990.1  503.83  4994.1  498.45  4994.6  497.65  4999.6  497.65  5000.1  498.45
  5002.1  498.45  5010.0  503.50  5020.0  504.84  5070.1  503.65  5150.5  504.35
  5199.6  503.83  5230.1  505.91  5238.9  507.31  5243.9  510.84  5250.1  511.80
  5280.2  512.02  5290.2  511.09  5330.2  510.20  5380.2  514.04  5410.2  517.31
#Mann=4,-1,0
  4684.0    0.16       0  4994.1    0.07       0  5000.1    0.16       0
  5150.5    0.05       0
Bank Sta=4990.1,5199.6
Exp/Cntr=0.3,0.1

Type RM Length L Ch R = 1,3512,197,197,197
BEGIN DESCRIPTION:
XS3098A
END DESCRIPTION:
XS GIS Cut Line= 3
      2780729.18      7077574.17      2780414.03      7077660.12
      2780132.76      7077803.36
#Sta/Elev= 30
  4691.2  513.53  4726.6  511.43  4746.8  509.45  4751.9  509.80  4757.7  508.75
  4768.1  507.93  4804.8  506.76  4939.6  502.78  4954.7  502.46  4985.8  502.94
  4996.1  500.80  5003.5  497.20  5004.0  496.40  5009.0  496.40  5009.5  497.20
  5014.5  502.90  5017.6  503.16  5100.1  501.94  5117.8  502.08  5125.6  501.32
  5140.2  501.16  5192.3  501.75  5237.6  501.18  5252.4  501.35  5274.8  502.78
  5277.6  504.46  5281.3  506.76  5286.9  507.47  5303.5  516.99  5333.5  517.10
#Mann=7,-1,0
  4691.2    0.05       0  4804.8    0.16       0  5003.5    0.07       0
  5009.5    0.16       0  5100.1    0.05       0  5237.6    0.16       0
  5277.6    0.05       0
Bank Sta=4939.6,5274.8
Exp/Cntr=0.3,0.1

Type RM Length L Ch R = 1,3315,427,427,427
BEGIN DESCRIPTION:
UNT 015 in LFCCL Watershed 4.0
END DESCRIPTION:
XS GIS Cut Line= 3
      2780725.03      7077274.98      2780375.00      7077475.00
      2780125.01      7077675.00
#Sta/Elev= 30
  4597.9  519.05  4638.7  516.39  4754.0  506.26  4804.5  502.57  4868.8  501.53
  4909.6  501.37  4987.4  501.73  4993.1  499.68  4995.2  496.25  4995.7  495.45
  5000.7  495.45  5001.2  496.25  5008.3  496.58  5014.7  501.55  5101.1  500.07
  5142.7  501.27  5189.9  500.92  5194.2  501.53  5200.3  504.86  5206.8  502.53
  5214.8  508.89  5221.2  508.38  5229.2  511.38  5285.2  513.62  5293.2  514.93
  5299.6  514.45  5307.6  516.73  5314.0  516.04  5318.0  517.73  5321.2  517.73
#Mann=7,-1,0
  4597.9    0.05       0  4638.7    0.16       0  4754.0    0.05       0
  4909.6    0.16       0  4995.2    0.07       0  5001.2    0.16       0
  5189.9    0.05       0
Bank Sta=4868.8,5194.2
Exp/Cntr=0.3,0.1

Type RM Length L Ch R = 1,2888,359,359,359
BEGIN DESCRIPTION:
UNT 015 in LFCCL Watershed 3.0
END DESCRIPTION:
XS GIS Cut Line= 3
      2780724.99      7077225.00      2780275.00      7077125.00
      2780025.02      7077324.99
#Sta/Elev= 30
  4527.5  518.97  4555.5  517.41  4638.9  510.48  4670.9  509.14  4687.5  507.43
  4752.9  503.16  4784.9  502.20  4814.8  499.28  4834.8  498.27  4853.9  498.47
  4860.9  498.52  4947.5  498.32  4957.7  496.94  4964.1  495.28  4969.3  497.94
  4991.7  497.77  4995.7  493.58  4999.1  492.32  4999.6  491.52  5004.6  491.52
  5005.1  492.32  5010.1  494.84  5016.5  496.69  5024.5  497.74  5103.1  499.28
  5123.7  500.24  5136.4  501.57  5187.8  504.50  5237.4  505.98  5308.6  512.89
#Mann=7,-1,0
  4527.5    0.05       0  4555.5    0.16       0  4853.9    0.05       0
  4860.9    0.16       0  4999.1    0.07       0  5005.1    0.16       0
  5136.4    0.05       0
Bank Sta=4814.8,5103.1
Exp/Cntr=0.3,0.1

Type RM Length L Ch R = 1,2529,211,211,211
BEGIN DESCRIPTION:
UNT 015 in LFCCL Watershed 2.0
END DESCRIPTION:
XS GIS Cut Line= 3
      2780724.99      7077174.99      2780225.00      7076775.00
      2779924.98      7077125.02
#Sta/Elev= 30
  4386.0  517.62  4412.9  516.00  4471.6  512.26  4506.8  511.41  4521.3  508.91
  4599.7  503.35  4620.5  503.73  4715.6  500.22  4912.5  495.47  4969.5  495.77
  4978.0  495.01  4983.9  492.99  4990.3  493.53  5001.7  491.47  5002.2  490.67
  5007.2  490.67  5007.7  491.47  5012.1  495.01  5154.2  496.36  5182.7  495.62
  5197.0  497.09  5216.7  497.49  5252.9  500.12  5310.0  502.08  5324.3  501.71
  5352.8  504.79  5373.7  504.33  5402.2  506.32  5423.1  505.37  5487.3  508.56
#Mann=7,-1,0
  4386.0    0.05       0  4412.9    0.16       0  4715.6    0.05       0
  4912.5    0.16       0  5001.7    0.07       0  5007.7    0.16       0
  5216.7    0.05       0
Bank Sta=4978,5012.1
Exp/Cntr=0.3,0.1

Type RM Length L Ch R = 1,2318,405,405,405
BEGIN DESCRIPTION:
Mapping XS 08674a0c
END DESCRIPTION:
XS GIS Cut Line= 3
      2780684.40      7076835.53      2780179.17      7076580.31
      2779955.22      7077028.22
#Sta/Elev= 30
  4402.7  512.37  4634.2  499.23  4701.1  497.07  4881.0  494.09  4901.7  493.07
  4907.3  494.19  4962.2  494.35  4968.3  491.01  4984.4  492.71  4987.0  490.72
  4987.5  489.92  4993.0  490.72  4996.3  491.93  5006.8  492.24  5018.7  491.40
  5041.0  494.54  5048.7  494.56  5073.8  495.41  5096.2  493.80  5101.8  494.62
  5108.1  493.30  5143.4  494.09  5201.1  495.26  5280.7  496.90  5319.8  498.98
  5342.2  499.43  5347.8  498.54  5386.9  500.55  5392.5  499.78  5469.5  502.97
#Mann=5,-1,0
  4402.7    0.05       0  4987.0    0.03       0  4993.0    0.05       0
  5048.7    0.16       0  5201.1    0.05       0
Bank Sta=4881,5143.4
Exp/Cntr=0.3,0.1

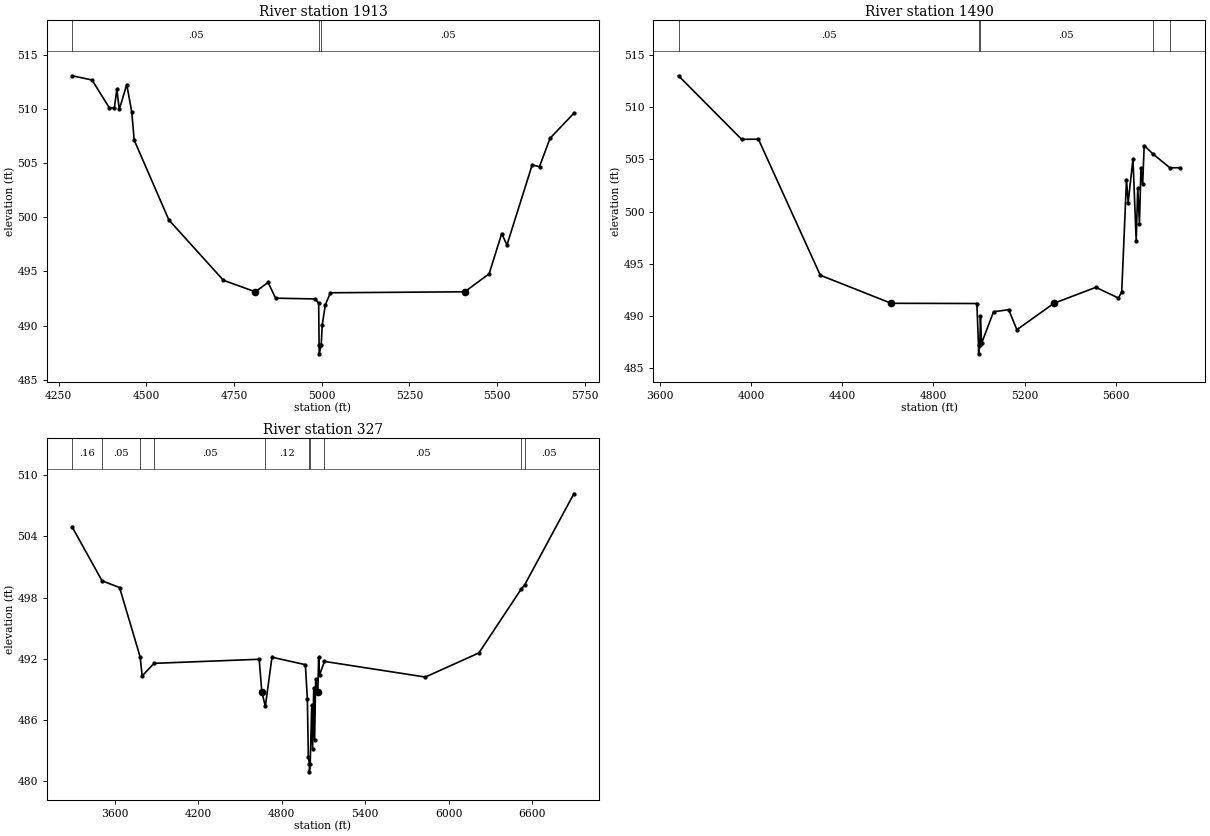
Type RM Length L Ch R = 1,1913,423,423,423
BEGIN DESCRIPTION:
Mapping XS 702f05d3
END DESCRIPTION:
XS GIS Cut Line= 3
      2780710.41      7076700.10      2780215.63      7076205.31
      2779611.46      7076616.78
#Sta/Elev= 30
  4288.2  513.07  4345.1  512.68  4394.6  510.10  4408.8  510.11  4415.8  511.81
  4422.9  509.96  4444.1  512.26  4458.3  509.75  4465.3  507.13  4564.3  499.75
  4719.9  494.18  4810.8  493.12  4847.2  493.99  4868.4  492.53  4981.5  492.46
  4991.3  492.08  4992.5  488.19  4993.0  487.39  4998.5  488.19  5001.5  490.06
  5010.4  491.93  5025.0  493.03  5407.8  493.12  5477.3  494.78  5513.2  498.50
  5528.1  497.44  5600.0  504.83  5621.0  504.68  5650.8  507.29  5718.9  509.61
#Mann=3,-1,0
  4288.2    0.05       0  4992.5    0.03       0  4998.5    0.05       0
Bank Sta=4810.8,5407.8
Exp/Cntr=0.3,0.1

Type RM Length L Ch R = 1,1490,1163,1163,1163
BEGIN DESCRIPTION:
Mapping XS 6b7e67c0
END DESCRIPTION:
XS GIS Cut Line= 4
      2780871.87      7076845.92      2780397.92      7075861.56
      2780111.47      7075809.48      2779559.71      7076413.29
#Sta/Elev= 30
  3681.8  513.01  3958.7  506.92  4032.2  506.94  4303.7  493.91  4614.8  491.22
  4990.7  491.20  4997.9  487.18  4998.4  486.38  5003.9  487.18  5006.3  489.98
  5011.4  487.39  5064.0  490.41  5130.4  490.61  5166.2  488.69  5328.8  491.22
  5512.8  492.75  5612.1  491.72  5626.3  492.33  5647.2  503.03  5654.6  500.87
  5675.6  505.04  5689.8  497.20  5696.6  502.29  5704.0  498.81  5710.7  504.17
  5718.1  502.61  5724.9  506.33  5762.5  505.54  5837.5  504.20  5883.4  504.20
#Mann=5,-1,0
  3681.8    0.05       0  4997.9    0.03       0  5003.9    0.05       0
  5762.5    0.16       0  5837.5    0.05       0
Bank Sta=4614.8,5328.8
Exp/Cntr=0.3,0.1

Type RM Length L Ch R = 1,327,0,0,0
BEGIN DESCRIPTION:
UNT 015 in LFCCL Watershed 1.0
END DESCRIPTION:
XS GIS Cut Line= 4
      2779361.46      7076314.70      2780570.53      7075108.15
      2780750.00      7075250.00      2781033.35      7076898.06
#Sta/Elev= 30
  3291.9  504.93  3507.6  499.64  3633.6  498.98  3781.3  492.20  3796.2  490.33
  3881.5  491.56  4637.7  491.96  4656.7  488.78  4682.0  487.34  4729.6  492.16
  4970.0  491.43  4984.2  488.07  4991.3  482.38  4998.7  481.74  4999.2  480.94
  5004.7  481.74  5015.6  487.47  5022.0  483.20  5030.0  489.14  5036.4  484.04
  5043.9  490.01  5059.6  488.78  5065.3  492.14  5071.6  490.40  5106.8  491.75
  5832.5  490.22  6218.1  492.58  6521.7  498.82  6546.2  499.22  6901.0  508.16
#Mann=10,-1,0
  3291.9    0.16       0  3507.6    0.05       0  3781.3    0.16       0
  3881.5    0.05       0  4682.0    0.12       0  4998.7    0.07       0
  5004.7    0.12       0  5106.8    0.05       0  6521.7    0.16       0
  6546.2    0.05       0
Bank Sta=4656.7,5059.6
Exp/Cntr=0.3,0.1

Chan Stop Cuts=-1