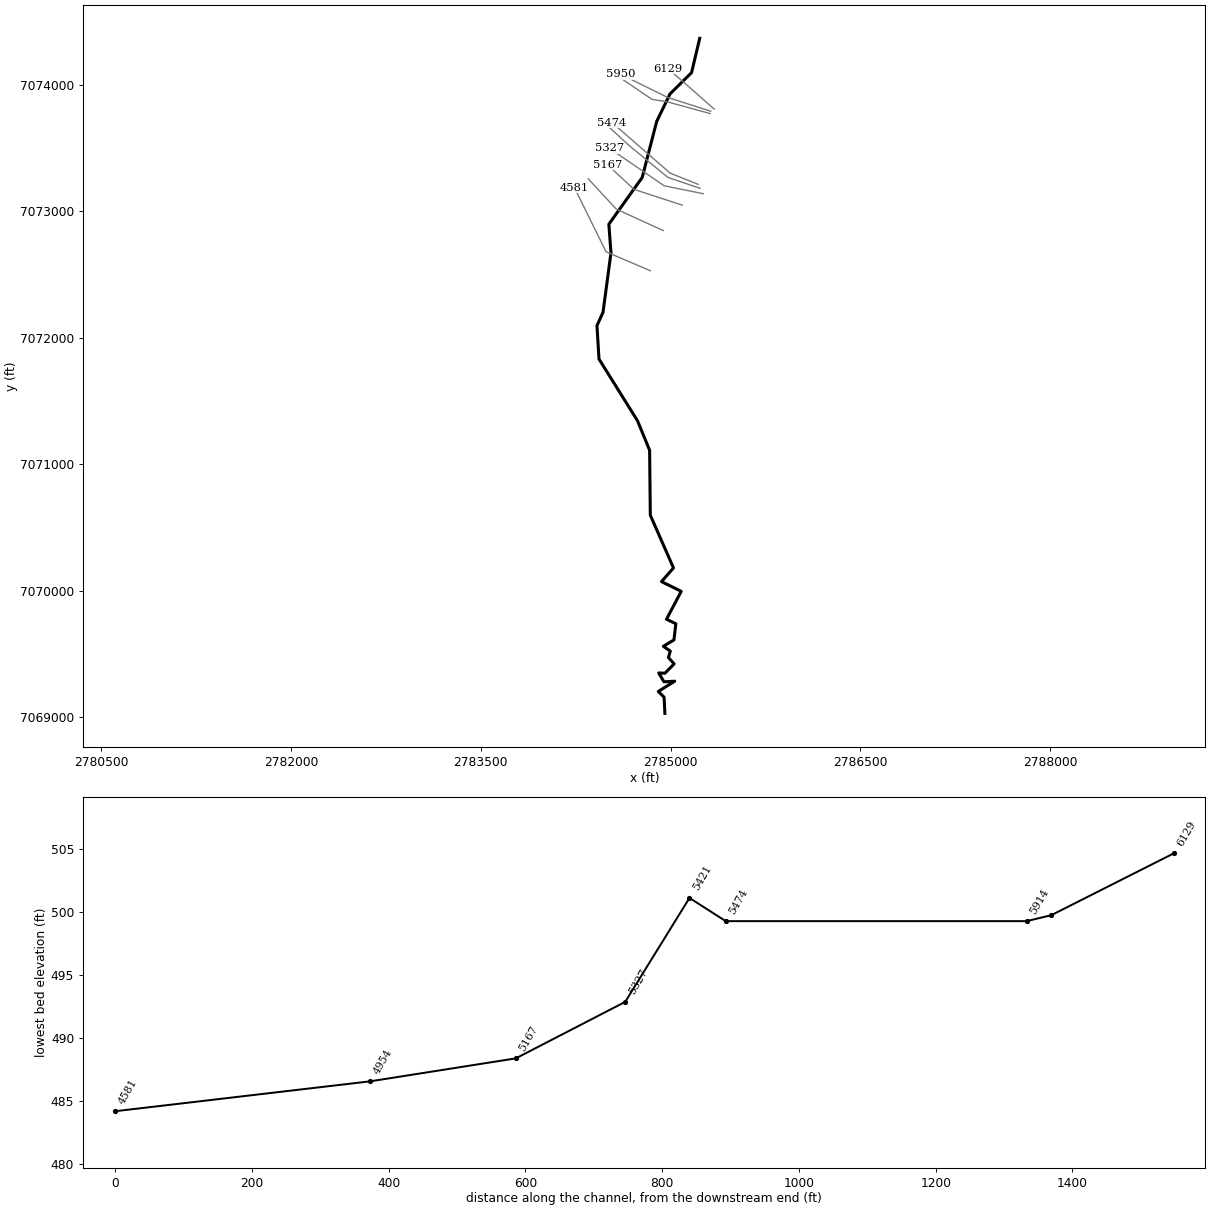
--- UNT 018 in LFCCL Watershed.prj (project) ---

Proj Title=UNT 018 in LFCCL Watershed Base Level Engineering
Current Plan=p01
Default Exp/Contr=0.3,0.1
English Units
Geom File=g01
Flow File=f01
Plan File=p01
BEGIN DESCRIPTION:
UNT 018 in LFCCL Watershed
END DESCRIPTION:

--- UNT 018 in LFCCL Watershed.p01 (plan) ---

Plan Title=Multiple Run
Short Identifier=Multiple
Geom File=g01
Flow File=f01
Subcritical Flow
K Sum by GR= 0
Std Step Tol= 0.01
Critical Tol= 0.01
Num of Std Step Trials= 20
Max Error Tol= 0.3
Flow Tol Ratio= 0.001
Split Flow NTrial= 30
Split Flow Tol= 0.02
Split Flow Ratio= 0.02
Log Output Level= 0
Friction Slope Method= 1
Unsteady Friction Slope Method= 2
Unsteady Bridges Friction Slope Method= 1
Parabolic Critical Depth
Global Vel Dist=  1 , 1 , 1
Global Log Level= 0
CheckData=True
Encroach Param= -1, 0, 0, 0
BEGIN DESCRIPTION:
Multiple Run
END DESCRIPTION:

--- UNT 018 in LFCCL Watershed.f01 (steady flow) ---

Flow Title=Multiple
Number of Profiles=7
Profile Names=10-year,25-year,50-year,1pct_min,100-year,1pct_plu,500-year
River Rch & RM= UNT 018 in LFCCL,Reach-1,6129
     175     214     243     138     275     548     348
Boundary for River Rch & Prof#=UNT 018 in LFCCL,Reach-1,1
Up Type=0
Dn Type=3
Dn Slope=0.005
Boundary for River Rch & Prof#=UNT 018 in LFCCL,Reach-1,2
Up Type=0
Dn Type=3
Dn Slope=0.005
Boundary for River Rch & Prof#=UNT 018 in LFCCL,Reach-1,3
Up Type=0
Dn Type=3
Dn Slope=0.005
Boundary for River Rch & Prof#=UNT 018 in LFCCL,Reach-1,4
Up Type=0
Dn Type=3
Dn Slope=0.005
Boundary for River Rch & Prof#=UNT 018 in LFCCL,Reach-1,5
Up Type=0
Dn Type=3
Dn Slope=0.005
Boundary for River Rch & Prof#=UNT 018 in LFCCL,Reach-1,6
Up Type=0
Dn Type=3
Dn Slope=0.005
Boundary for River Rch & Prof#=UNT 018 in LFCCL,Reach-1,7
Up Type=0
Dn Type=3
Dn Slope=0.005

--- UNT 018 in LFCCL Watershed.g01 (geometry) ---

Geom Title=Existing Conditions

River Reach=UNT 018 in LFCCL,Reach-1
Reach XY= 30
      2785230.91      7074366.34      2785166.59      7074095.51
      2784995.85      7073926.67      2784890.98      7073710.01
      2784776.40      7073266.60      2784512.71      7072897.14
      2784529.43      7072670.78      2784466.41      7072200.07
      2784418.83      7072095.89      2784434.81      7071831.42
      2784739.59      7071342.94      2784834.91      7071110.32
      2784840.45      7070597.39      2785023.59      7070180.44
      2784928.94      7070072.24      2785084.58      7069995.40
      2784968.40      7069774.55      2785042.10      7069739.33
      2785027.46      7069611.49      2784943.37      7069560.81
      2784998.66      7069523.16      2784983.45      7069472.02
      2785028.78      7069421.77      2784955.75      7069348.07
      2784906.77      7069350.19      2784948.35      7069280.23
      2785033.08      7069285.14      2784903.40      7069203.74
      2784949.33      7069158.92      2784955.59      7069030.71

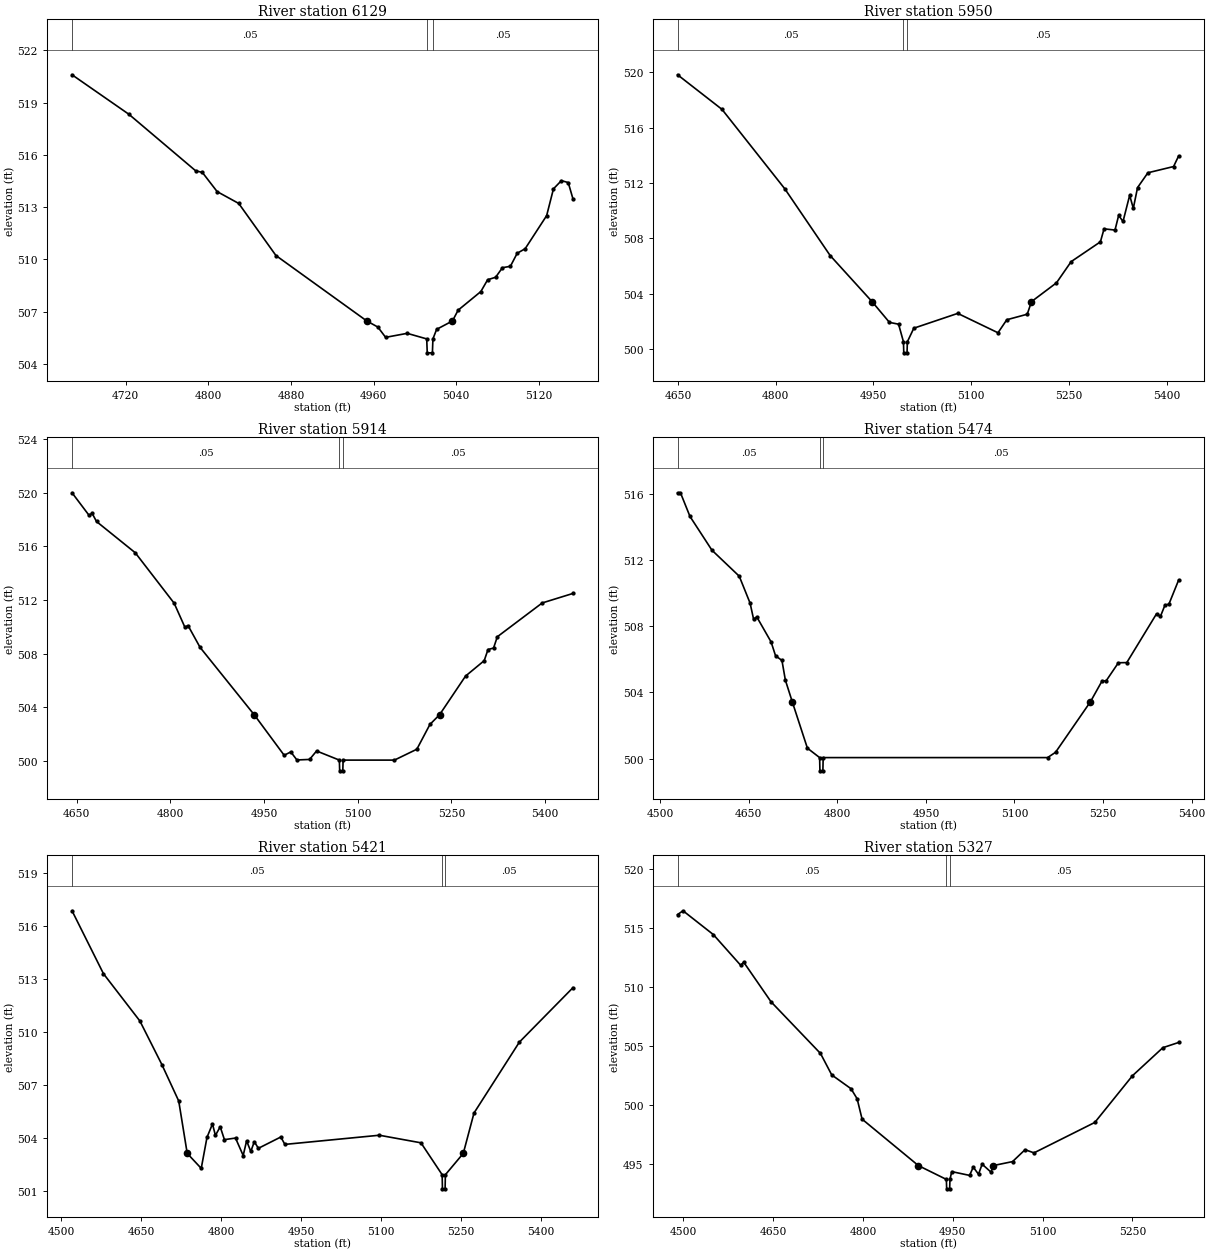
Type RM Length L Ch R = 1,6129,179,179,179
BEGIN DESCRIPTION:
UNT 018 in LFCCL Watershed 2.0
END DESCRIPTION:
XS GIS Cut Line= 3
      2785345.22      7073806.98      2785096.28      7074026.50
      2784979.79      7074125.84
#Sta/Elev= 30
  4668.1  520.60  4723.2  518.33  4787.7  515.09  4794.3  514.99  4808.6  513.89
  4829.5  513.21  4865.5  510.22  4953.5  506.46  4964.2  506.11  4971.7  505.52
  4992.6  505.75  5011.5  505.43  5012.0  504.63  5017.0  504.63  5017.5  505.43
  5021.1  505.98  5036.4  506.46  5041.9  507.08  5063.9  508.15  5070.5  508.83
  5078.2  508.97  5084.8  509.52  5092.5  509.60  5099.1  510.35  5106.8  510.61
  5127.6  512.51  5134.2  514.05  5141.9  514.52  5148.5  514.41  5153.1  513.47
#Mann=3,-1,0
  4668.1    0.05       0  5011.5    0.03       0  5017.5    0.05       0
Bank Sta=4953.5,5036.4
Exp/Cntr=0.3,0.1

Type RM Length L Ch R = 1,5950,36,36,36
BEGIN DESCRIPTION:
XS3102A
END DESCRIPTION:
XS GIS Cut Line= 3
      2785318.02      7073790.16      2784976.89      7073899.53
      2784608.55      7074081.10
#Sta/Elev= 30
  4649.3  519.82  4717.5  517.32  4813.9  511.58  4883.5  506.76  4947.8  503.43
  4974.5  501.93  4988.5  501.80  4996.0  500.53  4996.5  499.73  5001.5  499.73
  5002.0  500.53  5011.9  501.51  5079.3  502.58  5141.1  501.18  5154.6  502.12
  5186.0  502.52  5192.5  503.43  5230.9  504.79  5253.4  506.32  5298.3  507.75
  5303.9  508.69  5320.7  508.60  5326.3  509.66  5333.0  509.22  5343.2  511.11
  5348.8  510.17  5355.3  511.67  5371.2  512.74  5410.6  513.19  5418.2  513.94
#Mann=3,-1,0
  4649.3    0.05       0  4996.0    0.03       0  5002.0    0.05       0
Bank Sta=4947.8,5192.5
Exp/Cntr=0.3,0.1

Type RM Length L Ch R = 1,5914,440,440,440
BEGIN DESCRIPTION:
XS3101A
END DESCRIPTION:
XS GIS Cut Line= 4
      2785312.81      7073771.93      2784979.50      7073863.07
      2784854.50      7073883.90      2784581.02      7074068.82
#Sta/Elev= 30
  4642.4  519.98  4669.5  518.31  4674.7  518.44  4681.6  517.84  4743.7  515.51
  4806.0  511.75  4823.1  509.97  4828.3  510.08  4847.5  508.46  4934.2  503.44
  4982.2  500.42  4992.8  500.67  5002.6  500.07  5022.9  500.11  5034.1  500.74
  5070.6  500.06  5071.1  499.26  5076.1  499.26  5076.6  500.06  5158.8  500.06
  5194.7  500.87  5215.7  502.72  5231.1  503.44  5272.7  506.32  5302.6  507.47
  5308.7  508.30  5317.6  508.41  5323.6  509.25  5395.5  511.77  5444.8  512.48
#Mann=3,-1,0
  4642.4    0.05       0  5070.6    0.03       0  5076.6    0.05       0
Bank Sta=4934.2,5231.1
Exp/Cntr=0.3,0.1

Type RM Length L Ch R = 1,5474,53,53,53
BEGIN DESCRIPTION:
XS3099A
END DESCRIPTION:
XS GIS Cut Line= 3
      2785219.05      7073212.04      2784997.73      7073300.57
      2784537.73      7073700.79
#Sta/Elev= 30
  4529.6  516.06  4534.5  516.06  4550.6  514.63  4587.8  512.59  4634.0  511.02
  4652.4  509.39  4658.3  508.42  4663.7  508.56  4687.9  507.05  4695.5  506.21
  4706.3  505.93  4712.1  504.74  4723.8  503.43  4749.4  500.63  4770.1  500.06
  4770.6  499.26  4775.6  499.26  4776.1  500.06  5156.0  500.06  5169.5  500.38
  5228.5  503.43  5248.4  504.70  5255.0  504.69  5275.9  505.79  5290.1  505.80
  5340.5  508.75  5347.1  508.59  5354.7  509.27  5361.4  509.33  5377.7  510.77
#Mann=3,-1,0
  4529.6    0.05       0  4770.1   0.033       0  4776.1    0.05       0
Bank Sta=4723.8,5228.5
Exp/Cntr=0.3,0.1

Type RM Length L Ch R = 1,5421,94,94,94
BEGIN DESCRIPTION:
XS3100A
END DESCRIPTION:
XS GIS Cut Line= 4
      2785234.71      7073180.77      2784979.50      7073266.71
      2784669.60      7073521.92      2784471.71      7073704.19
#Sta/Elev= 30
  4520.6  516.87  4579.6  513.30  4647.9  510.62  4689.1  508.15  4720.8  506.08
  4736.7  503.11  4763.0  502.26  4773.8  504.02  4784.1  504.78  4789.6  504.13
  4798.6  504.62  4806.5  503.89  4827.3  503.98  4841.7  502.99  4848.1  503.82
  4856.0  503.22  4862.5  503.77  4870.3  503.40  4912.3  504.04  4919.9  503.62
  5097.1  504.14  5175.2  503.71  5215.0  501.90  5215.5  501.10  5220.5  501.10
  5221.0  501.90  5254.6  503.11  5274.7  505.40  5359.8  509.42  5460.4  512.51
#Mann=3,-1,0
  4520.6    0.05       0  5215.0    0.03       0  5221.0    0.05       0
Bank Sta=4736.7,5254.6
Exp/Cntr=0.3,0.1

Type RM Length L Ch R = 1,5327,160,160,160
BEGIN DESCRIPTION:
XS3103A
END DESCRIPTION:
XS GIS Cut Line= 4
      2785259.05      7073138.23      2784949.98      7073200.74
      2784772.90      7073322.27      2784519.70      7073495.69
#Sta/Elev= 30
  4490.1  516.12  4499.2  516.44  4549.9  514.42  4595.5  511.82  4600.6  512.08
  4646.3  508.72  4728.9  504.34  4747.7  502.52  4779.9  501.35  4790.1  500.50
  4798.4  498.77  4892.5  494.83  4939.2  493.66  4939.7  492.86  4944.7  492.86
  4945.2  493.66  4948.2  494.32  4978.0  494.00  4984.1  494.70  4992.9  494.10
  4999.0  494.95  5013.9  494.27  5017.3  494.83  5049.8  495.17  5070.7  496.18
  5085.6  495.91  5187.2  498.49  5250.1  502.45  5300.9  504.83  5327.1  505.27
#Mann=3,-1,0
  4490.1    0.05       0  4939.2    0.03       0  4945.2    0.05       0
Bank Sta=4892.5,5017.3
Exp/Cntr=0.3,0.1

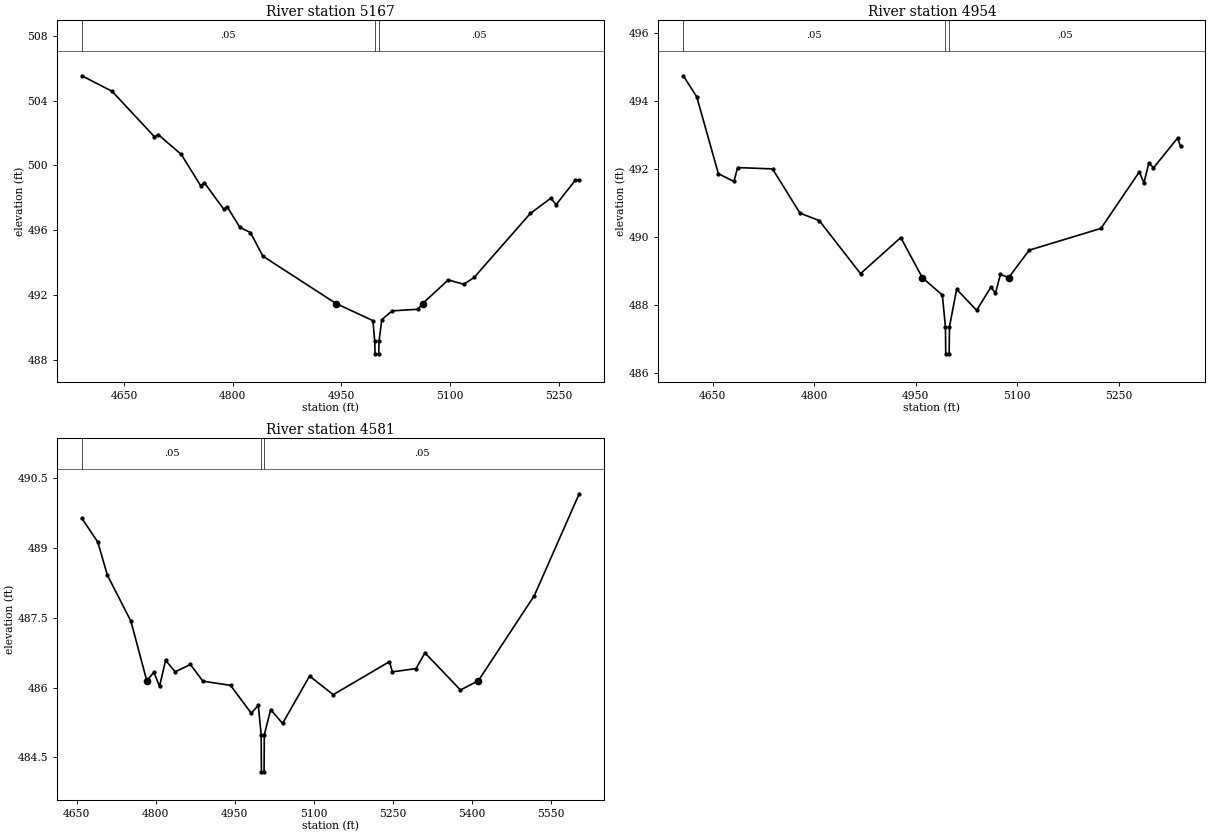
Type RM Length L Ch R = 1,5167,213,213,213
BEGIN DESCRIPTION:
XS3105A
END DESCRIPTION:
XS GIS Cut Line= 3
      2785092.39      7073047.95      2784710.40      7073172.96
      2784502.07      7073367.41
#Sta/Elev= 30
  4591.6  505.53  4633.3  504.57  4691.7  501.77  4697.0  501.90  4728.8  500.68
  4755.4  498.76  4760.7  498.93  4787.3  497.31  4792.6  497.42  4809.8  496.18
  4824.4  495.86  4841.4  494.41  4942.7  491.48  4993.5  490.43  4996.0  489.18
  4996.5  488.38  5001.5  488.38  5002.0  489.18  5005.8  490.49  5020.0  491.03
  5055.6  491.13  5062.1  491.48  5097.6  492.94  5119.1  492.67  5133.3  493.09
  5211.0  497.04  5239.3  497.98  5246.6  497.58  5273.1  499.09  5278.5  499.09
#Mann=3,-1,0
  4591.6    0.05       0  4996.0    0.03       0  5002.0    0.05       0
Bank Sta=4942.7,5062.1
Exp/Cntr=0.3,0.1

Type RM Length L Ch R = 1,4954,373,373,373
BEGIN DESCRIPTION:
XS3104A
END DESCRIPTION:
XS GIS Cut Line= 3
      2784943.07      7072846.56      2784571.51      7073016.71
      2784349.66      7073255.89
#Sta/Elev= 30
  4606.5  494.74  4626.4  494.12  4658.3  491.86  4681.3  491.63  4686.8  492.04
  4738.4  492.00  4778.9  490.70  4807.4  490.48  4868.4  488.92  4927.9  489.98
  4959.8  488.80  4989.3  488.29  4993.9  487.36  4994.4  486.56  4999.4  486.56
  4999.9  487.36  5010.5  488.46  5040.0  487.84  5061.0  488.52  5067.9  488.35
  5075.2  488.90  5087.3  488.80  5117.7  489.61  5223.8  490.25  5280.4  491.91
  5287.3  491.59  5294.6  492.18  5301.4  492.03  5337.1  492.91  5341.4  492.66
#Mann=3,-1,0
  4606.5    0.05       0  4993.9    0.03       0  4999.9    0.05       0
Bank Sta=4959.8,5087.3
Exp/Cntr=0.3,0.1

Type RM Length L Ch R = 1,4581,0,0,0
BEGIN DESCRIPTION:
UNT 018 in LFCCL Watershed 1.0
END DESCRIPTION:
XS GIS Cut Line= 3
      2784840.42      7072529.36      2784490.44      7072679.35
      2784241.44      7073184.55
#Sta/Elev= 30
  4660.2  489.64  4690.3  489.13  4708.4  488.42  4753.1  487.43  4783.2  486.15
  4796.7  486.33  4807.5  486.03  4819.0  486.59  4837.1  486.34  4866.1  486.50
  4889.7  486.14  4942.3  486.05  4981.6  485.45  4994.9  485.62  5000.4  484.99
  5000.9  484.19  5005.9  484.19  5006.4  484.99  5018.5  485.53  5041.0  485.23
  5092.3  486.25  5137.2  485.85  5244.0  486.56  5249.5  486.34  5294.4  486.41
  5311.3  486.75  5378.7  485.95  5412.7  486.15  5519.0  487.98  5604.2  490.17
#Mann=3,-1,0
  4660.2    0.05       0  5000.4    0.03       0  5006.4    0.05       0
Bank Sta=4783.2,5412.7
Exp/Cntr=0.3,0.1

Chan Stop Cuts=-1