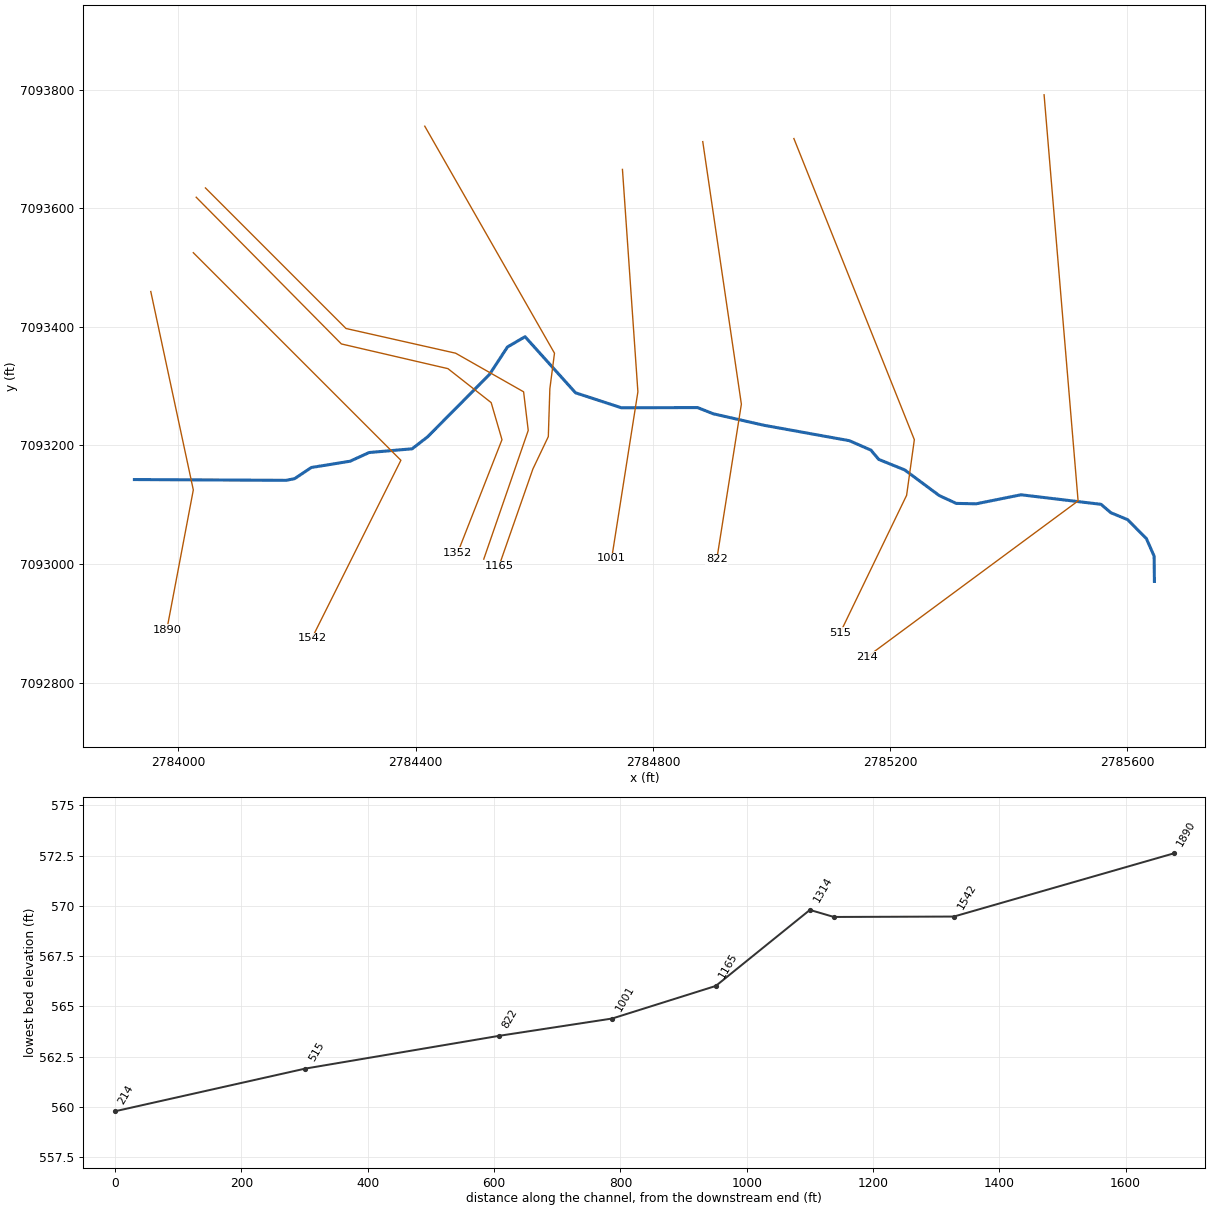
--- UNT 021 in LFCCL Watershed.prj (project) ---

Proj Title=UNT 021 in LFCCL Watershed Base Level Engineering
Current Plan=p01
Default Exp/Contr=0.3,0.1
English Units
Geom File=g01
Flow File=f01
Plan File=p01
BEGIN DESCRIPTION:
UNT 021 in LFCCL Watershed
END DESCRIPTION:

--- UNT 021 in LFCCL Watershed.p01 (plan) ---

Plan Title=Multiple Run
Short Identifier=Multiple
Geom File=g01
Flow File=f01
Subcritical Flow
K Sum by GR= 0
Std Step Tol= 0.01
Critical Tol= 0.01
Num of Std Step Trials= 20
Max Error Tol= 0.3
Flow Tol Ratio= 0.001
Split Flow NTrial= 30
Split Flow Tol= 0.02
Split Flow Ratio= 0.02
Log Output Level= 0
Friction Slope Method= 1
Unsteady Friction Slope Method= 2
Unsteady Bridges Friction Slope Method= 1
Parabolic Critical Depth
Global Vel Dist=  1 , 1 , 1
Global Log Level= 0
CheckData=True
Encroach Param= -1, 0, 0, 0
BEGIN DESCRIPTION:
Multiple Run
END DESCRIPTION:

--- UNT 021 in LFCCL Watershed.f01 (steady flow) ---

Flow Title=Multiple
Number of Profiles=7
Profile Names=10-year,25-year,50-year,1pct_min,100-year,1pct_plu,500-year
River Rch & RM= UNT 021 in LFCCL,Reach-1,1890
     323     412     481     279     557    1111     744
Boundary for River Rch & Prof#=UNT 021 in LFCCL,Reach-1,1
Up Type=0
Dn Type=3
Dn Slope=0.005
Boundary for River Rch & Prof#=UNT 021 in LFCCL,Reach-1,2
Up Type=0
Dn Type=3
Dn Slope=0.005
Boundary for River Rch & Prof#=UNT 021 in LFCCL,Reach-1,3
Up Type=0
Dn Type=3
Dn Slope=0.005
Boundary for River Rch & Prof#=UNT 021 in LFCCL,Reach-1,4
Up Type=0
Dn Type=3
Dn Slope=0.005
Boundary for River Rch & Prof#=UNT 021 in LFCCL,Reach-1,5
Up Type=0
Dn Type=3
Dn Slope=0.005
Boundary for River Rch & Prof#=UNT 021 in LFCCL,Reach-1,6
Up Type=0
Dn Type=3
Dn Slope=0.005
Boundary for River Rch & Prof#=UNT 021 in LFCCL,Reach-1,7
Up Type=0
Dn Type=3
Dn Slope=0.005

--- UNT 021 in LFCCL Watershed.g01 (geometry) ---

Geom Title=Existing Conditions

River Reach=UNT 021 in LFCCL,Reach-1
Reach XY= 30
      2783925.69      7093142.49      2784181.34      7093141.17
      2784195.78      7093143.97      2784224.03      7093162.82
      2784289.47      7093173.42      2784321.40      7093188.04
      2784394.07      7093194.37      2784420.20      7093214.67
      2784524.63      7093320.02      2784554.70      7093366.03
      2784584.38      7093383.33      2784669.48      7093288.77
      2784746.77      7093263.54      2784875.28      7093263.84
      2784901.69      7093253.39      2784986.99      7093234.05
      2785131.21      7093208.03      2785167.54      7093192.14
      2785180.71      7093176.47      2785224.50      7093158.75
      2785282.89      7093115.44      2785311.38      7093102.29
      2785344.96      7093101.58      2785420.55      7093116.82
      2785555.59      7093100.71      2785572.14      7093086.56
      2785600.38      7093074.91      2785632.07      7093042.88
      2785645.10      7093013.38      2785645.59      7092970.71

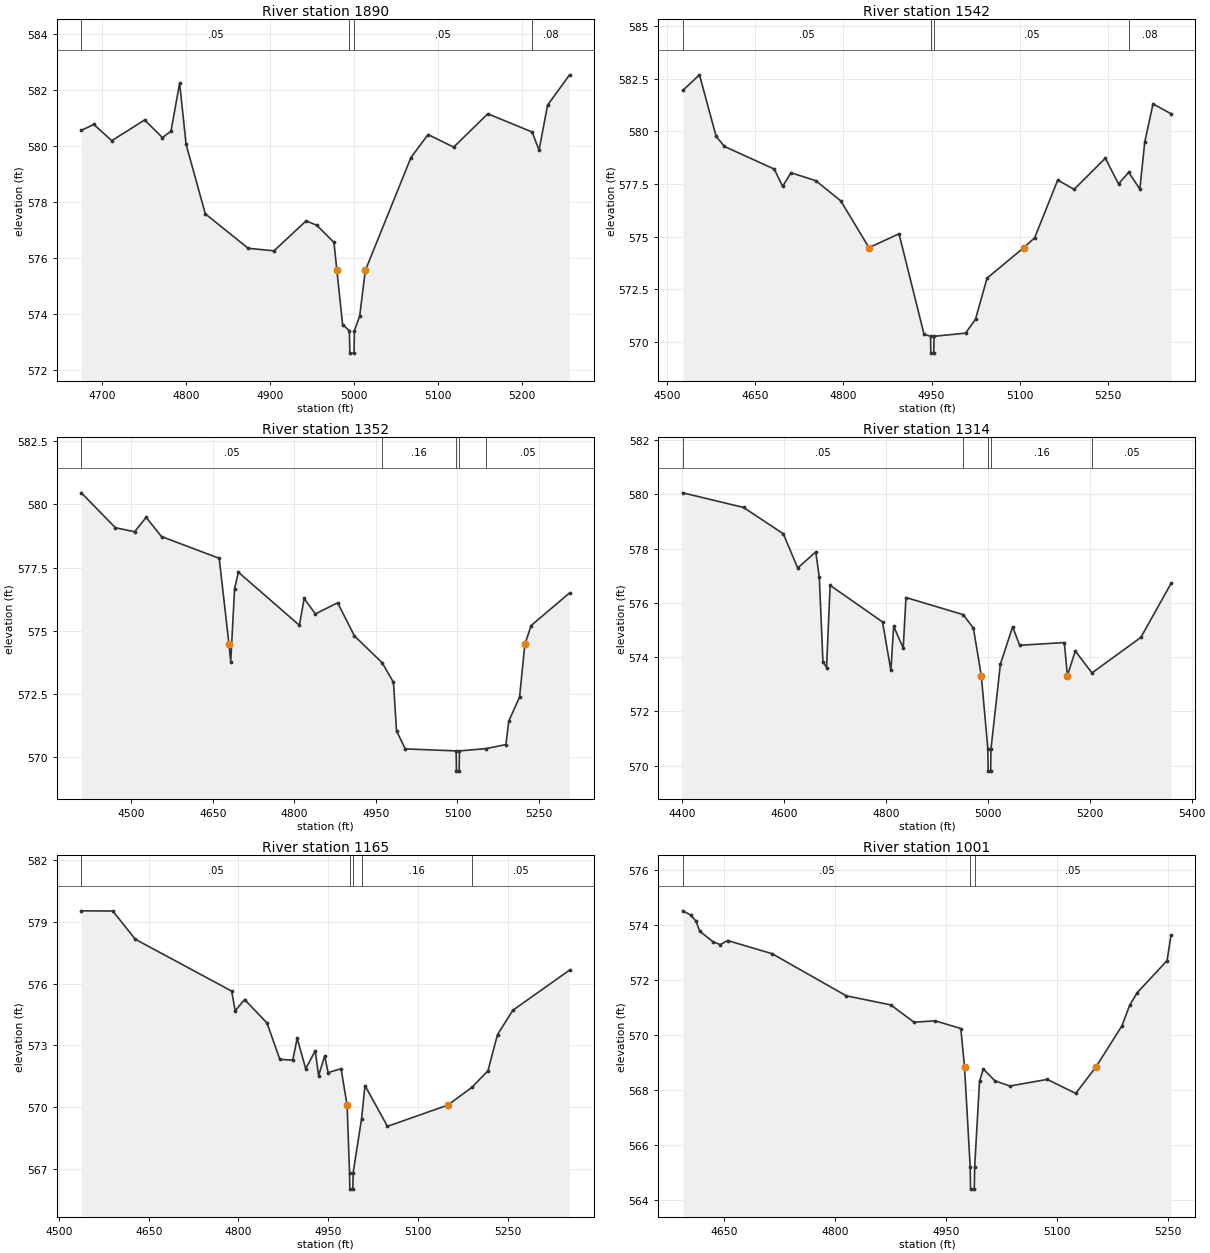
Type RM Length L Ch R = 1,1890,348,348,348
BEGIN DESCRIPTION:
UNT 021 in LFCCL Watershed 3.0
END DESCRIPTION:
XS GIS Cut Line= 3
      2783953.28      7093459.55      2784025.00      7093125.00
      2783980.32      7092889.25
#Sta/Elev= 30
  4674.8  580.56  4689.7  580.77  4711.1  580.19  4750.3  580.93  4771.5  580.30
  4781.7  580.53  4792.0  582.25  4799.7  580.06  4822.6  577.58  4873.8  576.35
  4904.5  576.26  4942.8  577.33  4955.6  577.17  4976.0  576.56  4979.5  575.56
  4986.3  573.63  4994.4  573.41  4994.9  572.61  4999.9  572.61  5000.4  573.41
  5006.7  573.94  5013.4  575.56  5067.8  579.59  5088.2  580.41  5118.7  579.96
  5159.4  581.15  5212.3  580.50  5220.5  579.85  5230.7  581.46  5256.9  582.54
#Mann=4,-1,0
  4674.8    0.05       0  4994.4    0.03       0  5000.4    0.05       0
  5212.3    0.08       0
Bank Sta=4979.5,5013.4
Exp/Cntr=0.3,0.1

Type RM Length L Ch R = 1,1542,190,190,190
BEGIN DESCRIPTION:
UNT 021 in LFCCL Watershed 2.0
END DESCRIPTION:
XS GIS Cut Line= 3
      2784024.98      7093525.02      2784375.00      7093175.00
      2784225.01      7092875.01
#Sta/Elev= 30
  4526.9  581.95  4555.2  582.69  4583.5  579.77  4597.6  579.29  4682.5  578.21
  4696.6  577.39  4710.8  578.04  4753.2  577.66  4795.6  576.70  4843.5  574.48
  4894.6  575.14  4937.1  570.37  4948.2  570.27  4948.7  569.47  4953.7  569.47
  4954.2  570.27  5007.8  570.42  5024.7  571.08  5044.3  573.03  5106.7  574.48
  5125.3  574.95  5164.5  577.69  5192.4  577.25  5245.5  578.73  5267.9  577.51
  5285.3  578.06  5304.2  577.26  5312.6  579.51  5326.6  581.31  5357.3  580.84
#Mann=4,-1,0
  4526.9    0.05       0  4948.2    0.03       0  4954.2    0.05       0
  5285.3    0.08       0
Bank Sta=4843.5,5106.7
Exp/Cntr=0.3,0.1

Type RM Length L Ch R = 1,1352,38,38,38
BEGIN DESCRIPTION:
XS3112A
END DESCRIPTION:
XS GIS Cut Line= 6
      2784029.88      7093618.53      2784274.64      7093371.17
      2784454.33      7093329.50      2784527.24      7093272.21
      2784545.47      7093209.71      2784470.51      7093018.53
#Sta/Elev= 30
  4408.1  580.46  4470.8  579.08  4506.1  578.92  4527.3  579.49  4555.6  578.73
  4661.7  577.87  4679.8  574.46  4682.9  573.77  4690.0  576.67  4697.0  577.32
  4809.2  575.22  4818.0  576.28  4838.6  575.67  4879.6  576.11  4910.4  574.80
  4961.4  573.74  4982.3  572.96  4987.9  571.04  5004.0  570.33  5097.6  570.25
  5098.1  569.45  5103.1  569.45  5103.6  570.25  5152.1  570.34  5189.1  570.50
  5194.4  571.43  5214.2  572.38  5223.9  574.46  5235.5  575.21  5306.2  576.50
#Mann=5,-1,0
  4408.1    0.05       0  4961.4    0.16       0  5097.6    0.07       0
  5103.6    0.16       0  5152.1    0.05       0
Bank Sta=4679.8,5223.9
Exp/Cntr=0.3,0.1

Type RM Length L Ch R = 1,1314,149,149,149
BEGIN DESCRIPTION:
XS3111A
END DESCRIPTION:
XS GIS Cut Line= 6
      2784045.45      7093634.21      2784282.45      7093397.21
      2784467.35      7093355.54      2784581.93      7093290.44
      2784589.74      7093225.33      2784514.74      7093008.29
#Sta/Elev= 30
  4401.7  580.06  4521.0  579.52  4598.8  578.55  4627.1  577.29  4662.5  577.88
  4669.5  576.94  4676.6  573.83  4683.7  573.62  4690.7  576.65  4793.5  575.30
  4809.9  573.51  4815.3  575.14  4834.1  574.34  4839.5  576.20  4951.7  575.57
  4971.8  575.07  4987.3  573.32  5000.2  570.60  5000.7  569.80  5005.7  569.80
  5006.2  570.60  5024.7  573.74  5048.7  575.12  5062.6  574.44  5150.2  574.54
  5156.2  573.32  5171.7  574.23  5204.4  573.42  5300.3  574.73  5359.6  576.72
#Mann=5,-1,0
  4401.7    0.05       0  4951.7    0.16       0  5000.2    0.07       0
  5006.2    0.16       0  5204.4    0.05       0
Bank Sta=4987.3,5156.2
Exp/Cntr=0.3,0.1

Type RM Length L Ch R = 1,1165,164,164,164
BEGIN DESCRIPTION:
XS3110A
END DESCRIPTION:
XS GIS Cut Line= 6
      2784415.28      7093738.33      2784634.01      7093355.54
      2784626.20      7093295.65      2784623.60      7093214.92
      2784597.56      7093160.23      2784540.26      7092996.17
#Sta/Elev= 30
  4537.3  579.54  4590.0  579.53  4627.5  578.16  4788.7  575.64  4794.5  574.68
  4810.3  575.23  4847.8  574.09  4869.3  572.32  4890.9  572.29  4898.2  573.35
  4912.5  571.87  4928.4  572.74  4934.1  571.53  4944.2  572.49  4950.0  571.68
  4971.6  571.87  4981.7  570.10  4985.8  566.82  4986.3  566.02  4991.3  566.02
  4991.8  566.82  5005.8  569.42  5011.6  571.05  5049.2  569.07  5150.0  570.10
  5190.2  570.96  5217.2  571.77  5233.2  573.53  5258.9  574.71  5353.7  576.66
#Mann=5,-1,0
  4537.3    0.05       0  4985.8    0.03       0  4991.8    0.05       0
  5005.8    0.16       0  5190.2    0.05       0
Bank Sta=4981.7,5150
Exp/Cntr=0.3,0.1

Type RM Length L Ch R = 1,1001,179,179,179
BEGIN DESCRIPTION:
XS3109A
END DESCRIPTION:
XS GIS Cut Line= 3
      2784748.60      7093665.47      2784774.64      7093290.44
      2784730.44      7093009.63
#Sta/Elev= 30
  4594.0  574.52  4604.5  574.37  4611.9  574.14  4616.9  573.78  4634.6  573.40
  4644.6  573.29  4654.6  573.44  4714.8  572.96  4815.0  571.43  4875.1  571.10
  4906.6  570.47  4935.3  570.52  4969.9  570.24  4974.9  568.85  4982.6  565.20
  4983.1  564.40  4988.1  564.40  4988.6  565.20  4995.2  568.32  5000.3  568.77
  5015.9  568.34  5036.2  568.15  5086.8  568.39  5125.3  567.88  5152.8  568.85
  5187.8  570.34  5198.1  571.08  5208.3  571.54  5248.8  572.71  5254.2  573.65
#Mann=3,-1,0
  4594.0    0.05       0  4982.6    0.03       0  4988.6    0.05       0
Bank Sta=4974.9,5152.8
Exp/Cntr=0.3,0.1

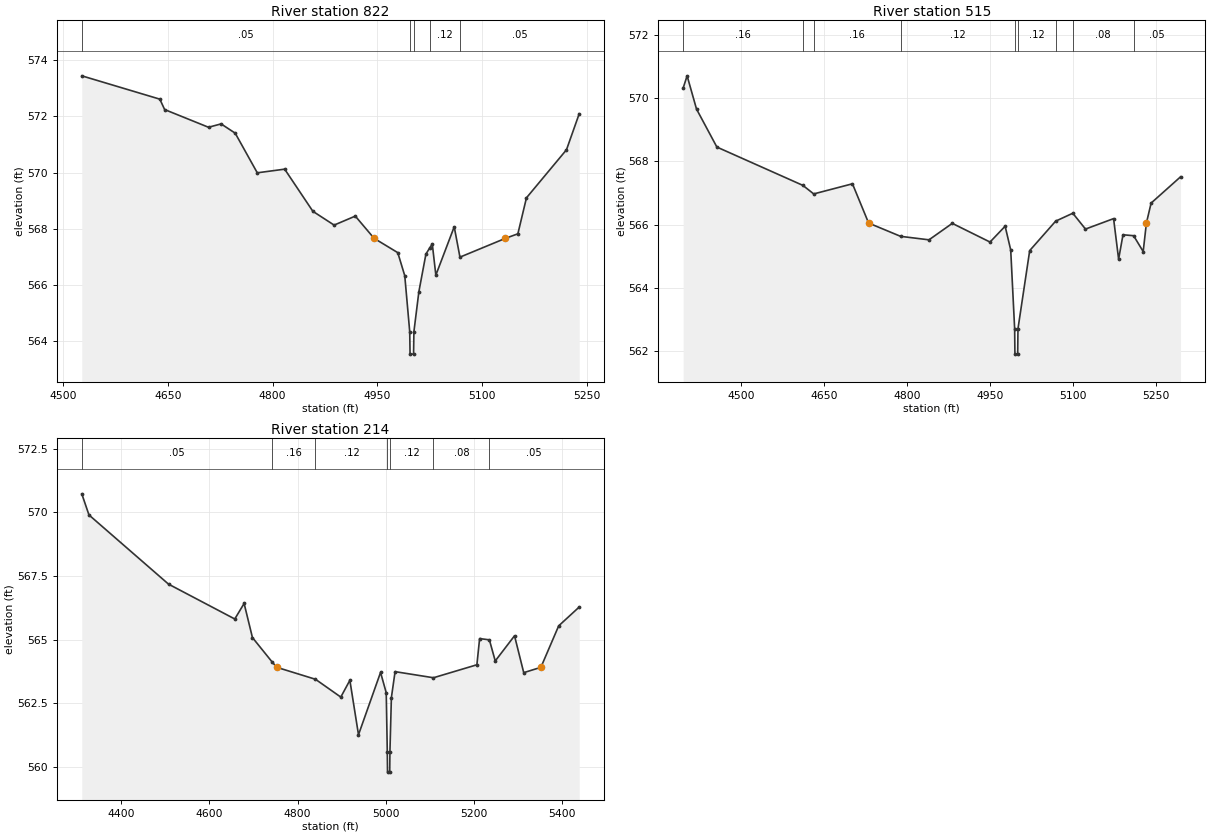
Type RM Length L Ch R = 1,822,307,307,307
BEGIN DESCRIPTION:
XS3108A
END DESCRIPTION:
XS GIS Cut Line= 3
      2784884.01      7093712.31      2784949.12      7093269.60
      2784907.73      7093008.33
#Sta/Elev= 30
  4526.8  573.44  4638.5  572.61  4645.4  572.24  4708.2  571.61  4726.2  571.73
  4746.4  571.40  4778.0  569.99  4817.2  570.12  4857.6  568.62  4888.0  568.13
  4918.3  568.45  4945.2  567.66  4979.1  567.15  4989.1  566.33  4996.2  564.34
  4996.7  563.54  5001.7  563.54  5002.2  564.34  5009.3  565.76  5019.4  567.10
  5024.9  567.32  5028.5  567.46  5033.6  566.35  5059.9  568.07  5068.1  566.99
  5133.3  567.66  5151.0  567.82  5163.3  569.10  5220.6  570.81  5238.8  572.09
#Mann=5,-1,0
  4526.8    0.05       0  4996.2    0.03       0  5002.2    0.05       0
  5024.9    0.12       0  5068.1    0.05       0
Bank Sta=4945.2,5133.3
Exp/Cntr=0.3,0.1

Type RM Length L Ch R = 1,515,301,301,301
BEGIN DESCRIPTION:
XS3107A
END DESCRIPTION:
XS GIS Cut Line= 4
      2785037.67      7093717.49      2785240.78      7093209.71
      2785227.76      7093115.96      2785115.80      7092884.23
#Sta/Elev= 30
  4395.9  570.31  4403.1  570.70  4420.1  569.65  4456.9  568.45  4612.3  567.24
  4631.9  566.97  4701.9  567.29  4731.1  566.05  4788.9  565.63  4840.2  565.52
  4882.3  566.04  4950.5  565.45  4977.8  565.95  4987.9  565.20  4995.0  562.71
  4995.5  561.91  5000.5  561.91  5001.0  562.71  5022.2  565.18  5069.1  566.11
  5100.1  566.36  5123.0  565.86  5173.8  566.19  5182.9  564.91  5190.8  565.68
  5210.0  565.65  5227.3  565.15  5233.1  566.05  5241.6  566.68  5294.8  567.51
#Mann=9,-1,0
  4395.9    0.16       0  4612.3    0.05       0  4631.9    0.16       0
  4788.9    0.12       0  4995.0    0.07       0  5001.0    0.12       0
  5069.1    0.05       0  5100.1    0.08       0  5210.0    0.05       0
Bank Sta=4731.1,5233.1
Exp/Cntr=0.3,0.1

Type RM Length L Ch R = 1,214,0,0,0
BEGIN DESCRIPTION:
XS3106A
END DESCRIPTION:
XS GIS Cut Line= 3
      2785459.54      7093791.27      2785516.91      7093106.49
      2785160.96      7092843.42
#Sta/Elev= 30
  4310.0  570.73  4326.3  569.90  4507.0  567.18  4657.5  565.81  4678.7  566.42
  4697.6  565.08  4742.8  564.11  4752.9  563.91  4840.8  563.44  4898.3  562.74
  4918.9  563.40  4938.5  561.26  4988.6  563.71  5001.5  562.91  5003.9  560.59
  5004.4  559.79  5009.4  559.79  5009.9  560.59  5013.2  562.72  5021.6  563.74
  5108.8  563.50  5207.4  564.01  5213.6  565.04  5235.8  564.99  5249.1  564.16
  5292.9  565.15  5313.8  563.70  5352.8  563.91  5393.2  565.54  5439.8  566.28
#Mann=7,-1,0
  4310.0    0.05       0  4742.8    0.16       0  4840.8    0.12       0
  5003.9    0.07       0  5009.9    0.12       0  5108.8    0.08       0
  5235.8    0.05       0
Bank Sta=4752.9,5352.8
Exp/Cntr=0.3,0.1

Chan Stop Cuts=-1