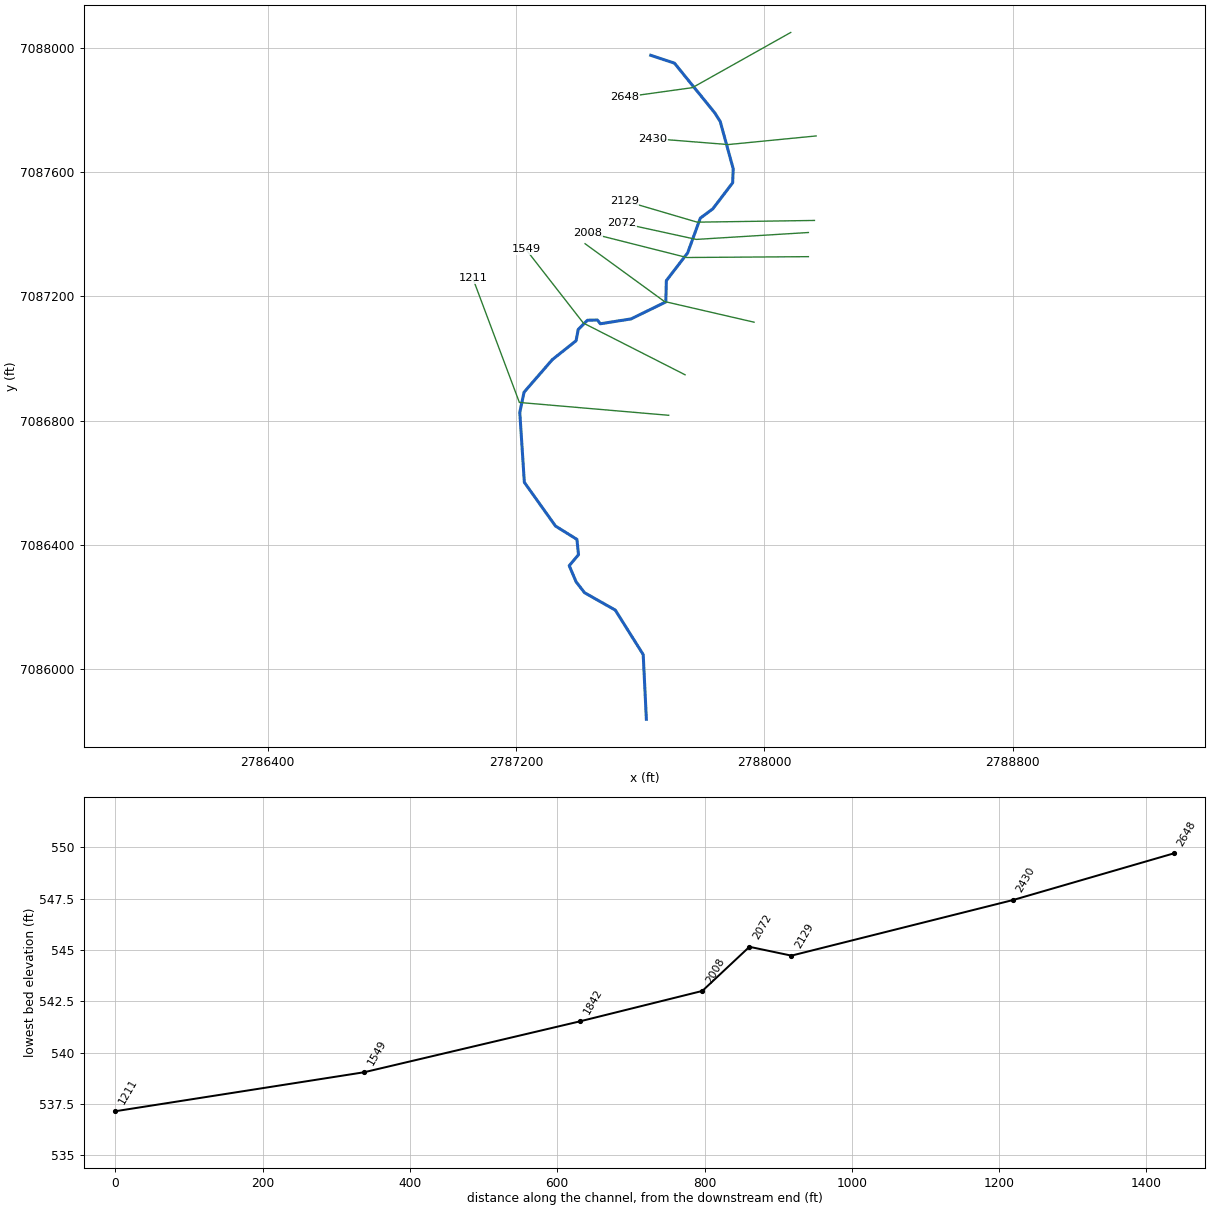
--- UNT 022 in LFCCL Watershed.prj (project) ---

Proj Title=UNT 022 in LFCCL Watershed Base Level Engineering
Current Plan=p01
Default Exp/Contr=0.3,0.1
English Units
Geom File=g01
Flow File=f01
Plan File=p01
BEGIN DESCRIPTION:
UNT 022 in LFCCL Watershed
END DESCRIPTION:

--- UNT 022 in LFCCL Watershed.p01 (plan) ---

Plan Title=Multiple Run
Short Identifier=Multiple
Geom File=g01
Flow File=f01
Subcritical Flow
K Sum by GR= 0
Std Step Tol= 0.01
Critical Tol= 0.01
Num of Std Step Trials= 20
Max Error Tol= 0.3
Flow Tol Ratio= 0.001
Split Flow NTrial= 30
Split Flow Tol= 0.02
Split Flow Ratio= 0.02
Log Output Level= 0
Friction Slope Method= 1
Unsteady Friction Slope Method= 2
Unsteady Bridges Friction Slope Method= 1
Parabolic Critical Depth
Global Vel Dist=  1 , 1 , 1
Global Log Level= 0
CheckData=True
Encroach Param= -1, 0, 0, 0
BEGIN DESCRIPTION:
Multiple Run
END DESCRIPTION:

--- UNT 022 in LFCCL Watershed.f01 (steady flow) ---

Flow Title=Multiple
Number of Profiles=7
Profile Names=10-year,25-year,50-year,1pct_min,100-year,1pct_plu,500-year
River Rch & RM= UNT 022 in LFCCL,Reach-1,2648
     206     253     287     163     324     647     411
Boundary for River Rch & Prof#=UNT 022 in LFCCL,Reach-1,1
Up Type=0
Dn Type=3
Dn Slope=0.005
Boundary for River Rch & Prof#=UNT 022 in LFCCL,Reach-1,2
Up Type=0
Dn Type=3
Dn Slope=0.005
Boundary for River Rch & Prof#=UNT 022 in LFCCL,Reach-1,3
Up Type=0
Dn Type=3
Dn Slope=0.005
Boundary for River Rch & Prof#=UNT 022 in LFCCL,Reach-1,4
Up Type=0
Dn Type=3
Dn Slope=0.005
Boundary for River Rch & Prof#=UNT 022 in LFCCL,Reach-1,5
Up Type=0
Dn Type=3
Dn Slope=0.005
Boundary for River Rch & Prof#=UNT 022 in LFCCL,Reach-1,6
Up Type=0
Dn Type=3
Dn Slope=0.005
Boundary for River Rch & Prof#=UNT 022 in LFCCL,Reach-1,7
Up Type=0
Dn Type=3
Dn Slope=0.005

--- UNT 022 in LFCCL Watershed.g01 (geometry) ---

Geom Title=Existing Conditions

River Reach=UNT 022 in LFCCL,Reach-1
Reach XY= 30
      2787634.20      7087976.42      2787710.59      7087951.24
      2787840.80      7087790.65      2787858.16      7087762.88
      2787899.83      7087610.97      2787898.09      7087565.83
      2787833.85      7087481.63      2787793.92      7087452.11
      2787753.13      7087340.13      2787684.55      7087250.72
      2787682.81      7087182.15      2787570.83      7087127.46
      2787471.88      7087111.83      2787462.33      7087123.99
      2787430.21      7087123.12      2787400.69      7087093.61
      2787393.75      7087057.15      2787317.36      7086996.38
      2787226.22      7086891.35      2787212.50      7086826.42
      2787227.17      7086601.05      2787327.43      7086460.43
      2787396.44      7086417.46      2787401.65      7086367.98
      2787371.70      7086332.82      2787393.84      7086280.74
      2787421.18      7086245.58      2787520.14      7086189.59
      2787609.98      7086046.37      2787620.16      7085838.10

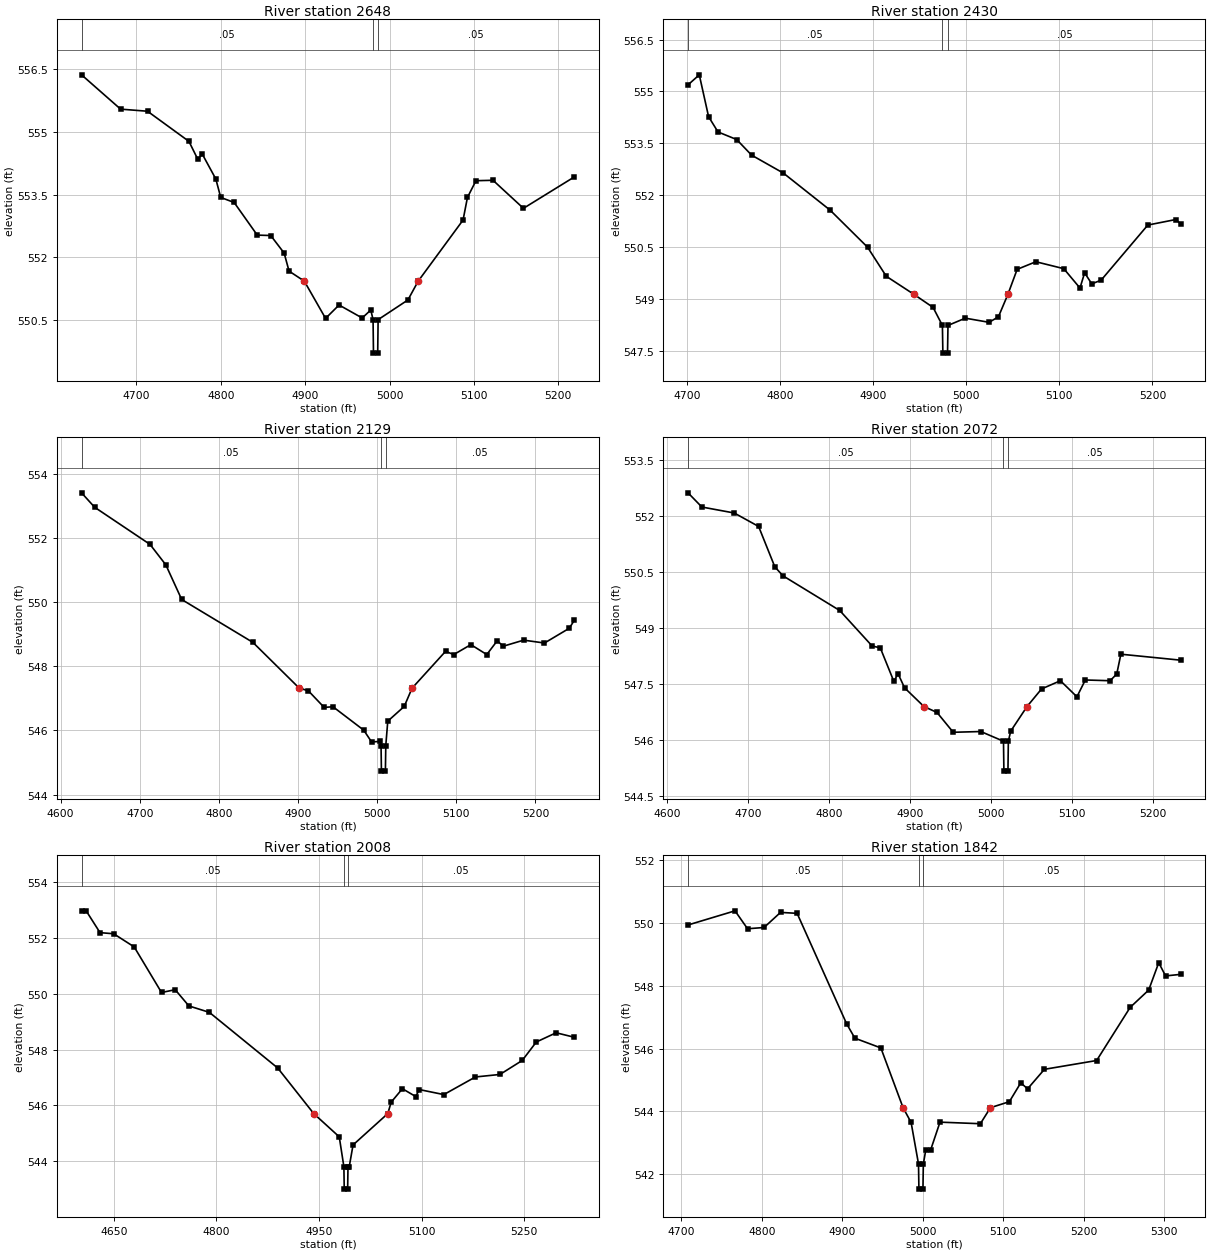
Type RM Length L Ch R = 1,2648,218,218,218
BEGIN DESCRIPTION:
UNT 022 in LFCCL Watershed 2.0
END DESCRIPTION:
XS GIS Cut Line= 3
      2788085.15      7088050.03      2787768.52      7087872.28
      2787549.54      7087841.79
#Sta/Elev= 30
  4634.9  556.36  4681.2  555.54  4713.1  555.49  4762.2  554.77  4772.5  554.35
  4778.2  554.46  4794.1  553.87  4799.9  553.43  4815.8  553.31  4843.2  552.53
  4859.2  552.52  4875.1  552.10  4880.9  551.67  4899.0  551.43  4924.2  550.54
  4940.2  550.86  4967.6  550.55  4977.8  550.74  4980.5  550.51  4981.0  549.71
  4986.0  549.71  4986.5  550.51  5021.8  550.98  5034.0  551.43  5087.2  552.89
  5092.4  553.43  5102.5  553.83  5122.7  553.84  5158.8  553.17  5219.1  553.92
#Mann=3,-1,0
  4634.9    0.05       0  4980.5    0.03       0  4986.5    0.05       0
Bank Sta=4899,5034
Exp/Cntr=0.3,0.1

Type RM Length L Ch R = 1,2430,301,301,301
BEGIN DESCRIPTION:
XS3113A
END DESCRIPTION:
XS GIS Cut Line= 3
      2788167.01      7087716.76      2787883.77      7087688.99
      2787639.74      7087708.41
#Sta/Elev= 30
  4701.0  555.19  4713.1  555.48  4723.1  554.27  4733.2  553.83  4753.3  553.61
  4769.3  553.16  4803.5  552.64  4853.7  551.57  4893.9  550.50  4914.0  549.66
  4943.6  549.14  4964.3  548.76  4974.3  548.24  4974.8  547.44  4979.8  547.44
  4980.3  548.24  4998.9  548.45  5024.5  548.33  5034.5  548.49  5044.7  549.14
  5054.6  549.86  5074.7  550.08  5104.7  549.88  5122.1  549.32  5127.1  549.76
  5134.8  549.44  5144.9  549.55  5195.0  551.14  5225.1  551.30  5230.4  551.17
#Mann=3,-1,0
  4701.0    0.05       0  4974.3    0.03       0  4980.3    0.05       0
Bank Sta=4943.6,5044.7
Exp/Cntr=0.3,0.1

Type RM Length L Ch R = 1,2129,57,57,57
BEGIN DESCRIPTION:
XS3115A
END DESCRIPTION:
XS GIS Cut Line= 3
      2788161.48      7087444.61      2787783.79      7087439.06
      2787548.87      7087508.16
#Sta/Elev= 30
  4626.5  553.42  4643.0  552.97  4713.0  551.81  4733.0  551.17  4753.0  550.09
  4843.0  548.75  4901.6  547.32  4913.0  547.24  4933.0  546.72  4944.2  546.74
  4983.0  546.01  4993.0  545.64  5004.2  545.66  5004.9  545.53  5005.4  544.73
  5010.4  544.73  5010.9  545.53  5013.4  546.29  5034.2  546.75  5044.1  547.32
  5086.4  548.47  5096.8  548.37  5118.4  548.68  5138.5  548.37  5151.7  548.80
  5159.3  548.63  5185.1  548.82  5211.4  548.73  5242.7  549.19  5249.1  549.44
#Mann=3,-1,0
  4626.5    0.05       0  5004.9    0.03       0  5010.9    0.05       0
Bank Sta=4901.6,5044.1
Exp/Cntr=0.3,0.1

Type RM Length L Ch R = 1,2072,64,64,64
BEGIN DESCRIPTION:
XS3114A
END DESCRIPTION:
XS GIS Cut Line= 3
      2788142.02      7087405.74      2787781.02      7087383.52
      2787539.69      7087436.22
#Sta/Elev= 30
  4625.5  552.61  4642.6  552.23  4682.6  552.07  4712.7  551.71  4732.7  550.63
  4742.7  550.39  4812.9  549.46  4852.9  548.51  4863.0  548.46  4879.8  547.56
  4884.9  547.77  4893.0  547.39  4916.9  546.89  4933.1  546.73  4953.1  546.20
  4987.2  546.22  5015.2  545.96  5015.7  545.16  5020.7  545.16  5021.2  545.96
  5024.1  546.23  5044.3  546.89  5062.2  547.36  5085.5  547.58  5105.9  547.15
  5116.3  547.60  5146.9  547.58  5155.1  547.76  5160.2  548.29  5234.2  548.13
#Mann=3,-1,0
  4625.5    0.05       0  5015.2    0.03       0  5021.2    0.05       0
Bank Sta=4916.9,5044.3
Exp/Cntr=0.3,0.1

Type RM Length L Ch R = 1,2008,166,166,166
BEGIN DESCRIPTION:
XS3116A
END DESCRIPTION:
XS GIS Cut Line= 3
      2788142.03      7087327.98      2787750.47      7087325.20
      2787431.13      7087405.73
#Sta/Elev= 30
  4602.6  552.96  4609.6  552.95  4629.6  552.18  4649.6  552.14  4679.6  551.67
  4719.6  550.04  4739.6  550.14  4759.6  549.56  4789.6  549.33  4889.6  547.34
  4942.3  545.71  4979.6  544.88  4986.4  543.81  4986.9  543.01  4991.9  543.01
  4992.4  543.81  4994.2  543.81  4999.8  544.59  5050.6  545.71  5055.6  546.12
  5072.0  546.60  5091.5  546.32  5096.7  546.57  5132.6  546.39  5178.8  547.02
  5214.7  547.11  5247.3  547.61  5267.9  548.27  5296.9  548.60  5323.5  548.44
#Mann=3,-1,0
  4602.6    0.05       0  4986.4    0.03       0  4992.4    0.05       0
Bank Sta=4942.3,5050.6
Exp/Cntr=0.3,0.1

Type RM Length L Ch R = 1,1842,293,293,293
BEGIN DESCRIPTION:
XS3117A
END DESCRIPTION:
XS GIS Cut Line= 3
      2787967.08      7087116.92      2787678.27      7087183.57
      2787422.75      7087369.65
#Sta/Elev= 30
  4708.3  549.93  4766.7  550.38  4782.3  549.81  4802.8  549.85  4823.3  550.33
  4843.9  550.30  4905.4  546.79  4915.7  546.33  4948.0  546.02  4975.6  544.12
  4985.6  543.65  4994.8  542.33  4995.3  541.53  5000.3  541.53  5000.8  542.33
  5003.8  542.77  5009.8  542.77  5021.5  543.66  5071.7  543.61  5084.2  544.12
  5107.7  544.31  5121.9  544.91  5130.4  544.72  5151.3  545.34  5216.2  545.62
  5257.9  547.31  5280.9  547.86  5293.4  548.73  5301.9  548.31  5320.8  548.36
#Mann=3,-1,0
  4708.3    0.05       0  4994.8    0.03       0  5000.8    0.05       0
Bank Sta=4975.6,5084.2
Exp/Cntr=0.3,0.1

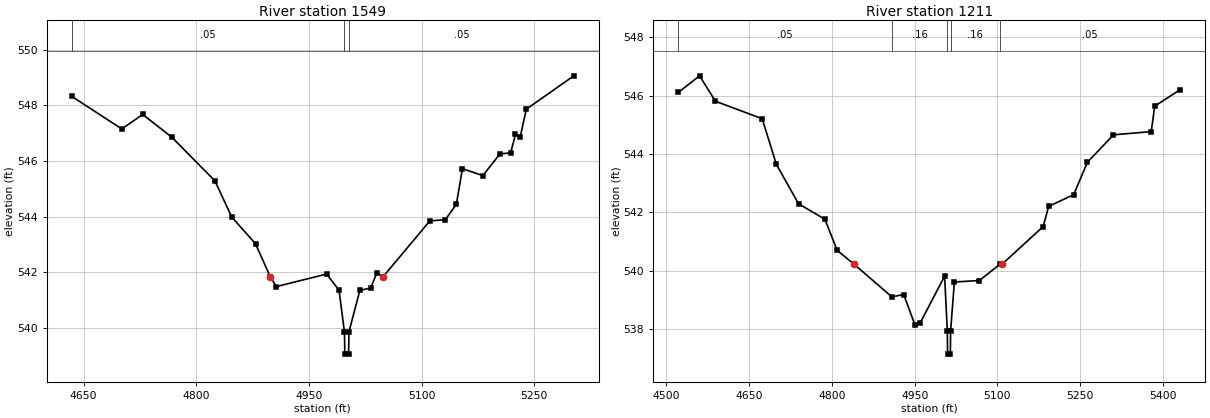
Type RM Length L Ch R = 1,1549,338,338,338
BEGIN DESCRIPTION:
XS3118A
END DESCRIPTION:
XS GIS Cut Line= 3
      2787744.87      7086947.55      2787417.22      7087114.15
      2787232.34      7087351.46
#Sta/Elev= 30
  4634.2  548.32  4700.8  547.15  4728.6  547.67  4767.5  546.85  4824.8  545.28
  4847.2  543.98  4878.8  543.02  4898.3  541.84  4906.6  541.48  4973.4  541.93
  4990.0  541.35  4997.2  539.85  4997.7  539.05  5002.7  539.05  5003.2  539.85
  5017.7  541.34  5032.2  541.43  5040.3  541.97  5048.8  541.84  5110.9  543.84
  5131.7  543.89  5146.2  544.44  5154.3  545.72  5181.5  545.47  5204.1  546.25
  5218.4  546.29  5224.9  546.95  5231.2  546.86  5239.3  547.86  5302.6  549.06
#Mann=3,-1,0
  4634.2    0.05       0  4997.2    0.03       0  5003.2    0.05       0
Bank Sta=4898.3,5048.8
Exp/Cntr=0.3,0.1

Type RM Length L Ch R = 1,1211,0,0,0
BEGIN DESCRIPTION:
UNT 022 in LFCCL Watershed 1.0
END DESCRIPTION:
XS GIS Cut Line= 3
      2787692.18      7086817.00      2787211.18      7086858.40
      2787061.17      7087258.42
#Sta/Elev= 30
  4521.5  546.11  4560.2  546.68  4588.9  545.81  4673.7  545.21  4699.3  543.65
  4739.5  542.30  4787.2  541.77  4809.7  540.70  4840.7  540.22  4908.7  539.11
  4930.2  539.19  4950.3  538.16  4960.3  538.23  5004.3  539.82  5009.2  537.95
  5009.7  537.15  5014.7  537.15  5015.2  537.95  5022.0  539.62  5067.3  539.67
  5104.6  540.23  5107.9  540.22  5183.0  541.52  5192.9  542.21  5238.2  542.61
  5263.1  543.72  5310.4  544.66  5378.8  544.77  5385.1  545.64  5431.5  546.21
#Mann=5,-1,0
  4521.5    0.05       0  4908.7    0.16       0  5009.2    0.07       0
  5015.2    0.16       0  5104.6    0.05       0
Bank Sta=4840.7,5107.9
Exp/Cntr=0.3,0.1

Chan Stop Cuts=-1