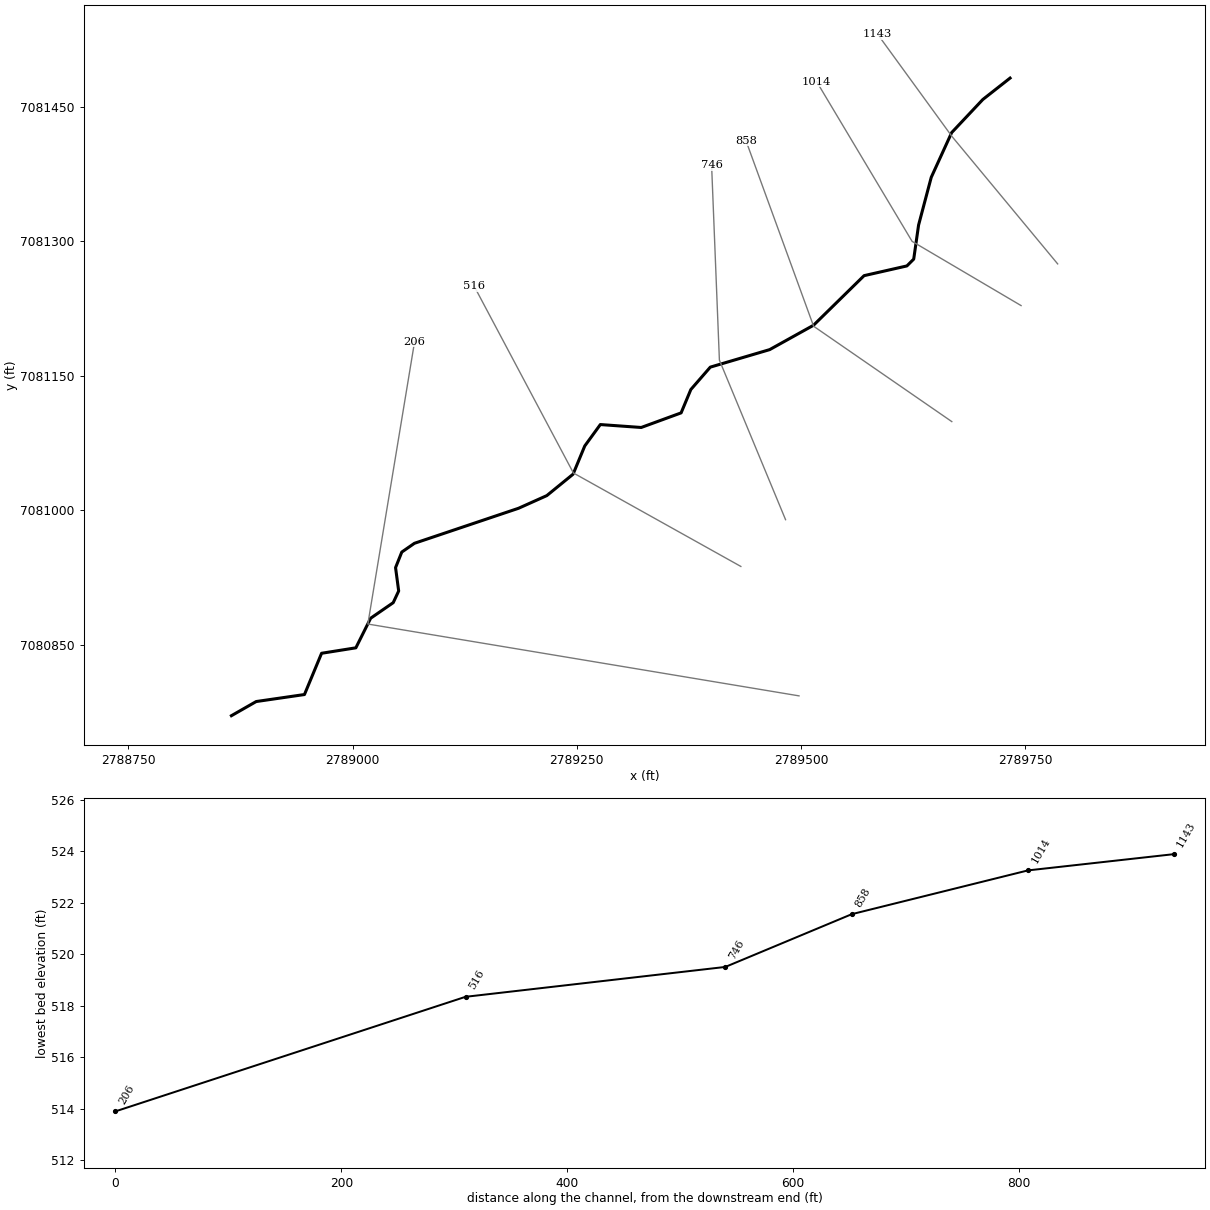
--- UNT 023 in LFCCL Watershed.prj (project) ---

Proj Title=UNT 023 in LFCCL Watershed Base Level Engineering
Current Plan=p01
Default Exp/Contr=0.3,0.1
English Units
Geom File=g01
Flow File=f01
Plan File=p01
BEGIN DESCRIPTION:
UNT 023 in LFCCL Watershed
END DESCRIPTION:

--- UNT 023 in LFCCL Watershed.p01 (plan) ---

Plan Title=Multiple Run
Short Identifier=Multiple
Geom File=g01
Flow File=f01
Subcritical Flow
K Sum by GR= 0
Std Step Tol= 0.01
Critical Tol= 0.01
Num of Std Step Trials= 20
Max Error Tol= 0.3
Flow Tol Ratio= 0.001
Split Flow NTrial= 30
Split Flow Tol= 0.02
Split Flow Ratio= 0.02
Log Output Level= 0
Friction Slope Method= 1
Unsteady Friction Slope Method= 2
Unsteady Bridges Friction Slope Method= 1
Parabolic Critical Depth
Global Vel Dist=  1 , 1 , 1
Global Log Level= 0
CheckData=True
Encroach Param= -1, 0, 0, 0
BEGIN DESCRIPTION:
Multiple Run
END DESCRIPTION:

--- UNT 023 in LFCCL Watershed.f01 (steady flow) ---

Flow Title=Multiple
Number of Profiles=7
Profile Names=10-year,25-year,50-year,1pct_min,100-year,1pct_plu,500-year
River Rch & RM= UNT 023 in LFCCL,Reach-1,1143
     113     132     146      81     161     321     193
Boundary for River Rch & Prof#=UNT 023 in LFCCL,Reach-1,1
Up Type=0
Dn Type=3
Dn Slope=0.005
Boundary for River Rch & Prof#=UNT 023 in LFCCL,Reach-1,2
Up Type=0
Dn Type=3
Dn Slope=0.005
Boundary for River Rch & Prof#=UNT 023 in LFCCL,Reach-1,3
Up Type=0
Dn Type=3
Dn Slope=0.005
Boundary for River Rch & Prof#=UNT 023 in LFCCL,Reach-1,4
Up Type=0
Dn Type=3
Dn Slope=0.005
Boundary for River Rch & Prof#=UNT 023 in LFCCL,Reach-1,5
Up Type=0
Dn Type=3
Dn Slope=0.005
Boundary for River Rch & Prof#=UNT 023 in LFCCL,Reach-1,6
Up Type=0
Dn Type=3
Dn Slope=0.005
Boundary for River Rch & Prof#=UNT 023 in LFCCL,Reach-1,7
Up Type=0
Dn Type=3
Dn Slope=0.005

--- UNT 023 in LFCCL Watershed.g01 (geometry) ---

Geom Title=Existing Conditions

River Reach=UNT 023 in LFCCL,Reach-1
Reach XY= 30
      2789733.01      7081481.82      2789702.63      7081457.95
      2789667.91      7081421.06      2789645.12      7081371.15
      2789631.01      7081317.98      2789625.59      7081280.00
      2789617.99      7081272.40      2789570.25      7081261.55
      2789513.83      7081206.22      2789465.00      7081179.09
      2789398.81      7081159.56      2789377.11      7081134.60
      2789366.26      7081108.56      2789321.77      7081092.28
      2789276.20      7081095.54      2789258.83      7081071.67
      2789245.81      7081040.20      2789216.52      7081016.33
      2789185.05      7081002.22      2789068.95      7080963.16
      2789054.84      7080953.39      2789047.90      7080936.03
      2789051.37      7080909.99      2789045.29      7080896.97
      2789020.12      7080879.61      2789003.63      7080846.62
      2788965.43      7080840.55      2788946.33      7080794.54
      2788892.51      7080786.73      2788864.89      7080770.94

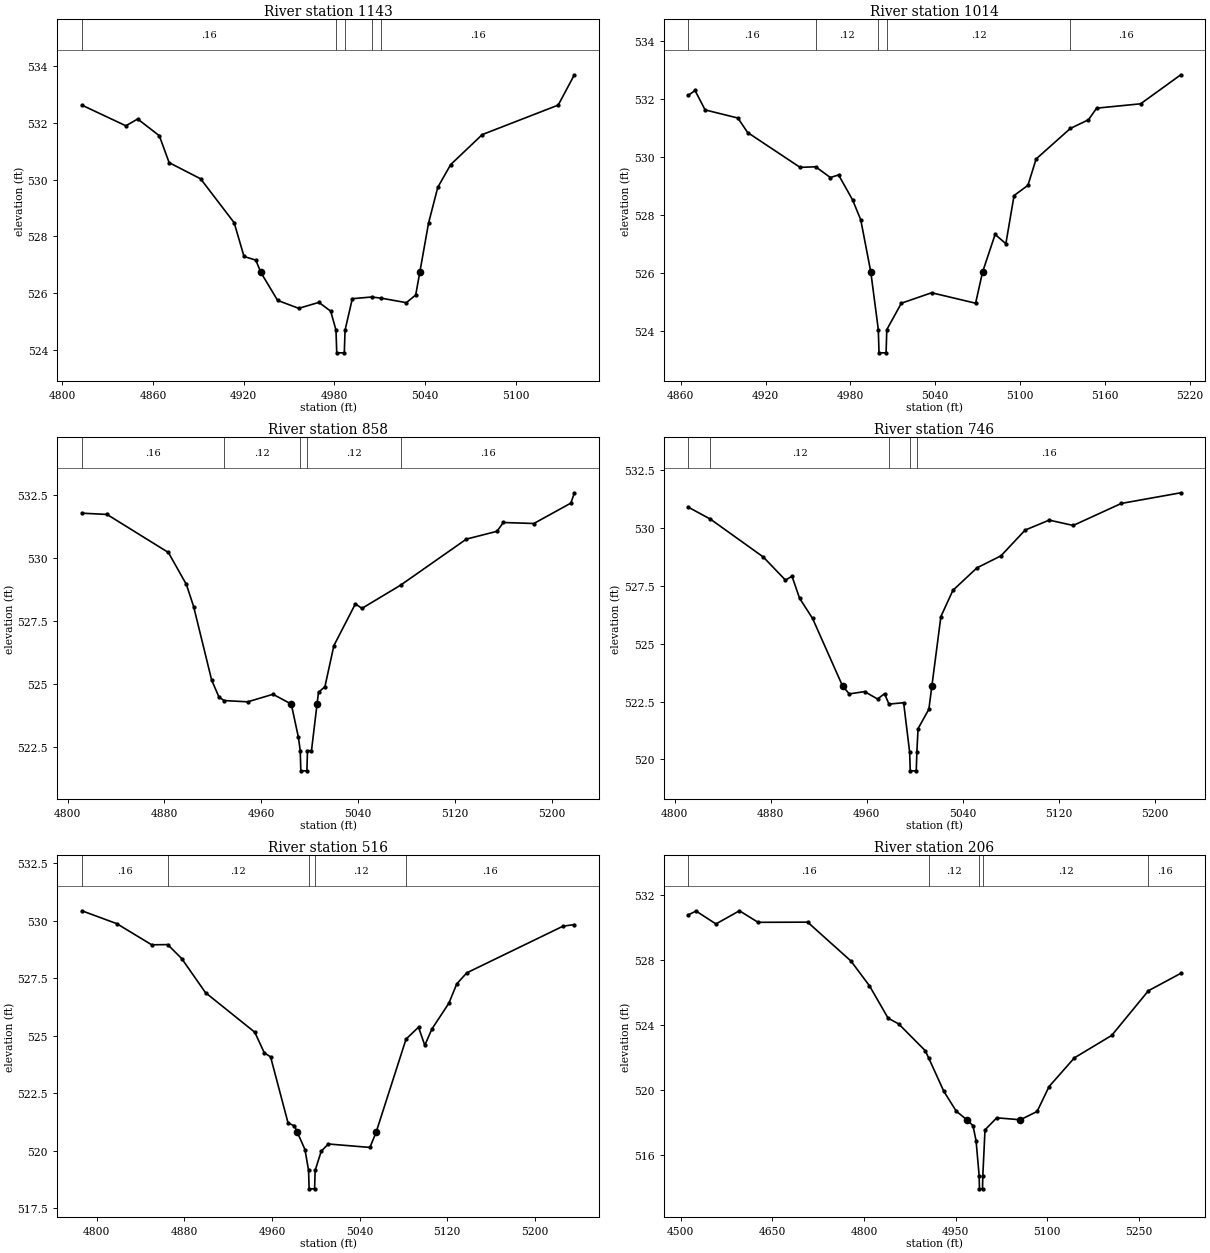
Type RM Length L Ch R = 1,1143,129,129,129
BEGIN DESCRIPTION:
UNT 023 in LFCCL Watershed 1.0
END DESCRIPTION:
XS GIS Cut Line= 3
      2789786.08      7081274.65      2789668.05      7081416.98
      2789585.29      7081530.77
#Sta/Elev= 30
  4813.0  532.63  4842.1  531.90  4849.9  532.14  4864.2  531.55  4870.7  530.60
  4891.5  530.03  4913.7  528.48  4920.2  527.29  4928.0  527.16  4931.3  526.73
  4942.4  525.74  4956.4  525.46  4969.7  525.67  4977.5  525.36  4981.0  524.69
  4981.5  523.89  4986.5  523.89  4987.0  524.69  4991.8  525.80  5004.5  525.86
  5010.8  525.82  5027.5  525.66  5033.7  525.93  5036.4  526.73  5042.2  528.47
  5048.3  529.73  5056.8  530.53  5077.7  531.59  5127.9  532.63  5138.6  533.70
#Mann=5,-1,0
  4813.0    0.16       0  4981.0    0.07       0  4987.0    0.16       0
  5004.5    0.12       0  5010.8    0.16       0
Bank Sta=4931.3,5036.4
Exp/Cntr=0.3,0.1

Type RM Length L Ch R = 1,1014,156,156,156
BEGIN DESCRIPTION:
XS3122A
END DESCRIPTION:
XS GIS Cut Line= 3
      2789745.28      7081228.19      2789623.78      7081299.79
      2789517.46      7081477.72
#Sta/Elev= 30
  4865.3  532.13  4870.1  532.30  4877.2  531.63  4900.4  531.35  4907.3  530.85
  4944.4  529.65  4955.4  529.67  4965.8  529.30  4971.6  529.39  4981.5  528.53
  4987.3  527.84  4994.4  526.04  4999.7  524.06  5000.2  523.26  5005.2  523.26
  5005.7  524.06  5016.0  524.97  5037.4  525.33  5068.5  524.97  5073.4  526.04
  5082.3  527.34  5089.9  527.02  5095.7  528.68  5105.5  529.03  5111.3  529.94
  5135.5  530.99  5148.3  531.29  5154.1  531.69  5185.2  531.84  5213.6  532.84
#Mann=5,-1,0
  4865.3    0.16       0  4955.4    0.12       0  4999.7    0.07       0
  5005.7    0.12       0  5135.5    0.16       0
Bank Sta=4994.4,5073.4
Exp/Cntr=0.3,0.1

Type RM Length L Ch R = 1,858,112,112,112
BEGIN DESCRIPTION:
XS3119A
END DESCRIPTION:
XS GIS Cut Line= 3
      2789668.04      7081098.84      2789513.97      7081205.17
      2789438.65      7081411.77
#Sta/Elev= 30
  4811.8  531.79  4832.6  531.74  4883.3  530.23  4898.2  528.96  4904.2  528.08
  4919.1  525.16  4925.2  524.48  4929.5  524.35  4948.9  524.30  4969.8  524.60
  4984.9  524.21  4990.8  522.89  4992.3  522.36  4992.8  521.56  4997.8  521.56
  4998.3  522.36  5001.6  522.36  5006.2  524.21  5007.4  524.68  5012.7  524.90
  5020.1  526.53  5037.9  528.19  5043.3  528.01  5075.2  528.93  5129.6  530.76
  5154.9  531.07  5160.2  531.42  5185.4  531.38  5216.0  532.19  5218.9  532.60
#Mann=5,-1,0
  4811.8    0.16       0  4929.5    0.12       0  4992.3    0.07       0
  4998.3    0.12       0  5075.2    0.16       0
Bank Sta=4984.9,5006.2
Exp/Cntr=0.3,0.1

Type RM Length L Ch R = 1,746,230,230,230
BEGIN DESCRIPTION:
XS3120A
END DESCRIPTION:
XS GIS Cut Line= 3
      2789482.70      7080989.50      2789408.94      7081167.41
      2789400.26      7081384.44
#Sta/Elev= 30
  4811.4  530.89  4829.9  530.37  4873.8  528.74  4892.3  527.74  4897.7  527.91
  4904.0  526.96  4914.8  526.09  4939.8  523.17  4945.4  522.83  4958.1  522.93
  4968.9  522.61  4974.7  522.84  4978.4  522.39  4990.6  522.45  4995.6  520.31
  4996.1  519.51  5001.1  519.51  5001.6  520.31  5002.6  521.33  5011.6  522.17
  5014.1  523.17  5021.6  526.17  5031.6  527.30  5051.6  528.27  5071.6  528.79
  5091.7  529.90  5111.7  530.33  5131.7  530.10  5171.7  531.05  5221.2  531.51
#Mann=5,-1,0
  4811.4    0.16       0  4829.9    0.12       0  4978.4    0.16       0
  4995.6    0.07       0  5001.6    0.16       0
Bank Sta=4939.8,5014.1
Exp/Cntr=0.3,0.1

Type RM Length L Ch R = 1,516,310,310,310
BEGIN DESCRIPTION:
XS3121A
END DESCRIPTION:
XS GIS Cut Line= 3
      2789432.85      7080937.36      2789246.18      7081041.54
      2789135.49      7081249.89
#Sta/Elev= 30
  4786.4  530.44  4818.3  529.88  4850.2  528.96  4864.8  528.97  4877.6  528.36
  4899.3  526.88  4944.3  525.16  4953.0  524.26  4958.7  524.09  4974.7  521.21
  4980.4  521.09  4983.2  520.80  4990.1  520.06  4993.4  519.15  4993.9  518.35
  4998.9  518.35  4999.4  519.15  5005.0  519.99  5011.5  520.30  5049.4  520.15
  5055.0  520.80  5082.4  524.86  5093.8  525.38  5099.5  524.59  5106.0  525.30
  5121.5  526.42  5128.7  527.26  5137.8  527.74  5225.7  529.77  5236.1  529.84
#Mann=5,-1,0
  4786.4    0.16       0  4864.8    0.12       0  4993.4    0.07       0
  4999.4    0.12       0  5082.4    0.16       0
Bank Sta=4983.2,5055
Exp/Cntr=0.3,0.1

Type RM Length L Ch R = 1,206,0,0,0
BEGIN DESCRIPTION:
UNT 023 in LFCCL Watershed 0.0
END DESCRIPTION:
XS GIS Cut Line= 3
      2789497.71      7080793.06      2789017.01      7080873.14
      2789069.10      7081187.84
#Sta/Elev= 30
  4512.3  530.76  4525.2  530.99  4557.6  530.20  4596.1  531.01  4626.6  530.30
  4707.7  530.31  4778.6  527.92  4809.0  526.39  4839.5  524.40  4856.7  524.05
  4900.3  522.40  4905.9  521.95  4930.7  519.90  4951.0  518.68  4968.3  518.15
  4978.4  517.79  4983.5  516.85  4988.5  514.70  4989.0  513.90  4994.0  513.90
  4994.5  514.70  4998.1  517.53  5017.3  518.27  5055.9  518.15  5083.4  518.66
  5102.9  520.19  5144.4  521.96  5205.5  523.34  5265.6  526.09  5318.6  527.16
#Mann=5,-1,0
  4512.3    0.16       0  4905.9    0.12       0  4988.5    0.07       0
  4994.5    0.12       0  5265.6    0.16       0
Bank Sta=4968.3,5055.9
Exp/Cntr=0.3,0.1

Chan Stop Cuts=-1