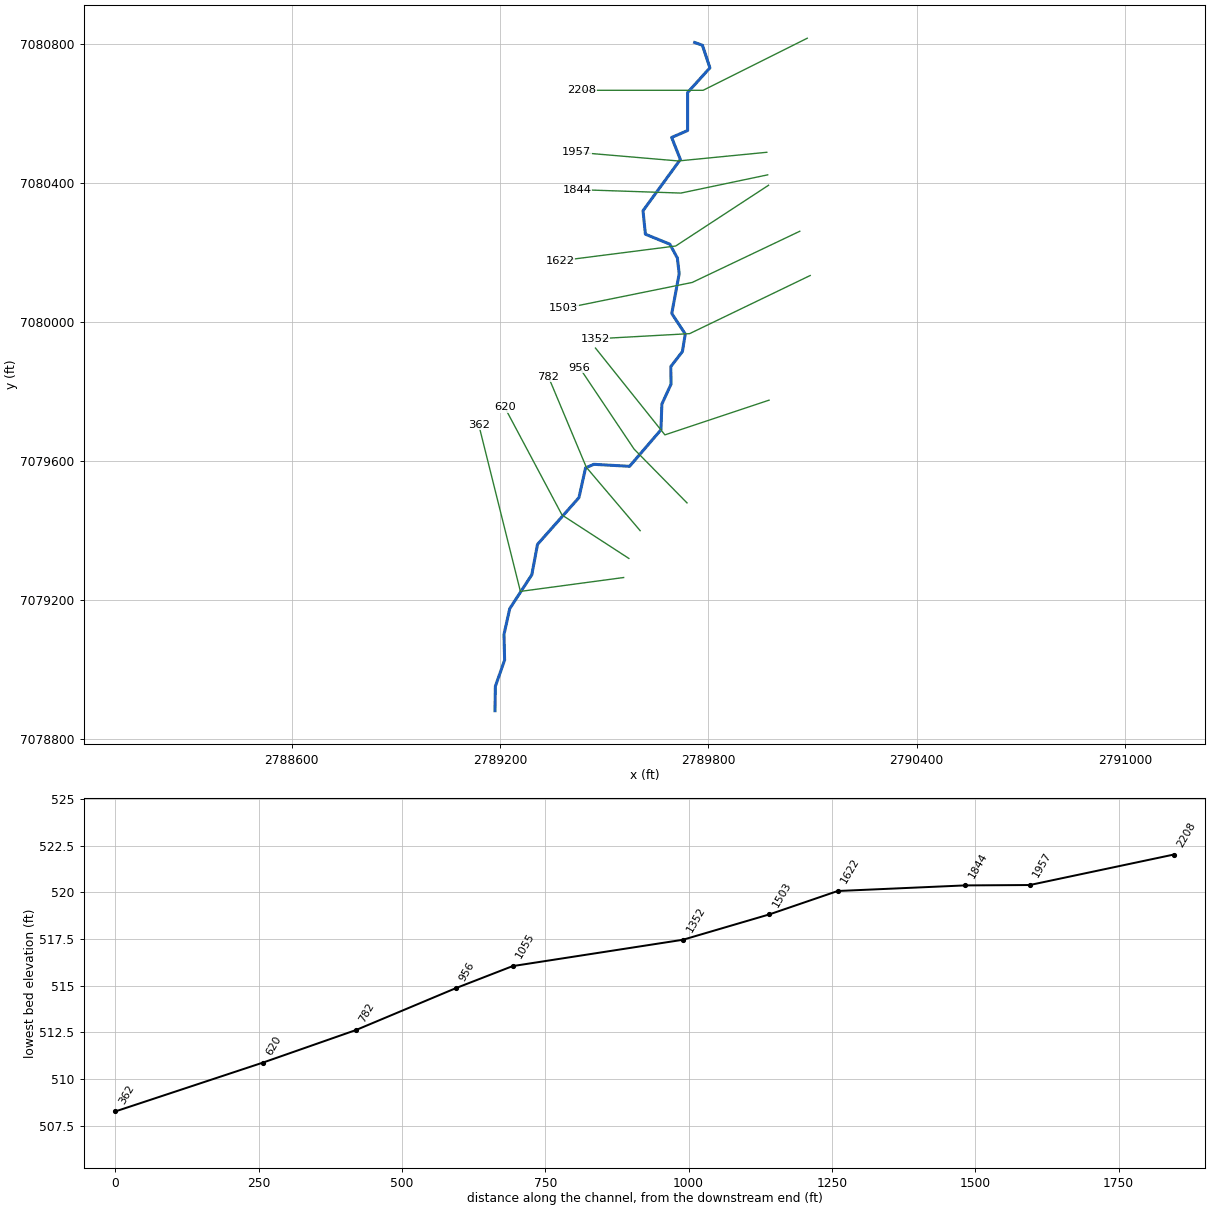
--- UNT 024 in LFCCL Watershed.prj (project) ---

Proj Title=UNT 024 in LFCCL Watershed Base Level Engineering
Current Plan=p01
Default Exp/Contr=0.3,0.1
English Units
Geom File=g01
Flow File=f01
Plan File=p01
BEGIN DESCRIPTION:
UNT 024 in LFCCL Watershed
END DESCRIPTION:

--- UNT 024 in LFCCL Watershed.p01 (plan) ---

Plan Title=Multiple Run
Short Identifier=Multiple
Geom File=g01
Flow File=f01
Subcritical Flow
K Sum by GR= 0
Std Step Tol= 0.01
Critical Tol= 0.01
Num of Std Step Trials= 20
Max Error Tol= 0.3
Flow Tol Ratio= 0.001
Split Flow NTrial= 30
Split Flow Tol= 0.02
Split Flow Ratio= 0.02
Log Output Level= 0
Friction Slope Method= 1
Unsteady Friction Slope Method= 2
Unsteady Bridges Friction Slope Method= 1
Parabolic Critical Depth
Global Vel Dist=  1 , 1 , 1
Global Log Level= 0
CheckData=True
Encroach Param= -1, 0, 0, 0
BEGIN DESCRIPTION:
Multiple Run
END DESCRIPTION:

--- UNT 024 in LFCCL Watershed.f01 (steady flow) ---

Flow Title=Multiple
Number of Profiles=7
Profile Names=10-year,25-year,50-year,1pct_min,100-year,1pct_plu,500-year
River Rch & RM= UNT 024 in LFCCL,Reach-1,2208
     167     202     227     128     255     508     317
Boundary for River Rch & Prof#=UNT 024 in LFCCL,Reach-1,1
Up Type=0
Dn Type=3
Dn Slope=0.005
Boundary for River Rch & Prof#=UNT 024 in LFCCL,Reach-1,2
Up Type=0
Dn Type=3
Dn Slope=0.005
Boundary for River Rch & Prof#=UNT 024 in LFCCL,Reach-1,3
Up Type=0
Dn Type=3
Dn Slope=0.005
Boundary for River Rch & Prof#=UNT 024 in LFCCL,Reach-1,4
Up Type=0
Dn Type=3
Dn Slope=0.005
Boundary for River Rch & Prof#=UNT 024 in LFCCL,Reach-1,5
Up Type=0
Dn Type=3
Dn Slope=0.005
Boundary for River Rch & Prof#=UNT 024 in LFCCL,Reach-1,6
Up Type=0
Dn Type=3
Dn Slope=0.005
Boundary for River Rch & Prof#=UNT 024 in LFCCL,Reach-1,7
Up Type=0
Dn Type=3
Dn Slope=0.005

--- UNT 024 in LFCCL Watershed.g01 (geometry) ---

Geom Title=Existing Conditions

River Reach=UNT 024 in LFCCL,Reach-1
Reach XY= 30
      2789760.62      7080804.87      2789782.90      7080797.06
      2789804.60      7080731.96      2789740.36      7080660.78
      2789740.36      7080551.40      2789694.35      7080531.44
      2789719.53      7080468.07      2789611.89      7080320.50
      2789618.83      7080252.79      2789689.15      7080224.15
      2789710.85      7080184.21      2789716.06      7080139.08
      2789694.70      7080024.49      2789733.59      7079965.46
      2789725.26      7079914.77      2789691.92      7079871.71
      2789692.62      7079821.02      2789666.24      7079763.82
      2789663.47      7079689.52      2789573.16      7079584.50
      2789470.26      7079590.25      2789446.48      7079580.09
      2789427.37      7079494.37      2789308.01      7079359.71
      2789291.64      7079272.34      2789228.04      7079174.63
      2789211.53      7079100.67      2789213.29      7079026.57
      2789186.64      7078950.89      2789185.59      7078880.71

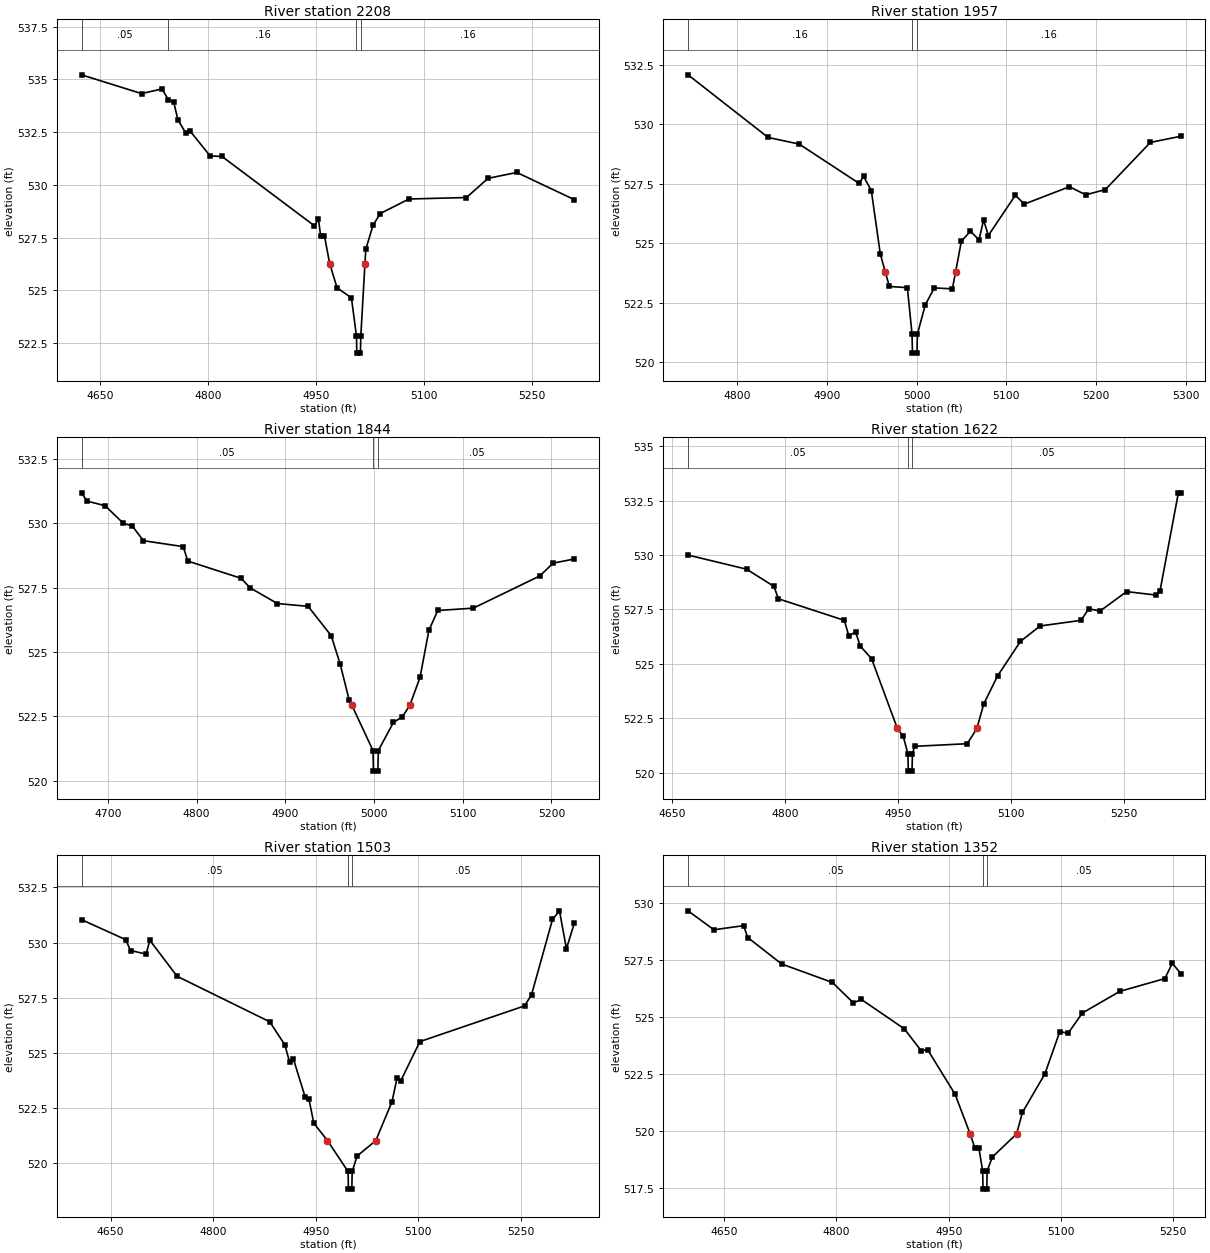
Type RM Length L Ch R = 1,2208,251,251,251
BEGIN DESCRIPTION:
UNT 024 in LFCCL Watershed 3.0
END DESCRIPTION:
XS GIS Cut Line= 3
      2790084.97      7080817.22      2789784.97      7080667.22
      2789434.98      7080667.22
#Sta/Elev= 30
  4623.9  535.22  4707.4  534.33  4735.7  534.55  4744.7  534.04  4752.1  533.93
  4758.0  533.08  4768.9  532.46  4774.5  532.57  4802.8  531.37  4819.2  531.35
  4947.8  528.06  4953.4  528.38  4956.5  527.57  4961.8  527.57  4969.0  526.27
  4979.3  525.12  4999.3  524.64  5006.3  522.82  5006.8  522.02  5011.8  522.02
  5012.3  522.82  5018.1  526.27  5019.3  526.95  5029.3  528.08  5039.3  528.64
  5079.3  529.33  5159.3  529.40  5189.3  530.31  5229.3  530.59  5309.3  529.30
#Mann=4,-1,0
  4623.9    0.05       0  4744.7    0.16       0  5006.3    0.07       0
  5012.3    0.16       0
Bank Sta=4969,5018.1
Exp/Cntr=0.3,0.1

Type RM Length L Ch R = 1,1957,113,113,113
BEGIN DESCRIPTION:
XS3123A
END DESCRIPTION:
XS GIS Cut Line= 3
      2789968.42      7080488.76      2789713.57      7080463.77
      2789421.21      7080488.76
#Sta/Elev= 30
  4745.2  532.08  4834.5  529.45  4869.2  529.17  4936.0  527.52  4941.0  527.81
  4949.6  527.22  4959.6  524.56  4965.3  523.78  4969.7  523.19  4989.8  523.14
  4995.0  521.19  4995.5  520.39  5000.5  520.39  5001.0  521.19  5009.9  522.43
  5019.9  523.13  5040.0  523.09  5043.5  523.78  5050.0  525.09  5060.1  525.51
  5069.7  525.15  5074.8  525.98  5080.1  525.33  5110.2  527.02  5120.3  526.65
  5170.5  527.38  5188.7  527.04  5210.6  527.26  5260.8  529.24  5294.7  529.50
#Mann=3,-1,0
  4745.2    0.16       0  4995.0    0.07       0  5001.0    0.16       0
Bank Sta=4965.3,5043.5
Exp/Cntr=0.3,0.1

Type RM Length L Ch R = 1,1844,222,222,222
BEGIN DESCRIPTION:
XS3124A
END DESCRIPTION:
XS GIS Cut Line= 3
      2789970.98      7080423.79      2789721.06      7080371.31
      2789421.19      7080381.31
#Sta/Elev= 30
  4670.4  531.18  4676.5  530.86  4696.9  530.68  4717.4  530.00  4727.6  529.89
  4740.2  529.32  4785.0  529.09  4790.1  528.53  4850.2  527.86  4860.4  527.49
  4891.1  526.88  4925.8  526.77  4951.8  525.63  4961.8  524.54  4971.9  523.15
  4975.2  522.92  4998.9  521.17  4999.4  520.37  5004.4  520.37  5004.9  521.17
  5021.9  522.26  5031.9  522.48  5040.3  522.92  5051.9  524.01  5061.9  525.84
  5071.9  526.61  5111.9  526.70  5186.8  527.95  5202.0  528.45  5225.8  528.61
#Mann=3,-1,0
  4670.4    0.05       0  4998.9    0.03       0  5004.9    0.05       0
Bank Sta=4975.2,5040.3
Exp/Cntr=0.3,0.1

Type RM Length L Ch R = 1,1622,119,119,119
BEGIN DESCRIPTION:
XS3125A
END DESCRIPTION:
XS GIS Cut Line= 3
      2789973.46      7080393.81      2789706.07      7080218.88
      2789373.70      7080176.40
#Sta/Elev= 30
  4671.1  530.00  4749.0  529.35  4785.2  528.56  4791.2  527.99  4878.7  527.00
  4884.7  526.29  4893.8  526.46  4899.8  525.82  4914.9  525.24  4949.2  522.03
  4957.0  521.67  4963.2  520.87  4963.7  520.07  4968.7  520.07  4969.2  520.87
  4972.1  521.21  5042.1  521.33  5054.8  522.03  5064.0  523.16  5082.4  524.45
  5112.7  526.03  5138.7  526.74  5193.3  527.00  5203.4  527.53  5218.5  527.43
  5253.8  528.32  5293.2  528.16  5298.2  528.37  5322.5  532.86  5325.7  532.86
#Mann=3,-1,0
  4671.1    0.05       0  4963.2    0.03       0  4969.2    0.05       0
Bank Sta=4949.2,5054.8
Exp/Cntr=0.3,0.1

Type RM Length L Ch R = 1,1503,151,151,151
BEGIN DESCRIPTION:
XS3126A
END DESCRIPTION:
XS GIS Cut Line= 3
      2790063.42      7080261.36      2789753.55      7080113.92
      2789383.73      7080038.96
#Sta/Elev= 30
  4607.5  531.04  4672.2  530.13  4679.1  529.64  4701.8  529.48  4707.4  530.10
  4747.3  528.47  4882.6  526.41  4904.8  525.36  4911.8  524.57  4917.3  524.72
  4934.5  522.99  4940.0  522.90  4947.1  521.81  4967.1  521.02  4997.2  519.62
  4997.7  518.82  5002.7  518.82  5003.2  519.62  5010.4  520.32  5037.7  521.02
  5061.4  522.78  5068.8  523.86  5073.9  523.71  5102.2  525.51  5255.3  527.13
  5265.5  527.64  5296.1  531.05  5306.3  531.44  5316.5  529.72  5328.0  530.88
#Mann=3,-1,0
  4607.5    0.05       0  4997.2    0.03       0  5003.2    0.05       0
Bank Sta=4967.1,5037.7
Exp/Cntr=0.3,0.1

Type RM Length L Ch R = 1,1352,297,297,297
BEGIN DESCRIPTION:
XS3127A
END DESCRIPTION:
XS GIS Cut Line= 3
      2790093.42      7080133.93      2789746.05      7079966.49
      2789473.68      7079951.49
#Sta/Elev= 30
  4601.7  529.66  4636.3  528.83  4676.0  529.01  4681.5  528.49  4726.8  527.33
  4794.6  526.52  4822.8  525.62  4833.1  525.78  4890.6  524.49  4913.2  523.53
  4921.9  523.57  4958.5  521.62  4978.7  519.88  4985.1  519.25  4990.4  519.25
  4995.4  518.26  4995.9  517.46  5000.9  517.46  5001.4  518.26  5008.4  518.87
  5040.7  519.88  5048.5  520.82  5078.5  522.51  5098.5  524.37  5109.5  524.29
  5128.6  525.18  5178.7  526.13  5238.8  526.69  5248.8  527.36  5260.1  526.91
#Mann=3,-1,0
  4601.7    0.05       0  4995.4    0.03       0  5001.4    0.05       0
Bank Sta=4978.7,5040.7
Exp/Cntr=0.3,0.1

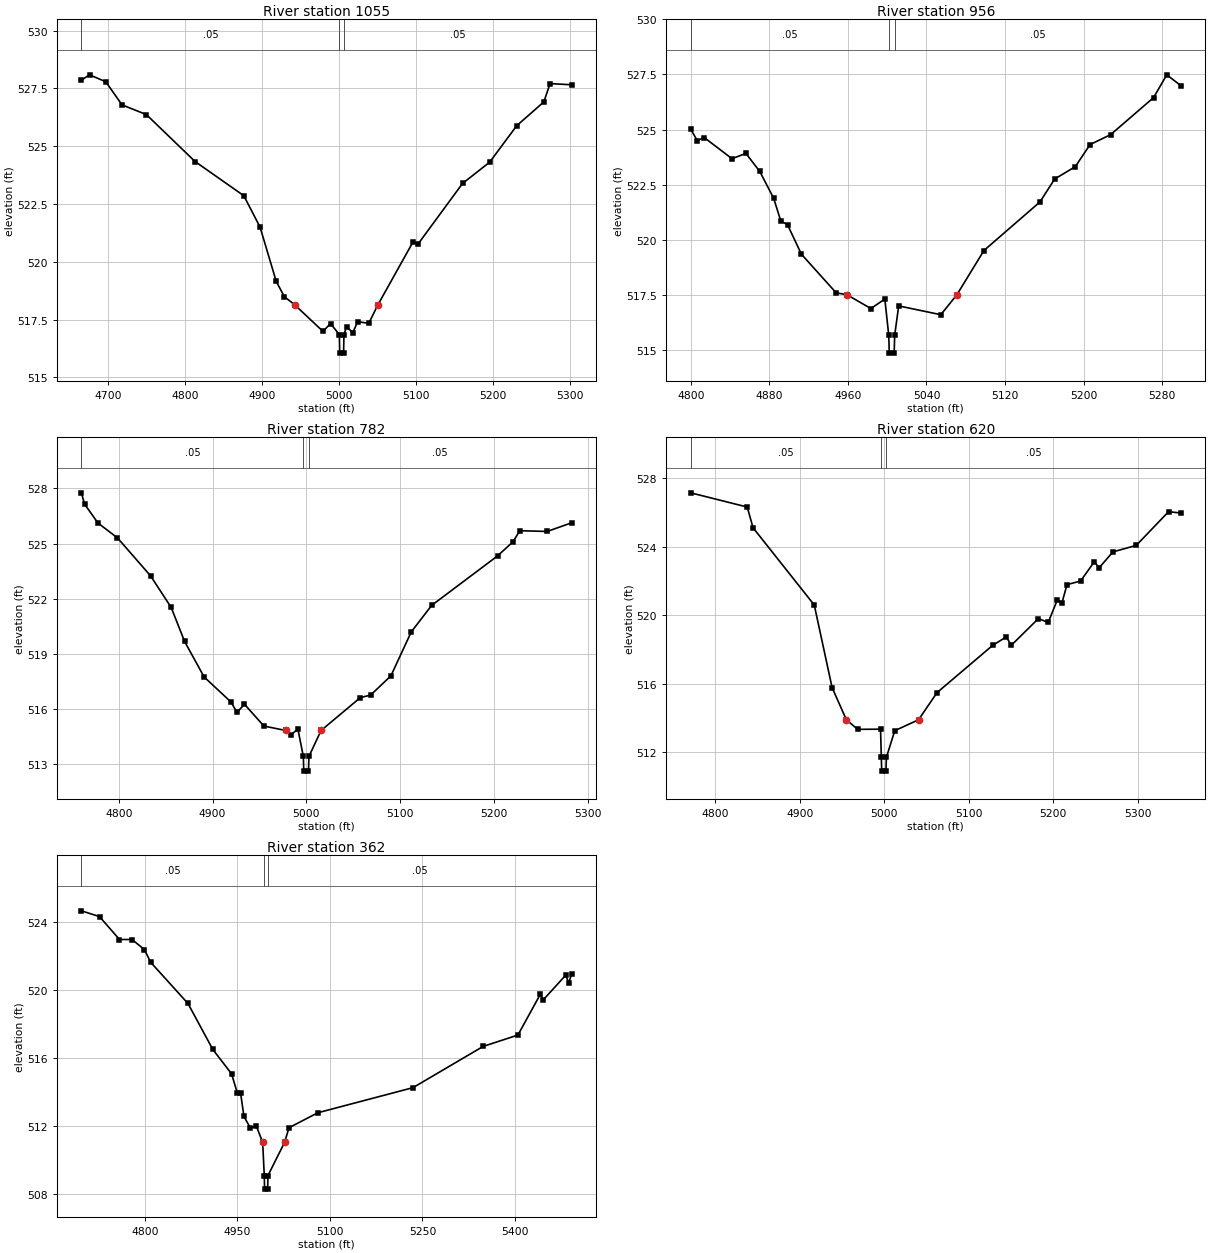
Type RM Length L Ch R = 1,1055,99,99,99
BEGIN DESCRIPTION:
UNT 024 in LFCCL Watershed 2.0
END DESCRIPTION:
XS GIS Cut Line= 3
      2789974.96      7079774.99      2789675.00      7079675.00
      2789475.03      7079924.97
#Sta/Elev= 30
  4665.3  527.86  4675.8  528.09  4696.9  527.79  4718.0  526.79  4749.6  526.37
  4812.8  524.34  4876.1  522.86  4897.2  521.50  4918.2  519.15  4928.8  518.49
  4942.5  518.13  4978.9  516.99  4988.7  517.33  5000.1  516.85  5000.6  516.05
  5005.6  516.05  5006.1  516.85  5009.5  517.20  5017.5  516.93  5023.9  517.41
  5038.3  517.34  5050.0  518.13  5095.9  520.87  5102.3  520.77  5160.0  523.39
  5195.2  524.31  5230.4  525.89  5265.6  526.92  5273.6  527.71  5301.6  527.66
#Mann=3,-1,0
  4665.3    0.05       0  5000.1    0.03       0  5006.1    0.05       0
Bank Sta=4942.5,5050
Exp/Cntr=0.3,0.1

Type RM Length L Ch R = 1,956,174,174,174
BEGIN DESCRIPTION:
XS3130A
END DESCRIPTION:
XS GIS Cut Line= 3
      2789738.59      7079479.17      2789586.12      7079634.13
      2789429.34      7079868.06
#Sta/Elev= 30
  4800.0  525.01  4806.7  524.50  4813.7  524.64  4842.0  523.68  4856.2  523.92
  4870.3  523.10  4884.4  521.89  4891.6  520.87  4898.6  520.68  4912.7  519.35
  4948.1  517.60  4958.9  517.52  4983.4  516.89  4997.6  517.32  5001.6  515.67
  5002.1  514.87  5007.1  514.87  5007.6  515.67  5011.7  517.01  5054.6  516.61
  5071.0  517.52  5098.5  519.52  5155.5  521.72  5170.5  522.76  5191.5  523.32
  5206.5  524.32  5227.5  524.77  5271.2  526.45  5284.6  527.48  5299.0  526.99
#Mann=3,-1,0
  4800.0    0.05       0  5001.6    0.03       0  5007.6    0.05       0
Bank Sta=4958.9,5071
Exp/Cntr=0.3,0.1

Type RM Length L Ch R = 1,782,162,162,162
BEGIN DESCRIPTION:
XS3128A
END DESCRIPTION:
XS GIS Cut Line= 3
      2789603.63      7079399.22      2789448.68      7079581.65
      2789339.37      7079842.52
#Sta/Elev= 30
  4760.3  527.76  4763.6  527.15  4777.9  526.12  4798.7  525.31  4833.9  523.25
  4855.9  521.53  4870.2  519.68  4891.0  517.75  4919.6  516.39  4926.1  515.82
  4933.9  516.27  4954.7  515.08  4977.9  514.84  4983.3  514.59  4990.9  514.92
  4996.7  513.43  4997.2  512.63  5002.2  512.63  5002.7  513.43  5015.6  514.84
  5057.5  516.63  5068.3  516.76  5090.0  517.81  5111.7  520.20  5133.4  521.64
  5203.6  524.33  5220.1  525.10  5227.3  525.70  5256.5  525.66  5282.5  526.13
#Mann=3,-1,0
  4760.3    0.05       0  4996.7    0.03       0  5002.7    0.05       0
Bank Sta=4977.9,5015.6
Exp/Cntr=0.3,0.1

Type RM Length L Ch R = 1,620,258,258,258
BEGIN DESCRIPTION:
XS3129A
END DESCRIPTION:
XS GIS Cut Line= 3
      2789571.13      7079319.27      2789378.71      7079444.21
      2789213.76      7079754.12
#Sta/Elev= 30
  4770.9  527.14  4837.8  526.31  4844.7  525.10  4917.2  520.59  4938.3  515.77
  4955.2  513.89  4968.6  513.33  4995.7  513.34  4996.6  511.69  4997.1  510.89
  5002.1  510.89  5002.6  511.69  5012.5  513.25  5040.7  513.89  5062.5  515.47
  5128.4  518.23  5144.7  518.73  5150.4  518.23  5182.5  519.79  5194.3  519.58
  5204.9  520.87  5210.6  520.73  5216.5  521.78  5232.6  521.99  5248.9  523.12
  5254.5  522.76  5270.9  523.69  5298.5  524.07  5336.8  526.04  5351.4  525.96
#Mann=3,-1,0
  4770.9    0.05       0  4996.6    0.03       0  5002.6    0.05       0
Bank Sta=4955.2,5040.7
Exp/Cntr=0.3,0.1

Type RM Length L Ch R = 1,362,0,0,0
BEGIN DESCRIPTION:
UNT 024 in LFCCL Watershed 1.0
END DESCRIPTION:
XS GIS Cut Line= 3
      2789556.15      7079264.29      2789258.76      7079224.31
      2789138.82      7079704.08
#Sta/Elev= 30
  4697.3  524.67  4726.6  524.33  4759.0  522.98  4779.2  522.98  4799.4  522.39
  4809.5  521.64  4870.0  519.21  4910.3  516.50  4940.6  515.07  4950.2  513.92
  4955.2  513.95  4960.8  512.55  4970.9  511.89  4981.0  511.97  4991.1  511.03
  4993.7  509.07  4994.2  508.27  4999.2  508.27  4999.7  509.07  5026.7  511.03
  5033.8  511.89  5080.5  512.77  5234.8  514.25  5348.5  516.68  5404.9  517.35
  5441.0  519.74  5446.1  519.43  5482.2  520.87  5487.4  520.43  5491.9  520.95
#Mann=3,-1,0
  4697.3    0.05       0  4993.7    0.03       0  4999.7    0.05       0
Bank Sta=4991.1,5026.7
Exp/Cntr=0.3,0.1

Chan Stop Cuts=-1