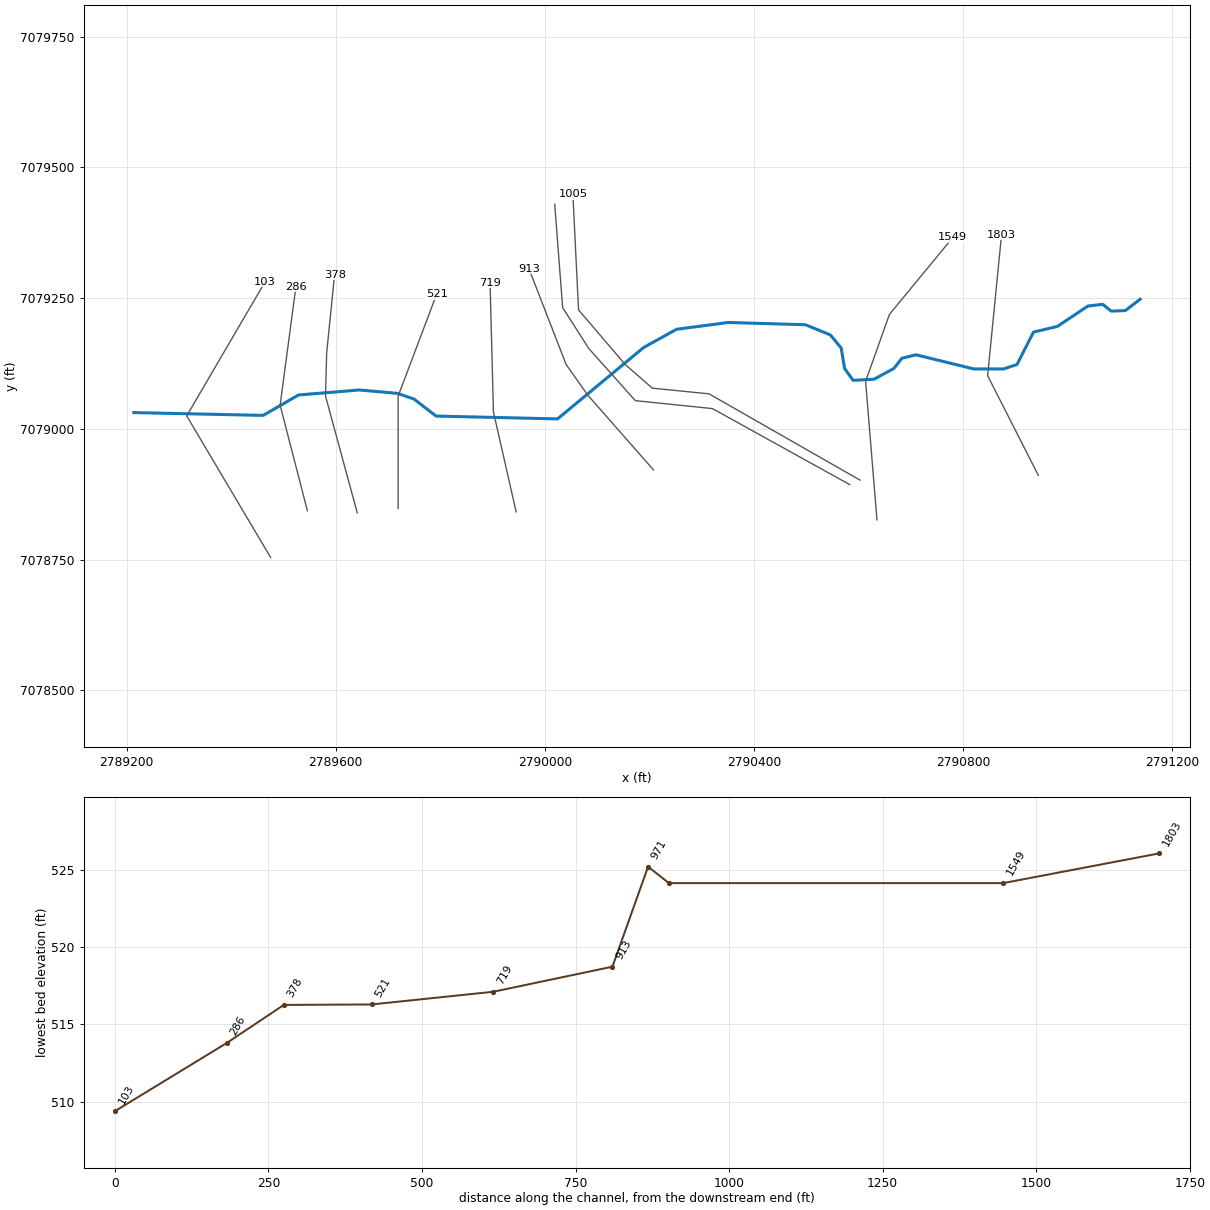
--- UNT 025 in LFCCL Watershed.prj (project) ---

Proj Title=UNT 025 in LFCCL Watershed Base Level Engineering
Current Plan=p01
Default Exp/Contr=0.3,0.1
English Units
Geom File=g01
Flow File=f01
Plan File=p01
BEGIN DESCRIPTION:
UNT 025 in LFCCL Watershed
END DESCRIPTION:

--- UNT 025 in LFCCL Watershed.p01 (plan) ---

Plan Title=Multiple Run
Short Identifier=Multiple
Geom File=g01
Flow File=f01
Subcritical Flow
K Sum by GR= 0
Std Step Tol= 0.01
Critical Tol= 0.01
Num of Std Step Trials= 20
Max Error Tol= 0.3
Flow Tol Ratio= 0.001
Split Flow NTrial= 30
Split Flow Tol= 0.02
Split Flow Ratio= 0.02
Log Output Level= 0
Friction Slope Method= 1
Unsteady Friction Slope Method= 2
Unsteady Bridges Friction Slope Method= 1
Parabolic Critical Depth
Global Vel Dist=  1 , 1 , 1
Global Log Level= 0
CheckData=True
Encroach Param= -1, 0, 0, 0
BEGIN DESCRIPTION:
Multiple Run
END DESCRIPTION:

--- UNT 025 in LFCCL Watershed.f01 (steady flow) ---

Flow Title=Multiple
Number of Profiles=7
Profile Names=10-year,25-year,50-year,1pct_min,100-year,1pct_plu,500-year
River Rch & RM= UNT 025 in LFCCL,Reach-1,1803
     114     134     147      81     162     324     195
Boundary for River Rch & Prof#=UNT 025 in LFCCL,Reach-1,1
Up Type=0
Dn Type=3
Dn Slope=0.005
Boundary for River Rch & Prof#=UNT 025 in LFCCL,Reach-1,2
Up Type=0
Dn Type=3
Dn Slope=0.005
Boundary for River Rch & Prof#=UNT 025 in LFCCL,Reach-1,3
Up Type=0
Dn Type=3
Dn Slope=0.005
Boundary for River Rch & Prof#=UNT 025 in LFCCL,Reach-1,4
Up Type=0
Dn Type=3
Dn Slope=0.005
Boundary for River Rch & Prof#=UNT 025 in LFCCL,Reach-1,5
Up Type=0
Dn Type=3
Dn Slope=0.005
Boundary for River Rch & Prof#=UNT 025 in LFCCL,Reach-1,6
Up Type=0
Dn Type=3
Dn Slope=0.005
Boundary for River Rch & Prof#=UNT 025 in LFCCL,Reach-1,7
Up Type=0
Dn Type=3
Dn Slope=0.005

--- UNT 025 in LFCCL Watershed.g01 (geometry) ---

Geom Title=Existing Conditions

River Reach=UNT 025 in LFCCL,Reach-1
Reach XY= 30
      2791138.53      7079248.01      2791110.32      7079226.31
      2791083.20      7079225.23      2791066.92      7079238.25
      2791038.71      7079234.99      2790980.11      7079195.93
      2790934.54      7079185.08      2790903.07      7079123.23
      2790877.03      7079114.55      2790820.61      7079114.55
      2790709.93      7079141.68      2790682.81      7079135.17
      2790667.61      7079115.64      2790629.64      7079095.02
      2790589.49      7079092.85      2790573.21      7079115.64
      2790566.70      7079154.70      2790546.09      7079179.65
      2790498.34      7079199.19      2790350.77      7079203.53
      2790252.03      7079190.51      2790189.10      7079155.78
      2790024.17      7079019.06      2789791.96      7079024.49
      2789749.65      7079057.04      2789718.18      7079067.89
      2789645.26      7079074.40      2789528.94      7079064.85
      2789461.23      7079025.79      2789213.88      7079031.14

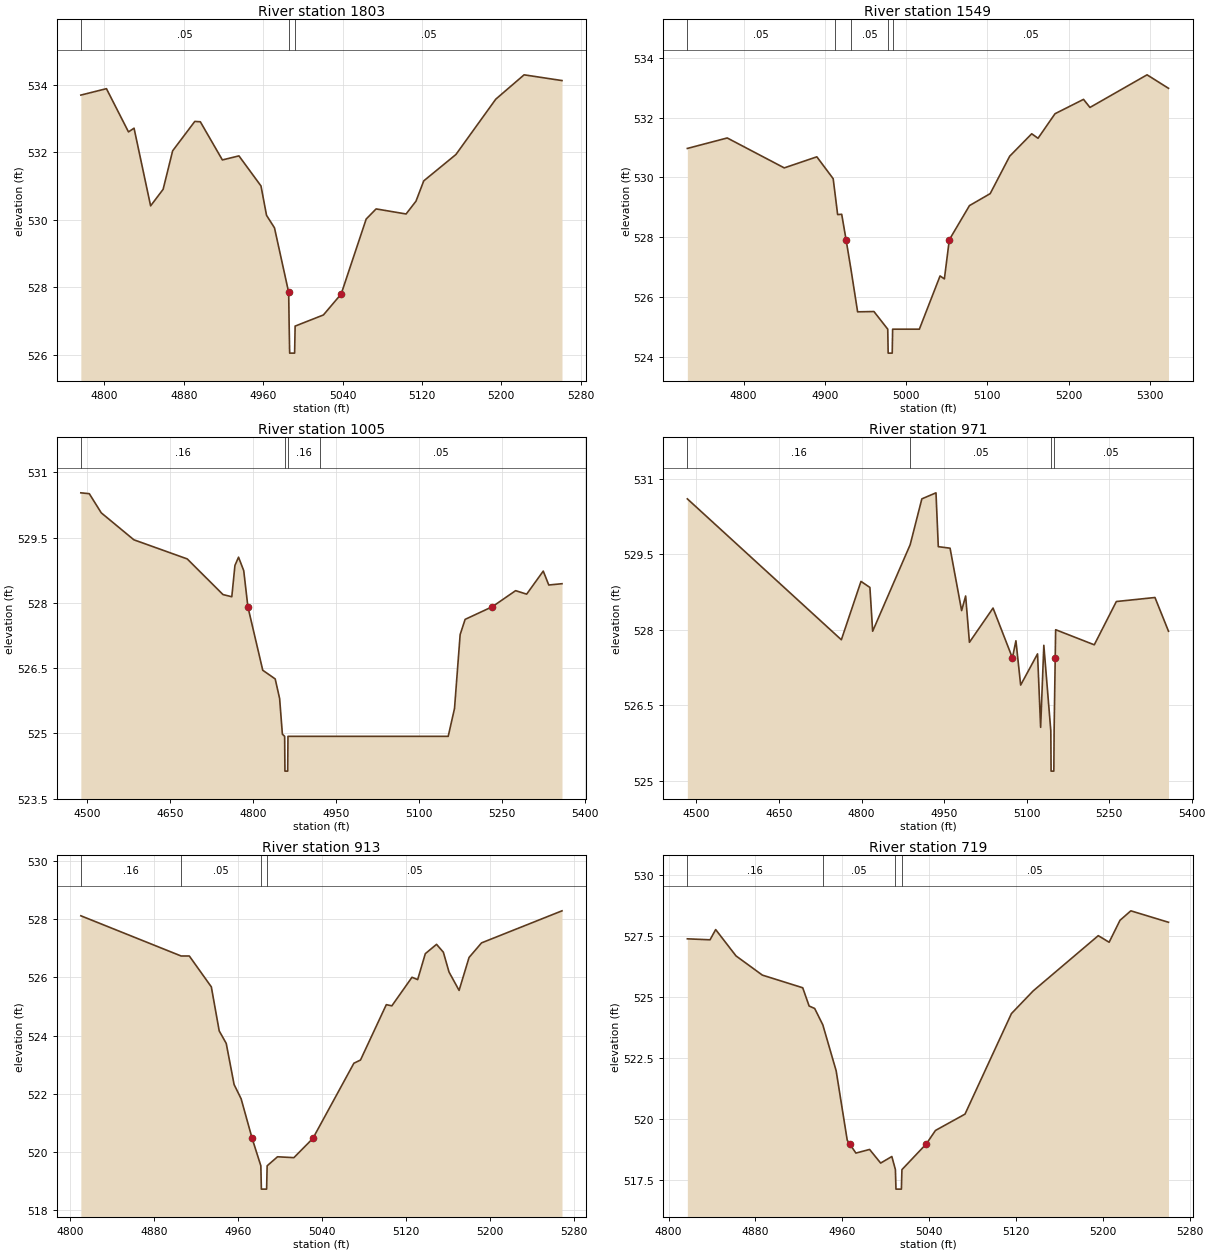
Type RM Length L Ch R = 1,1803,254,254,254
BEGIN DESCRIPTION:
UNT 025 in LFCCL Watershed 3.0
END DESCRIPTION:
XS GIS Cut Line= 3
      2790943.79      7078911.13      2790846.80      7079101.77
      2790873.42      7079371.36
#Sta/Elev= 30
  4776.3  533.69  4802.1  533.88  4824.3  532.60  4829.9  532.71  4846.6  530.41
  4859.2  530.90  4868.8  532.04  4891.1  532.91  4896.7  532.90  4918.9  531.77
  4935.6  531.89  4957.8  531.00  4963.4  530.13  4971.4  529.76  4985.7  527.85
  4986.2  526.85  4986.7  526.05  4991.7  526.05  4992.2  526.85  5020.7  527.18
  5038.6  527.80  5063.8  530.02  5073.8  530.32  5104.0  530.17  5114.0  530.55
  5121.8  531.15  5154.2  531.93  5194.4  533.57  5222.9  534.29  5261.1  534.12
#Mann=3,-1,0
  4776.3    0.05       0  4986.2    0.03       0  4992.2    0.05       0
Bank Sta=4985.7,5038.6
Exp/Cntr=0.3,0.1

Type RM Length L Ch R = 1,1549,544,544,544
BEGIN DESCRIPTION:
XS3131A
END DESCRIPTION:
XS GIS Cut Line= 4
      2790635.15      7078826.10      2790613.44      7079090.89
      2790659.01      7079218.93      2790780.25      7079366.15
#Sta/Elev= 30
  4730.8  530.97  4779.9  531.32  4850.1  530.32  4890.2  530.69  4910.3  529.96
  4912.1  529.57  4915.8  528.76  4920.8  528.77  4926.2  527.92  4932.4  526.90
  4940.4  525.51  4960.5  525.52  4977.5  524.93  4978.0  524.13  4983.0  524.13
  4983.5  524.93  5016.4  524.93  5041.9  526.71  5047.2  526.61  5053.3  527.92
  5078.1  529.06  5103.6  529.46  5127.6  530.71  5154.7  531.46  5162.5  531.31
  5183.4  532.13  5218.5  532.61  5226.4  532.34  5296.7  533.43  5323.1  532.98
#Mann=5,-1,0
  4730.8    0.05       0  4912.1    0.16       0  4932.4    0.05       0
  4977.5    0.03       0  4983.5    0.05       0
Bank Sta=4926.2,5053.3
Exp/Cntr=0.3,0.1

Type RM Length L Ch R = 1,1005,34,34,34
BEGIN DESCRIPTION:
XS3132A
END DESCRIPTION:
XS GIS Cut Line= 6
      2790602.63      7078902.06      2790313.96      7079067.02
      2790205.46      7079077.87      2790153.37      7079123.44
      2790064.40      7079227.61      2790053.55      7079448.92
#Sta/Elev= 30
  4488.0  530.53  4503.3  530.51  4524.9  530.07  4583.9  529.45  4680.4  529.01
  4745.1  528.19  4761.0  528.14  4766.7  528.86  4773.2  529.05  4782.6  528.74
  4790.1  527.91  4817.0  526.45  4839.5  526.25  4847.5  525.80  4852.5  524.98
  4856.6  524.93  4857.1  524.13  4862.1  524.13  4862.6  524.93  4920.1  524.93
  5152.4  524.93  5163.8  525.57  5174.0  527.27  5183.0  527.62  5232.1  527.91
  5274.3  528.28  5294.3  528.20  5324.3  528.73  5334.3  528.41  5358.2  528.44
#Mann=4,-1,0
  4488.0    0.16       0  4856.6    0.03       0  4862.6    0.16       0
  4920.1    0.05       0
Bank Sta=4790.1,5232.1
Exp/Cntr=0.3,0.1

Type RM Length L Ch R = 1,971,58,58,58
BEGIN DESCRIPTION:
XS3133A
END DESCRIPTION:
XS GIS Cut Line= 6
      2790583.07      7078893.40      2790320.47      7079038.81
      2790172.90      7079054.00      2790083.93      7079153.82
      2790034.01      7079231.95      2790018.82      7079429.47
#Sta/Elev= 30
  4483.4  530.60  4763.3  527.80  4799.0  528.96  4815.2  528.84  4820.2  527.97
  4888.4  529.69  4909.6  530.60  4935.3  530.72  4939.5  529.65  4960.9  529.62
  4981.9  528.38  4989.2  528.67  4996.1  527.75  5039.0  528.43  5074.2  527.44
  5080.6  527.78  5089.2  526.90  5119.9  527.52  5125.5  526.06  5131.3  527.69
  5144.0  525.99  5144.5  525.19  5149.5  525.19  5150.0  525.99  5152.0  527.44
  5152.8  528.00  5223.0  527.70  5263.1  528.56  5333.3  528.64  5357.9  527.97
#Mann=4,-1,0
  4483.4    0.16       0  4888.4    0.05       0  5144.0    0.03       0
  5150.0    0.05       0
Bank Sta=5074.2,5152
Exp/Cntr=0.3,0.1

Type RM Length L Ch R = 1,913,194,194,194
BEGIN DESCRIPTION:
XS3134A
END DESCRIPTION:
XS GIS Cut Line= 4
      2790207.66      7078921.58      2790081.76      7079064.85
      2790040.53      7079123.44      2789969.47      7079306.46
#Sta/Elev= 30
  4810.2  528.11  4905.8  526.73  4913.6  526.73  4934.6  525.67  4942.1  524.16
  4948.8  523.73  4956.3  522.32  4963.0  521.83  4973.5  520.47  4981.8  519.53
  4982.3  518.73  4987.3  518.73  4987.8  519.53  4997.7  519.84  5013.3  519.81
  5031.4  520.47  5070.5  523.05  5076.8  523.16  5101.4  525.06  5106.7  525.02
  5125.9  526.00  5131.3  525.92  5138.6  526.81  5149.3  527.13  5155.8  526.86
  5161.2  526.18  5170.8  525.55  5180.3  526.68  5192.2  527.18  5268.9  528.28
#Mann=4,-1,0
  4810.2    0.16       0  4905.8    0.05       0  4981.8    0.03       0
  4987.8    0.05       0
Bank Sta=4973.5,5031.4
Exp/Cntr=0.3,0.1

Type RM Length L Ch R = 1,719,198,198,198
BEGIN DESCRIPTION:
XS3135A
END DESCRIPTION:
XS GIS Cut Line= 3
      2789945.04      7078841.32      2789901.64      7079032.30
      2789895.13      7079279.67
#Sta/Elev= 30
  4817.3  527.39  4838.2  527.35  4843.4  527.77  4862.1  526.69  4886.4  525.90
  4923.6  525.38  4929.5  524.63  4934.6  524.53  4942.1  523.86  4954.4  521.97
  4964.6  519.12  4966.8  518.97  4972.6  518.59  4985.2  518.74  4995.4  518.18
  5005.7  518.45  5009.0  517.91  5009.5  517.11  5014.5  517.11  5015.0  517.91
  5037.5  518.97  5045.9  519.52  5073.1  520.19  5115.9  524.32  5135.9  525.25
  5195.9  527.52  5205.9  527.25  5215.9  528.15  5225.9  528.54  5260.6  528.07
#Mann=4,-1,0
  4817.3    0.16       0  4942.1    0.05       0  5009.0    0.03       0
  5015.0    0.05       0
Bank Sta=4966.8,5037.5
Exp/Cntr=0.3,0.1

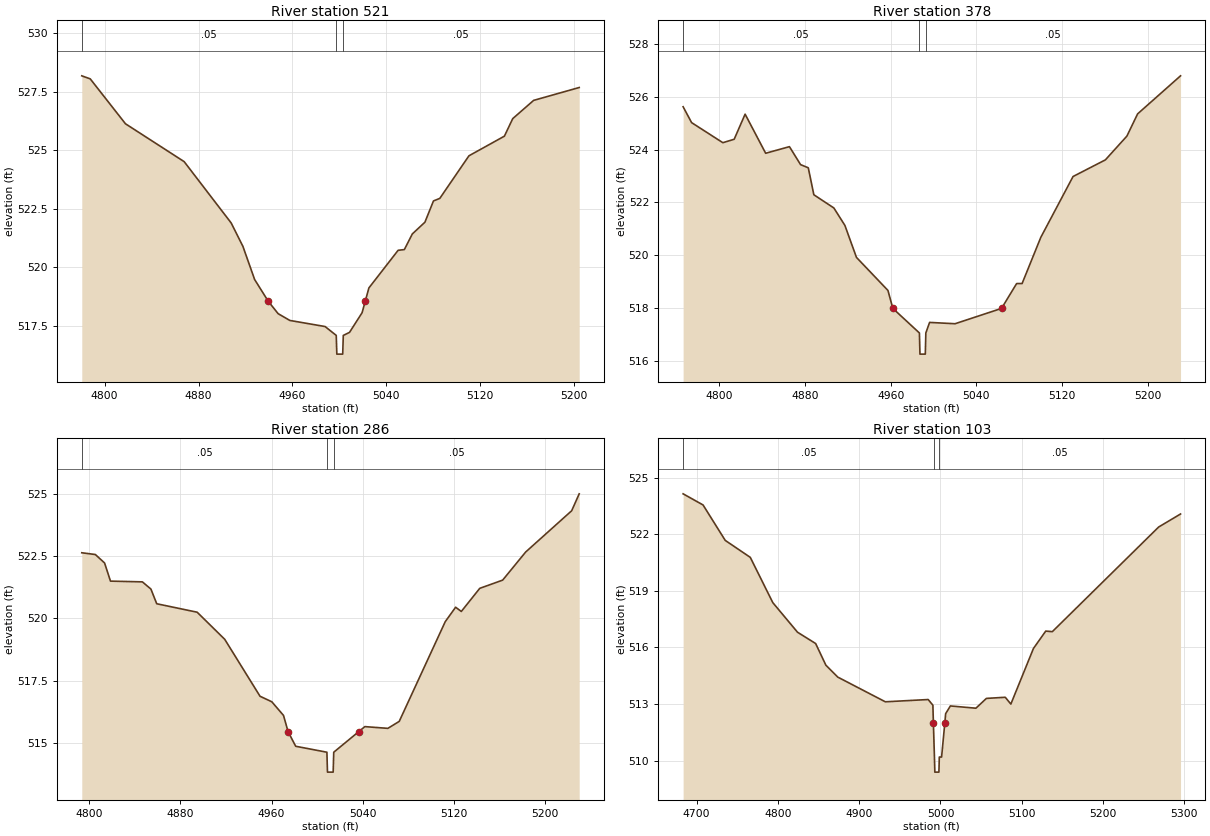
Type RM Length L Ch R = 1,521,143,143,143
BEGIN DESCRIPTION:
XS3136A
END DESCRIPTION:
XS GIS Cut Line= 3
      2789719.34      7078847.83      2789719.34      7079062.68
      2789793.12      7079257.96
#Sta/Elev= 30
  4780.6  528.19  4787.8  528.06  4817.8  526.14  4867.8  524.52  4907.8  521.90
  4917.8  520.90  4927.8  519.48  4939.4  518.55  4947.8  518.02  4957.8  517.73
  4987.8  517.47  4997.3  517.09  4997.8  516.29  5002.8  516.29  5003.3  517.09
  5008.6  517.22  5019.3  518.06  5022.0  518.55  5025.1  519.12  5050.0  520.73
  5055.3  520.76  5062.1  521.43  5072.8  521.93  5080.1  522.84  5085.5  522.95
  5110.3  524.77  5140.5  525.61  5147.6  526.36  5165.4  527.14  5204.2  527.69
#Mann=3,-1,0
  4780.6    0.05       0  4997.3    0.03       0  5003.3    0.05       0
Bank Sta=4939.4,5022
Exp/Cntr=0.3,0.1

Type RM Length L Ch R = 1,378,92,92,92
BEGIN DESCRIPTION:
XS3137A
END DESCRIPTION:
XS GIS Cut Line= 4
      2789641.22      7078839.16      2789580.46      7079062.68
      2789582.63      7079145.14      2789597.81      7079294.85
#Sta/Elev= 30
  4766.1  525.62  4774.0  525.02  4803.2  524.26  4813.8  524.39  4824.0  525.34
  4843.2  523.86  4865.4  524.11  4875.8  523.43  4883.0  523.31  4888.2  522.29
  4906.9  521.79  4917.2  521.13  4928.0  519.92  4957.4  518.67  4962.0  517.99
  4986.8  517.06  4987.3  516.26  4992.3  516.26  4992.8  517.06  4996.3  517.46
  5020.1  517.41  5063.5  517.99  5077.6  518.93  5082.7  518.93  5100.2  520.68
  5130.3  522.98  5160.5  523.61  5180.6  524.51  5190.6  525.35  5230.7  526.79
#Mann=3,-1,0
  4766.1    0.05       0  4986.8    0.03       0  4992.8    0.05       0
Bank Sta=4962,5063.5
Exp/Cntr=0.3,0.1

Type RM Length L Ch R = 1,286,183,183,183
BEGIN DESCRIPTION:
XS3138A
END DESCRIPTION:
XS GIS Cut Line= 3
      2789545.74      7078843.48      2789493.65      7079045.32
      2789523.82      7079271.57
#Sta/Elev= 30
  4793.4  522.64  4805.3  522.57  4813.4  522.23  4818.6  521.50  4846.6  521.47
  4854.1  521.18  4859.2  520.59  4894.7  520.25  4918.9  519.16  4949.9  516.87
  4960.2  516.65  4970.5  516.10  4974.5  515.45  4981.2  514.86  5008.6  514.62
  5009.1  513.82  5014.1  513.82  5014.6  514.62  5036.6  515.45  5041.9  515.65
  5062.1  515.58  5072.1  515.86  5112.5  519.87  5121.6  520.45  5126.6  520.28
  5142.8  521.21  5162.9  521.54  5183.1  522.67  5223.5  524.33  5230.1  525.01
#Mann=3,-1,0
  4793.4    0.05       0  5008.6    0.03       0  5014.6    0.05       0
Bank Sta=4974.5,5036.6
Exp/Cntr=0.3,0.1

Type RM Length L Ch R = 1,103,0,0,0
BEGIN DESCRIPTION:
UNT 025 in LFCCL Watershed 1.0
END DESCRIPTION:
XS GIS Cut Line= 3
      2789475.53      7078753.91      2789314.98      7079024.84
      2789464.77      7079281.16
#Sta/Elev= 30
  4683.5  524.15  4708.0  523.56  4735.3  521.68  4766.1  520.78  4793.8  518.38
  4824.2  516.81  4846.5  516.21  4859.1  515.06  4873.7  514.43  4932.2  513.12
  4984.9  513.24  4990.7  512.94  4991.3  512.01  4992.6  510.19  4993.1  509.39
  4998.1  509.39  4998.6  510.19  5001.4  510.19  5005.4  512.01  5006.4  512.49
  5012.2  512.90  5043.6  512.78  5056.5  513.30  5079.7  513.36  5086.6  513.00
  5114.4  515.95  5129.5  516.87  5137.6  516.84  5268.4  522.39  5295.3  523.08
#Mann=3,-1,0
  4683.5    0.05       0  4992.6    0.03       0  4998.6    0.05       0
Bank Sta=4991.3,5005.4
Exp/Cntr=0.3,0.1

Chan Stop Cuts=-1