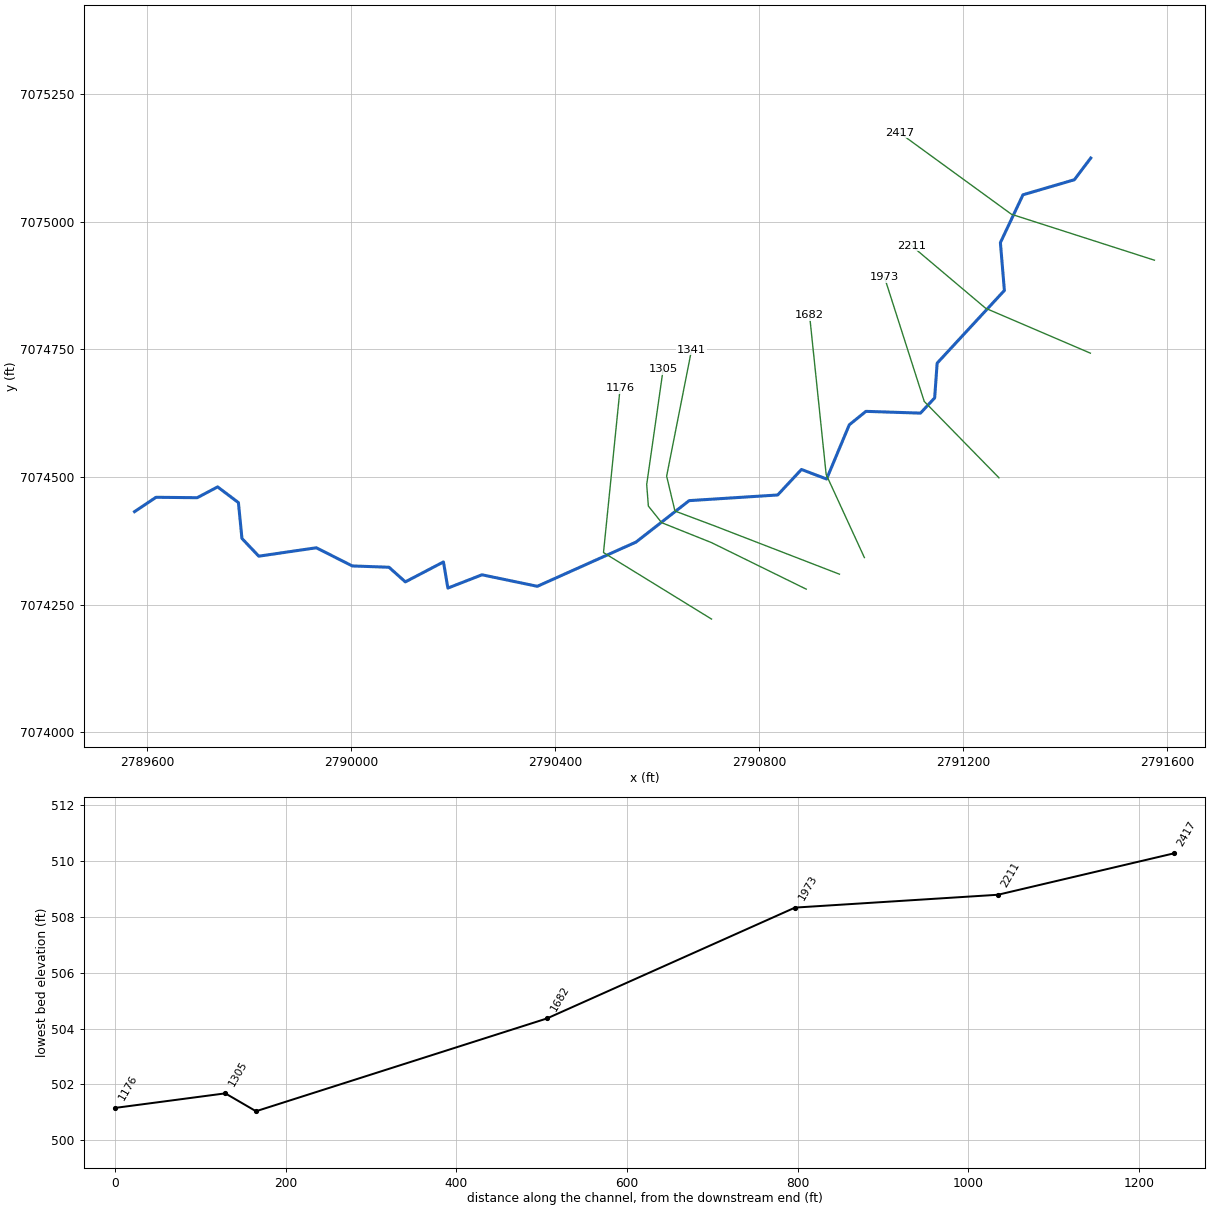
--- UNT 026 in LFCCL Watershed.prj (project) ---

Proj Title=UNT 026 in LFCCL Watershed Base Level Engineering
Current Plan=p01
Default Exp/Contr=0.3,0.1
English Units
Geom File=g01
Flow File=f01
Plan File=p01
BEGIN DESCRIPTION:
UNT 026 in LFCCL Watershed
END DESCRIPTION:

--- UNT 026 in LFCCL Watershed.p01 (plan) ---

Plan Title=Multiple Run
Short Identifier=Multiple
Geom File=g01
Flow File=f01
Subcritical Flow
K Sum by GR= 0
Std Step Tol= 0.01
Critical Tol= 0.01
Num of Std Step Trials= 20
Max Error Tol= 0.3
Flow Tol Ratio= 0.001
Split Flow NTrial= 30
Split Flow Tol= 0.02
Split Flow Ratio= 0.02
Log Output Level= 0
Friction Slope Method= 1
Unsteady Friction Slope Method= 2
Unsteady Bridges Friction Slope Method= 1
Parabolic Critical Depth
Global Vel Dist=  1 , 1 , 1
Global Log Level= 0
CheckData=True
Encroach Param= -1, 0, 0, 0
BEGIN DESCRIPTION:
Multiple Run
END DESCRIPTION:

--- UNT 026 in LFCCL Watershed.f01 (steady flow) ---

Flow Title=Multiple
Number of Profiles=7
Profile Names=10-year,25-year,50-year,1pct_min,100-year,1pct_plu,500-year
River Rch & RM= UNT 026 in LFCCL,Reach-1,2417
     192     235     267     152     302     603     384
Boundary for River Rch & Prof#=UNT 026 in LFCCL,Reach-1,1
Up Type=0
Dn Type=3
Dn Slope=0.005
Boundary for River Rch & Prof#=UNT 026 in LFCCL,Reach-1,2
Up Type=0
Dn Type=3
Dn Slope=0.005
Boundary for River Rch & Prof#=UNT 026 in LFCCL,Reach-1,3
Up Type=0
Dn Type=3
Dn Slope=0.005
Boundary for River Rch & Prof#=UNT 026 in LFCCL,Reach-1,4
Up Type=0
Dn Type=3
Dn Slope=0.005
Boundary for River Rch & Prof#=UNT 026 in LFCCL,Reach-1,5
Up Type=0
Dn Type=3
Dn Slope=0.005
Boundary for River Rch & Prof#=UNT 026 in LFCCL,Reach-1,6
Up Type=0
Dn Type=3
Dn Slope=0.005
Boundary for River Rch & Prof#=UNT 026 in LFCCL,Reach-1,7
Up Type=0
Dn Type=3
Dn Slope=0.005

--- UNT 026 in LFCCL Watershed.g01 (geometry) ---

Geom Title=Existing Conditions

River Reach=UNT 026 in LFCCL,Reach-1
Reach XY= 30
      2791450.21      7075125.23      2791418.10      7075082.70
      2791317.40      7075053.18      2791273.13      7074959.43
      2791280.94      7074865.68      2791149.13      7074723.19
      2791144.27      7074655.13      2791116.49      7074625.27
      2791009.55      7074628.75      2790976.91      7074602.36
      2790932.46      7074496.11      2790883.16      7074514.86
      2790836.63      7074464.86      2790663.02      7074453.75
      2790558.85      7074372.50      2790365.45      7074285.86
      2790256.94      7074308.43      2790190.10      7074282.39
      2790181.42      7074333.61      2790106.77      7074294.54
      2790074.65      7074323.19      2790002.60      7074325.79
      2789932.29      7074361.38      2789819.44      7074344.89
      2789786.46      7074379.61      2789779.51      7074449.93
      2789738.76      7074480.66      2789698.78      7074459.48
      2789618.05      7074460.34      2789575.91      7074432.14

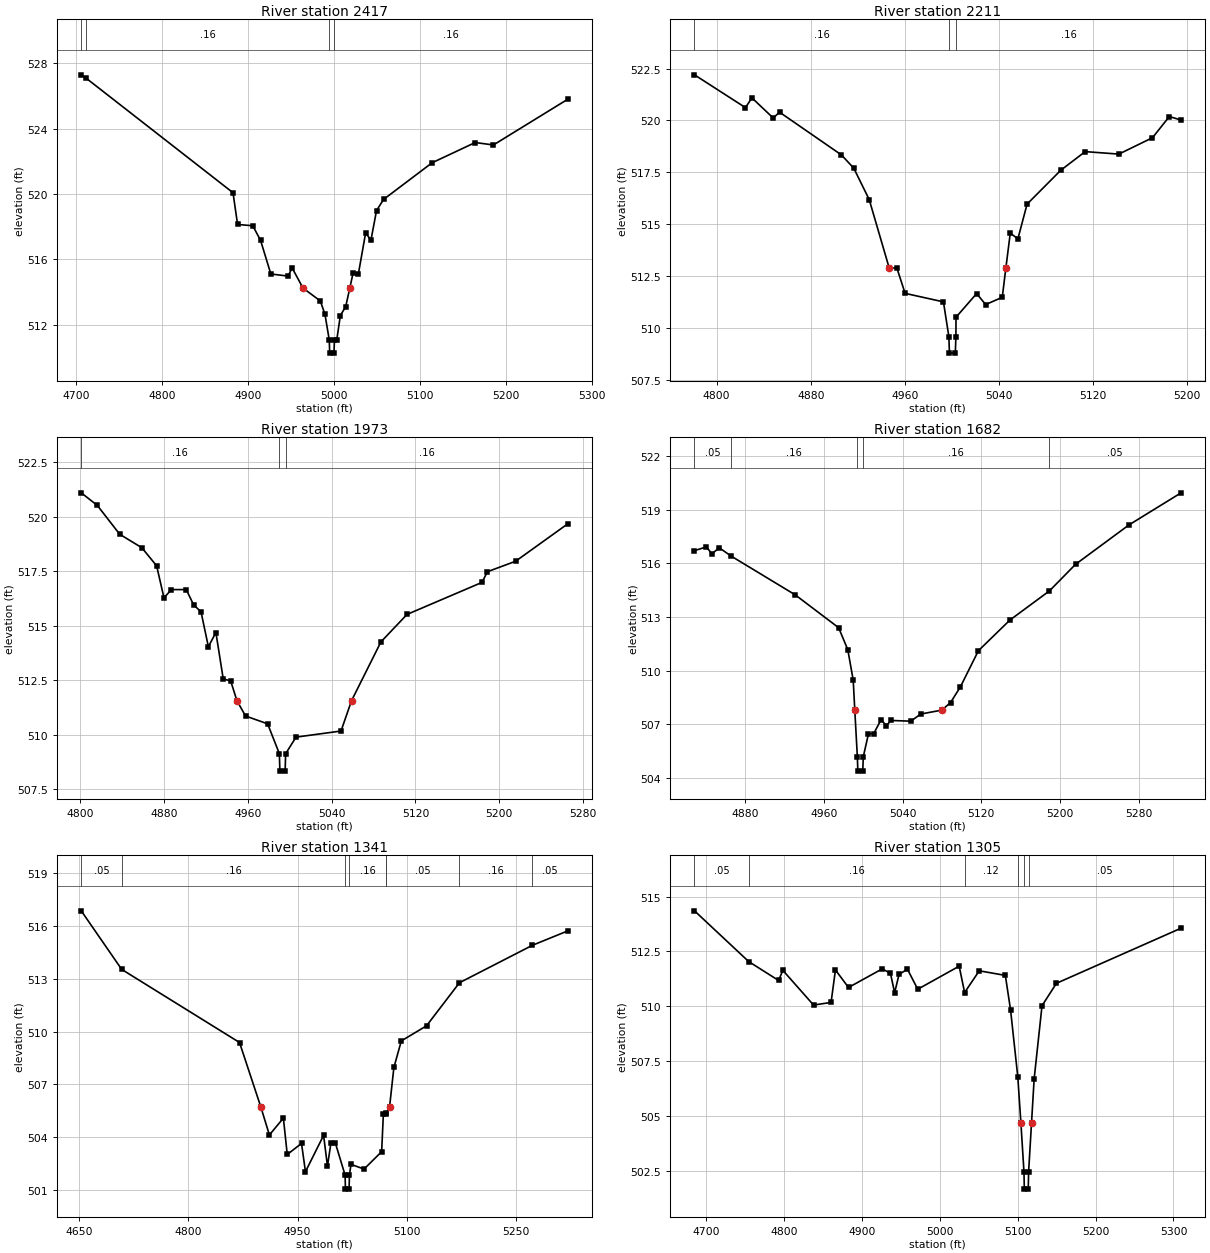
Type RM Length L Ch R = 1,2417,206,206,206
BEGIN DESCRIPTION:
UNT 026 in LFCCL Watershed 4.0
END DESCRIPTION:
XS GIS Cut Line= 3
      2791575.03      7074924.99      2791294.83      7075014.99
      2791075.00      7075175.00
#Sta/Elev= 30
  4705.7  527.29  4711.5  527.08  4882.3  520.08  4887.6  518.14  4905.3  518.06
  4914.4  517.16  4926.3  515.11  4946.5  514.98  4951.0  515.49  4963.7  514.25
  4983.9  513.46  4989.3  512.64  4994.3  511.07  4994.8  510.27  4999.8  510.27
  5000.3  511.07  5003.0  511.07  5007.2  512.57  5013.4  513.11  5018.2  514.25
  5021.9  515.14  5028.1  515.09  5036.6  517.62  5042.8  517.18  5049.3  518.99
  5057.5  519.67  5113.9  521.91  5164.1  523.15  5185.3  523.00  5271.9  525.80
#Mann=4,-1,0
  4705.7    0.05       0  4711.5    0.16       0  4994.3    0.07       0
  5000.3    0.16       0
Bank Sta=4963.7,5018.2
Exp/Cntr=0.3,0.1

Type RM Length L Ch R = 1,2211,238,238,238
BEGIN DESCRIPTION:
XS3139A
END DESCRIPTION:
XS GIS Cut Line= 3
      2791449.48      7074742.78      2791244.28      7074830.73
      2791098.85      7074953.53
#Sta/Elev= 30
  4781.2  522.20  4824.5  520.62  4830.0  521.09  4848.1  520.12  4853.5  520.40
  4906.1  518.34  4916.6  517.70  4929.7  516.19  4946.6  512.91  4953.3  512.88
  4960.2  511.67  4992.8  511.26  4997.4  509.59  4997.9  508.79  5002.9  508.79
  5003.4  509.59  5003.5  510.52  5021.0  511.66  5028.7  511.13  5042.8  511.48
  5045.9  512.91  5049.6  514.57  5056.1  514.30  5063.9  515.97  5092.5  517.60
  5113.3  518.50  5141.9  518.38  5170.5  519.17  5184.8  520.19  5194.8  520.02
#Mann=3,-1,0
  4781.2    0.16       0  4997.4    0.07       0  5003.4    0.16       0
Bank Sta=4946.6,5045.9
Exp/Cntr=0.3,0.1

Type RM Length L Ch R = 1,1973,291,291,291
BEGIN DESCRIPTION:
XS3143A
END DESCRIPTION:
XS GIS Cut Line= 3
      2791270.33      7074498.51      2791123.77      7074648.33
      2791046.01      7074891.31
#Sta/Elev= 30
  4800.8  521.10  4816.2  520.52  4837.5  519.20  4858.7  518.58  4872.8  517.75
  4879.8  516.28  4886.9  516.66  4901.1  516.66  4908.1  515.96  4915.2  515.64
  4922.2  514.04  4929.4  514.69  4936.4  512.56  4943.5  512.47  4949.5  511.56
  4957.7  510.86  4978.8  510.50  4990.0  509.13  4990.5  508.33  4995.5  508.33
  4996.0  509.13  5005.9  509.89  5048.9  510.17  5058.9  511.56  5087.0  514.26
  5111.9  515.52  5183.5  516.99  5188.7  517.48  5215.6  517.96  5265.5  519.68
#Mann=3,-1,0
  4800.8    0.16       0  4990.0    0.07       0  4996.0    0.16       0
Bank Sta=4949.5,5058.9
Exp/Cntr=0.3,0.1

Type RM Length L Ch R = 1,1682,341,341,341
BEGIN DESCRIPTION:
XS3142A
END DESCRIPTION:
XS GIS Cut Line= 3
      2791006.52      7074342.15      2790931.60      7074505.02
      2790899.03      7074817.65
#Sta/Elev= 30
  4829.0  516.72  4841.1  516.93  4846.6  516.54  4854.1  516.88  4866.0  516.42
  4931.2  514.24  4975.2  512.40  4984.5  511.17  4990.0  509.46  4991.6  507.78
  4994.2  505.16  4994.7  504.36  4999.7  504.36  5000.2  505.16  5005.5  506.46
  5010.8  506.46  5018.3  507.25  5023.5  506.91  5028.5  507.20  5048.5  507.16
  5058.5  507.56  5079.9  507.78  5088.7  508.20  5098.7  509.08  5117.0  511.11
  5149.0  512.83  5189.0  514.46  5215.5  515.95  5269.7  518.16  5322.6  519.96
#Mann=5,-1,0
  4829.0    0.05       0  4866.0    0.16       0  4994.2    0.07       0
  5000.2    0.16       0  5189.0    0.05       0
Bank Sta=4991.6,5079.9
Exp/Cntr=0.3,0.1

Type RM Length L Ch R = 1,1341,36,36,36
BEGIN DESCRIPTION:
XS3141A
END DESCRIPTION:
XS GIS Cut Line= 5
      2790957.63      7074309.60      2790713.37      7074404.05
      2790635.20      7074433.37      2790618.92      7074501.76
      2790667.77      7074749.31
#Sta/Elev= 30
  4653.0  516.87  4708.5  513.54  4870.3  509.38  4899.4  505.73  4911.3  504.12
  4930.5  505.08  4935.8  503.01  4955.4  503.64  4960.8  502.03  4985.7  504.10
  4991.0  502.35  4995.8  503.67  5001.8  503.67  5015.2  501.84  5015.7  501.04
  5020.7  501.04  5021.2  501.84  5023.3  502.45  5041.2  502.18  5065.4  503.17
  5067.8  505.34  5070.8  505.34  5072.0  505.36  5076.3  505.73  5082.2  507.96
  5092.4  509.47  5127.0  510.33  5172.2  512.78  5272.4  514.91  5321.0  515.73
#Mann=8,-1,0
  4653.0    0.05       0  4708.5    0.16       0  5015.2    0.07       0
  5021.2    0.16       0  5070.8    0.12       0  5072.0    0.05       0
  5172.2    0.16       0  5272.4    0.05       0
Bank Sta=4899.4,5076.3
Exp/Cntr=0.3,0.1

Type RM Length L Ch R = 1,1305,129,129,129
BEGIN DESCRIPTION:
XS3140A
END DESCRIPTION:
XS GIS Cut Line= 6
      2790892.54      7074280.27      2790706.86      7074371.48
      2790609.15      7074410.57      2790583.09      7074443.14
      2790579.83      7074485.48      2790612.16      7074711.78
#Sta/Elev= 30
  4684.9  514.35  4754.5  512.04  4792.9  511.18  4798.4  511.64  4837.8  510.06
  4860.3  510.18  4865.9  511.66  4882.7  510.86  4926.1  511.71  4936.6  511.50
  4941.9  510.62  4947.6  511.46  4958.4  511.69  4971.6  510.78  5024.8  511.83
  5031.8  510.63  5050.6  511.62  5084.1  511.41  5090.8  509.84  5100.1  506.79
  5104.1  504.68  5108.0  502.48  5108.5  501.68  5113.5  501.68  5114.0  502.48
  5117.7  504.68  5121.1  506.70  5131.2  510.03  5149.7  511.05  5309.8  513.56
#Mann=6,-1,0
  4684.9    0.05       0  4754.5    0.16       0  5031.8    0.12       0
  5100.1    0.05       0  5108.0    0.07       0  5114.0    0.05       0
Bank Sta=5104.1,5117.7
Exp/Cntr=0.3,0.1

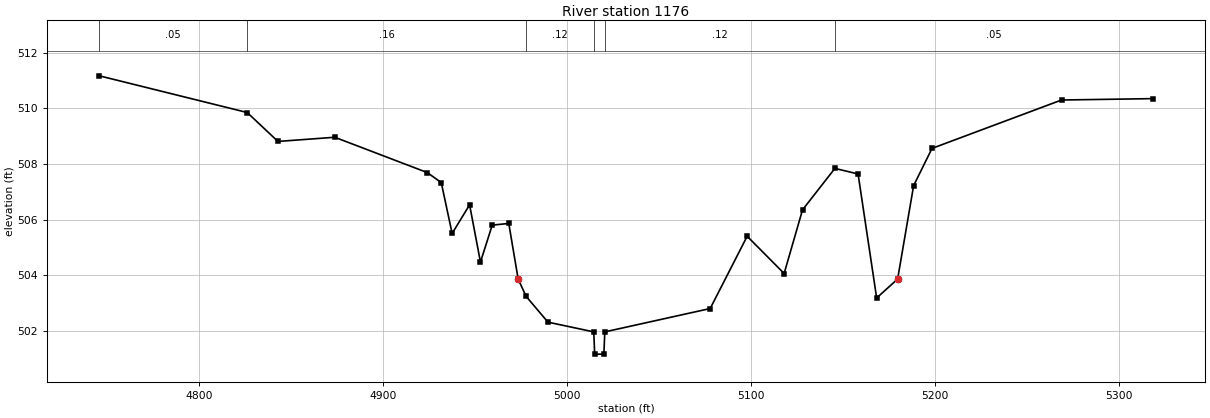
Type RM Length L Ch R = 1,1176,0,0,0
BEGIN DESCRIPTION:
UNT 026 in LFCCL Watershed 3.0
END DESCRIPTION:
XS GIS Cut Line= 3
      2790706.88      7074221.64      2790495.15      7074351.94
      2790527.72      7074674.39
#Sta/Elev= 30
  4745.8  511.17  4826.2  509.85  4842.9  508.81  4873.8  508.96  4924.1  507.69
  4931.7  507.33  4937.6  505.50  4947.1  506.53  4953.0  504.47  4959.4  505.80
  4968.4  505.86  4973.5  503.86  4977.8  503.24  4989.7  502.31  5014.6  501.96
  5015.1  501.16  5020.1  501.16  5020.6  501.96  5077.9  502.80  5098.0  505.40
  5118.1  504.06  5128.1  506.35  5145.7  507.84  5158.3  507.64  5168.4  503.18
  5179.8  503.86  5188.5  507.22  5198.5  508.56  5268.9  510.30  5318.5  510.35
#Mann=6,-1,0
  4745.8    0.05       0  4826.2    0.16       0  4977.8    0.12       0
  5014.6    0.07       0  5020.6    0.12       0  5145.7    0.05       0
Bank Sta=4973.5,5179.8
Exp/Cntr=0.3,0.1

Chan Stop Cuts=-1