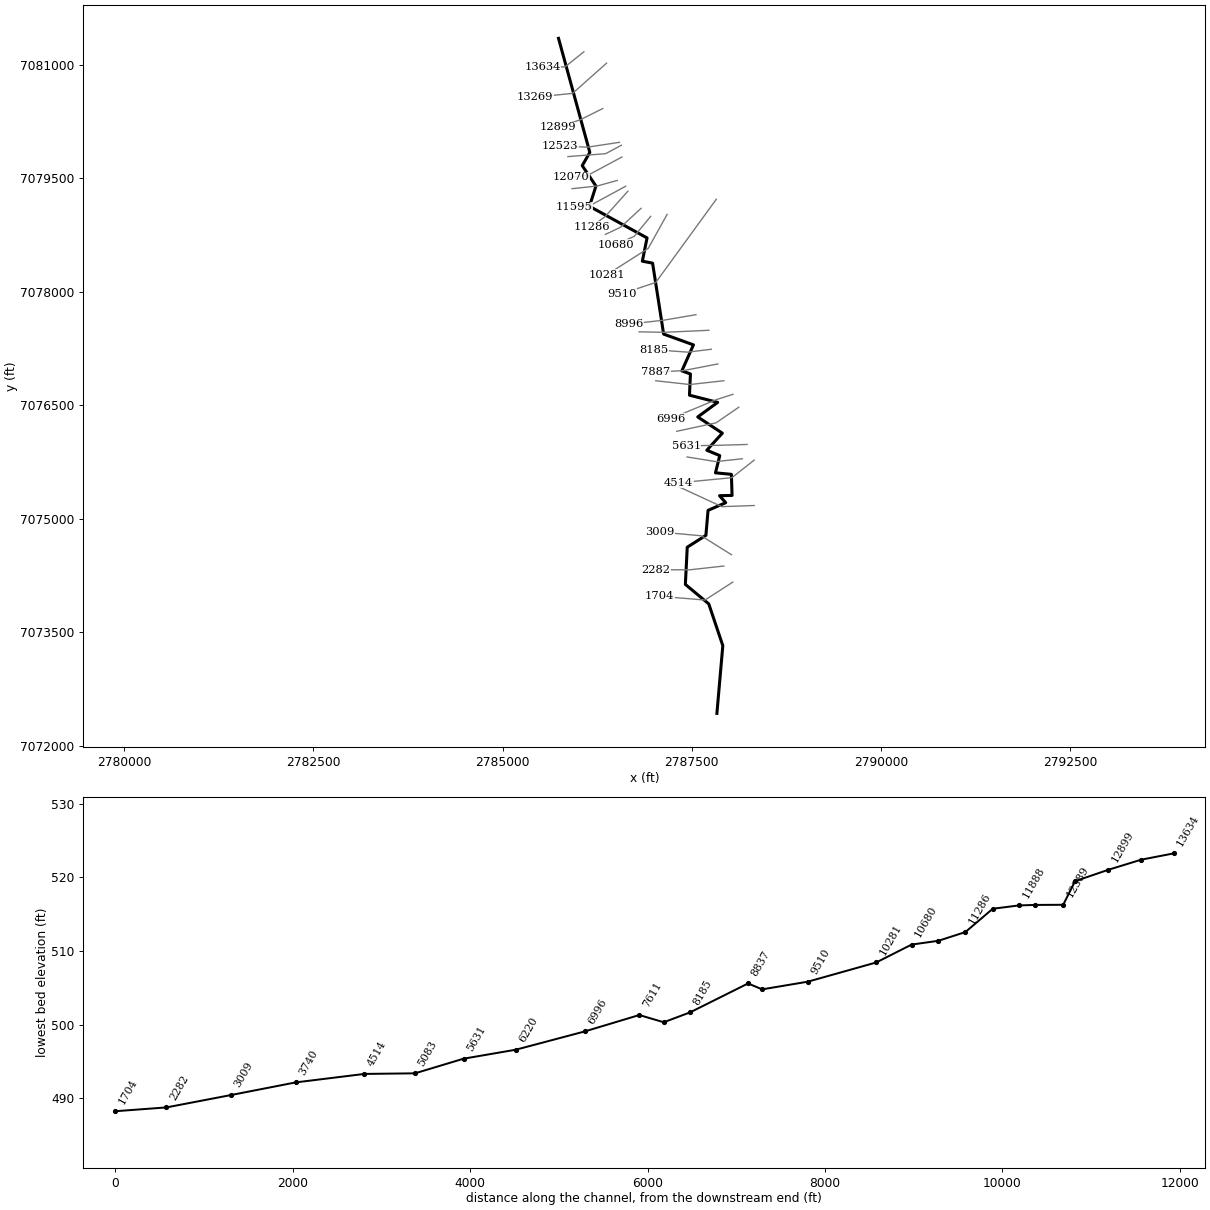
--- UNT 027 in LFCCL Watershed.prj (project) ---

Proj Title=UNT 027 in LFCCL Watershed Base Level Engineering
Current Plan=p01
Default Exp/Contr=0.3,0.1
English Units
Geom File=g01
Flow File=f01
Plan File=p01
BEGIN DESCRIPTION:
UNT 027 in LFCCL Watershed
END DESCRIPTION:

--- UNT 027 in LFCCL Watershed.p01 (plan) ---

Plan Title=Multiple Run
Short Identifier=Multiple
Geom File=g01
Flow File=f01
Subcritical Flow
K Sum by GR= 0
Std Step Tol= 0.01
Critical Tol= 0.01
Num of Std Step Trials= 20
Max Error Tol= 0.3
Flow Tol Ratio= 0.001
Split Flow NTrial= 30
Split Flow Tol= 0.02
Split Flow Ratio= 0.02
Log Output Level= 0
Friction Slope Method= 1
Unsteady Friction Slope Method= 2
Unsteady Bridges Friction Slope Method= 1
Parabolic Critical Depth
Global Vel Dist=  1 , 1 , 1
Global Log Level= 0
CheckData=True
Encroach Param= -1, 0, 0, 0
BEGIN DESCRIPTION:
Multiple Run
END DESCRIPTION:

--- UNT 027 in LFCCL Watershed.f01 (steady flow) ---

Flow Title=Multiple
Number of Profiles=7
Profile Names=10-year,25-year,50-year,1pct_min,100-year,1pct_plu,500-year
River Rch & RM= UNT 027 in LFCCL,Reach-1,13634
     664     881    1053     624    1246    2485    1738
River Rch & RM= UNT 027 in LFCCL,Reach-1,12070
     923    1245    1506     902    1799    3589    2563
Boundary for River Rch & Prof#=UNT 027 in LFCCL,Reach-1,1
Up Type=0
Dn Type=3
Dn Slope=0.005
Boundary for River Rch & Prof#=UNT 027 in LFCCL,Reach-1,2
Up Type=0
Dn Type=3
Dn Slope=0.005
Boundary for River Rch & Prof#=UNT 027 in LFCCL,Reach-1,3
Up Type=0
Dn Type=3
Dn Slope=0.005
Boundary for River Rch & Prof#=UNT 027 in LFCCL,Reach-1,4
Up Type=0
Dn Type=3
Dn Slope=0.005
Boundary for River Rch & Prof#=UNT 027 in LFCCL,Reach-1,5
Up Type=0
Dn Type=3
Dn Slope=0.005
Boundary for River Rch & Prof#=UNT 027 in LFCCL,Reach-1,6
Up Type=0
Dn Type=3
Dn Slope=0.005
Boundary for River Rch & Prof#=UNT 027 in LFCCL,Reach-1,7
Up Type=0
Dn Type=3
Dn Slope=0.005

--- UNT 027 in LFCCL Watershed.g01 (geometry) ---

Geom Title=Existing Conditions

River Reach=UNT 027 in LFCCL,Reach-1
Reach XY= 30
      2785739.85      7081353.04      2786153.42      7079845.05
      2786053.36      7079669.73      2786234.55      7079400.13
      2786149.00      7079131.95      2786909.79      7078713.62
      2786847.54      7078406.24      2786982.99      7078380.05
      2787129.02      7077441.76      2787522.98      7077299.49
      2787369.54      7076955.34      2787483.21      7076914.83
      2787470.26      7076634.05      2787843.18      7076539.31
      2787579.55      7076346.49      2787904.47      7076131.69
      2787699.48      7075905.99      2787870.67      7075835.12
      2787813.97      7075607.24      2788024.41      7075587.61
      2788033.13      7075308.48      2787867.40      7075305.21
      2787949.17      7075212.53      2787715.84      7075111.13
      2787687.49      7074780.75      2787441.07      7074623.75
      2787415.99      7074132.00      2787725.65      7073873.59
      2787911.01      7073321.87      2787832.77      7072426.41

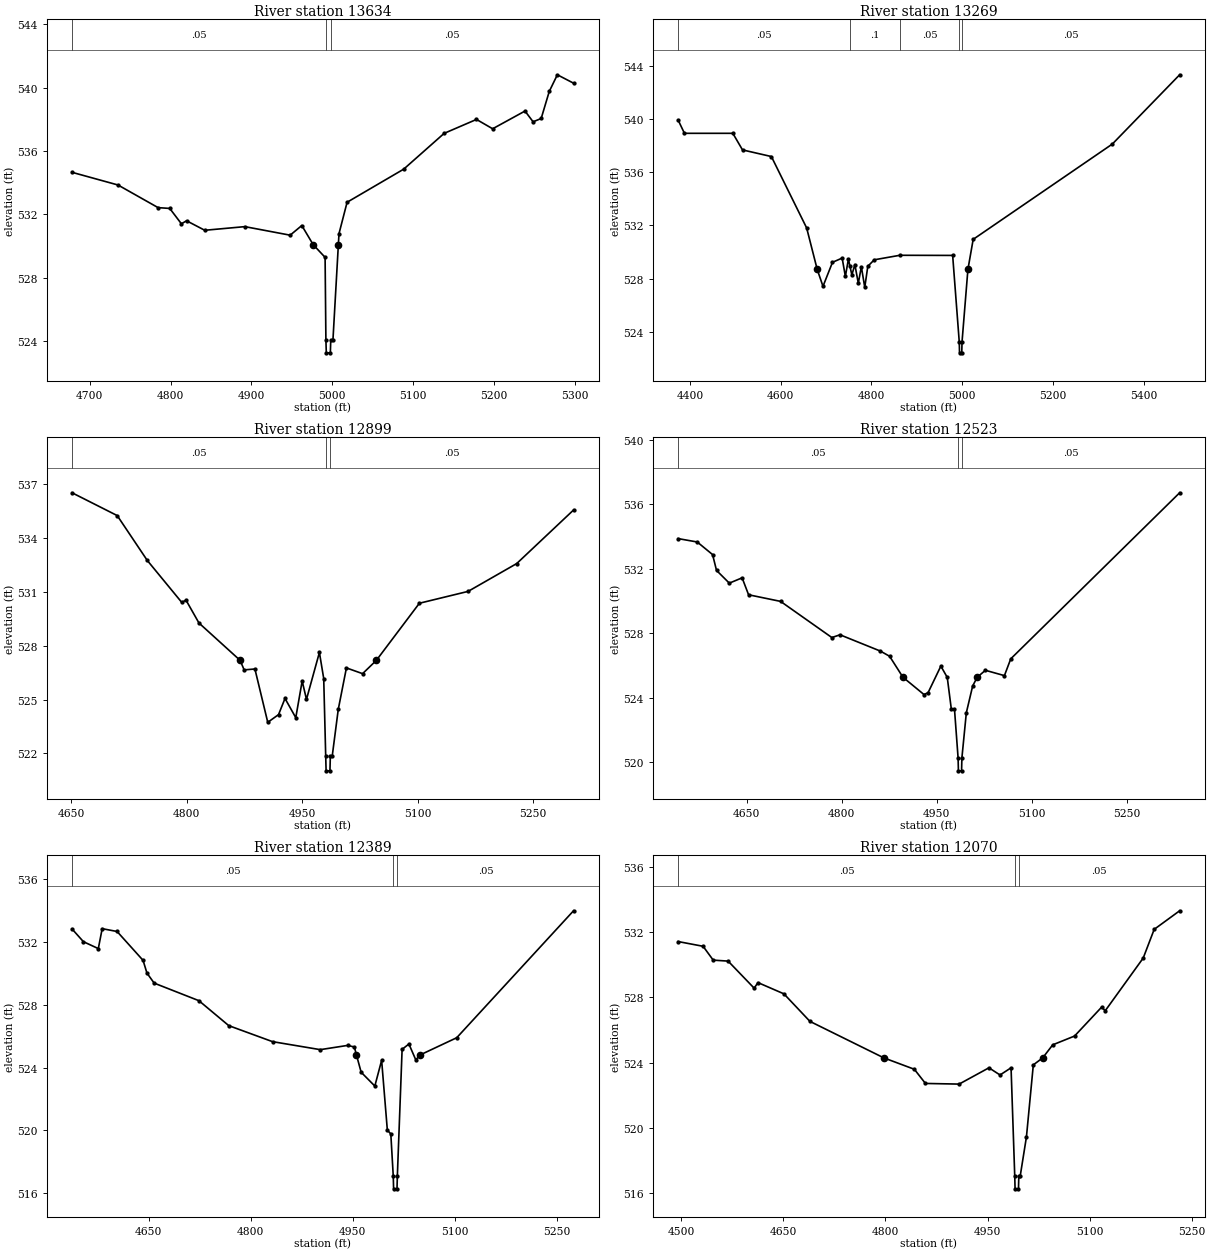
Type RM Length L Ch R = 1,13634,365,365,365
BEGIN DESCRIPTION:
UNT 027 in LFCCL Watershed 20.0
END DESCRIPTION:
XS GIS Cut Line= 3
      2786074.98      7081174.98      2785825.00      7080975.00
      2785525.03      7080975.00
#Sta/Elev= 30
  4678.2  534.65  4735.0  533.85  4784.6  532.42  4799.0  532.37  4813.4  531.40
  4819.8  531.59  4842.3  530.99  4891.9  531.22  4947.9  530.68  4962.3  531.29
  4976.4  530.08  4991.1  529.28  4992.1  524.05  4992.6  523.25  4997.6  523.25
  4998.1  524.05  5000.8  524.05  5007.5  530.08  5008.3  530.78  5018.3  532.76
  5088.3  534.85  5138.3  537.11  5178.3  537.99  5198.3  537.40  5238.3  538.52
  5248.3  537.84  5258.3  538.05  5268.3  539.76  5278.3  540.81  5298.3  540.28
#Mann=3,-1,0
  4678.2    0.05       0  4992.1    0.03       0  4998.1    0.05       0
Bank Sta=4976.4,5007.5
Exp/Cntr=0.3,0.1

Type RM Length L Ch R = 1,13269,370,370,370
BEGIN DESCRIPTION:
UNT 027 in LFCCL Watershed 19.0
END DESCRIPTION:
XS GIS Cut Line= 3
      2786374.99      7081024.99      2785925.00      7080625.00
      2785424.96      7080575.00
#Sta/Elev= 30
  4374.3  539.93  4388.1  538.94  4494.7  538.94  4516.0  537.69  4579.6  537.19
  4657.3  531.81  4680.6  528.68  4693.3  527.41  4714.2  529.22  4735.5  529.54
  4742.6  528.16  4749.3  529.46  4752.4  528.97  4756.9  528.27  4763.5  529.05
  4771.1  527.64  4777.8  528.89  4785.3  527.33  4792.0  528.92  4806.2  529.41
  4862.6  529.75  4978.9  529.74  4993.5  523.20  4994.0  522.40  4999.0  522.40
  4999.5  523.20  5012.5  528.68  5024.1  530.95  5330.6  538.13  5478.9  543.35
#Mann=5,-1,0
  4374.3    0.05       0  4752.4     0.1       0  4862.6    0.05       0
  4993.5    0.03       0  4999.5    0.05       0
Bank Sta=4680.6,5012.5
Exp/Cntr=0.3,0.1

Type RM Length L Ch R = 1,12899,376,376,376
BEGIN DESCRIPTION:
UNT 027 in LFCCL Watershed 18.0
END DESCRIPTION:
XS GIS Cut Line= 3
      2786324.97      7080424.99      2786025.00      7080275.00
      2785725.01      7080175.00
#Sta/Elev= 30
  4651.0  536.51  4709.7  535.24  4748.8  532.74  4793.5  530.41  4799.1  530.53
  4815.9  529.26  4869.4  527.18  4874.6  526.65  4888.6  526.70  4905.3  523.73
  4919.3  524.16  4927.7  525.06  4941.7  523.99  4950.0  526.03  4955.6  525.01
  4972.4  527.62  4978.0  526.17  4980.6  521.83  4981.1  521.03  4986.1  521.03
  4986.6  521.83  4989.0  521.83  4996.9  524.45  5007.5  526.76  5028.5  526.44
  5046.4  527.18  5102.3  530.36  5165.6  531.02  5228.8  532.57  5302.6  535.55
#Mann=3,-1,0
  4651.0    0.05       0  4980.6    0.03       0  4986.6    0.05       0
Bank Sta=4869.4,5046.4
Exp/Cntr=0.3,0.1

Type RM Length L Ch R = 1,12523,134,134,134
BEGIN DESCRIPTION:
XS3144A
END DESCRIPTION:
XS GIS Cut Line= 3
      2786544.80      7079977.97      2786117.29      7079913.11
      2785758.82      7079930.74
#Sta/Elev= 30
  4541.8  533.87  4571.9  533.66  4596.1  532.88  4602.3  531.90  4622.5  531.11
  4642.7  531.44  4652.9  530.39  4703.4  529.98  4784.3  527.74  4797.2  527.91
  4860.9  526.90  4875.4  526.58  4896.5  525.28  4929.6  524.21  4936.1  524.32
  4956.3  525.97  4966.4  525.27  4972.8  523.31  4977.8  523.31  4983.5  520.28
  4984.0  519.48  4989.0  519.48  4989.5  520.28  4996.5  523.08  5006.5  524.74
  5013.7  525.28  5026.6  525.71  5056.6  525.38  5066.6  526.42  5333.1  536.71
#Mann=3,-1,0
  4541.8    0.05       0  4983.5    0.03       0  4989.5    0.05       0
Bank Sta=4896.5,5013.7
Exp/Cntr=0.3,0.1

Type RM Length L Ch R = 1,12389,319,319,319
BEGIN DESCRIPTION:
XS3145A
END DESCRIPTION:
XS GIS Cut Line= 3
      2786571.39      7079939.65      2786362.03      7079827.60
      2785863.76      7079789.27
#Sta/Elev= 30
  4537.4  532.83  4554.1  532.02  4576.0  531.58  4581.7  532.85  4603.6  532.67
  4641.8  530.83  4647.5  530.02  4658.1  529.38  4723.9  528.26  4767.8  526.67
  4832.1  525.65  4902.3  525.14  4942.4  525.41  4952.4  525.31  4955.5  524.80
  4962.4  523.70  4982.5  522.82  4992.5  524.46  5000.9  520.01  5006.0  519.77
  5009.6  517.07  5010.1  516.27  5015.1  516.27  5015.6  517.07  5022.6  525.16
  5032.6  525.50  5042.7  524.49  5048.9  524.80  5102.9  525.90  5274.6  533.99
#Mann=3,-1,0
  4537.4    0.05       0  5009.6    0.03       0  5015.6    0.05       0
Bank Sta=4955.5,5048.9
Exp/Cntr=0.3,0.1

Type RM Length L Ch R = 1,12070,182,182,182
BEGIN DESCRIPTION:
XS3146A
END DESCRIPTION:
XS GIS Cut Line= 3
      2786577.26      7079783.36      2786137.93      7079547.48
      2785902.00      7079515.04
#Sta/Elev= 30
  4495.5  531.43  4532.1  531.14  4547.0  530.29  4568.9  530.23  4607.1  528.57
  4612.8  528.91  4650.9  528.22  4689.1  526.53  4797.7  524.29  4842.5  523.59
  4858.8  522.72  4908.3  522.68  4952.1  523.68  4968.4  523.24  4984.6  523.68
  4990.0  517.05  4990.5  516.25  4995.5  516.25  4996.0  517.05  4998.1  517.05
  5007.2  519.44  5017.3  523.86  5031.1  524.29  5045.8  525.09  5077.9  525.63
  5117.8  527.41  5122.9  527.18  5178.8  530.42  5194.9  532.18  5232.3  533.32
#Mann=3,-1,0
  4495.5    0.05       0  4990.0    0.03       0  4996.0    0.05       0
Bank Sta=4797.7,5031.1
Exp/Cntr=0.3,0.1

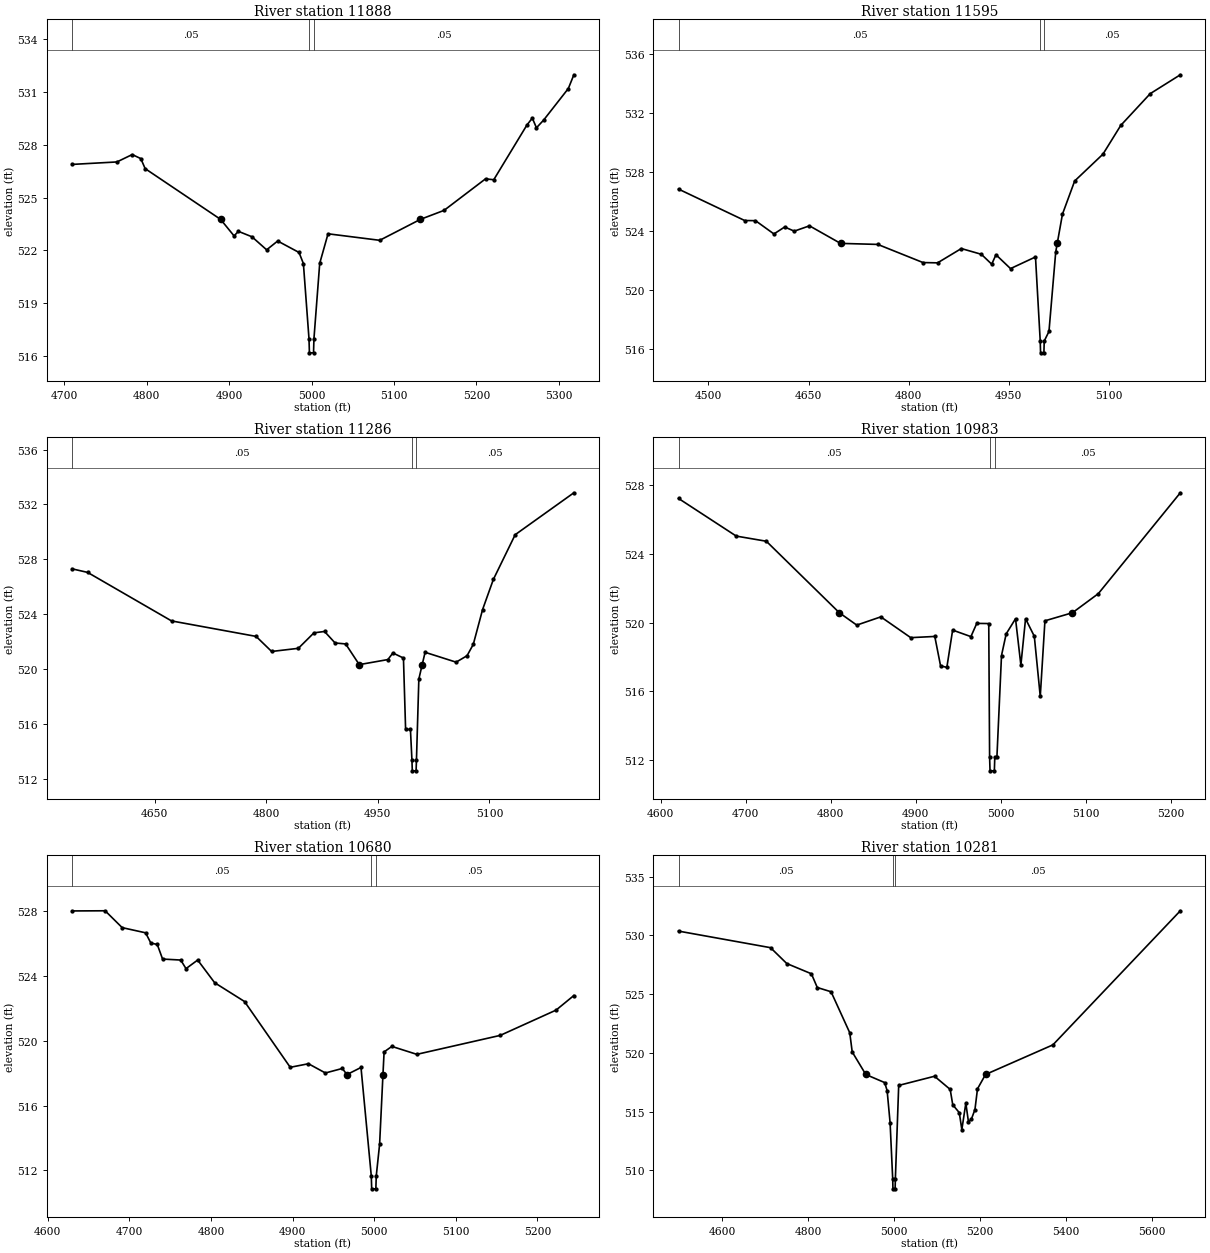
Type RM Length L Ch R = 1,11888,293,293,293
BEGIN DESCRIPTION:
XS3147A
END DESCRIPTION:
XS GIS Cut Line= 3
      2786515.36      7079473.77      2786249.98      7079400.05
      2785918.37      7079364.83
#Sta/Elev= 30
  4709.3  526.88  4763.7  527.02  4782.3  527.44  4792.7  527.21  4798.0  526.64
  4889.5  523.76  4905.9  522.82  4911.1  523.08  4927.6  522.77  4945.4  522.03
  4958.8  522.53  4984.7  521.88  4990.0  521.25  4996.8  516.98  4997.3  516.18
  5002.3  516.18  5002.8  516.98  5009.8  521.26  5019.9  522.94  5082.6  522.57
  5132.0  523.76  5160.7  524.27  5211.0  526.06  5221.0  526.01  5261.3  529.12
  5267.8  529.51  5272.8  528.96  5281.4  529.39  5311.5  531.19  5318.2  531.97
#Mann=3,-1,0
  4709.3    0.05       0  4996.8    0.03       0  5002.8    0.05       0
Bank Sta=4889.5,5132
Exp/Cntr=0.3,0.1

Type RM Length L Ch R = 1,11595,309,309,309
BEGIN DESCRIPTION:
XS3148A
END DESCRIPTION:
XS GIS Cut Line= 3
      2786627.42      7079397.11      2786176.27      7079152.37
      2785940.37      7079116.98
#Sta/Elev= 30
  4455.2  526.83  4554.3  524.70  4570.5  524.69  4598.1  523.79  4614.2  524.26
  4628.6  523.98  4651.4  524.34  4697.9  523.15  4753.7  523.08  4821.5  521.85
  4843.3  521.83  4878.9  522.80  4908.9  522.41  4924.4  521.74  4930.8  522.38
  4952.6  521.44  4990.0  522.23  4997.1  516.53  4997.6  515.73  5002.6  515.73
  5003.1  516.53  5010.2  517.18  5020.3  522.56  5022.6  523.15  5030.4  525.13
  5048.7  527.38  5091.1  529.20  5117.8  531.15  5161.9  533.30  5207.0  534.58
#Mann=3,-1,0
  4455.2    0.05       0  4997.1    0.03       0  5003.1    0.05       0
Bank Sta=4697.9,5022.6
Exp/Cntr=0.3,0.1

Type RM Length L Ch R = 1,11286,303,303,303
BEGIN DESCRIPTION:
XS3149A
END DESCRIPTION:
XS GIS Cut Line= 3
      2786656.89      7079332.23      2786356.13      7078996.09
      2786176.23      7078863.38
#Sta/Elev= 30
  4538.9  527.30  4559.8  527.04  4672.6  523.50  4786.3  522.37  4807.2  521.27
  4843.1  521.50  4864.1  522.63  4878.3  522.73  4892.5  521.89  4906.7  521.82
  4925.0  520.31  4963.5  520.68  4970.2  521.16  4984.4  520.79  4987.3  515.58
  4993.8  515.58  4995.8  513.36  4996.3  512.56  5001.4  512.56  5001.9  513.36
  5005.1  519.26  5009.6  520.31  5013.5  521.21  5055.2  520.49  5069.9  520.96
  5078.3  521.79  5090.8  524.33  5105.3  526.53  5134.6  529.79  5213.5  532.85
#Mann=3,-1,0
  4538.9    0.05       0  4995.8    0.03       0  5001.9    0.05       0
Bank Sta=4925,5009.6
Exp/Cntr=0.3,0.1

Type RM Length L Ch R = 1,10983,303,303,303
BEGIN DESCRIPTION:
XS3150A
END DESCRIPTION:
XS GIS Cut Line= 3
      2786830.85      7079105.18      2786559.59      7078854.55
      2786359.55      7078760.42
#Sta/Elev= 30
  4621.0  527.23  4688.9  525.04  4724.3  524.74  4810.2  520.58  4830.7  519.86
  4859.0  520.34  4894.2  519.13  4922.5  519.20  4929.3  517.49  4936.7  517.40
  4943.5  519.57  4965.0  519.19  4971.9  519.96  4986.0  519.95  4987.0  512.18
  4987.5  511.38  4992.6  511.38  4993.1  512.18  4995.6  512.18  5001.0  518.09
  5006.5  519.35  5017.5  520.23  5023.8  517.53  5029.3  520.23  5039.6  519.21
  5046.6  515.71  5052.1  520.11  5084.5  520.58  5114.9  521.69  5211.4  527.56
#Mann=3,-1,0
  4621.0    0.05       0  4987.0    0.03       0  4993.1    0.05       0
Bank Sta=4810.2,5084.5
Exp/Cntr=0.3,0.1

Type RM Length L Ch R = 1,10680,399,399,399
BEGIN DESCRIPTION:
XS3151A
END DESCRIPTION:
XS GIS Cut Line= 3
      2786957.63      7078999.01      2786742.40      7078736.61
      2786493.19      7078619.33
#Sta/Elev= 30
  4629.9  528.01  4670.4  528.02  4691.3  526.98  4720.0  526.66  4726.4  526.03
  4734.3  525.94  4740.8  525.04  4763.0  524.98  4769.5  524.45  4783.8  524.98
  4804.6  523.58  4841.2  522.42  4897.2  518.36  4919.5  518.58  4940.3  518.01
  4961.1  518.29  4966.6  517.91  4983.9  518.35  4996.5  511.66  4997.0  510.86
  5002.1  510.86  5002.6  511.66  5006.7  513.61  5010.8  517.91  5012.2  519.31
  5021.7  519.65  5052.3  519.16  5154.5  520.33  5222.9  521.89  5244.7  522.79
#Mann=3,-1,0
  4629.9    0.05       0  4996.5    0.03       0  5002.6    0.05       0
Bank Sta=4966.6,5010.8
Exp/Cntr=0.3,0.1

Type RM Length L Ch R = 1,10281,771,771,771
BEGIN DESCRIPTION:
UNT 027 in LFCCL Watershed 13.0
END DESCRIPTION:
XS GIS Cut Line= 3
      2787175.00      7079025.01      2786925.00      7078575.00
      2786375.01      7078225.00
#Sta/Elev= 30
  4498.7  530.36  4712.6  528.95  4750.4  527.60  4807.6  526.73  4821.3  525.56
  4853.3  525.20  4896.8  521.71  4902.5  520.08  4934.1  518.16  4978.0  517.47
  4983.7  516.79  4990.6  514.05  4996.7  509.23  4997.2  508.43  5002.3  508.43
  5002.8  509.23  5010.6  517.23  5093.9  518.01  5130.3  516.89  5136.3  515.58
  5151.5  514.91  5157.4  513.47  5166.7  515.72  5172.7  514.15  5179.4  514.34
  5187.9  515.18  5193.8  516.94  5212.5  518.16  5369.1  520.68  5665.4  532.09
#Mann=3,-1,0
  4498.7    0.05       0  4996.7    0.03       0  5002.8    0.05       0
Bank Sta=4934.1,5212.5
Exp/Cntr=0.3,0.1

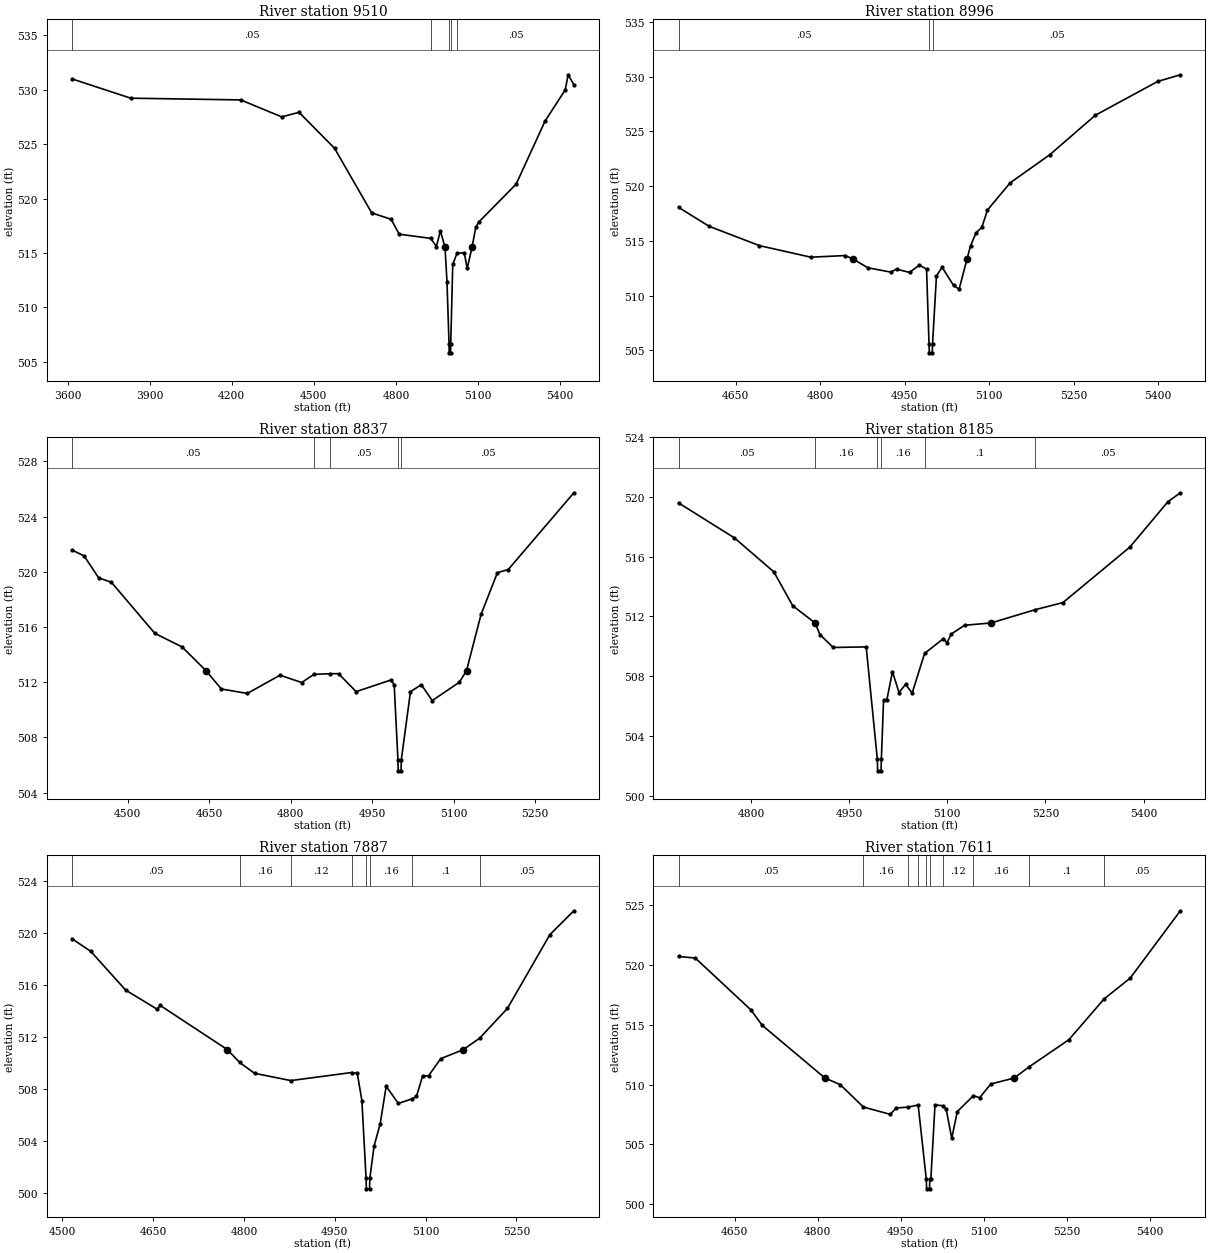
Type RM Length L Ch R = 1,9510,514,514,514
BEGIN DESCRIPTION:
UNT 027 in LFCCL Watershed 12.0
END DESCRIPTION:
XS GIS Cut Line= 3
      2787824.97      7079224.96      2787025.00      7078125.00
      2786575.04      7077975.01
#Sta/Elev= 30
  3616.1  530.99  3830.5  529.22  4232.4  529.06  4382.7  527.50  4445.7  527.92
  4575.5  524.62  4711.5  518.68  4782.6  518.09  4812.0  516.72  4927.1  516.34
  4948.0  515.59  4962.7  517.03  4979.5  515.51  4986.7  512.35  4994.2  506.62
  4994.7  505.82  4999.8  505.82  5000.3  506.62  5007.8  513.95  5023.5  514.98
  5050.0  515.01  5060.5  513.57  5078.2  515.51  5092.1  517.37  5102.7  517.83
  5239.7  521.33  5345.1  527.11  5418.9  529.98  5429.5  531.37  5450.5  530.46
#Mann=5,-1,0
  3616.1    0.05       0  4927.1    0.16       0  4994.2    0.07       0
  5000.3    0.16       0  5023.5    0.05       0
Bank Sta=4979.5,5078.2
Exp/Cntr=0.3,0.1

Type RM Length L Ch R = 1,8996,159,159,159
BEGIN DESCRIPTION:
UNT 027 in LFCCL Watershed 11.0
END DESCRIPTION:
XS GIS Cut Line= 3
      2787556.21      7077698.69      2787125.00      7077625.00
      2786675.03      7077575.00
#Sta/Elev= 30
  4548.9  518.06  4603.2  516.33  4692.2  514.57  4783.6  513.51  4844.3  513.66
  4858.2  513.35  4884.9  512.54  4925.5  512.15  4935.6  512.42  4958.8  512.12
  4976.2  512.79  4988.9  512.42  4993.3  505.58  4993.8  504.78  4999.0  504.78
  4999.5  505.58  5006.5  511.81  5016.5  512.59  5036.7  510.94  5046.7  510.59
  5060.7  513.35  5066.9  514.55  5076.9  515.75  5087.0  516.23  5097.0  517.82
  5137.3  520.30  5207.7  522.87  5288.2  526.46  5398.9  529.55  5439.1  530.16
#Mann=3,-1,0
  4548.9    0.05       0  4993.3    0.03       0  4999.5    0.05       0
Bank Sta=4858.2,5060.7
Exp/Cntr=0.3,0.1

Type RM Length L Ch R = 1,8837,652,652,652
BEGIN DESCRIPTION:
XS3152A
END DESCRIPTION:
XS GIS Cut Line= 3
      2787727.27      7077492.29      2787140.47      7077465.75
      2786804.32      7077471.65
#Sta/Elev= 30
  4397.4  521.58  4419.7  521.15  4446.4  519.56  4469.7  519.25  4549.8  515.54
  4599.9  514.56  4643.8  512.84  4672.2  511.51  4720.0  511.19  4780.1  512.51
  4820.1  511.98  4842.6  512.57  4872.4  512.62  4888.0  512.62  4920.2  511.32
  4984.8  512.17  4990.3  511.81  4997.2  506.38  4997.7  505.58  5002.9  505.58
  5003.4  506.38  5020.3  511.32  5040.3  511.82  5060.3  510.67  5110.3  512.00
  5123.4  512.84  5150.3  516.93  5180.3  519.94  5200.3  520.17  5321.0  525.73
#Mann=5,-1,0
  4397.4    0.05       0  4842.6     0.1       0  4872.4    0.05       0
  4997.2    0.03       0  5003.4    0.05       0
Bank Sta=4643.8,5123.4
Exp/Cntr=0.3,0.1

Type RM Length L Ch R = 1,8185,298,298,298
BEGIN DESCRIPTION:
XS3153A
END DESCRIPTION:
XS GIS Cut Line= 3
      2787759.72      7077241.66      2787447.12      7077203.33
      2786996.03      7077235.76
#Sta/Elev= 30
  4689.1  519.60  4774.5  517.26  4834.9  514.98  4863.6  512.72  4897.9  511.56
  4898.2  511.53  4905.4  510.78  4925.6  509.92  4976.0  509.96  4993.0  502.46
  4993.5  501.66  4998.7  501.66  4999.2  502.46  5002.6  506.42  5007.6  506.42
  5016.2  508.30  5026.2  506.90  5036.2  507.45  5046.3  506.87  5065.3  509.52
  5094.2  510.52  5099.3  510.24  5106.4  510.83  5126.5  511.41  5166.7  511.56
  5233.5  512.44  5276.9  512.93  5379.1  516.64  5437.3  519.68  5456.3  520.28
#Mann=6,-1,0
  4689.1    0.05       0  4898.2    0.16       0  4993.0    0.07       0
  4999.2    0.16       0  5065.3     0.1       0  5233.5    0.05       0
Bank Sta=4897.9,5166.7
Exp/Cntr=0.3,0.1

Type RM Length L Ch R = 1,7887,276,276,276
BEGIN DESCRIPTION:
XS3154A
END DESCRIPTION:
XS GIS Cut Line= 3
      2787845.18      7077047.05      2787385.20      7076958.59
      2787025.45      7076940.90
#Sta/Elev= 30
  4516.2  519.57  4546.9  518.61  4604.7  515.62  4656.6  514.15  4661.7  514.44
  4772.8  511.03  4792.8  510.05  4817.5  509.21  4877.4  508.65  4977.8  509.27
  4987.2  509.20  4994.8  507.10  5001.7  501.11  5002.2  500.31  5007.4  500.31
  5007.9  501.11  5014.8  503.59  5024.9  505.30  5034.9  508.21  5054.9  506.89
  5077.0  507.23  5084.9  507.43  5094.9  508.98  5105.0  509.03  5125.0  510.34
  5162.1  511.03  5189.1  511.91  5235.1  514.21  5305.2  519.89  5344.8  521.73
#Mann=8,-1,0
  4516.2    0.05       0  4792.8    0.16       0  4877.4    0.12       0
  4977.8    0.16       0  5001.7    0.07       0  5007.9    0.16       0
  5077.0     0.1       0  5189.1    0.05       0
Bank Sta=4772.8,5162.1
Exp/Cntr=0.3,0.1

Type RM Length L Ch R = 1,7611,615,615,615
BEGIN DESCRIPTION:
UNT 027 in LFCCL Watershed 9.0
END DESCRIPTION:
XS GIS Cut Line= 3
      2787924.99      7076825.00      2787475.00      7076775.00
      2787025.03      7076825.00
#Sta/Elev= 30
  4548.8  520.71  4579.0  520.58  4679.6  516.24  4699.7  514.96  4813.0  510.55
  4840.6  510.00  4882.3  508.13  4931.1  507.51  4941.2  508.05  4963.4  508.12
  4981.2  508.30  4995.9  502.09  4996.4  501.29  5001.7  501.29  5002.2  502.09
  5004.1  502.09  5011.6  508.31  5026.3  508.23  5031.7  507.97  5041.8  505.52
  5051.9  507.75  5081.0  509.08  5092.1  508.90  5112.2  510.05  5154.4  510.55
  5181.0  511.47  5253.1  513.75  5316.7  517.16  5363.8  518.90  5454.3  524.53
#Mann=10,-1,0
  4548.8    0.05       0  4882.3    0.16       0  4963.4    0.12       0
  4981.2    0.16       0  4995.9    0.07       0  5002.2    0.16       0
  5026.3    0.12       0  5081.0    0.16       0  5181.0     0.1       0
  5316.7    0.05       0
Bank Sta=4813,5154.4
Exp/Cntr=0.3,0.1

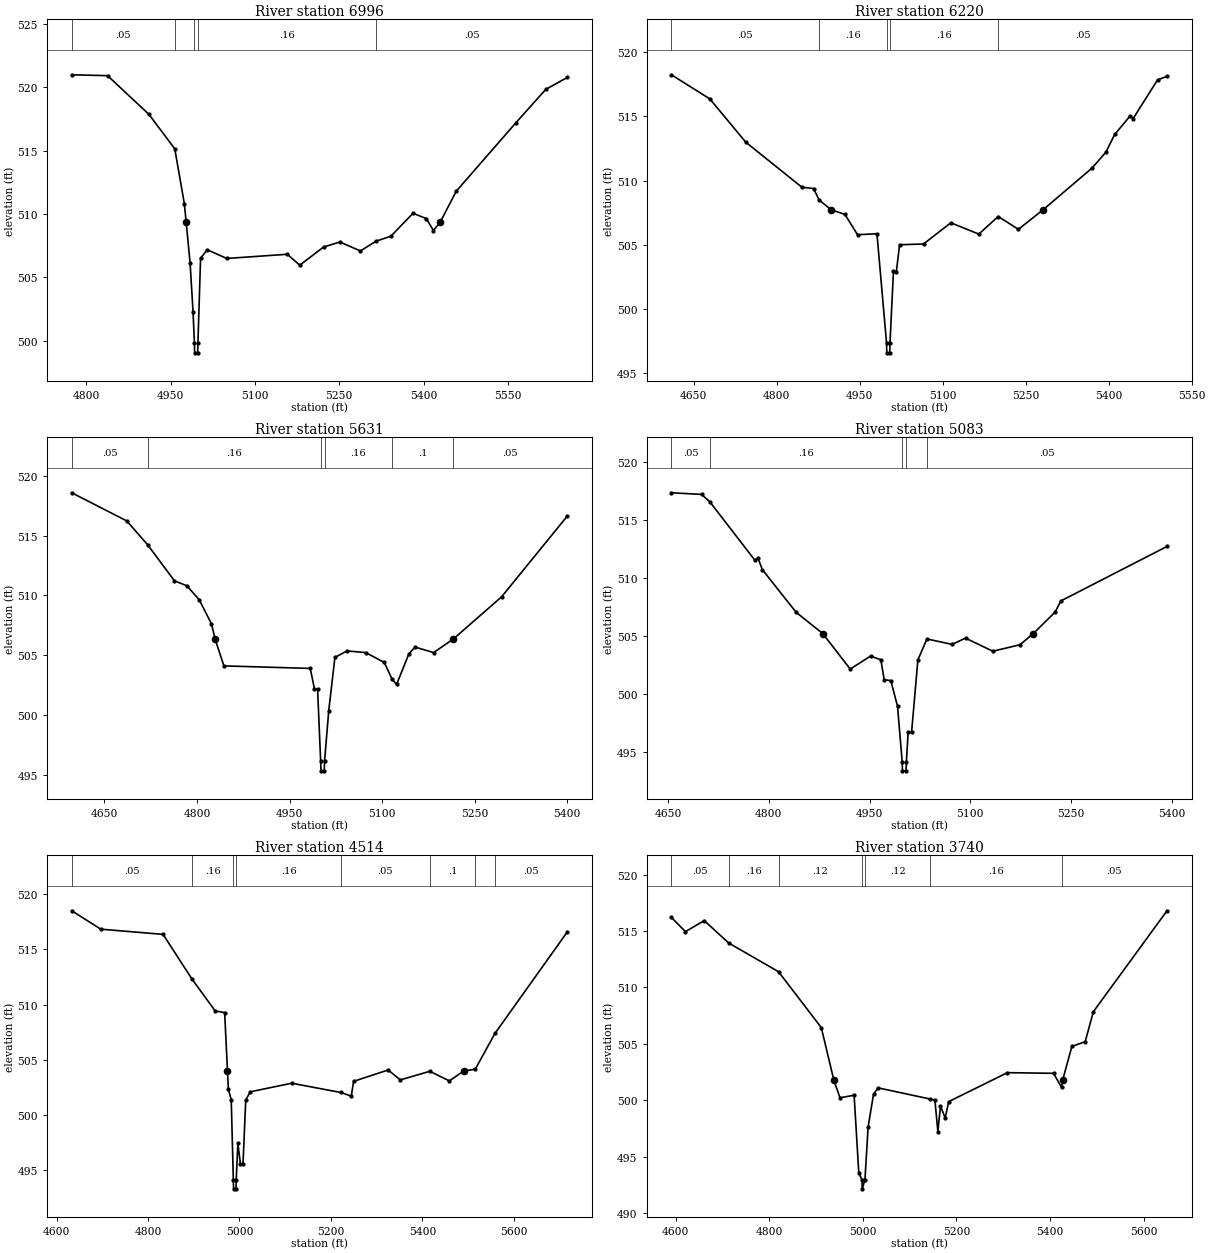
Type RM Length L Ch R = 1,6996,776,776,776
BEGIN DESCRIPTION:
UNT 027 in LFCCL Watershed 8.0
END DESCRIPTION:
XS GIS Cut Line= 3
      2788045.68      7076646.03      2787825.00      7076575.00
      2787225.03      7076325.01
#Sta/Elev= 30
  4774.1  520.98  4837.8  520.91  4911.4  517.86  4957.4  515.14  4974.4  510.83
  4977.6  509.38  4984.6  506.18  4989.9  502.30  4992.3  499.86  4992.8  499.06
  4998.1  499.06  4998.6  499.86  5003.3  506.51  5015.1  507.19  5049.8  506.50
  5157.6  506.83  5179.8  505.97  5222.1  507.40  5251.3  507.80  5287.6  507.09
  5315.8  507.87  5341.8  508.25  5381.3  510.06  5405.1  509.64  5417.6  508.70
  5429.9  509.38  5458.2  511.80  5564.4  517.20  5617.5  519.83  5655.9  520.77
#Mann=5,-1,0
  4774.1    0.05       0  4957.4    0.16       0  4992.3    0.07       0
  4998.6    0.16       0  5315.8    0.05       0
Bank Sta=4977.6,5429.9
Exp/Cntr=0.3,0.1

Type RM Length L Ch R = 1,6220,589,589,589
BEGIN DESCRIPTION:
XS3155A
END DESCRIPTION:
XS GIS Cut Line= 3
      2788122.33      7076474.99      2787821.60      7076268.61
      2787302.59      7076156.55
#Sta/Elev= 30
  4609.7  518.24  4679.2  516.36  4744.1  512.99  4845.6  509.48  4866.6  509.38
  4876.7  508.48  4898.8  507.72  4923.4  507.36  4946.1  505.78  4981.2  505.86
  4998.5  497.38  4999.0  496.58  5004.3  496.58  5004.8  497.38  5011.0  502.92
  5016.1  502.85  5022.1  505.00  5065.4  505.06  5114.7  506.71  5165.3  505.83
  5200.3  507.20  5236.9  506.20  5281.3  507.72  5369.9  510.97  5394.9  512.21
  5410.9  513.59  5439.1  515.05  5444.2  514.83  5488.3  517.84  5505.4  518.12
#Mann=5,-1,0
  4609.7    0.05       0  4876.7    0.16       0  4998.5    0.07       0
  5004.8    0.16       0  5200.3    0.05       0
Bank Sta=4898.8,5281.3
Exp/Cntr=0.3,0.1

Type RM Length L Ch R = 1,5631,548,548,548
BEGIN DESCRIPTION:
XS3156A
END DESCRIPTION:
XS GIS Cut Line= 3
      2788231.45      7075982.60      2787836.34      7075970.80
      2787428.27      7075964.93
#Sta/Elev= 30
  4597.0  518.57  4686.2  516.22  4720.0  514.23  4763.5  511.22  4783.5  510.81
  4803.5  509.65  4823.5  507.63  4829.3  506.37  4843.6  504.12  4983.6  503.91
  4990.5  502.19  4995.5  502.19  5000.5  496.16  5001.0  495.36  5006.3  495.36
  5006.8  496.16  5013.6  500.39  5023.6  504.83  5043.3  505.37  5073.6  505.23
  5103.6  504.41  5116.2  503.02  5123.6  502.57  5143.6  505.14  5153.6  505.69
  5183.6  505.23  5215.2  506.35  5215.7  506.37  5293.7  509.88  5400.4  516.63
#Mann=6,-1,0
  4597.0    0.05       0  4720.0    0.16       0  5000.5    0.07       0
  5006.8    0.16       0  5116.2     0.1       0  5215.2    0.05       0
Bank Sta=4829.3,5215.7
Exp/Cntr=0.3,0.1

Type RM Length L Ch R = 1,5083,569,569,569
BEGIN DESCRIPTION:
XS3157A
END DESCRIPTION:
XS GIS Cut Line= 3
      2788169.54      7075793.88      2787818.65      7075755.55
      2787439.12      7075817.34
#Sta/Elev= 30
  4655.2  517.36  4700.0  517.22  4712.1  516.60  4779.3  511.55  4784.3  511.69
  4790.5  510.73  4840.8  507.05  4880.5  505.21  4921.3  502.15  4951.5  503.27
  4966.9  502.95  4971.9  501.22  4981.7  501.16  4991.7  498.94  4998.6  494.17
  4999.1  493.37  5004.4  493.37  5004.9  494.17  5007.5  496.68  5012.6  496.68
  5022.0  502.94  5035.5  504.75  5072.7  504.28  5092.9  504.82  5133.5  503.69
  5174.0  504.25  5193.7  505.21  5226.1  507.06  5234.8  508.03  5392.7  512.73
#Mann=5,-1,0
  4655.2    0.05       0  4712.1    0.16       0  4998.6    0.07       0
  5004.9    0.16       0  5035.5    0.05       0
Bank Sta=4880.5,5193.7
Exp/Cntr=0.3,0.1

Type RM Length L Ch R = 1,4514,774,774,774
BEGIN DESCRIPTION:
UNT 027 in LFCCL Watershed 5.0
END DESCRIPTION:
XS GIS Cut Line= 3
      2788324.98      7075774.99      2788030.95      7075543.25
      2787325.02      7075475.00
#Sta/Elev= 30
  4633.3  518.51  4696.9  516.84  4832.9  516.37  4896.3  512.31  4946.8  509.43
  4967.6  509.27  4973.8  503.98  4975.7  502.33  4982.0  501.37  4986.6  494.09
  4987.1  493.29  4992.4  493.29  4992.9  494.09  4996.5  497.43  5002.2  495.51
  5007.7  495.51  5013.7  501.36  5023.7  502.09  5114.1  502.87  5221.5  502.03
  5244.5  501.70  5249.5  503.04  5325.1  504.07  5351.7  503.17  5416.1  503.95
  5458.9  503.08  5490.4  503.98  5515.5  504.14  5558.7  507.39  5716.9  516.60
#Mann=8,-1,0
  4633.3    0.05       0  4896.3    0.16       0  4986.6    0.07       0
  4992.9    0.16       0  5221.5    0.05       0  5416.1     0.1       0
  5515.5    0.16       0  5558.7    0.05       0
Bank Sta=4973.8,5490.4
Exp/Cntr=0.3,0.1

Type RM Length L Ch R = 1,3740,731,731,731
BEGIN DESCRIPTION:
UNT 027 in LFCCL Watershed 4.0
END DESCRIPTION:
XS GIS Cut Line= 3
      2788325.02      7075175.00      2787898.26      7075159.93
      2787325.01      7075425.00
#Sta/Elev= 30
  4591.2  516.20  4621.2  514.94  4661.3  515.92  4713.7  513.93  4820.0  511.39
  4911.4  506.43  4938.3  501.76  4951.4  500.21  4981.5  500.44  4991.5  493.53
  4998.3  492.94  4998.8  492.14  5004.6  492.94  5011.4  497.62  5022.9  500.52
  5032.8  501.09  5144.2  500.10  5154.0  500.02  5160.4  497.22  5166.0  499.48
  5176.1  498.41  5183.4  499.87  5309.0  502.44  5407.4  502.38  5424.6  501.13
  5426.8  501.76  5446.6  504.76  5475.1  505.19  5492.5  507.84  5649.8  516.79
#Mann=7,-1,0
  4591.2    0.05       0  4713.7    0.16       0  4820.0    0.12       0
  4998.3    0.07       0  5004.6    0.12       0  5144.2    0.16       0
  5424.6    0.05       0
Bank Sta=4938.3,5426.8
Exp/Cntr=0.3,0.1

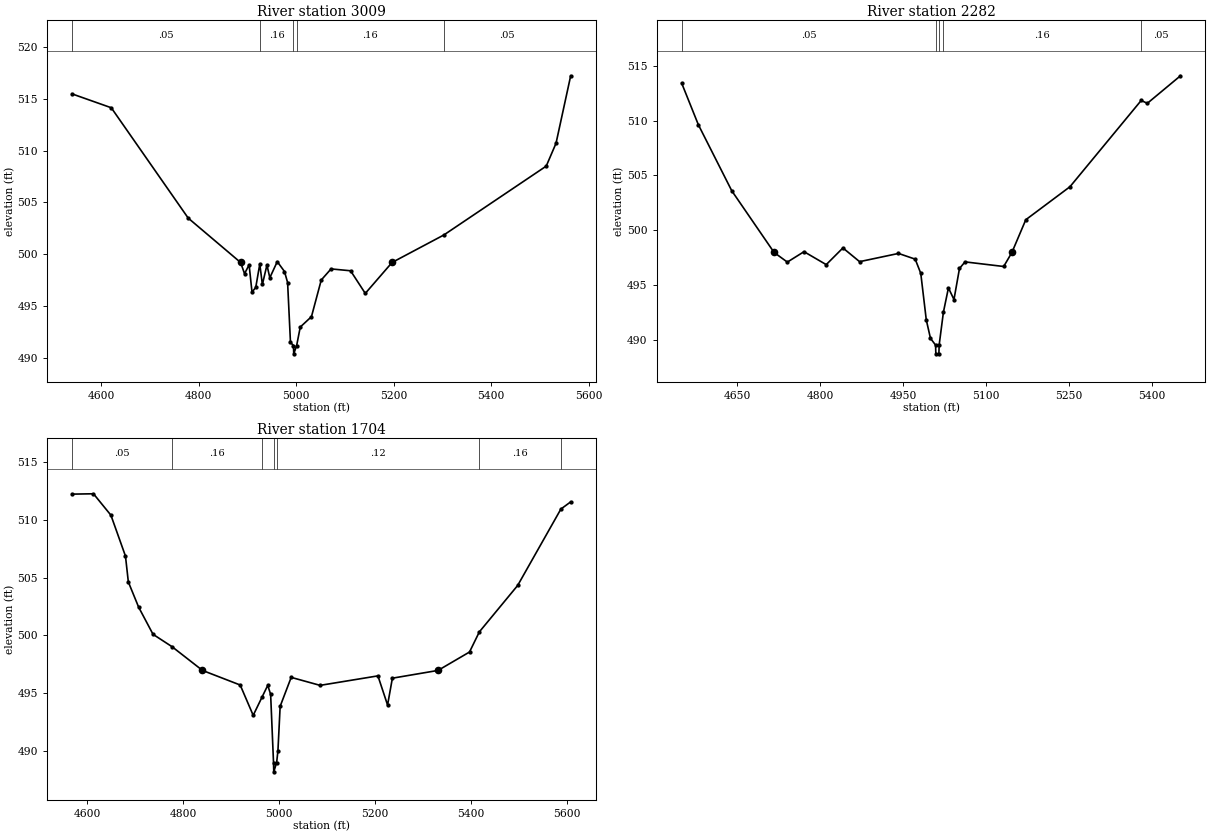
Type RM Length L Ch R = 1,3009,727,727,727
BEGIN DESCRIPTION:
UNT 027 in LFCCL Watershed 3.0
END DESCRIPTION:
XS GIS Cut Line= 3
      2788025.03      7074524.98      2787625.00      7074775.00
      2787075.00      7074825.00
#Sta/Elev= 30
  4539.4  515.46  4620.2  514.12  4778.2  503.49  4885.7  499.22  4893.8  498.14
  4903.2  498.99  4909.1  496.37  4916.8  496.81  4925.1  499.07  4930.4  497.10
  4939.8  498.97  4945.7  497.75  4961.0  499.30  4975.8  498.35  4982.2  497.29
  4988.1  491.52  4994.3  491.22  4994.8  490.42  5000.8  491.22  5008.2  493.00
  5031.2  494.00  5051.3  497.53  5071.4  498.60  5111.5  498.42  5141.7  496.24
  5196.7  499.22  5303.1  501.87  5513.2  508.50  5533.3  510.70  5563.4  517.20
#Mann=5,-1,0
  4539.4    0.05       0  4925.1    0.16       0  4994.3    0.07       0
  5000.8    0.16       0  5303.1    0.05       0
Bank Sta=4885.7,5196.7
Exp/Cntr=0.3,0.1

Type RM Length L Ch R = 1,2282,578,578,578
BEGIN DESCRIPTION:
UNT 027 in LFCCL Watershed 2.0
END DESCRIPTION:
XS GIS Cut Line= 3
      2787925.02      7074375.00      2787475.00      7074325.00
      2787024.99      7074325.00
#Sta/Elev= 30
  4549.2  513.40  4579.4  509.61  4639.8  503.60  4716.4  497.98  4740.4  497.10
  4770.6  498.05  4810.8  496.87  4841.0  498.39  4871.2  497.14  4941.6  497.89
  4971.8  497.37  4981.9  496.08  4991.9  491.83  4999.5  490.15  5008.7  489.54
  5009.2  488.74  5014.7  488.74  5015.2  489.54  5022.9  492.54  5032.0  494.75
  5042.0  493.69  5052.0  496.52  5062.0  497.12  5132.0  496.70  5146.9  497.98
  5172.0  500.96  5252.0  503.97  5380.9  511.83  5392.0  511.57  5452.0  514.08
#Mann=5,-1,0
  4549.2    0.05       0  5008.7    0.03       0  5015.2    0.05       0
  5022.9    0.16       0  5380.9    0.05       0
Bank Sta=4716.4,5146.9
Exp/Cntr=0.3,0.1

Type RM Length L Ch R = 1,1704,0,0,0
BEGIN DESCRIPTION:
UNT 027 in LFCCL Watershed 1.0
END DESCRIPTION:
XS GIS Cut Line= 3
      2788041.80      7074161.70      2787675.00      7073925.00
      2787075.03      7073975.00
#Sta/Elev= 30
  4568.5  512.21  4613.4  512.24  4649.7  510.39  4680.0  506.86  4686.0  504.62
  4707.5  502.44  4737.4  500.10  4777.0  499.03  4840.4  496.98  4918.9  495.72
  4946.0  493.10  4964.2  494.66  4976.3  495.69  4982.3  494.91  4988.3  489.02
  4988.8  488.22  4994.8  489.02  4997.5  490.04  5002.1  493.88  5025.1  496.38
  5085.3  495.69  5205.7  496.51  5225.8  493.99  5235.8  496.31  5330.8  496.98
  5396.4  498.57  5416.9  500.31  5496.7  504.32  5586.7  510.92  5607.1  511.54
#Mann=7,-1,0
  4568.5    0.05       0  4777.0    0.16       0  4964.2    0.12       0
  4988.3    0.07       0  4994.8    0.12       0  5416.9    0.16       0
  5586.7    0.05       0
Bank Sta=4840.4,5330.8
Exp/Cntr=0.3,0.1

Chan Stop Cuts=-1