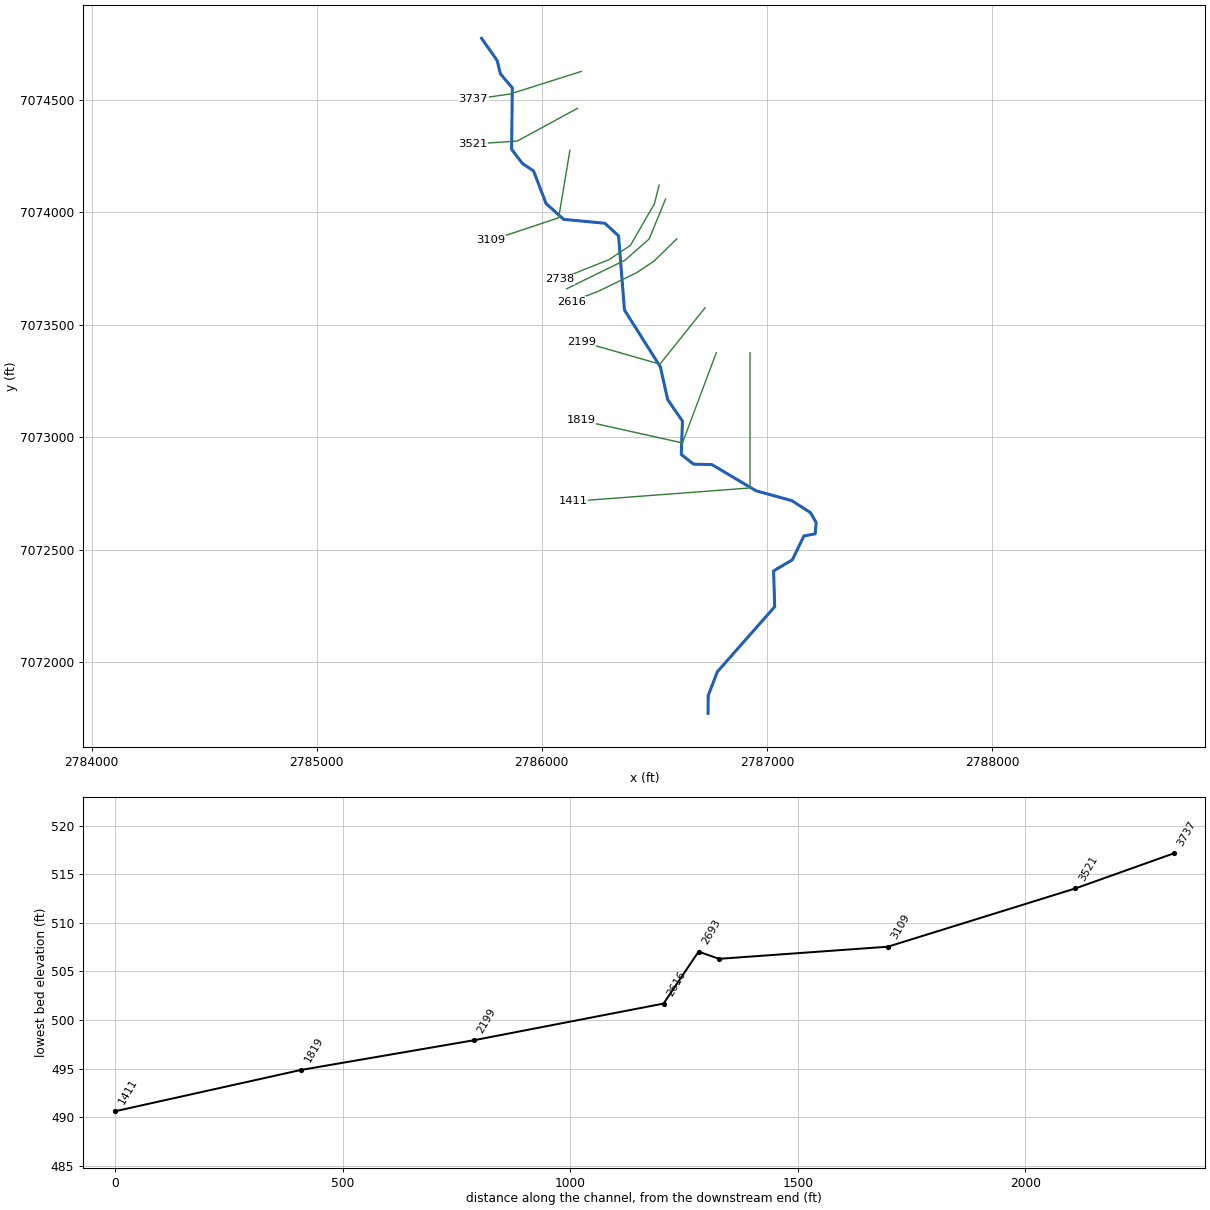
--- UNT 028 in LFCCL Watershed.prj (project) ---

Proj Title=UNT 028 in LFCCL Watershed Base Level Engineering
Current Plan=p01
Default Exp/Contr=0.3,0.1
English Units
Geom File=g01
Flow File=f01
Plan File=p01
BEGIN DESCRIPTION:
UNT 028 in LFCCL Watershed
END DESCRIPTION:

--- UNT 028 in LFCCL Watershed.p01 (plan) ---

Plan Title=Multiple Run
Short Identifier=Multiple
Geom File=g01
Flow File=f01
Subcritical Flow
K Sum by GR= 0
Std Step Tol= 0.01
Critical Tol= 0.01
Num of Std Step Trials= 20
Max Error Tol= 0.3
Flow Tol Ratio= 0.001
Split Flow NTrial= 30
Split Flow Tol= 0.02
Split Flow Ratio= 0.02
Log Output Level= 0
Friction Slope Method= 1
Unsteady Friction Slope Method= 2
Unsteady Bridges Friction Slope Method= 1
Parabolic Critical Depth
Global Vel Dist=  1 , 1 , 1
Global Log Level= 0
CheckData=True
Encroach Param= -1, 0, 0, 0
BEGIN DESCRIPTION:
Multiple Run
END DESCRIPTION:

--- UNT 028 in LFCCL Watershed.f01 (steady flow) ---

Flow Title=Multiple
Number of Profiles=7
Profile Names=10-year,25-year,50-year,1pct_min,100-year,1pct_plu,500-year
River Rch & RM= UNT 028 in LFCCL,Reach-1,3737
     229     285     326     187     372     743     481
Boundary for River Rch & Prof#=UNT 028 in LFCCL,Reach-1,1
Up Type=0
Dn Type=3
Dn Slope=0.005
Boundary for River Rch & Prof#=UNT 028 in LFCCL,Reach-1,2
Up Type=0
Dn Type=3
Dn Slope=0.005
Boundary for River Rch & Prof#=UNT 028 in LFCCL,Reach-1,3
Up Type=0
Dn Type=3
Dn Slope=0.005
Boundary for River Rch & Prof#=UNT 028 in LFCCL,Reach-1,4
Up Type=0
Dn Type=3
Dn Slope=0.005
Boundary for River Rch & Prof#=UNT 028 in LFCCL,Reach-1,5
Up Type=0
Dn Type=3
Dn Slope=0.005
Boundary for River Rch & Prof#=UNT 028 in LFCCL,Reach-1,6
Up Type=0
Dn Type=3
Dn Slope=0.005
Boundary for River Rch & Prof#=UNT 028 in LFCCL,Reach-1,7
Up Type=0
Dn Type=3
Dn Slope=0.005

--- UNT 028 in LFCCL Watershed.g01 (geometry) ---

Geom Title=Existing Conditions

River Reach=UNT 028 in LFCCL,Reach-1
Reach XY= 30
      2785732.52      7074772.14      2785801.97      7074673.39
      2785816.07      7074614.80      2785869.24      7074551.87
      2785865.99      7074279.51      2785913.73      7074216.58
      2785963.64      7074182.94      2786018.98      7074038.63
      2786097.11      7073968.10      2786280.48      7073950.74
      2786341.25      7073894.31      2786367.29      7073565.54
      2786526.79      7073312.72      2786559.35      7073167.32
      2786624.88      7073072.05      2786619.68      7072923.61
      2786674.36      7072880.64      2786755.61      7072878.91
      2786952.14      7072762.24      2787111.17      7072718.49
      2787193.11      7072665.71      2787218.81      7072621.96
      2787214.51      7072570.98      2787164.51      7072561.96
      2787113.12      7072455.71      2787029.79      7072406.40
      2787034.65      7072247.37      2786780.08      7071958.66
      2786739.28      7071852.76      2786738.65      7071773.67

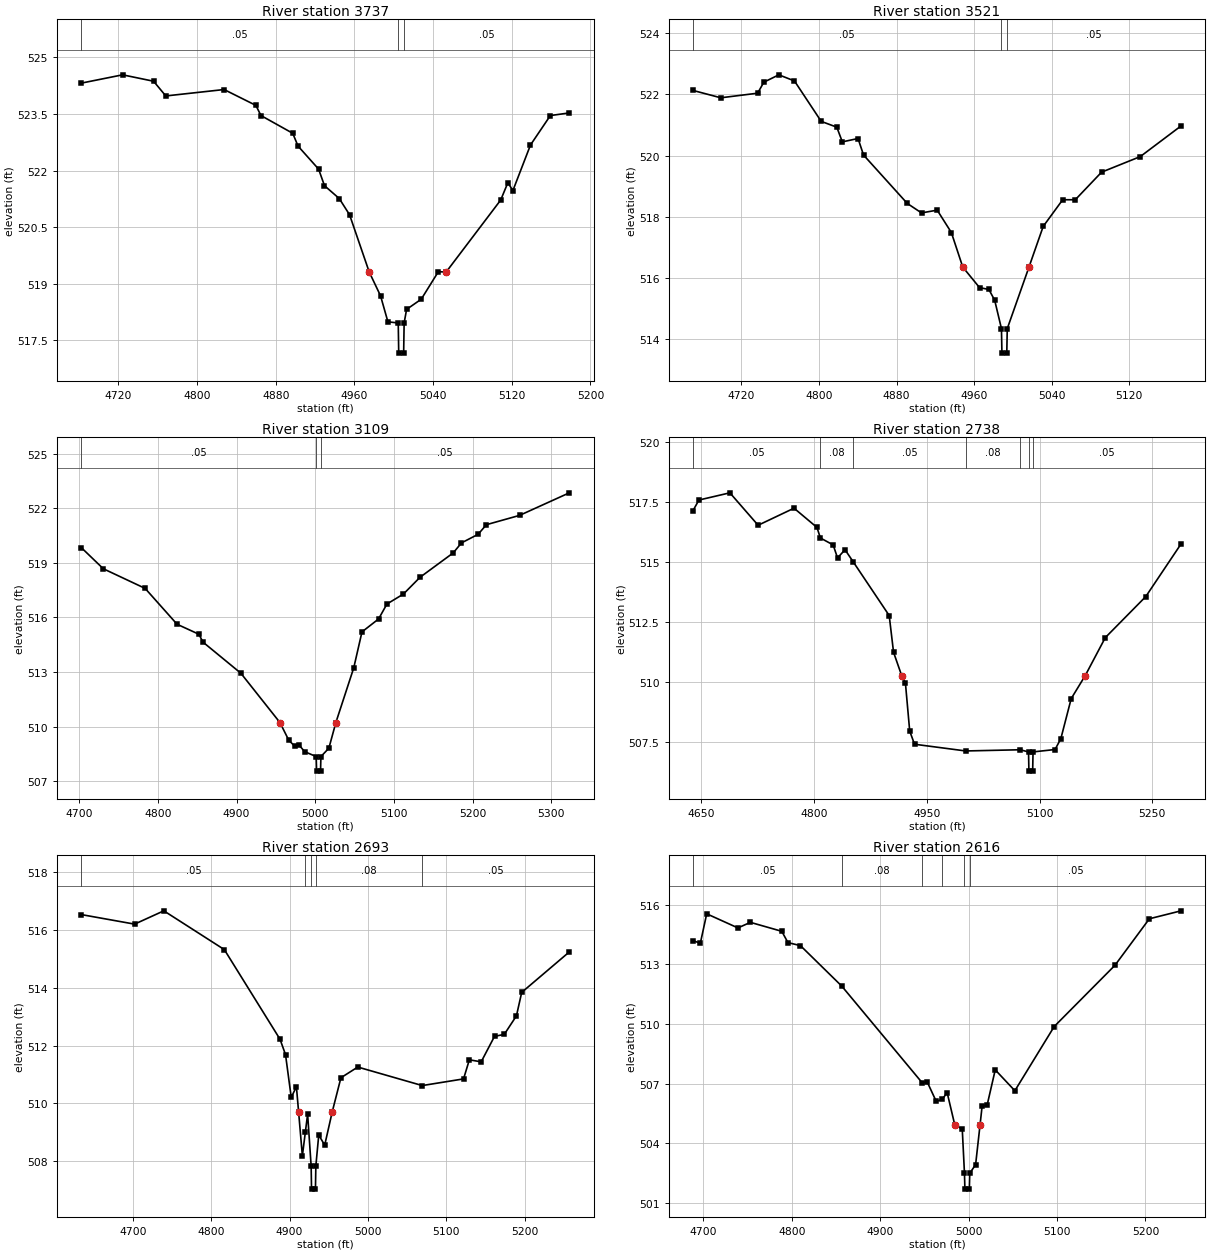
Type RM Length L Ch R = 1,3737,216,216,216
BEGIN DESCRIPTION:
UNT 028 in LFCCL Watershed 7.0
END DESCRIPTION:
XS GIS Cut Line= 3
      2786175.03      7074625.01      2785859.49      7074524.86
      2785695.91      7074501.49
#Sta/Elev= 30
  4682.2  524.32  4724.2  524.54  4755.7  524.37  4768.1  523.98  4827.4  524.15
  4859.7  523.73  4864.9  523.46  4897.2  522.99  4902.6  522.65  4923.5  522.04
  4929.5  521.60  4944.5  521.26  4955.0  520.83  4975.0  519.31  4986.5  518.68
  4994.0  517.99  5004.5  517.96  5005.0  517.16  5010.0  517.16  5010.5  517.96
  5013.0  518.32  5027.9  518.59  5045.3  519.32  5053.2  519.31  5108.7  521.22
  5116.0  521.68  5121.1  521.47  5139.0  522.68  5159.2  523.46  5178.5  523.53
#Mann=3,-1,0
  4682.2    0.05       0  5004.5    0.03       0  5010.5    0.05       0
Bank Sta=4975,5053.2
Exp/Cntr=0.3,0.1

Type RM Length L Ch R = 1,3521,412,412,412
BEGIN DESCRIPTION:
XS3158A
END DESCRIPTION:
XS GIS Cut Line= 3
      2786159.23      7074461.55      2785891.01      7074315.72
      2785693.14      7074302.70
#Sta/Elev= 30
  4670.0  522.13  4698.7  521.89  4736.7  522.04  4743.1  522.40  4758.6  522.64
  4774.7  522.44  4802.3  521.12  4818.4  520.93  4824.1  520.45  4840.3  520.56
  4846.0  520.02  4891.1  518.44  4905.8  518.13  4922.0  518.22  4936.6  517.49
  4948.4  516.36  4965.7  515.69  4975.3  515.63  4981.3  515.28  4988.3  514.35
  4988.8  513.55  4993.8  513.55  4994.3  514.35  5016.7  516.36  5031.4  517.69
  5051.5  518.56  5064.5  518.56  5091.6  519.46  5131.6  519.97  5173.6  520.97
#Mann=3,-1,0
  4670.0    0.05       0  4988.3    0.03       0  4994.3    0.05       0
Bank Sta=4948.4,5016.7
Exp/Cntr=0.3,0.1

Type RM Length L Ch R = 1,3109,371,371,371
BEGIN DESCRIPTION:
UNT 028 in LFCCL Watershed 6.0
END DESCRIPTION:
XS GIS Cut Line= 3
      2786125.00      7074275.00      2786075.00      7073975.00
      2785774.97      7073874.99
#Sta/Elev= 30
  4702.6  519.83  4730.5  518.67  4783.7  517.59  4824.3  515.62  4852.1  515.07
  4857.2  514.64  4905.4  512.93  4955.1  510.22  4966.2  509.26  4973.8  508.92
  4978.9  509.01  4986.5  508.62  5001.2  508.35  5001.7  507.55  5006.7  507.55
  5007.2  508.35  5017.3  508.81  5026.2  510.22  5048.9  513.22  5059.4  515.20
  5080.5  515.91  5091.1  516.73  5112.1  517.28  5133.2  518.20  5175.4  519.54
  5185.9  520.09  5207.0  520.56  5217.6  521.09  5259.7  521.60  5323.0  522.84
#Mann=3,-1,0
  4702.6    0.05       0  5001.2    0.03       0  5007.2    0.05       0
Bank Sta=4955.1,5026.2
Exp/Cntr=0.3,0.1

Type RM Length L Ch R = 1,2738,45,45,45
BEGIN DESCRIPTION:
XS3160A
END DESCRIPTION:
XS GIS Cut Line= 5
      2786521.23      7074120.44      2786500.38      7074037.07
      2786393.61      7073852.18      2786299.86      7073789.68
      2786079.27      7073701.44
#Sta/Elev= 30
  4638.7  517.15  4646.6  517.59  4687.8  517.89  4725.4  516.54  4773.2  517.25
  4803.7  516.45  4808.3  516.01  4825.3  515.72  4831.1  515.18  4841.1  515.52
  4851.7  515.03  4899.9  512.78  4905.7  511.25  4916.5  510.28  4921.5  509.97
  4927.2  507.97  4933.6  507.42  5001.7  507.14  5074.2  507.19  5085.4  507.10
  5085.9  506.30  5090.9  506.30  5091.4  507.10  5120.7  507.20  5128.4  507.65
  5142.2  509.32  5160.9  510.28  5187.6  511.86  5241.5  513.57  5288.4  515.76
#Mann=7,-1,0
  4638.7    0.05       0  4808.3    0.08       0  4851.7    0.05       0
  5001.7    0.08       0  5074.2    0.05       0  5085.4    0.03       0
  5091.4    0.05       0
Bank Sta=4916.5,5160.9
Exp/Cntr=0.3,0.1

Type RM Length L Ch R = 1,2693,77,77,77
BEGIN DESCRIPTION:
XS3159A
END DESCRIPTION:
XS GIS Cut Line= 4
      2786549.85      7074057.88      2786476.95      7073880.82
      2786370.18      7073787.07      2786110.44      7073659.81
#Sta/Elev= 30
  4634.3  516.53  4702.3  516.20  4739.6  516.66  4816.8  515.32  4887.9  512.22
  4894.9  511.69  4902.2  510.21  4908.8  510.58  4911.6  509.71  4916.4  508.19
  4920.2  509.01  4923.1  509.63  4927.6  507.84  4928.1  507.04  4933.1  507.04
  4933.6  507.84  4937.3  508.91  4944.9  508.56  4954.5  509.71  4965.6  510.89
  4987.1  511.26  5069.4  510.62  5122.1  510.85  5129.5  511.51  5144.6  511.44
  5161.6  512.32  5174.1  512.39  5189.6  513.03  5196.3  513.84  5257.1  515.24
#Mann=5,-1,0
  4634.3    0.05       0  4920.2    0.08       0  4927.6    0.07       0
  4933.6    0.08       0  5069.4    0.05       0
Bank Sta=4911.6,4954.5
Exp/Cntr=0.3,0.1

Type RM Length L Ch R = 1,2616,417,417,417
BEGIN DESCRIPTION:
Mapping XS 784f17db
END DESCRIPTION:
XS GIS Cut Line= 5
      2786600.18      7073881.71      2786498.65      7073782.78
      2786420.52      7073730.69      2786248.65      7073647.36
      2786131.50      7073603.10
#Sta/Elev= 30
  4688.3  514.19  4696.6  514.06  4703.8  515.54  4739.1  514.83  4753.2  515.11
  4788.7  514.66  4795.7  514.09  4809.8  513.94  4856.6  511.90  4947.3  507.05
  4953.2  507.08  4963.4  506.10  4970.3  506.21  4975.7  506.55  4984.4  504.91
  4992.8  504.72  4995.3  502.49  4995.8  501.69  5000.8  501.69  5001.3  502.49
  5007.9  502.92  5012.9  504.91  5015.3  505.88  5020.9  505.91  5030.1  507.69
  5052.3  506.64  5096.8  509.87  5165.5  512.95  5204.4  515.29  5240.2  515.69
#Mann=6,-1,0
  4688.3    0.05       0  4856.6    0.08       0  4947.3    0.16       0
  4970.3    0.05       0  4995.3    0.04       0  5001.3    0.05       0
Bank Sta=4984.4,5012.9
Exp/Cntr=0.3,0.1

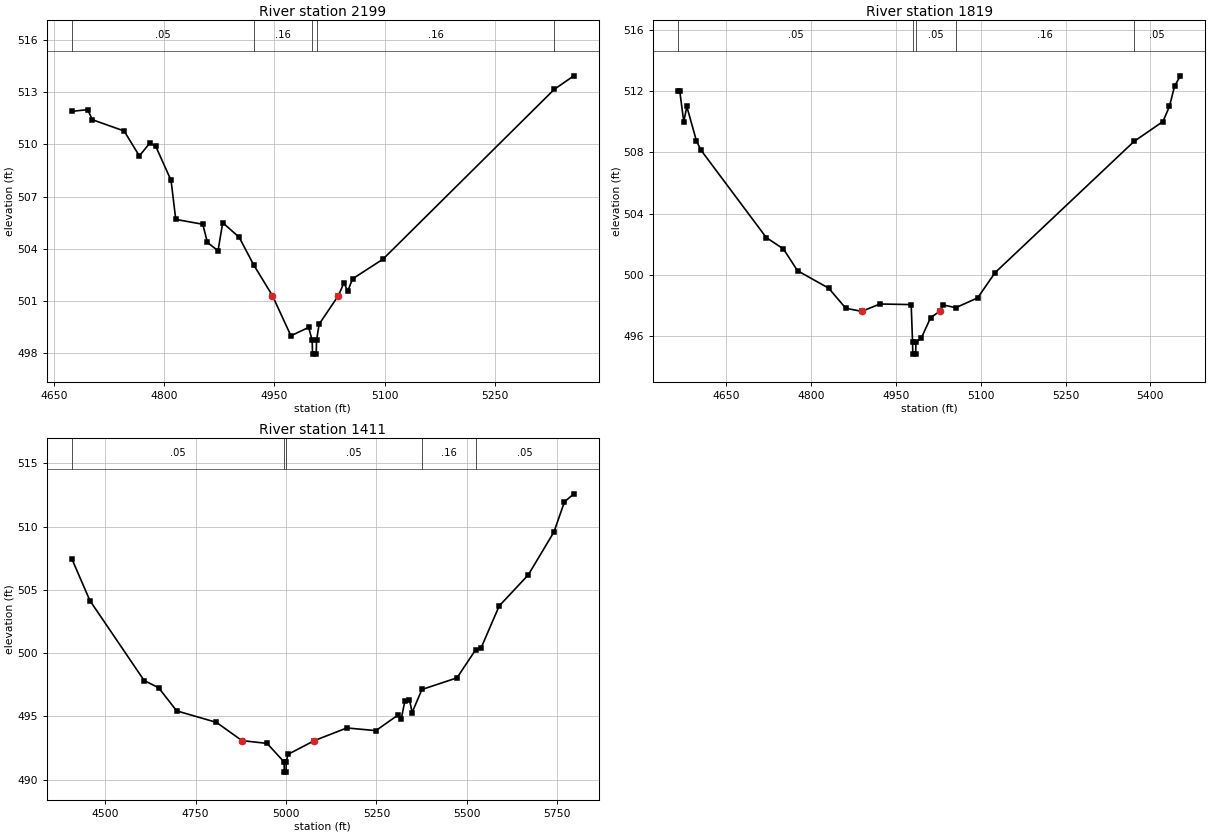
Type RM Length L Ch R = 1,2199,380,380,380
BEGIN DESCRIPTION:
UNT 028 in LFCCL Watershed 3.0
END DESCRIPTION:
XS GIS Cut Line= 3
      2786725.02      7073575.03      2786525.00      7073325.00
      2786174.99      7073425.00
#Sta/Elev= 30
  4673.8  511.91  4695.4  512.01  4701.8  511.43  4745.1  510.78  4765.9  509.34
  4780.3  510.09  4788.3  509.89  4809.1  507.93  4815.5  505.68  4852.3  505.40
  4858.7  504.35  4873.1  503.87  4879.5  505.49  4901.9  504.65  4921.8  503.05
  4947.3  501.28  4972.4  498.97  4996.6  499.45  5001.4  498.71  5001.9  497.91
  5006.9  497.91  5007.4  498.71  5010.9  499.64  5037.1  501.28  5044.7  502.02
  5049.9  501.54  5056.4  502.25  5098.0  503.39  5331.3  513.18  5358.0  513.96
#Mann=5,-1,0
  4673.8    0.05       0  4921.8    0.16       0  5001.4    0.07       0
  5007.4    0.16       0  5331.3    0.05       0
Bank Sta=4947.3,5037.1
Exp/Cntr=0.3,0.1

Type RM Length L Ch R = 1,1819,408,408,408
BEGIN DESCRIPTION:
UNT 028 in LFCCL Watershed 2.0
END DESCRIPTION:
XS GIS Cut Line= 3
      2786775.02      7073375.04      2786625.00      7072975.00
      2786175.02      7073075.00
#Sta/Elev= 30
  4564.7  512.00  4567.4  512.00  4574.5  510.00  4579.9  511.00  4596.8  508.77
  4604.8  508.16  4720.5  502.45  4750.8  501.71  4775.7  500.29  4830.9  499.15
  4861.1  497.84  4889.3  497.64  4921.6  498.12  4976.8  498.08  4979.2  495.65
  4979.7  494.85  4984.7  494.85  4985.2  495.65  4994.5  495.88  5011.2  497.23
  5027.3  497.64  5032.9  498.06  5055.8  497.88  5094.4  498.52  5125.1  500.16
  5371.0  508.72  5422.2  510.02  5433.7  511.01  5442.7  512.32  5452.9  513.00
#Mann=5,-1,0
  4564.7    0.05       0  4979.2    0.03       0  4985.2    0.05       0
  5055.8    0.16       0  5371.0    0.05       0
Bank Sta=4889.3,5027.3
Exp/Cntr=0.3,0.1

Type RM Length L Ch R = 1,1411,0,0,0
BEGIN DESCRIPTION:
UNT 028 in LFCCL Watershed 1.0
END DESCRIPTION:
XS GIS Cut Line= 3
      2786925.00      7073374.97      2786925.00      7072775.00
      2786139.22      7072715.52
#Sta/Elev= 30
  4407.9  507.47  4457.9  504.16  4607.9  497.84  4647.9  497.27  4697.9  495.44
  4807.9  494.53  4878.4  493.09  4947.9  492.87  4994.9  491.40  4995.4  490.60
  5000.4  490.60  5000.9  491.40  5005.4  492.00  5078.6  493.09  5168.3  494.09
  5248.6  493.88  5308.7  495.09  5318.8  494.81  5328.8  496.23  5341.5  496.32
  5348.8  495.31  5375.9  497.13  5472.9  498.05  5524.2  500.26  5539.4  500.41
  5589.5  503.73  5669.8  506.18  5740.8  509.57  5770.0  511.96  5795.9  512.59
#Mann=5,-1,0
  4407.9    0.05       0  4994.9    0.03       0  5000.9    0.05       0
  5375.9    0.16       0  5524.2    0.05       0
Bank Sta=4878.4,5078.6
Exp/Cntr=0.3,0.1

Chan Stop Cuts=-1