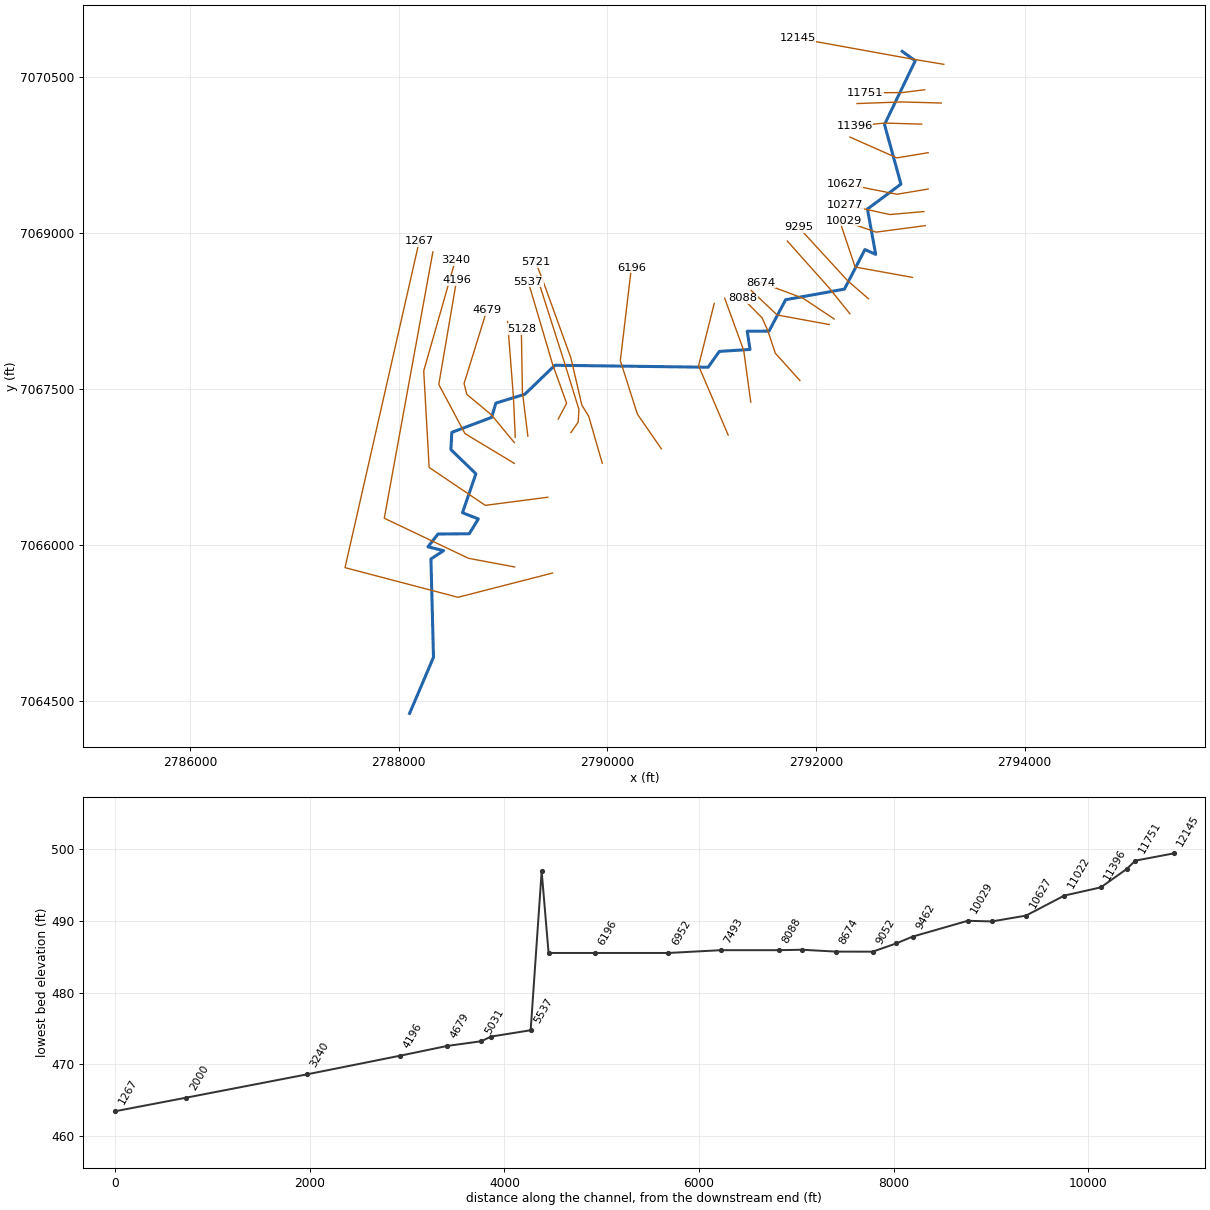
--- UNT 029 in LFCCL Watershed.prj (project) ---

Proj Title=UNT 029 in LFCCL Watershed Base Level Engineering
Current Plan=p01
Default Exp/Contr=0.3,0.1
English Units
Geom File=g01
Flow File=f01
Plan File=p01
BEGIN DESCRIPTION:
UNT 029 in LFCCL Watershed
END DESCRIPTION:

--- UNT 029 in LFCCL Watershed.p01 (plan) ---

Plan Title=Multiple Run
Short Identifier=Multiple
Geom File=g01
Flow File=f01
Subcritical Flow
K Sum by GR= 0
Std Step Tol= 0.01
Critical Tol= 0.01
Num of Std Step Trials= 20
Max Error Tol= 0.3
Flow Tol Ratio= 0.001
Split Flow NTrial= 30
Split Flow Tol= 0.02
Split Flow Ratio= 0.02
Log Output Level= 0
Friction Slope Method= 1
Unsteady Friction Slope Method= 2
Unsteady Bridges Friction Slope Method= 1
Parabolic Critical Depth
Global Vel Dist=  1 , 1 , 1
Global Log Level= 0
CheckData=True
Encroach Param= -1, 0, 0, 0
BEGIN DESCRIPTION:
Multiple Run
END DESCRIPTION:

--- UNT 029 in LFCCL Watershed.f01 (steady flow) ---

Flow Title=Multiple
Program Version=5.07
Number of Profiles= 7
Profile Names=10-year,25-year,50-year,1pct_min,100-year,1pct_plu,500-year
River Rch & RM=UNT 029 in LFCCL,Reach-1         ,12145
     533     697     827     486     970    1936    1333
River Rch & RM=UNT 029 in LFCCL,Reach-1         ,8088
     685     908    1086     644    1284    2562    1792
River Rch & RM=UNT 029 in LFCCL,Reach-1         ,5721
     864    1160    1400     836    1669    3330    2367
Boundary for River Rch & Prof#=UNT 029 in LFCCL,Reach-1         , 1
Up Type= 0
Dn Type= 3
Dn Slope=0.005
Boundary for River Rch & Prof#=UNT 029 in LFCCL,Reach-1         , 2
Up Type= 0
Dn Type= 3
Dn Slope=0.005
Boundary for River Rch & Prof#=UNT 029 in LFCCL,Reach-1         , 3
Up Type= 0
Dn Type= 3
Dn Slope=0.005
Boundary for River Rch & Prof#=UNT 029 in LFCCL,Reach-1         , 4
Up Type= 0
Dn Type= 3
Dn Slope=0.005
Boundary for River Rch & Prof#=UNT 029 in LFCCL,Reach-1         , 5
Up Type= 0
Dn Type= 3
Dn Slope=0.005
Boundary for River Rch & Prof#=UNT 029 in LFCCL,Reach-1         , 6
Up Type= 0
Dn Type= 3
Dn Slope=0.005
Boundary for River Rch & Prof#=UNT 029 in LFCCL,Reach-1         , 7
Up Type= 0
Dn Type= 3
Dn Slope=0.005
DSS Import GetInterval= 0
DSS Import GetPeak= 0
DSS Import FillOption= 0

--- UNT 029 in LFCCL Watershed.g01 (geometry) ---

Geom Title=Existing Conditions

River Reach=UNT 029 in LFCCL,Reach-1
Reach XY= 30
      2792826.33      7070749.35      2792951.48      7070659.33
      2792656.65      7070045.87      2792814.24      7069472.60
      2792493.02      7069232.89      2792572.13      7068796.60
      2792469.05      7068843.35      2792272.48      7068462.20
      2791709.15      7068360.32      2791549.74      7068058.28
      2791341.18      7068057.08      2791367.55      7067882.09
      2791073.90      7067862.91      2790966.03      7067710.69
      2789497.77      7067729.87      2789210.42      7067451.25
      2788932.22      7067365.68      2788891.76      7067228.62
      2788510.23      7067084.07      2788501.39      7066918.43
      2788740.93      7066685.85      2788612.35      7066311.26
      2788764.35      7066251.39      2788677.07      7066108.76
      2788377.52      7066106.10      2788281.46      7065982.94
      2788431.67      7065946.03      2788310.02      7065866.16
      2788334.56      7064920.66      2788105.59      7064380.71

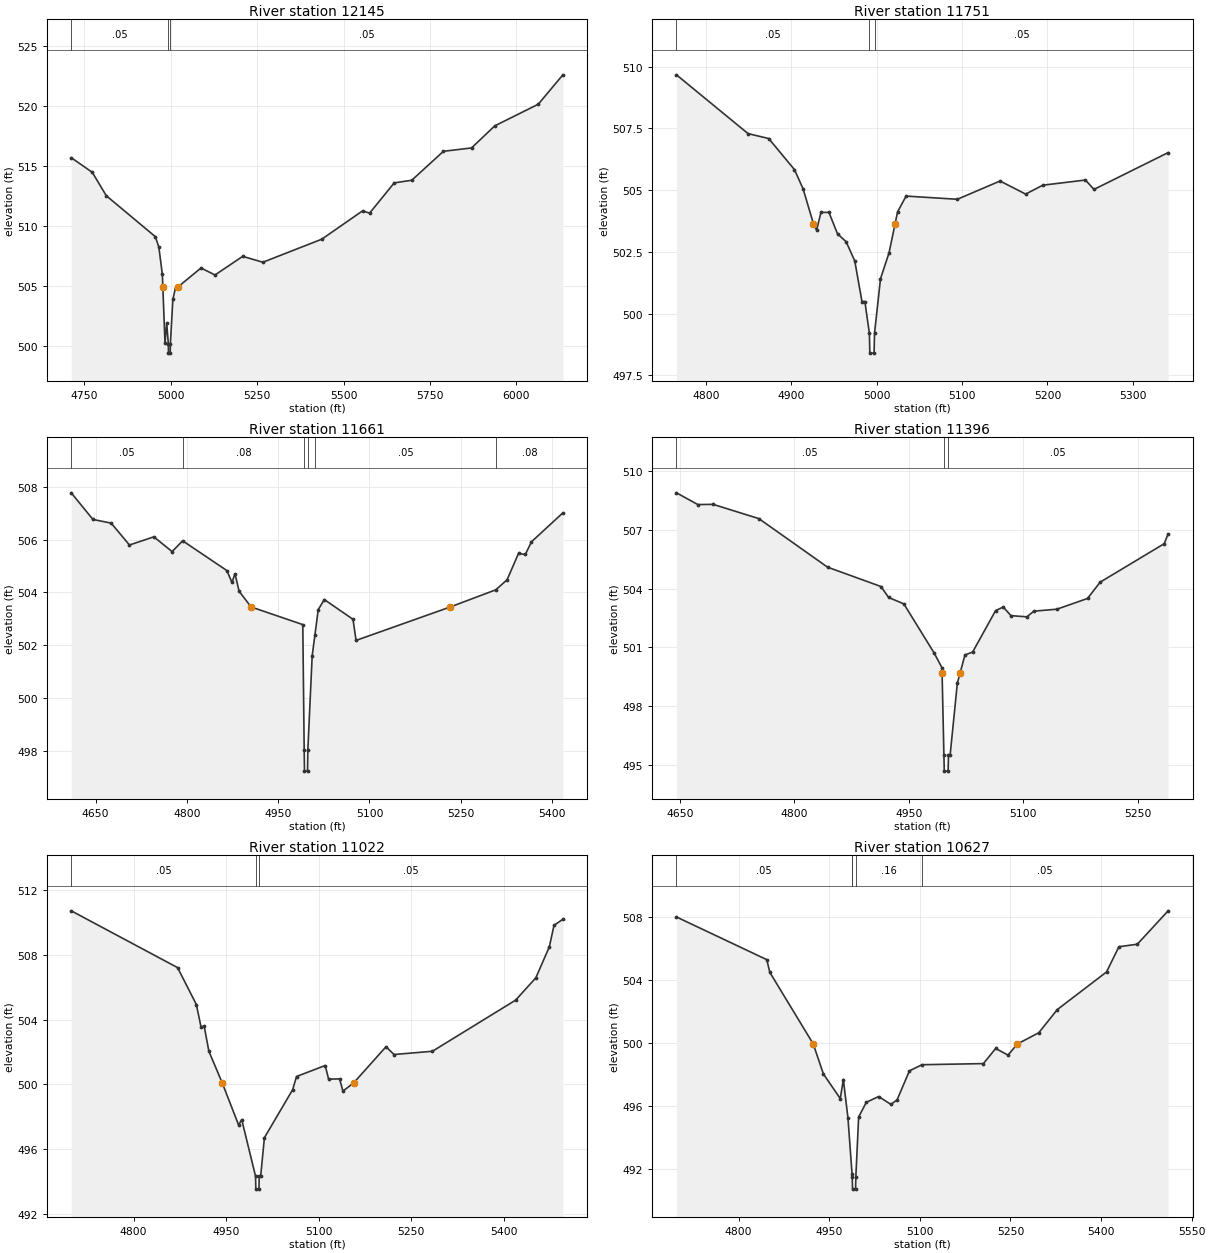
Type RM Length L Ch R = 1,12145,394,394,394
BEGIN DESCRIPTION:
UNT 029 in LFCCL Watershed 19.0
END DESCRIPTION:
XS GIS Cut Line= 3
      2793224.99      7070625.00      2792925.00      7070675.00
      2791824.96      7070875.01
#Sta/Elev= 30
  4712.0  515.69  4772.8  514.47  4813.4  512.52  4955.3  509.11  4965.4  508.24
  4975.6  505.96  4976.9  504.95  4983.2  500.27  4988.2  501.90  4992.8  500.21
  4993.3  499.41  4998.3  499.41  4998.8  500.21  5006.0  503.89  5013.6  504.85
  5021.9  504.95  5087.3  506.50  5127.9  505.92  5208.0  507.47  5266.4  506.98
  5436.7  508.90  5554.8  511.26  5575.1  511.07  5646.3  513.59  5697.1  513.81
  5788.6  516.22  5869.9  516.50  5937.2  518.34  6063.0  520.14  6134.2  522.59
#Mann=3,-1,0
  4712.0    0.05       0  4992.8    0.03       0  4998.8    0.05       0
Bank Sta=4976.9,5021.9
Exp/Cntr=0.3,0.1

Type RM Length L Ch R = 1,11751,90,90,90
BEGIN DESCRIPTION:
UNT 029 in LFCCL Watershed 18.0
END DESCRIPTION:
XS GIS Cut Line= 3
      2793042.15      7070380.61      2792823.27      7070353.02
      2792468.18      7070351.19
#Sta/Elev= 30
  4765.6  509.67  4849.4  507.29  4873.6  507.09  4903.8  505.83  4913.9  505.05
  4926.0  503.64  4929.7  503.38  4934.8  504.10  4944.1  504.10  4954.2  503.23
  4964.3  502.91  4974.4  502.13  4982.8  500.49  4986.2  500.49  4991.5  499.20
  4992.0  498.40  4997.0  498.40  4997.5  499.20  5004.5  501.41  5014.5  502.46
  5021.6  503.64  5024.5  504.12  5034.5  504.76  5094.5  504.63  5144.5  505.37
  5174.5  504.84  5194.5  505.20  5244.5  505.41  5254.5  505.03  5341.3  506.52
#Mann=3,-1,0
  4765.6    0.05       0  4991.5    0.03       0  4997.5    0.05       0
Bank Sta=4926,5021.6
Exp/Cntr=0.3,0.1

Type RM Length L Ch R = 1,11661,265,265,265
BEGIN DESCRIPTION:
XS3162A
END DESCRIPTION:
XS GIS Cut Line= 3
      2793200.60      7070252.68      2792820.37      7070263.10
      2792393.33      7070247.47
#Sta/Elev= 30
  4610.1  507.78  4645.7  506.77  4675.7  506.63  4705.7  505.80  4745.8  506.11
  4775.8  505.55  4793.1  505.96  4865.8  504.83  4874.1  504.38  4879.1  504.71
  4885.8  504.05  4905.5  503.45  4990.5  502.78  4992.8  498.02  4993.3  497.22
  4998.3  497.22  4998.8  498.02  5005.9  501.59  5010.5  502.40  5015.9  503.35
  5025.9  503.73  5073.0  502.98  5078.0  502.18  5232.9  503.45  5307.6  504.10
  5326.1  504.48  5344.9  505.48  5356.1  505.44  5366.1  505.92  5417.8  507.02
#Mann=6,-1,0
  4610.1    0.05       0  4793.1    0.08       0  4992.8    0.07       0
  4998.8    0.08       0  5010.5    0.05       0  5307.6    0.08       0
Bank Sta=4905.5,5232.9
Exp/Cntr=0.3,0.1

Type RM Length L Ch R = 1,11396,374,374,374
BEGIN DESCRIPTION:
XS3163A
END DESCRIPTION:
XS GIS Cut Line= 3
      2793013.03      7070049.56      2792658.91      7070059.97
      2792369.90      7070031.33
#Sta/Elev= 30
  4645.4  508.90  4673.4  508.30  4693.5  508.31  4753.5  507.58  4843.5  505.10
  4913.5  504.11  4923.6  503.55  4943.6  503.22  4983.6  500.69  4993.6  499.95
  4993.7  499.70  4996.1  495.47  4996.6  494.67  5001.6  494.67  5002.1  495.47
  5004.2  495.47  5013.7  499.17  5017.4  499.70  5023.7  500.61  5033.8  500.76
  5063.9  502.88  5073.9  503.06  5084.0  502.62  5104.9  502.56  5114.1  502.85
  5144.3  502.95  5184.5  503.50  5200.9  504.33  5285.0  506.30  5290.1  506.80
#Mann=3,-1,0
  4645.4    0.05       0  4996.1    0.03       0  5002.1    0.05       0
Bank Sta=4993.7,5017.4
Exp/Cntr=0.3,0.1

Type RM Length L Ch R = 1,11022,395,395,395
BEGIN DESCRIPTION:
UNT 029 in LFCCL Watershed 16.0
END DESCRIPTION:
XS GIS Cut Line= 3
      2793074.98      7069775.00      2792775.00      7069725.00
      2792324.97      7069925.01
#Sta/Elev= 30
  4699.1  510.73  4871.4  507.22  4901.8  504.94  4909.4  503.55  4914.5  503.60
  4922.1  502.05  4943.8  500.09  4970.3  497.49  4975.3  497.83  4997.7  494.33
  4998.2  493.53  5003.2  493.53  5003.7  494.33  5006.0  494.33  5012.1  496.71
  5057.9  499.68  5064.1  500.49  5110.6  501.17  5116.1  500.33  5133.9  500.34
  5139.3  499.59  5156.6  500.09  5209.1  502.33  5222.1  501.85  5284.3  502.05
  5419.1  505.21  5451.9  506.59  5473.8  508.51  5481.3  509.83  5495.7  510.21
#Mann=3,-1,0
  4699.1    0.05       0  4997.7    0.03       0  5003.7    0.05       0
Bank Sta=4943.8,5156.6
Exp/Cntr=0.3,0.1

Type RM Length L Ch R = 1,10627,350,350,350
BEGIN DESCRIPTION:
UNT 029 in LFCCL Watershed 15.0
END DESCRIPTION:
XS GIS Cut Line= 3
      2793075.00      7069425.00      2792775.00      7069375.00
      2792275.04      7069474.99
#Sta/Elev= 30
  4697.0  508.01  4846.5  505.30  4851.6  504.49  4923.4  499.95  4940.3  498.04
  4968.2  496.48  4973.3  497.69  4980.9  495.26  4987.7  491.69  4988.0  491.53
  4988.5  490.73  4993.5  490.73  4994.0  491.53  4998.6  495.31  5011.3  496.24
  5031.7  496.61  5052.1  496.11  5062.3  496.40  5082.7  498.24  5103.6  498.63
  5205.1  498.70  5225.5  499.66  5245.9  499.24  5261.6  499.95  5296.9  500.66
  5327.5  502.13  5409.1  504.52  5429.5  506.12  5460.0  506.28  5511.0  508.40
#Mann=5,-1,0
  4697.0    0.05       0  4987.7    0.16       0  4988.0    0.07       0
  4994.0    0.16       0  5103.6    0.05       0
Bank Sta=4923.4,5261.6
Exp/Cntr=0.3,0.1

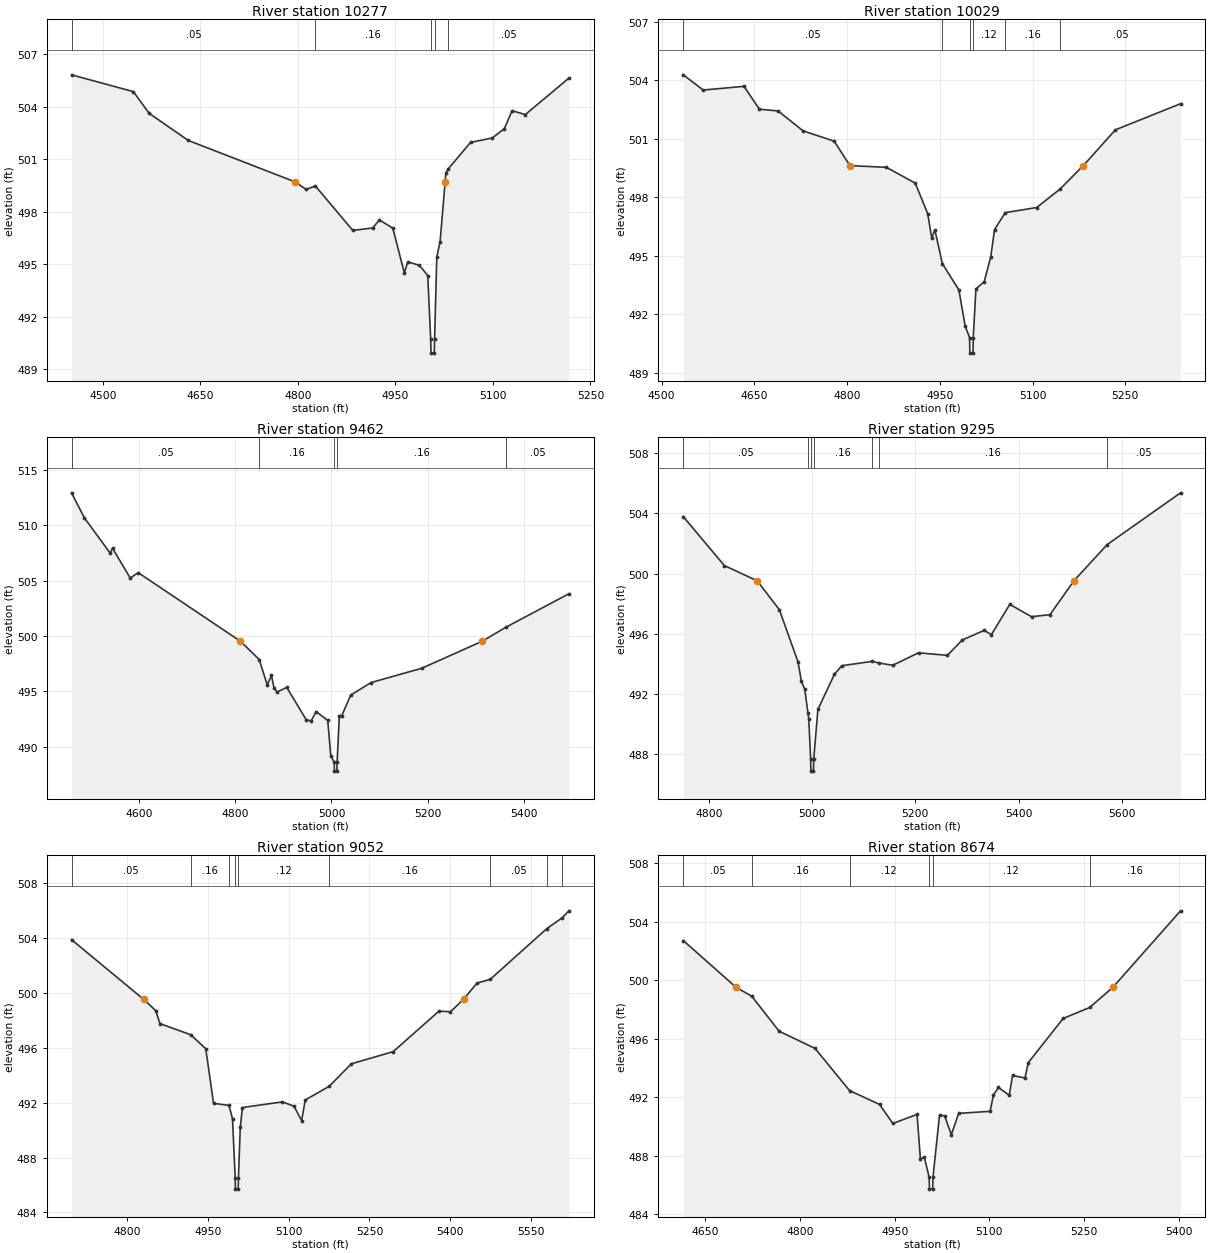
Type RM Length L Ch R = 1,10277,248,248,248
BEGIN DESCRIPTION:
XS3164A
END DESCRIPTION:
XS GIS Cut Line= 4
      2793033.91      7069208.41      2792708.39      7069179.76
      2792494.85      7069226.64      2792279.32      7069268.18
#Sta/Elev= 30
  4451.8  505.82  4546.9  504.86  4571.2  503.62  4631.4  502.07  4795.9  499.70
  4812.8  499.27  4826.8  499.47  4884.4  496.93  4914.8  497.07  4925.4  497.53
  4945.9  497.06  4963.7  494.50  4968.9  495.13  4986.8  494.94  4999.7  494.35
  5004.2  490.72  5004.7  489.92  5009.7  489.92  5010.2  490.72  5013.6  495.41
  5018.7  496.29  5026.4  499.70  5027.6  500.22  5031.1  500.44  5065.5  501.96
  5098.9  502.21  5117.4  502.74  5129.4  503.77  5149.8  503.55  5216.7  505.63
#Mann=5,-1,0
  4451.8    0.05       0  4826.8    0.16       0  5004.2    0.07       0
  5010.2    0.16       0  5031.1    0.05       0
Bank Sta=4795.9,5026.4
Exp/Cntr=0.3,0.1

Type RM Length L Ch R = 1,10029,567,567,567
BEGIN DESCRIPTION:
XS3165A
END DESCRIPTION:
XS GIS Cut Line= 3
      2793046.97      7069073.00      2792575.58      7069010.49
      2792265.64      7069119.88
#Sta/Elev= 30
  4535.1  504.27  4567.4  503.49  4633.4  503.68  4658.1  502.51  4688.4  502.42
  4728.8  501.40  4779.2  500.87  4804.6  499.62  4863.6  499.53  4910.3  498.72
  4930.5  497.15  4936.9  495.91  4942.0  496.33  4954.1  494.60  4980.9  493.24
  4991.0  491.40  4998.1  490.81  4998.6  490.01  5003.6  490.01  5004.1  490.81
  5008.4  493.30  5021.8  493.67  5032.4  494.95  5038.5  496.34  5055.9  497.21
  5106.7  497.47  5144.5  498.42  5182.1  499.62  5233.9  501.45  5339.3  502.79
#Mann=6,-1,0
  4535.1    0.05       0  4954.1    0.12       0  4998.1    0.07       0
  5004.1    0.12       0  5055.9    0.16       0  5144.5    0.05       0
Bank Sta=4804.6,5182.1
Exp/Cntr=0.3,0.1

Type RM Length L Ch R = 1,9462,167,167,167
BEGIN DESCRIPTION:
UNT 029 in LFCCL Watershed 12.0
END DESCRIPTION:
XS GIS Cut Line= 3
      2792925.03      7068574.99      2792375.00      7068675.00
      2792225.00      7069125.01
#Sta/Elev= 30
  4459.9  512.94  4486.6  510.68  4540.0  507.50  4545.1  507.93  4581.9  505.24
  4598.4  505.73  4811.0  499.53  4849.9  497.88  4866.5  495.60  4875.4  496.44
  4880.5  495.35  4886.8  494.94  4907.1  495.36  4947.8  492.43  4958.0  492.35
  4968.1  493.18  4992.3  492.38  4998.6  489.19  5005.8  488.60  5006.3  487.80
  5011.3  487.80  5011.8  488.60  5016.4  492.82  5021.6  492.82  5040.0  494.67
  5082.2  495.80  5187.6  497.09  5313.2  499.53  5363.0  500.81  5493.3  503.82
#Mann=5,-1,0
  4459.9    0.05       0  4849.9    0.16       0  5005.8    0.07       0
  5011.8    0.16       0  5363.0    0.05       0
Bank Sta=4811,5313.2
Exp/Cntr=0.3,0.1

Type RM Length L Ch R = 1,9295,243,243,243
BEGIN DESCRIPTION:
XS3166A
END DESCRIPTION:
XS GIS Cut Line= 3
      2792502.66      7068369.87      2792304.75      7068541.74
      2791831.87      7069059.06
#Sta/Elev= 30
  4750.6  503.79  4830.3  500.53  4893.7  499.52  4936.7  497.60  4972.7  494.14
  4979.4  492.84  4986.0  492.29  4992.1  490.74  4993.7  490.33  4997.3  487.66
  4997.8  486.86  5002.8  486.86  5003.3  487.66  5011.4  490.97  5043.4  493.30
  5057.6  493.87  5116.4  494.16  5130.1  494.05  5156.3  493.90  5206.2  494.73
  5262.3  494.56  5290.7  495.58  5333.3  496.22  5347.4  495.94  5382.9  497.95
  5425.1  497.13  5460.9  497.27  5507.1  499.52  5571.6  501.93  5713.6  505.37
#Mann=7,-1,0
  4750.6    0.05       0  4992.1    0.16       0  4997.3    0.07       0
  5003.3    0.16       0  5116.4    0.12       0  5130.1    0.16       0
  5571.6    0.05       0
Bank Sta=4893.7,5507.1
Exp/Cntr=0.3,0.1

Type RM Length L Ch R = 1,9052,378,378,378
BEGIN DESCRIPTION:
UNT 029 in LFCCL Watershed 11.0
END DESCRIPTION:
XS GIS Cut Line= 3
      2792324.97      7068225.03      2792125.00      7068475.00
      2791725.00      7068925.00
#Sta/Elev= 30
  4697.5  503.86  4831.1  499.52  4853.5  498.70  4861.5  497.75  4918.4  496.94
  4946.4  495.92  4960.8  491.95  4989.5  491.79  4996.0  490.82  5001.0  486.50
  5001.5  485.70  5006.5  485.70  5007.0  486.50  5010.4  490.19  5014.4  491.64
  5088.3  492.05  5110.0  491.74  5124.2  490.69  5130.9  492.19  5175.5  493.19
  5216.2  494.82  5294.0  495.71  5378.9  498.66  5400.2  498.61  5424.4  499.52
  5449.5  500.70  5473.9  500.97  5578.7  504.66  5607.3  505.45  5619.7  505.96
#Mann=9,-1,0
  4697.5    0.05       0  4918.4    0.16       0  4989.5    0.12       0
  5001.0    0.07       0  5007.0    0.12       0  5175.5    0.16       0
  5473.9    0.05       0  5578.7    0.16       0  5607.3    0.05       0
Bank Sta=4831.1,5424.4
Exp/Cntr=0.3,0.1

Type RM Length L Ch R = 1,8674,347,347,347
BEGIN DESCRIPTION:
UNT 029 in LFCCL Watershed 10.0
END DESCRIPTION:
XS GIS Cut Line= 3
      2792175.04      7068174.97      2791875.00      7068375.00
      2791475.00      7068525.00
#Sta/Elev= 30
  4615.0  502.71  4698.7  499.51  4723.6  498.90  4766.8  496.51  4823.9  495.33
  4878.4  492.45  4926.0  491.50  4947.1  490.20  4985.4  490.82  4990.7  487.77
  4997.0  487.88  5004.6  486.51  5005.1  485.71  5010.1  485.71  5010.6  486.51
  5021.0  490.76  5029.0  490.73  5039.7  489.43  5051.3  490.89  5101.1  491.03
  5106.4  492.15  5114.4  492.66  5131.4  492.13  5136.7  493.48  5156.3  493.31
  5161.6  494.36  5216.8  497.38  5258.9  498.13  5295.6  499.51  5402.8  504.74
#Mann=6,-1,0
  4615.0    0.05       0  4723.6    0.16       0  4878.4    0.12       0
  5004.6    0.07       0  5010.6    0.12       0  5258.9    0.16       0
Bank Sta=4698.7,5295.6
Exp/Cntr=0.3,0.1

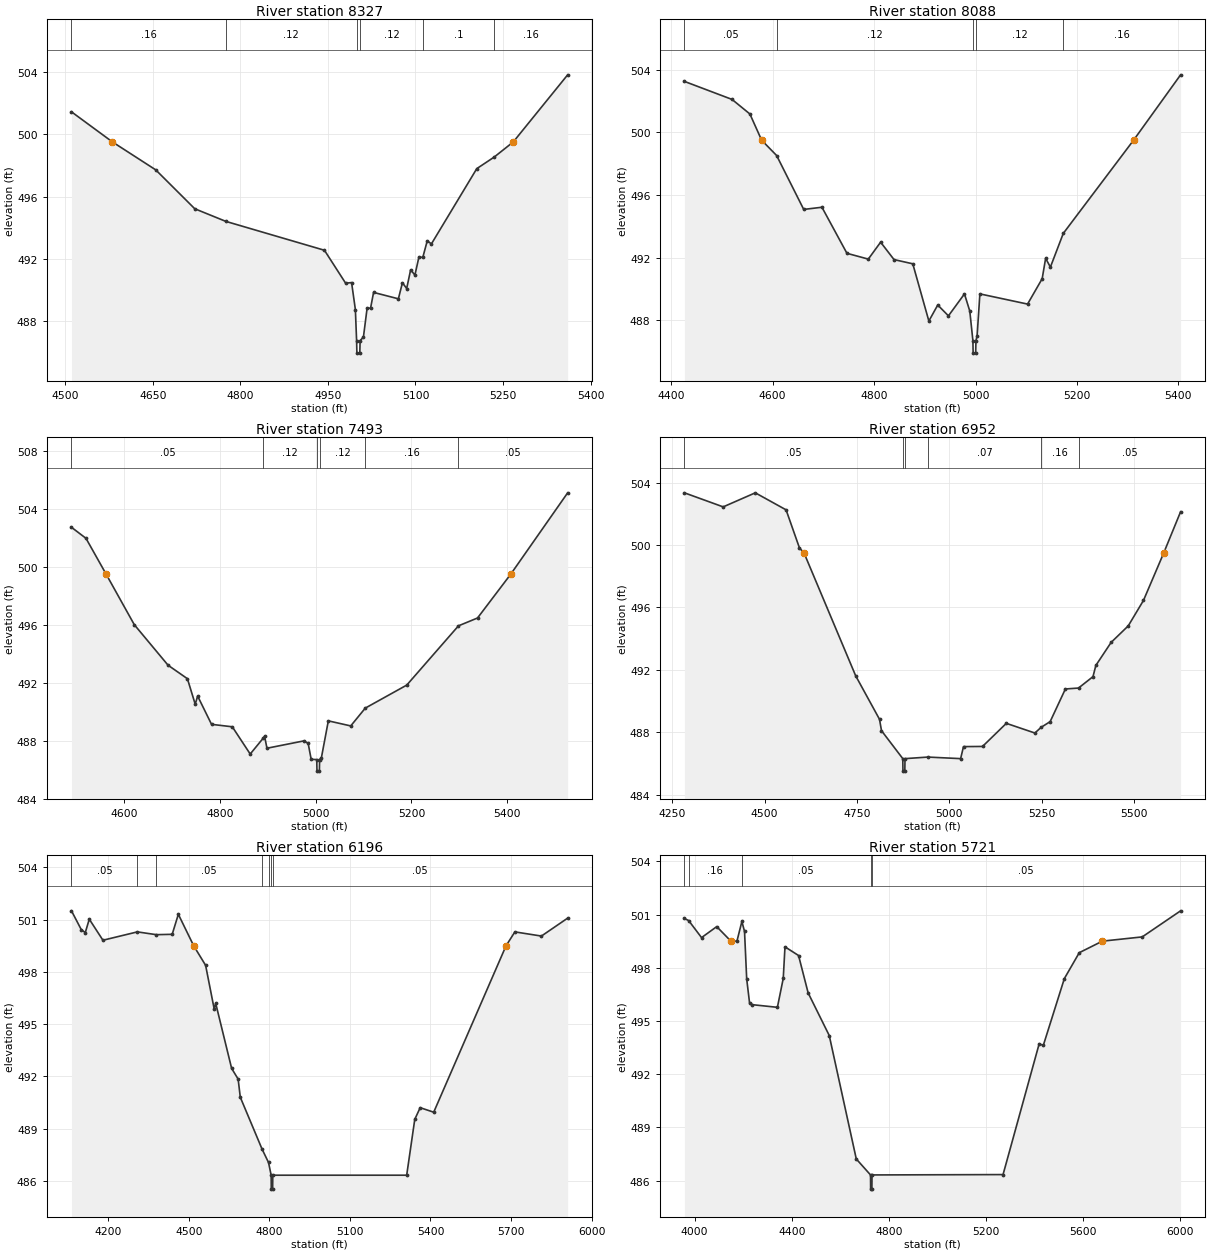
Type RM Length L Ch R = 1,8327,239,239,239
BEGIN DESCRIPTION:
XS3167A
END DESCRIPTION:
XS GIS Cut Line= 3
      2792126.96      7068121.59      2791627.66      7068213.62
      2791379.17      7068449.16
#Sta/Elev= 30
  4510.7  501.43  4580.9  499.50  4655.1  497.71  4721.9  495.22  4775.2  494.41
  4944.1  492.56  4980.4  490.45  4990.6  490.49  4997.1  488.76  4999.2  486.77
  4999.7  485.97  5004.7  485.97  5005.2  486.77  5010.9  487.00  5017.2  488.85
  5023.1  488.85  5028.3  489.86  5070.8  489.45  5077.7  490.48  5085.0  490.11
  5091.8  491.31  5099.1  490.97  5106.0  492.13  5112.6  492.10  5120.2  493.16
  5127.4  492.97  5205.1  497.79  5234.9  498.53  5267.6  499.50  5360.8  503.80
#Mann=6,-1,0
  4510.7    0.16       0  4775.2    0.12       0  4999.2    0.07       0
  5005.2    0.12       0  5112.6     0.1       0  5234.9    0.16       0
Bank Sta=4580.9,5267.6
Exp/Cntr=0.3,0.1

Type RM Length L Ch R = 1,8088,595,595,595
BEGIN DESCRIPTION:
XS3168A
END DESCRIPTION:
XS GIS Cut Line= 5
      2791845.73      7067583.39      2791610.25      7067845.19
      2791536.52      7068067.78      2791484.43      7068184.97
      2791299.53      7068372.48
#Sta/Elev= 30
  4426.1  503.25  4520.0  502.10  4555.2  501.17  4578.3  499.50  4607.9  498.52
  4661.3  495.08  4697.2  495.22  4746.5  492.28  4788.6  491.91  4812.9  492.99
  4839.3  491.88  4876.3  491.61  4908.0  487.96  4925.5  488.98  4946.6  488.29
  4978.2  489.69  4988.7  488.59  4994.8  486.71  4995.3  485.91  5000.3  485.91
  5000.8  486.71  5003.1  487.00  5008.6  489.69  5102.6  489.04  5131.4  490.66
  5138.2  491.96  5147.6  491.40  5173.0  493.55  5311.6  499.50  5404.3  503.67
#Mann=5,-1,0
  4426.1    0.05       0  4607.9    0.12       0  4994.8    0.07       0
  5000.8    0.12       0  5173.0    0.16       0
Bank Sta=4578.3,5311.6
Exp/Cntr=0.3,0.1

Type RM Length L Ch R = 1,7493,541,541,541
BEGIN DESCRIPTION:
UNT 029 in LFCCL Watershed 7.0
END DESCRIPTION:
XS GIS Cut Line= 3
      2791375.00      7067375.02      2791307.35      7067872.47
      2791125.01      7068374.98
#Sta/Elev= 30
  4489.7  502.74  4520.0  501.98  4562.2  499.50  4620.9  496.02  4691.5  493.22
  4731.9  492.29  4748.2  490.53  4753.3  491.09  4782.3  489.14  4825.7  488.97
  4863.1  487.09  4890.4  488.19  4893.1  488.32  4898.1  487.49  4975.6  488.00
  4984.2  487.82  4990.5  486.72  5002.1  486.71  5002.6  485.91  5007.6  485.91
  5008.1  486.71  5011.8  486.83  5026.3  489.38  5073.1  489.03  5103.5  490.26
  5190.2  491.85  5298.2  495.94  5338.0  496.48  5407.3  499.50  5526.3  505.12
#Mann=6,-1,0
  4489.7    0.05       0  4890.4    0.12       0  5002.1    0.07       0
  5008.1    0.12       0  5103.5    0.16       0  5298.2    0.05       0
Bank Sta=4562.2,5407.3
Exp/Cntr=0.3,0.1

Type RM Length L Ch R = 1,6952,756,756,756
BEGIN DESCRIPTION:
UNT 029 in LFCCL Watershed 6.0
END DESCRIPTION:
XS GIS Cut Line= 3
      2791158.36      7067058.48      2790875.00      7067725.00
      2791025.00      7068324.98
#Sta/Elev= 30
  4283.3  503.34  4388.2  502.44  4475.1  503.34  4558.4  502.25  4594.6  499.81
  4606.8  499.50  4746.8  491.62  4811.2  488.84  4816.6  488.11  4874.2  486.32
  4874.7  485.52  4879.7  485.52  4880.2  486.32  4942.2  486.42  5030.7  486.32
  5038.5  487.09  5090.0  487.10  5154.4  488.58  5231.7  487.96  5248.3  488.32
  5273.0  488.69  5314.2  490.78  5349.7  490.84  5388.9  491.57  5396.7  492.29
  5437.9  493.76  5484.3  494.82  5525.5  496.45  5580.5  499.50  5626.0  502.13
#Mann=6,-1,0
  4283.3    0.05       0  4874.2    0.07       0  4880.2    0.05       0
  4942.2    0.07       0  5248.3    0.16       0  5349.7    0.05       0
Bank Sta=4606.8,5580.5
Exp/Cntr=0.3,0.1

Type RM Length L Ch R = 1,6196,475,475,475
BEGIN DESCRIPTION:
UNT 029 in LFCCL Watershed 4.0
END DESCRIPTION:
XS GIS Cut Line= 4
      2790518.14      7066926.15      2790288.13      7067260.31
      2790125.00      7067775.00      2790231.14      7068670.13
#Sta/Elev= 30
  4063.6  501.51  4100.1  500.43  4115.0  500.26  4129.9  501.03  4180.7  499.82
  4308.9  500.30  4379.5  500.14  4438.5  500.16  4461.4  501.31  4518.6  499.50
  4562.9  498.38  4595.1  495.85  4600.4  496.20  4659.7  492.46  4684.0  491.84
  4692.0  490.80  4773.0  487.82  4797.1  487.05  4806.9  486.32  4807.4  485.52
  4812.4  485.52  4812.9  486.32  5311.4  486.32  5341.5  489.53  5361.6  490.20
  5412.0  489.94  5681.2  499.50  5714.1  500.30  5812.9  500.06  5910.6  501.09
#Mann=7,-1,0
  4063.6    0.05       0  4308.9    0.16       0  4379.5    0.05       0
  4773.0    0.07       0  4797.1    0.05       0  4806.9   0.033       0
  4812.9    0.05       0
Bank Sta=4518.6,5681.2
Exp/Cntr=0.3,0.1

Type RM Length L Ch R = 1,5721,71,71,71
BEGIN DESCRIPTION:
XS3169A
END DESCRIPTION:
XS GIS Cut Line= 6
      2789951.76      7066787.19      2789822.11      7067238.79
      2789756.14      7067346.43      2789651.97      7067797.82
      2789381.48      7068548.09      2789313.70      7068720.67
#Sta/Elev= 30
  3958.4  500.78  3975.9  500.66  4028.9  499.70  4091.4  500.32  4149.8  499.50
  4174.6  499.50  4194.9  500.61  4205.8  500.05  4214.7  497.37  4226.6  496.01
  4237.0  495.92  4341.1  495.77  4365.2  497.40  4372.3  499.18  4428.2  498.69
  4467.7  496.58  4554.5  494.18  4665.8  487.22  4724.4  486.32  4724.9  485.52
  4730.0  485.52  4730.5  486.32  5269.9  486.34  5418.7  493.72  5435.5  493.62
  5522.2  497.39  5583.6  498.85  5678.6  499.50  5842.8  499.74  6000.7  501.21
#Mann=5,-1,0
  3958.4    0.05       0  3975.9    0.16       0  4194.9    0.05       0
  4724.4   0.033       0  4730.5    0.05       0
Bank Sta=4149.8,5678.6
Exp/Cntr=0.3,0.1

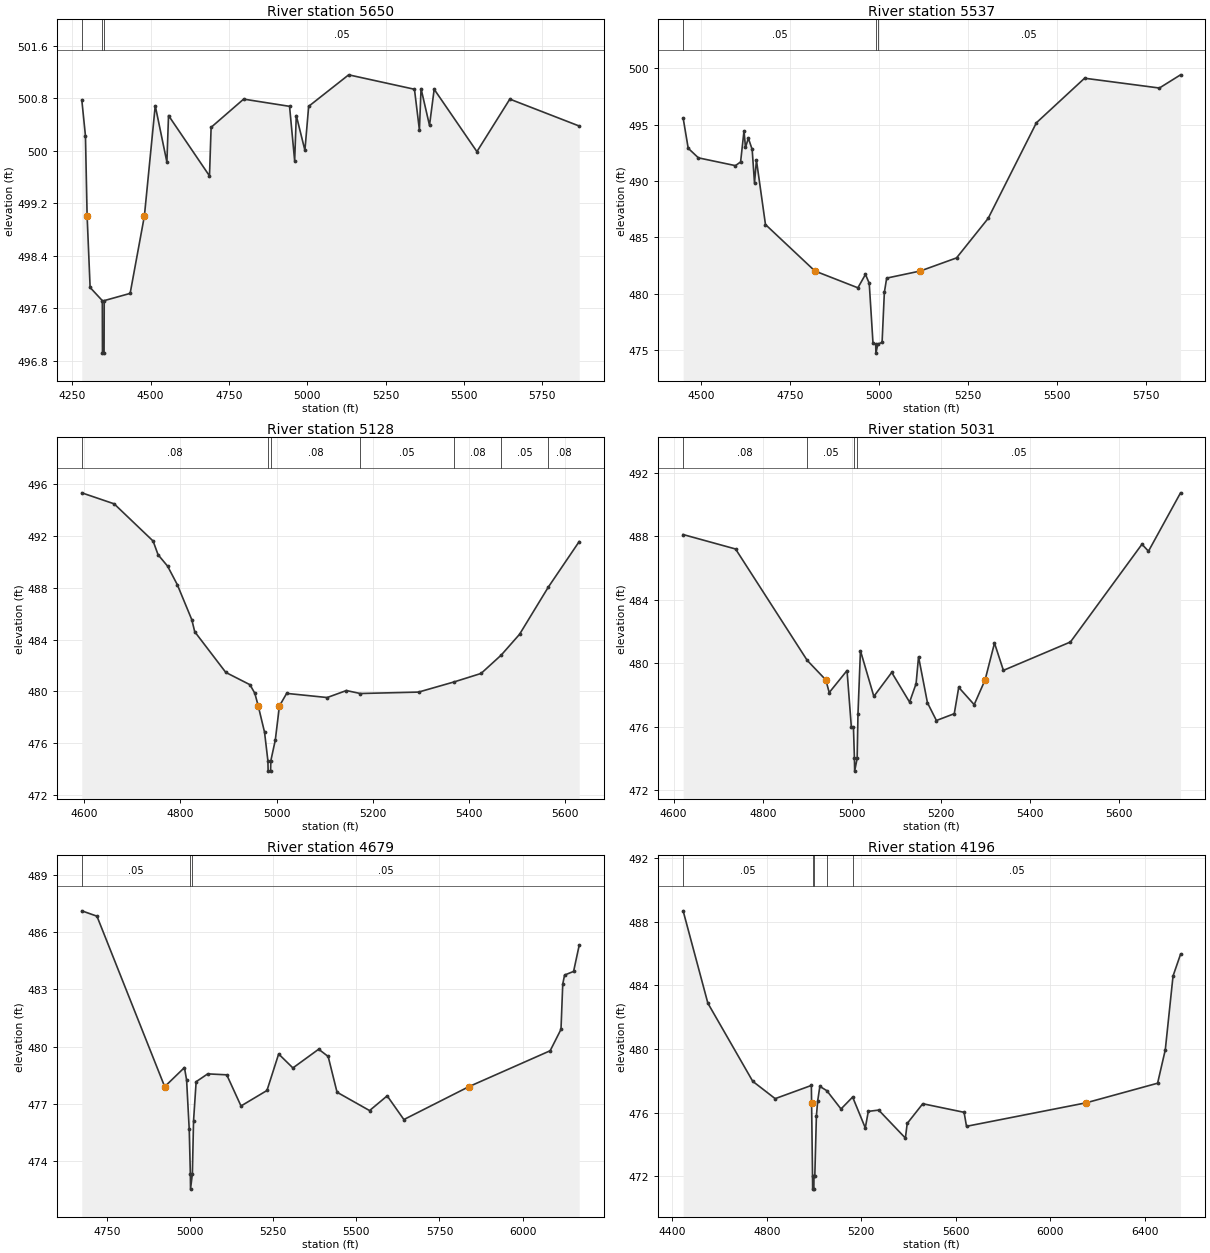
Type RM Length L Ch R = 1,5650,113,113,113
BEGIN DESCRIPTION:
XS3170A
END DESCRIPTION:
XS GIS Cut Line= 5
      2789651.92      7067082.40      2789721.41      7067183.23
      2789728.36      7067304.76      2789586.00      7067766.57
      2789325.57      7068586.04
#Sta/Elev= 30
  4280.6  500.78  4292.3  500.23  4297.6  499.01  4307.2  497.92  4346.1  497.72
  4346.6  496.92  4351.7  496.92  4352.2  497.72  4434.9  497.83  4480.4  499.01
  4515.0  500.69  4552.2  499.83  4557.4  500.54  4688.1  499.62  4693.3  500.36
  4797.1  500.79  4943.6  500.68  4959.9  499.85  4965.1  500.54  4992.6  500.01
  5004.6  500.68  5132.3  501.16  5342.2  500.94  5358.0  500.32  5363.2  500.95
  5390.2  500.39  5405.1  500.94  5541.5  499.99  5646.5  500.79  5867.9  500.38
#Mann=3,-1,0
  4280.6    0.05       0  4346.1    0.03       0  4352.2    0.05       0
Bank Sta=4297.6,4480.4
Exp/Cntr=0.3,0.1

Type RM Length L Ch R = 1,5537,409,409,409
BEGIN DESCRIPTION:
XS3171A
END DESCRIPTION:
XS GIS Cut Line= 4
      2789529.64      7067212.40      2789610.30      7067363.79
      2789474.89      7067742.26      2789242.26      7068533.88
#Sta/Elev= 30
  4449.9  495.59  4464.2  492.90  4492.9  492.05  4597.0  491.36  4611.5  491.69
  4621.1  494.45  4625.2  492.97  4633.3  493.79  4644.0  492.80  4650.6  489.82
  4656.0  491.85  4681.4  486.14  4820.4  482.02  4941.3  480.53  4962.6  481.72
  4973.2  480.93  4983.8  475.61  4991.4  475.54  4991.9  474.74  4997.5  475.54
  5009.3  475.69  5015.7  480.12  5022.2  481.39  5116.8  482.02  5218.6  483.18
  5307.7  486.69  5443.2  495.16  5578.7  499.11  5789.0  498.24  5848.5  499.41
#Mann=3,-1,0
  4449.9    0.05       0  4991.4    0.03       0  4997.5    0.05       0
Bank Sta=4820.4,5116.8
Exp/Cntr=0.3,0.1

Type RM Length L Ch R = 1,5128,97,97,97
BEGIN DESCRIPTION:
XS3172A
END DESCRIPTION:
XS GIS Cut Line= 3
      2789238.78      7067047.79      2789186.69      7067471.43
      2789176.27      7068079.11
#Sta/Elev= 30
  4594.8  495.33  4662.1  494.48  4743.1  491.61  4753.5  490.55  4773.3  489.67
  4793.5  488.24  4823.7  485.53  4829.7  484.61  4894.3  481.47  4944.6  480.52
  4954.7  479.86  4961.8  478.88  4974.9  476.86  4981.9  474.65  4982.4  473.85
  4987.5  473.85  4988.0  474.65  4997.3  476.25  5005.9  478.88  5020.9  479.85
  5105.2  479.53  5145.2  480.07  5174.0  479.84  5295.2  479.95  5369.6  480.74
  5425.3  481.39  5467.3  482.81  5505.3  484.41  5565.1  488.05  5629.4  491.57
#Mann=7,-1,0
  4594.8    0.08       0  4981.9    0.07       0  4988.0    0.08       0
  5174.0    0.05       0  5369.6    0.08       0  5467.3    0.05       0
  5565.1    0.08       0
Bank Sta=4961.8,5005.9
Exp/Cntr=0.3,0.1

Type RM Length L Ch R = 1,5031,352,352,352
BEGIN DESCRIPTION:
XS3175A
END DESCRIPTION:
XS GIS Cut Line= 3
      2789118.11      7067037.45      2789100.75      7067419.35
      2789044.44      7068151.39
#Sta/Elev= 30
  4621.4  488.12  4739.1  487.21  4899.9  480.19  4941.7  478.96  4949.3  478.16
  4989.3  479.55  4999.0  475.98  5003.7  475.98  5005.9  474.01  5006.4  473.21
  5012.0  474.01  5013.9  476.84  5019.4  480.80  5049.5  477.92  5089.6  479.43
  5129.7  477.56  5144.3  478.72  5149.8  480.42  5169.8  477.52  5189.9  476.40
  5230.0  476.83  5240.0  478.49  5274.7  477.40  5299.2  478.96  5320.3  481.28
  5340.3  479.56  5490.8  481.35  5651.3  487.51  5665.9  487.07  5737.9  490.75
#Mann=4,-1,0
  4621.4    0.08       0  4899.9    0.05       0  5005.9    0.03       0
  5012.0    0.05       0
Bank Sta=4941.7,5299.2
Exp/Cntr=0.3,0.1

Type RM Length L Ch R = 1,4679,483,483,483
BEGIN DESCRIPTION:
XS3174A
END DESCRIPTION:
XS GIS Cut Line= 5
      2789109.43      7066985.32      2788888.08      7067254.41
      2788653.70      7067449.73      2788627.66      7067553.89
      2788844.69      7068257.06
#Sta/Elev= 30
  4673.6  487.11  4719.2  486.83  4923.1  477.91  4982.5  478.91  4989.0  478.26
  4996.9  475.67  5000.3  473.35  5000.8  472.55  5006.4  473.35  5009.9  476.12
  5017.7  478.17  5052.5  478.58  5109.8  478.53  5152.7  476.90  5230.8  477.71
  5266.0  479.62  5308.9  478.89  5386.4  479.87  5415.0  479.49  5441.7  477.62
  5539.6  476.66  5592.6  477.43  5642.8  476.19  5838.3  477.91  6083.0  479.79
  6115.6  480.91  6120.9  483.28  6126.4  483.75  6153.5  483.94  6170.4  485.31
#Mann=3,-1,0
  4673.6    0.05       0  5000.3    0.03       0  5006.4    0.05       0
Bank Sta=4923.1,5838.3
Exp/Cntr=0.3,0.1

Type RM Length L Ch R = 1,4196,956,956,956
BEGIN DESCRIPTION:
XS3173A
END DESCRIPTION:
XS GIS Cut Line= 4
      2789109.46      7066785.65      2788636.34      7067072.12
      2788385.38      7067545.45      2788555.80      7068548.64
#Sta/Elev= 30
  4445.8  488.69  4550.6  482.88  4740.6  477.97  4835.6  476.88  4988.8  477.71
  4989.8  476.62  4993.8  471.99  4994.3  471.19  4999.4  471.19  4999.9  471.99
  5003.4  471.99  5010.1  475.78  5015.8  476.76  5024.8  477.65  5054.3  477.38
  5114.4  476.23  5163.6  476.98  5217.2  475.04  5230.0  476.08  5274.0  476.16
  5387.0  474.40  5394.7  475.32  5460.6  476.56  5635.6  476.02  5645.8  475.14
  6153.1  476.62  6455.0  477.85  6487.6  479.95  6520.4  484.59  6552.2  485.96
#Mann=5,-1,0
  4445.8    0.05       0  4993.8    0.03       0  4999.9    0.05       0
  5054.3    0.12       0  5163.6    0.05       0
Bank Sta=4989.8,6153.1
Exp/Cntr=0.3,0.1

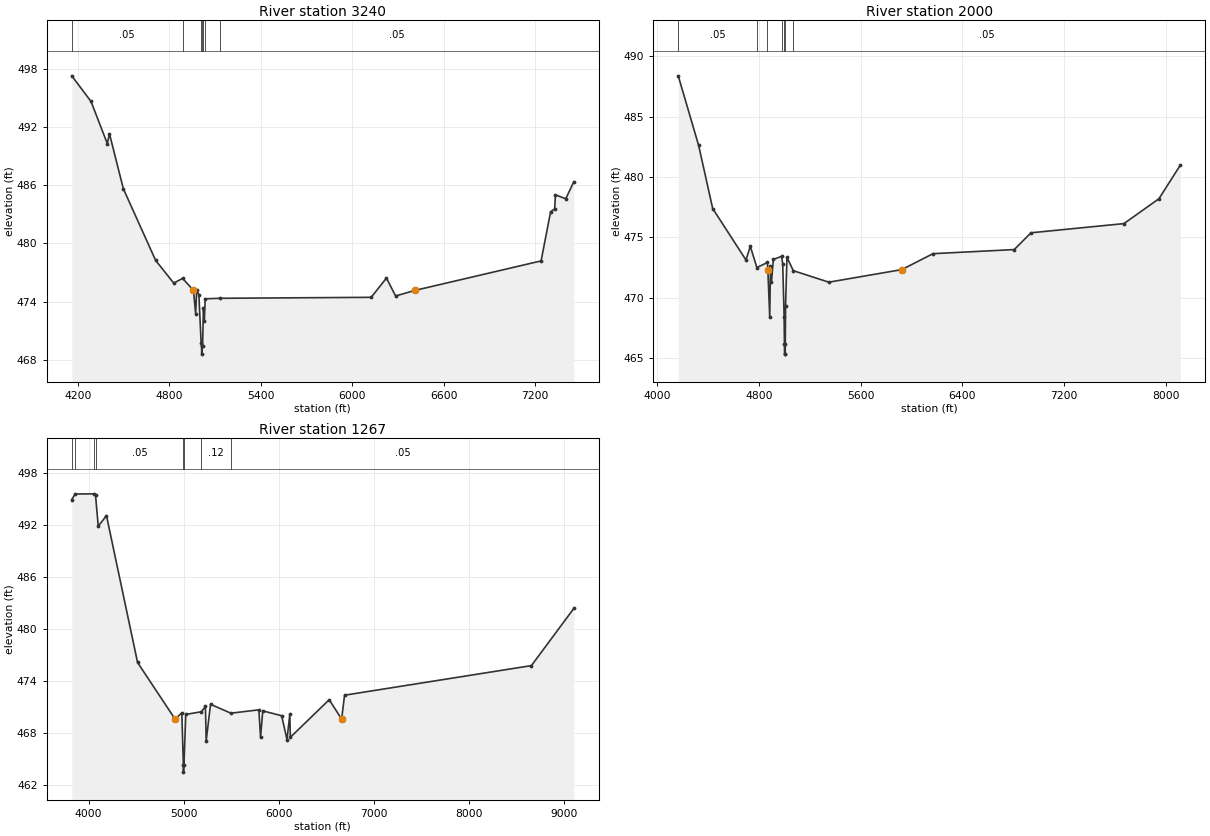
Type RM Length L Ch R = 1,3240,1240,1240,1240
BEGIN DESCRIPTION:
Mapping XS 4cf66508
END DESCRIPTION:
XS GIS Cut Line= 5
      2789430.19      7066460.23      2788831.20      7066382.10
      2788293.00      7066746.68      2788240.92      7067675.50
      2788544.27      7068741.58
#Sta/Elev= 30
  4161.4  497.25  4287.6  494.61  4394.3  490.28  4408.7  491.28  4499.4  485.63
  4711.2  478.25  4830.2  475.90  4888.1  476.39  4959.5  475.16  4974.0  472.74
  4980.0  475.15  4995.0  474.73  5009.7  469.76  5012.9  469.39  5013.4  468.59
  5019.1  469.39  5024.9  473.32  5030.9  472.05  5036.4  474.29  5131.3  474.34
  6125.0  474.44  6225.1  476.42  6285.2  474.58  6414.1  475.16  7239.4  478.19
  7301.8  483.25  7328.4  483.55  7333.6  484.99  7401.3  484.59  7454.2  486.35
#Mann=7,-1,0
  4161.4    0.05       0  4888.1    0.12       0  5009.7    0.07       0
  5012.9    0.07       0  5019.1    0.07       0  5036.4    0.12       0
  5131.3    0.05       0
Bank Sta=4959.5,6414.1
Exp/Cntr=0.3,0.1

Type RM Length L Ch R = 1,2000,733,733,733
BEGIN DESCRIPTION:
Mapping XS ea86e46c
END DESCRIPTION:
XS GIS Cut Line= 4
      2789112.85      7065789.22      2788670.17      7065872.55
      2787862.88      7066257.97      2788328.58      7068820.47
#Sta/Elev= 30
  4165.9  488.39  4326.5  482.62  4436.9  477.40  4698.7  473.14  4732.9  474.27
  4784.6  472.51  4867.5  472.93  4870.8  472.34  4885.7  468.38  4891.3  472.66
  4899.1  471.29  4914.0  473.18  4978.5  473.44  4987.8  472.83  4998.8  468.44
  5001.5  466.14  5002.0  465.34  5007.3  465.34  5007.8  466.14  5010.2  469.36
  5021.0  473.36  5071.3  472.25  5350.5  471.30  5924.5  472.34  6169.8  473.66
  6808.9  474.00  6941.0  475.39  7671.8  476.15  7947.2  478.21  8115.4  480.99
#Mann=7,-1,0
  4165.9    0.05       0  4784.6    0.12       0  4867.5    0.16       0
  4978.5    0.12       0  5001.5    0.07       0  5007.8    0.12       0
  5071.3    0.05       0
Bank Sta=4870.8,5924.5
Exp/Cntr=0.3,0.1

Type RM Length L Ch R = 1,1267,0,0,0
BEGIN DESCRIPTION:
UNT 029 in LFCCL Watershed 1.0
END DESCRIPTION:
XS GIS Cut Line= 4
      2789474.51      7065730.71      2788569.40      7065497.47
      2787486.66      7065782.79      2788198.46      7068925.11
#Sta/Elev= 30
  3823.5  494.94  3859.3  495.58  4062.2  495.60  4072.9  495.46  4101.8  491.86
  4188.3  493.08  4514.9  476.11  4909.1  469.57  4979.9  470.29  4996.3  464.24
  4996.8  463.44  5002.6  464.24  5021.3  470.11  5186.5  470.42  5228.1  471.03
  5236.1  467.05  5281.6  471.28  5495.8  470.25  5790.1  470.64  5807.2  467.47
  5830.4  470.52  6028.8  469.96  6085.2  467.21  6115.1  470.14  6120.2  467.46
  6529.0  471.81  6659.5  469.57  6690.2  472.33  8653.9  475.75  9099.8  482.36
#Mann=8,-1,0
  3823.5    0.16       0  3859.3    0.05       0  4062.2    0.08       0
  4072.9    0.05       0  4996.3    0.03       0  5002.6    0.05       0
  5186.5    0.12       0  5495.8    0.05       0
Bank Sta=4909.1,6659.5
Exp/Cntr=0.3,0.1

Chan Stop Cuts=-1