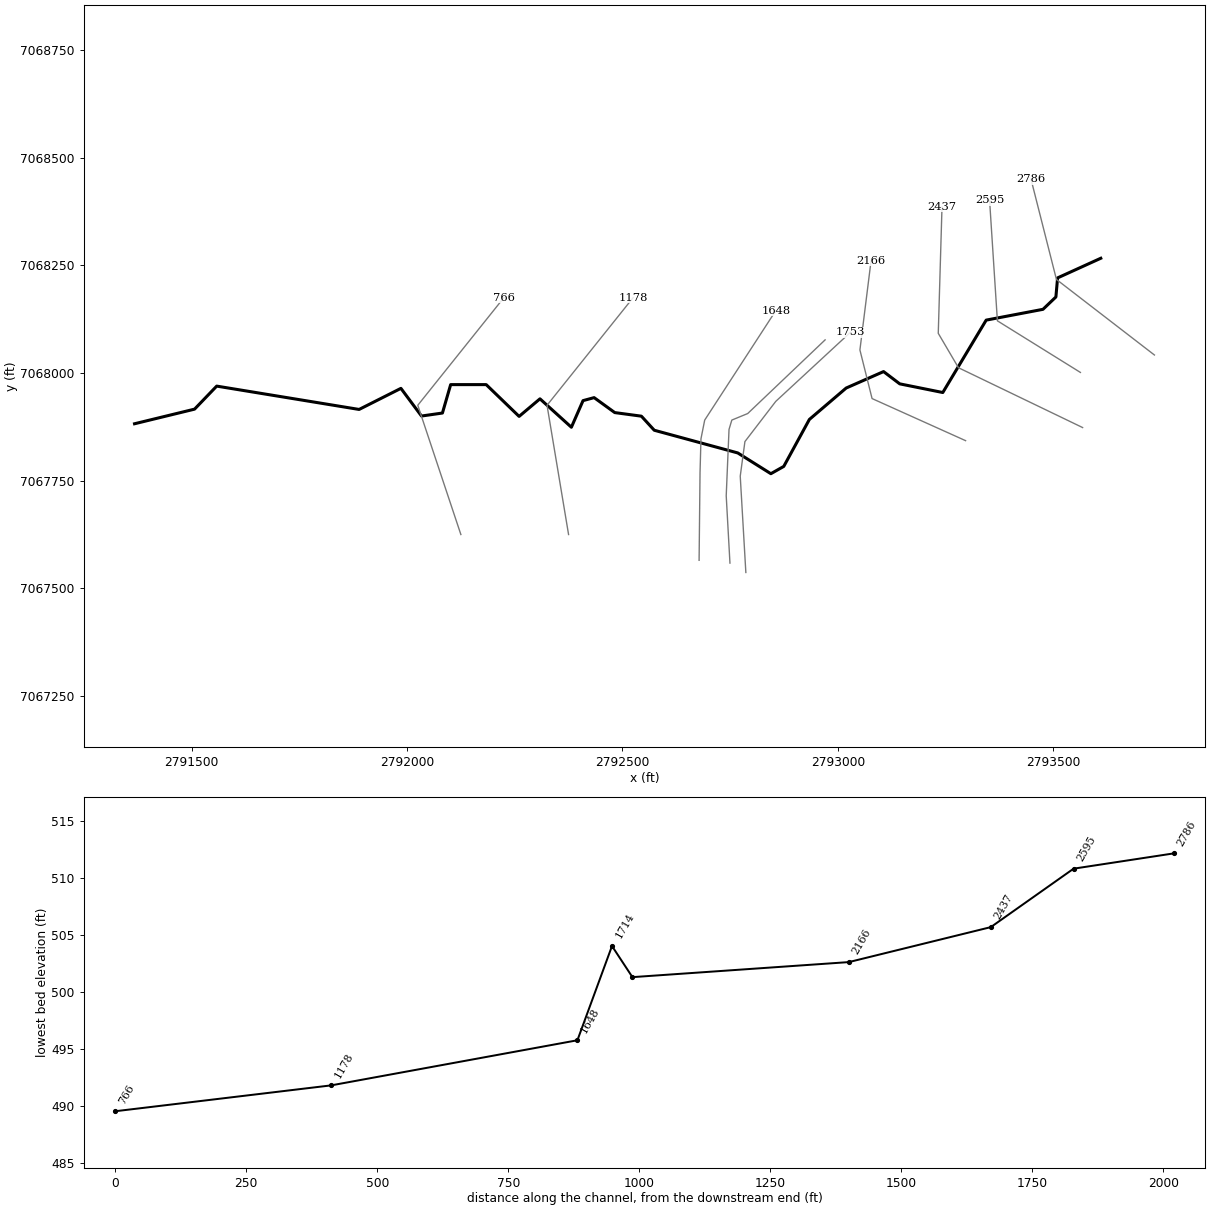
--- UNT 030 in LFCCL Watershed.prj (project) ---

Proj Title=UNT 030 in LFCCL Watershed Base Level Engineering
Current Plan=p01
Default Exp/Contr=0.3,0.1
English Units
Geom File=g01
Flow File=f01
Plan File=p01
BEGIN DESCRIPTION:
UNT 030 in LFCCL Watershed
END DESCRIPTION:

--- UNT 030 in LFCCL Watershed.p01 (plan) ---

Plan Title=Multiple Run
Short Identifier=Multiple
Geom File=g01
Flow File=f01
Subcritical Flow
K Sum by GR= 0
Std Step Tol= 0.01
Critical Tol= 0.01
Num of Std Step Trials= 20
Max Error Tol= 0.3
Flow Tol Ratio= 0.001
Split Flow NTrial= 30
Split Flow Tol= 0.02
Split Flow Ratio= 0.02
Log Output Level= 0
Friction Slope Method= 1
Unsteady Friction Slope Method= 2
Unsteady Bridges Friction Slope Method= 1
Parabolic Critical Depth
Global Vel Dist=  1 , 1 , 1
Global Log Level= 0
CheckData=True
Encroach Param= -1, 0, 0, 0
BEGIN DESCRIPTION:
Multiple Run
END DESCRIPTION:

--- UNT 030 in LFCCL Watershed.f01 (steady flow) ---

Flow Title=Multiple
Number of Profiles=7
Profile Names=10-year,25-year,50-year,1pct_min,100-year,1pct_plu,500-year
River Rch & RM= UNT 030 in LFCCL,Reach-1,2786
     160     193     217     122     244     487     304
Boundary for River Rch & Prof#=UNT 030 in LFCCL,Reach-1,1
Up Type=0
Dn Type=3
Dn Slope=0.005
Boundary for River Rch & Prof#=UNT 030 in LFCCL,Reach-1,2
Up Type=0
Dn Type=3
Dn Slope=0.005
Boundary for River Rch & Prof#=UNT 030 in LFCCL,Reach-1,3
Up Type=0
Dn Type=3
Dn Slope=0.005
Boundary for River Rch & Prof#=UNT 030 in LFCCL,Reach-1,4
Up Type=0
Dn Type=3
Dn Slope=0.005
Boundary for River Rch & Prof#=UNT 030 in LFCCL,Reach-1,5
Up Type=0
Dn Type=3
Dn Slope=0.005
Boundary for River Rch & Prof#=UNT 030 in LFCCL,Reach-1,6
Up Type=0
Dn Type=3
Dn Slope=0.005
Boundary for River Rch & Prof#=UNT 030 in LFCCL,Reach-1,7
Up Type=0
Dn Type=3
Dn Slope=0.005

--- UNT 030 in LFCCL Watershed.g01 (geometry) ---

Geom Title=Existing Conditions

River Reach=UNT 030 in LFCCL,Reach-1
Reach XY= 30
      2793610.30      7068266.23      2793510.04      7068220.66
      2793506.13      7068176.39      2793476.18      7068147.74
      2793344.32      7068122.66      2793243.63      7067954.60
      2793143.63      7067974.74      2793106.13      7068003.21
      2793019.32      7067965.02      2792933.91      7067892.10
      2792874.49      7067783.12      2792844.54      7067766.19
      2792767.72      7067814.37      2792573.88      7067867.06
      2792544.02      7067899.70      2792482.21      7067908.03
      2792434.30      7067942.75      2792408.60      7067935.81
      2792381.52      7067874.00      2792308.60      7067939.98
      2792260.17      7067899.18      2792183.78      7067972.96
      2792101.31      7067972.96      2792082.21      7067906.99
      2792033.60      7067900.04      2791985.86      7067964.28
      2791888.81      7067915.32      2791558.26      7067969.49
      2791506.87      7067916.02      2791367.55      7067882.09

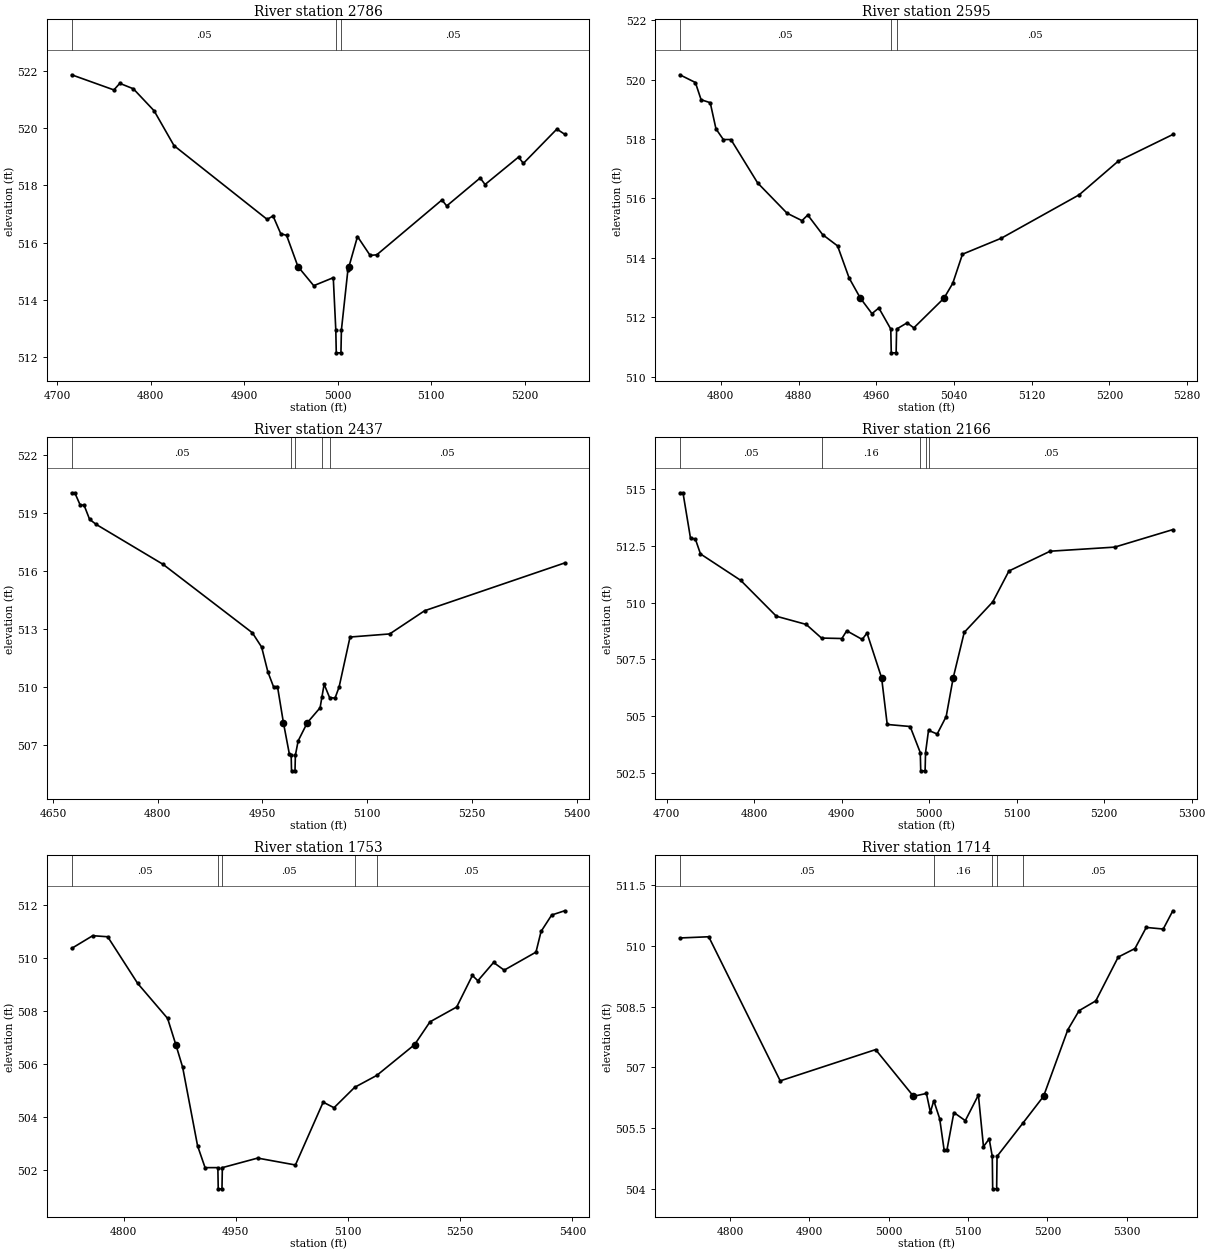
Type RM Length L Ch R = 1,2786,191,191,191
BEGIN DESCRIPTION:
Mapping XS 1d71c0db
END DESCRIPTION:
XS GIS Cut Line= 3
      2793734.82      7068041.70      2793507.40      7068217.04
      2793448.37      7068449.70
#Sta/Elev= 30
  4715.3  521.87  4760.5  521.34  4766.8  521.57  4781.3  521.38  4803.5  520.61
  4824.8  519.39  4924.4  516.81  4930.7  516.93  4938.9  516.31  4945.2  516.25
  4957.3  515.16  4974.2  514.49  4995.1  514.77  4997.8  512.94  4998.3  512.14
  5003.3  512.14  5003.8  512.94  5010.7  515.03  5011.9  515.16  5021.0  516.21
  5034.5  515.55  5041.6  515.57  5111.3  517.49  5116.4  517.28  5152.2  518.26
  5157.4  518.03  5193.2  518.99  5198.4  518.77  5234.2  519.97  5242.5  519.79
#Mann=3,-1,0
  4715.3    0.05       0  4997.8    0.03       0  5003.8    0.05       0
Bank Sta=4957.3,5011.9
Exp/Cntr=0.3,0.1

Type RM Length L Ch R = 1,2595,158,158,158
BEGIN DESCRIPTION:
Mapping XS 98d2cf51
END DESCRIPTION:
XS GIS Cut Line= 3
      2793563.03      7068001.24      2793370.34      7068121.02
      2793352.18      7068401.15
#Sta/Elev= 30
  4757.8  520.16  4773.8  519.90  4779.7  519.32  4789.1  519.22  4795.0  518.34
  4802.6  517.98  4810.4  517.98  4837.9  516.52  4868.2  515.50  4883.6  515.25
  4889.5  515.44  4904.8  514.78  4920.2  514.40  4932.1  513.32  4943.7  512.64
  4955.6  512.12  4962.7  512.31  4975.0  511.60  4975.5  510.80  4980.5  510.80
  4981.0  511.60  4991.8  511.81  4998.7  511.64  5029.8  512.64  5038.8  513.14
  5048.8  514.12  5088.9  514.66  5169.0  516.12  5209.1  517.25  5265.4  518.15
#Mann=3,-1,0
  4757.8    0.05       0  4975.0    0.03       0  4981.0    0.05       0
Bank Sta=4943.7,5029.8
Exp/Cntr=0.3,0.1

Type RM Length L Ch R = 1,2437,271,271,271
BEGIN DESCRIPTION:
Mapping XS 086a4778
END DESCRIPTION:
XS GIS Cut Line= 4
      2793568.15      7067873.29      2793279.97      7068012.17
      2793233.09      7068092.04      2793241.77      7068385.41
#Sta/Elev= 30
  4676.7  520.05  4681.2  520.05  4688.9  519.42  4694.5  519.41  4702.4  518.68
  4711.6  518.42  4807.6  516.35  4935.5  512.81  4948.8  512.07  4957.7  510.79
  4965.9  510.01  4971.5  510.03  4980.0  508.16  4988.5  506.54  4991.1  506.47
  4991.6  505.67  4996.6  505.67  4997.1  506.47  5001.1  507.22  5014.2  508.16
  5032.5  508.93  5035.2  509.50  5038.3  510.15  5046.1  509.46  5053.9  509.43
  5059.7  510.00  5075.4  512.59  5132.2  512.75  5182.2  513.95  5382.7  516.42
#Mann=5,-1,0
  4676.7    0.05       0  4991.1    0.03       0  4997.1    0.05       0
  5035.2    0.16       0  5046.1    0.05       0
Bank Sta=4980,5014.2
Exp/Cntr=0.3,0.1

Type RM Length L Ch R = 1,2166,413,413,413
BEGIN DESCRIPTION:
Mapping XS 67140dfd
END DESCRIPTION:
XS GIS Cut Line= 4
      2793296.49      7067842.89      2793079.45      7067940.56
      2793051.24      7068053.41      2793077.17      7068260.87
#Sta/Elev= 30
  4715.1  514.83  4718.7  514.83  4727.3  512.83  4732.8  512.80  4738.7  512.14
  4784.6  510.98  4825.4  509.40  4859.5  509.04  4877.0  508.44  4900.3  508.42
  4905.8  508.76  4923.5  508.38  4929.0  508.66  4945.7  506.69  4952.1  504.64
  4978.3  504.55  4989.9  503.40  4990.4  502.60  4995.4  502.60  4995.9  503.40
  4999.3  504.38  5009.2  504.22  5019.5  504.99  5027.5  506.69  5040.1  508.69
  5072.7  510.03  5091.2  511.39  5138.3  512.26  5212.1  512.44  5278.5  513.21
#Mann=5,-1,0
  4715.1    0.05       0  4877.0    0.16       0  4989.9    0.03       0
  4995.9    0.16       0  4999.3    0.05       0
Bank Sta=4945.7,5027.5
Exp/Cntr=0.3,0.1

Type RM Length L Ch R = 1,1753,39,39,39
BEGIN DESCRIPTION:
Mapping XS dad4f743
END DESCRIPTION:
XS GIS Cut Line= 5
      2792786.48      7067536.88      2792773.46      7067760.44
      2792784.31      7067840.73      2792855.92      7067934.05
      2793029.55      7068094.65
#Sta/Elev= 30
  4730.6  510.35  4758.8  510.83  4778.8  510.79  4818.9  509.03  4858.9  507.71
  4869.9  506.72  4879.0  505.87  4899.0  502.90  4909.0  502.08  4926.1  502.08
  4926.6  501.28  4931.6  501.28  4932.1  502.08  4979.3  502.44  5029.8  502.18
  5066.9  504.55  5081.4  504.34  5109.0  505.11  5138.6  505.56  5189.1  506.72
  5209.7  507.58  5245.4  508.14  5266.4  509.33  5273.7  509.13  5294.7  509.82
  5308.9  509.53  5351.4  510.21  5358.2  510.99  5372.4  511.61  5389.7  511.77
#Mann=5,-1,0
  4730.6    0.05       0  4926.1    0.03       0  4932.1    0.05       0
  5109.0    0.16       0  5138.6    0.05       0
Bank Sta=4869.9,5189.1
Exp/Cntr=0.3,0.1

Type RM Length L Ch R = 1,1714,66,66,66
BEGIN DESCRIPTION:
Mapping XS 24aeed76
END DESCRIPTION:
XS GIS Cut Line= 6
      2792749.58      7067558.65      2792740.91      7067714.87
      2792747.42      7067868.94      2792753.93      7067890.65
      2792790.82      7067905.84      2792970.44      7068076.80
#Sta/Elev= 30
  4736.9  510.19  4773.3  510.22  4863.4  506.67  4983.6  507.44  5031.3  506.29
  5047.6  506.36  5052.6  505.90  5056.9  506.18  5064.3  505.74  5069.9  504.97
  5073.5  504.97  5082.2  505.89  5096.6  505.69  5113.1  506.32  5119.5  505.05
  5126.7  505.24  5130.6  504.81  5131.1  504.01  5136.1  504.01  5136.6  504.81
  5169.6  505.64  5195.2  506.29  5225.8  507.93  5240.0  508.40  5261.0  508.64
  5289.3  509.72  5310.4  509.93  5324.6  510.45  5346.0  510.41  5358.1  510.86
#Mann=5,-1,0
  4736.9    0.05       0  5056.9    0.16       0  5130.6    0.03       0
  5136.6    0.16       0  5169.6    0.05       0
Bank Sta=5031.3,5195.2
Exp/Cntr=0.3,0.1

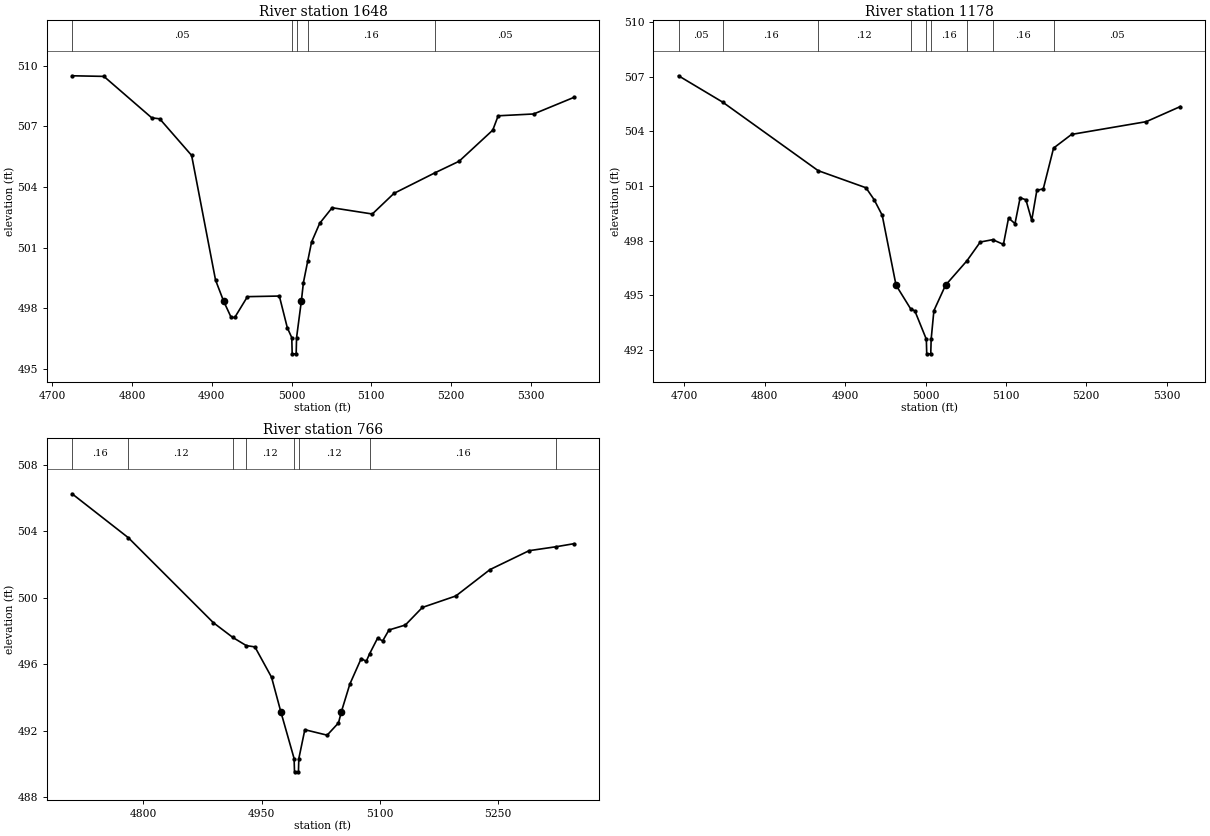
Type RM Length L Ch R = 1,1648,470,470,470
BEGIN DESCRIPTION:
Mapping XS 9c92ca27
END DESCRIPTION:
XS GIS Cut Line= 5
      2792677.97      7067565.12      2792680.14      7067769.12
      2792682.31      7067847.24      2792690.99      7067890.65
      2792855.92      7068144.55
#Sta/Elev= 30
  4724.8  509.50  4764.7  509.47  4824.7  507.42  4834.7  507.37  4874.7  505.56
  4904.7  499.39  4914.8  498.35  4924.3  497.54  4928.8  497.54  4944.7  498.57
  4984.7  498.60  4994.7  497.03  5000.3  496.54  5000.8  495.74  5005.8  495.74
  5006.3  496.54  5012.3  498.35  5014.9  499.27  5020.4  500.35  5025.1  501.27
  5035.3  502.20  5050.9  502.97  5101.3  502.66  5128.4  503.68  5179.9  504.70
  5210.1  505.27  5252.3  506.81  5259.1  507.52  5303.6  507.61  5354.0  508.43
#Mann=5,-1,0
  4724.8    0.05       0  5000.3    0.03       0  5006.3    0.05       0
  5020.4    0.16       0  5179.9    0.05       0
Bank Sta=4914.8,5012.3
Exp/Cntr=0.3,0.1

Type RM Length L Ch R = 1,1178,412,412,412
BEGIN DESCRIPTION:
UNT 030 in LFCCL Watershed 2.0
END DESCRIPTION:
XS GIS Cut Line= 3
      2792375.00      7067625.01      2792325.00      7067925.00
      2792525.01      7068175.01
#Sta/Elev= 30
  4692.7  507.05  4747.7  505.60  4866.4  501.84  4925.9  500.90  4936.0  500.25
  4946.1  499.39  4963.3  495.55  4981.5  494.25  4986.7  494.14  5001.0  492.58
  5001.5  491.78  5006.5  491.78  5007.0  492.58  5010.4  494.15  5024.9  495.55
  5051.5  496.89  5068.1  497.92  5083.6  498.05  5096.9  497.79  5103.3  499.24
  5111.3  498.93  5117.7  500.35  5124.9  500.24  5132.1  499.11  5138.5  500.76
  5146.5  500.84  5159.3  503.08  5181.7  503.83  5274.6  504.53  5317.0  505.36
#Mann=9,-1,0
  4692.7    0.05       0  4747.7    0.16       0  4866.4    0.12       0
  4981.5    0.16       0  5001.0    0.07       0  5007.0    0.16       0
  5051.5    0.12       0  5083.6    0.16       0  5159.3    0.05       0
Bank Sta=4963.3,5024.9
Exp/Cntr=0.3,0.1

Type RM Length L Ch R = 1,766,0,0,0
BEGIN DESCRIPTION:
UNT 030 in LFCCL Watershed 1.0
END DESCRIPTION:
XS GIS Cut Line= 3
      2792125.01      7067624.98      2792025.00      7067925.00
      2792224.99      7068174.99
#Sta/Elev= 30
  4709.7  506.27  4781.1  503.62  4888.9  498.50  4913.6  497.61  4930.6  497.12
  4941.6  497.04  4962.7  495.21  4974.4  493.14  4991.3  490.31  4991.8  489.51
  4996.8  489.51  4997.3  490.31  5004.9  492.05  5033.2  491.72  5047.6  492.46
  5051.3  493.14  5062.0  494.80  5076.4  496.34  5082.8  496.17  5087.1  496.63
  5097.2  497.57  5103.6  497.40  5111.6  498.06  5132.4  498.36  5154.0  499.42
  5196.4  500.11  5239.7  501.70  5289.3  502.84  5323.8  503.08  5346.1  503.26
#Mann=8,-1,0
  4709.7    0.16       0  4781.1    0.12       0  4913.6    0.16       0
  4930.6    0.12       0  4991.3    0.07       0  4997.3    0.12       0
  5087.1    0.16       0  5323.8    0.05       0
Bank Sta=4974.4,5051.3
Exp/Cntr=0.3,0.1

Chan Stop Cuts=-1