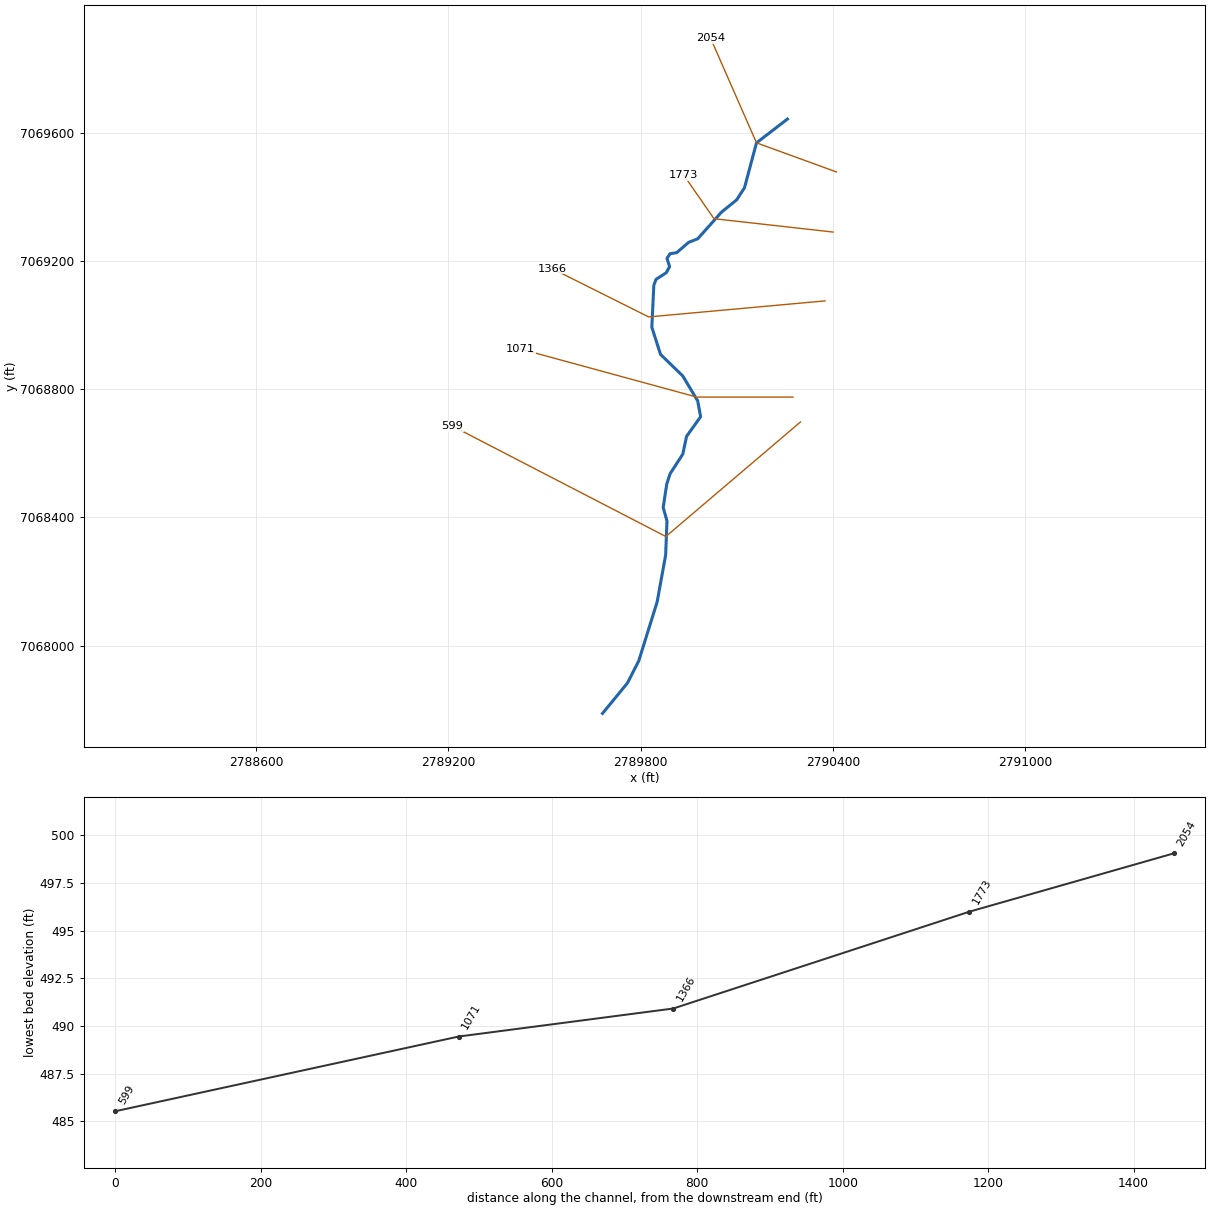
--- UNT 031 in LFCCL Watershed.prj (project) ---

Proj Title=UNT 031 in LFCCL Watershed Base Level Engineering
Current Plan=p01
Default Exp/Contr=0.3,0.1
English Units
Geom File=g01
Flow File=f01
Plan File=p01
BEGIN DESCRIPTION:
UNT 031 in LFCCL Watershed
END DESCRIPTION:

--- UNT 031 in LFCCL Watershed.p01 (plan) ---

Plan Title=Multiple Run
Short Identifier=Multiple
Geom File=g01
Flow File=f01
Subcritical Flow
K Sum by GR= 0
Std Step Tol= 0.01
Critical Tol= 0.01
Num of Std Step Trials= 20
Max Error Tol= 0.3
Flow Tol Ratio= 0.001
Split Flow NTrial= 30
Split Flow Tol= 0.02
Split Flow Ratio= 0.02
Log Output Level= 0
Friction Slope Method= 1
Unsteady Friction Slope Method= 2
Unsteady Bridges Friction Slope Method= 1
Parabolic Critical Depth
Global Vel Dist=  1 , 1 , 1
Global Log Level= 0
CheckData=True
Encroach Param= -1, 0, 0, 0
BEGIN DESCRIPTION:
Multiple Run
END DESCRIPTION:

--- UNT 031 in LFCCL Watershed.f01 (steady flow) ---

Flow Title=Multiple
Number of Profiles=7
Profile Names=10-year,25-year,50-year,1pct_min,100-year,1pct_plu,500-year
River Rch & RM= UNT 031 in LFCCL,Reach-1,2054
     152     183     204     114     228     455     281
Boundary for River Rch & Prof#=UNT 031 in LFCCL,Reach-1,1
Up Type=0
Dn Type=3
Dn Slope=0.005
Boundary for River Rch & Prof#=UNT 031 in LFCCL,Reach-1,2
Up Type=0
Dn Type=3
Dn Slope=0.005
Boundary for River Rch & Prof#=UNT 031 in LFCCL,Reach-1,3
Up Type=0
Dn Type=3
Dn Slope=0.005
Boundary for River Rch & Prof#=UNT 031 in LFCCL,Reach-1,4
Up Type=0
Dn Type=3
Dn Slope=0.005
Boundary for River Rch & Prof#=UNT 031 in LFCCL,Reach-1,5
Up Type=0
Dn Type=3
Dn Slope=0.005
Boundary for River Rch & Prof#=UNT 031 in LFCCL,Reach-1,6
Up Type=0
Dn Type=3
Dn Slope=0.005
Boundary for River Rch & Prof#=UNT 031 in LFCCL,Reach-1,7
Up Type=0
Dn Type=3
Dn Slope=0.005

--- UNT 031 in LFCCL Watershed.g01 (geometry) ---

Geom Title=Existing Conditions

River Reach=UNT 031 in LFCCL,Reach-1
Reach XY= 30
      2790257.60      7069641.97      2790161.20      7069567.93
      2790123.70      7069427.65      2790099.39      7069390.15
      2790052.17      7069351.95      2789977.87      7069268.62
      2789949.39      7069257.51      2789912.59      7069225.56
      2789891.76      7069222.09      2789882.03      7069207.51
      2789890.37      7069181.81      2789879.26      7069162.37
      2789848.01      7069142.23      2789841.06      7069124.18
      2789834.81      7068992.93      2789861.89      7068908.20
      2789931.34      7068840.84      2789977.87      7068763.06
      2789986.89      7068713.76      2789943.14      7068652.65
      2789931.34      7068597.09      2789891.76      7068535.98
      2789881.34      7068504.04      2789870.23      7068430.43
      2789882.03      7068388.76      2789877.87      7068282.51
      2789851.30      7068136.00      2789794.01      7067952.41
      2789758.86      7067883.39      2789681.15      7067788.60

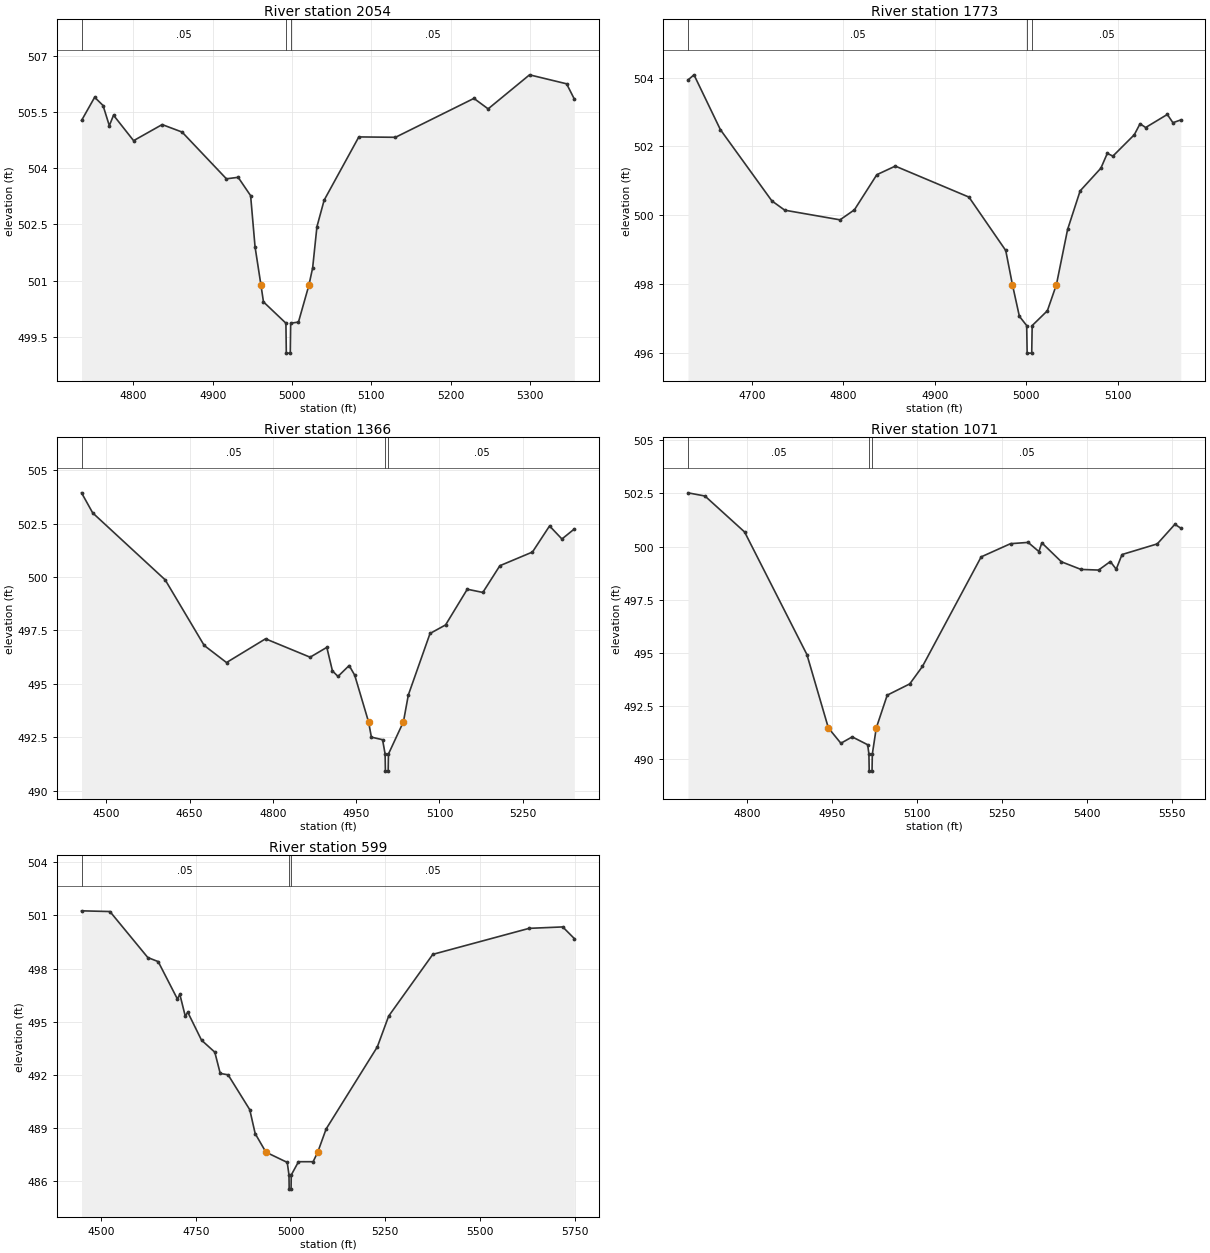
Type RM Length L Ch R = 1,2054,281,281,281
BEGIN DESCRIPTION:
UNT 031 in LFCCL Watershed 4.0
END DESCRIPTION:
XS GIS Cut Line= 3
      2790410.50      7069477.18      2790161.20      7069567.93
      2790018.17      7069893.82
#Sta/Elev= 30
  4734.7  505.28  4751.2  505.90  4761.8  505.68  4769.7  505.14  4775.0  505.42
  4800.3  504.74  4836.3  505.17  4861.4  504.97  4917.3  503.72  4932.1  503.76
  4947.8  503.27  4953.4  501.90  4960.9  500.87  4964.0  500.43  4992.3  499.86
  4992.8  499.06  4997.8  499.06  4998.3  499.86  5008.1  499.89  5021.2  500.87
  5026.0  501.34  5031.4  502.44  5040.5  503.15  5084.2  504.84  5130.4  504.83
  5229.3  505.87  5247.2  505.59  5299.4  506.50  5346.1  506.26  5355.9  505.85
#Mann=3,-1,0
  4734.7    0.05       0  4992.3    0.03       0  4998.3    0.05       0
Bank Sta=4960.9,5021.2
Exp/Cntr=0.3,0.1

Type RM Length L Ch R = 1,1773,407,407,407
BEGIN DESCRIPTION:
Mapping XS 205d404f
END DESCRIPTION:
XS GIS Cut Line= 3
      2790400.15      7069289.66      2790028.58      7069331.33
      2789934.83      7069466.75
#Sta/Elev= 30
  4630.1  503.93  4636.7  504.08  4665.5  502.49  4721.8  500.42  4735.9  500.15
  4796.3  499.87  4812.0  500.16  4836.5  501.18  4856.7  501.43  4937.2  500.53
  4977.4  498.98  4984.7  497.99  4992.3  497.07  5000.3  496.80  5000.8  496.00
  5005.8  496.00  5006.3  496.80  5022.9  497.23  5032.8  497.99  5045.0  499.59
  5058.7  500.71  5081.4  501.37  5088.4  501.80  5094.5  501.72  5117.9  502.34
  5124.2  502.66  5130.3  502.55  5154.0  502.93  5160.1  502.69  5168.7  502.77
#Mann=3,-1,0
  4630.1    0.05       0  5000.3    0.03       0  5006.3    0.05       0
Bank Sta=4984.7,5032.8
Exp/Cntr=0.3,0.1

Type RM Length L Ch R = 1,1366,295,295,295
BEGIN DESCRIPTION:
UNT 031 in LFCCL Watershed 3.0
END DESCRIPTION:
XS GIS Cut Line= 3
      2790375.00      7069075.00      2789825.00      7069025.00
      2789524.98      7069175.01
#Sta/Elev= 30
  4455.3  503.94  4475.4  503.00  4605.9  499.87  4676.2  496.80  4716.4  496.00
  4786.7  497.11  4867.0  496.25  4897.1  496.71  4907.2  495.61  4917.2  495.35
  4937.3  495.86  4947.3  495.41  4972.2  493.23  4977.4  492.51  4997.5  492.39
  5002.1  491.72  5002.6  490.92  5007.6  490.92  5008.1  491.72  5035.1  493.23
  5043.9  494.48  5083.0  497.36  5111.0  497.76  5150.1  499.43  5178.1  499.28
  5208.8  500.53  5267.5  501.17  5298.3  502.39  5320.6  501.78  5343.0  502.25
#Mann=3,-1,0
  4455.3    0.05       0  5002.1    0.03       0  5008.1    0.05       0
Bank Sta=4972.2,5035.1
Exp/Cntr=0.3,0.1

Type RM Length L Ch R = 1,1071,472,472,472
BEGIN DESCRIPTION:
UNT 031 in LFCCL Watershed 2.0
END DESCRIPTION:
XS GIS Cut Line= 3
      2790275.00      7068775.00      2789975.00      7068775.00
      2789424.99      7068925.00
#Sta/Elev= 30
  4695.4  502.53  4725.4  502.38  4795.4  500.69  4905.4  494.93  4943.3  491.48
  4965.4  490.76  4985.4  491.06  5012.7  490.69  5014.9  490.25  5015.4  489.45
  5020.4  489.45  5020.9  490.25  5027.9  491.48  5047.2  493.02  5087.0  493.55
  5109.4  494.37  5213.1  499.52  5264.9  500.14  5296.0  500.20  5315.0  499.77
  5320.2  500.18  5354.7  499.29  5389.3  498.93  5420.4  498.90  5441.1  499.30
  5451.5  498.94  5461.8  499.63  5524.0  500.13  5555.1  501.05  5565.5  500.87
#Mann=3,-1,0
  4695.4    0.05       0  5014.9    0.03       0  5020.9    0.05       0
Bank Sta=4943.3,5027.9
Exp/Cntr=0.3,0.1

Type RM Length L Ch R = 1,599,0,0,0
BEGIN DESCRIPTION:
UNT 031 in LFCCL Watershed 1.0
END DESCRIPTION:
XS GIS Cut Line= 3
      2790298.33      7068697.38      2789878.56      7068340.15
      2789213.24      7068684.38
#Sta/Elev= 30
  4448.8  501.26  4523.7  501.22  4623.6  498.62  4651.0  498.39  4701.6  496.28
  4708.1  496.54  4722.4  495.31  4729.0  495.53  4765.3  493.95  4800.4  493.27
  4814.7  492.07  4835.5  491.99  4892.6  490.02  4906.9  488.67  4935.2  487.62
  4991.5  487.04  4996.1  486.33  4996.6  485.53  5001.6  485.53  5002.1  486.33
  5021.2  487.08  5059.8  487.08  5072.0  487.62  5094.1  488.93  5229.2  493.57
  5259.1  495.31  5375.6  498.80  5629.8  500.27  5718.4  500.35  5749.1  499.69
#Mann=3,-1,0
  4448.8    0.05       0  4996.1    0.03       0  5002.1    0.05       0
Bank Sta=4935.2,5072
Exp/Cntr=0.3,0.1

Chan Stop Cuts=-1