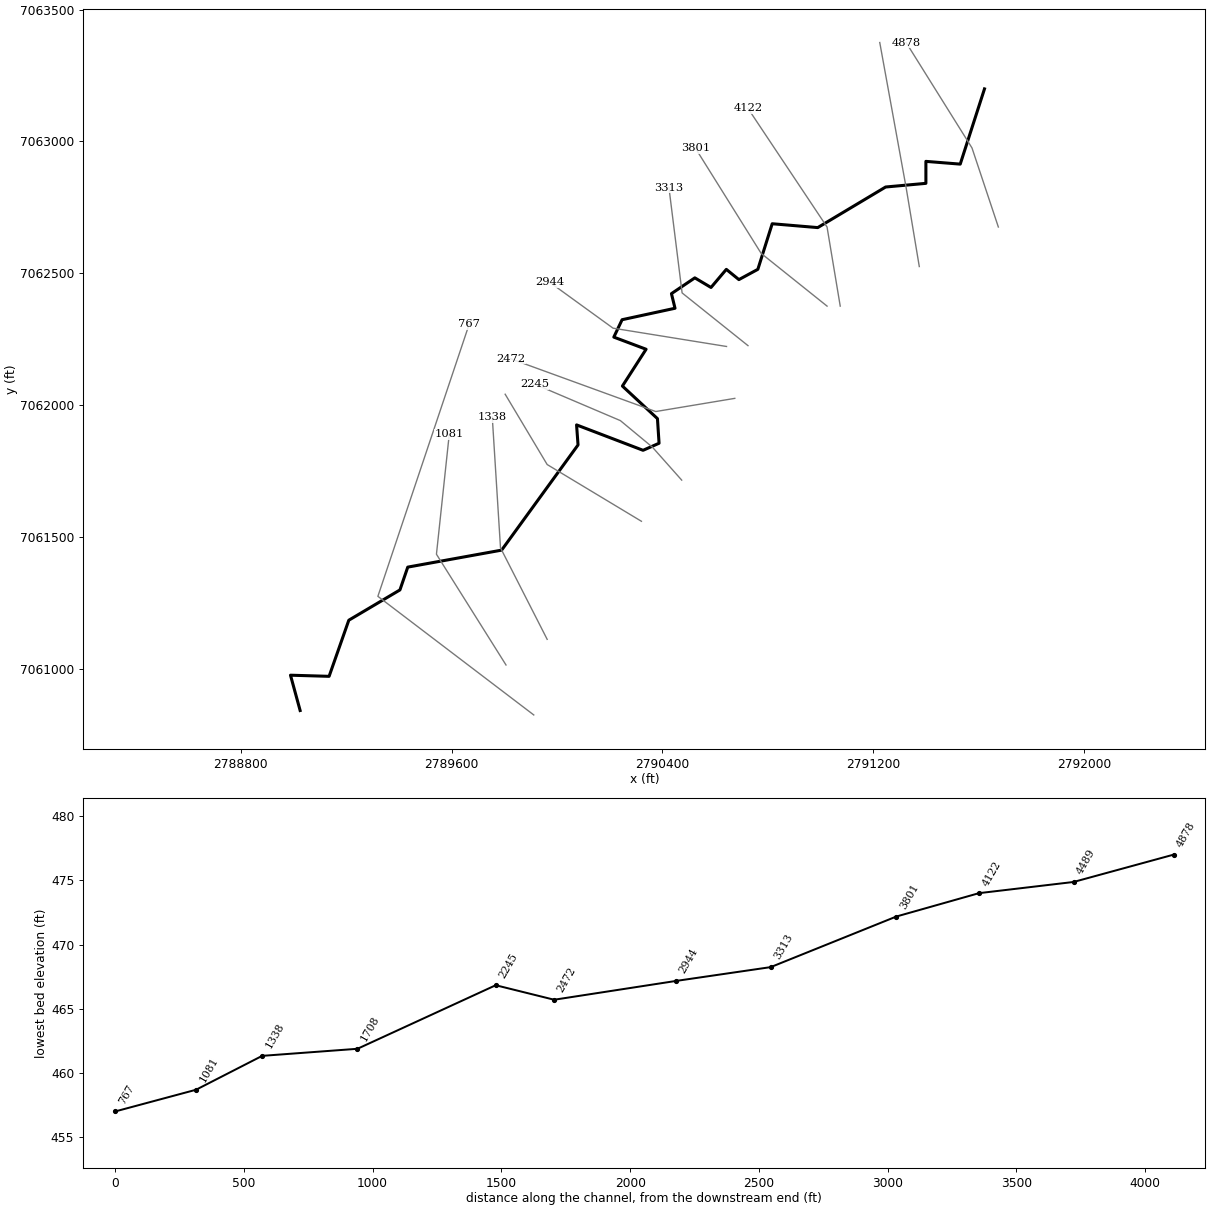
--- UNT 032 in LFCCL Watershed.prj (project) ---

Proj Title=UNT 032 in LFCCL Watershed Base Level Engineering
Current Plan=p01
Default Exp/Contr=0.3,0.1
English Units
Geom File=g01
Flow File=f01
Plan File=p01
BEGIN DESCRIPTION:
UNT 032 in LFCCL Watershed
END DESCRIPTION:

--- UNT 032 in LFCCL Watershed.p01 (plan) ---

Plan Title=Multiple Run
Short Identifier=Multiple
Geom File=g01
Flow File=f01
Subcritical Flow
K Sum by GR= 0
Std Step Tol= 0.01
Critical Tol= 0.01
Num of Std Step Trials= 20
Max Error Tol= 0.3
Flow Tol Ratio= 0.001
Split Flow NTrial= 30
Split Flow Tol= 0.02
Split Flow Ratio= 0.02
Log Output Level= 0
Friction Slope Method= 1
Unsteady Friction Slope Method= 2
Unsteady Bridges Friction Slope Method= 1
Parabolic Critical Depth
Global Vel Dist=  1 , 1 , 1
Global Log Level= 0
CheckData=True
Encroach Param= -1, 0, 0, 0
BEGIN DESCRIPTION:
Multiple Run
END DESCRIPTION:

--- UNT 032 in LFCCL Watershed.f01 (steady flow) ---

Flow Title=Multiple
Number of Profiles=7
Profile Names=10-year,25-year,50-year,1pct_min,100-year,1pct_plu,500-year
River Rch & RM= UNT 032 in LFCCL,Reach-1,4878
     595     787     941     558    1114    2223    1557
Boundary for River Rch & Prof#=UNT 032 in LFCCL,Reach-1,1
Up Type=0
Dn Type=3
Dn Slope=0.005
Boundary for River Rch & Prof#=UNT 032 in LFCCL,Reach-1,2
Up Type=0
Dn Type=3
Dn Slope=0.005
Boundary for River Rch & Prof#=UNT 032 in LFCCL,Reach-1,3
Up Type=0
Dn Type=3
Dn Slope=0.005
Boundary for River Rch & Prof#=UNT 032 in LFCCL,Reach-1,4
Up Type=0
Dn Type=3
Dn Slope=0.005
Boundary for River Rch & Prof#=UNT 032 in LFCCL,Reach-1,5
Up Type=0
Dn Type=3
Dn Slope=0.005
Boundary for River Rch & Prof#=UNT 032 in LFCCL,Reach-1,6
Up Type=0
Dn Type=3
Dn Slope=0.005
Boundary for River Rch & Prof#=UNT 032 in LFCCL,Reach-1,7
Up Type=0
Dn Type=3
Dn Slope=0.005

--- UNT 032 in LFCCL Watershed.g01 (geometry) ---

Geom Title=Existing Conditions

River Reach=UNT 032 in LFCCL,Reach-1
Reach XY= 30
      2791622.41      7063199.12      2791530.35      7062913.68
      2791400.06      7062924.11      2791400.06      7062840.72
      2791247.27      7062826.86      2790989.68      7062672.87
      2790816.88      7062687.47      2790762.38      7062514.50
      2790690.49      7062475.55      2790642.79      7062514.43
      2790584.69      7062445.68      2790523.31      7062482.17
      2790434.55      7062422.29      2790448.08      7062366.83
      2790247.28      7062323.37      2790215.87      7062257.34
      2790338.33      7062211.29      2790248.50      7062071.65
      2790381.45      7061948.09      2790387.56      7061854.69
      2790326.87      7061827.92      2790074.54      7061924.30
      2790080.09      7061848.26      2789790.18      7061449.18
      2789433.99      7061384.71      2789404.32      7061298.19
      2789210.28      7061183.26      2789135.50      7060970.37
      2788988.98      7060974.65      2789025.59      7060840.71

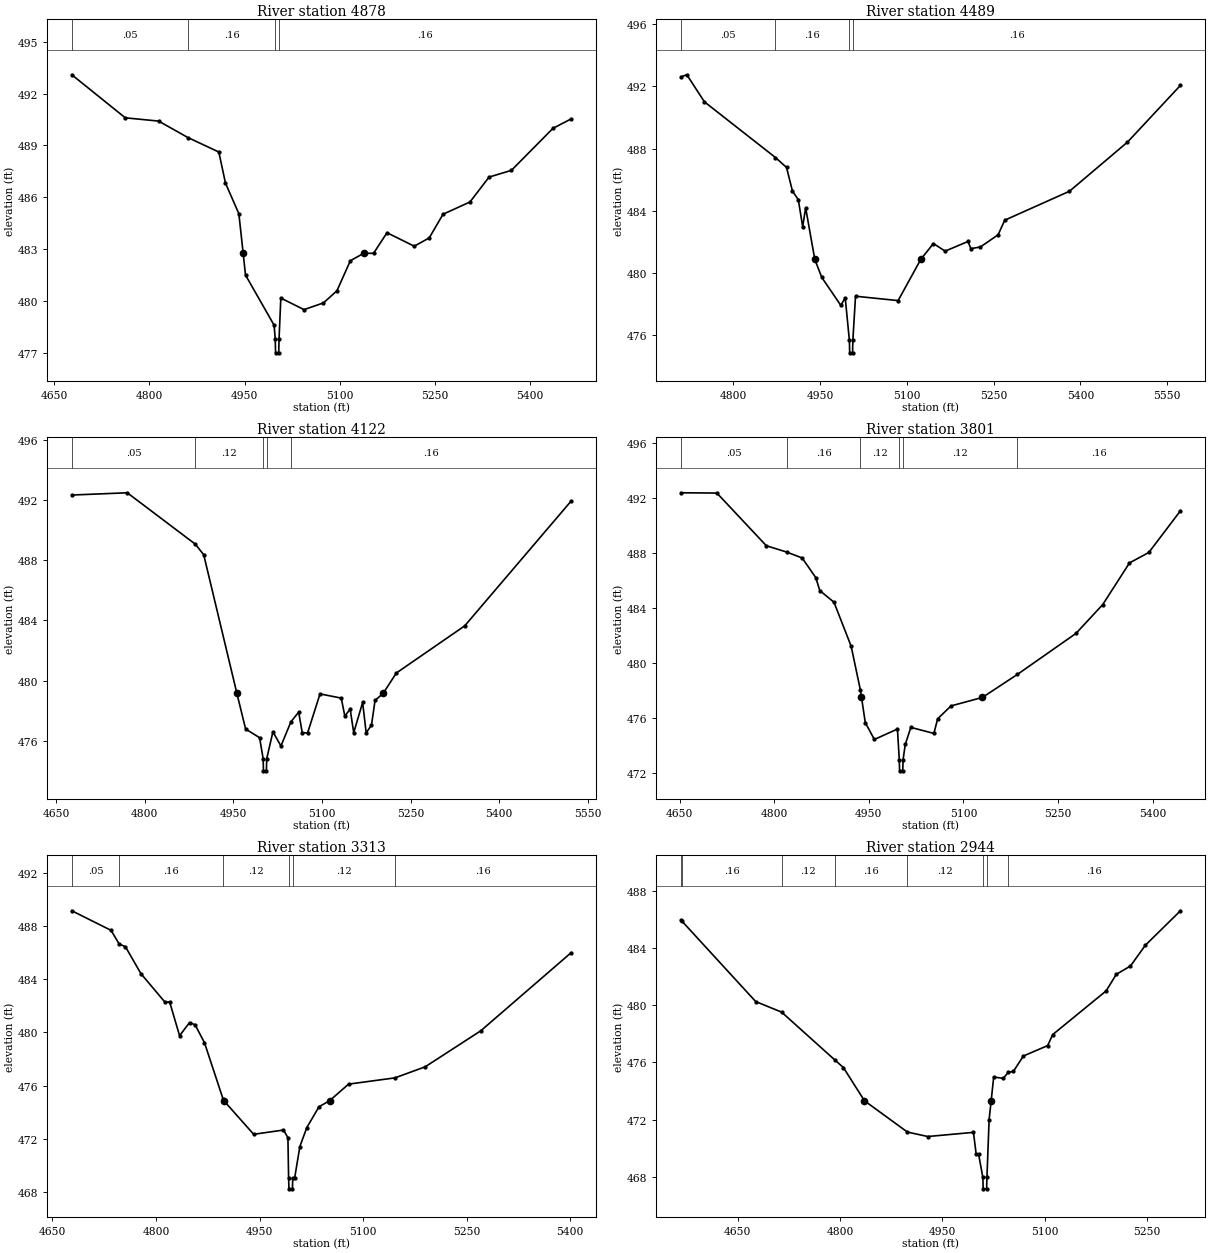
Type RM Length L Ch R = 1,4878,389,389,389
BEGIN DESCRIPTION:
UNT 032 in LFCCL Watershed 8.0
END DESCRIPTION:
XS GIS Cut Line= 3
      2791674.99      7062675.04      2791575.00      7062975.00
      2791324.99      7063375.01
#Sta/Elev= 30
  4677.5  493.09  4761.8  490.60  4814.5  490.41  4860.5  489.46  4909.4  488.62
  4919.9  486.82  4941.0  485.05  4947.8  482.76  4951.5  481.50  4996.6  478.60
  4998.4  477.80  4998.9  477.00  5003.9  477.00  5004.4  477.80  5007.2  480.17
  5043.8  479.50  5074.5  479.89  5095.7  480.59  5116.9  482.33  5137.9  482.76
  5153.5  482.76  5174.7  483.95  5217.7  483.17  5241.3  483.65  5263.1  485.02
  5305.6  485.73  5335.7  487.17  5371.0  487.56  5436.5  489.99  5465.4  490.54
#Mann=4,-1,0
  4677.5    0.05       0  4860.5    0.16       0  4998.4    0.07       0
  5004.4    0.16       0
Bank Sta=4947.8,5137.9
Exp/Cntr=0.3,0.1

Type RM Length L Ch R = 1,4489,367,367,367
BEGIN DESCRIPTION:
UNT 032 in LFCCL Watershed 7.0
END DESCRIPTION:
XS GIS Cut Line= 3
      2791374.99      7062525.05      2791325.00      7062825.00
      2791225.00      7063374.99
#Sta/Elev= 30
  4709.8  492.62  4719.9  492.75  4750.3  491.01  4873.0  487.43  4892.2  486.79
  4902.4  485.27  4912.5  484.72  4920.1  482.98  4925.2  484.20  4941.0  480.88
  4953.1  479.72  4986.0  477.92  4993.6  478.41  5000.8  475.67  5001.3  474.87
  5006.3  474.87  5006.8  475.67  5011.4  478.51  5085.0  478.23  5124.2  480.88
  5146.0  481.90  5166.3  481.41  5205.7  482.03  5210.8  481.57  5227.3  481.68
  5257.8  482.46  5269.3  483.40  5381.1  485.26  5481.4  488.42  5572.9  492.07
#Mann=4,-1,0
  4709.8    0.05       0  4873.0    0.16       0  5000.8    0.07       0
  5006.8    0.16       0
Bank Sta=4941,5124.2
Exp/Cntr=0.3,0.1

Type RM Length L Ch R = 1,4122,321,321,321
BEGIN DESCRIPTION:
UNT 032 in LFCCL Watershed 6.0
END DESCRIPTION:
XS GIS Cut Line= 3
      2791075.01      7062374.96      2791025.00      7062675.00
      2790725.00      7063124.99
#Sta/Elev= 30
  4676.9  492.32  4770.7  492.47  4885.7  489.06  4900.0  488.36  4956.2  479.14
  4970.9  476.78  4994.6  476.20  5000.6  474.80  5001.1  474.00  5006.1  474.00
  5006.6  474.80  5017.1  476.59  5030.7  475.65  5047.6  477.26  5060.7  477.90
  5066.7  476.54  5075.7  476.51  5096.8  479.11  5132.8  478.83  5138.8  477.63
  5147.8  478.11  5153.8  476.53  5168.9  478.54  5174.9  476.52  5183.9  477.04
  5189.9  478.68  5203.5  479.14  5226.0  480.50  5341.6  483.63  5521.9  491.93
#Mann=5,-1,0
  4676.9    0.05       0  4885.7    0.12       0  5000.6    0.07       0
  5006.6    0.12       0  5047.6    0.16       0
Bank Sta=4956.2,5203.5
Exp/Cntr=0.3,0.1

Type RM Length L Ch R = 1,3801,488,488,488
BEGIN DESCRIPTION:
UNT 032 in LFCCL Watershed 5.0
END DESCRIPTION:
XS GIS Cut Line= 3
      2791025.03      7062374.97      2790775.00      7062575.00
      2790525.00      7062975.00
#Sta/Elev= 30
  4652.2  492.40  4709.1  492.38  4787.5  488.55  4819.7  488.09  4844.3  487.66
  4865.9  486.23  4872.3  485.29  4894.8  484.44  4922.0  481.24  4936.7  478.04
  4938.4  477.52  4944.4  475.69  4958.8  474.46  4995.4  475.22  4998.3  472.98
  4998.8  472.18  5003.8  472.18  5004.3  472.98  5007.8  474.10  5016.6  475.34
  5053.2  474.90  5059.1  475.96  5080.3  476.90  5130.2  477.52  5185.5  479.19
  5278.4  482.17  5320.9  484.27  5363.3  487.30  5394.0  488.06  5444.1  491.09
#Mann=6,-1,0
  4652.2    0.05       0  4819.7    0.16       0  4936.7    0.12       0
  4998.3    0.07       0  5004.3    0.12       0  5185.5    0.16       0
Bank Sta=4938.4,5130.2
Exp/Cntr=0.3,0.1

Type RM Length L Ch R = 1,3313,369,369,369
BEGIN DESCRIPTION:
UNT 032 in LFCCL Watershed 4.0
END DESCRIPTION:
XS GIS Cut Line= 3
      2790724.98      7062225.02      2790475.00      7062425.00
      2790425.00      7062824.96
#Sta/Elev= 30
  4678.2  489.14  4735.0  487.67  4746.8  486.64  4755.8  486.44  4778.2  484.42
  4813.4  482.25  4819.8  482.30  4834.2  479.75  4848.7  480.74  4856.7  480.57
  4870.3  479.22  4897.0  475.02  4898.2  474.87  4941.5  472.34  4984.7  472.66
  4991.1  472.09  4992.1  469.04  4992.6  468.24  4997.6  468.24  4998.1  469.04
  5000.8  469.04  5008.4  471.42  5018.5  472.85  5036.1  474.41  5051.6  474.87
  5078.9  476.11  5146.0  476.58  5189.8  477.41  5270.4  480.12  5401.4  486.00
#Mann=6,-1,0
  4678.2    0.05       0  4746.8    0.16       0  4897.0    0.12       0
  4992.1    0.07       0  4998.1    0.12       0  5146.0    0.16       0
Bank Sta=4898.2,5051.6
Exp/Cntr=0.3,0.1

Type RM Length L Ch R = 1,2944,472,472,472
BEGIN DESCRIPTION:
XS3176A
END DESCRIPTION:
XS GIS Cut Line= 3
      2790643.54      7062221.83      2790212.97      7062291.28
      2789973.39      7062464.88
#Sta/Elev= 30
  4566.9  485.97  4568.2  485.89  4676.4  480.26  4714.4  479.52  4792.0  476.19
  4805.0  475.64  4835.8  473.32  4898.8  471.13  4928.6  470.82  4995.5  471.11
  4999.5  469.60  5003.0  469.60  5009.3  467.96  5009.8  467.16  5014.8  467.16
  5015.3  467.96  5018.5  472.01  5021.5  473.32  5025.2  474.98  5039.3  474.89
  5046.5  475.31  5054.0  475.37  5068.7  476.45  5104.3  477.18  5111.7  477.95
  5190.1  481.01  5204.8  482.16  5225.7  482.75  5247.5  484.20  5298.9  486.61
#Mann=8,-1,0
  4566.9    0.05       0  4568.2    0.16       0  4714.4    0.12       0
  4792.0    0.16       0  4898.8    0.12       0  5009.3    0.07       0
  5015.3    0.12       0  5046.5    0.16       0
Bank Sta=4835.8,5021.5
Exp/Cntr=0.3,0.1

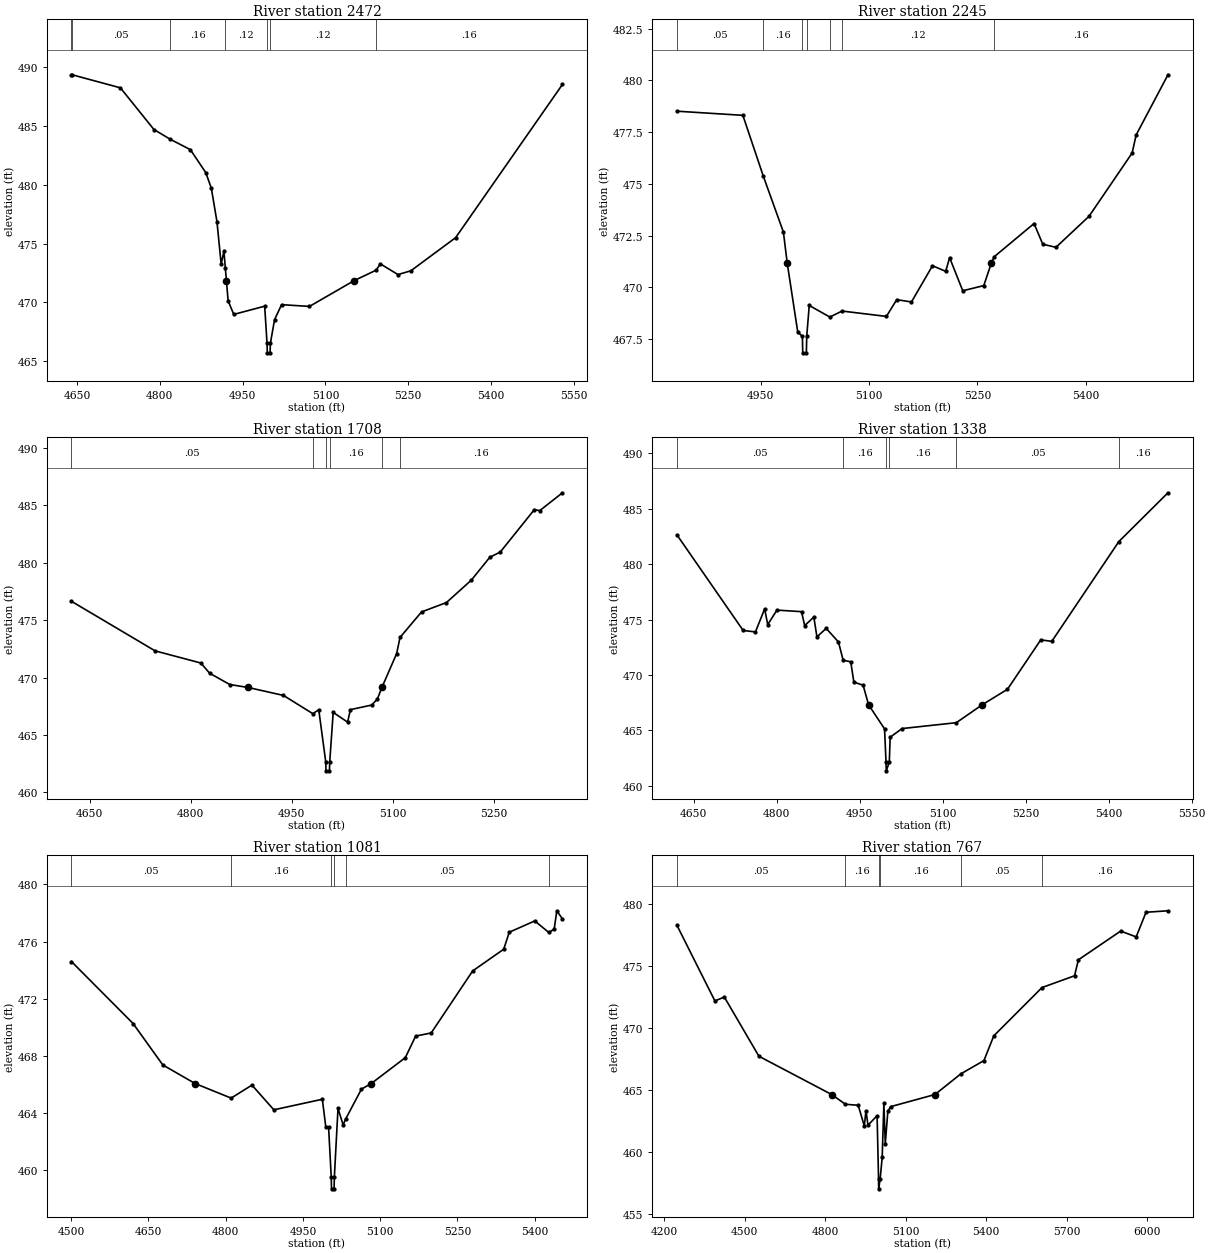
Type RM Length L Ch R = 1,2472,227,227,227
BEGIN DESCRIPTION:
UNT 032 in LFCCL Watershed 2.0
END DESCRIPTION:
XS GIS Cut Line= 3
      2790674.97      7062024.99      2790375.00      7061975.00
      2789825.04      7062174.99
#Sta/Elev= 30
  4639.9  489.36  4641.2  489.36  4728.6  488.25  4789.4  484.70  4819.0  483.87
  4855.3  482.99  4883.2  481.04  4893.3  479.71  4903.5  476.86  4911.1  473.25
  4916.1  474.34  4918.6  472.96  4920.6  471.85  4923.7  470.13  4933.9  468.97
  4989.9  469.67  4994.2  466.50  4994.7  465.70  4999.7  465.70  5000.2  466.50
  5007.8  468.52  5020.5  469.80  5071.0  469.65  5152.1  471.85  5191.6  472.73
  5199.4  473.27  5231.3  472.36  5254.6  472.68  5335.7  475.50  5529.2  488.54
#Mann=7,-1,0
  4639.9    0.16       0  4641.2    0.05       0  4819.0    0.16       0
  4918.6    0.12       0  4994.2    0.07       0  5000.2    0.12       0
  5191.6    0.16       0
Bank Sta=4920.6,5152.1
Exp/Cntr=0.3,0.1

Type RM Length L Ch R = 1,2245,537,537,537
BEGIN DESCRIPTION:
XS3180A
END DESCRIPTION:
XS GIS Cut Line= 4
      2790473.42      7061714.85      2790362.28      7061839.89
      2790240.75      7061940.58      2789914.38      7062079.46
#Sta/Elev= 30
  4834.0  478.51  4925.3  478.31  4953.6  475.37  4981.4  472.67  4986.7  471.17
  5001.3  467.83  5007.7  467.63  5008.2  466.83  5013.2  466.83  5013.7  467.63
  5017.2  469.12  5045.7  468.56  5062.6  468.85  5124.0  468.59  5138.3  469.40
  5158.7  469.29  5187.8  471.04  5206.1  470.77  5211.5  471.43  5229.7  469.83
  5258.8  470.08  5269.4  471.18  5273.4  471.48  5328.4  473.08  5340.5  472.08
  5358.7  471.93  5404.5  473.43  5464.2  476.49  5469.7  477.36  5513.8  480.27
#Mann=7,-1,0
  4834.0    0.05       0  4953.6    0.16       0  5007.7    0.07       0
  5013.7    0.16       0  5045.7    0.05       0  5062.6    0.12       0
  5273.4    0.16       0
Bank Sta=4986.7,5269.4
Exp/Cntr=0.3,0.1

Type RM Length L Ch R = 1,1708,370,370,370
BEGIN DESCRIPTION:
XS3179A
END DESCRIPTION:
XS GIS Cut Line= 3
      2790320.64      7061558.62      2789962.97      7061773.91
      2789803.61      7062040.68
#Sta/Elev= 30
  4623.1  476.65  4747.2  472.33  4815.1  471.27  4828.1  470.38  4857.9  469.40
  4885.2  469.14  4937.5  468.45  4981.1  466.86  4989.9  467.20  5000.2  462.68
  5000.7  461.88  5005.7  461.88  5006.2  462.68  5011.3  466.97  5032.7  466.12
  5036.8  467.21  5068.4  467.61  5076.8  468.13  5083.3  469.11  5083.5  469.14
  5105.4  472.09  5110.4  473.50  5142.3  475.72  5179.3  476.54  5216.3  478.50
  5243.5  480.48  5259.1  480.94  5309.7  484.64  5317.5  484.54  5351.3  486.10
#Mann=6,-1,0
  4623.1    0.05       0  4981.1    0.16       0  5000.2    0.07       0
  5006.2    0.16       0  5083.3    0.12       0  5110.4    0.16       0
Bank Sta=4885.2,5083.5
Exp/Cntr=0.3,0.1

Type RM Length L Ch R = 1,1338,257,257,257
BEGIN DESCRIPTION:
XS3178A
END DESCRIPTION:
XS GIS Cut Line= 3
      2789962.98      7061110.70      2789785.89      7061457.94
      2789754.64      7061954.46
#Sta/Elev= 30
  4619.9  482.65  4739.6  474.01  4761.8  473.88  4778.4  475.96  4784.0  474.54
  4800.6  475.85  4845.1  475.71  4850.7  474.45  4867.3  475.22  4872.9  473.43
  4889.6  474.20  4911.8  472.97  4920.3  471.32  4934.0  471.18  4939.6  469.34
  4956.3  469.07  4966.3  467.29  4995.1  465.12  4997.7  462.13  4998.2  461.33
  5003.7  462.13  5005.2  464.37  5026.8  465.15  5124.8  465.68  5171.3  467.29
  5217.2  468.70  5277.3  473.16  5297.3  473.03  5418.4  482.04  5507.2  486.45
#Mann=6,-1,0
  4619.9    0.05       0  4920.3    0.16       0  4997.7    0.07       0
  5003.7    0.16       0  5124.8    0.05       0  5418.4    0.16       0
Bank Sta=4966.3,5171.3
Exp/Cntr=0.3,0.1

Type RM Length L Ch R = 1,1081,314,314,314
BEGIN DESCRIPTION:
XS3177A
END DESCRIPTION:
XS GIS Cut Line= 3
      2789806.75      7061013.46      2789542.83      7061433.64
      2789591.44      7061888.46
#Sta/Elev= 30
  4500.4  474.60  4620.2  470.26  4677.9  467.36  4740.6  466.06  4810.6  465.04
  4851.0  465.95  4893.5  464.22  4987.7  464.96  4994.4  463.02  4999.8  463.02
  5005.0  459.49  5005.5  458.69  5010.5  458.69  5011.0  459.49  5018.1  464.32
  5028.1  463.16  5032.7  463.56  5063.7  465.67  5082.7  466.06  5148.8  467.87
  5168.9  469.38  5199.1  469.60  5279.6  473.94  5339.9  475.46  5350.7  476.65
  5400.2  477.44  5427.2  476.64  5437.9  476.86  5443.0  478.15  5454.0  477.58
#Mann=6,-1,0
  4500.4    0.05       0  4810.6    0.16       0  5005.0    0.07       0
  5011.0    0.16       0  5032.7    0.05       0  5427.2    0.16       0
Bank Sta=4740.6,5082.7
Exp/Cntr=0.3,0.1

Type RM Length L Ch R = 1,767,0,0,0
BEGIN DESCRIPTION:
UNT 032 in LFCCL Watershed 1.0
END DESCRIPTION:
XS GIS Cut Line= 3
      2789912.11      7060823.86      2789320.61      7061273.91
      2789666.75      7062305.34
#Sta/Elev= 30
  4247.0  478.29  4388.6  472.18  4423.9  472.49  4552.8  467.71  4824.0  464.62
  4875.5  463.83  4923.0  463.75  4945.8  462.08  4952.0  463.31  4959.6  462.14
  4993.5  462.91  4998.9  457.80  4999.4  457.00  5004.9  457.80  5012.5  459.54
  5018.8  463.91  5024.0  460.64  5033.6  463.27  5044.1  463.64  5209.4  464.62
  5306.0  466.29  5391.9  467.36  5428.7  469.36  5608.6  473.26  5729.8  474.21
  5744.1  475.50  5901.8  477.82  5959.6  477.35  5996.4  479.34  6078.2  479.46
#Mann=6,-1,0
  4247.0    0.05       0  4875.5    0.16       0  4998.9    0.07       0
  5004.9    0.16       0  5306.0    0.05       0  5608.6    0.16       0
Bank Sta=4824,5209.4
Exp/Cntr=0.3,0.1

Chan Stop Cuts=-1