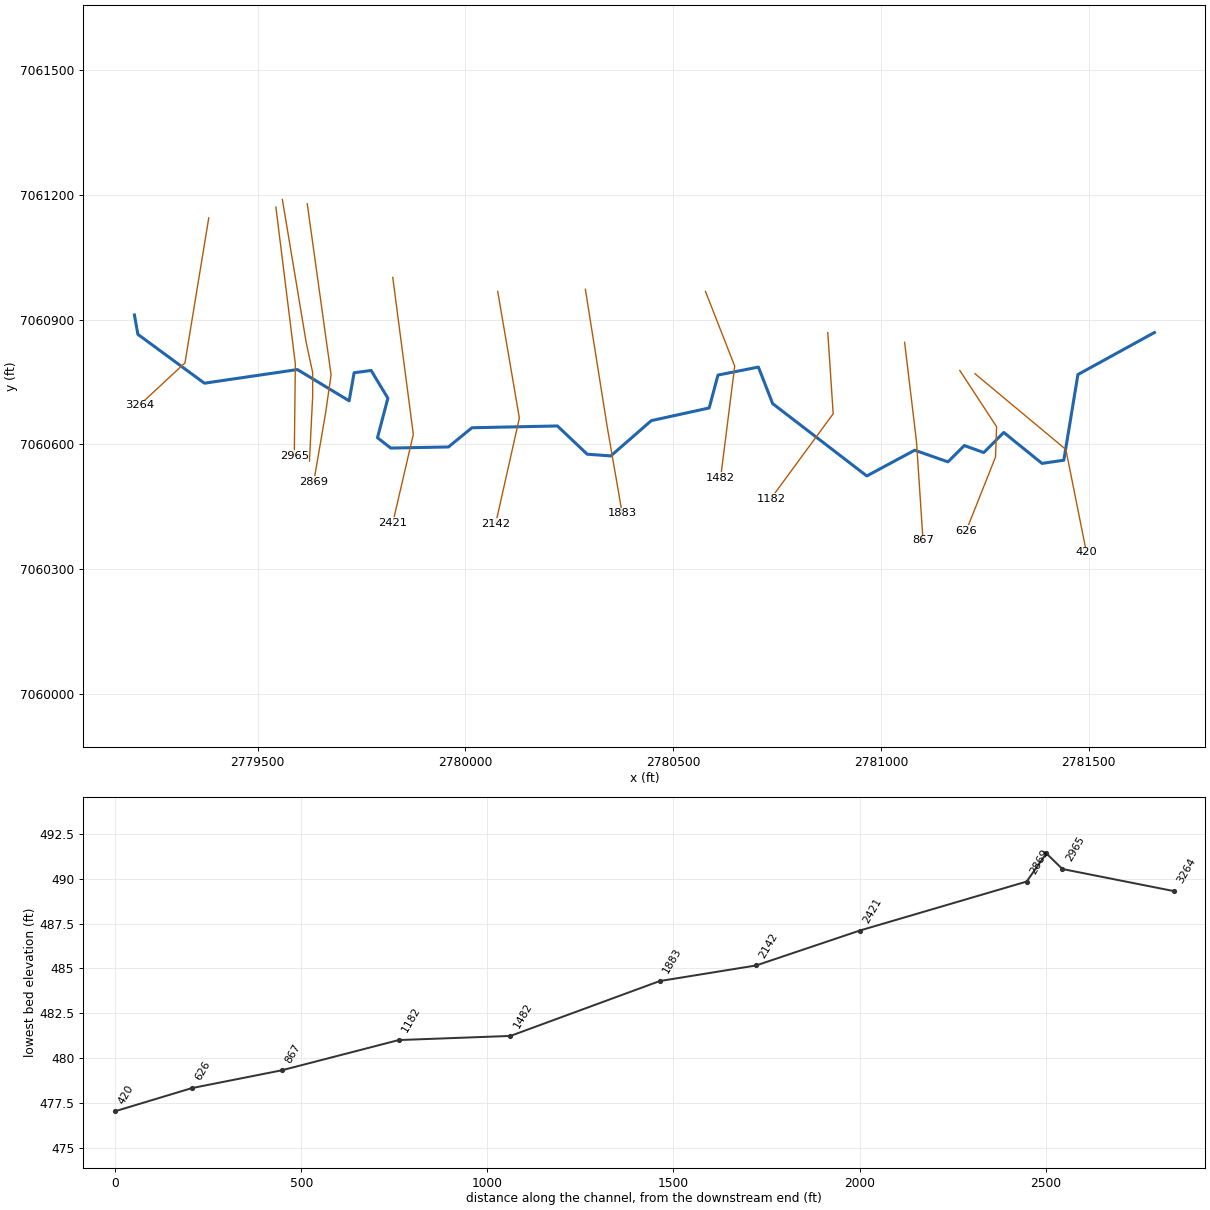
--- UNT 035 in LFCCL Watershed.prj (project) ---

Proj Title=UNT 035 in LFCCL Watershed Base Level Engineering
Current Plan=p01
Default Exp/Contr=0.3,0.1
English Units
Geom File=g01
Flow File=f01
Plan File=p01
BEGIN DESCRIPTION:
UNT 035 in LFCCL Watershed
END DESCRIPTION:

--- UNT 035 in LFCCL Watershed.p01 (plan) ---

Plan Title=Multiple Run
Short Identifier=Multiple
Geom File=g01
Flow File=f01
Subcritical Flow
K Sum by GR= 0
Std Step Tol= 0.01
Critical Tol= 0.01
Num of Std Step Trials= 20
Max Error Tol= 0.3
Flow Tol Ratio= 0.001
Split Flow NTrial= 30
Split Flow Tol= 0.02
Split Flow Ratio= 0.02
Log Output Level= 0
Friction Slope Method= 1
Unsteady Friction Slope Method= 2
Unsteady Bridges Friction Slope Method= 1
Parabolic Critical Depth
Global Vel Dist=  1 , 1 , 1
Global Log Level= 0
CheckData=True
Encroach Param= -1, 0, 0, 0
BEGIN DESCRIPTION:
Multiple Run
END DESCRIPTION:

--- UNT 035 in LFCCL Watershed.f01 (steady flow) ---

Flow Title=Multiple
Number of Profiles=7
Profile Names=10-year,25-year,50-year,1pct_min,100-year,1pct_plu,500-year
River Rch & RM= UNT 035 in LFCCL,Reach-1,3264
     398     516     608     356     710    1418     967
Boundary for River Rch & Prof#=UNT 035 in LFCCL,Reach-1,1
Up Type=0
Dn Type=3
Dn Slope=0.005
Boundary for River Rch & Prof#=UNT 035 in LFCCL,Reach-1,2
Up Type=0
Dn Type=3
Dn Slope=0.005
Boundary for River Rch & Prof#=UNT 035 in LFCCL,Reach-1,3
Up Type=0
Dn Type=3
Dn Slope=0.005
Boundary for River Rch & Prof#=UNT 035 in LFCCL,Reach-1,4
Up Type=0
Dn Type=3
Dn Slope=0.005
Boundary for River Rch & Prof#=UNT 035 in LFCCL,Reach-1,5
Up Type=0
Dn Type=3
Dn Slope=0.005
Boundary for River Rch & Prof#=UNT 035 in LFCCL,Reach-1,6
Up Type=0
Dn Type=3
Dn Slope=0.005
Boundary for River Rch & Prof#=UNT 035 in LFCCL,Reach-1,7
Up Type=0
Dn Type=3
Dn Slope=0.005

--- UNT 035 in LFCCL Watershed.g01 (geometry) ---

Geom Title=Existing Conditions

River Reach=UNT 035 in LFCCL,Reach-1
Reach XY= 30
      2779203.36      7060911.12      2779211.71      7060864.49
      2779371.76      7060746.95      2779595.63      7060779.78
      2779720.09      7060704.56      2779732.03      7060772.12
      2779773.06      7060777.55      2779813.27      7060710.81
      2779788.30      7060615.72      2779820.12      7060590.87
      2779959.16      7060593.53      2780015.48      7060639.74
      2780221.22      7060644.08      2780292.97      7060576.13
      2780349.77      7060571.95      2780447.27      7060656.89
      2780586.49      7060687.36      2780607.66      7060766.55
      2780704.92      7060785.75      2780739.30      7060697.76
      2780965.78      7060523.73      2781081.08      7060585.71
      2781161.08      7060557.69      2781200.55      7060596.95
      2781247.33      7060580.02      2781295.40      7060628.41
      2781387.35      7060553.98      2781439.90      7060561.63
      2781473.84      7060767.81      2781657.92      7060868.88

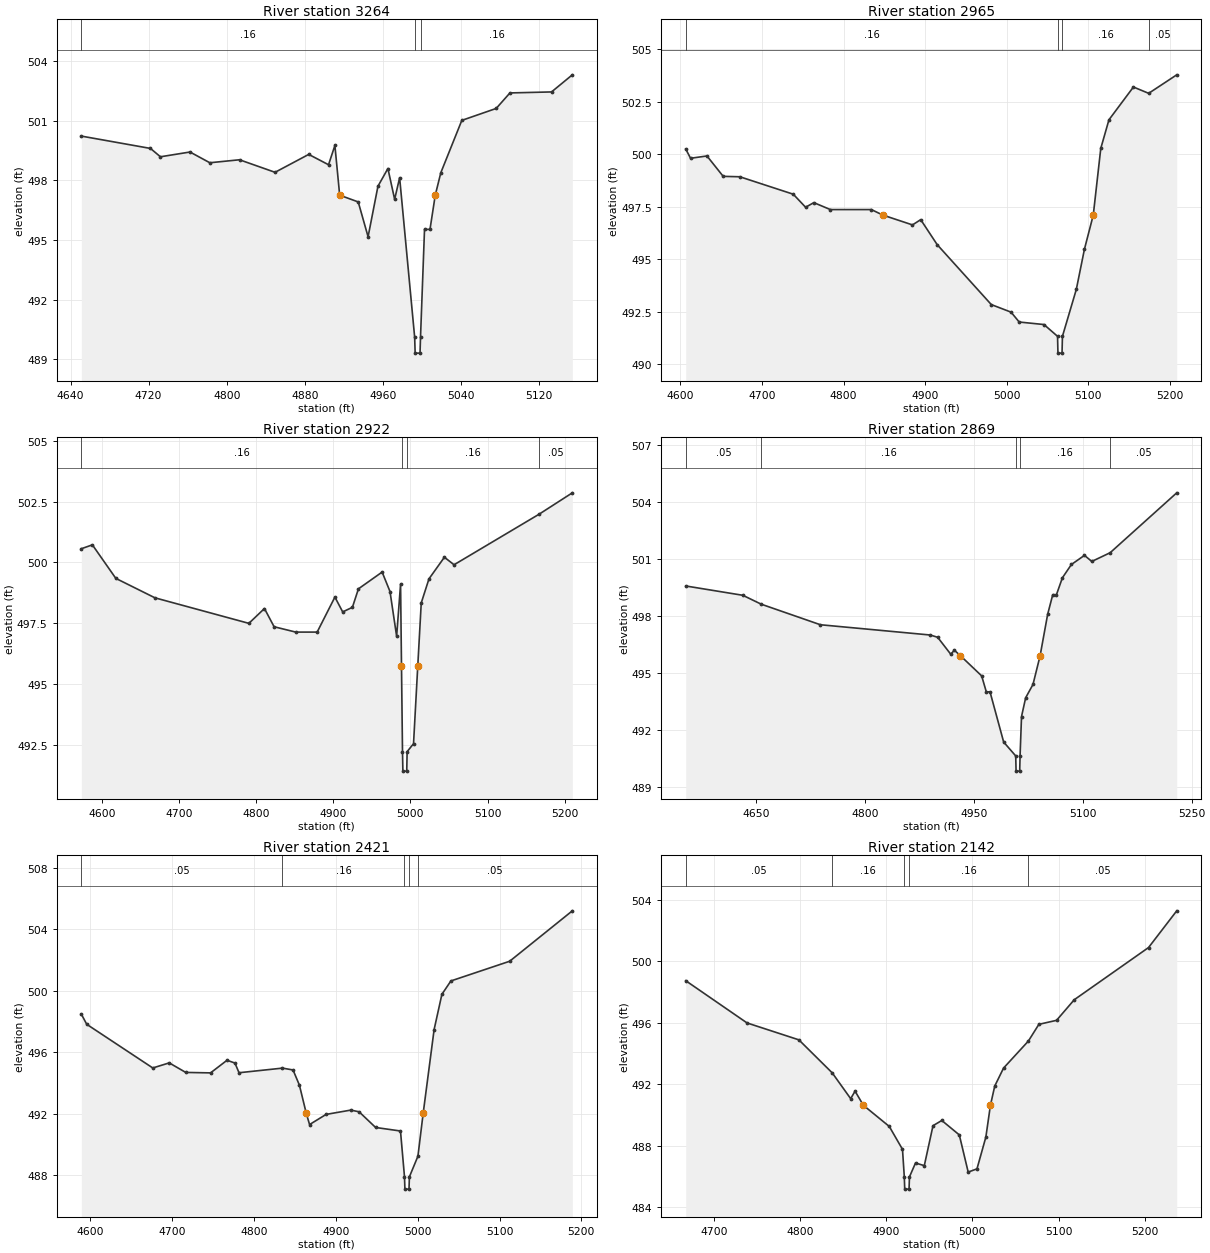
Type RM Length L Ch R = 1,3264,299,299,299
BEGIN DESCRIPTION:
UNT 035 in LFCCL Watershed 4.0
END DESCRIPTION:
XS GIS Cut Line= 3
      2779382.30      7061144.82      2779325.01      7060795.86
      2779215.63      7060694.29
#Sta/Elev= 30
  4651.1  500.22  4721.9  499.60  4732.1  499.18  4762.4  499.42  4782.7  498.88
  4813.1  499.03  4849.5  498.40  4884.0  499.30  4904.3  498.78  4910.8  499.75
  4915.7  497.25  4934.7  496.91  4944.8  495.16  4954.9  497.70  4965.1  498.59
  4972.0  497.04  4977.1  498.13  4992.5  490.11  4993.0  489.31  4998.0  489.31
  4998.5  490.11  5002.6  495.53  5008.2  495.53  5013.6  497.25  5019.3  498.38
  5040.8  501.01  5076.0  501.61  5090.1  502.39  5132.7  502.44  5154.0  503.30
#Mann=3,-1,0
  4651.1    0.16       0  4992.5    0.07       0  4998.5    0.16       0
Bank Sta=4915.7,5013.6
Exp/Cntr=0.3,0.1

Type RM Length L Ch R = 1,2965,43,43,43
BEGIN DESCRIPTION:
XS3181A
END DESCRIPTION:
XS GIS Cut Line= 3
      2779543.77      7061170.81      2779590.64      7060793.25
      2779588.03      7060571.92
#Sta/Elev= 30
  4606.6  500.25  4612.5  499.81  4632.6  499.92  4652.5  498.95  4672.9  498.93
  4738.4  498.10  4753.5  497.48  4763.6  497.70  4783.8  497.37  4834.1  497.37
  4848.0  497.11  4884.5  496.64  4894.6  496.89  4914.8  495.70  4981.1  492.85
  5005.3  492.49  5015.3  492.02  5045.7  491.90  5062.3  491.34  5062.8  490.54
  5067.8  490.54  5068.3  491.34  5085.3  493.57  5095.3  495.49  5106.1  497.11
  5115.3  500.28  5125.3  501.64  5155.3  503.20  5174.0  502.90  5208.4  503.78
#Mann=4,-1,0
  4606.6    0.16       0  5062.3    0.07       0  5068.3    0.16       0
  5174.0    0.05       0
Bank Sta=4848,5106.1
Exp/Cntr=0.3,0.1

Type RM Length L Ch R = 1,2922,53,53,53
BEGIN DESCRIPTION:
XS3182A
END DESCRIPTION:
XS GIS Cut Line= 5
      2779559.38      7061189.12      2779616.68      7060845.33
      2779632.30      7060772.42      2779632.30      7060715.13
      2779624.52      7060559.41
#Sta/Elev= 30
  4573.6  500.56  4587.9  500.72  4618.3  499.34  4669.0  498.54  4790.7  497.49
  4810.9  498.10  4823.4  497.35  4851.5  497.13  4879.2  497.13  4902.2  498.57
  4912.3  497.96  4924.9  498.15  4932.7  498.91  4963.4  499.60  4973.6  498.80
  4982.2  496.96  4987.3  499.10  4988.5  495.74  4989.8  492.21  4990.3  491.41
  4995.3  491.41  4995.8  492.21  5004.1  492.54  5009.6  495.74  5014.1  498.33
  5024.1  499.32  5044.1  500.21  5056.6  499.90  5166.8  501.98  5209.9  502.86
#Mann=4,-1,0
  4573.6    0.16       0  4989.8    0.07       0  4995.8    0.16       0
  5166.8    0.05       0
Bank Sta=4988.5,5009.6
Exp/Cntr=0.3,0.1

Type RM Length L Ch R = 1,2869,448,448,448
BEGIN DESCRIPTION:
XS3183A
END DESCRIPTION:
XS GIS Cut Line= 4
      2779619.28      7061178.69      2779676.57      7060767.21
      2779663.55      7060676.06      2779634.96      7060509.73
#Sta/Elev= 30
  4553.1  499.58  4631.7  499.09  4657.2  498.62  4738.6  497.54  4890.0  497.00
  4900.1  496.88  4918.1  495.99  4923.1  496.20  4931.5  495.91  4960.7  494.85
  4967.1  494.01  4972.2  494.01  4991.0  491.37  5007.6  490.64  5008.1  489.84
  5013.1  489.84  5013.6  490.64  5015.6  492.71  5021.3  493.70  5031.4  494.40
  5041.2  495.91  5051.6  498.09  5058.6  499.12  5063.7  499.12  5071.9  500.01
  5084.3  500.71  5102.3  501.19  5112.4  500.87  5137.7  501.33  5229.4  504.48
#Mann=5,-1,0
  4553.1    0.05       0  4657.2    0.16       0  5007.6    0.07       0
  5013.6    0.16       0  5137.7    0.05       0
Bank Sta=4931.5,5041.2
Exp/Cntr=0.3,0.1

Type RM Length L Ch R = 1,2421,279,279,279
BEGIN DESCRIPTION:
XS3184A
END DESCRIPTION:
XS GIS Cut Line= 3
      2779825.02      7061001.54      2779874.49      7060623.98
      2779825.01      7060410.42
#Sta/Elev= 30
  4589.0  498.49  4595.6  497.83  4676.3  494.99  4696.4  495.32  4716.6  494.70
  4746.9  494.67  4767.0  495.49  4776.7  495.31  4781.7  494.68  4834.8  494.98
  4847.7  494.86  4855.5  493.87  4863.9  492.03  4867.9  491.31  4888.1  491.97
  4918.3  492.25  4928.4  492.14  4948.6  491.12  4979.0  490.89  4983.9  487.91
  4984.4  487.11  4989.4  487.11  4989.9  487.91  5000.3  489.25  5006.7  492.03
  5020.1  497.49  5029.6  499.78  5040.6  500.65  5112.4  501.93  5189.0  505.21
#Mann=5,-1,0
  4589.0    0.05       0  4834.8    0.16       0  4983.9    0.07       0
  4989.9    0.16       0  5000.3    0.05       0
Bank Sta=4863.9,5006.7
Exp/Cntr=0.3,0.1

Type RM Length L Ch R = 1,2142,259,259,259
BEGIN DESCRIPTION:
XS3185A
END DESCRIPTION:
XS GIS Cut Line= 3
      2780077.62      7060967.72      2780129.70      7060663.04
      2780072.66      7060408.96
#Sta/Elev= 30
  4667.5  498.73  4738.6  495.98  4798.7  494.88  4837.4  492.73  4858.8  491.05
  4863.9  491.54  4873.5  490.62  4903.6  489.24  4918.9  487.75  4921.0  485.96
  4921.5  485.16  4926.5  485.16  4927.0  485.96  4934.0  486.86  4944.2  486.69
  4954.3  489.29  4964.5  489.63  4984.8  488.69  4995.1  486.27  5005.3  486.48
  5015.6  488.55  5020.9  490.62  5025.9  491.87  5036.1  493.04  5064.9  494.80
  5077.1  495.89  5097.6  496.15  5118.1  497.49  5204.3  500.89  5237.0  503.28
#Mann=5,-1,0
  4667.5    0.05       0  4837.4    0.16       0  4921.0    0.07       0
  4927.0    0.16       0  5064.9    0.05       0
Bank Sta=4873.5,5020.9
Exp/Cntr=0.3,0.1

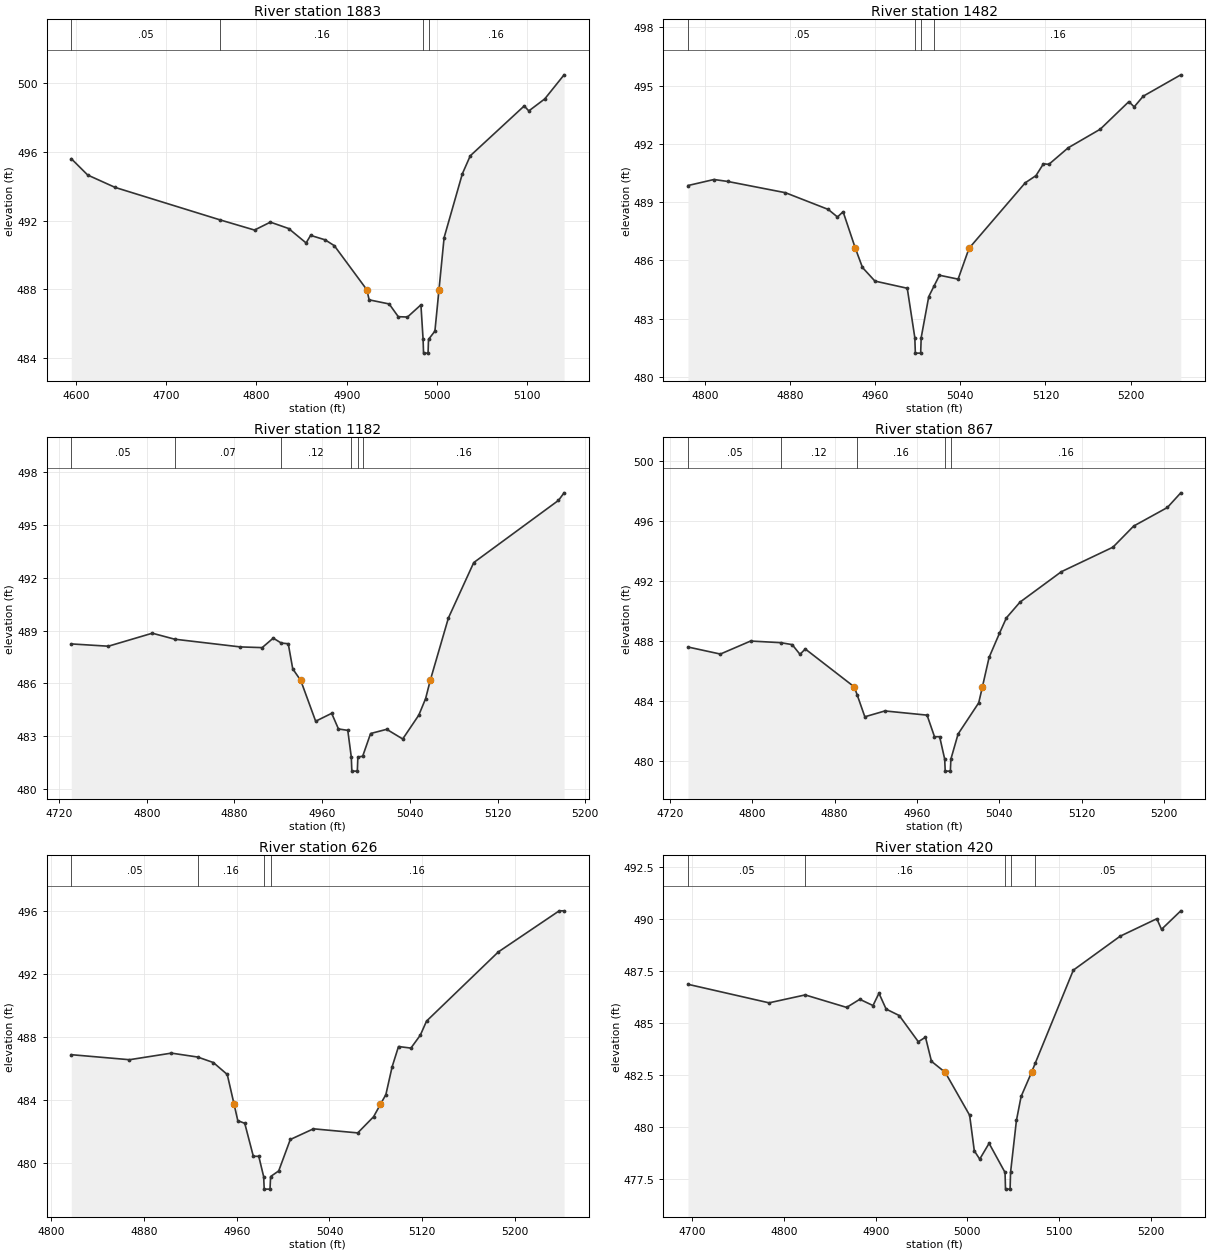
Type RM Length L Ch R = 1,1883,401,401,401
BEGIN DESCRIPTION:
XS3186A
END DESCRIPTION:
XS GIS Cut Line= 3
      2780288.55      7060972.96      2780340.64      7060644.81
      2780377.09      7060433.90
#Sta/Elev= 30
  4594.7  495.60  4612.9  494.65  4643.3  493.93  4759.7  492.04  4797.8  491.45
  4815.4  491.91  4835.6  491.54  4855.0  490.70  4860.0  491.14  4876.1  490.88
  4886.3  490.54  4922.3  487.98  4924.9  487.39  4947.1  487.15  4957.2  486.41
  4967.4  486.39  4982.3  487.10  4984.7  485.09  4985.2  484.29  4990.2  484.29
  4990.7  485.09  4997.8  485.57  5002.3  487.97  5008.0  491.01  5028.2  494.72
  5037.0  495.77  5096.8  498.67  5101.9  498.38  5119.6  499.08  5141.0  500.48
#Mann=4,-1,0
  4594.7    0.05       0  4759.7    0.16       0  4984.7    0.07       0
  4990.7    0.16       0
Bank Sta=4922.3,5002.3
Exp/Cntr=0.3,0.1

Type RM Length L Ch R = 1,1482,300,300,300
BEGIN DESCRIPTION:
XS3187A
END DESCRIPTION:
XS GIS Cut Line= 3
      2780577.61      7060967.74      2780647.93      7060788.04
      2780614.09      7060519.94
#Sta/Elev= 30
  4784.0  489.86  4808.4  490.17  4821.3  490.07  4875.6  489.49  4915.8  488.63
  4924.5  488.24  4929.8  488.51  4941.3  486.63  4948.0  485.64  4959.7  484.94
  4990.1  484.57  4997.2  482.03  4997.7  481.23  5002.7  481.23  5003.2  482.03
  5010.3  484.14  5015.5  484.71  5020.4  485.24  5037.9  485.04  5048.2  486.63
  5101.0  490.00  5111.1  490.37  5118.1  490.98  5123.2  490.95  5141.3  491.80
  5171.5  492.76  5198.4  494.18  5203.4  493.91  5211.9  494.46  5247.2  495.56
#Mann=4,-1,0
  4784.0    0.05       0  4997.2    0.03       0  5003.2    0.05       0
  5015.5    0.16       0
Bank Sta=4941.3,5048.2
Exp/Cntr=0.3,0.1

Type RM Length L Ch R = 1,1182,315,315,315
BEGIN DESCRIPTION:
XS3188A
END DESCRIPTION:
XS GIS Cut Line= 3
      2780871.89      7060868.75      2780884.91      7060673.46
      2780734.72      7060468.90
#Sta/Elev= 30
  4731.2  488.24  4765.0  488.11  4805.1  488.85  4825.4  488.51  4885.3  488.07
  4905.3  488.03  4915.4  488.57  4922.7  488.29  4929.1  488.25  4933.2  486.82
  4940.5  486.16  4954.1  483.84  4968.7  484.29  4974.9  483.40  4983.4  483.32
  4986.6  481.80  4987.1  481.00  4992.1  481.00  4992.6  481.80  4997.0  481.85
  5004.2  483.14  5018.9  483.38  5033.5  482.83  5048.2  484.19  5054.4  485.13
  5058.6  486.16  5075.2  489.72  5098.3  492.87  5175.6  496.41  5180.7  496.84
#Mann=6,-1,0
  4731.2    0.05       0  4825.4    0.07       0  4922.7    0.12       0
  4986.6    0.07       0  4992.6    0.12       0  4997.0    0.16       0
Bank Sta=4940.5,5058.6
Exp/Cntr=0.3,0.1

Type RM Length L Ch R = 1,867,241,241,241
BEGIN DESCRIPTION:
XS3189A
END DESCRIPTION:
XS GIS Cut Line= 3
      2781056.78      7060845.35      2781085.43      7060605.75
      2781101.01      7060369.37
#Sta/Elev= 30
  4737.8  487.60  4769.2  487.13  4798.6  488.00  4827.9  487.89  4838.9  487.76
  4846.5  487.11  4851.6  487.47  4899.1  484.94  4902.1  484.38  4909.4  482.94
  4928.9  483.33  4969.8  483.05  4977.0  481.61  4982.0  481.61  4986.9  480.11
  4987.4  479.31  4992.4  479.31  4992.9  480.11  4999.9  481.79  5019.9  483.87
  5023.5  484.94  5030.0  486.91  5040.0  488.51  5046.8  489.55  5060.0  490.60
  5100.1  492.63  5150.2  494.27  5170.3  495.68  5203.0  496.92  5216.0  497.90
#Mann=5,-1,0
  4737.8    0.05       0  4827.9    0.12       0  4902.1    0.16       0
  4986.9    0.07       0  4992.9    0.16       0
Bank Sta=4899.1,5023.5
Exp/Cntr=0.3,0.1

Type RM Length L Ch R = 1,626,206,206,206
BEGIN DESCRIPTION:
XS3190A
END DESCRIPTION:
XS GIS Cut Line= 4
      2781189.62      7060777.59      2781278.14      7060642.21
      2781275.53      7060569.29      2781205.20      7060392.16
#Sta/Elev= 30
  4817.2  486.88  4867.4  486.56  4903.6  486.98  4926.3  486.73  4939.8  486.38
  4951.8  485.62  4957.7  483.72  4960.9  482.68  4966.9  482.51  4974.3  480.41
  4979.0  480.41  4983.2  479.12  4983.7  478.32  4988.7  478.32  4989.2  479.12
  4996.2  479.48  5006.2  481.48  5026.2  482.16  5064.4  481.90  5078.1  482.93
  5084.0  483.72  5088.7  484.34  5094.1  486.11  5099.6  487.40  5110.3  487.30
  5118.4  488.12  5123.8  489.02  5185.7  493.42  5238.3  496.04  5242.5  496.04
#Mann=4,-1,0
  4817.2    0.05       0  4926.3    0.16       0  4983.2    0.07       0
  4989.2    0.16       0
Bank Sta=4957.7,5084
Exp/Cntr=0.3,0.1

Type RM Length L Ch R = 1,420,0,0,0
BEGIN DESCRIPTION:
UNT 035 in LFCCL Watershed 1.0
END DESCRIPTION:
XS GIS Cut Line= 3
      2781226.07      7060769.80      2781444.80      7060587.52
      2781494.28      7060340.15
#Sta/Elev= 30
  4695.5  486.87  4783.8  485.98  4823.2  486.36  4868.4  485.76  4882.7  486.15
  4897.1  485.85  4903.6  486.44  4911.4  485.68  4925.7  485.37  4946.5  484.11
  4954.3  484.33  4960.8  483.17  4975.8  482.64  5002.4  480.58  5007.5  478.87
  5013.4  478.47  5023.6  479.23  5041.0  477.83  5041.5  477.03  5046.5  477.03
  5047.0  477.83  5053.4  480.33  5058.5  481.48  5069.9  482.64  5073.9  483.08
  5115.4  487.55  5166.4  489.18  5206.4  490.02  5211.5  489.51  5232.5  490.40
#Mann=5,-1,0
  4695.5    0.05       0  4823.2    0.16       0  5041.0    0.07       0
  5047.0    0.16       0  5073.9    0.05       0
Bank Sta=4975.8,5069.9
Exp/Cntr=0.3,0.1

Chan Stop Cuts=-1