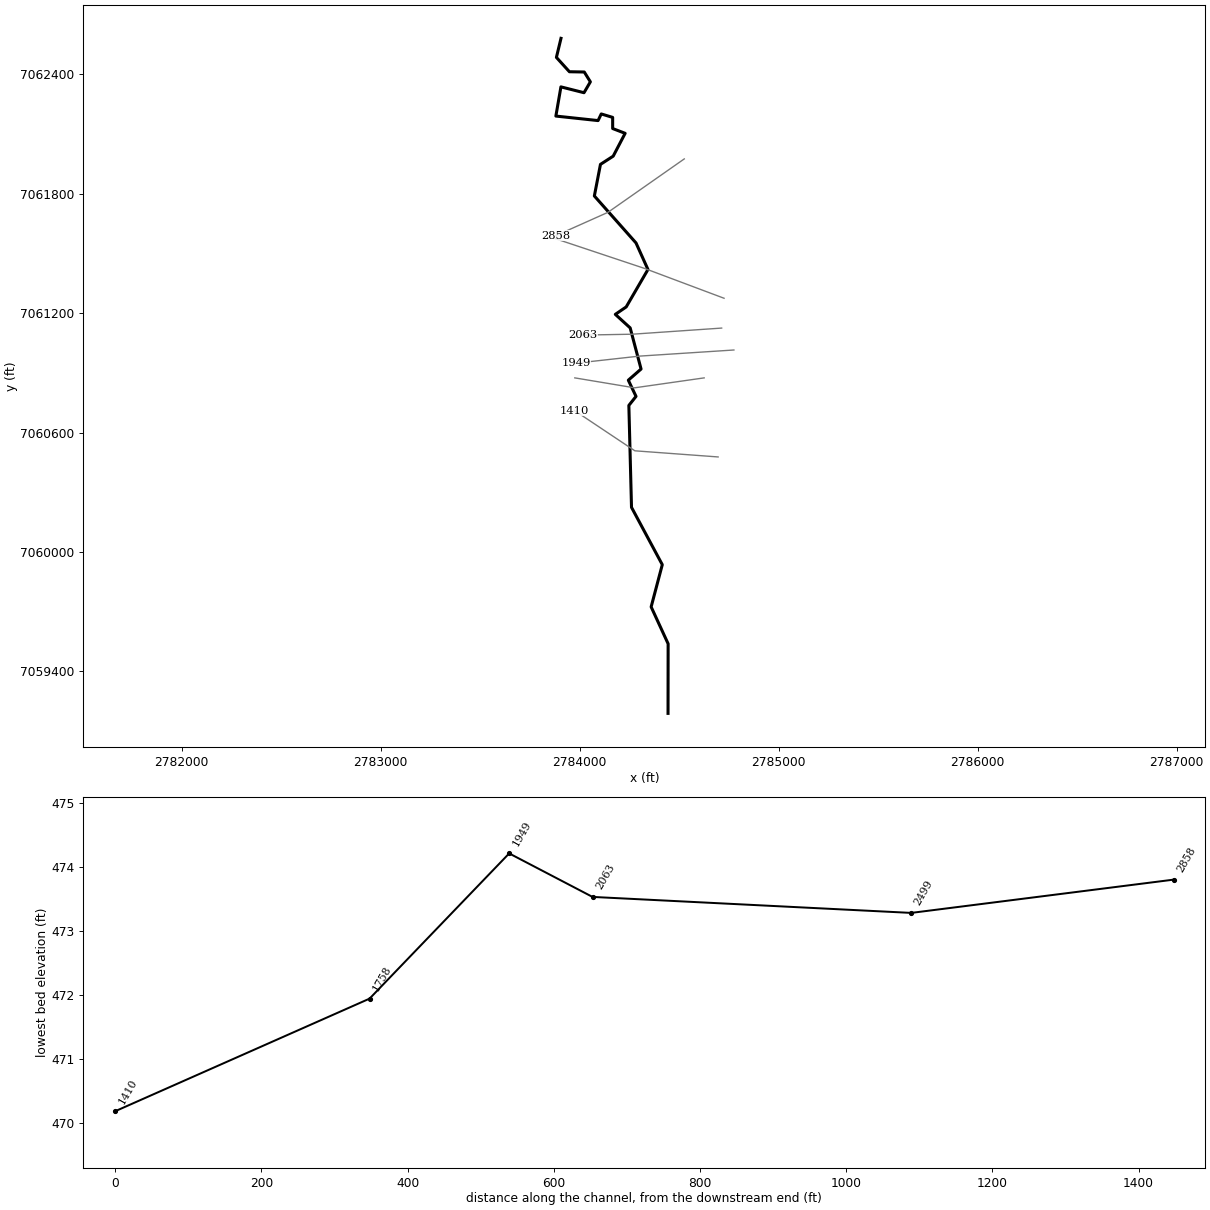
--- UNT 036 in LFCCL Watershed.prj (project) ---

Proj Title=UNT 036 in LFCCL Watershed Base Level Engineering
Current Plan=p01
Default Exp/Contr=0.3,0.1
English Units
Geom File=g01
Flow File=f01
Plan File=p01
BEGIN DESCRIPTION:
UNT 036 in LFCCL Watershed
END DESCRIPTION:

--- UNT 036 in LFCCL Watershed.p01 (plan) ---

Plan Title=Multiple Run
Short Identifier=Multiple
Geom File=g01
Flow File=f01
Subcritical Flow
K Sum by GR= 0
Std Step Tol= 0.01
Critical Tol= 0.01
Num of Std Step Trials= 20
Max Error Tol= 0.3
Flow Tol Ratio= 0.001
Split Flow NTrial= 30
Split Flow Tol= 0.02
Split Flow Ratio= 0.02
Log Output Level= 0
Friction Slope Method= 1
Unsteady Friction Slope Method= 2
Unsteady Bridges Friction Slope Method= 1
Parabolic Critical Depth
Global Vel Dist=  1 , 1 , 1
Global Log Level= 0
CheckData=True
Encroach Param= -1, 0, 0, 0
BEGIN DESCRIPTION:
Multiple Run
END DESCRIPTION:

--- UNT 036 in LFCCL Watershed.f01 (steady flow) ---

Flow Title=Multiple
Number of Profiles=7
Profile Names=10-year,25-year,50-year,1pct_min,100-year,1pct_plu,500-year
River Rch & RM= UNT 036 in LFCCL,Reach-1,2858
     540     708     840     494     986    1967    1356
Boundary for River Rch & Prof#=UNT 036 in LFCCL,Reach-1,1
Up Type=0
Dn Type=3
Dn Slope=0.005
Boundary for River Rch & Prof#=UNT 036 in LFCCL,Reach-1,2
Up Type=0
Dn Type=3
Dn Slope=0.005
Boundary for River Rch & Prof#=UNT 036 in LFCCL,Reach-1,3
Up Type=0
Dn Type=3
Dn Slope=0.005
Boundary for River Rch & Prof#=UNT 036 in LFCCL,Reach-1,4
Up Type=0
Dn Type=3
Dn Slope=0.005
Boundary for River Rch & Prof#=UNT 036 in LFCCL,Reach-1,5
Up Type=0
Dn Type=3
Dn Slope=0.005
Boundary for River Rch & Prof#=UNT 036 in LFCCL,Reach-1,6
Up Type=0
Dn Type=3
Dn Slope=0.005
Boundary for River Rch & Prof#=UNT 036 in LFCCL,Reach-1,7
Up Type=0
Dn Type=3
Dn Slope=0.005

--- UNT 036 in LFCCL Watershed.g01 (geometry) ---

Geom Title=Existing Conditions

River Reach=UNT 036 in LFCCL,Reach-1
Reach XY= 30
      2783905.59      7062580.71      2783882.56      7062484.91
      2783947.90      7062412.90      2784022.58      7062411.57
      2784053.25      7062362.23      2784021.24      7062307.55
      2783905.23      7062336.89      2783879.89      7062190.21
      2784091.92      7062167.54      2784107.92      7062200.88
      2784165.26      7062183.54      2784165.26      7062127.53
      2784227.93      7062103.53      2784167.93      7061988.85
      2784103.92      7061947.51      2784073.25      7061788.83
      2784282.61      7061552.80      2784342.61      7061419.45
      2784233.27      7061231.43      2784178.59      7061194.09
      2784253.27      7061126.08      2784307.94      7060919.39
      2784243.94      7060863.38      2784282.61      7060782.04
      2784246.60      7060736.70      2784259.94      7060224.64
      2784414.62      7059936.61      2784358.62      7059724.58
      2784443.96      7059539.23      2784443.48      7059189.60

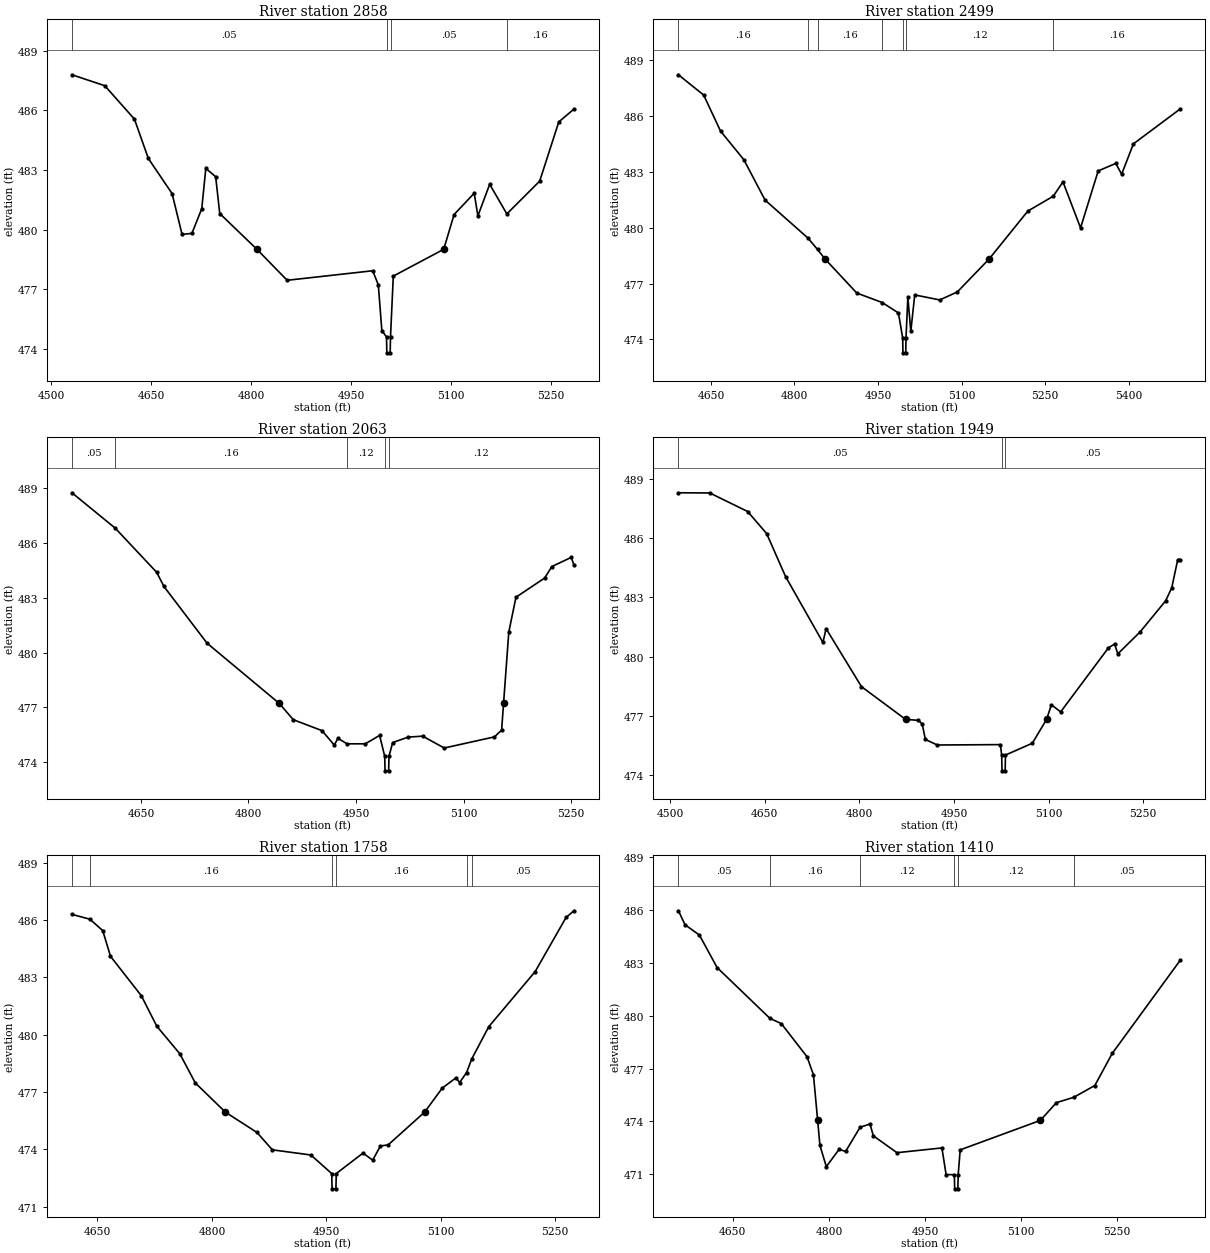
Type RM Length L Ch R = 1,2858,359,359,359
BEGIN DESCRIPTION:
UNT 036 in LFCCL Watershed 5.0
END DESCRIPTION:
XS GIS Cut Line= 3
      2784525.03      7061975.02      2784141.33      7061706.48
      2783880.86      7061590.14
#Sta/Elev= 30
  4531.0  487.79  4580.3  487.24  4624.8  485.56  4645.7  483.58  4681.4  481.81
  4696.3  479.76  4711.1  479.81  4725.9  481.05  4732.0  483.08  4746.8  482.66
  4752.9  480.81  4808.7  479.01  4854.1  477.45  4982.6  477.93  4991.0  477.22
  4996.3  474.92  5003.3  474.60  5003.8  473.80  5008.8  473.80  5009.3  474.60
  5013.5  477.66  5089.2  479.01  5104.8  480.76  5135.0  481.83  5140.5  480.69
  5158.2  482.28  5184.0  480.79  5233.3  482.44  5262.0  485.42  5284.6  486.06
#Mann=4,-1,0
  4531.0    0.05       0  5003.3    0.04       0  5009.3    0.05       0
  5184.0    0.16       0
Bank Sta=4808.7,5089.2
Exp/Cntr=0.3,0.1

Type RM Length L Ch R = 1,2499,436,436,436
BEGIN DESCRIPTION:
UNT 036 in LFCCL Watershed 4.0
END DESCRIPTION:
XS GIS Cut Line= 3
      2784725.00      7061275.00      2784325.00      7061425.00
      2783875.04      7061574.99
#Sta/Elev= 30
  4591.5  488.21  4636.9  487.12  4667.1  485.19  4709.0  483.65  4747.2  481.48
  4823.9  479.45  4841.4  478.83  4854.5  478.33  4911.9  476.49  4957.7  475.98
  4986.7  475.42  4994.3  474.08  4994.8  473.28  4999.8  473.28  5000.3  474.08
  5003.6  476.26  5008.9  474.44  5016.0  476.39  5060.9  476.12  5092.5  476.55
  5149.9  478.33  5219.0  480.89  5264.8  481.69  5282.2  482.46  5313.8  479.99
  5345.5  483.05  5377.1  483.45  5387.6  482.87  5408.7  484.50  5493.0  486.38
#Mann=7,-1,0
  4591.5    0.16       0  4823.9    0.12       0  4841.4    0.16       0
  4957.7    0.12       0  4994.3    0.07       0  5000.3    0.12       0
  5264.8    0.16       0
Bank Sta=4854.5,5149.9
Exp/Cntr=0.3,0.1

Type RM Length L Ch R = 1,2063,114,114,114
BEGIN DESCRIPTION:
XS3191A
END DESCRIPTION:
XS GIS Cut Line= 3
      2784712.92      7061125.18      2784263.68      7061094.35
      2784014.32      7061089.97
#Sta/Elev= 30
  4553.9  488.76  4614.3  486.82  4672.1  484.40  4682.1  483.63  4742.3  480.52
  4843.0  477.22  4862.5  476.33  4902.6  475.73  4919.6  474.94  4924.7  475.31
  4937.4  475.01  4962.8  475.01  4982.8  475.47  4989.9  474.33  4990.4  473.53
  4995.4  473.53  4995.9  474.33  5001.0  475.08  5022.9  475.38  5042.9  475.43
  5072.9  474.78  5142.9  475.39  5152.9  475.76  5155.6  477.22  5162.9  481.13
  5172.9  483.04  5212.9  484.09  5222.9  484.72  5249.9  485.22  5253.6  484.82
#Mann=5,-1,0
  4553.9    0.05       0  4614.3    0.16       0  4937.4    0.12       0
  4989.9    0.07       0  4995.9    0.12       0
Bank Sta=4843,5155.6
Exp/Cntr=0.3,0.1

Type RM Length L Ch R = 1,1949,191,191,191
BEGIN DESCRIPTION:
XS3192A
END DESCRIPTION:
XS GIS Cut Line= 3
      2784774.57      7061015.07      2784298.92      7060984.24
      2783981.82      7060949.01
#Sta/Elev= 30
  4513.0  488.31  4562.7  488.30  4622.8  487.36  4652.9  486.24  4682.9  484.06
  4742.1  480.72  4747.1  481.42  4803.2  478.48  4873.1  476.82  4893.4  476.77
  4899.5  476.59  4904.5  475.80  4923.4  475.52  5023.4  475.54  5025.5  475.01
  5026.0  474.21  5031.0  474.21  5031.5  475.01  5074.1  475.61  5096.7  476.82
  5104.3  477.56  5119.0  477.20  5194.8  480.45  5204.5  480.64  5209.6  480.14
  5245.1  481.26  5285.4  482.83  5295.1  483.49  5304.6  484.92  5308.7  484.92
#Mann=3,-1,0
  4513.0    0.05       0  5025.5    0.04       0  5031.5    0.05       0
Bank Sta=4873.1,5096.7
Exp/Cntr=0.3,0.1

Type RM Length L Ch R = 1,1758,348,348,348
BEGIN DESCRIPTION:
UNT 036 in LFCCL Watershed 3.0
END DESCRIPTION:
XS GIS Cut Line= 3
      2784624.98      7060875.00      2784275.00      7060825.00
      2783974.97      7060875.01
#Sta/Elev= 30
  4616.6  486.29  4640.1  486.04  4657.0  485.44  4667.1  484.10  4707.5  482.04
  4727.7  480.45  4758.0  479.00  4778.2  477.48  4817.7  475.95  4859.0  474.89
  4879.2  473.98  4929.7  473.71  4957.0  472.74  4957.5  471.94  4962.5  471.94
  4963.0  472.74  4998.0  473.81  5010.7  473.44  5020.8  474.18  5031.0  474.24
  5078.7  475.95  5101.9  477.21  5119.7  477.74  5124.7  477.50  5133.7  478.02
  5140.6  478.74  5162.8  480.42  5223.6  483.30  5264.1  486.13  5274.3  486.48
#Mann=6,-1,0
  4616.6    0.05       0  4640.1    0.16       0  4957.0    0.07       0
  4963.0    0.16       0  5133.7    0.07       0  5140.6    0.05       0
Bank Sta=4817.7,5078.7
Exp/Cntr=0.3,0.1

Type RM Length L Ch R = 1,1410,0,0,0
BEGIN DESCRIPTION:
XS3193A
END DESCRIPTION:
XS GIS Cut Line= 3
      2784695.26      7060477.78      2784276.90      7060508.61
      2783973.94      7060710.58
#Sta/Elev= 30
  4565.0  485.95  4575.3  485.16  4597.8  484.57  4625.4  482.73  4707.8  479.85
  4725.7  479.55  4765.8  477.67  4775.8  476.65  4782.4  474.06  4785.9  472.65
  4795.9  471.44  4815.9  472.42  4826.0  472.30  4848.6  473.67  4864.2  473.86
  4869.2  473.19  4906.2  472.23  4976.4  472.50  4982.9  470.99  4995.8  470.98
  4996.3  470.18  5001.3  470.18  5001.8  470.98  5004.9  472.39  5130.0  474.06
  5155.2  475.07  5182.2  475.37  5215.1  476.04  5242.3  477.86  5348.6  483.15
#Mann=6,-1,0
  4565.0    0.05       0  4707.8    0.16       0  4848.6    0.12       0
  4995.8    0.07       0  5001.8    0.12       0  5182.2    0.05       0
Bank Sta=4782.4,5130
Exp/Cntr=0.3,0.1

Chan Stop Cuts=-1