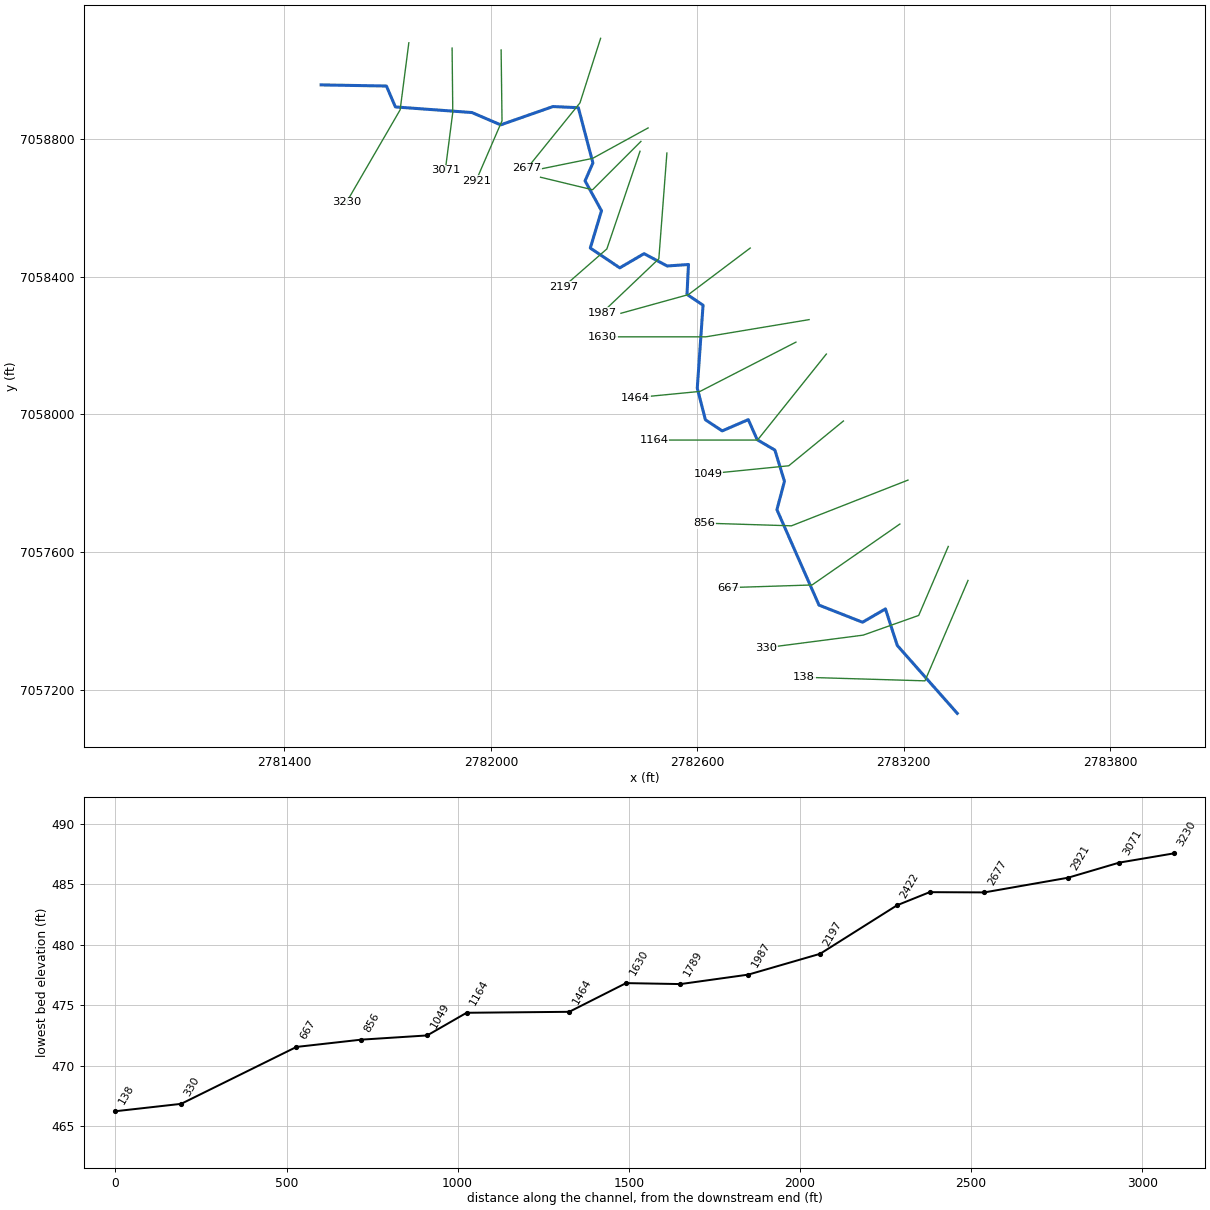
--- UNT 038 in LFCCL Watershed.prj (project) ---

Proj Title=UNT 038 in LFCCL Watershed Base Level Engineering
Current Plan=p01
Default Exp/Contr=0.3,0.1
English Units
Geom File=g01
Flow File=f01
Plan File=p01
BEGIN DESCRIPTION:
UNT 038 in LFCCL Watershed
END DESCRIPTION:

--- UNT 038 in LFCCL Watershed.p01 (plan) ---

Plan Title=Multiple Run
Short Identifier=Multiple
Geom File=g01
Flow File=f01
Subcritical Flow
K Sum by GR= 0
Std Step Tol= 0.01
Critical Tol= 0.01
Num of Std Step Trials= 20
Max Error Tol= 0.3
Flow Tol Ratio= 0.001
Split Flow NTrial= 30
Split Flow Tol= 0.02
Split Flow Ratio= 0.02
Log Output Level= 0
Friction Slope Method= 1
Unsteady Friction Slope Method= 2
Unsteady Bridges Friction Slope Method= 1
Parabolic Critical Depth
Global Vel Dist=  1 , 1 , 1
Global Log Level= 0
CheckData=True
Encroach Param= -1, 0, 0, 0
BEGIN DESCRIPTION:
Multiple Run
END DESCRIPTION:

--- UNT 038 in LFCCL Watershed.f01 (steady flow) ---

Flow Title=Multiple
Number of Profiles=7
Profile Names=10-year,25-year,50-year,1pct_min,100-year,1pct_plu,500-year
River Rch & RM= UNT 038 in LFCCL,Reach-1,3230
     172     209     237     134     267     532     335
Boundary for River Rch & Prof#=UNT 038 in LFCCL,Reach-1,1
Up Type=0
Dn Type=3
Dn Slope=0.005
Boundary for River Rch & Prof#=UNT 038 in LFCCL,Reach-1,2
Up Type=0
Dn Type=3
Dn Slope=0.005
Boundary for River Rch & Prof#=UNT 038 in LFCCL,Reach-1,3
Up Type=0
Dn Type=3
Dn Slope=0.005
Boundary for River Rch & Prof#=UNT 038 in LFCCL,Reach-1,4
Up Type=0
Dn Type=3
Dn Slope=0.005
Boundary for River Rch & Prof#=UNT 038 in LFCCL,Reach-1,5
Up Type=0
Dn Type=3
Dn Slope=0.005
Boundary for River Rch & Prof#=UNT 038 in LFCCL,Reach-1,6
Up Type=0
Dn Type=3
Dn Slope=0.005
Boundary for River Rch & Prof#=UNT 038 in LFCCL,Reach-1,7
Up Type=0
Dn Type=3
Dn Slope=0.005

--- UNT 038 in LFCCL Watershed.g01 (geometry) ---

Geom Title=Existing Conditions

River Reach=UNT 038 in LFCCL,Reach-1
Reach XY= 30
      2781506.68      7058957.12      2781696.56      7058953.86
      2781722.60      7058893.10      2781945.04      7058876.82
      2782028.59      7058841.02      2782180.50      7058894.18
      2782254.29      7058890.93      2782296.61      7058730.34
      2782273.82      7058678.26      2782321.56      7058591.45
      2782289.01      7058482.94      2782374.73      7058425.43
      2782445.26      7058466.67      2782512.53      7058430.86
      2782574.38      7058435.20      2782570.04      7058348.39
      2782616.70      7058316.93      2782599.92      7058075.82
      2782623.57      7057984.00      2782672.37      7057951.63
      2782748.22      7057984.38      2782774.01      7057926.09
      2782825.48      7057895.80      2782853.29      7057805.16
      2782831.37      7057722.71      2782953.66      7057445.35
      2783080.16      7057395.56      2783146.76      7057434.23
      2783181.21      7057328.06      2783355.59      7057130.71

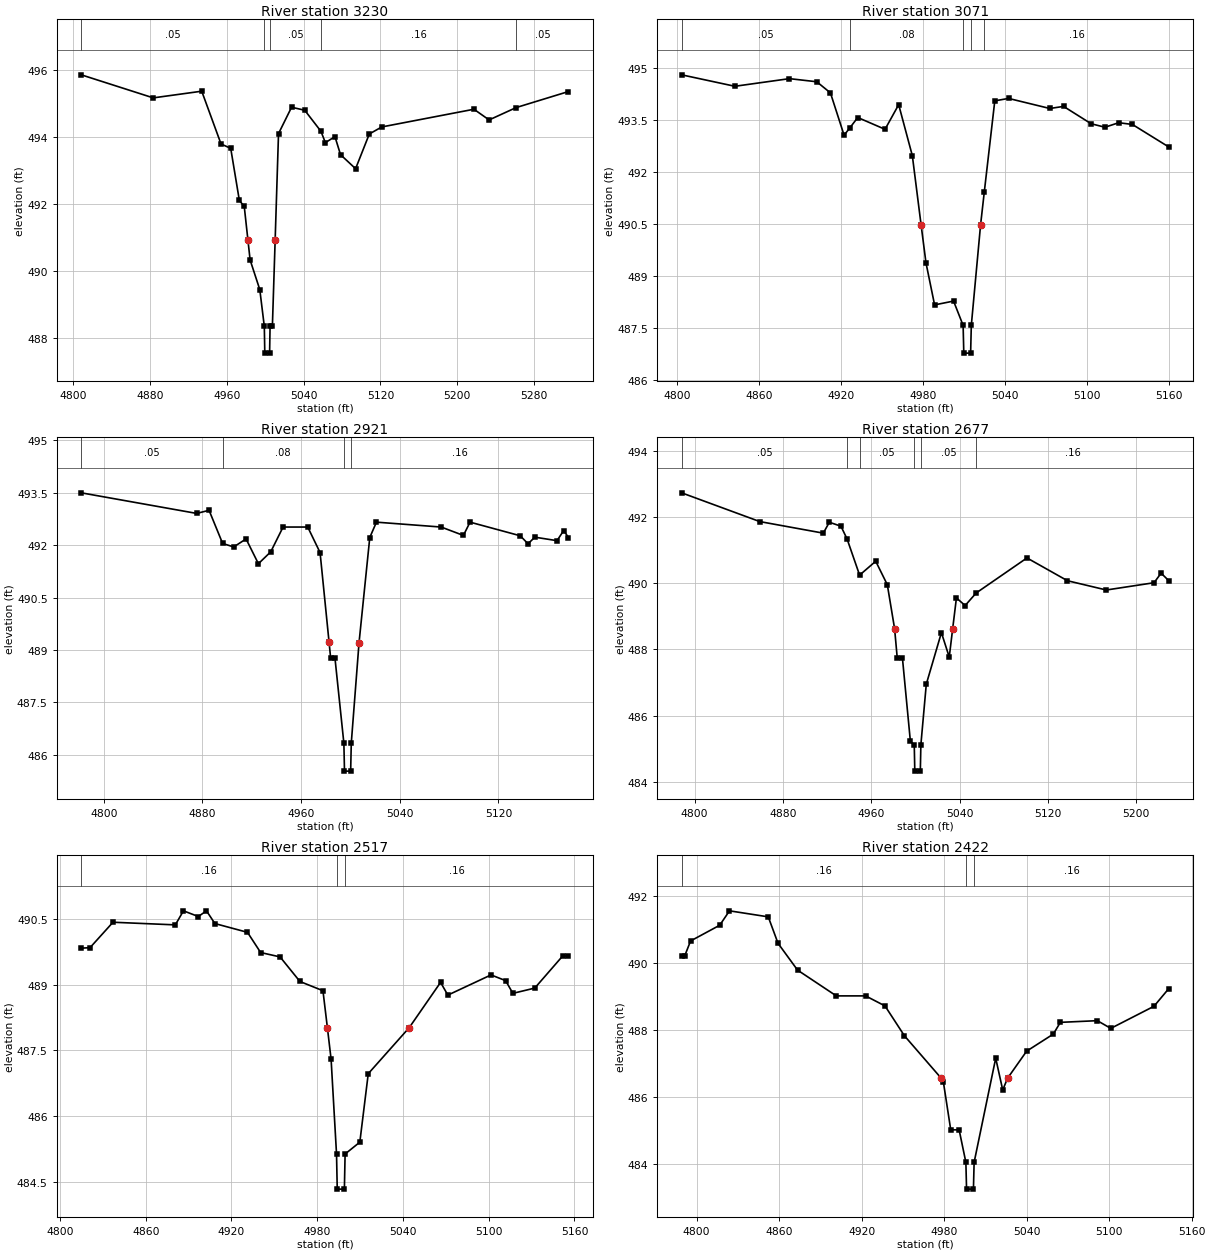
Type RM Length L Ch R = 1,3230,159,159,159
BEGIN DESCRIPTION:
UNT 038 in LFCCL Watershed 4.0
END DESCRIPTION:
XS GIS Cut Line= 3
      2781761.66      7059079.41      2781736.44      7058884.65
      2781580.17      7058615.52
#Sta/Elev= 30
  4808.3  495.87  4883.3  495.18  4933.8  495.38  4953.9  493.80  4964.0  493.67
  4973.0  492.11  4978.1  491.93  4981.9  490.93  4984.2  490.33  4994.3  489.44
  4999.0  488.34  4999.5  487.54  5004.5  487.54  5005.0  488.34  5007.4  488.34
  5010.3  490.93  5013.8  494.11  5027.4  494.90  5041.1  494.81  5058.0  494.18
  5062.6  493.84  5072.6  494.02  5078.4  493.48  5094.1  493.06  5108.4  494.10
  5121.4  494.31  5217.4  494.84  5233.2  494.52  5261.4  494.89  5315.9  495.37
#Mann=5,-1,0
  4808.3    0.05       0  4999.0    0.04       0  5005.0    0.05       0
  5058.0    0.16       0  5261.4    0.05       0
Bank Sta=4981.9,5010.3
Exp/Cntr=0.3,0.1

Type RM Length L Ch R = 1,3071,150,150,150
BEGIN DESCRIPTION:
Mapping XS 30228122
END DESCRIPTION:
XS GIS Cut Line= 3
      2781887.42      7059064.04      2781889.43      7058877.57
      2781867.55      7058708.56
#Sta/Elev= 30
  4803.1  494.80  4842.1  494.47  4882.1  494.69  4902.1  494.60  4912.1  494.28
  4922.1  493.06  4926.5  493.28  4932.1  493.57  4952.1  493.23  4962.1  493.94
  4972.1  492.47  4978.5  490.48  4982.1  489.38  4988.4  488.17  5002.3  488.28
  5009.3  487.58  5009.8  486.78  5014.8  486.78  5015.3  487.58  5022.1  490.48
  5024.8  491.42  5032.5  494.05  5042.6  494.12  5072.8  493.83  5082.9  493.89
  5103.1  493.39  5113.2  493.29  5123.3  493.42  5133.3  493.37  5160.0  492.72
#Mann=5,-1,0
  4803.1    0.05       0  4926.5    0.08       0  5009.3    0.07       0
  5015.3    0.08       0  5024.8    0.16       0
Bank Sta=4978.5,5022.1
Exp/Cntr=0.3,0.1

Type RM Length L Ch R = 1,2921,244,244,244
BEGIN DESCRIPTION:
XS3194A
END DESCRIPTION:
XS GIS Cut Line= 3
      2782029.89      7059058.56      2782032.49      7058852.86
      2781957.31      7058679.15
#Sta/Elev= 30
  4781.8  493.50  4875.4  492.91  4885.4  493.00  4896.4  492.05  4905.4  491.95
  4915.4  492.18  4925.4  491.47  4935.4  491.81  4945.4  492.52  4965.4  492.52
  4975.4  491.79  4982.7  489.22  4984.0  488.76  4987.5  488.76  4994.7  486.33
  4995.2  485.53  5000.2  485.53  5000.7  486.33  5007.0  489.21  5015.7  492.22
  5021.1  492.66  5073.6  492.52  5091.6  492.28  5097.0  492.66  5137.7  492.27
  5144.0  492.04  5149.5  492.23  5167.5  492.13  5172.9  492.42  5176.8  492.22
#Mann=4,-1,0
  4781.8    0.05       0  4896.4    0.08       0  4994.7    0.07       0
  5000.7    0.16       0
Bank Sta=4982.7,5007
Exp/Cntr=0.3,0.1

Type RM Length L Ch R = 1,2677,160,160,160
BEGIN DESCRIPTION:
XS3195A
END DESCRIPTION:
XS GIS Cut Line= 3
      2782318.95      7059092.45      2782259.05      7058904.94
      2782105.40      7058714.82
#Sta/Elev= 30
  4788.3  492.74  4859.1  491.87  4916.6  491.52  4922.1  491.85  4932.6  491.73
  4938.2  491.34  4949.5  490.25  4964.1  490.67  4974.6  489.96  4981.2  488.63
  4983.6  487.74  4988.3  487.74  4995.5  485.22  4999.0  485.12  4999.5  484.32
  5004.5  484.32  5005.0  485.12  5009.9  486.95  5023.6  488.51  5030.7  487.77
  5033.8  488.63  5037.2  489.56  5045.1  489.33  5055.1  489.71  5101.1  490.77
  5137.8  490.08  5173.0  489.80  5216.2  490.02  5222.6  490.31  5229.6  490.08
#Mann=6,-1,0
  4788.3    0.05       0  4938.2    0.08       0  4949.5    0.05       0
  4999.0    0.04       0  5005.0    0.05       0  5055.1    0.16       0
Bank Sta=4981.2,5033.8
Exp/Cntr=0.3,0.1

Type RM Length L Ch R = 1,2517,95,95,95
BEGIN DESCRIPTION:
XS3196A
END DESCRIPTION:
XS GIS Cut Line= 3
      2782456.96      7058832.02      2782295.51      7058743.48
      2782141.89      7058712.23
#Sta/Elev= 30
  4814.9  489.83  4821.0  489.84  4837.1  490.42  4880.7  490.36  4886.4  490.68
  4896.8  490.55  4902.5  490.68  4908.4  490.39  4931.2  490.19  4940.4  489.73
  4954.0  489.63  4967.9  489.07  4984.0  488.86  4987.1  488.02  4989.7  487.30
  4993.5  485.14  4994.0  484.34  4999.0  484.34  4999.5  485.14  5009.8  485.41
  5015.7  486.97  5044.4  488.02  5066.3  489.05  5071.4  488.76  5101.6  489.22
  5111.8  489.09  5116.9  488.80  5132.2  488.92  5151.7  489.65  5155.8  489.65
#Mann=3,-1,0
  4814.9    0.16       0  4993.5    0.07       0  4999.5    0.16       0
Bank Sta=4987.1,5044.4
Exp/Cntr=0.3,0.1

Type RM Length L Ch R = 1,2422,225,225,225
BEGIN DESCRIPTION:
XS3200A
END DESCRIPTION:
XS GIS Cut Line= 3
      2782436.17      7058792.99      2782295.51      7058652.33
      2782144.47      7058688.79
#Sta/Elev= 30
  4789.1  490.21  4791.2  490.21  4795.6  490.67  4816.8  491.14  4823.9  491.57
  4852.1  491.39  4859.2  490.60  4873.4  489.80  4901.6  489.03  4922.9  489.03
  4937.0  488.73  4951.1  487.84  4977.9  486.57  4979.4  486.47  4984.8  485.03
  4990.9  485.03  4995.8  484.06  4996.3  483.26  5001.3  483.26  5001.8  484.06
  5017.5  487.17  5022.6  486.22  5026.1  486.57  5040.0  487.38  5059.4  487.89
  5064.5  488.24  5091.4  488.29  5101.2  488.06  5132.6  488.72  5143.4  489.25
#Mann=3,-1,0
  4789.1    0.16       0  4995.8    0.07       0  5001.8    0.16       0
Bank Sta=4977.9,5026.1
Exp/Cntr=0.3,0.1

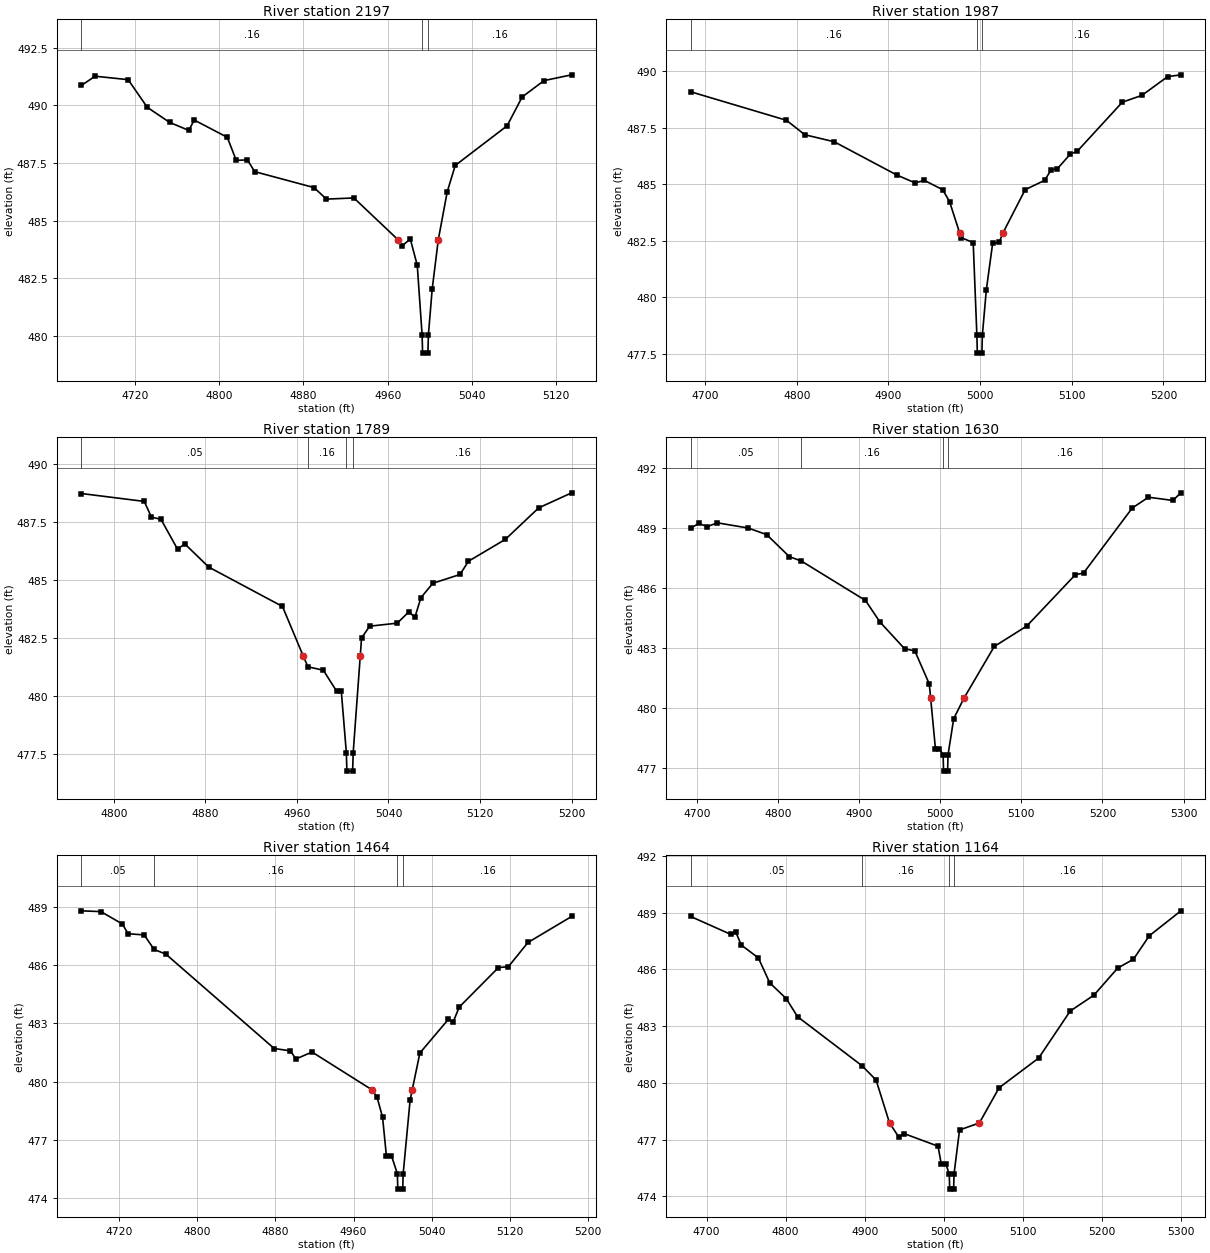
Type RM Length L Ch R = 1,2197,210,210,210
BEGIN DESCRIPTION:
XS3197A
END DESCRIPTION:
XS GIS Cut Line= 3
      2782433.53      7058764.30      2782337.18      7058480.46
      2782212.21      7058371.12
#Sta/Elev= 30
  4669.0  490.86  4682.0  491.26  4713.4  491.11  4731.6  489.91  4752.7  489.26
  4771.0  488.91  4776.2  489.36  4807.6  488.61  4816.1  487.61  4826.7  487.63
  4833.7  487.12  4890.0  486.43  4901.8  485.93  4927.9  485.98  4969.8  484.17
  4973.9  483.91  4981.5  484.20  4988.1  483.06  4992.7  480.05  4993.2  479.25
  4998.2  479.25  4998.7  480.05  5002.3  482.03  5008.1  484.17  5016.6  486.25
  5024.2  487.39  5073.5  489.11  5087.8  490.36  5108.6  491.07  5134.8  491.32
#Mann=3,-1,0
  4669.0    0.16       0  4992.7    0.07       0  4998.7    0.16       0
Bank Sta=4969.8,5008.1
Exp/Cntr=0.3,0.1

Type RM Length L Ch R = 1,1987,198,198,198
BEGIN DESCRIPTION:
XS3198A
END DESCRIPTION:
XS GIS Cut Line= 3
      2782511.66      7058759.13      2782488.22      7058451.81
      2782324.14      7058295.55
#Sta/Elev= 30
  4684.3  489.09  4788.7  487.83  4808.8  487.19  4840.8  486.88  4909.1  485.41
  4929.1  485.06  4939.2  485.17  4959.2  484.76  4966.7  484.23  4977.7  482.85
  4979.3  482.64  4992.5  482.42  4996.5  478.33  4997.0  477.53  5002.0  477.53
  5002.5  478.33  5006.8  480.32  5013.7  482.38  5020.9  482.44  5025.0  482.85
  5049.2  484.76  5070.3  485.17  5077.5  485.63  5084.4  485.69  5098.6  486.34
  5105.8  486.45  5155.2  488.63  5176.5  488.93  5204.6  489.76  5219.1  489.84
#Mann=3,-1,0
  4684.3    0.16       0  4996.5    0.07       0  5002.5    0.16       0
Bank Sta=4977.7,5025
Exp/Cntr=0.3,0.1

Type RM Length L Ch R = 1,1789,159,159,159
BEGIN DESCRIPTION:
XS3199A
END DESCRIPTION:
XS GIS Cut Line= 3
      2782753.82      7058483.05      2782574.16      7058347.65
      2782378.08      7058293.47
#Sta/Elev= 30
  4771.7  488.72  4826.6  488.38  4832.9  487.70  4841.2  487.61  4855.7  486.32
  4862.0  486.55  4882.9  485.55  4947.4  483.85  4965.4  481.73  4969.6  481.25
  4983.1  481.10  4994.7  480.20  4998.8  480.20  5003.2  477.55  5003.7  476.75
  5008.7  476.75  5009.2  477.55  5015.4  481.73  5016.5  482.49  5023.6  483.00
  5047.7  483.13  5057.9  483.62  5063.1  483.38  5068.4  484.23  5078.8  484.85
  5102.6  485.23  5109.9  485.80  5142.1  486.74  5171.3  488.10  5200.1  488.75
#Mann=4,-1,0
  4771.7    0.05       0  4969.6    0.16       0  5003.2    0.07       0
  5009.2    0.16       0
Bank Sta=4965.4,5015.4
Exp/Cntr=0.3,0.1

Type RM Length L Ch R = 1,1630,166,166,166
BEGIN DESCRIPTION:
UNT 038 in LFCCL Watershed 3.0
END DESCRIPTION:
XS GIS Cut Line= 3
      2782924.95      7058274.99      2782625.00      7058225.00
      2782324.99      7058225.00
#Sta/Elev= 30
  4692.6  488.98  4702.7  489.21  4712.8  489.05  4725.5  489.24  4763.5  488.98
  4786.3  488.65  4814.2  487.55  4829.0  487.33  4908.0  485.36  4925.7  484.29
  4956.1  482.95  4968.8  482.84  4986.6  481.19  4988.3  480.48  4994.2  477.95
  4999.2  477.95  5003.7  477.63  5004.2  476.83  5009.2  476.83  5009.7  477.63
  5016.7  479.45  5029.4  480.48  5066.7  483.06  5106.7  484.08  5166.7  486.65
  5176.7  486.73  5236.7  489.98  5256.7  490.52  5286.7  490.36  5296.7  490.74
#Mann=4,-1,0
  4692.6    0.05       0  4829.0    0.16       0  5003.7    0.07       0
  5009.7    0.16       0
Bank Sta=4988.3,5029.4
Exp/Cntr=0.3,0.1

Type RM Length L Ch R = 1,1464,300,300,300
BEGIN DESCRIPTION:
XS3201A
END DESCRIPTION:
XS GIS Cut Line= 3
      2782886.63      7058209.61      2782608.01      7058066.40
      2782420.46      7058048.16
#Sta/Elev= 30
  4681.5  488.79  4701.4  488.75  4723.5  488.11  4729.2  487.61  4745.7  487.55
  4755.9  486.80  4767.9  486.56  4878.8  481.70  4895.4  481.58  4901.0  481.16
  4917.5  481.52  4979.3  479.56  4984.1  479.19  4989.7  478.16  4993.6  476.18
  4998.8  476.18  5004.8  475.26  5005.3  474.46  5010.3  474.46  5010.8  475.26
  5017.9  479.05  5020.0  479.56  5027.9  481.47  5057.0  483.20  5062.0  483.07
  5068.1  483.83  5108.3  485.87  5118.4  485.91  5138.5  487.16  5183.2  488.50
#Mann=4,-1,0
  4681.5    0.05       0  4755.9    0.16       0  5004.8    0.07       0
  5010.8    0.16       0
Bank Sta=4979.3,5020
Exp/Cntr=0.3,0.1

Type RM Length L Ch R = 1,1164,115,115,115
BEGIN DESCRIPTION:
UNT 038 in LFCCL Watershed 2.0
END DESCRIPTION:
XS GIS Cut Line= 3
      2782974.98      7058174.97      2782775.00      7057925.00
      2782475.02      7057925.00
#Sta/Elev= 30
  4679.9  488.80  4730.3  487.86  4736.7  488.00  4743.9  487.29  4765.5  486.61
  4779.9  485.29  4800.7  484.46  4815.1  483.50  4896.8  480.90  4914.4  480.15
  4931.4  477.88  4943.2  477.13  4949.6  477.32  4992.8  476.65  4996.8  475.72
  5002.5  475.72  5007.0  475.18  5007.5  474.38  5012.5  474.38  5013.0  475.18
  5020.0  477.51  5045.1  477.88  5070.0  479.74  5120.0  481.31  5160.0  483.80
  5190.0  484.64  5220.0  486.07  5240.0  486.54  5260.0  487.78  5300.0  489.10
#Mann=4,-1,0
  4679.9    0.05       0  4896.8    0.16       0  5007.0    0.07       0
  5013.0    0.16       0
Bank Sta=4931.4,5045.1
Exp/Cntr=0.3,0.1

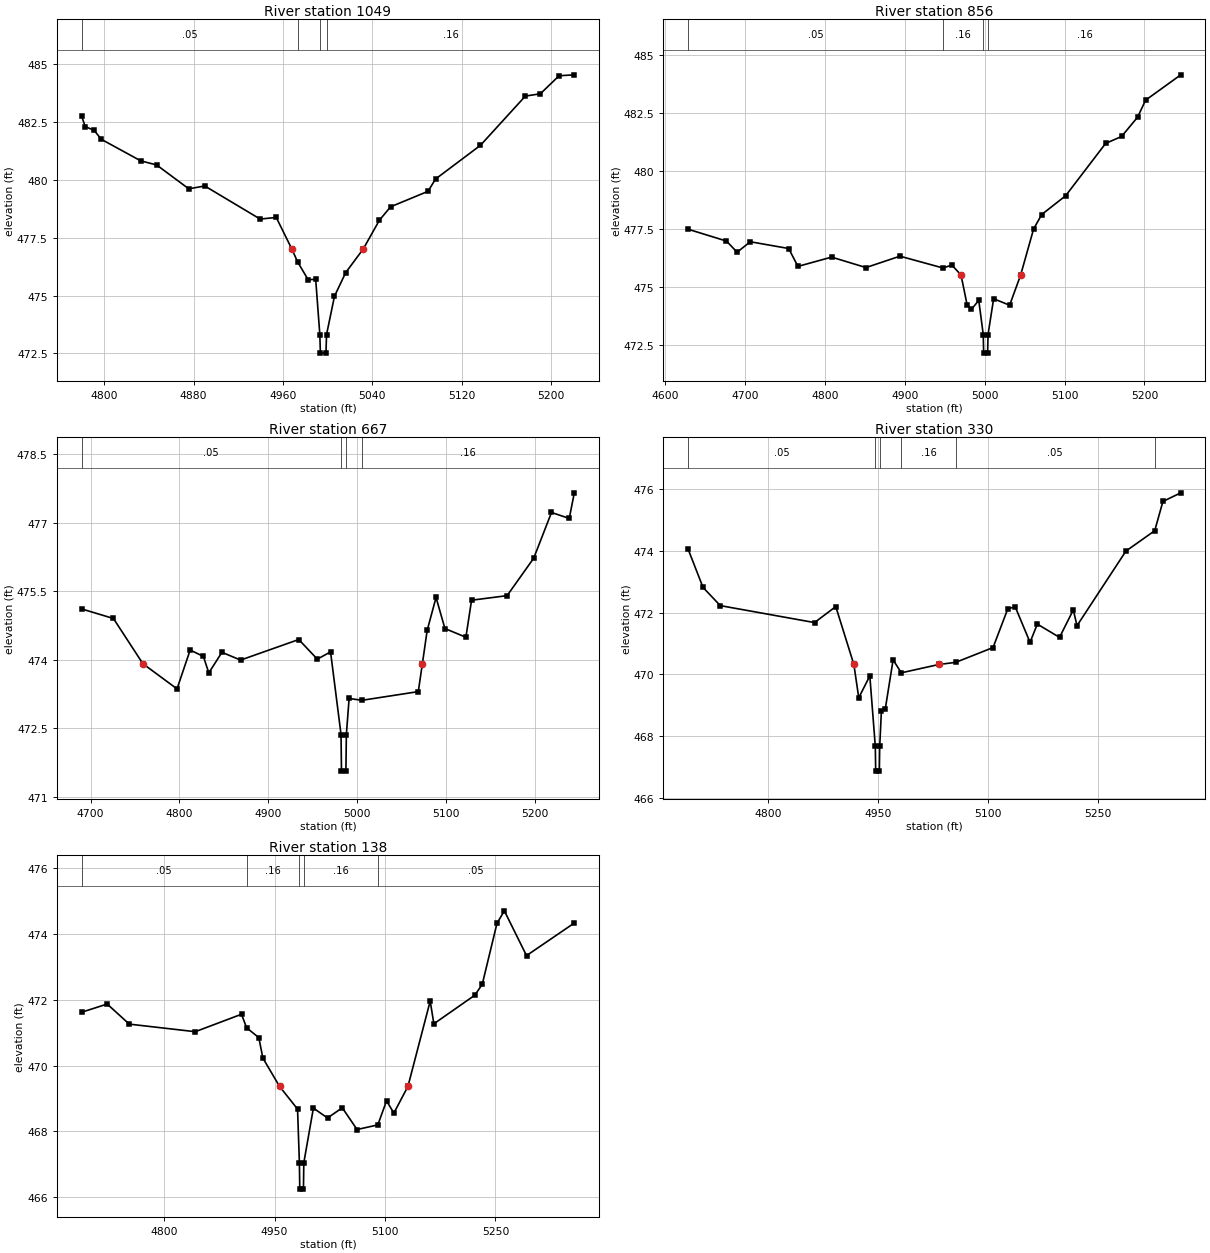
Type RM Length L Ch R = 1,1049,193,193,193
BEGIN DESCRIPTION:
XS3205A
END DESCRIPTION:
XS GIS Cut Line= 3
      2783024.65      7057980.43      2782865.82      7057850.25
      2782631.45      7057826.81
#Sta/Elev= 30
  4779.8  482.77  4783.1  482.31  4791.0  482.15  4797.5  481.76  4832.7  480.83
  4847.0  480.65  4875.7  479.62  4890.1  479.74  4939.6  478.31  4954.0  478.38
  4967.9  477.02  4973.1  476.46  4982.5  475.69  4989.3  475.70  4993.0  473.31
  4993.5  472.51  4998.5  472.51  4999.0  473.31  5006.1  474.97  5016.1  475.99
  5031.9  477.02  5046.3  478.26  5056.3  478.84  5089.8  479.51  5096.5  480.04
  5136.7  481.50  5176.9  483.63  5190.3  483.73  5207.1  484.51  5220.7  484.55
#Mann=4,-1,0
  4779.8    0.05       0  4973.1    0.16       0  4993.0    0.07       0
  4999.0    0.16       0
Bank Sta=4967.9,5031.9
Exp/Cntr=0.3,0.1

Type RM Length L Ch R = 1,856,189,189,189
BEGIN DESCRIPTION:
XS3202A
END DESCRIPTION:
XS GIS Cut Line= 3
      2783212.19      7057808.59      2782873.64      7057675.77
      2782621.03      7057683.58
#Sta/Elev= 30
  4629.0  477.49  4677.1  476.98  4690.4  476.50  4706.9  476.95  4754.9  476.66
  4766.5  475.89  4808.6  476.29  4851.6  475.84  4894.1  476.33  4948.1  475.82
  4959.0  475.95  4970.5  475.52  4978.1  474.24  4983.5  474.04  4992.7  474.43
  4998.3  472.96  4998.8  472.16  5003.8  472.16  5004.3  472.96  5011.3  474.50
  5031.3  474.22  5045.1  475.52  5061.3  477.50  5071.4  478.12  5101.4  478.93
  5151.4  481.18  5171.4  481.48  5191.4  482.31  5201.4  483.04  5245.4  484.13
#Mann=4,-1,0
  4629.0    0.05       0  4948.1    0.16       0  4998.3    0.07       0
  5004.3    0.16       0
Bank Sta=4970.5,5045.1
Exp/Cntr=0.3,0.1

Type RM Length L Ch R = 1,667,337,337,337
BEGIN DESCRIPTION:
XS3203A
END DESCRIPTION:
XS GIS Cut Line= 3
      2783188.71      7057680.96      2782933.53      7057503.90
      2782689.35      7057496.10
#Sta/Elev= 30
  4689.9  475.11  4725.8  474.90  4759.0  473.91  4797.4  473.36  4812.2  474.21
  4827.1  474.07  4833.2  473.71  4848.0  474.16  4869.0  473.99  4934.5  474.44
  4955.4  474.01  4970.3  474.17  4982.1  472.36  4982.6  471.56  4987.6  471.56
  4988.1  472.36  4991.2  473.15  5005.7  473.11  5069.1  473.30  5073.7  473.91
  5079.1  474.64  5089.1  475.36  5099.1  474.68  5122.7  474.49  5129.1  475.30
  5169.1  475.40  5199.1  476.22  5219.1  477.22  5239.1  477.09  5244.8  477.65
#Mann=4,-1,0
  4689.9    0.05       0  4982.1    0.03       0  4988.1    0.05       0
  5005.7    0.16       0
Bank Sta=4759,5073.7
Exp/Cntr=0.3,0.1

Type RM Length L Ch R = 1,330,192,192,192
BEGIN DESCRIPTION:
XS3204A
END DESCRIPTION:
XS GIS Cut Line= 4
      2783329.35      7057615.83      2783243.43      7057415.36
      2783081.97      7057358.06      2782800.76      7057321.61
#Sta/Elev= 30
  4690.1  474.07  4710.6  472.82  4734.2  472.23  4862.9  471.68  4891.9  472.20
  4916.6  470.32  4923.3  469.24  4938.4  469.95  4945.9  467.66  4946.4  466.86
  4951.4  466.86  4951.9  467.66  4954.2  468.80  4959.6  468.89  4970.2  470.47
  4981.4  470.05  5032.7  470.32  5055.8  470.39  5106.7  470.87  5126.9  472.13
  5137.0  472.19  5157.2  471.04  5167.2  471.63  5197.5  471.20  5216.3  472.09
  5221.4  471.58  5288.2  474.00  5327.5  474.66  5338.7  475.61  5363.1  475.89
#Mann=6,-1,0
  4690.1    0.05       0  4945.9    0.07       0  4951.9    0.05       0
  4981.4    0.16       0  5055.8    0.05       0  5327.5    0.16       0
Bank Sta=4916.6,5032.7
Exp/Cntr=0.3,0.1

Type RM Length L Ch R = 1,138,0,0,0
BEGIN DESCRIPTION:
UNT 038 in LFCCL Watershed 1.0
END DESCRIPTION:
XS GIS Cut Line= 3
      2783386.68      7057516.96      2783261.66      7057225.25
      2782910.08      7057235.67
#Sta/Elev= 30
  4688.0  471.62  4722.8  471.87  4752.8  471.26  4842.4  471.03  4905.2  471.56
  4912.1  471.15  4928.7  470.85  4934.2  470.23  4956.8  469.37  4981.3  468.68
  4983.8  467.05  4984.3  466.25  4989.3  466.25  4989.8  467.05  5002.8  468.71
  5022.0  468.41  5042.0  468.72  5062.1  468.06  5090.3  468.20  5102.1  468.93
  5112.1  468.56  5131.2  469.37  5161.4  471.96  5166.4  471.27  5222.1  472.14
  5232.1  472.47  5252.1  474.32  5262.1  474.70  5292.2  473.34  5357.1  474.33
#Mann=5,-1,0
  4688.0    0.05       0  4912.1    0.16       0  4983.8    0.07       0
  4989.8    0.16       0  5090.3    0.05       0
Bank Sta=4956.8,5131.2
Exp/Cntr=0.3,0.1

Chan Stop Cuts=-1