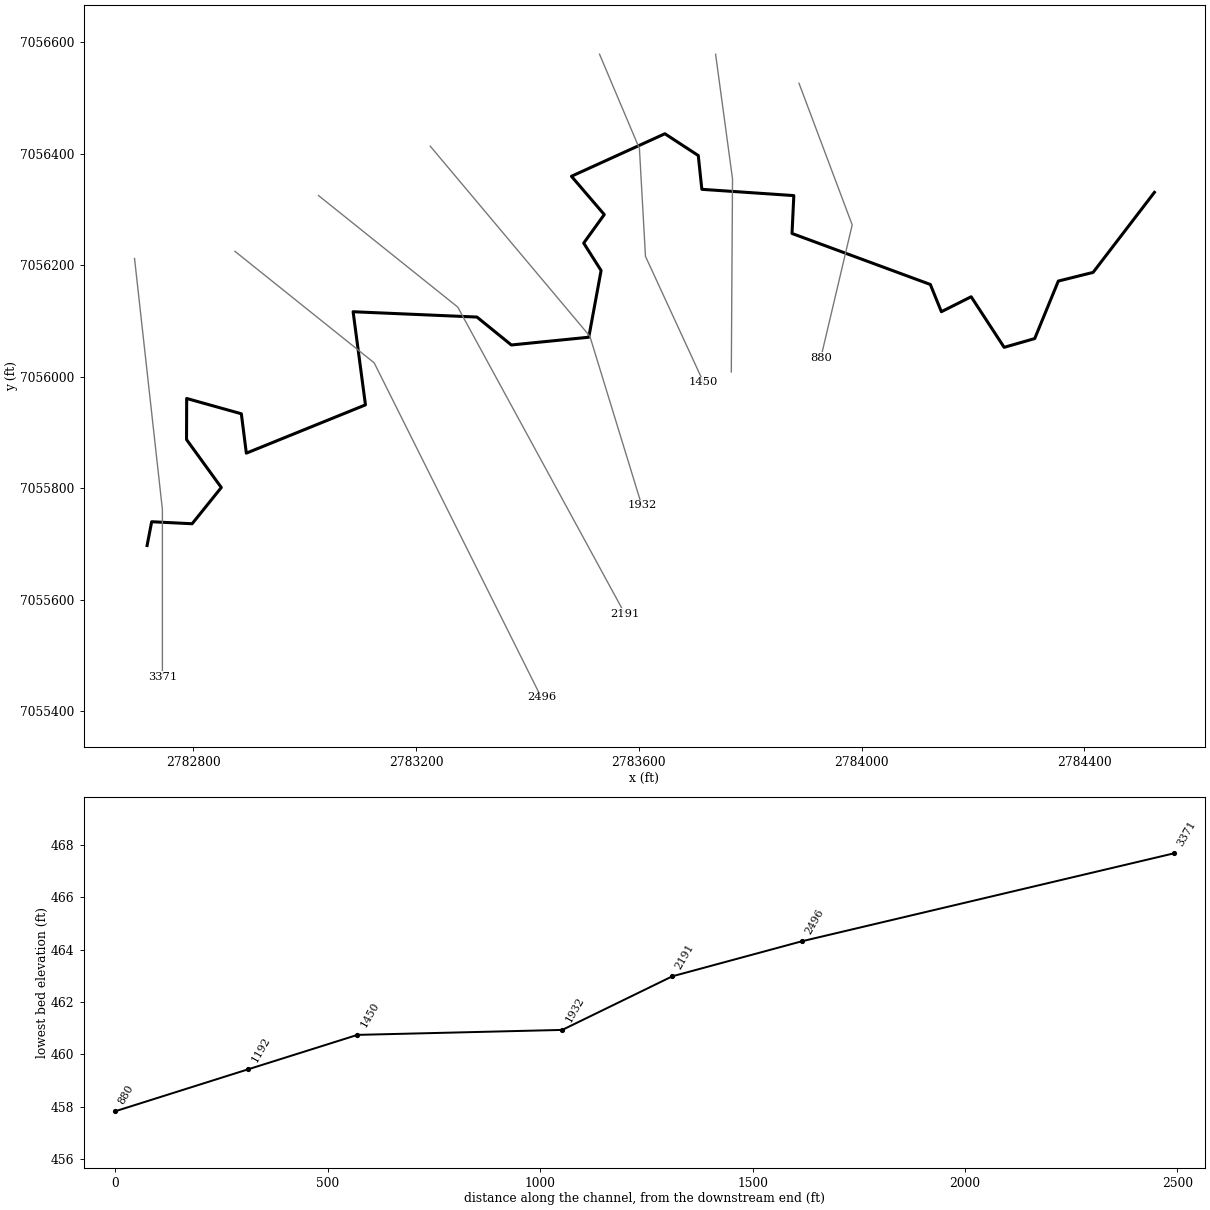
--- UNT 039 in LFCCL Watershed.prj (project) ---

Proj Title=UNT 039 in LFCCL Watershed Base Level Engineering
Current Plan=p01
Default Exp/Contr=0.3,0.1
English Units
Geom File=g01
Flow File=f01
Plan File=p01
BEGIN DESCRIPTION:
UNT 039 in LFCCL Watershed
END DESCRIPTION:

--- UNT 039 in LFCCL Watershed.p01 (plan) ---

Plan Title=Multiple Run
Short Identifier=Multiple
Geom File=g01
Flow File=f01
Subcritical Flow
K Sum by GR= 0
Std Step Tol= 0.01
Critical Tol= 0.01
Num of Std Step Trials= 20
Max Error Tol= 0.3
Flow Tol Ratio= 0.001
Split Flow NTrial= 30
Split Flow Tol= 0.02
Split Flow Ratio= 0.02
Log Output Level= 0
Friction Slope Method= 1
Unsteady Friction Slope Method= 2
Unsteady Bridges Friction Slope Method= 1
Parabolic Critical Depth
Global Vel Dist=  1 , 1 , 1
Global Log Level= 0
CheckData=True
Encroach Param= -1, 0, 0, 0
BEGIN DESCRIPTION:
Multiple Run
END DESCRIPTION:

--- UNT 039 in LFCCL Watershed.f01 (steady flow) ---

Flow Title=Multiple
Number of Profiles=7
Profile Names=10-year,25-year,50-year,1pct_min,100-year,1pct_plu,500-year
River Rch & RM= UNT 039 in LFCCL,Reach-1,3371
     277     354     414     242     482     961     652
Boundary for River Rch & Prof#=UNT 039 in LFCCL,Reach-1,1
Up Type=0
Dn Type=3
Dn Slope=0.005
Boundary for River Rch & Prof#=UNT 039 in LFCCL,Reach-1,2
Up Type=0
Dn Type=3
Dn Slope=0.005
Boundary for River Rch & Prof#=UNT 039 in LFCCL,Reach-1,3
Up Type=0
Dn Type=3
Dn Slope=0.005
Boundary for River Rch & Prof#=UNT 039 in LFCCL,Reach-1,4
Up Type=0
Dn Type=3
Dn Slope=0.005
Boundary for River Rch & Prof#=UNT 039 in LFCCL,Reach-1,5
Up Type=0
Dn Type=3
Dn Slope=0.005
Boundary for River Rch & Prof#=UNT 039 in LFCCL,Reach-1,6
Up Type=0
Dn Type=3
Dn Slope=0.005
Boundary for River Rch & Prof#=UNT 039 in LFCCL,Reach-1,7
Up Type=0
Dn Type=3
Dn Slope=0.005

--- UNT 039 in LFCCL Watershed.g01 (geometry) ---

Geom Title=Existing Conditions

River Reach=UNT 039 in LFCCL,Reach-1
Reach XY= 30
      2782717.31      7055697.49      2782725.56      7055740.11
      2782798.19      7055736.52      2782850.54      7055801.49
      2782788.12      7055887.47      2782788.40      7055961.13
      2782886.51      7055933.72      2782895.48      7055863.08
      2783109.31      7055949.64      2783087.15      7056116.65
      2783309.47      7056107.11      2783371.20      7056057.05
      2783510.20      7056070.94      2783532.31      7056190.56
      2783501.07      7056239.73      2783538.02      7056290.89
      2783479.09      7056359.54      2783646.83      7056435.80
      2783706.76      7056396.72      2783713.19      7056336.15
      2783878.27      7056324.92      2783875.04      7056256.99
      2784123.34      7056165.54      2784143.15      7056116.70
      2784196.62      7056143.54      2784255.82      7056052.84
      2784310.70      7056068.54      2784353.09      7056171.65
      2784415.52      7056187.21      2784525.59      7056330.71

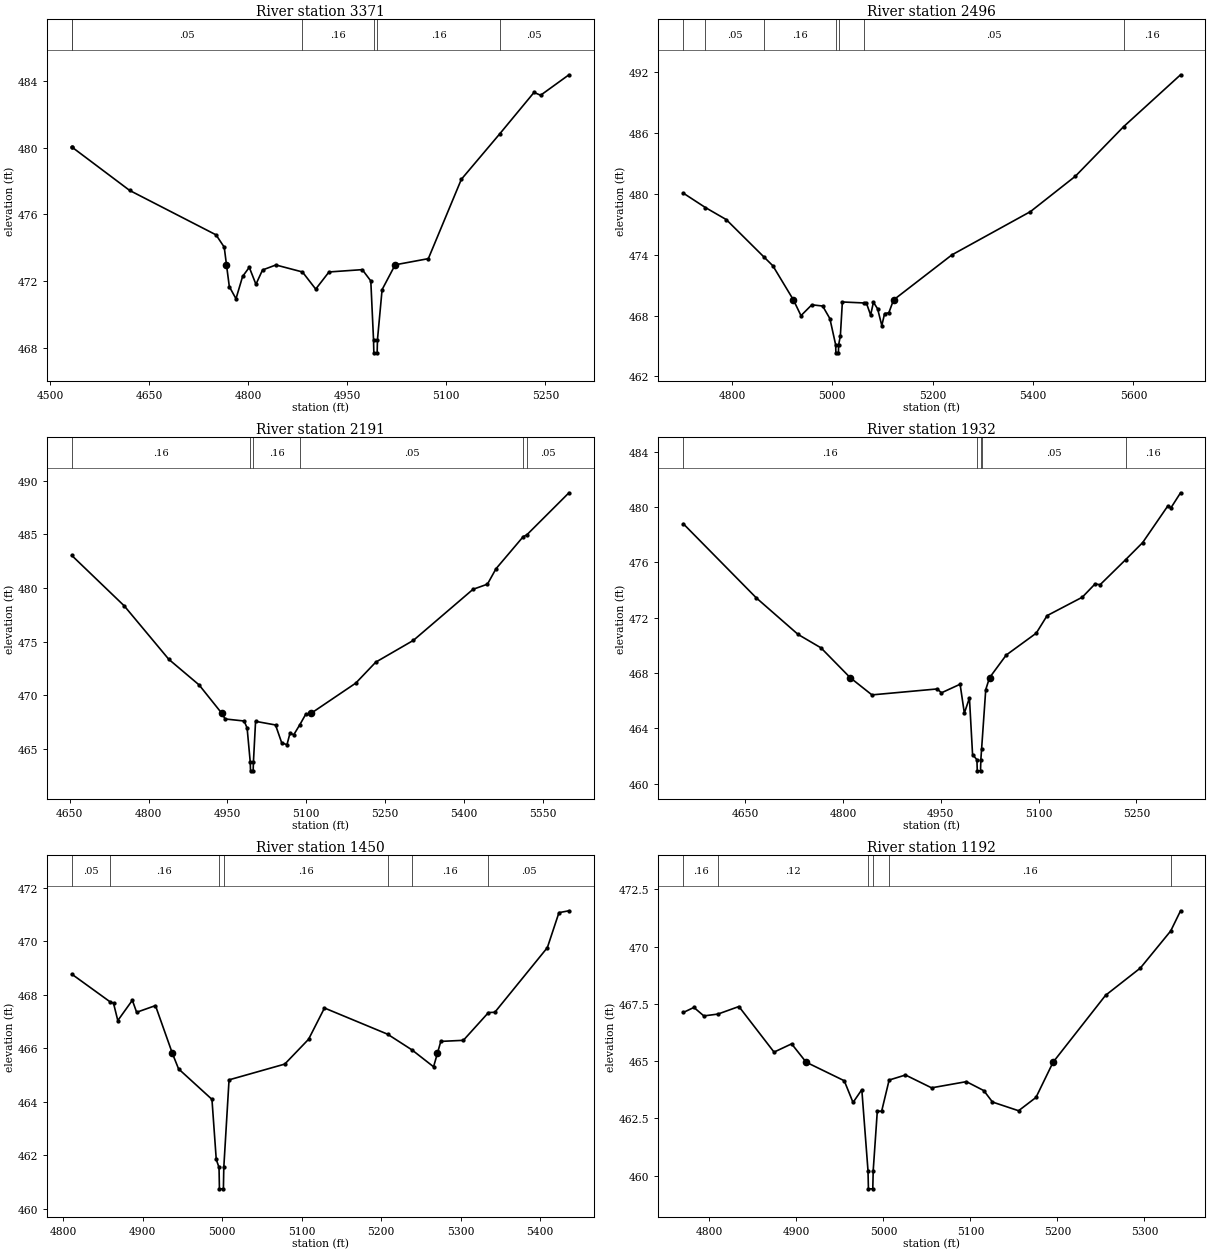
Type RM Length L Ch R = 1,3371,875,875,875
BEGIN DESCRIPTION:
UNT 039 in LFCCL Watershed 4.0
END DESCRIPTION:
XS GIS Cut Line= 3
      2782694.79      7056212.17      2782744.79      7055762.15
      2782744.79      7055462.14
#Sta/Elev= 30
  4532.8  480.06  4533.3  480.04  4620.5  477.44  4751.3  474.77  4763.7  474.03
  4767.1  472.97  4771.4  471.66  4781.5  470.93  4791.5  472.27  4801.6  472.82
  4811.7  471.80  4821.7  472.66  4841.9  472.96  4882.1  472.54  4902.2  471.51
  4922.3  472.54  4972.7  472.68  4985.6  472.00  4989.7  468.48  4990.2  467.68
  4995.2  467.68  4995.7  468.48  5002.7  471.48  5022.5  472.97  5072.7  473.34
  5122.7  478.11  5180.8  480.84  5232.7  483.33  5242.7  483.16  5285.6  484.39
#Mann=6,-1,0
  4532.8    0.16       0  4533.3    0.05       0  4882.1    0.16       0
  4989.7    0.07       0  4995.7    0.16       0  5180.8    0.05       0
Bank Sta=4767.1,5022.5
Exp/Cntr=0.3,0.1

Type RM Length L Ch R = 1,2496,305,305,305
BEGIN DESCRIPTION:
UNT 039 in LFCCL Watershed 3.0
END DESCRIPTION:
XS GIS Cut Line= 3
      2782874.99      7056225.00      2783125.00      7056025.00
      2783425.01      7055424.98
#Sta/Elev= 30
  4703.0  480.08  4747.0  478.66  4788.6  477.47  4863.1  473.81  4881.5  472.91
  4922.5  469.54  4937.5  467.99  4959.1  469.06  4980.7  468.94  4995.1  467.70
  5006.6  465.12  5007.1  464.32  5012.1  464.32  5012.6  465.12  5016.0  465.99
  5020.0  469.34  5063.9  469.24  5067.9  469.23  5076.3  468.05  5081.9  469.31
  5090.2  468.67  5098.6  467.01  5104.2  468.20  5112.6  468.27  5122.0  469.54
  5238.4  473.99  5394.9  478.26  5484.4  481.75  5580.3  486.63  5694.0  491.76
#Mann=7,-1,0
  4703.0    0.16       0  4747.0    0.05       0  4863.1    0.16       0
  5006.6    0.07       0  5012.6    0.16       0  5063.9    0.05       0
  5580.3    0.16       0
Bank Sta=4922.5,5122
Exp/Cntr=0.3,0.1

Type RM Length L Ch R = 1,2191,259,259,259
BEGIN DESCRIPTION:
UNT 039 in LFCCL Watershed 2.0
END DESCRIPTION:
XS GIS Cut Line= 3
      2783025.02      7056324.99      2783275.00      7056125.00
      2783574.98      7055575.03
#Sta/Elev= 30
  4653.6  483.04  4753.6  478.34  4838.5  473.36  4896.1  470.98  4939.1  468.35
  4945.7  467.81  4981.8  467.62  4987.5  466.97  4993.5  463.78  4994.0  462.98
  4999.0  462.98  4999.5  463.78  5003.6  467.59  5041.6  467.25  5053.5  465.57
  5063.4  465.42  5069.1  466.48  5076.3  466.34  5087.9  467.28  5099.0  468.24
  5109.7  468.35  5194.4  471.15  5232.4  473.10  5304.1  475.13  5417.5  479.88
  5445.0  480.36  5461.2  481.79  5513.2  484.79  5519.7  484.94  5600.2  488.87
#Mann=6,-1,0
  4653.6    0.16       0  4993.5    0.07       0  4999.5    0.16       0
  5087.9    0.05       0  5513.2    0.16       0  5519.7    0.05       0
Bank Sta=4939.1,5109.7
Exp/Cntr=0.3,0.1

Type RM Length L Ch R = 1,1932,482,482,482
BEGIN DESCRIPTION:
XS3208A
END DESCRIPTION:
XS GIS Cut Line= 3
      2783225.69      7056413.45      2783512.15      7056072.73
      2783605.30      7055769.45
#Sta/Elev= 30
  4555.3  478.79  4667.5  473.42  4731.3  470.79  4766.4  469.82  4811.3  467.66
  4844.5  466.42  4944.6  466.85  4951.1  466.57  4979.7  467.19  4986.2  465.10
  4994.0  466.20  4998.8  462.11  5005.5  461.73  5006.0  460.93  5011.0  460.93
  5011.5  461.73  5012.7  462.54  5019.0  466.80  5024.8  467.66  5050.4  469.30
  5096.4  470.88  5113.1  472.15  5167.0  473.48  5186.4  474.43  5194.5  474.39
  5233.4  476.19  5259.6  477.43  5297.9  480.06  5303.2  479.96  5317.7  481.03
#Mann=5,-1,0
  4555.3    0.16       0  5005.5    0.07       0  5011.5    0.16       0
  5012.7    0.05       0  5233.4    0.16       0
Bank Sta=4811.3,5024.8
Exp/Cntr=0.3,0.1

Type RM Length L Ch R = 1,1450,258,258,258
BEGIN DESCRIPTION:
XS3207A
END DESCRIPTION:
XS GIS Cut Line= 4
      2783529.50      7056578.40      2783601.13      7056409.10
      2783611.98      7056215.96      2783716.12      7055990.31
#Sta/Elev= 30
  4810.5  468.78  4858.4  467.75  4863.1  467.69  4868.5  467.04  4886.8  467.80
  4892.2  467.35  4915.9  467.60  4937.2  465.81  4945.0  465.23  4987.0  464.09
  4992.4  461.84  4995.9  461.54  4996.4  460.74  5001.4  460.74  5001.9  461.54
  5008.5  464.82  5078.6  465.41  5108.6  466.34  5128.6  467.51  5208.0  466.53
  5238.8  465.94  5265.9  465.31  5270.7  465.81  5275.0  466.26  5303.4  466.30
  5335.0  467.34  5343.0  467.35  5409.1  469.77  5423.7  471.08  5436.3  471.15
#Mann=7,-1,0
  4810.5    0.05       0  4858.4    0.16       0  4995.9    0.07       0
  5001.9    0.16       0  5208.0    0.12       0  5238.8    0.16       0
  5335.0    0.05       0
Bank Sta=4937.2,5270.7
Exp/Cntr=0.3,0.1

Type RM Length L Ch R = 1,1192,312,312,312
BEGIN DESCRIPTION:
XS3206A
END DESCRIPTION:
XS GIS Cut Line= 3
      2783737.85      7056578.35      2783768.23      7056354.85
      2783766.06      7056008.81
#Sta/Elev= 30
  4769.9  467.12  4782.1  467.34  4793.5  466.97  4809.7  467.05  4833.8  467.38
  4874.2  465.39  4894.4  465.75  4911.1  464.95  4954.9  464.14  4965.0  463.19
  4975.1  463.75  4982.2  460.22  4982.7  459.42  4987.7  459.42  4988.2  460.22
  4992.9  462.81  4997.9  462.81  5006.5  464.17  5025.3  464.39  5055.3  463.83
  5095.3  464.10  5115.3  463.71  5125.3  463.21  5155.3  462.83  5175.3  463.41
  5195.0  464.95  5255.3  467.87  5295.3  469.06  5330.2  470.68  5341.5  471.56
#Mann=6,-1,0
  4769.9    0.16       0  4809.7    0.12       0  4982.2    0.07       0
  4988.2    0.12       0  5006.5    0.16       0  5330.2    0.05       0
Bank Sta=4911.1,5195
Exp/Cntr=0.3,0.1

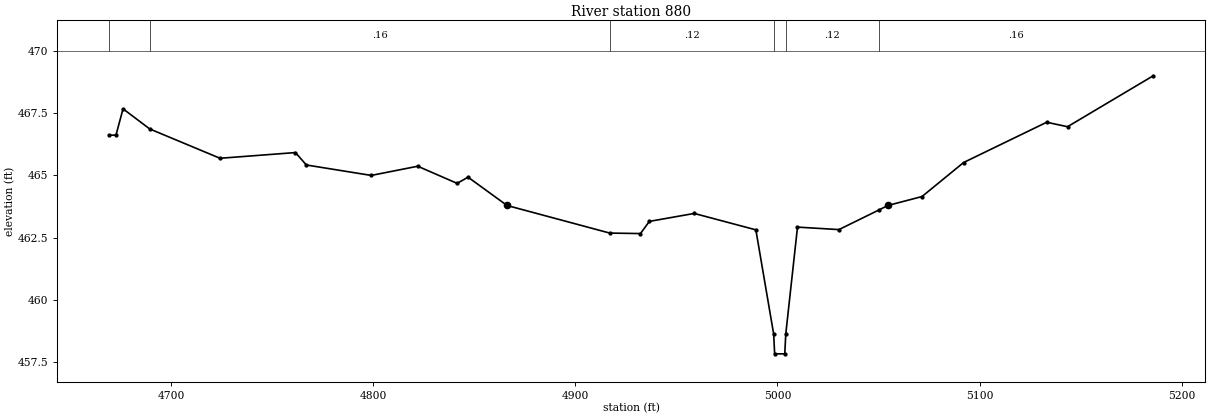
Type RM Length L Ch R = 1,880,0,0,0
BEGIN DESCRIPTION:
UNT 039 in LFCCL Watershed 1.0
END DESCRIPTION:
XS GIS Cut Line= 3
      2783887.59      7056526.27      2783983.07      7056272.38
      2783926.66      7056033.71
#Sta/Elev= 30
  4669.4  466.62  4672.7  466.62  4676.2  467.68  4689.4  466.87  4724.2  465.69
  4761.5  465.92  4766.9  465.42  4799.0  465.00  4822.0  465.37  4841.5  464.68
  4846.9  464.93  4866.2  463.79  4917.0  462.68  4932.2  462.66  4936.6  463.15
  4958.8  463.47  4989.3  462.81  4998.1  458.62  4998.6  457.82  5003.6  457.82
  5004.1  458.62  5009.9  462.92  5030.4  462.82  5050.2  463.61  5054.6  463.79
  5071.5  464.15  5092.1  465.52  5133.2  467.14  5143.5  466.96  5185.9  469.01
#Mann=6,-1,0
  4669.4    0.12       0  4689.4    0.16       0  4917.0    0.12       0
  4998.1    0.07       0  5004.1    0.12       0  5050.2    0.16       0
Bank Sta=4866.2,5054.6
Exp/Cntr=0.3,0.1

Chan Stop Cuts=-1