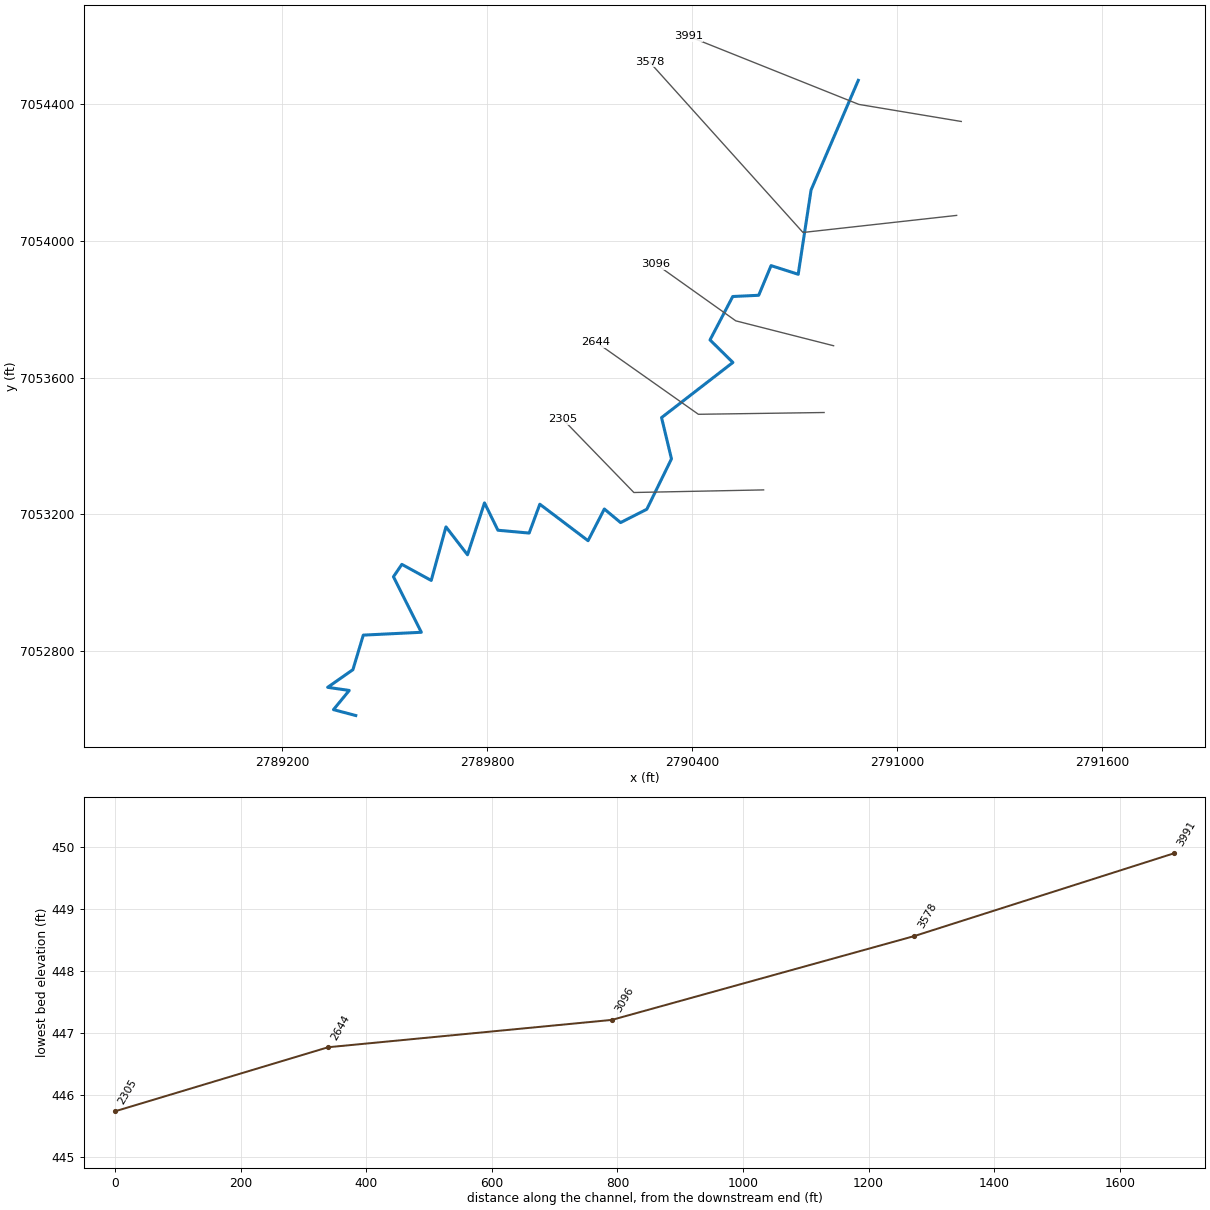
--- UNT 040 in LFCCL Watershed.prj (project) ---

Proj Title=UNT 040 in LFCCL Watershed Base Level Engineering
Current Plan=p01
Default Exp/Contr=0.3,0.1
English Units
Geom File=g01
Flow File=f01
Plan File=p01
BEGIN DESCRIPTION:
UNT 040 in LFCCL Watershed
END DESCRIPTION:

--- UNT 040 in LFCCL Watershed.p01 (plan) ---

Plan Title=Multiple Run
Short Identifier=Multiple
Geom File=g01
Flow File=f01
Subcritical Flow
K Sum by GR= 0
Std Step Tol= 0.01
Critical Tol= 0.01
Num of Std Step Trials= 20
Max Error Tol= 0.3
Flow Tol Ratio= 0.001
Split Flow NTrial= 30
Split Flow Tol= 0.02
Split Flow Ratio= 0.02
Log Output Level= 0
Friction Slope Method= 1
Unsteady Friction Slope Method= 2
Unsteady Bridges Friction Slope Method= 1
Parabolic Critical Depth
Global Vel Dist=  1 , 1 , 1
Global Log Level= 0
CheckData=True
Encroach Param= -1, 0, 0, 0
BEGIN DESCRIPTION:
Multiple Run
END DESCRIPTION:

--- UNT 040 in LFCCL Watershed.f01 (steady flow) ---

Flow Title=Multiple
Number of Profiles=7
Profile Names=10-year,25-year,50-year,1pct_min,100-year,1pct_plu,500-year
River Rch & RM= UNT 040 in LFCCL,Reach-1,3991
     588     777     927     549    1096    2186    1531
Boundary for River Rch & Prof#=UNT 040 in LFCCL,Reach-1,1
Up Type=0
Dn Type=3
Dn Slope=0.005
Boundary for River Rch & Prof#=UNT 040 in LFCCL,Reach-1,2
Up Type=0
Dn Type=3
Dn Slope=0.005
Boundary for River Rch & Prof#=UNT 040 in LFCCL,Reach-1,3
Up Type=0
Dn Type=3
Dn Slope=0.005
Boundary for River Rch & Prof#=UNT 040 in LFCCL,Reach-1,4
Up Type=0
Dn Type=3
Dn Slope=0.005
Boundary for River Rch & Prof#=UNT 040 in LFCCL,Reach-1,5
Up Type=0
Dn Type=3
Dn Slope=0.005
Boundary for River Rch & Prof#=UNT 040 in LFCCL,Reach-1,6
Up Type=0
Dn Type=3
Dn Slope=0.005
Boundary for River Rch & Prof#=UNT 040 in LFCCL,Reach-1,7
Up Type=0
Dn Type=3
Dn Slope=0.005

--- UNT 040 in LFCCL Watershed.g01 (geometry) ---

Geom Title=Existing Conditions

River Reach=UNT 040 in LFCCL,Reach-1
Reach XY= 30
      2790886.91      7054470.44      2790748.67      7054149.36
      2790711.03      7053902.59      2790631.57      7053927.95
      2790595.38      7053841.12      2790519.38      7053837.51
      2790452.82      7053710.40      2790519.79      7053644.44
      2790310.95      7053482.95      2790339.98      7053362.15
      2790267.78      7053214.64      2790191.06      7053175.63
      2790143.39      7053215.36      2790095.73      7053122.58
      2789954.52      7053229.36      2789923.31      7053144.89
      2789831.79      7053153.22      2789792.54      7053233.26
      2789742.74      7053081.32      2789679.72      7053162.98
      2789636.50      7053006.21      2789550.57      7053053.26
      2789525.94      7053016.99      2789607.59      7052854.44
      2789437.66      7052846.10      2789407.27      7052744.93
      2789333.37      7052693.24      2789396.52      7052684.14
      2789350.38      7052627.92      2789415.59      7052610.71

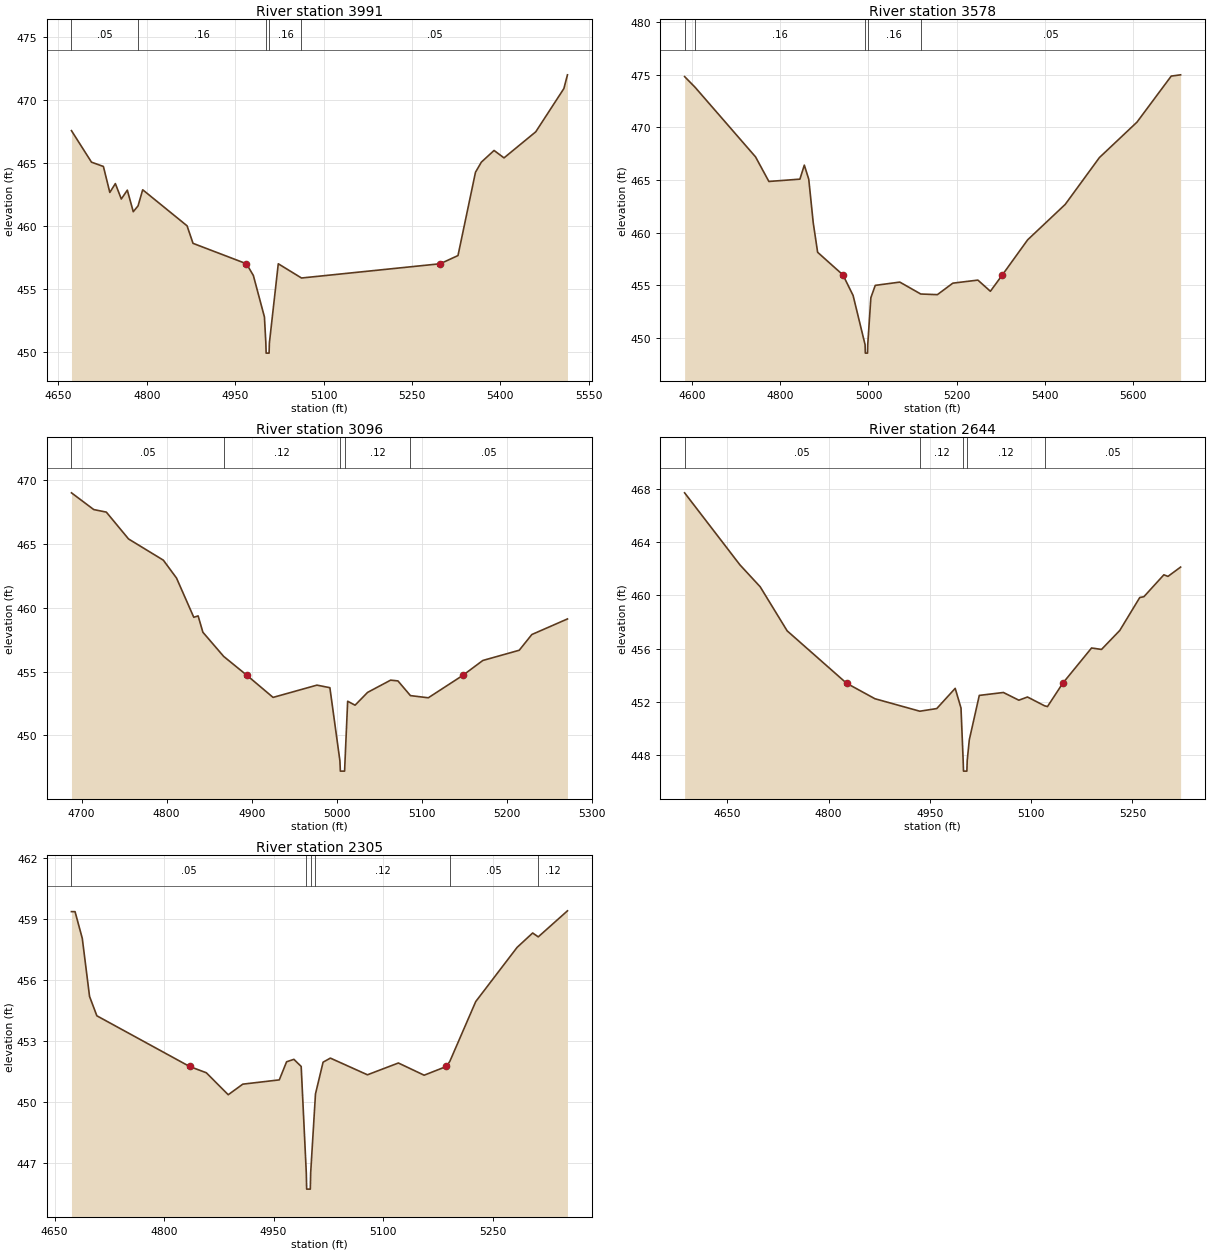
Type RM Length L Ch R = 1,3991,413,413,413
BEGIN DESCRIPTION:
UNT 040 in LFCCL Watershed 3.0
END DESCRIPTION:
XS GIS Cut Line= 3
      2791188.50      7054350.01      2790888.54      7054400.00
      2790389.29      7054599.70
#Sta/Elev= 30
  4672.1  467.54  4706.1  465.04  4726.3  464.70  4737.2  462.64  4746.6  463.34
  4756.7  462.12  4766.9  462.82  4777.0  461.11  4785.1  461.57  4793.0  462.85
  4868.3  459.99  4878.4  458.60  4969.1  456.98  4980.8  456.05  4999.6  452.76
  5002.0  450.69  5002.5  449.89  5007.5  449.89  5008.0  450.69  5023.1  456.98
  5062.5  455.85  5297.8  456.98  5328.1  457.63  5357.8  464.24  5367.7  465.04
  5389.3  465.97  5406.2  465.38  5460.1  467.45  5507.8  470.88  5513.9  471.97
#Mann=5,-1,0
  4672.1    0.05       0  4785.1    0.16       0  5002.0    0.07       0
  5008.0    0.16       0  5062.5    0.05       0
Bank Sta=4969.1,5297.8
Exp/Cntr=0.3,0.1

Type RM Length L Ch R = 1,3578,482,482,482
BEGIN DESCRIPTION:
UNT 040 in LFCCL Watershed 2.0
END DESCRIPTION:
XS GIS Cut Line= 3
      2791174.98      7054075.00      2790725.00      7054025.00
      2790275.02      7054524.98
#Sta/Elev= 30
  4582.8  474.80  4606.3  473.80  4743.8  467.18  4774.0  464.85  4844.4  465.07
  4854.4  466.40  4864.5  465.06  4874.6  460.94  4884.6  458.13  4942.1  455.98
  4965.1  454.03  4992.3  449.36  4992.8  448.56  4997.8  448.56  4998.3  449.36
  5005.4  453.82  5015.4  454.99  5071.1  455.30  5118.6  454.17  5156.3  454.11
  5191.4  455.20  5248.2  455.49  5276.6  454.43  5303.7  455.98  5361.1  459.31
  5446.3  462.67  5524.0  467.12  5609.2  470.48  5686.9  474.85  5708.2  474.97
#Mann=5,-1,0
  4582.8    0.05       0  4606.3    0.16       0  4992.3    0.07       0
  4998.3    0.16       0  5118.6    0.05       0
Bank Sta=4942.1,5303.7
Exp/Cntr=0.3,0.1

Type RM Length L Ch R = 1,3096,452,452,452
BEGIN DESCRIPTION:
XS3209A
END DESCRIPTION:
XS GIS Cut Line= 3
      2790814.69      7053693.36      2790528.27      7053766.27
      2790293.93      7053932.90
#Sta/Elev= 30
  4688.2  468.99  4714.4  467.68  4729.2  467.48  4755.3  465.38  4796.2  463.72
  4811.7  462.32  4832.0  459.25  4837.1  459.36  4842.7  458.08  4867.1  456.19
  4894.6  454.70  4925.2  452.98  4976.8  453.94  4992.0  453.74  5003.8  448.01
  5004.3  447.21  5009.3  447.21  5009.8  448.01  5012.9  452.68  5021.6  452.37
  5036.3  453.37  5063.4  454.33  5072.0  454.27  5086.7  453.12  5107.7  452.95
  5148.2  454.70  5171.8  455.87  5214.6  456.67  5229.4  457.90  5271.3  459.12
#Mann=5,-1,0
  4688.2    0.05       0  4867.1    0.12       0  5003.8    0.07       0
  5009.8    0.12       0  5086.7    0.05       0
Bank Sta=4894.6,5148.2
Exp/Cntr=0.3,0.1

Type RM Length L Ch R = 1,2644,339,339,339
BEGIN DESCRIPTION:
Mapping XS 6c8ef791
END DESCRIPTION:
XS GIS Cut Line= 3
      2790786.86      7053497.88      2790418.77      7053492.67
      2790119.20      7053703.93
#Sta/Elev= 30
  4586.7  467.72  4668.6  462.30  4698.6  460.65  4738.6  457.33  4826.5  453.39
  4868.6  452.22  4935.1  451.28  4960.2  451.48  4987.5  453.00  4996.1  451.52
  4999.3  447.57  4999.8  446.77  5004.8  446.77  5005.3  447.57  5008.4  449.13
  5023.2  452.47  5058.9  452.69  5081.8  452.11  5094.6  452.35  5119.8  451.69
  5124.2  451.63  5146.9  453.39  5189.5  456.04  5204.2  455.93  5231.3  457.36
  5260.9  459.84  5267.0  459.90  5296.6  461.55  5302.7  461.43  5321.4  462.13
#Mann=5,-1,0
  4586.7    0.05       0  4935.1    0.12       0  4999.3    0.07       0
  5005.3    0.12       0  5119.8    0.05       0
Bank Sta=4826.5,5146.9
Exp/Cntr=0.3,0.1

Type RM Length L Ch R = 1,2305,0,0,0
BEGIN DESCRIPTION:
UNT 040 in LFCCL Watershed 1.0
END DESCRIPTION:
XS GIS Cut Line= 3
      2790609.75      7053271.30      2790229.87      7053263.67
      2790021.17      7053478.81
#Sta/Elev= 30
  4673.0  459.38  4677.9  459.38  4687.8  458.07  4697.8  455.21  4707.8  454.26
  4834.8  451.77  4857.8  451.46  4887.8  450.38  4907.8  450.90  4957.8  451.11
  4967.8  452.00  4977.8  452.12  4987.8  451.77  4994.8  446.54  4995.3  445.74
  5000.3  445.74  5000.8  446.54  5007.4  450.42  5017.8  451.98  5027.8  452.18
  5078.6  451.36  5121.0  451.94  5156.3  451.34  5186.8  451.77  5191.5  452.02
  5227.0  454.96  5283.6  457.62  5305.0  458.33  5312.7  458.14  5352.7  459.42
#Mann=6,-1,0
  4673.0    0.05       0  4994.8    0.03       0  5000.8    0.05       0
  5007.4    0.12       0  5191.5    0.05       0  5312.7    0.12       0
Bank Sta=4834.8,5186.8
Exp/Cntr=0.3,0.1

Chan Stop Cuts=-1