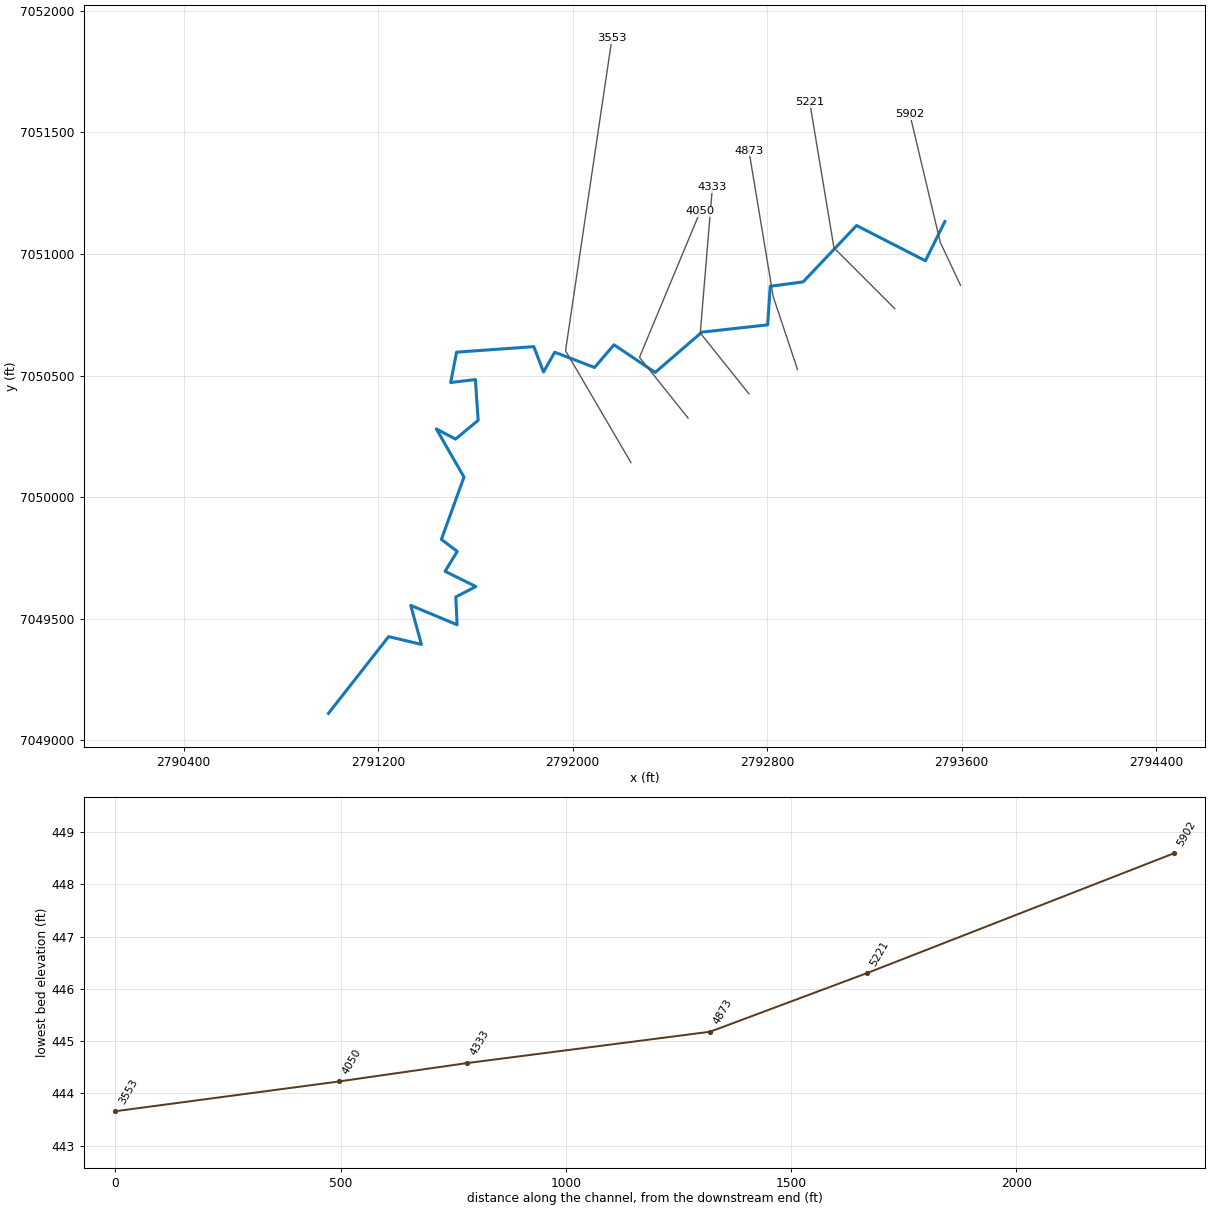
--- UNT 041 in LFCCL Watershed.prj (project) ---

Proj Title=UNT 041 in LFCCL Watershed Base Level Engineering
Current Plan=p01
Default Exp/Contr=0.3,0.1
English Units
Geom File=g01
Flow File=f01
Plan File=p01
BEGIN DESCRIPTION:
UNT 041 in LFCCL Watershed
END DESCRIPTION:

--- UNT 041 in LFCCL Watershed.p01 (plan) ---

Plan Title=Multiple Run
Short Identifier=Multiple
Geom File=g01
Flow File=f01
Subcritical Flow
K Sum by GR= 0
Std Step Tol= 0.01
Critical Tol= 0.01
Num of Std Step Trials= 20
Max Error Tol= 0.3
Flow Tol Ratio= 0.001
Split Flow NTrial= 30
Split Flow Tol= 0.02
Split Flow Ratio= 0.02
Log Output Level= 0
Friction Slope Method= 1
Unsteady Friction Slope Method= 2
Unsteady Bridges Friction Slope Method= 1
Parabolic Critical Depth
Global Vel Dist=  1 , 1 , 1
Global Log Level= 0
CheckData=True
Encroach Param= -1, 0, 0, 0
BEGIN DESCRIPTION:
Multiple Run
END DESCRIPTION:

--- UNT 041 in LFCCL Watershed.f01 (steady flow) ---

Flow Title=Multiple
Number of Profiles=7
Profile Names=10-year,25-year,50-year,1pct_min,100-year,1pct_plu,500-year
River Rch & RM= UNT 041 in LFCCL,Reach-1,5902
     436     571     678     401     800    1595    1113
Boundary for River Rch & Prof#=UNT 041 in LFCCL,Reach-1,1
Up Type=0
Dn Type=3
Dn Slope=0.005
Boundary for River Rch & Prof#=UNT 041 in LFCCL,Reach-1,2
Up Type=0
Dn Type=3
Dn Slope=0.005
Boundary for River Rch & Prof#=UNT 041 in LFCCL,Reach-1,3
Up Type=0
Dn Type=3
Dn Slope=0.005
Boundary for River Rch & Prof#=UNT 041 in LFCCL,Reach-1,4
Up Type=0
Dn Type=3
Dn Slope=0.005
Boundary for River Rch & Prof#=UNT 041 in LFCCL,Reach-1,5
Up Type=0
Dn Type=3
Dn Slope=0.005
Boundary for River Rch & Prof#=UNT 041 in LFCCL,Reach-1,6
Up Type=0
Dn Type=3
Dn Slope=0.005
Boundary for River Rch & Prof#=UNT 041 in LFCCL,Reach-1,7
Up Type=0
Dn Type=3
Dn Slope=0.005

--- UNT 041 in LFCCL Watershed.g01 (geometry) ---

Geom Title=Existing Conditions

River Reach=UNT 041 in LFCCL,Reach-1
Reach XY= 30
      2793531.11      7051133.36      2793451.13      7050971.86
      2793167.87      7051116.82      2792948.27      7050885.23
      2792812.73      7050866.94      2792802.06      7050708.36
      2792531.84      7050678.47      2792339.45      7050512.71
      2792170.25      7050626.44      2792090.16      7050533.18
      2791926.28      7050595.78      2791880.33      7050514.66
      2791840.30      7050618.80      2791522.67      7050596.07
      2791498.24      7050471.19      2791600.09      7050483.49
      2791611.33      7050315.59      2791518.33      7050238.56
      2791439.34      7050280.60      2791553.11      7050082.37
      2791460.19      7049826.05      2791525.43      7049776.84
      2791475.45      7049694.81      2791602.13      7049632.21
      2791519.43      7049589.51      2791524.91      7049475.02
      2791334.04      7049554.87      2791378.03      7049394.37
      2791243.11      7049426.34      2790995.59      7049110.71

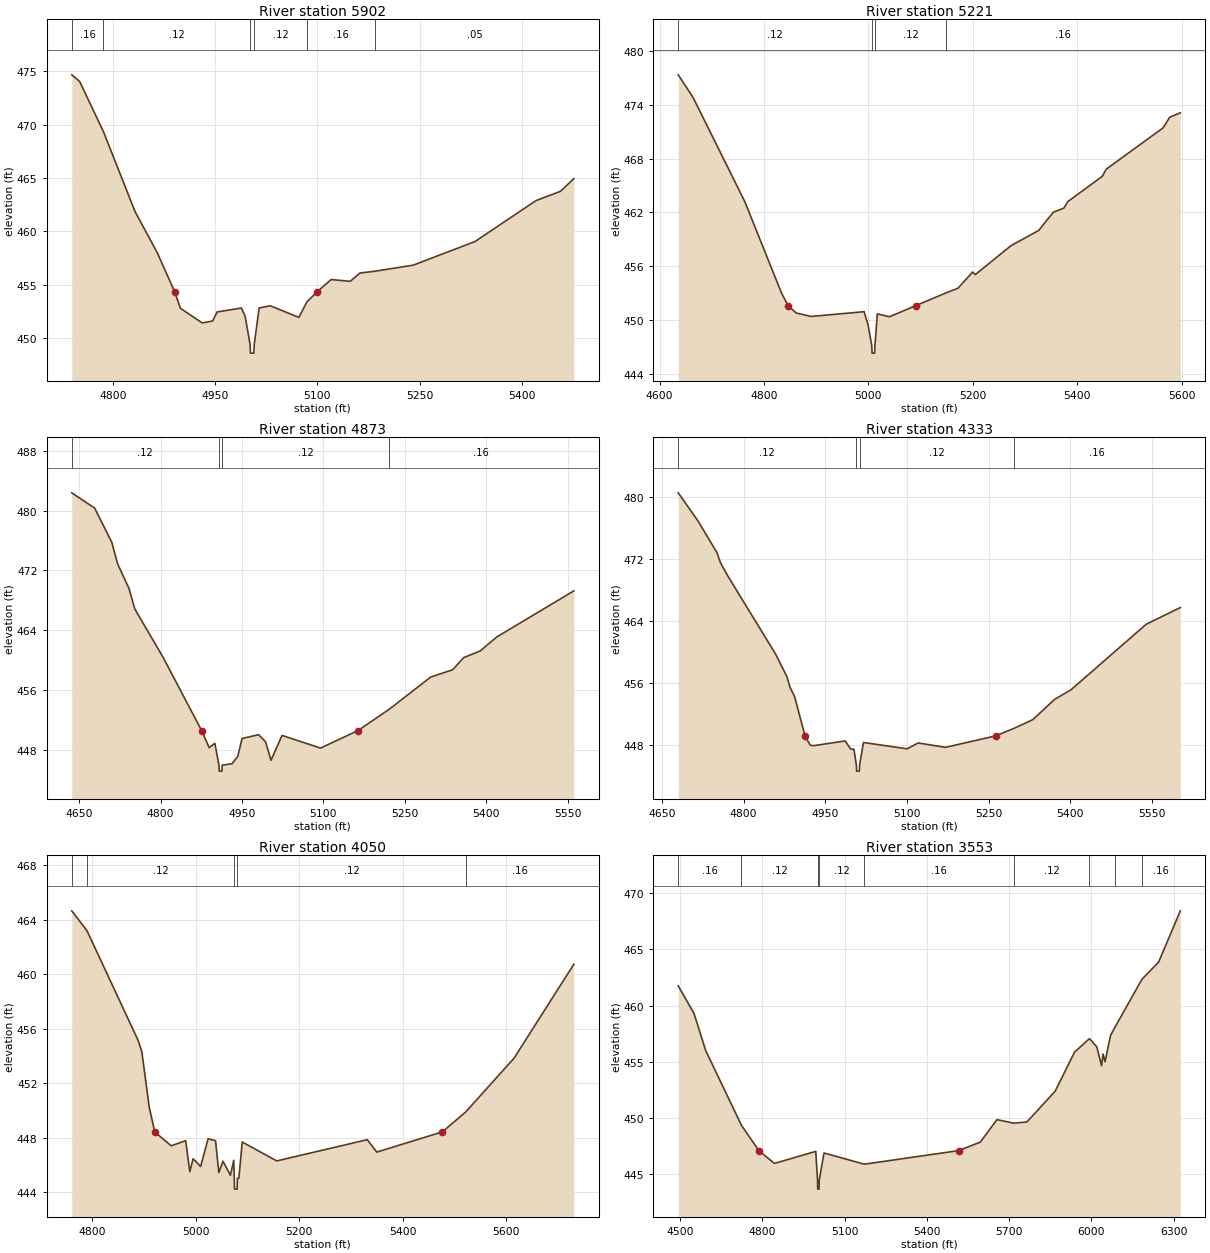
Type RM Length L Ch R = 1,5902,681,681,681
BEGIN DESCRIPTION:
XS3210A
END DESCRIPTION:
XS GIS Cut Line= 3
      2793595.52      7050870.94      2793512.19      7051048.01
      2793387.19      7051574.07
#Sta/Elev= 30
  4739.9  474.68  4751.4  474.07  4786.2  469.37  4832.8  461.85  4865.4  457.99
  4890.8  454.35  4899.2  452.80  4931.2  451.42  4946.5  451.60  4953.1  452.45
  4988.7  452.82  4994.2  452.04  5001.5  449.39  5002.0  448.59  5007.0  448.59
  5007.5  449.39  5014.7  452.82  5030.9  453.03  5073.1  451.94  5084.6  453.38
  5099.9  454.35  5120.4  455.49  5148.3  455.32  5162.6  456.10  5184.6  456.27
  5240.9  456.84  5331.3  459.05  5420.8  462.89  5456.7  463.76  5476.3  464.95
#Mann=6,-1,0
  4739.9    0.16       0  4786.2    0.12       0  5001.5    0.07       0
  5007.5    0.12       0  5084.6    0.16       0  5184.6    0.05       0
Bank Sta=4890.8,5099.9
Exp/Cntr=0.3,0.1

Type RM Length L Ch R = 1,5221,348,348,348
BEGIN DESCRIPTION:
UNT 041 in LFCCL Watershed 5.0
END DESCRIPTION:
XS GIS Cut Line= 3
      2793324.98      7050775.02      2793075.00      7051025.00
      2792975.00      7051625.00
#Sta/Elev= 30
  4635.7  477.33  4664.0  474.82  4763.0  463.22  4833.7  452.98  4846.2  451.59
  4861.9  450.77  4890.2  450.39  4991.8  450.92  4999.4  449.44  5006.5  447.10
  5007.0  446.30  5012.0  446.30  5012.5  447.10  5017.1  450.68  5039.9  450.35
  5090.7  451.59  5149.3  453.03  5171.7  453.54  5199.6  455.34  5204.7  455.05
  5273.1  458.28  5326.3  459.98  5354.2  462.01  5374.5  462.47  5382.1  463.20
  5448.0  466.01  5455.6  466.81  5564.6  471.42  5577.2  472.60  5597.5  473.10
#Mann=4,-1,0
  4635.7    0.12       0  5006.5    0.07       0  5012.5    0.12       0
  5149.3    0.16       0
Bank Sta=4846.2,5090.7
Exp/Cntr=0.3,0.1

Type RM Length L Ch R = 1,4873,540,540,540
BEGIN DESCRIPTION:
UNT 041 in LFCCL Watershed 4.0
END DESCRIPTION:
XS GIS Cut Line= 3
      2792924.99      7050525.02      2792825.00      7050825.00
      2792725.00      7051425.02
#Sta/Elev= 30
  4636.6  482.37  4678.7  480.33  4710.4  475.74  4720.9  472.90  4742.0  469.59
  4752.5  466.87  4805.2  460.33  4875.8  450.59  4889.6  448.32  4900.1  448.90
  4907.6  445.98  4908.1  445.18  4913.1  445.18  4913.6  445.98  4931.7  446.17
  4942.3  447.15  4950.2  449.54  4980.7  450.05  4993.4  449.10  5003.5  446.63
  5023.8  449.95  5094.7  448.26  5163.3  450.59  5220.5  453.41  5297.5  457.75
  5338.0  458.73  5358.3  460.35  5388.7  461.24  5419.2  463.11  5561.1  469.27
#Mann=4,-1,0
  4636.6    0.12       0  4907.6    0.07       0  4913.6    0.12       0
  5220.5    0.16       0
Bank Sta=4875.8,5163.3
Exp/Cntr=0.3,0.1

Type RM Length L Ch R = 1,4333,283,283,283
BEGIN DESCRIPTION:
UNT 041 in LFCCL Watershed 3.0
END DESCRIPTION:
XS GIS Cut Line= 3
      2792725.01      7050424.99      2792525.00      7050675.00
      2792575.00      7051274.95
#Sta/Elev= 30
  4680.1  480.53  4716.1  476.93  4751.3  472.80  4757.7  471.50  4772.2  469.67
  4858.6  459.74  4879.4  456.83  4885.8  455.35  4893.8  454.23  4912.9  449.14
  4922.6  447.93  4929.0  447.87  4986.7  448.48  4997.1  447.41  5002.8  447.41
  5007.3  445.38  5007.8  444.58  5012.8  444.58  5013.3  445.38  5020.3  448.28
  5100.6  447.46  5120.7  448.22  5170.9  447.65  5263.6  449.14  5296.9  450.11
  5331.4  451.23  5371.5  453.85  5401.7  455.10  5539.6  463.55  5602.3  465.71
#Mann=4,-1,0
  4680.1    0.12       0  5007.3    0.07       0  5013.3    0.12       0
  5296.9    0.16       0
Bank Sta=4912.9,5263.6
Exp/Cntr=0.3,0.1

Type RM Length L Ch R = 1,4050,497,497,497
BEGIN DESCRIPTION:
UNT 041 in LFCCL Watershed 2.0
END DESCRIPTION:
XS GIS Cut Line= 3
      2792475.02      7050324.97      2792275.00      7050575.00
      2792525.00      7051175.01
#Sta/Elev= 30
  4760.5  464.66  4789.9  463.20  4888.6  455.16  4895.8  454.34  4910.2  450.24
  4920.9  448.43  4952.6  447.41  4980.6  447.79  4988.6  445.51  4995.0  446.46
  5009.5  445.89  5023.9  447.92  5038.3  447.79  5044.7  445.45  5052.7  446.28
  5067.1  445.25  5073.5  446.35  5074.5  445.03  5075.0  444.23  5080.0  444.23
  5080.5  445.03  5083.4  445.03  5089.9  447.69  5156.5  446.30  5331.5  447.86
  5349.9  446.95  5476.5  448.43  5521.9  449.90  5615.3  453.85  5730.7  460.74
#Mann=5,-1,0
  4760.5    0.16       0  4789.9    0.12       0  5074.5    0.07       0
  5080.5    0.12       0  5521.9    0.16       0
Bank Sta=4920.9,5476.5
Exp/Cntr=0.3,0.1

Type RM Length L Ch R = 1,3553,0,0,0
BEGIN DESCRIPTION:
UNT 041 in LFCCL Watershed 1.0
END DESCRIPTION:
XS GIS Cut Line= 3
      2792239.97      7050141.86      2791970.87      7050601.93
      2792161.84      7051886.62
#Sta/Elev= 30
  4492.6  461.76  4550.2  459.30  4593.1  455.98  4723.3  449.34  4786.7  447.09
  4843.5  445.95  4994.4  447.02  5000.9  444.46  5001.4  443.66  5006.4  443.66
  5006.9  444.46  5024.5  446.88  5171.5  445.88  5516.0  447.09  5594.9  447.85
  5655.5  449.85  5717.0  449.53  5764.7  449.64  5867.8  452.38  5938.6  455.86
  5992.9  457.06  6019.5  456.34  6037.2  454.65  6042.3  455.69  6049.8  455.01
  6070.0  457.36  6085.4  458.05  6184.6  462.35  6245.4  463.88  6324.4  468.44
#Mann=9,-1,0
  4492.6    0.16       0  4723.3    0.12       0  5000.9    0.07       0
  5006.9    0.12       0  5171.5    0.16       0  5717.0    0.12       0
  5992.9    0.16       0  6085.4    0.12       0  6184.6    0.16       0
Bank Sta=4786.7,5516
Exp/Cntr=0.3,0.1

Chan Stop Cuts=-1