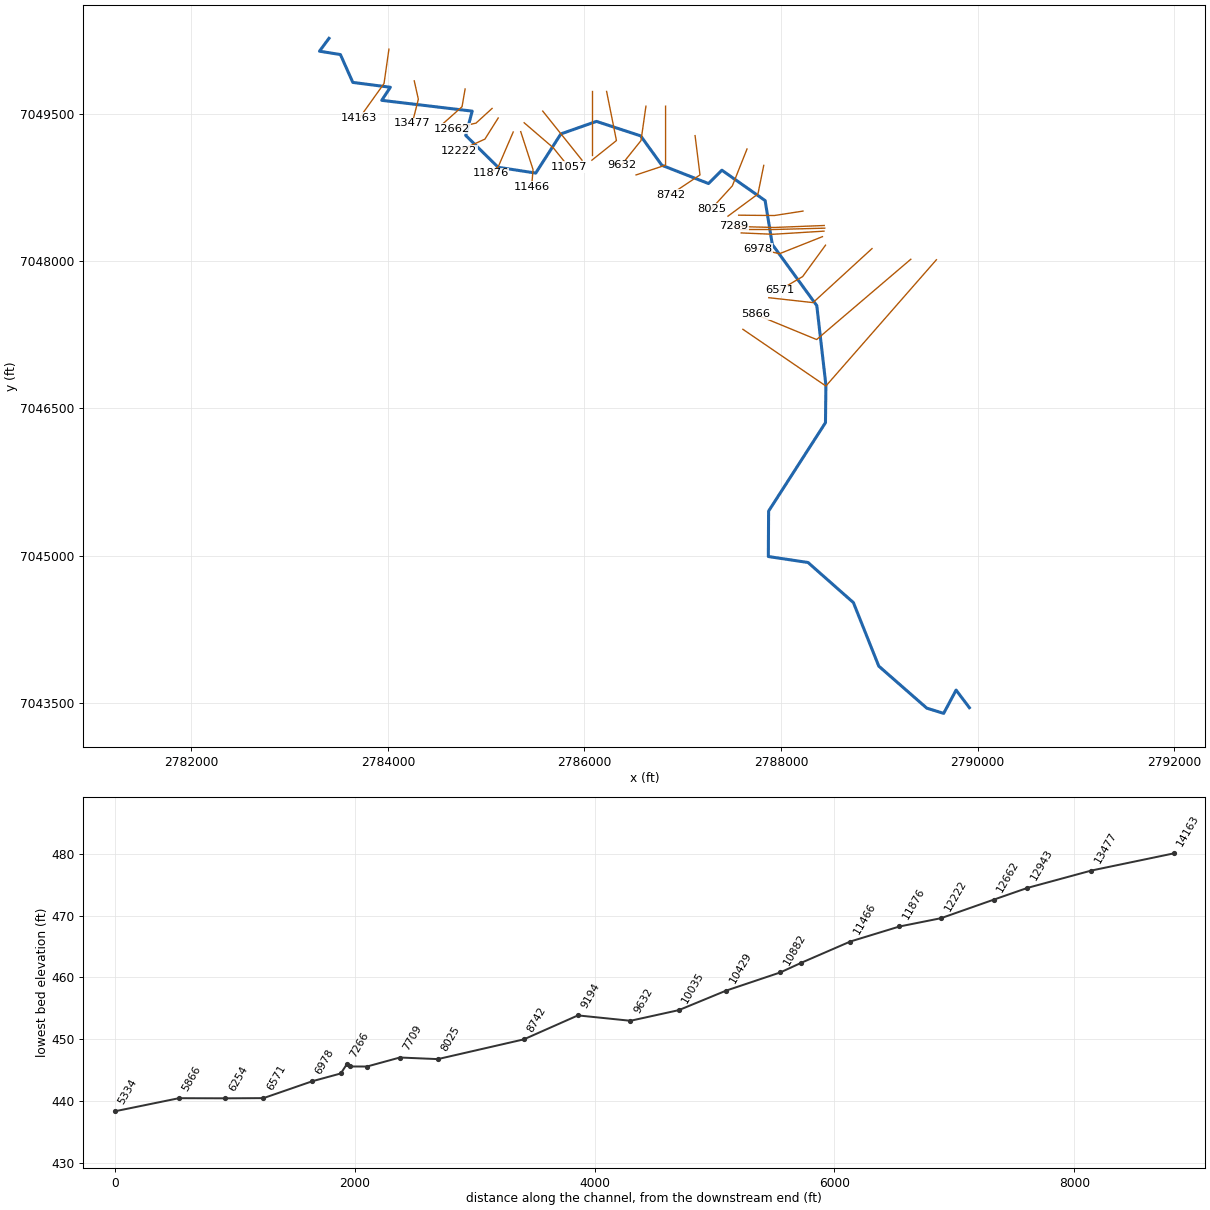
--- UNT 042 in LFCCL Watershed.prj (project) ---

Proj Title=UNT 042 in LFCCL Watershed Base Level Engineering
Current Plan=p01
Default Exp/Contr=0.3,0.1
English Units
Geom File=g01
Flow File=f01
Plan File=p01
BEGIN DESCRIPTION:
UNT 042 in LFCCL Watershed
END DESCRIPTION:

--- UNT 042 in LFCCL Watershed.p01 (plan) ---

Plan Title=Multiple Run
Short Identifier=Multiple
Geom File=g01
Flow File=f01
Subcritical Flow
K Sum by GR= 0
Std Step Tol= 0.01
Critical Tol= 0.01
Num of Std Step Trials= 20
Max Error Tol= 0.3
Flow Tol Ratio= 0.001
Split Flow NTrial= 30
Split Flow Tol= 0.02
Split Flow Ratio= 0.02
Log Output Level= 0
Friction Slope Method= 1
Unsteady Friction Slope Method= 2
Unsteady Bridges Friction Slope Method= 1
Parabolic Critical Depth
Global Vel Dist=  1 , 1 , 1
Global Log Level= 0
CheckData=True
Encroach Param= -1, 0, 0, 0
BEGIN DESCRIPTION:
Multiple Run
END DESCRIPTION:

--- UNT 042 in LFCCL Watershed.f01 (steady flow) ---

Flow Title=Multiple
Number of Profiles=7
Profile Names=10-year,25-year,50-year,1pct_min,100-year,1pct_plu,500-year
River Rch & RM= UNT 042 in LFCCL,Reach-1,14163
     369     481     570     336     671    1339     930
River Rch & RM= UNT 042 in LFCCL,Reach-1,6571
     488     646     773     460     917    1829    1293
Boundary for River Rch & Prof#=UNT 042 in LFCCL,Reach-1,1
Up Type=0
Dn Type=3
Dn Slope=0.005
Boundary for River Rch & Prof#=UNT 042 in LFCCL,Reach-1,2
Up Type=0
Dn Type=3
Dn Slope=0.005
Boundary for River Rch & Prof#=UNT 042 in LFCCL,Reach-1,3
Up Type=0
Dn Type=3
Dn Slope=0.005
Boundary for River Rch & Prof#=UNT 042 in LFCCL,Reach-1,4
Up Type=0
Dn Type=3
Dn Slope=0.005
Boundary for River Rch & Prof#=UNT 042 in LFCCL,Reach-1,5
Up Type=0
Dn Type=3
Dn Slope=0.005
Boundary for River Rch & Prof#=UNT 042 in LFCCL,Reach-1,6
Up Type=0
Dn Type=3
Dn Slope=0.005
Boundary for River Rch & Prof#=UNT 042 in LFCCL,Reach-1,7
Up Type=0
Dn Type=3
Dn Slope=0.005

--- UNT 042 in LFCCL Watershed.g01 (geometry) ---

Geom Title=Existing Conditions

River Reach=UNT 042 in LFCCL,Reach-1
Reach XY= 30
      2783400.59      7050265.71      2783303.60      7050134.77
      2783516.73      7050100.49      2783643.03      7049816.92
      2784024.60      7049767.51      2783937.41      7049634.42
      2784857.54      7049524.52      2784791.50      7049277.34
      2785121.54      7048952.70      2785504.00      7048893.88
      2785759.56      7049292.56      2786121.83      7049420.01
      2786571.83      7049272.46      2786786.79      7048973.52
      2787261.39      7048787.25      2787397.57      7048923.17
      2787837.67      7048613.76      2787910.82      7048166.93
      2788363.35      7047544.22      2788455.89      7046735.78
      2788451.70      7046352.90      2787873.03      7045452.27
      2787870.23      7044989.84      2788274.20      7044929.04
      2788735.81      7044520.75      2788993.74      7043874.17
      2789482.77      7043445.84      2789654.03      7043392.92
      2789780.68      7043629.96      2789915.59      7043450.71

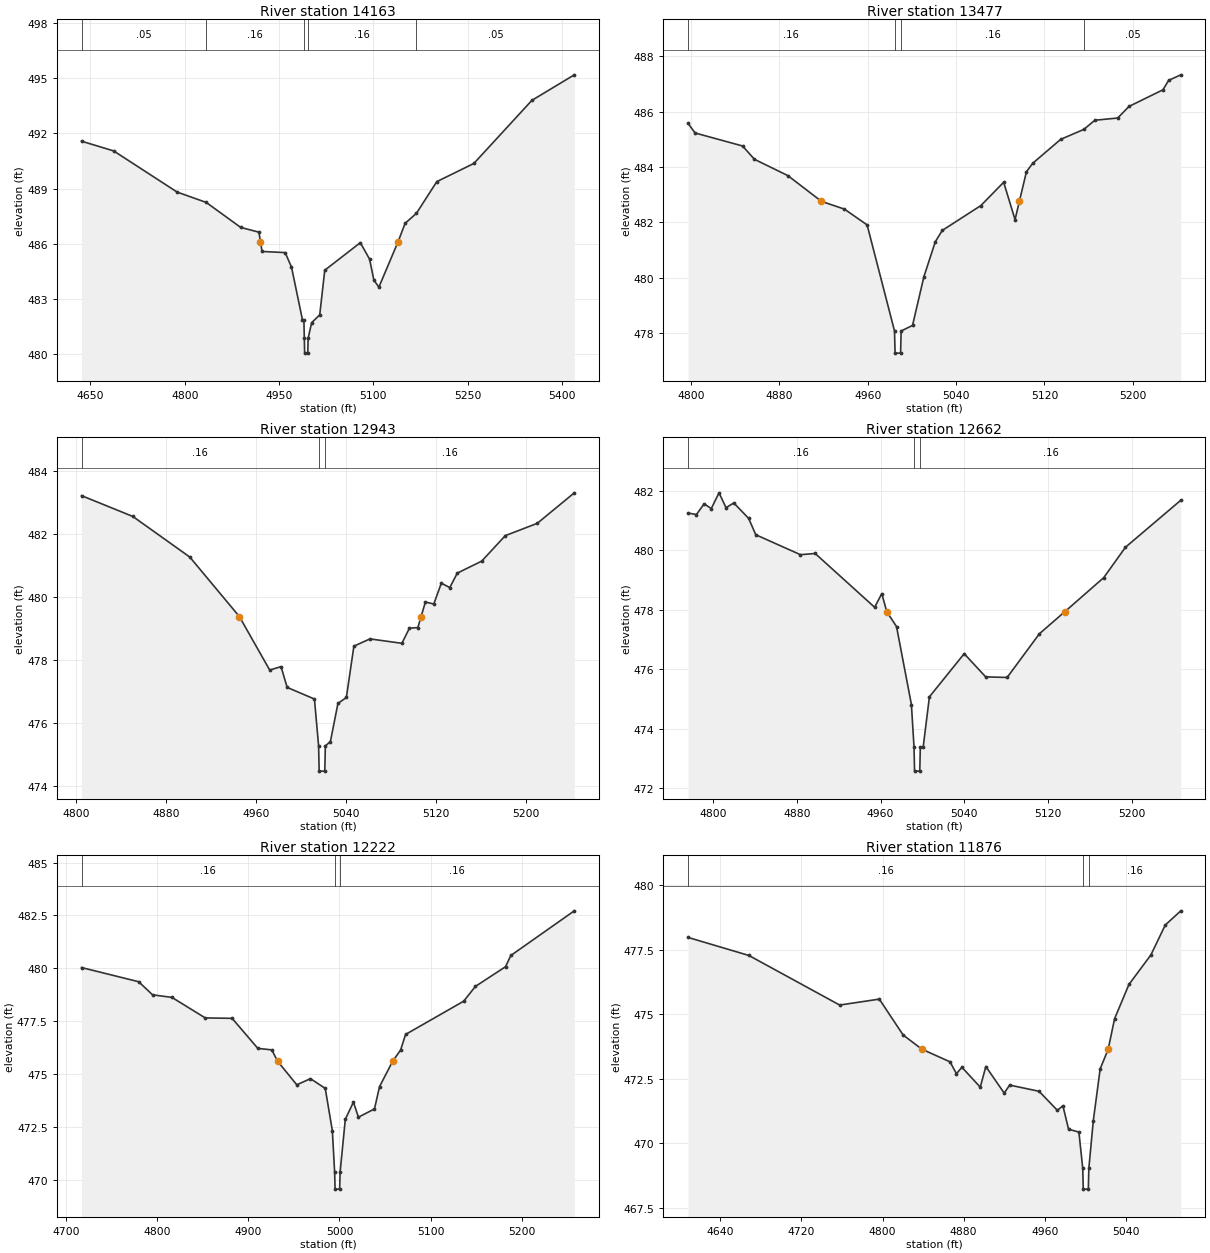
Type RM Length L Ch R = 1,14163,686,686,686
BEGIN DESCRIPTION:
UNT 042 in LFCCL Watershed 18.0
END DESCRIPTION:
XS GIS Cut Line= 3
      2784010.42      7050155.58      2783960.42      7049805.56
      2783710.41      7049455.55
#Sta/Elev= 30
  4635.9  491.58  4687.0  491.05  4788.0  488.81  4834.1  488.25  4889.0  486.89
  4918.0  486.63  4920.5  486.10  4923.0  485.58  4959.7  485.52  4969.8  484.73
  4987.2  481.87  4989.5  481.87  4990.2  480.85  4990.7  480.05  4995.7  480.05
  4996.2  480.85  5001.9  481.71  5014.7  482.13  5022.7  484.56  5079.3  486.06
  5094.0  485.16  5100.8  484.02  5108.8  483.64  5139.2  486.10  5150.5  487.11
  5168.6  487.66  5200.9  489.38  5259.9  490.37  5352.1  493.80  5419.6  495.19
#Mann=5,-1,0
  4635.9    0.05       0  4834.1    0.16       0  4990.2    0.07       0
  4996.2    0.16       0  5168.6    0.05       0
Bank Sta=4920.5,5139.2
Exp/Cntr=0.3,0.1

Type RM Length L Ch R = 1,13477,534,534,534
BEGIN DESCRIPTION:
XS3211A
END DESCRIPTION:
XS GIS Cut Line= 3
      2784267.97      7049833.25      2784309.64      7049645.73
      2784247.24      7049399.61
#Sta/Elev= 30
  4797.4  485.58  4803.8  485.23  4846.8  484.76  4857.5  484.28  4887.8  483.69
  4918.2  482.76  4939.0  482.48  4959.5  481.91  4984.3  478.08  4984.8  477.28
  4989.8  477.28  4990.3  478.08  5000.6  478.28  5010.9  480.04  5021.2  481.30
  5027.5  481.71  5062.5  482.61  5083.1  483.45  5093.4  482.10  5097.3  482.76
  5103.7  483.83  5109.5  484.14  5134.7  485.00  5155.7  485.36  5165.6  485.69
  5186.3  485.77  5196.6  486.19  5227.3  486.79  5232.4  487.13  5243.4  487.33
#Mann=4,-1,0
  4797.4    0.16       0  4984.3    0.07       0  4990.3    0.16       0
  5155.7    0.05       0
Bank Sta=4918.2,5097.3
Exp/Cntr=0.3,0.1

Type RM Length L Ch R = 1,12943,281,281,281
BEGIN DESCRIPTION:
XS3212A
END DESCRIPTION:
XS GIS Cut Line= 3
      2784785.33      7049749.90      2784754.08      7049569.34
      2784563.57      7049399.61
#Sta/Elev= 30
  4804.5  483.22  4850.1  482.56  4900.8  481.27  4944.9  479.38  4971.9  477.68
  4982.0  477.79  4987.4  477.13  5011.7  476.76  5015.4  475.27  5015.9  474.47
  5020.9  474.47  5021.4  475.27  5025.9  475.41  5032.6  476.62  5040.1  476.81
  5046.8  478.44  5061.1  478.67  5089.5  478.53  5096.2  479.01  5103.7  479.03
  5106.6  479.38  5110.4  479.84  5117.9  479.78  5124.6  480.44  5132.1  480.30
  5138.8  480.76  5160.5  481.14  5181.5  481.95  5209.9  482.34  5242.9  483.31
#Mann=3,-1,0
  4804.5    0.16       0  5015.4    0.07       0  5021.4    0.16       0
Bank Sta=4944.9,5106.6
Exp/Cntr=0.3,0.1

Type RM Length L Ch R = 1,12662,440,440,440
BEGIN DESCRIPTION:
XS3214A
END DESCRIPTION:
XS GIS Cut Line= 3
      2785059.62      7049551.96      2784896.44      7049402.67
      2784653.38      7049347.11
#Sta/Elev= 30
  4776.1  481.25  4784.1  481.20  4791.5  481.56  4798.3  481.40  4805.7  481.93
  4812.4  481.43  4819.8  481.59  4834.0  481.07  4840.8  480.52  4883.4  479.85
  4897.5  479.89  4954.3  478.08  4961.1  478.54  4965.9  477.93  4975.2  477.43
  4989.4  474.81  4991.9  473.37  4992.4  472.57  4997.4  472.57  4997.9  473.37
  5000.6  473.37  5006.6  475.07  5039.8  476.52  5060.3  475.74  5080.8  475.72
  5111.6  477.19  5135.8  477.93  5173.1  479.08  5193.8  480.10  5246.6  481.68
#Mann=3,-1,0
  4776.1    0.16       0  4991.9    0.07       0  4997.9    0.16       0
Bank Sta=4965.9,5135.8
Exp/Cntr=0.3,0.1

Type RM Length L Ch R = 1,12222,346,346,346
BEGIN DESCRIPTION:
XS3213A
END DESCRIPTION:
XS GIS Cut Line= 3
      2785122.16      7049454.78      2784986.72      7049239.48
      2784726.30      7049121.42
#Sta/Elev= 30
  4717.2  480.04  4779.8  479.37  4795.1  478.75  4816.3  478.63  4852.8  477.66
  4882.3  477.64  4910.5  476.22  4925.8  476.15  4932.2  475.61  4953.2  474.50
  4968.2  474.79  4984.4  474.33  4992.2  472.33  4994.7  470.37  4995.2  469.57
  5000.2  469.57  5000.7  470.37  5006.4  472.87  5015.3  473.68  5020.8  472.97
  5038.4  473.36  5043.9  474.41  5058.3  475.61  5067.0  476.14  5072.5  476.88
  5136.2  478.45  5149.1  479.15  5182.1  480.08  5187.9  480.61  5257.5  482.72
#Mann=3,-1,0
  4717.2    0.16       0  4994.7    0.07       0  5000.7    0.16       0
Bank Sta=4932.2,5058.3
Exp/Cntr=0.3,0.1

Type RM Length L Ch R = 1,11876,410,410,410
BEGIN DESCRIPTION:
XS3215A
END DESCRIPTION:
XS GIS Cut Line= 3
      2785274.93      7049312.43      2785125.61      7048965.17
      2785045.79      7048892.29
#Sta/Elev= 30
  4608.1  477.98  4668.2  477.28  4757.7  475.36  4796.8  475.59  4820.3  474.20
  4838.8  473.65  4866.6  473.16  4872.9  472.70  4878.3  472.95  4896.4  472.18
  4901.9  472.98  4920.0  471.95  4925.4  472.26  4954.4  472.02  4972.5  471.28
  4977.9  471.46  4983.5  470.55  4993.7  470.44  4997.5  469.03  4998.0  468.23
  5003.0  468.23  5003.5  469.03  5007.9  470.88  5014.7  472.89  5022.6  473.65
  5028.9  474.83  5043.1  476.16  5064.7  477.30  5078.9  478.46  5094.2  479.01
#Mann=3,-1,0
  4608.1    0.16       0  4997.5    0.07       0  5003.5    0.16       0
Bank Sta=4838.8,5022.6
Exp/Cntr=0.3,0.1

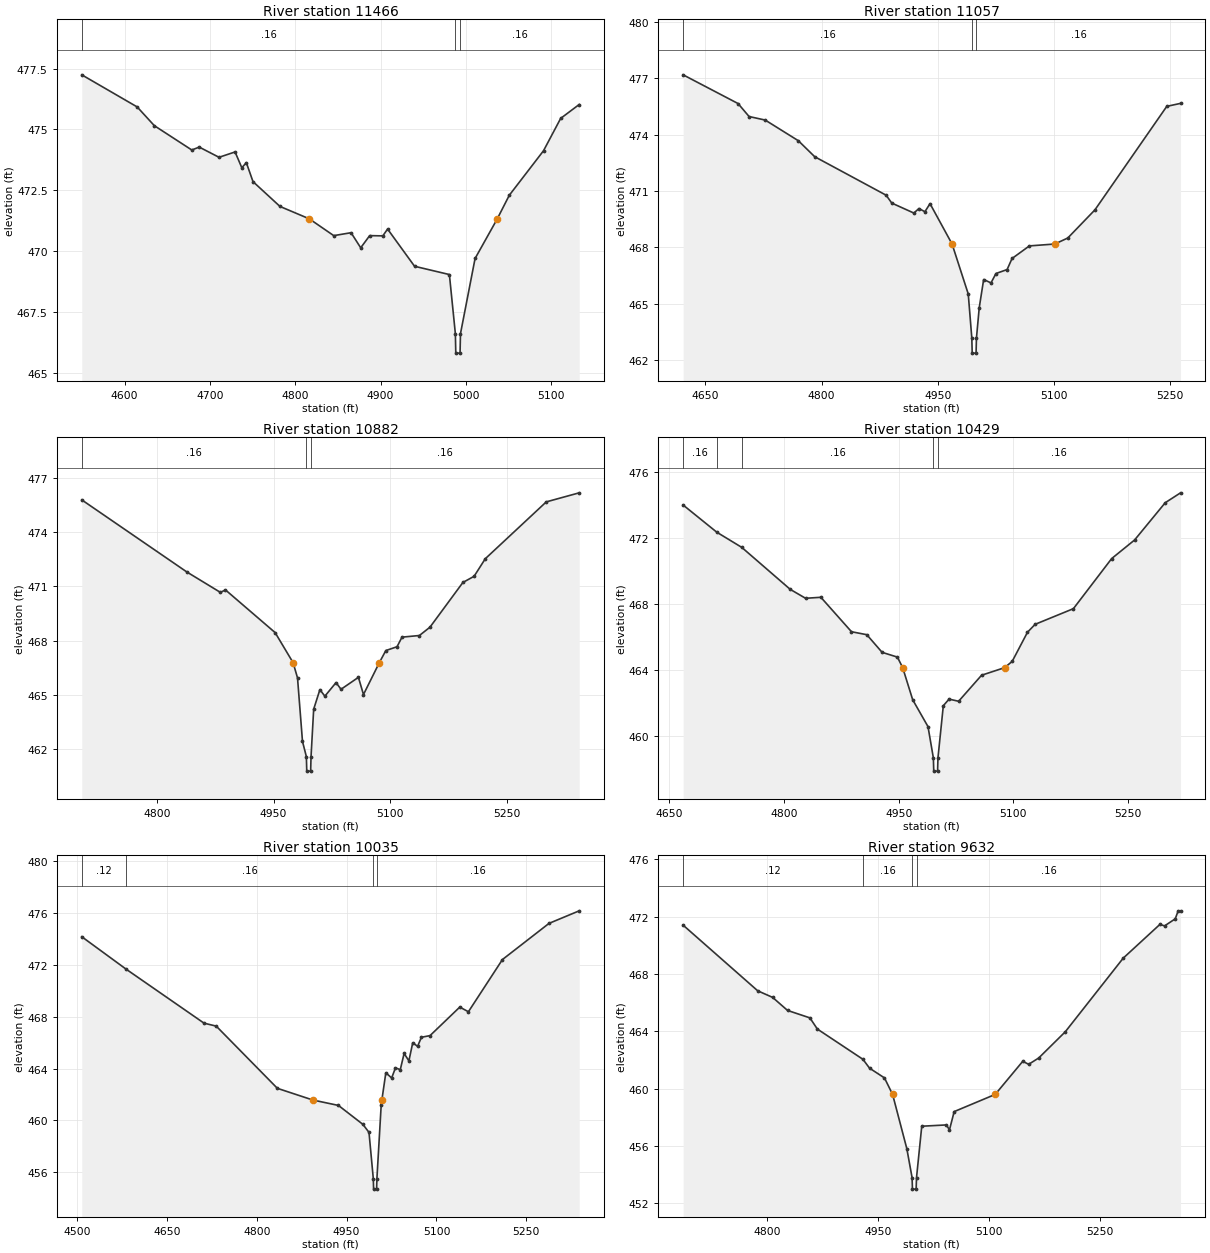
Type RM Length L Ch R = 1,11466,409,409,409
BEGIN DESCRIPTION:
XS3216A
END DESCRIPTION:
XS GIS Cut Line= 3
      2785351.31      7049315.84      2785476.30      7048930.45
      2785462.41      7048753.35
#Sta/Elev= 30
  4549.9  477.24  4614.8  475.92  4634.9  475.15  4678.8  474.15  4687.5  474.27
  4710.7  473.85  4729.5  474.07  4737.4  473.42  4742.7  473.63  4750.5  472.85
  4782.1  471.83  4816.5  471.32  4845.1  470.63  4865.4  470.75  4876.7  470.13
  4887.2  470.63  4902.6  470.62  4908.2  470.90  4939.8  469.37  4980.6  469.03
  4987.6  466.60  4988.1  465.80  4993.1  465.80  4993.6  466.60  5010.7  469.69
  5036.7  471.32  5050.8  472.29  5090.9  474.12  5111.0  475.45  5132.7  476.02
#Mann=3,-1,0
  4549.9    0.16       0  4987.6    0.07       0  4993.6    0.16       0
Bank Sta=4816.5,5036.7
Exp/Cntr=0.3,0.1

Type RM Length L Ch R = 1,11057,175,175,175
BEGIN DESCRIPTION:
XS3217A
END DESCRIPTION:
XS GIS Cut Line= 3
      2785386.04      7049406.13      2785681.17      7049152.67
      2785840.47      7048955.27
#Sta/Elev= 30
  4621.1  477.18  4692.1  475.65  4706.3  474.96  4727.2  474.77  4770.0  473.67
  4791.1  472.82  4883.4  470.77  4890.7  470.35  4919.2  469.82  4925.8  470.06
  4933.5  469.89  4940.1  470.32  4968.6  468.17  4989.5  465.51  4994.1  463.16
  4994.6  462.36  4999.6  462.36  5000.1  463.16  5003.7  464.78  5009.4  466.28
  5018.9  466.10  5025.3  466.60  5039.7  466.81  5046.1  467.40  5068.5  468.07
  5101.3  468.17  5118.1  468.49  5153.2  469.99  5246.0  475.50  5263.8  475.66
#Mann=3,-1,0
  4621.1    0.16       0  4994.1    0.07       0  5000.1    0.16       0
Bank Sta=4968.6,5101.3
Exp/Cntr=0.3,0.1

Type RM Length L Ch R = 1,10882,453,453,453
BEGIN DESCRIPTION:
UNT 042 in LFCCL Watershed 12.0
END DESCRIPTION:
XS GIS Cut Line= 3
      2785575.02      7049524.98      2785775.00      7049275.00
      2785975.01      7049024.99
#Sta/Elev= 30
  4703.1  475.78  4838.3  471.80  4881.6  470.67  4888.0  470.81  4952.0  468.45
  4975.1  466.79  4980.8  465.95  4987.2  462.44  4992.2  461.60  4992.7  460.80
  4997.7  460.80  4998.2  461.60  5001.6  464.22  5009.6  465.30  5016.0  464.94
  5030.4  465.69  5036.8  465.32  5059.2  465.98  5065.7  465.03  5086.1  466.79
  5094.5  467.46  5108.9  467.67  5115.3  468.20  5137.7  468.29  5151.3  468.75
  5193.7  471.22  5208.1  471.56  5222.5  472.53  5301.0  475.67  5343.4  476.17
#Mann=3,-1,0
  4703.1    0.16       0  4992.2    0.07       0  4998.2    0.16       0
Bank Sta=4975.1,5086.1
Exp/Cntr=0.3,0.1

Type RM Length L Ch R = 1,10429,394,394,394
BEGIN DESCRIPTION:
UNT 042 in LFCCL Watershed 11.0
END DESCRIPTION:
XS GIS Cut Line= 3
      2786075.00      7049724.99      2786075.00      7049375.00
      2786075.00      7049074.99
#Sta/Elev= 30
  4668.4  474.00  4712.4  472.35  4745.0  471.43  4808.4  468.88  4828.4  468.34
  4848.4  468.40  4888.4  466.31  4908.4  466.13  4928.4  465.06  4948.4  464.77
  4955.3  464.13  4968.4  462.18  4988.4  460.55  4995.4  458.65  4995.9  457.85
  5000.9  457.85  5001.4  458.65  5008.4  461.82  5015.9  462.22  5028.4  462.09
  5058.4  463.67  5088.5  464.13  5098.4  464.51  5118.4  466.28  5128.4  466.76
  5178.4  467.71  5228.4  470.75  5258.4  471.88  5298.4  474.14  5318.4  474.74
#Mann=5,-1,0
  4668.4    0.16       0  4712.4    0.12       0  4745.0    0.16       0
  4995.4    0.07       0  5001.4    0.16       0
Bank Sta=4955.3,5088.5
Exp/Cntr=0.3,0.1

Type RM Length L Ch R = 1,10035,403,403,403
BEGIN DESCRIPTION:
UNT 042 in LFCCL Watershed 10.0
END DESCRIPTION:
XS GIS Cut Line= 3
      2786224.99      7049725.03      2786325.00      7049225.00
      2786074.99      7049024.99
#Sta/Elev= 30
  4508.1  474.18  4582.3  471.67  4712.1  467.51  4732.5  467.28  4834.5  462.48
  4893.5  461.58  4936.4  461.16  4977.2  459.70  4987.4  459.08  4994.6  455.50
  4995.1  454.70  5000.1  454.70  5000.6  455.50  5007.8  461.22  5008.9  461.58
  5015.5  463.68  5025.2  463.28  5031.6  464.06  5039.6  463.92  5046.0  465.17
  5054.0  464.60  5060.4  466.00  5068.5  465.72  5074.9  466.42  5089.3  466.55
  5138.9  468.75  5153.3  468.39  5210.1  472.42  5287.8  475.21  5338.2  476.18
#Mann=4,-1,0
  4508.1    0.12       0  4582.3    0.16       0  4994.6    0.07       0
  5000.6    0.16       0
Bank Sta=4893.5,5008.9
Exp/Cntr=0.3,0.1

Type RM Length L Ch R = 1,9632,438,438,438
BEGIN DESCRIPTION:
UNT 042 in LFCCL Watershed 9.0
END DESCRIPTION:
XS GIS Cut Line= 3
      2786625.00      7049574.98      2786575.00      7049225.00
      2786375.00      7048974.99
#Sta/Elev= 30
  4685.9  471.40  4786.9  466.82  4807.1  466.36  4827.3  465.45  4857.6  464.93
  4867.7  464.15  4929.4  462.04  4938.4  461.42  4958.6  460.74  4969.6  459.59
  4988.9  455.80  4996.0  453.78  4996.5  452.98  5001.5  452.98  5002.0  453.78
  5009.1  457.37  5042.6  457.46  5046.6  457.11  5053.0  458.39  5108.6  459.59
  5145.9  461.90  5153.9  461.69  5167.5  462.13  5203.5  463.96  5282.0  469.10
  5331.6  471.45  5338.0  471.35  5352.4  471.84  5356.4  472.40  5359.6  472.40
#Mann=4,-1,0
  4685.9    0.12       0  4929.4    0.16       0  4996.0    0.07       0
  5002.0    0.16       0
Bank Sta=4969.6,5108.6
Exp/Cntr=0.3,0.1

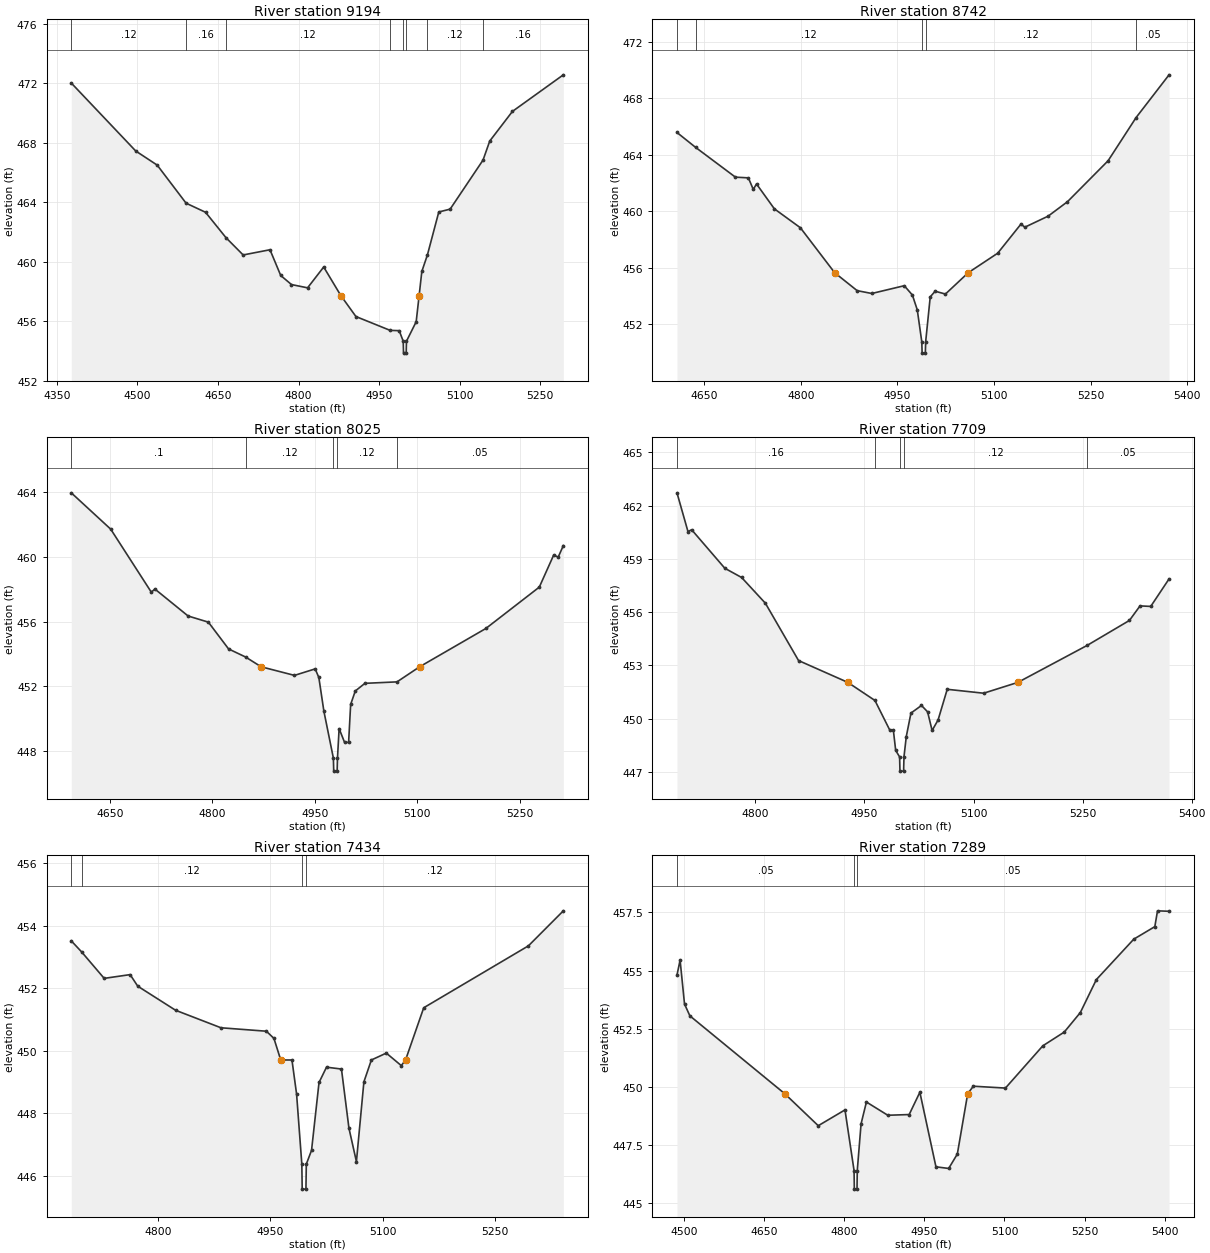
Type RM Length L Ch R = 1,9194,452,452,452
BEGIN DESCRIPTION:
UNT 042 in LFCCL Watershed 8.0
END DESCRIPTION:
XS GIS Cut Line= 3
      2786825.00      7049575.02      2786825.00      7048975.00
      2786525.04      7048875.01
#Sta/Elev= 30
  4376.7  472.01  4496.7  467.44  4536.7  466.49  4590.5  463.93  4626.7  463.32
  4664.8  461.61  4696.7  460.45  4746.7  460.80  4766.7  459.07  4786.7  458.46
  4816.7  458.24  4846.7  459.64  4878.6  457.72  4906.7  456.31  4970.4  455.38
  4987.3  455.36  4994.8  454.65  4995.3  453.85  5000.3  453.85  5000.8  454.65
  5018.9  455.96  5024.4  457.72  5029.4  459.34  5039.8  460.45  5061.0  463.34
  5082.1  463.53  5143.4  466.83  5155.9  468.11  5198.1  470.10  5292.9  472.56
#Mann=8,-1,0
  4376.7    0.12       0  4590.5    0.16       0  4664.8    0.12       0
  4970.4    0.16       0  4994.8    0.07       0  5000.8    0.16       0
  5039.8    0.12       0  5143.4    0.16       0
Bank Sta=4878.6,5024.4
Exp/Cntr=0.3,0.1

Type RM Length L Ch R = 1,8742,717,717,717
BEGIN DESCRIPTION:
UNT 042 in LFCCL Watershed 7.0
END DESCRIPTION:
XS GIS Cut Line= 3
      2787125.00      7049274.97      2787175.00      7048875.00
      2786875.03      7048675.02
#Sta/Elev= 30
  4608.0  465.58  4637.1  464.52  4698.7  462.42  4718.8  462.37  4726.4  461.55
  4731.4  461.94  4759.1  460.18  4799.5  458.84  4852.7  455.66  4887.6  454.39
  4910.3  454.19  4960.7  454.74  4973.3  454.08  4980.9  453.03  4987.9  450.77
  4988.4  449.97  4993.4  449.97  4993.9  450.77  5001.0  453.95  5008.6  454.35
  5024.6  454.15  5060.0  455.66  5105.7  457.04  5141.8  459.10  5147.8  458.88
  5183.9  459.66  5213.9  460.68  5277.0  463.58  5320.5  466.64  5371.6  469.66
#Mann=5,-1,0
  4608.0    0.16       0  4637.1    0.12       0  4987.9    0.07       0
  4993.9    0.12       0  5320.5    0.05       0
Bank Sta=4852.7,5060
Exp/Cntr=0.3,0.1

Type RM Length L Ch R = 1,8025,316,316,316
BEGIN DESCRIPTION:
XS3218A
END DESCRIPTION:
XS GIS Cut Line= 3
      2787653.38      7049138.75      2787504.08      7048763.78
      2787290.43      7048529.46
#Sta/Elev= 30
  4593.2  463.93  4651.0  461.69  4710.4  457.81  4715.7  458.00  4764.3  456.34
  4794.0  455.96  4823.6  454.31  4848.6  453.81  4871.3  453.21  4920.1  452.68
  4950.4  453.08  4955.8  452.55  4963.2  450.47  4977.1  447.58  4977.6  446.78
  4982.6  446.78  4983.1  447.58  4985.5  449.40  4993.5  448.55  4999.4  448.55
  5002.4  450.89  5009.2  451.72  5023.3  452.19  5070.3  452.28  5103.4  453.21
  5200.4  455.57  5278.7  458.12  5299.7  460.09  5306.4  459.97  5313.9  460.68
#Mann=5,-1,0
  4593.2     0.1       0  4848.6    0.12       0  4977.1    0.07       0
  4983.1    0.12       0  5070.3    0.05       0
Bank Sta=4871.3,5103.4
Exp/Cntr=0.3,0.1

Type RM Length L Ch R = 1,7709,275,275,275
BEGIN DESCRIPTION:
XS3219A
END DESCRIPTION:
XS GIS Cut Line= 3
      2787823.53      7048972.14      2787764.50      7048680.45
      2787459.49      7048455.15
#Sta/Elev= 30
  4692.1  462.72  4707.2  460.54  4712.3  460.64  4757.9  458.47  4781.0  457.95
  4813.7  456.50  4859.3  453.27  4927.1  452.04  4964.4  451.02  4984.8  449.35
  4989.7  449.35  4992.9  448.21  4998.3  447.84  4998.8  447.04  5003.8  447.04
  5004.3  447.84  5007.5  448.99  5013.9  450.31  5028.4  450.74  5036.8  450.38
  5043.0  449.33  5051.2  449.92  5063.8  451.65  5113.9  451.43  5161.0  452.04
  5256.1  454.12  5314.4  455.53  5329.0  456.35  5343.7  456.32  5368.9  457.87
#Mann=5,-1,0
  4692.1    0.16       0  4964.4    0.12       0  4998.3    0.07       0
  5004.3    0.12       0  5256.1    0.05       0
Bank Sta=4927.1,5161
Exp/Cntr=0.3,0.1

Type RM Length L Ch R = 1,7434,145,145,145
BEGIN DESCRIPTION:
XS3220A
END DESCRIPTION:
XS GIS Cut Line= 3
      2788222.81      7048506.83      2787931.17      7048461.70
      2787568.30      7048465.15
#Sta/Elev= 30
  4683.8  453.52  4697.5  453.17  4727.8  452.32  4762.5  452.44  4772.7  452.07
  4823.3  451.30  4884.0  450.74  4944.7  450.63  4954.8  450.40  4963.9  449.71
  4978.9  449.71  4985.1  448.62  4992.1  446.38  4992.6  445.58  4997.6  445.58
  4998.1  446.38  5005.1  446.82  5015.1  448.99  5025.1  449.48  5045.1  449.42
  5055.1  447.53  5065.1  446.46  5075.1  449.01  5085.1  449.71  5105.1  449.93
  5125.1  449.53  5130.8  449.71  5155.1  451.38  5295.1  453.36  5341.8  454.48
#Mann=4,-1,0
  4683.8    0.05       0  4697.5    0.12       0  4992.1    0.07       0
  4998.1    0.12       0
Bank Sta=4963.9,5130.8
Exp/Cntr=0.3,0.1

Type RM Length L Ch R = 1,7289,23,23,23
BEGIN DESCRIPTION:
XS3221A
END DESCRIPTION:
XS GIS Cut Line= 3
      2788439.09      7048360.10      2787931.17      7048340.17
      2787519.01      7048350.56
#Sta/Elev= 30
  4487.3  454.80  4493.1  455.45  4501.4  453.56  4511.4  453.05  4688.8  449.70
  4751.6  448.32  4801.6  449.00  4818.6  446.39  4819.1  445.59  4824.1  445.59
  4824.6  446.39  4831.7  448.40  4841.7  449.34  4881.7  448.77  4921.7  448.80
  4941.7  449.76  4971.8  446.55  4995.6  446.48  5011.8  447.10  5031.2  449.70
  5041.8  450.02  5101.8  449.94  5171.8  451.76  5211.8  452.35  5241.9  453.19
  5271.9  454.61  5341.9  456.35  5381.3  456.89  5386.3  457.57  5407.9  457.55
#Mann=3,-1,0
  4487.3    0.05       0  4818.6    0.04       0  4824.6    0.05       0
Bank Sta=4688.8,5031.2
Exp/Cntr=0.3,0.1

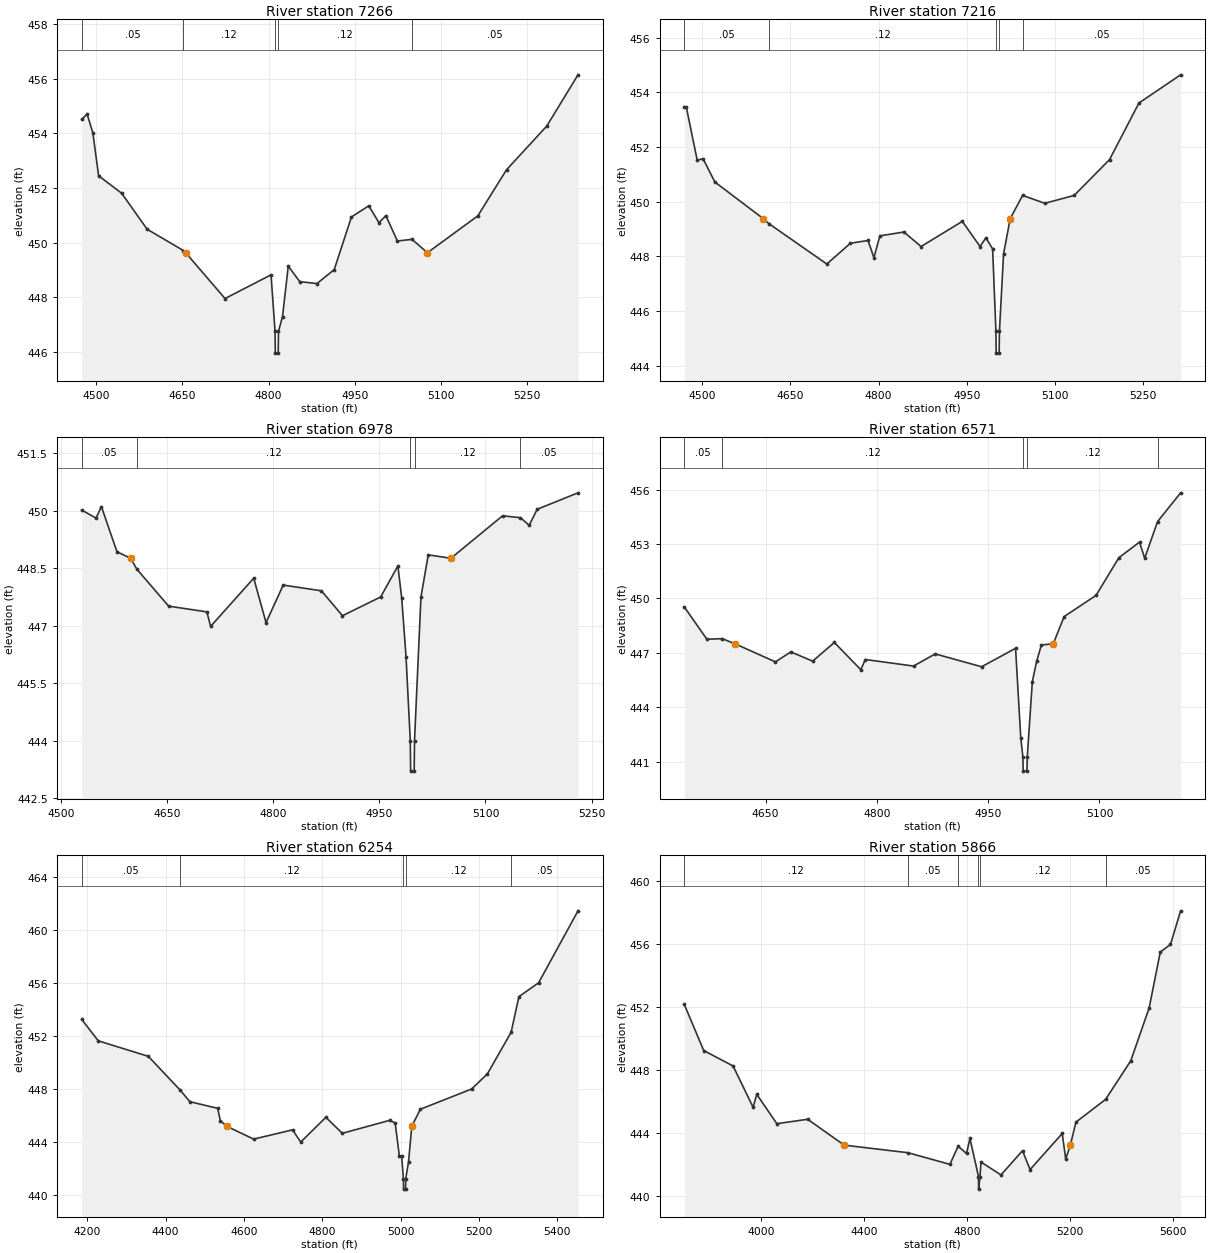
Type RM Length L Ch R = 1,7266,50,50,50
BEGIN DESCRIPTION:
XS3222A
END DESCRIPTION:
XS GIS Cut Line= 3
      2788444.44      7048332.97      2787924.22      7048319.34
      2787580.52      7048319.34
#Sta/Elev= 30
  4474.6  454.52  4484.0  454.71  4494.0  454.02  4504.0  452.45  4544.1  451.81
  4588.5  450.49  4651.6  449.71  4655.6  449.63  4724.1  447.95  4804.2  448.82
  4811.2  446.75  4811.7  445.95  4816.7  445.95  4817.2  446.75  4824.2  447.29
  4834.2  449.14  4854.2  448.57  4884.2  448.50  4914.2  449.01  4944.2  450.94
  4974.4  451.35  4992.1  450.73  5004.2  450.99  5024.2  450.06  5049.7  450.12
  5076.5  449.63  5164.2  450.98  5214.2  452.67  5284.2  454.27  5338.7  456.15
#Mann=5,-1,0
  4474.6    0.05       0  4651.6    0.12       0  4811.2    0.07       0
  4817.2    0.12       0  5049.7    0.05       0
Bank Sta=4655.6,5076.5
Exp/Cntr=0.3,0.1

Type RM Length L Ch R = 1,7216,238,238,238
BEGIN DESCRIPTION:
XS3223A
END DESCRIPTION:
XS GIS Cut Line= 3
      2788436.84      7048302.58      2787917.28      7048270.73
      2787594.31      7048284.62
#Sta/Elev= 30
  4469.8  453.46  4473.2  453.46  4491.7  451.52  4501.7  451.57  4521.7  450.72
  4604.0  449.38  4614.0  449.19  4712.1  447.72  4752.2  448.48  4782.2  448.58
  4792.2  447.95  4802.3  448.75  4843.1  448.89  4872.4  448.36  4942.5  449.28
  4972.6  448.36  4982.6  448.68  4994.0  448.27  4999.6  445.26  5000.1  444.46
  5005.1  444.46  5005.6  445.26  5012.6  448.09  5023.9  449.38  5045.0  450.23
  5082.7  449.94  5132.7  450.23  5192.8  451.54  5242.8  453.61  5313.6  454.64
#Mann=5,-1,0
  4469.8    0.05       0  4614.0    0.12       0  4999.6    0.07       0
  5005.6    0.12       0  5045.0    0.05       0
Bank Sta=4604,5023.9
Exp/Cntr=0.3,0.1

Type RM Length L Ch R = 1,6978,407,407,407
BEGIN DESCRIPTION:
XS3224A
END DESCRIPTION:
XS GIS Cut Line= 3
      2788420.84      7048246.61      2787983.25      7048072.81
      2787758.79      7048124.61
#Sta/Elev= 30
  4529.6  450.02  4549.8  449.81  4557.4  450.11  4579.4  448.93  4598.8  448.76
  4607.3  448.48  4652.4  447.51  4706.4  447.36  4711.7  446.98  4772.6  448.24
  4790.0  447.08  4814.3  448.06  4868.3  447.91  4898.0  447.26  4952.0  447.75
  4976.3  448.56  4981.7  447.72  4987.8  446.19  4993.8  444.00  4994.3  443.20
  4999.3  443.20  4999.8  444.00  5008.9  447.75  5019.2  448.85  5051.2  448.76
  5124.2  449.87  5149.5  449.82  5161.8  449.62  5173.1  450.04  5230.8  450.47
#Mann=5,-1,0
  4529.6    0.05       0  4607.3    0.12       0  4993.8    0.07       0
  4999.8    0.12       0  5149.5    0.05       0
Bank Sta=4598.8,5051.2
Exp/Cntr=0.3,0.1

Type RM Length L Ch R = 1,6571,317,317,317
BEGIN DESCRIPTION:
XS3225A
END DESCRIPTION:
XS GIS Cut Line= 3
      2788451.99      7048159.61      2788219.36      7047840.17
      2787983.25      7047701.28
#Sta/Elev= 30
  4540.3  449.53  4570.7  447.75  4591.5  447.78  4608.5  447.50  4663.1  446.50
  4683.9  447.05  4713.3  446.54  4742.6  447.57  4778.2  446.07  4784.4  446.63
  4849.3  446.27  4878.6  446.94  4941.1  446.23  4986.9  447.25  4993.9  442.31
  4996.7  441.27  4997.2  440.47  5002.2  440.47  5002.7  441.27  5009.5  445.41
  5015.3  446.53  5021.7  447.43  5037.7  447.50  5052.4  449.00  5095.4  450.17
  5126.2  452.25  5154.0  453.11  5161.0  452.22  5178.3  454.24  5209.4  455.83
#Mann=5,-1,0
  4540.3    0.05       0  4591.5    0.12       0  4996.7    0.07       0
  5002.7    0.12       0  5178.3    0.05       0
Bank Sta=4608.5,5037.7
Exp/Cntr=0.3,0.1

Type RM Length L Ch R = 1,6254,388,388,388
BEGIN DESCRIPTION:
UNT 042 in LFCCL Watershed 2.0
END DESCRIPTION:
XS GIS Cut Line= 3
      2788925.02      7048125.02      2788325.00      7047575.00
      2787875.04      7047625.00
#Sta/Elev= 30
  4185.9  453.27  4228.2  451.65  4355.8  450.48  4437.0  447.93  4461.9  447.05
  4532.8  446.55  4539.6  445.62  4555.5  445.20  4624.7  444.22  4723.9  444.92
  4744.9  444.00  4809.0  445.87  4851.0  444.66  4971.8  445.64  4986.0  445.44
  4996.5  442.96  5002.4  442.96  5006.9  441.24  5007.4  440.44  5012.4  440.44
  5012.9  441.24  5020.0  442.50  5028.4  445.20  5050.2  446.48  5181.0  448.01
  5221.2  449.15  5281.9  452.30  5301.7  454.99  5352.0  456.04  5452.6  461.48
#Mann=5,-1,0
  4185.9    0.05       0  4437.0    0.12       0  5006.9    0.07       0
  5012.9    0.12       0  5281.9    0.05       0
Bank Sta=4555.5,5028.4
Exp/Cntr=0.3,0.1

Type RM Length L Ch R = 1,5866,532,532,532
BEGIN DESCRIPTION:
Mapping XS 2d5c3415
END DESCRIPTION:
XS GIS Cut Line= 3
      2789319.95      7048016.71      2788361.65      7047199.03
      2787741.87      7047454.23
#Sta/Elev= 30
  3701.1  452.17  3776.5  449.25  3890.7  448.27  3968.6  445.65  3982.9  446.47
  4060.9  444.61  4180.8  444.89  4322.8  443.25  4570.8  442.77  4733.9  442.03
  4765.9  443.18  4798.7  442.72  4811.8  443.68  4845.1  441.26  4845.6  440.46
  4851.1  441.26  4854.7  442.18  4932.6  441.36  5016.3  442.90  5045.7  441.70
  5170.8  443.99  5184.3  442.37  5202.4  443.25  5224.1  444.71  5339.3  446.15
  5437.3  448.60  5508.8  451.95  5552.0  455.49  5591.8  455.98  5631.1  458.11
#Mann=6,-1,0
  3701.1    0.12       0  4570.8    0.05       0  4765.9    0.12       0
  4845.1    0.07       0  4851.1    0.12       0  5339.3    0.05       0
Bank Sta=4322.8,5202.4
Exp/Cntr=0.3,0.1

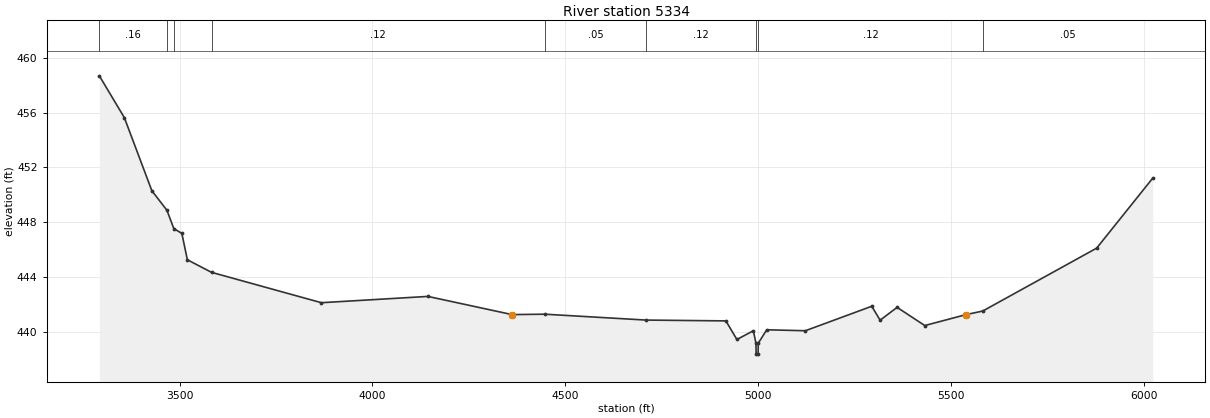
Type RM Length L Ch R = 1,5334,0,0,0
BEGIN DESCRIPTION:
UNT 042 in LFCCL Watershed 1.0
END DESCRIPTION:
XS GIS Cut Line= 3
      2789580.41      7048011.54      2788455.94      7046725.78
      2787611.61      7047303.22
#Sta/Elev= 30
  3291.9  458.70  3356.8  455.64  3428.0  450.30  3467.1  448.87  3485.0  447.53
  3505.8  447.18  3520.1  445.25  3582.8  444.33  3867.5  442.11  4143.7  442.57
  4362.0  441.24  4446.6  441.27  4709.4  440.84  4916.3  440.78  4944.8  439.42
  4987.5  440.06  4994.2  439.15  4994.7  438.35  4999.7  438.35  5000.2  439.15
  5022.2  440.13  5122.3  440.06  5294.4  441.85  5316.1  440.83  5360.1  441.77
  5431.9  440.44  5538.9  441.24  5582.1  441.50  5877.5  446.10  6022.9  451.22
#Mann=9,-1,0
  3291.9    0.16       0  3467.1    0.12       0  3485.0    0.16       0
  3582.8    0.12       0  4446.6    0.05       0  4709.4    0.12       0
  4994.2    0.07       0  5000.2    0.12       0  5582.1    0.05       0
Bank Sta=4362,5538.9
Exp/Cntr=0.3,0.1

Chan Stop Cuts=-1