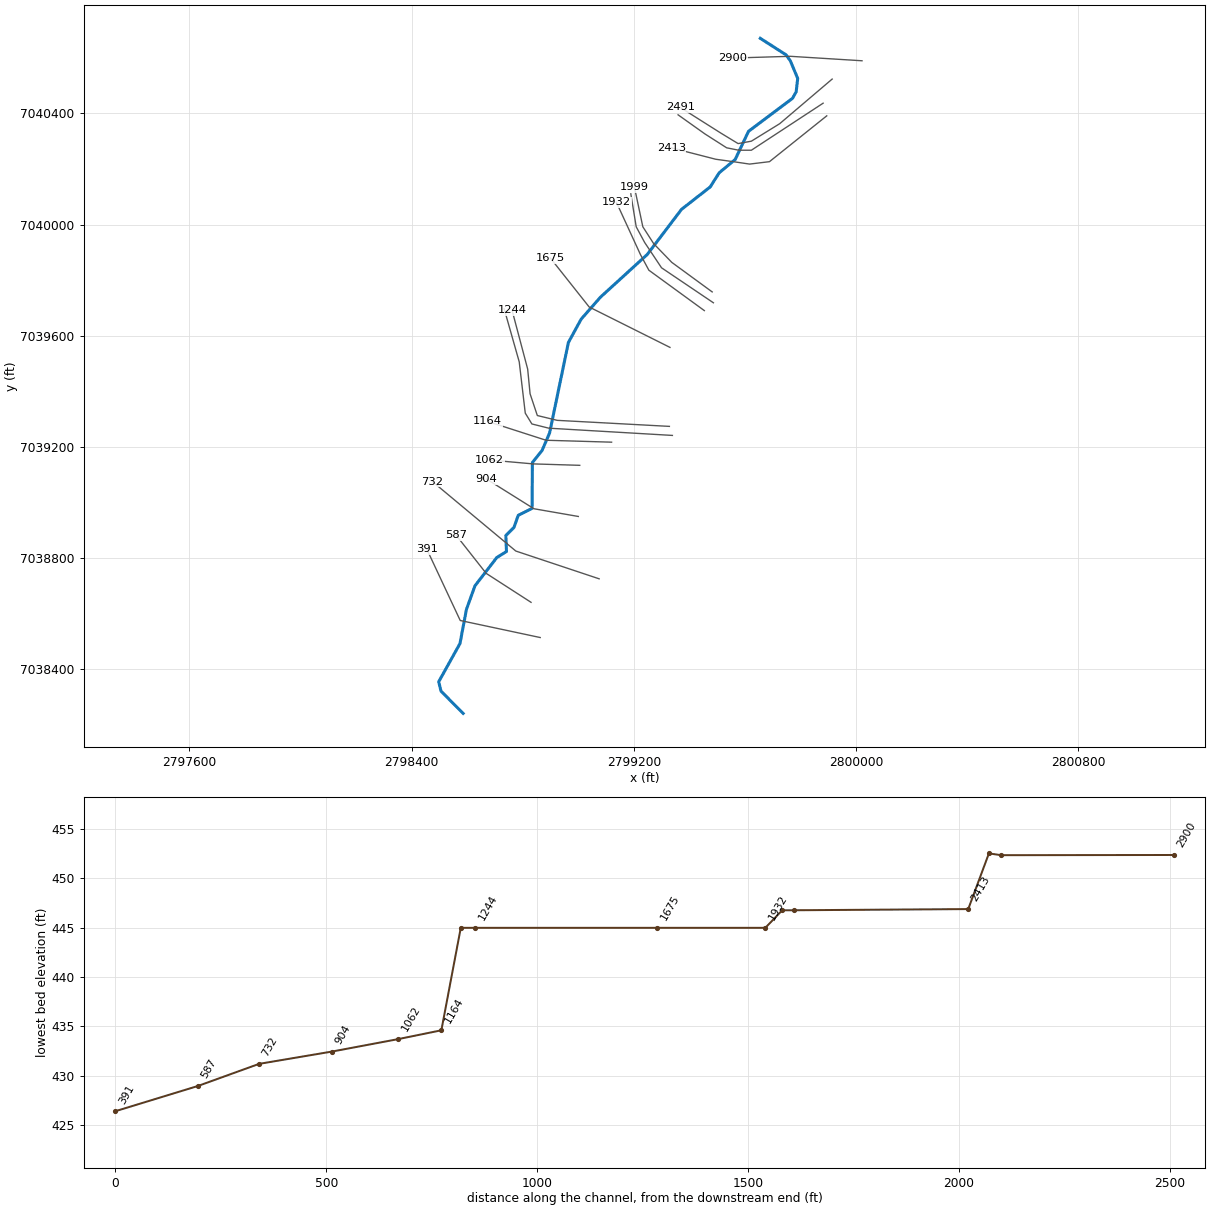
--- UNT 046 in LFCCL Watershed.prj (project) ---

Proj Title=UNT 046 in LFCCL Watershed Base Level Engineering
Current Plan=p01
Default Exp/Contr=0.3,0.1
English Units
Geom File=g01
Flow File=f01
Plan File=p01
BEGIN DESCRIPTION:
UNT 046 in LFCCL Watershed
END DESCRIPTION:

--- UNT 046 in LFCCL Watershed.p01 (plan) ---

Plan Title=Multiple Run
Short Identifier=Multiple
Geom File=g01
Flow File=f01
Subcritical Flow
K Sum by GR= 0
Std Step Tol= 0.01
Critical Tol= 0.01
Num of Std Step Trials= 20
Max Error Tol= 0.3
Flow Tol Ratio= 0.001
Split Flow NTrial= 30
Split Flow Tol= 0.02
Split Flow Ratio= 0.02
Log Output Level= 0
Friction Slope Method= 1
Unsteady Friction Slope Method= 2
Unsteady Bridges Friction Slope Method= 1
Parabolic Critical Depth
Global Vel Dist=  1 , 1 , 1
Global Log Level= 0
CheckData=True
Encroach Param= -1, 0, 0, 0
BEGIN DESCRIPTION:
Multiple Run
END DESCRIPTION:

--- UNT 046 in LFCCL Watershed.f01 (steady flow) ---

Flow Title=Multiple
Number of Profiles=7
Profile Names=10-year,25-year,50-year,1pct_min,100-year,1pct_plu,500-year
River Rch & RM= UNT 046 in LFCCL,Reach-1,2900
     106     125     139      77     154     307     188
Boundary for River Rch & Prof#=UNT 046 in LFCCL,Reach-1,1
Up Type=0
Dn Type=3
Dn Slope=0.005
Boundary for River Rch & Prof#=UNT 046 in LFCCL,Reach-1,2
Up Type=0
Dn Type=3
Dn Slope=0.005
Boundary for River Rch & Prof#=UNT 046 in LFCCL,Reach-1,3
Up Type=0
Dn Type=3
Dn Slope=0.005
Boundary for River Rch & Prof#=UNT 046 in LFCCL,Reach-1,4
Up Type=0
Dn Type=3
Dn Slope=0.005
Boundary for River Rch & Prof#=UNT 046 in LFCCL,Reach-1,5
Up Type=0
Dn Type=3
Dn Slope=0.005
Boundary for River Rch & Prof#=UNT 046 in LFCCL,Reach-1,6
Up Type=0
Dn Type=3
Dn Slope=0.005
Boundary for River Rch & Prof#=UNT 046 in LFCCL,Reach-1,7
Up Type=0
Dn Type=3
Dn Slope=0.005

--- UNT 046 in LFCCL Watershed.g01 (geometry) ---

Geom Title=Existing Conditions

River Reach=UNT 046 in LFCCL,Reach-1
Reach XY= 30
      2799655.00      7040670.23      2799747.95      7040610.57
      2799763.23      7040589.04      2799789.62      7040525.84
      2799784.07      7040477.93      2799770.87      7040454.32
      2799612.54      7040335.57      2799564.62      7040234.18
      2799506.98      7040186.26      2799474.69      7040135.39
      2799371.39      7040054.66      2799248.13      7039892.34
      2799079.73      7039738.69      2799010.28      7039659.70
      2798964.27      7039575.50      2798896.57      7039249.76
      2798869.44      7039186.82      2798834.72      7039143.42
      2798833.63      7038978.49      2798783.72      7038953.53
      2798768.53      7038910.13      2798739.23      7038880.83
      2798741.40      7038823.33      2798706.68      7038801.62
      2798627.99      7038699.80      2798597.36      7038614.97
      2798574.17      7038492.20      2798497.57      7038354.64
      2798505.77      7038320.64      2798585.59      7038240.71

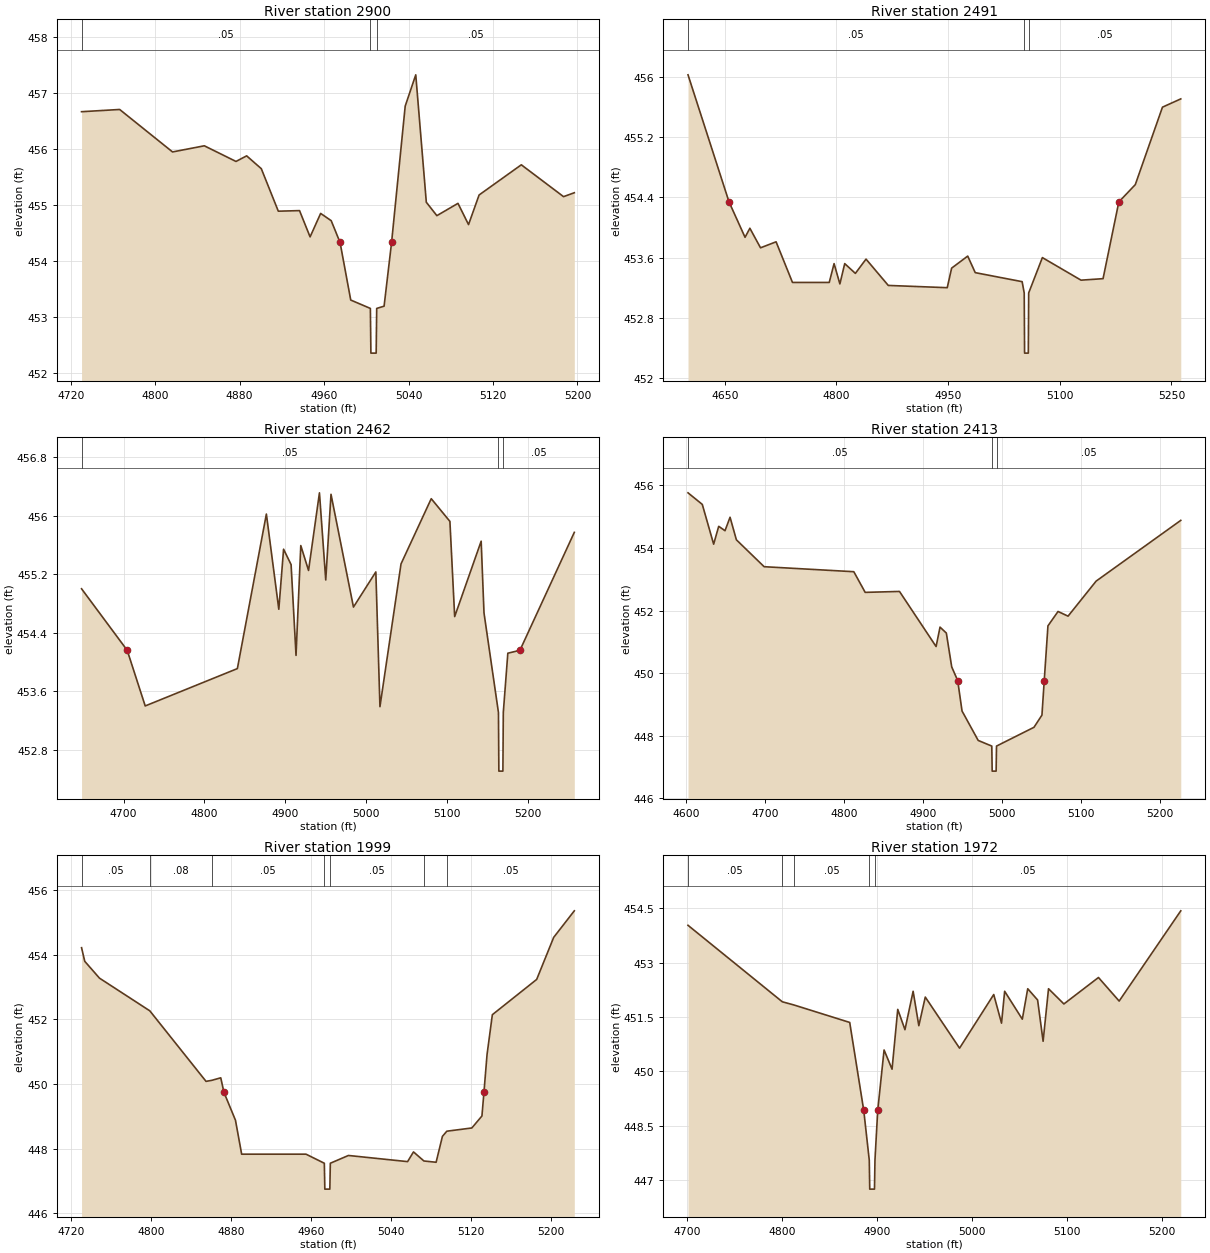
Type RM Length L Ch R = 1,2900,409,409,409
BEGIN DESCRIPTION:
UNT 046 in LFCCL Watershed 3.0
END DESCRIPTION:
XS GIS Cut Line= 3
      2800021.06      7040589.51      2799763.05      7040605.55
      2799554.85      7040599.24
#Sta/Elev= 30
  4730.2  456.67  4766.3  456.71  4816.4  455.95  4846.5  456.06  4876.5  455.78
  4886.6  455.88  4900.5  455.65  4916.6  454.89  4936.7  454.90  4946.7  454.43
  4956.7  454.85  4966.7  454.72  4975.1  454.33  4985.2  453.30  5003.8  453.15
  5004.3  452.35  5009.3  452.35  5009.8  453.15  5016.8  453.19  5023.9  454.33
  5036.8  456.77  5046.8  457.33  5056.8  455.05  5066.8  454.81  5086.8  455.03
  5096.8  454.65  5106.8  455.18  5146.8  455.72  5186.8  455.15  5197.0  455.22
#Mann=3,-1,0
  4730.2    0.05       0  5003.8    0.03       0  5009.8    0.05       0
Bank Sta=4975.1,5023.9
Exp/Cntr=0.3,0.1

Type RM Length L Ch R = 1,2491,29,29,29
BEGIN DESCRIPTION:
XS3227A
END DESCRIPTION:
XS GIS Cut Line= 6
      2799913.63      7040523.62      2799724.85      7040363.05
      2799622.86      7040300.11      2799575.11      7040291.43
      2799514.35      7040328.32      2799366.77      7040421.64
#Sta/Elev= 30
  4600.6  456.03  4655.7  454.34  4677.2  453.87  4683.7  453.99  4698.0  453.73
  4718.9  453.81  4740.9  453.27  4790.3  453.27  4796.8  453.52  4804.6  453.25
  4811.1  453.52  4825.4  453.39  4839.7  453.58  4869.6  453.23  4948.8  453.20
  4954.7  453.46  4976.3  453.62  4986.4  453.40  5049.4  453.28  5052.2  453.13
  5052.7  452.33  5057.7  452.33  5058.2  453.13  5076.6  453.60  5128.5  453.30
  5158.1  453.32  5179.3  454.34  5201.4  454.57  5237.9  455.60  5262.5  455.71
#Mann=3,-1,0
  4600.6    0.05       0  5052.2    0.03       0  5058.2    0.05       0
Bank Sta=4655.7,5179.3
Exp/Cntr=0.3,0.1

Type RM Length L Ch R = 1,2462,49,49,49
BEGIN DESCRIPTION:
XS3226A
END DESCRIPTION:
XS GIS Cut Line= 6
      2799881.07      7040436.81      2799622.86      7040267.56
      2799577.28      7040267.56      2799533.88      7040276.24
      2799455.75      7040326.15      2799359.05      7040394.92
#Sta/Elev= 30
  4647.9  455.00  4704.4  454.16  4726.7  453.40  4840.8  453.91  4876.7  456.02
  4892.1  454.72  4898.0  455.54  4907.3  455.33  4913.4  454.09  4919.3  455.59
  4928.9  455.25  4942.4  456.31  4950.2  455.12  4956.7  456.29  4984.5  454.75
  5012.2  455.23  5017.3  453.39  5043.4  455.34  5080.8  456.23  5103.9  455.92
  5109.8  454.62  5142.6  455.65  5146.1  454.67  5164.0  453.31  5164.5  452.51
  5169.5  452.51  5170.0  453.31  5175.6  454.12  5190.6  454.16  5257.9  455.77
#Mann=3,-1,0
  4647.9    0.05       0  5164.0    0.03       0  5170.0    0.05       0
Bank Sta=4704.4,5190.6
Exp/Cntr=0.3,0.1

Type RM Length L Ch R = 1,2413,414,414,414
BEGIN DESCRIPTION:
XS3228A
END DESCRIPTION:
XS GIS Cut Line= 6
      2799894.14      7040391.27      2799687.96      7040226.33
      2799616.34      7040217.65      2799557.75      7040226.33
      2799494.82      7040235.01      2799334.27      7040276.23
#Sta/Elev= 30
  4602.0  455.76  4620.1  455.39  4634.5  454.12  4640.9  454.69  4648.9  454.55
  4655.3  454.98  4663.3  454.26  4698.5  453.40  4812.2  453.24  4826.6  452.58
  4870.1  452.61  4916.5  450.85  4921.5  451.47  4929.5  451.28  4936.3  450.20
  4943.9  449.76  4949.4  448.79  4969.9  447.85  4987.1  447.67  4987.6  446.87
  4992.6  446.87  4993.1  447.67  5040.6  448.27  5050.7  448.66  5053.6  449.76
  5058.3  451.51  5071.1  451.97  5083.8  451.82  5119.4  452.94  5226.7  454.88
#Mann=3,-1,0
  4602.0    0.05       0  4987.1    0.03       0  4993.1    0.05       0
Bank Sta=4943.9,5053.6
Exp/Cntr=0.3,0.1

Type RM Length L Ch R = 1,1999,27,27,27
BEGIN DESCRIPTION:
XS3229A
END DESCRIPTION:
XS GIS Cut Line= 5
      2799481.82      7039757.56      2799336.40      7039863.91
      2799271.29      7039931.19      2799232.23      7039991.95
      2799201.86      7040135.14
#Sta/Elev= 30
  4730.9  454.21  4734.1  453.79  4748.8  453.27  4799.1  452.26  4855.3  450.08
  4860.8  450.11  4870.0  450.19  4873.2  449.74  4884.7  448.88  4890.9  447.83
  4955.2  447.83  4973.5  447.55  4974.0  446.75  4979.0  446.75  4979.5  447.55
  4997.6  447.79  5056.7  447.60  5062.6  447.90  5073.0  447.62  5085.2  447.58
  5091.5  448.38  5095.9  448.54  5120.9  448.64  5131.0  449.01  5133.0  449.74
  5136.1  450.91  5141.4  452.14  5185.7  453.23  5202.7  454.53  5223.3  455.35
#Mann=7,-1,0
  4730.9    0.05       0  4799.1    0.08       0  4860.8    0.05       0
  4973.5    0.03       0  4979.5    0.05       0  5073.0    0.16       0
  5095.9    0.05       0
Bank Sta=4873.2,5133
Exp/Cntr=0.3,0.1

Type RM Length L Ch R = 1,1972,40,40,40
BEGIN DESCRIPTION:
XS3230A
END DESCRIPTION:
XS GIS Cut Line= 5
      2799486.16      7039718.50      2799299.50      7039844.38
      2799238.74      7039935.53      2799208.36      7039991.95
      2799188.94      7040110.61
#Sta/Elev= 30
  4700.7  454.03  4800.0  451.92  4812.5  451.83  4871.0  451.35  4885.8  448.92
  4891.6  447.55  4892.1  446.75  4897.1  446.75  4897.6  447.55  4900.5  448.92
  4907.2  450.59  4915.6  450.06  4921.6  451.71  4929.2  451.15  4937.8  452.21
  4943.8  451.26  4950.6  452.05  4986.7  450.64  5022.7  452.12  5030.9  451.33
  5034.2  452.21  5052.8  451.44  5058.5  452.28  5068.9  451.97  5074.7  450.83
  5080.4  452.28  5096.6  451.86  5133.0  452.59  5154.8  451.94  5219.7  454.43
#Mann=5,-1,0
  4700.7    0.05       0  4800.0    0.08       0  4812.5    0.05       0
  4891.6    0.03       0  4897.6    0.05       0
Bank Sta=4885.8,4900.5
Exp/Cntr=0.3,0.1

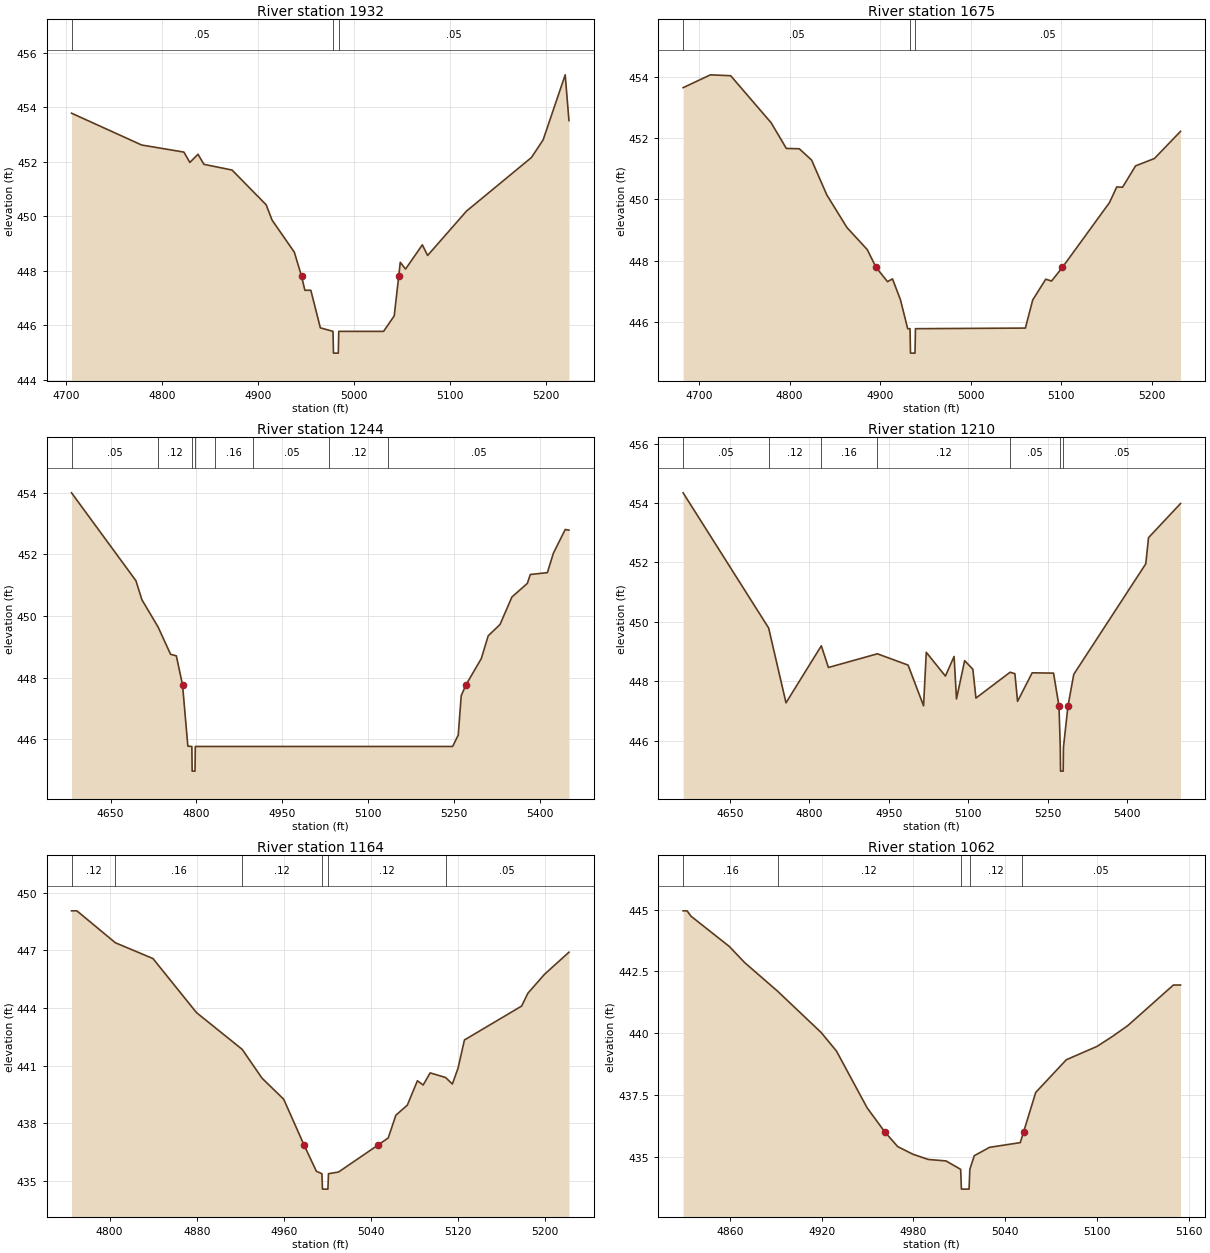
Type RM Length L Ch R = 1,1932,257,257,257
BEGIN DESCRIPTION:
XS3231A
END DESCRIPTION:
XS GIS Cut Line= 4
      2799453.59      7039690.30      2799253.93      7039835.70
      2799223.55      7039892.13      2799136.94      7040080.49
#Sta/Elev= 30
  4706.0  453.79  4779.1  452.62  4823.1  452.36  4829.3  451.98  4837.8  452.28
  4844.0  451.91  4873.3  451.70  4908.9  450.42  4915.0  449.86  4938.2  448.68
  4945.7  447.80  4949.2  447.28  4955.4  447.28  4965.3  445.90  4978.5  445.77
  4979.0  444.97  4984.0  444.97  4984.5  445.77  5031.2  445.77  5042.3  446.34
  5047.0  447.80  5048.6  448.31  5054.1  448.06  5071.6  448.95  5077.1  448.56
  5117.6  450.19  5185.3  452.16  5197.5  452.81  5220.5  455.20  5224.4  453.52
#Mann=3,-1,0
  4706.0    0.05       0  4978.5    0.03       0  4984.5    0.05       0
Bank Sta=4945.7,5047
Exp/Cntr=0.3,0.1

Type RM Length L Ch R = 1,1675,431,431,431
BEGIN DESCRIPTION:
XS3234A
END DESCRIPTION:
XS GIS Cut Line= 3
      2799329.88      7039557.93      2799039.09      7039703.32
      2798899.51      7039879.40
#Sta/Elev= 30
  4682.3  453.66  4712.5  454.08  4734.9  454.05  4779.6  452.51  4796.4  451.67
  4810.7  451.66  4824.3  451.29  4841.1  450.15  4863.4  449.08  4885.8  448.36
  4895.5  447.78  4908.2  447.31  4913.7  447.40  4922.5  446.72  4930.5  445.77
  4933.1  445.77  4933.6  444.97  4938.6  444.97  4939.1  445.77  5060.6  445.79
  5068.7  446.71  5083.1  447.39  5089.5  447.33  5101.6  447.78  5153.6  449.90
  5161.6  450.41  5168.0  450.40  5182.4  451.10  5203.2  451.34  5232.1  452.23
#Mann=3,-1,0
  4682.3    0.05       0  4933.1   0.033       0  4939.1    0.05       0
Bank Sta=4895.5,5101.6
Exp/Cntr=0.3,0.1

Type RM Length L Ch R = 1,1244,34,34,34
BEGIN DESCRIPTION:
XS3232A
END DESCRIPTION:
XS GIS Cut Line= 6
      2799327.77      7039273.63      2798924.07      7039295.34
      2798852.46      7039312.70      2798826.41      7039390.82
      2798817.73      7039479.80      2798761.63      7039691.27
#Sta/Elev= 30
  4581.9  454.00  4694.3  451.15  4704.8  450.53  4732.9  449.65  4754.9  448.76
  4764.9  448.71  4775.7  447.77  4785.0  445.78  4792.0  445.77  4792.5  444.97
  4797.5  444.97  4798.0  445.77  4832.2  445.77  4899.1  445.77  5032.2  445.77
  5135.3  445.77  5247.3  445.77  5257.1  446.14  5262.3  447.42  5270.6  447.77
  5297.3  448.62  5309.4  449.36  5330.1  449.73  5350.8  450.62  5377.7  451.06
  5382.9  451.35  5412.7  451.41  5423.2  452.04  5443.9  452.81  5450.4  452.79
#Mann=8,-1,0
  4581.9    0.05       0  4732.9    0.12       0  4792.0   0.033       0
  4798.0    0.12       0  4832.2    0.16       0  4899.1    0.05       0
  5032.2    0.12       0  5135.3    0.05       0
Bank Sta=4775.7,5270.6
Exp/Cntr=0.3,0.1

Type RM Length L Ch R = 1,1210,46,46,46
BEGIN DESCRIPTION:
XS3233A
END DESCRIPTION:
XS GIS Cut Line= 6
      2799338.61      7039241.08      2798893.69      7039267.13
      2798832.92      7039282.32      2798809.05      7039321.38
      2798787.35      7039505.84      2798733.10      7039696.80
#Sta/Elev= 30
  4562.1  454.34  4723.4  449.79  4756.2  447.27  4822.8  449.19  4836.2  448.46
  4928.6  448.92  4986.5  448.54  5015.7  447.17  5020.8  448.97  5056.9  448.17
  5073.3  448.83  5077.8  447.40  5093.2  448.69  5108.7  448.40  5114.5  447.43
  5179.0  448.30  5188.0  448.25  5193.0  447.32  5220.6  448.28  5260.9  448.27
  5271.2  447.16  5273.6  445.77  5274.1  444.97  5279.1  444.97  5279.6  445.77
  5288.1  447.16  5299.1  448.23  5434.9  451.95  5440.1  452.83  5500.5  453.98
#Mann=7,-1,0
  4562.1    0.05       0  4723.4    0.12       0  4822.8    0.16       0
  4928.6    0.12       0  5179.0    0.05       0  5273.6    0.07       0
  5279.6    0.05       0
Bank Sta=5271.2,5288.1
Exp/Cntr=0.3,0.1

Type RM Length L Ch R = 1,1164,102,102,102
BEGIN DESCRIPTION:
XS3235A
END DESCRIPTION:
XS GIS Cut Line= 3
      2799119.78      7039216.78      2798883.71      7039223.72
      2798673.62      7039291.44
#Sta/Elev= 30
  4765.0  449.05  4769.9  449.05  4805.3  447.39  4839.8  446.57  4879.8  443.76
  4921.8  441.85  4939.9  440.36  4959.9  439.26  4978.5  436.89  4989.9  435.52
  4995.0  435.39  4995.5  434.59  5000.5  434.59  5001.0  435.39  5010.3  435.48
  5046.8  436.89  5055.9  437.25  5062.9  438.43  5073.4  438.95  5082.7  440.22
  5088.0  440.00  5094.4  440.63  5108.6  440.39  5114.8  440.05  5120.0  440.87
  5125.9  442.34  5178.4  444.10  5184.2  444.77  5199.4  445.75  5221.9  446.90
#Mann=6,-1,0
  4765.0    0.12       0  4805.3    0.16       0  4921.8    0.12       0
  4995.0    0.07       0  5001.0    0.12       0  5108.6    0.05       0
Bank Sta=4978.5,5046.8
Exp/Cntr=0.3,0.1

Type RM Length L Ch R = 1,1062,158,158,158
BEGIN DESCRIPTION:
XS3238A
END DESCRIPTION:
XS GIS Cut Line= 3
      2799005.23      7039133.44      2798836.83      7039138.65
      2798680.62      7039152.54
#Sta/Elev= 30
  4829.4  444.95  4832.0  444.95  4834.6  444.73  4859.6  443.51  4869.6  442.86
  4891.2  441.70  4919.7  440.03  4929.7  439.28  4949.7  436.99  4961.2  436.02
  4969.7  435.42  4979.7  435.11  4989.7  434.90  5001.3  434.84  5010.9  434.50
  5011.4  433.70  5016.4  433.70  5016.9  434.50  5019.8  435.05  5029.8  435.39
  5049.9  435.58  5050.8  435.76  5052.1  436.02  5060.0  437.61  5080.0  438.93
  5100.1  439.47  5110.1  439.87  5120.2  440.31  5150.0  441.95  5154.7  441.95
#Mann=5,-1,0
  4829.4    0.16       0  4891.2    0.12       0  5010.9    0.07       0
  5016.9    0.12       0  5050.8    0.05       0
Bank Sta=4961.2,5052.1
Exp/Cntr=0.3,0.1

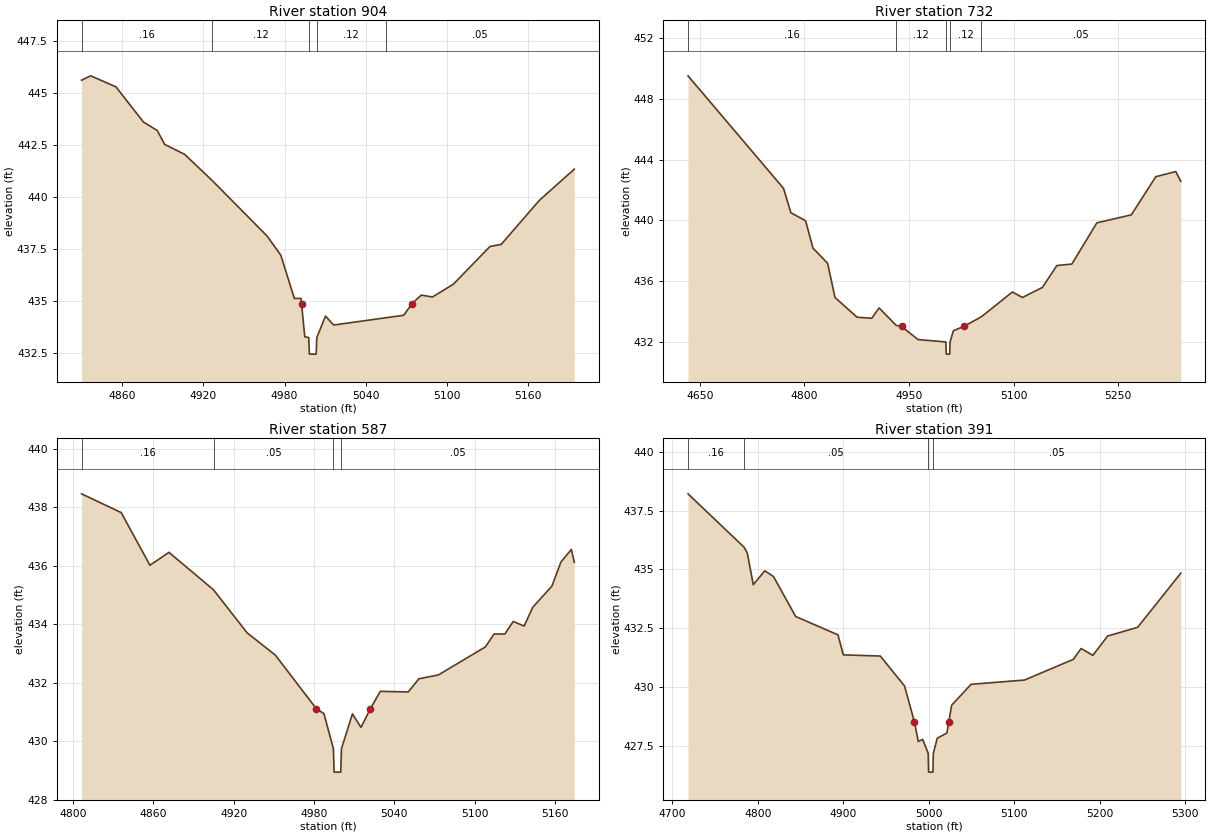
Type RM Length L Ch R = 1,904,172,172,172
BEGIN DESCRIPTION:
XS3237A
END DESCRIPTION:
XS GIS Cut Line= 3
      2799000.03      7038949.42      2798840.30      7038977.19
      2798669.21      7039084.34
#Sta/Elev= 30
  4830.0  445.61  4836.8  445.82  4855.4  445.29  4875.7  443.60  4885.9  443.19
  4891.4  442.52  4906.2  442.04  4926.7  440.77  4967.1  438.11  4977.2  437.19
  4987.2  435.11  4992.1  435.11  4992.5  434.86  4994.9  433.26  4997.8  433.23
  4998.3  432.43  5003.3  432.43  5003.8  433.23  5010.2  434.26  5016.2  433.83
  5054.8  434.18  5068.0  434.30  5074.1  434.86  5081.0  435.27  5089.2  435.18
  5104.6  435.79  5131.7  437.61  5140.0  437.71  5168.2  439.83  5194.0  441.33
#Mann=5,-1,0
  4830.0    0.16       0  4926.7    0.12       0  4997.8    0.07       0
  5003.8    0.12       0  5054.8    0.05       0
Bank Sta=4992.5,5074.1
Exp/Cntr=0.3,0.1

Type RM Length L Ch R = 1,732,145,145,145
BEGIN DESCRIPTION:
UNT 046 in LFCCL Watershed 2.0
END DESCRIPTION:
XS GIS Cut Line= 3
      2799074.96      7038725.01      2798775.00      7038825.00
      2798475.00      7039075.00
#Sta/Elev= 30
  4633.1  449.51  4770.1  442.10  4780.6  440.50  4801.7  439.97  4812.3  438.17
  4833.3  437.17  4843.9  434.92  4875.5  433.62  4896.6  433.55  4907.1  434.23
  4931.7  433.08  4939.3  433.01  4963.0  432.15  5002.9  431.99  5003.4  431.19
  5008.4  431.19  5008.9  431.99  5013.7  432.73  5028.4  433.01  5053.9  433.65
  5098.3  435.28  5112.7  434.92  5141.3  435.58  5162.1  437.02  5183.6  437.12
  5219.4  439.83  5268.9  440.36  5304.0  442.87  5332.6  443.21  5339.8  442.57
#Mann=5,-1,0
  4633.1    0.16       0  4931.7    0.12       0  5002.9    0.07       0
  5008.9    0.12       0  5053.9    0.05       0
Bank Sta=4939.3,5028.4
Exp/Cntr=0.3,0.1

Type RM Length L Ch R = 1,587,196,196,196
BEGIN DESCRIPTION:
XS3236A
END DESCRIPTION:
XS GIS Cut Line= 3
      2798829.90      7038640.38      2798668.43      7038744.56
      2798559.51      7038882.86
#Sta/Elev= 30
  4806.3  438.46  4835.9  437.82  4857.4  436.02  4871.6  436.46  4904.9  435.18
  4930.0  433.71  4951.1  432.95  4981.7  431.12  4987.4  430.95  4994.5  429.75
  4995.0  428.95  5000.0  428.95  5000.5  429.75  5008.7  430.94  5015.1  430.48
  5022.2  431.12  5029.5  431.71  5050.4  431.69  5058.4  432.14  5072.9  432.27
  5108.1  433.23  5114.5  433.67  5122.6  433.67  5128.9  434.10  5137.0  433.94
  5143.4  434.58  5157.8  435.31  5164.5  436.13  5172.3  436.56  5174.5  436.12
#Mann=4,-1,0
  4806.3    0.16       0  4904.9    0.05       0  4994.5    0.03       0
  5000.5    0.05       0
Bank Sta=4981.7,5022.2
Exp/Cntr=0.3,0.1

Type RM Length L Ch R = 1,391,0,0,0
BEGIN DESCRIPTION:
UNT 046 in LFCCL Watershed 1.0
END DESCRIPTION:
XS GIS Cut Line= 3
      2798862.84      7038513.66      2798575.00      7038575.00
      2798455.19      7038830.72
#Sta/Elev= 30
  4718.2  438.21  4783.9  435.94  4787.6  435.69  4794.6  434.35  4808.0  434.94
  4818.2  434.70  4844.2  433.00  4893.7  432.22  4900.0  431.37  4943.3  431.32
  4971.6  430.05  4983.2  428.52  4987.7  427.69  4992.8  427.78  4999.3  427.19
  4999.8  426.39  5004.8  426.39  5005.3  427.19  5009.9  427.83  5021.2  428.05
  5023.4  428.52  5026.7  429.23  5049.5  430.12  5111.9  430.30  5169.2  431.18
  5178.2  431.64  5192.0  431.35  5209.3  432.17  5244.4  432.54  5294.9  434.84
#Mann=4,-1,0
  4718.2    0.16       0  4783.9    0.05       0  4999.3    0.03       0
  5005.3    0.05       0
Bank Sta=4983.2,5023.4
Exp/Cntr=0.3,0.1

Chan Stop Cuts=-1