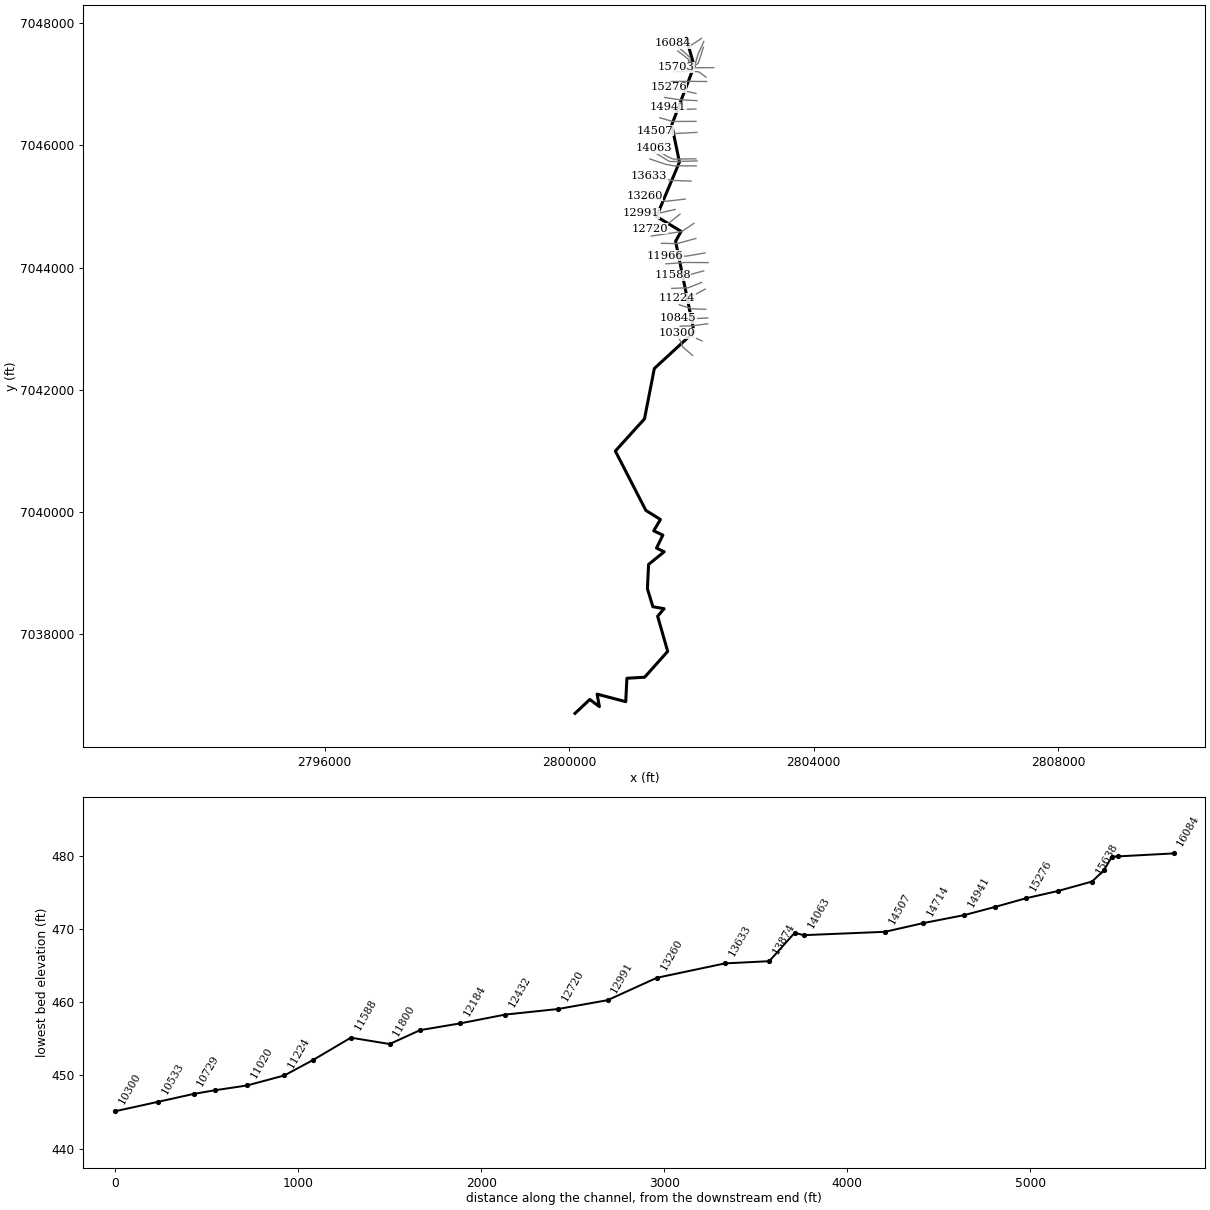
--- UNT 047 in LFCCL Watershed.prj (project) ---

Proj Title=UNT 047 in LFCCL Watershed Base Level Engineering
Current Plan=p01
Default Exp/Contr=0.3,0.1
English Units
Geom File=g01
Flow File=f01
Plan File=p01
BEGIN DESCRIPTION:
UNT 047 in LFCCL Watershed
END DESCRIPTION:

--- UNT 047 in LFCCL Watershed.p01 (plan) ---

Plan Title=Multiple Run
Short Identifier=Multiple
Geom File=g01
Flow File=f01
Subcritical Flow
K Sum by GR= 0
Std Step Tol= 0.01
Critical Tol= 0.01
Num of Std Step Trials= 20
Max Error Tol= 0.3
Flow Tol Ratio= 0.001
Split Flow NTrial= 30
Split Flow Tol= 0.02
Split Flow Ratio= 0.02
Log Output Level= 0
Friction Slope Method= 1
Unsteady Friction Slope Method= 2
Unsteady Bridges Friction Slope Method= 1
Parabolic Critical Depth
Global Vel Dist=  1 , 1 , 1
Global Log Level= 0
CheckData=True
Encroach Param= -1, 0, 0, 0
BEGIN DESCRIPTION:
Multiple Run
END DESCRIPTION:

--- UNT 047 in LFCCL Watershed.f01 (steady flow) ---

Flow Title=Multiple
Number of Profiles=7
Profile Names=10-year,25-year,50-year,1pct_min,100-year,1pct_plu,500-year
River Rch & RM= UNT 047 in LFCCL,Reach-1,16084
     269     341     397     230     459     916     615
River Rch & RM= UNT 047 in LFCCL,Reach-1,11020
     484     638     760     451     899    1795    1260
River Rch & RM= UNT 047 in LFCCL,Reach-1,7821
     620     827     995     594    1185    2365    1686
River Rch & RM= UNT 047 in LFCCL,Reach-1,2992
     905    1234    1505     911    1817    3625    2654
Boundary for River Rch & Prof#=UNT 047 in LFCCL,Reach-1,1
Up Type=0
Dn Type=3
Dn Slope=0.005
Boundary for River Rch & Prof#=UNT 047 in LFCCL,Reach-1,2
Up Type=0
Dn Type=3
Dn Slope=0.005
Boundary for River Rch & Prof#=UNT 047 in LFCCL,Reach-1,3
Up Type=0
Dn Type=3
Dn Slope=0.005
Boundary for River Rch & Prof#=UNT 047 in LFCCL,Reach-1,4
Up Type=0
Dn Type=3
Dn Slope=0.005
Boundary for River Rch & Prof#=UNT 047 in LFCCL,Reach-1,5
Up Type=0
Dn Type=3
Dn Slope=0.005
Boundary for River Rch & Prof#=UNT 047 in LFCCL,Reach-1,6
Up Type=0
Dn Type=3
Dn Slope=0.005
Boundary for River Rch & Prof#=UNT 047 in LFCCL,Reach-1,7
Up Type=0
Dn Type=3
Dn Slope=0.005

--- UNT 047 in LFCCL Watershed.g01 (geometry) ---

Geom Title=Existing Conditions

River Reach=UNT 047 in LFCCL,Reach-1
Reach XY= 30
      2801916.60      7047750.27      2802044.73      7047299.58
      2801678.03      7046335.16      2801803.69      7045725.90
      2801429.04      7044835.69      2801830.60      7044592.66
      2801740.70      7044430.09      2802043.02      7042946.44
      2801392.99      7042346.88      2801231.82      7041522.20
      2800755.11      7040995.60      2801254.11      7040024.41
      2801493.06      7039874.95      2801382.94      7039690.07
      2801532.26      7039618.57      2801428.91      7039407.04
      2801554.18      7039346.72      2801299.20      7039139.13
      2801279.68      7038741.37      2801369.50      7038447.05
      2801553.18      7038414.87      2801447.01      7038291.32
      2801611.52      7037716.05      2801234.69      7037292.65
      2800944.48      7037275.68      2800925.19      7036892.55
      2800456.58      7037015.62      2800494.52      7036811.17
      2800337.51      7036928.43      2800095.59      7036700.71

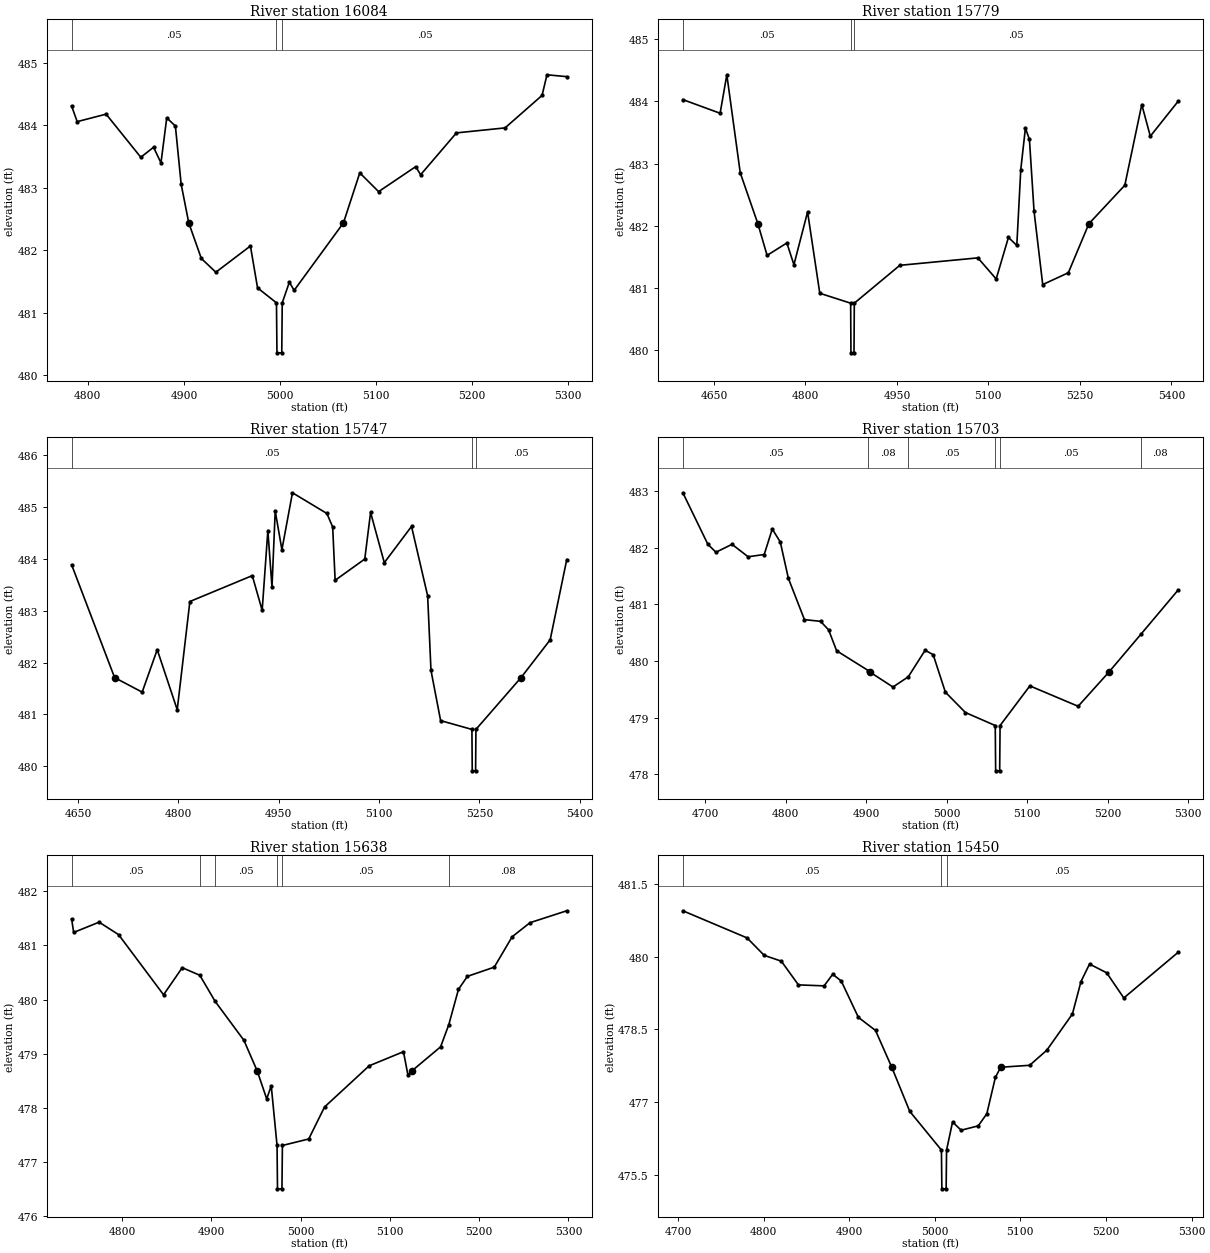
Type RM Length L Ch R = 1,16084,305,305,305
BEGIN DESCRIPTION:
UNT 047 in LFCCL Watershed 31.0
END DESCRIPTION:
XS GIS Cut Line= 3
      2802166.00      7047752.49      2801980.66      7047628.93
      2801691.51      7047673.42
#Sta/Elev= 30
  4783.1  484.31  4788.9  484.06  4819.0  484.18  4855.1  483.49  4868.4  483.65
  4876.1  483.40  4882.1  484.12  4891.1  483.99  4897.1  483.06  4905.0  482.44
  4918.1  481.87  4933.2  481.65  4969.2  482.07  4976.6  481.40  4996.3  481.16
  4996.8  480.36  5001.8  480.36  5002.3  481.16  5009.7  481.49  5014.7  481.36
  5066.0  482.44  5083.0  483.24  5102.6  482.94  5141.2  483.34  5146.3  483.21
  5183.6  483.88  5234.2  483.96  5272.7  484.48  5277.8  484.81  5298.4  484.78
#Mann=3,-1,0
  4783.1    0.05       0  4996.3    0.03       0  5002.3    0.05       0
Bank Sta=4905,5066
Exp/Cntr=0.3,0.1

Type RM Length L Ch R = 1,15779,32,32,32
BEGIN DESCRIPTION:
XS3241A
END DESCRIPTION:
XS GIS Cut Line= 6
      2802203.04      7047700.57      2802109.15      7047495.50
      2802064.68      7047344.77      2801983.13      7047359.59
      2801978.19      7047438.66      2801780.54      7047614.08
#Sta/Elev= 30
  4599.1  484.03  4660.2  483.81  4671.2  484.43  4693.2  482.85  4722.1  482.03
  4737.2  481.52  4769.6  481.72  4781.2  481.37  4803.6  482.22  4823.6  480.91
  4874.2  480.75  4874.7  479.95  4879.7  479.95  4880.2  480.75  4954.8  481.36
  5082.8  481.48  5112.8  481.14  5132.9  481.81  5146.6  481.68  5153.1  482.90
  5160.7  483.57  5167.3  483.39  5174.9  482.23  5189.1  481.05  5231.1  481.24
  5264.8  482.03  5323.7  482.65  5351.5  483.95  5365.5  483.44  5410.9  484.00
#Mann=3,-1,0
  4599.1    0.05       0  4874.2    0.03       0  4880.2    0.05       0
Bank Sta=4722.1,5264.8
Exp/Cntr=0.3,0.1

Type RM Length L Ch R = 1,15747,44,44,44
BEGIN DESCRIPTION:
XS3240A
END DESCRIPTION:
XS GIS Cut Line= 6
      2802195.62      7047606.66      2802114.10      7047349.71
      2802067.15      7047310.17      2801968.31      7047327.47
      2801946.07      7047413.95      2801779.01      7047544.16
#Sta/Elev= 30
  4640.3  483.89  4704.6  481.71  4745.8  481.43  4768.3  482.25  4798.2  481.09
  4817.1  483.18  4910.4  483.68  4925.2  483.01  4933.7  484.55  4939.9  483.46
  4944.7  484.93  4954.7  484.18  4970.5  485.28  5022.0  484.88  5030.6  484.62
  5034.3  483.59  5078.6  484.00  5087.3  484.90  5107.8  483.93  5148.5  484.63
  5172.6  483.29  5177.6  481.85  5192.0  480.88  5238.8  480.71  5239.3  479.91
  5244.3  479.91  5244.8  480.71  5312.2  481.71  5355.8  482.44  5380.6  483.99
#Mann=3,-1,0
  4640.3    0.05       0  5238.8    0.03       0  5244.8    0.05       0
Bank Sta=4704.6,5312.2
Exp/Cntr=0.3,0.1

Type RM Length L Ch R = 1,15703,65,65,65
BEGIN DESCRIPTION:
XS3239A
END DESCRIPTION:
XS GIS Cut Line= 3
      2802366.13      7047273.11      2802039.96      7047270.63
      2801750.88      7047275.58
#Sta/Elev= 30
  4672.3  482.97  4703.4  482.06  4713.4  481.92  4733.4  482.06  4753.4  481.84
  4773.4  481.88  4783.4  482.33  4793.4  482.10  4803.4  481.46  4823.4  480.73
  4843.4  480.70  4853.4  480.55  4863.4  480.18  4902.8  479.83  4905.2  479.80
  4933.4  479.54  4952.4  479.72  4973.4  480.19  4983.4  480.11  4998.5  479.45
  5023.4  479.09  5060.5  478.86  5061.0  478.06  5066.0  478.06  5066.5  478.86
  5103.5  479.56  5163.5  479.20  5201.5  479.80  5241.4  480.47  5287.6  481.25
#Mann=6,-1,0
  4672.3    0.05       0  4902.8    0.08       0  4952.4    0.05       0
  5060.5    0.03       0  5066.5    0.05       0  5241.4    0.08       0
Bank Sta=4905.2,5201.5
Exp/Cntr=0.3,0.1

Type RM Length L Ch R = 1,15638,188,188,188
BEGIN DESCRIPTION:
XS3242A
END DESCRIPTION:
XS GIS Cut Line= 4
      2802240.10      7047117.44      2802119.04      7047203.92
      2802005.37      7047213.80      2801713.81      7047203.92
#Sta/Elev= 30
  4743.5  481.49  4745.8  481.24  4774.3  481.43  4796.1  481.20  4846.5  480.09
  4867.4  480.59  4887.1  480.45  4904.2  479.97  4936.5  479.25  4951.5  478.68
  4962.0  478.17  4967.1  478.41  4973.6  477.31  4974.1  476.51  4979.1  476.51
  4979.6  477.31  5009.1  477.43  5026.8  478.02  5076.8  478.78  5115.2  479.04
  5120.2  478.61  5124.2  478.68  5156.8  479.13  5166.0  479.54  5176.8  480.19
  5186.8  480.43  5216.9  480.60  5236.9  481.16  5256.9  481.42  5298.1  481.64
#Mann=6,-1,0
  4743.5    0.05       0  4887.1    0.08       0  4904.2    0.05       0
  4973.6    0.03       0  4979.6    0.05       0  5166.0    0.08       0
Bank Sta=4951.5,5124.2
Exp/Cntr=0.3,0.1

Type RM Length L Ch R = 1,15450,174,174,174
BEGIN DESCRIPTION:
XS3243A
END DESCRIPTION:
XS GIS Cut Line= 3
      2802250.02      7047045.77      2801958.42      7047048.24
      2801671.74      7047045.77
#Sta/Elev= 30
  4705.8  480.95  4780.8  480.39  4800.8  480.03  4820.8  479.91  4840.8  479.42
  4870.8  479.40  4880.8  479.64  4890.8  479.50  4910.8  478.75  4930.8  478.48
  4949.8  477.72  4970.8  476.81  5007.8  476.01  5008.3  475.21  5013.3  475.21
  5013.8  476.01  5020.8  476.59  5030.8  476.42  5050.8  476.51  5060.8  476.76
  5070.8  477.51  5077.0  477.72  5110.8  477.76  5130.8  478.07  5160.8  478.82
  5170.8  479.49  5180.8  479.85  5200.8  479.67  5220.8  479.15  5284.1  480.09
#Mann=3,-1,0
  4705.8    0.05       0  5007.8    0.03       0  5013.8    0.05       0
Bank Sta=4949.8,5077
Exp/Cntr=0.3,0.1

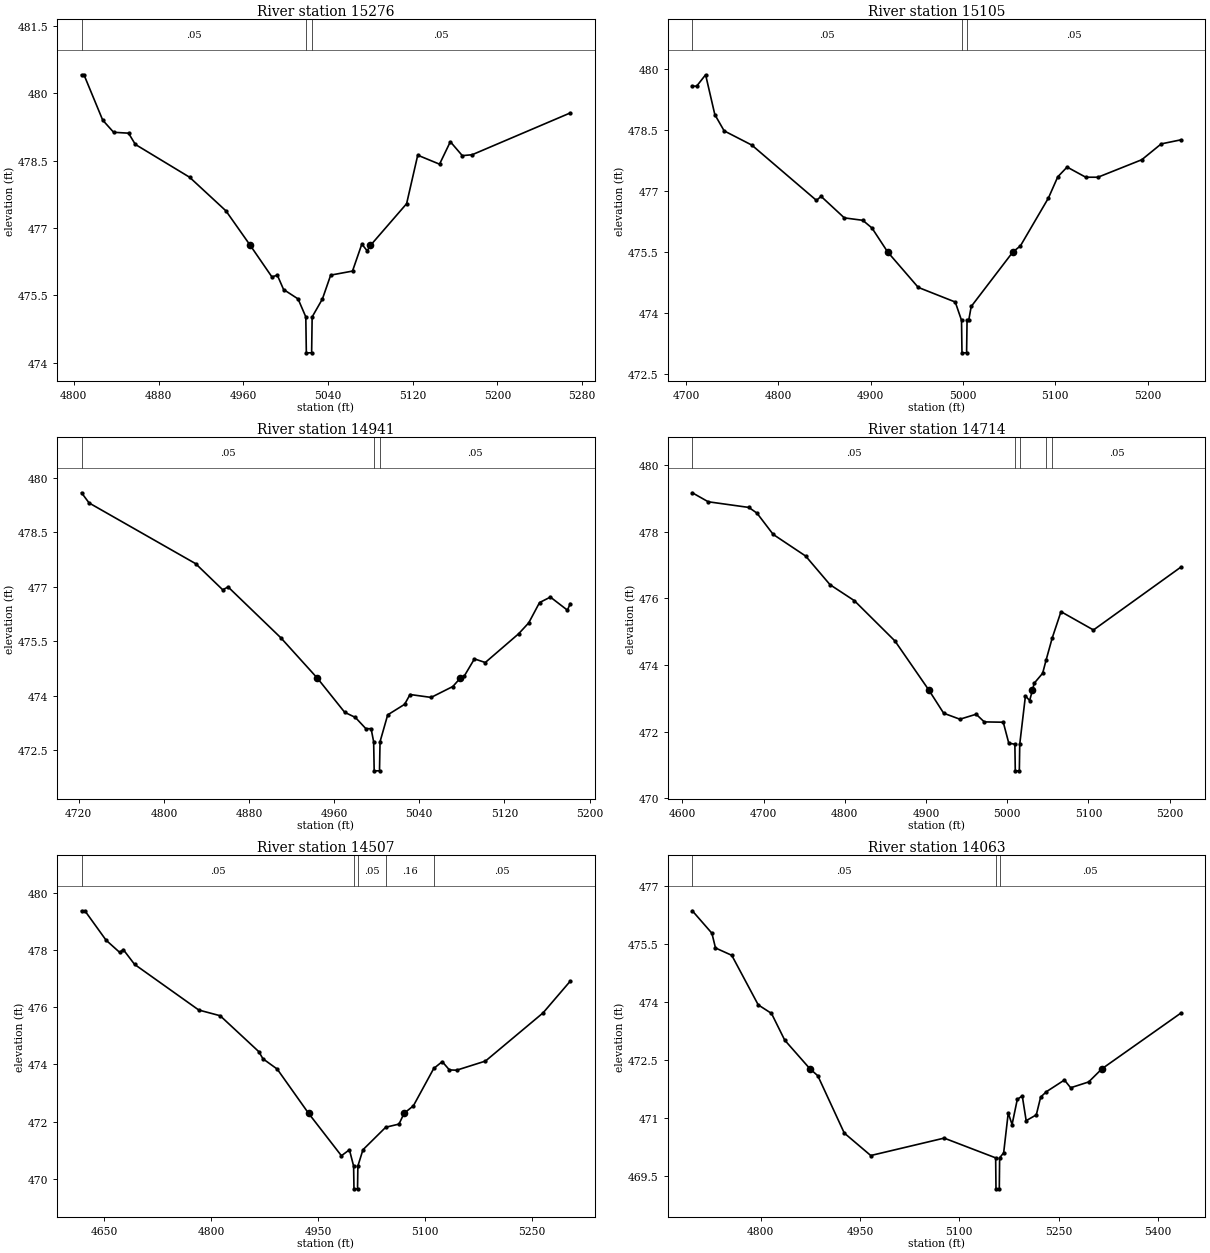
Type RM Length L Ch R = 1,15276,171,171,171
BEGIN DESCRIPTION:
XS3244A
END DESCRIPTION:
XS GIS Cut Line= 3
      2802074.54      7046850.56      2801886.76      7046892.57
      2801624.87      7046954.33
#Sta/Elev= 30
  4807.3  480.41  4809.6  480.41  4827.3  479.40  4837.6  479.13  4851.7  479.11
  4858.1  478.86  4909.3  478.13  4943.7  477.38  4966.7  476.61  4987.1  475.91
  4992.2  475.95  4998.1  475.63  5011.8  475.42  5019.1  475.02  5019.6  474.22
  5024.6  474.22  5025.1  475.02  5034.8  475.42  5042.6  475.95  5063.2  476.04
  5072.0  476.64  5077.1  476.49  5080.1  476.61  5114.3  477.54  5124.8  478.62
  5145.4  478.42  5155.6  478.92  5166.9  478.61  5176.2  478.63  5268.8  479.56
#Mann=3,-1,0
  4807.3    0.05       0  5019.1    0.03       0  5025.1    0.05       0
Bank Sta=4966.7,5080.1
Exp/Cntr=0.3,0.1

Type RM Length L Ch R = 1,15105,164,164,164
BEGIN DESCRIPTION:
XS3245A
END DESCRIPTION:
XS GIS Cut Line= 3
      2802089.40      7046731.95      2801790.39      7046749.25
      2801563.01      7046783.85
#Sta/Elev= 30
  4706.7  479.58  4711.4  479.58  4721.1  479.86  4731.1  478.88  4741.2  478.48
  4771.2  478.13  4841.2  476.77  4846.2  476.87  4871.4  476.34  4891.4  476.28
  4901.4  476.09  4918.4  475.50  4951.5  474.63  4991.6  474.27  4998.4  473.82
  4998.9  473.02  5003.9  473.02  5004.4  473.82  5006.2  473.82  5008.9  474.16
  5054.0  475.50  5062.2  475.65  5092.6  476.83  5102.7  477.35  5112.8  477.59
  5133.0  477.34  5146.2  477.34  5193.7  477.77  5214.8  478.16  5236.2  478.26
#Mann=3,-1,0
  4706.7    0.05       0  4998.4    0.03       0  5004.4    0.05       0
Bank Sta=4918.4,5054
Exp/Cntr=0.3,0.1

Type RM Length L Ch R = 1,14941,227,227,227
BEGIN DESCRIPTION:
XS3246A
END DESCRIPTION:
XS GIS Cut Line= 3
      2802072.08      7046596.04      2801800.28      7046583.69
      2801616.79      7046620.39
#Sta/Elev= 30
  4722.6  479.58  4729.7  479.30  4829.8  477.63  4855.3  476.91  4860.3  476.99
  4909.9  475.59  4944.2  474.48  4969.9  473.54  4979.9  473.40  4989.8  473.09
  4994.7  473.09  4997.1  472.73  4997.6  471.93  5002.6  471.93  5003.1  472.73
  5010.3  473.47  5026.2  473.76  5031.3  474.03  5051.1  473.95  5071.5  474.25
  5078.5  474.48  5082.3  474.54  5091.8  475.01  5102.0  474.91  5133.3  475.70
  5142.8  476.00  5153.0  476.56  5163.2  476.71  5179.2  476.35  5181.8  476.53
#Mann=3,-1,0
  4722.6    0.05       0  4997.1    0.03       0  5003.1    0.05       0
Bank Sta=4944.2,5078.5
Exp/Cntr=0.3,0.1

Type RM Length L Ch R = 1,14714,207,207,207
BEGIN DESCRIPTION:
XS3247A
END DESCRIPTION:
XS GIS Cut Line= 3
      2802074.56      7046393.42      2801691.55      7046390.95
      2801481.56      7046452.71
#Sta/Elev= 30
  4612.1  479.17  4631.7  478.90  4681.7  478.73  4691.7  478.56  4711.7  477.92
  4751.7  477.27  4781.7  476.41  4811.7  475.93  4861.7  474.72  4903.6  473.24
  4921.7  472.55  4941.7  472.37  4961.7  472.52  4971.7  472.29  4995.1  472.28
  5001.9  471.65  5009.4  471.62  5009.9  470.82  5014.9  470.82  5015.4  471.62
  5022.4  473.07  5027.6  472.93  5031.0  473.24  5033.2  473.45  5043.6  473.75
  5047.9  474.15  5055.4  474.81  5066.2  475.60  5106.2  475.05  5214.0  476.94
#Mann=5,-1,0
  4612.1    0.05       0  5009.4    0.03       0  5015.4    0.05       0
  5047.9    0.16       0  5055.4    0.05       0
Bank Sta=4903.6,5031
Exp/Cntr=0.3,0.1

Type RM Length L Ch R = 1,14507,444,444,444
BEGIN DESCRIPTION:
XS3248A
END DESCRIPTION:
XS GIS Cut Line= 3
      2802089.37      7046213.03      2801713.79      7046193.27
      2801407.36      7046240.22
#Sta/Elev= 30
  4617.8  479.39  4622.5  479.39  4652.2  478.36  4671.4  477.93  4676.4  478.03
  4692.3  477.51  4782.4  475.91  4812.4  475.71  4866.7  474.45  4872.5  474.20
  4892.5  473.84  4936.5  472.29  4982.7  470.80  4993.9  471.01  4999.8  470.44
  5000.3  469.64  5005.3  469.64  5005.8  470.44  5012.9  471.01  5044.9  471.80
  5063.5  471.91  5070.7  472.29  5083.7  472.55  5112.3  473.86  5124.2  474.10
  5134.3  473.81  5144.4  473.80  5184.9  474.12  5265.8  475.81  5303.9  476.92
#Mann=5,-1,0
  4617.8    0.05       0  4999.8    0.03       0  5005.8    0.05       0
  5044.9    0.16       0  5112.3    0.05       0
Bank Sta=4936.5,5070.7
Exp/Cntr=0.3,0.1

Type RM Length L Ch R = 1,14063,50,50,50
BEGIN DESCRIPTION:
XS3249A
END DESCRIPTION:
XS GIS Cut Line= 5
      2802074.56      7045780.61      2801785.45      7045775.66
      2801698.96      7045775.66      2801614.95      7045812.73
      2801385.14      7045956.05
#Sta/Elev= 30
  4696.6  476.36  4726.2  475.78  4731.6  475.40  4756.2  475.21  4796.2  473.93
  4816.2  473.71  4836.2  473.02  4874.3  472.28  4886.2  472.10  4926.2  470.62
  4966.2  470.04  5077.1  470.49  5154.9  469.98  5155.4  469.18  5160.4  469.18
  5160.9  469.98  5167.0  470.11  5173.9  471.14  5179.7  470.84  5187.6  471.49
  5195.1  471.58  5201.0  470.94  5216.3  471.09  5222.9  471.55  5231.7  471.69
  5258.8  471.99  5268.2  471.79  5295.4  471.94  5315.5  472.28  5434.9  473.72
#Mann=3,-1,0
  4696.6    0.05       0  5154.9    0.03       0  5160.9    0.05       0
Bank Sta=4874.3,5315.5
Exp/Cntr=0.3,0.1

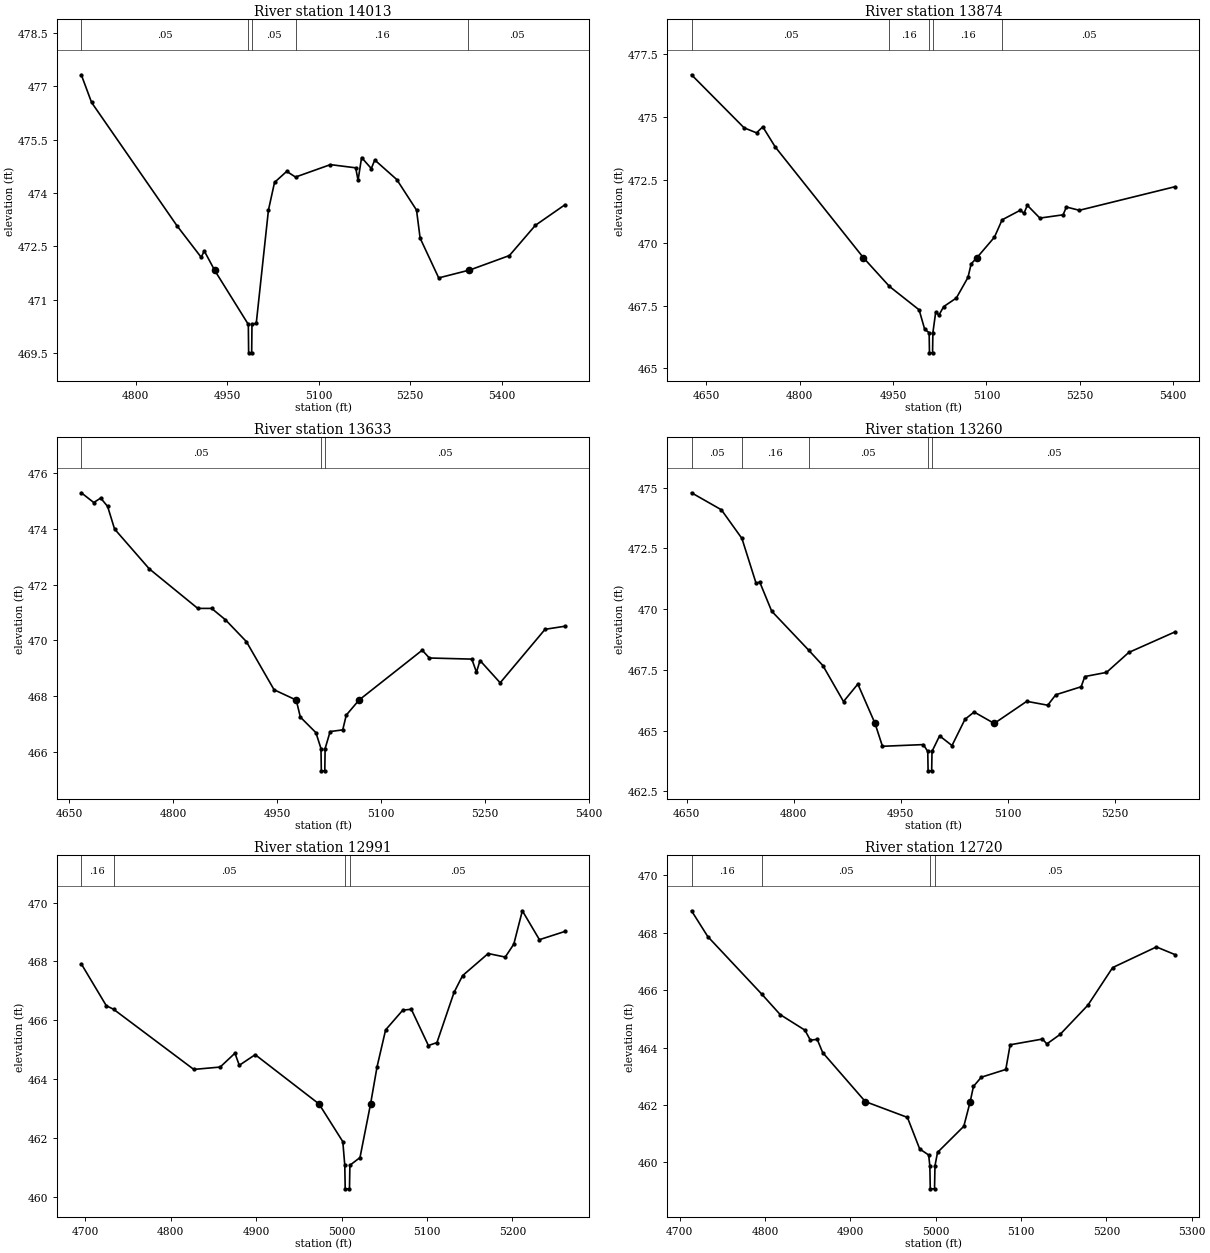
Type RM Length L Ch R = 1,14013,139,139,139
BEGIN DESCRIPTION:
XS3250A
END DESCRIPTION:
XS GIS Cut Line= 6
      2802091.88      7045746.01      2801760.74      7045736.13
      2801686.61      7045736.13      2801644.60      7045736.13
      2801582.83      7045770.72      2801349.07      7045915.90
#Sta/Elev= 30
  4710.6  477.33  4727.5  476.55  4867.5  473.08  4907.3  472.19  4912.3  472.37
  4929.5  471.82  4984.6  470.30  4985.1  469.50  4990.1  469.50  4990.6  470.30
  4997.6  470.33  5017.6  473.52  5027.6  474.30  5047.6  474.61  5062.0  474.45
  5119.3  474.80  5160.7  474.71  5164.6  474.36  5170.4  475.00  5186.3  474.69
  5192.0  474.93  5228.1  474.38  5260.5  473.52  5266.4  472.73  5296.9  471.61
  5344.9  471.82  5345.9  471.82  5412.9  472.24  5455.4  473.09  5504.0  473.67
#Mann=5,-1,0
  4710.6    0.05       0  4984.6    0.03       0  4990.6    0.05       0
  5062.0    0.16       0  5344.9    0.05       0
Bank Sta=4929.5,5345.9
Exp/Cntr=0.3,0.1

Type RM Length L Ch R = 1,13874,241,241,241
BEGIN DESCRIPTION:
XS3251A
END DESCRIPTION:
XS GIS Cut Line= 4
      2802079.46      7045664.47      2801713.79      7045664.47
      2801572.94      7045691.65      2801319.21      7045777.87
#Sta/Elev= 30
  4626.1  476.68  4710.6  474.57  4730.6  474.37  4740.6  474.61  4760.6  473.81
  4902.4  469.40  4944.2  468.26  4991.8  467.33  5000.7  466.56  5007.9  466.42
  5008.4  465.62  5013.4  465.62  5013.9  466.42  5018.5  467.25  5023.6  467.12
  5031.3  467.46  5051.6  467.80  5070.3  468.62  5075.4  469.16  5084.5  469.40
  5112.8  470.22  5125.1  470.91  5154.2  471.29  5160.3  471.17  5165.6  471.49
  5185.8  470.98  5223.1  471.11  5228.4  471.42  5249.2  471.29  5403.2  472.23
#Mann=5,-1,0
  4626.1    0.05       0  4944.2    0.16       0  5007.9    0.07       0
  5013.9    0.16       0  5125.1    0.05       0
Bank Sta=4902.4,5084.5
Exp/Cntr=0.3,0.1

Type RM Length L Ch R = 1,13633,373,373,373
BEGIN DESCRIPTION:
XS3252A
END DESCRIPTION:
XS GIS Cut Line= 3
      2801992.98      7045414.90      2801674.25      7045427.25
      2801303.56      7045506.33
#Sta/Elev= 30
  4667.3  475.30  4685.3  474.95  4695.3  475.11  4705.3  474.81  4715.3  474.00
  4765.4  472.57  4835.4  471.15  4855.4  471.15  4875.4  470.74  4905.5  469.96
  4945.5  468.23  4977.5  467.86  4983.4  467.25  5005.9  466.69  5013.2  466.12
  5013.7  465.32  5018.7  465.32  5019.2  466.12  5026.4  466.73  5044.6  466.79
  5049.7  467.32  5068.1  467.86  5159.3  469.65  5169.6  469.37  5230.9  469.33
  5237.6  468.86  5242.7  469.28  5271.8  468.48  5336.6  470.40  5365.3  470.51
#Mann=3,-1,0
  4667.3    0.05       0  5013.2    0.03       0  5019.2    0.05       0
Bank Sta=4977.5,5068.1
Exp/Cntr=0.3,0.1

Type RM Length L Ch R = 1,13260,269,269,269
BEGIN DESCRIPTION:
XS3253A
END DESCRIPTION:
XS GIS Cut Line= 3
      2801896.65      7045120.84      2801577.88      7045083.78
      2801231.95      7045172.73
#Sta/Elev= 30
  4656.7  474.79  4698.6  474.09  4727.4  472.91  4747.3  471.06  4752.3  471.12
  4769.1  469.92  4820.8  468.32  4840.9  467.68  4869.8  466.20  4889.9  466.92
  4914.0  465.30  4924.4  464.36  4981.7  464.43  4987.9  464.15  4988.4  463.35
  4993.4  463.35  4993.9  464.15  5004.5  464.79  5021.9  464.39  5040.1  465.47
  5052.9  465.77  5081.1  465.30  5126.7  466.21  5156.1  466.05  5167.4  466.48
  5203.0  466.81  5208.1  467.23  5238.5  467.40  5269.7  468.22  5334.8  469.07
#Mann=5,-1,0
  4656.7    0.05       0  4727.4    0.16       0  4820.8    0.05       0
  4987.9    0.03       0  4993.9    0.05       0
Bank Sta=4914,5081.1
Exp/Cntr=0.3,0.1

Type RM Length L Ch R = 1,12991,271,271,271
BEGIN DESCRIPTION:
XS3254A
END DESCRIPTION:
XS GIS Cut Line= 3
      2801733.56      7044950.34      2801429.62      7044881.15
      2801175.09      7044886.10
#Sta/Elev= 30
  4695.3  467.92  4724.6  466.50  4733.1  466.38  4827.0  464.34  4857.9  464.42
  4875.2  464.89  4880.3  464.48  4898.9  464.84  4973.6  463.17  5001.5  461.89
  5003.8  461.09  5004.3  460.29  5009.3  460.29  5009.8  461.09  5021.6  461.35
  5034.0  463.17  5041.6  464.43  5051.6  465.68  5071.7  466.35  5081.7  466.38
  5101.7  465.15  5111.7  465.25  5131.7  466.95  5141.7  467.52  5171.7  468.27
  5191.7  468.15  5201.7  468.59  5211.7  469.72  5231.7  468.74  5261.6  469.02
#Mann=4,-1,0
  4695.3    0.16       0  4733.1    0.05       0  5003.8    0.03       0
  5009.8    0.05       0
Bank Sta=4973.6,5034
Exp/Cntr=0.3,0.1

Type RM Length L Ch R = 1,12720,288,288,288
BEGIN DESCRIPTION:
XS3255A
END DESCRIPTION:
XS GIS Cut Line= 3
      2801812.66      7044873.76      2801595.18      7044700.77
      2801313.51      7044636.53
#Sta/Elev= 30
  4713.9  468.77  4733.0  467.87  4796.4  465.86  4817.9  465.15  4846.8  464.61
  4853.2  464.26  4861.2  464.29  4867.6  463.83  4917.6  462.12  4966.9  461.57
  4981.3  460.47  4991.8  460.26  4993.2  459.88  4993.7  459.08  4998.7  459.08
  4999.2  459.88  5002.2  460.35  5033.0  461.26  5040.5  462.12  5044.3  462.65
  5053.5  462.97  5082.2  463.24  5087.3  464.10  5125.2  464.30  5130.3  464.13
  5145.8  464.46  5178.4  465.48  5207.4  466.79  5258.7  467.51  5280.7  467.24
#Mann=4,-1,0
  4713.9    0.16       0  4796.4    0.05       0  4993.2    0.03       0
  4999.2    0.05       0
Bank Sta=4917.6,5040.5
Exp/Cntr=0.3,0.1

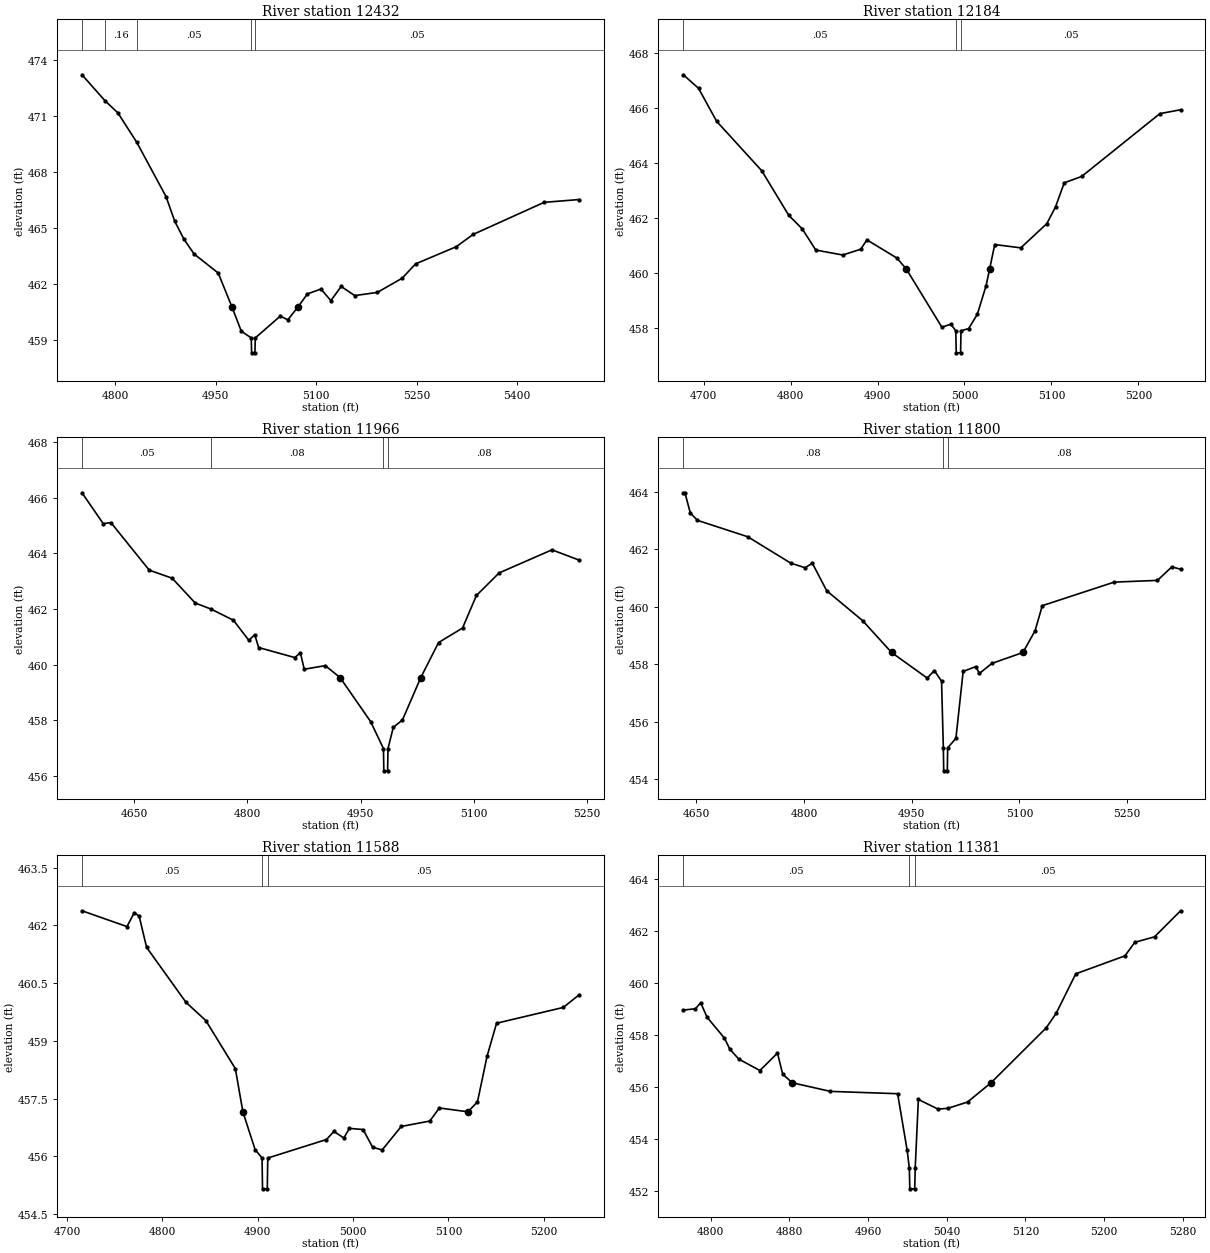
Type RM Length L Ch R = 1,12432,248,248,248
BEGIN DESCRIPTION:
XS3256A
END DESCRIPTION:
XS GIS Cut Line= 3
      2802039.99      7044723.02      2801842.28      7044589.57
      2801343.18      7044515.45
#Sta/Elev= 30
  4749.9  473.23  4784.3  471.84  4803.5  471.19  4831.8  469.61  4875.5  466.70
  4888.6  465.37  4902.5  464.40  4917.5  463.62  4953.5  462.60  4974.3  460.76
  4988.0  459.48  5002.9  459.12  5003.4  458.32  5008.4  458.32  5008.9  459.12
  5046.3  460.29  5057.5  460.09  5072.3  460.76  5086.8  461.48  5107.0  461.74
  5121.9  461.12  5137.3  461.88  5157.5  461.39  5191.3  461.56  5228.3  462.32
  5248.5  463.09  5309.2  464.01  5334.5  464.67  5440.6  466.39  5493.0  466.54
#Mann=5,-1,0
  4749.9    0.05       0  4784.3    0.16       0  4831.8    0.05       0
  5002.9    0.03       0  5008.9    0.05       0
Bank Sta=4974.3,5072.3
Exp/Cntr=0.3,0.1

Type RM Length L Ch R = 1,12184,218,218,218
BEGIN DESCRIPTION:
XS3257A
END DESCRIPTION:
XS GIS Cut Line= 3
      2802072.04      7044475.89      2801763.21      7044391.89
      2801511.21      7044396.83
#Sta/Elev= 30
  4676.5  467.20  4694.0  466.71  4714.9  465.51  4766.7  463.72  4797.8  462.10
  4813.3  461.61  4828.9  460.84  4860.0  460.66  4880.7  460.87  4887.7  461.21
  4922.2  460.55  4932.9  460.16  4974.0  458.04  4984.3  458.15  4990.0  457.91
  4990.5  457.11  4995.5  457.11  4996.0  457.91  5004.8  457.99  5014.8  458.51
  5024.8  459.54  5029.0  460.16  5034.8  461.04  5064.8  460.92  5094.8  461.80
  5104.8  462.41  5114.8  463.28  5134.8  463.51  5224.8  465.79  5248.6  465.93
#Mann=3,-1,0
  4676.5    0.05       0  4990.0    0.03       0  4996.0    0.05       0
Bank Sta=4932.9,5029
Exp/Cntr=0.3,0.1

Type RM Length L Ch R = 1,11966,166,166,166
BEGIN DESCRIPTION:
XS3258A
END DESCRIPTION:
XS GIS Cut Line= 4
      2802222.81      7044238.68      2801916.41      7044186.79
      2801802.75      7044186.79      2801568.98      7044196.64
#Sta/Elev= 30
  4581.1  466.18  4609.3  465.07  4619.4  465.11  4670.2  463.40  4700.6  463.11
  4731.0  462.22  4752.1  462.00  4781.7  461.60  4802.0  460.88  4809.9  461.08
  4815.0  460.62  4862.9  460.26  4870.3  460.43  4875.4  459.84  4903.3  459.97
  4922.9  459.54  4963.3  457.96  4980.3  456.99  4980.8  456.19  4985.8  456.19
  4986.3  456.99  4993.3  457.75  5005.5  458.02  5029.7  459.54  5053.3  460.80
  5085.0  461.32  5103.4  462.49  5133.4  463.30  5203.4  464.13  5239.5  463.76
#Mann=4,-1,0
  4581.1    0.05       0  4752.1    0.08       0  4980.3    0.07       0
  4986.3    0.08       0
Bank Sta=4922.9,5029.7
Exp/Cntr=0.3,0.1

Type RM Length L Ch R = 1,11800,212,212,212
BEGIN DESCRIPTION:
XS3259A
END DESCRIPTION:
XS GIS Cut Line= 3
      2802274.69      7044080.54      2801909.00      7044083.01
      2801582.86      7044060.77
#Sta/Elev= 30
  4631.8  463.97  4634.1  463.97  4641.5  463.27  4651.5  463.01  4721.5  462.44
  4781.5  461.52  4801.5  461.36  4811.5  461.52  4831.5  460.56  4881.5  459.52
  4921.9  458.41  4971.5  457.52  4981.5  457.78  4991.5  457.41  4994.0  455.09
  4994.5  454.29  4999.5  454.29  5000.0  455.09  5011.5  455.42  5021.6  457.75
  5039.2  457.92  5044.2  457.68  5061.6  458.03  5104.9  458.41  5121.8  459.17
  5131.8  460.04  5232.0  460.86  5292.2  460.92  5312.2  461.39  5324.4  461.31
#Mann=3,-1,0
  4631.8    0.08       0  4994.0    0.07       0  5000.0    0.08       0
Bank Sta=4921.9,5104.9
Exp/Cntr=0.3,0.1

Type RM Length L Ch R = 1,11588,207,207,207
BEGIN DESCRIPTION:
XS3260A
END DESCRIPTION:
XS GIS Cut Line= 3
      2802200.60      7043944.64      2801928.77      7043872.97
      2801688.29      7043872.97
#Sta/Elev= 30
  4715.6  462.38  4762.8  461.97  4770.5  462.33  4775.6  462.24  4783.4  461.43
  4824.8  460.00  4845.5  459.53  4876.5  458.28  4884.4  457.16  4897.2  456.18
  4904.5  455.96  4905.0  455.16  4910.0  455.16  4910.5  455.96  4972.0  456.44
  4979.9  456.65  4990.3  456.48  4996.1  456.73  5010.5  456.70  5020.5  456.24
  5030.5  456.17  5050.5  456.78  5080.5  456.92  5090.5  457.26  5120.5  457.16
  5130.5  457.42  5140.5  458.60  5150.5  459.46  5220.5  459.87  5237.2  460.20
#Mann=3,-1,0
  4715.6    0.05       0  4904.5    0.03       0  4910.5    0.05       0
Bank Sta=4884.4,5120.5
Exp/Cntr=0.3,0.1

Type RM Length L Ch R = 1,11381,157,157,157
BEGIN DESCRIPTION:
XS3261A
END DESCRIPTION:
XS GIS Cut Line= 3
      2802167.36      7043756.19      2801950.39      7043669.39
      2801678.49      7043658.61
#Sta/Elev= 30
  4772.0  458.96  4784.3  459.01  4789.7  459.24  4796.1  458.69  4813.9  457.88
  4819.3  457.46  4828.4  457.08  4849.9  456.64  4867.8  457.31  4873.1  456.50
  4882.8  456.17  4921.6  455.84  4990.0  455.75  4999.7  453.58  5001.9  452.90
  5002.4  452.10  5007.4  452.10  5007.9  452.90  5011.1  455.53  5031.1  455.16
  5041.1  455.19  5061.1  455.43  5085.0  456.17  5141.2  458.28  5151.2  458.83
  5171.2  460.35  5221.2  461.04  5231.3  461.56  5251.3  461.77  5277.8  462.77
#Mann=3,-1,0
  4772.0    0.05       0  5001.9    0.03       0  5007.9    0.05       0
Bank Sta=4882.8,5085
Exp/Cntr=0.3,0.1

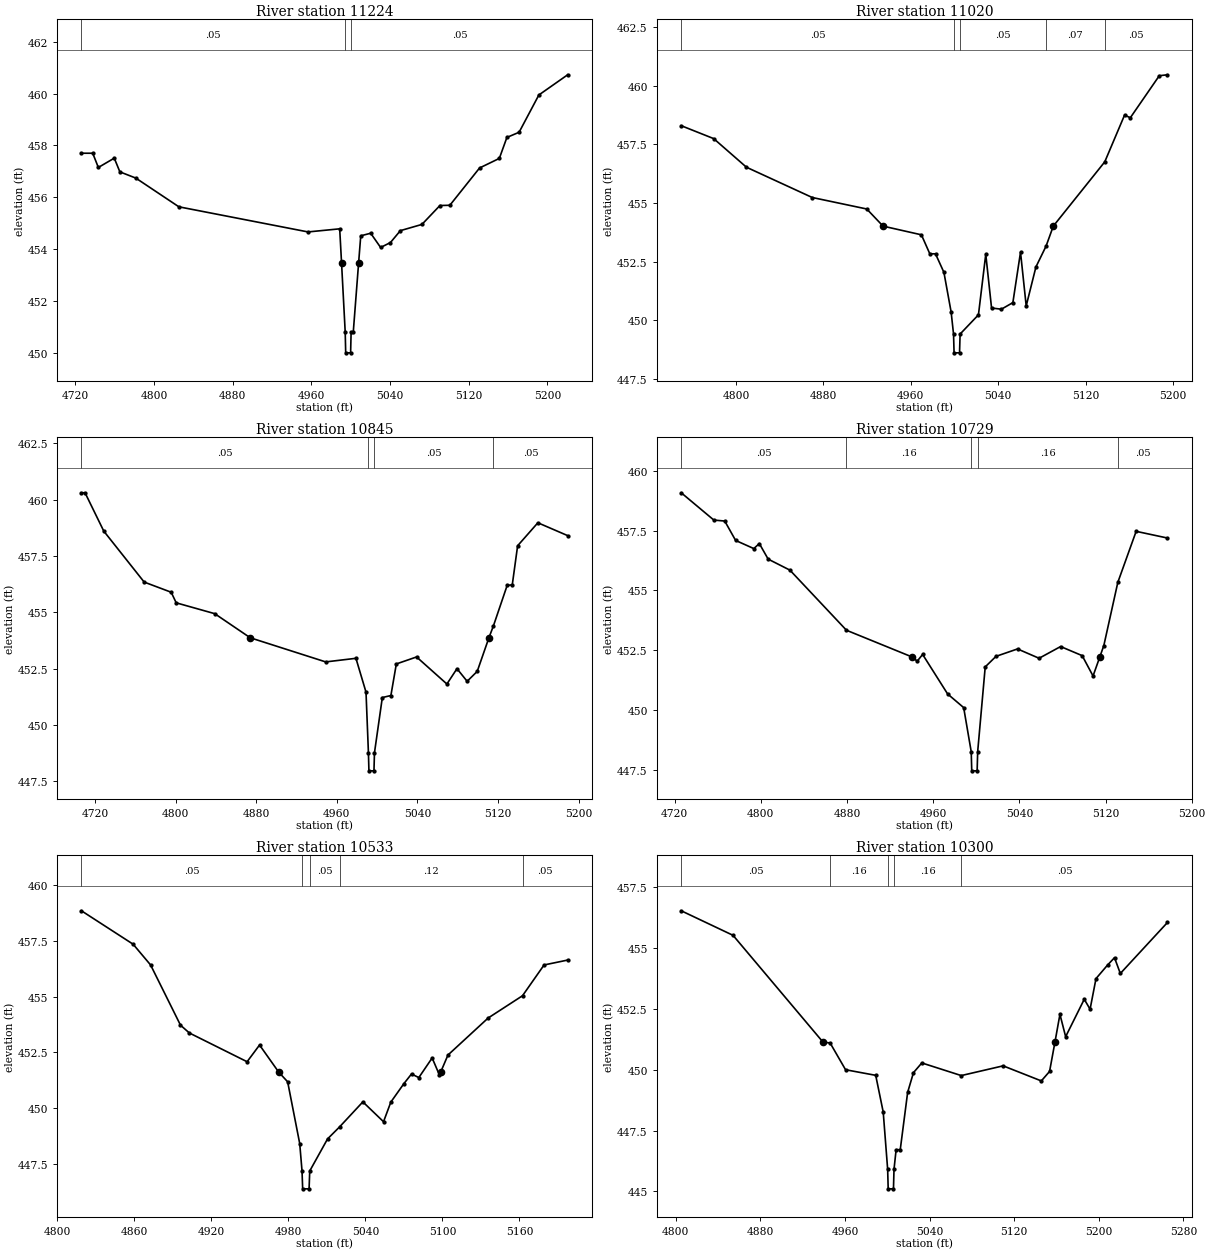
Type RM Length L Ch R = 1,11224,204,204,204
BEGIN DESCRIPTION:
XS3262A
END DESCRIPTION:
XS GIS Cut Line= 3
      2802226.04      7043647.72      2801985.11      7043517.49
      2801765.88      7043493.61
#Sta/Elev= 30
  4726.3  457.70  4737.8  457.70  4743.5  457.15  4759.7  457.51  4765.4  456.98
  4781.6  456.74  4825.4  455.63  4956.7  454.66  4988.9  454.78  4990.8  453.45
  4994.5  450.79  4995.0  449.99  5000.0  449.99  5000.5  450.79  5002.7  450.79
  5008.1  453.45  5010.3  454.51  5020.4  454.61  5030.5  454.06  5040.5  454.25
  5050.6  454.71  5072.5  454.95  5090.8  455.68  5100.9  455.69  5131.1  457.13
  5151.2  457.50  5158.9  458.31  5171.3  458.51  5191.4  459.95  5220.7  460.73
#Mann=3,-1,0
  4726.3    0.05       0  4994.5    0.03       0  5000.5    0.05       0
Bank Sta=4990.8,5008.1
Exp/Cntr=0.3,0.1

Type RM Length L Ch R = 1,11020,175,175,175
BEGIN DESCRIPTION:
XS3263A
END DESCRIPTION:
XS GIS Cut Line= 3
      2802234.69      7043315.66      2802004.64      7043324.34
      2801800.66      7043391.61
#Sta/Elev= 30
  4749.9  458.30  4779.6  457.75  4809.6  456.53  4869.8  455.24  4919.7  454.75
  4934.6  454.02  4969.7  453.65  4977.4  452.84  4982.6  452.84  4990.3  452.05
  4996.9  450.36  4999.1  449.42  4999.6  448.62  5004.6  448.62  5005.1  449.42
  5021.9  450.24  5028.6  452.82  5033.9  450.53  5042.9  450.48  5053.4  450.76
  5060.4  452.91  5065.6  450.62  5074.5  452.28  5083.8  453.17  5090.4  454.02
  5137.5  456.76  5155.6  458.75  5160.9  458.64  5187.4  460.43  5194.9  460.47
#Mann=5,-1,0
  4749.9    0.05       0  4999.1    0.03       0  5005.1    0.05       0
  5083.8    0.07       0  5137.5    0.05       0
Bank Sta=4934.6,5090.4
Exp/Cntr=0.3,0.1

Type RM Length L Ch R = 1,10845,116,116,116
BEGIN DESCRIPTION:
XS3264A
END DESCRIPTION:
XS GIS Cut Line= 3
      2802267.18      7043174.60      2801967.75      7043159.41
      2801785.50      7043174.60
#Sta/Elev= 30
  4706.5  460.30  4710.1  460.30  4728.7  458.60  4768.8  456.34  4795.6  455.89
  4800.6  455.42  4838.8  454.94  4874.1  453.87  4949.0  452.80  4979.0  452.96
  4989.0  451.46  4991.4  448.77  4991.9  447.97  4996.9  447.97  4997.4  448.77
  5005.2  451.22  5013.7  451.31  5019.1  452.71  5039.2  453.02  5069.3  451.82
  5079.3  452.50  5089.4  451.94  5099.4  452.38  5111.0  453.87  5115.5  454.40
  5129.1  456.19  5134.2  456.22  5139.5  457.95  5159.6  458.97  5189.2  458.40
#Mann=4,-1,0
  4706.5    0.05       0  4991.4    0.07       0  4997.4    0.05       0
  5115.5    0.05       0
Bank Sta=4874.1,5111
Exp/Cntr=0.3,0.1

Type RM Length L Ch R = 1,10729,196,196,196
BEGIN DESCRIPTION:
XS3265A
END DESCRIPTION:
XS GIS Cut Line= 3
      2802265.03      7043079.11      2802019.83      7043046.56
      2801815.89      7043040.06
#Sta/Elev= 30
  4726.1  459.08  4756.4  457.94  4766.5  457.90  4776.6  457.09  4793.5  456.75
  4798.6  456.96  4806.8  456.31  4827.0  455.85  4879.5  453.34  4940.1  452.23
  4945.2  452.05  4950.2  452.33  4973.4  450.68  4988.3  450.11  4995.3  448.27
  4995.8  447.47  5000.8  447.47  5001.3  448.27  5008.3  451.81  5018.3  452.25
  5038.3  452.56  5058.3  452.17  5078.3  452.66  5098.3  452.28  5108.4  451.43
  5114.7  452.23  5118.4  452.70  5131.4  455.34  5148.4  457.47  5177.5  457.19
#Mann=5,-1,0
  4726.1    0.05       0  4879.5    0.16       0  4995.3    0.07       0
  5001.3    0.16       0  5131.4    0.05       0
Bank Sta=4940.1,5114.7
Exp/Cntr=0.3,0.1

Type RM Length L Ch R = 1,10533,233,233,233
BEGIN DESCRIPTION:
XS3266A
END DESCRIPTION:
XS GIS Cut Line= 3
      2802171.78      7042799.15      2802011.15      7042870.78
      2801833.17      7042968.46
#Sta/Elev= 30
  4818.7  458.85  4859.0  457.35  4872.6  456.42  4895.9  453.72  4902.8  453.37
  4947.8  452.08  4957.5  452.83  4972.5  451.61  4979.4  451.18  4988.8  448.41
  4990.6  447.18  4991.1  446.38  4996.1  446.38  4996.6  447.18  5010.5  448.62
  5019.9  449.16  5038.0  450.28  5054.1  449.39  5059.8  450.27  5070.0  451.10
  5075.9  451.53  5081.6  451.37  5092.0  452.25  5097.7  451.48  5098.6  451.61
  5104.3  452.38  5135.6  454.04  5162.4  455.04  5179.2  456.42  5197.6  456.64
#Mann=5,-1,0
  4818.7    0.05       0  4990.6    0.03       0  4996.6    0.05       0
  5019.9    0.12       0  5162.4    0.05       0
Bank Sta=4972.5,5098.6
Exp/Cntr=0.3,0.1

Type RM Length L Ch R = 1,10300,164,164,164
BEGIN DESCRIPTION:
XS3267A
END DESCRIPTION:
XS GIS Cut Line= 3
      2802019.86      7042560.43      2801865.75      7042692.83
      2801759.72      7042926.53
#Sta/Elev= 30
  4805.1  456.54  4854.1  455.53  4939.1  451.14  4945.9  451.10  4960.5  450.00
  4989.0  449.77  4996.1  448.26  5000.3  445.90  5000.8  445.10  5005.8  445.10
  5006.3  445.90  5008.3  446.71  5012.2  446.71  5019.2  449.07  5024.7  449.88
  5032.6  450.28  5069.9  449.76  5109.5  450.16  5145.6  449.54  5153.4  449.93
  5158.5  451.14  5163.2  452.28  5168.6  451.36  5186.2  452.90  5191.7  452.49
  5197.3  453.75  5208.3  454.31  5214.8  454.61  5220.3  453.96  5264.9  456.06
#Mann=5,-1,0
  4805.1    0.05       0  4945.9    0.16       0  5000.3    0.07       0
  5006.3    0.16       0  5069.9    0.05       0
Bank Sta=4939.1,5158.5
Exp/Cntr=0.3,0.1