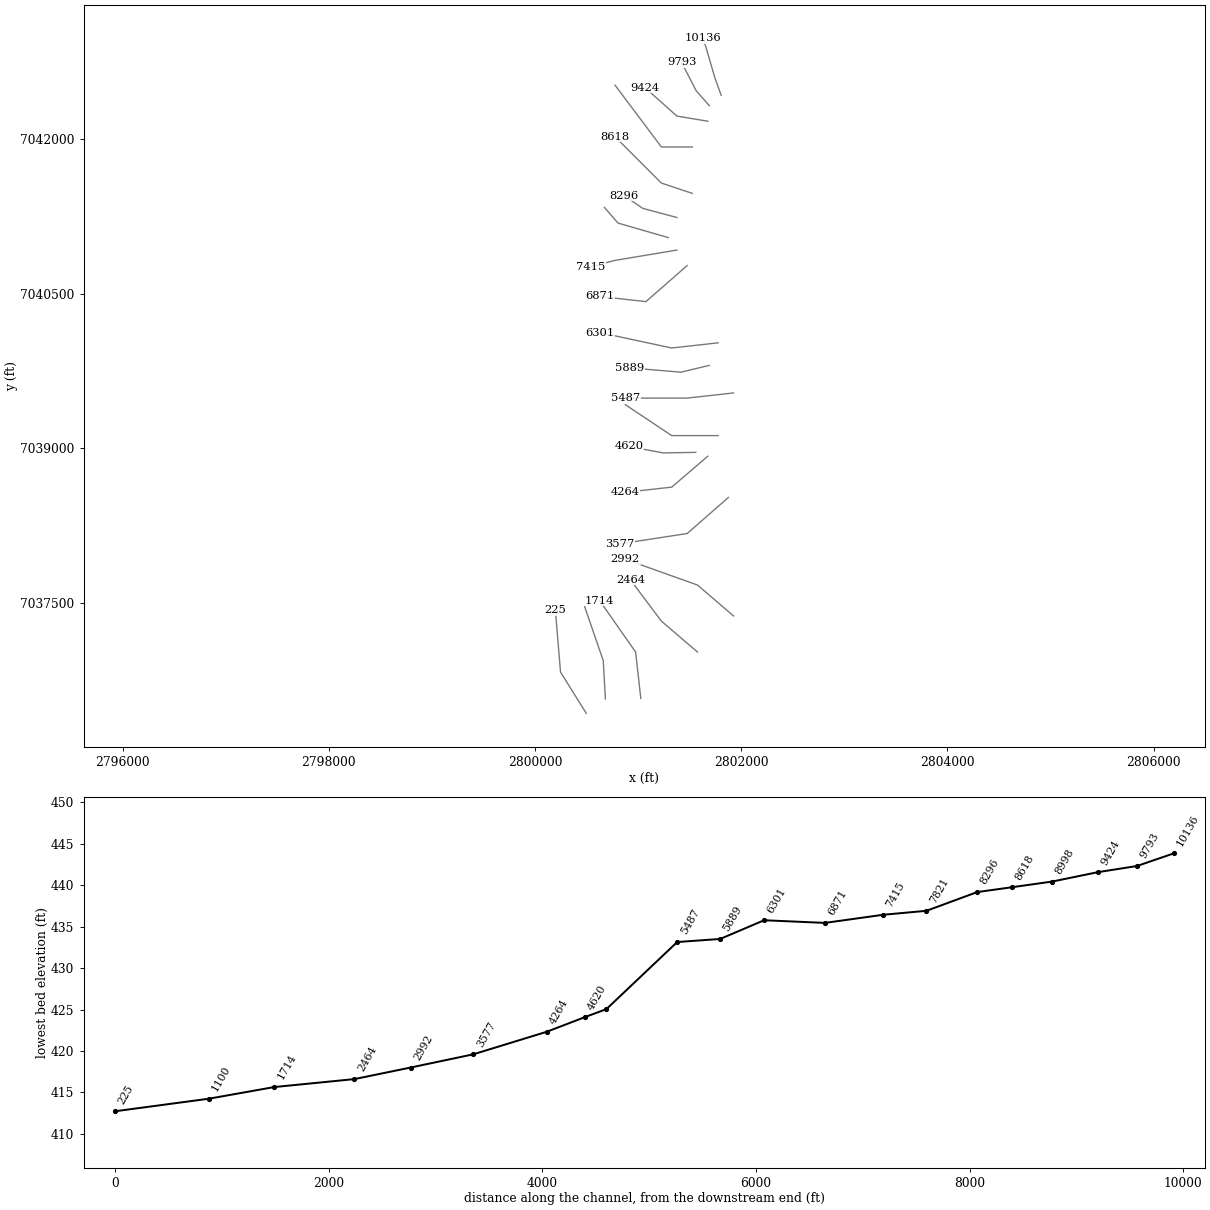
HEC-RAS study UNT 047 in LFCCL Watershed.prj: UNT 047 in LFCCL Watershed Base Level Engineering

--- UNT 047 in LFCCL Watershed.g01 (geometry) --- (continued)

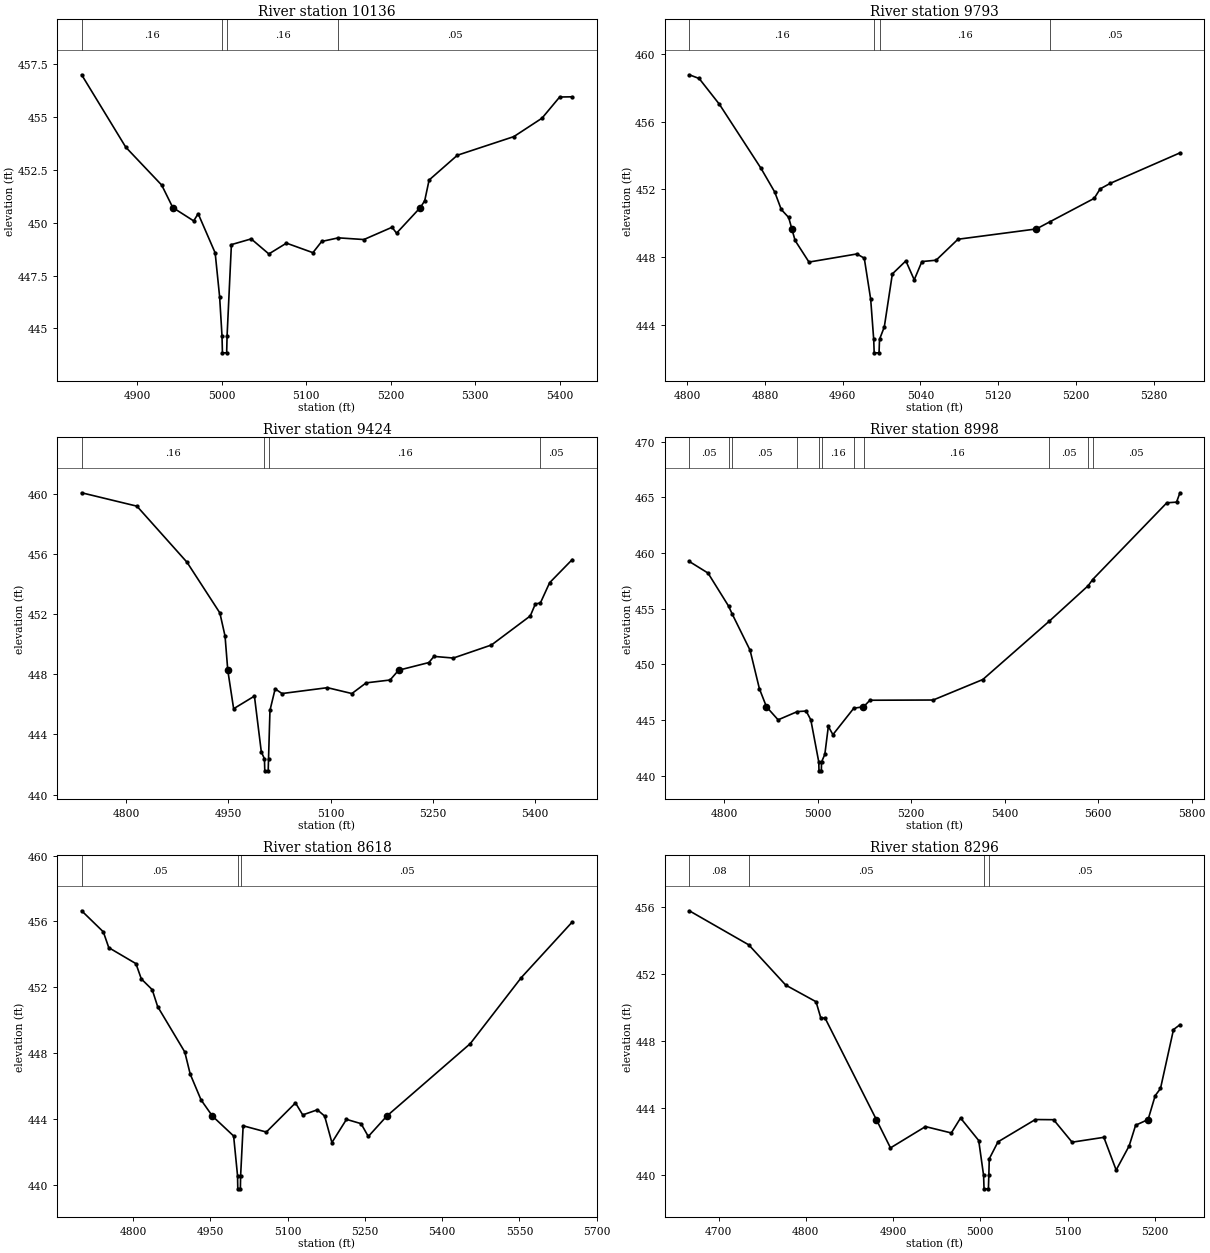
Type RM Length L Ch R = 1,10136,343,343,343
BEGIN DESCRIPTION:
XS3268A
END DESCRIPTION:
XS GIS Cut Line= 3
      2801804.99      7042425.90      2801744.22      7042595.18
      2801631.38      7042979.29
#Sta/Elev= 30
  4834.4  456.98  4886.6  453.56  4929.1  451.77  4942.2  450.71  4966.9  450.08
  4972.2  450.42  4992.3  448.57  4997.6  446.49  5000.4  444.65  5000.9  443.85
  5005.9  443.85  5006.4  444.65  5011.5  448.96  5034.9  449.23  5055.8  448.52
  5076.6  449.03  5107.9  448.58  5118.3  449.11  5138.0  449.28  5168.2  449.20
  5201.5  449.78  5206.8  449.50  5234.9  450.71  5240.1  451.03  5245.3  452.01
  5278.7  453.18  5345.5  454.06  5378.8  454.93  5399.7  455.93  5414.6  455.94
#Mann=4,-1,0
  4834.4    0.16       0  5000.4    0.07       0  5006.4    0.16       0
  5138.0    0.05       0
Bank Sta=4942.2,5234.9
Exp/Cntr=0.3,0.1

Type RM Length L Ch R = 1,9793,369,369,369
BEGIN DESCRIPTION:
XS3269A
END DESCRIPTION:
XS GIS Cut Line= 3
      2801689.96      7042326.09      2801561.93      7042471.48
      2801419.37      7042747.96
#Sta/Elev= 30
  4802.2  458.78  4812.3  458.56  4833.2  457.03  4875.9  453.25  4890.1  451.84
  4896.8  450.81  4904.4  450.34  4907.7  449.66  4911.0  448.98  4925.3  447.70
  4974.6  448.18  4982.2  447.93  4988.8  445.50  4991.9  443.13  4992.4  442.33
  4997.4  442.33  4997.9  443.13  5002.8  443.86  5011.1  447.00  5025.0  447.77
  5033.6  446.65  5041.5  447.73  5056.1  447.81  5078.6  449.05  5159.3  449.66
  5173.4  450.09  5218.8  451.47  5224.9  452.03  5235.4  452.36  5307.0  454.16
#Mann=4,-1,0
  4802.2    0.16       0  4991.9    0.07       0  4997.9    0.16       0
  5173.4    0.05       0
Bank Sta=4907.7,5159.3
Exp/Cntr=0.3,0.1

Type RM Length L Ch R = 1,9424,426,426,426
BEGIN DESCRIPTION:
UNT 047 in LFCCL Watershed 14.0
END DESCRIPTION:
XS GIS Cut Line= 3
      2801675.00      7042175.00      2801375.00      7042225.00
      2801064.97      7042501.86
#Sta/Elev= 30
  4734.6  460.07  4815.7  459.18  4889.2  455.45  4937.4  452.08  4945.0  450.54
  4949.0  448.27  4957.6  445.71  4988.1  446.55  4998.2  442.84  5002.8  442.38
  5003.3  441.58  5008.3  441.58  5008.8  442.38  5010.9  445.60  5018.5  447.03
  5028.6  446.72  5095.2  447.11  5131.1  446.72  5152.0  447.43  5187.1  447.62
  5199.6  448.27  5244.0  448.78  5251.5  449.19  5279.9  449.08  5335.9  449.95
  5392.8  451.88  5400.3  452.68  5407.6  452.74  5421.2  454.09  5454.4  455.63
#Mann=4,-1,0
  4734.6    0.16       0  5002.8    0.07       0  5008.8    0.16       0
  5407.6    0.05       0
Bank Sta=4949,5199.6
Exp/Cntr=0.3,0.1

Type RM Length L Ch R = 1,8998,380,380,380
BEGIN DESCRIPTION:
UNT 047 in LFCCL Watershed 13.0
END DESCRIPTION:
XS GIS Cut Line= 3
      2801525.01      7041925.00      2801225.00      7041925.00
      2800775.01      7042524.99
#Sta/Elev= 30
  4725.0  459.25  4765.0  458.21  4808.9  455.25  4816.9  454.52  4855.0  451.28
  4875.0  447.82  4890.1  446.20  4915.0  445.03  4956.1  445.77  4975.0  445.82
  4985.0  445.03  5002.0  441.25  5002.5  440.45  5007.5  440.45  5008.0  441.25
  5015.0  441.93  5022.5  444.44  5032.3  443.70  5076.9  446.07  5097.0  446.20
  5098.1  446.21  5111.5  446.79  5246.9  446.81  5353.1  448.65  5495.6  453.90
  5578.7  457.08  5588.2  457.63  5746.9  464.52  5767.7  464.58  5775.0  465.42
#Mann=11,-1,0
  4725.0    0.05       0  4808.9    0.16       0  4816.9    0.05       0
  4956.1    0.16       0  5002.0    0.07       0  5008.0    0.16       0
  5076.9    0.07       0  5098.1    0.16       0  5495.6    0.05       0
  5578.7    0.08       0  5588.2    0.05       0
Bank Sta=4890.1,5097
Exp/Cntr=0.3,0.1

Type RM Length L Ch R = 1,8618,322,322,322
BEGIN DESCRIPTION:
UNT 047 in LFCCL Watershed 12.0
END DESCRIPTION:
XS GIS Cut Line= 3
      2801524.98      7041475.01      2801225.00      7041575.00
      2800775.00      7042025.00
#Sta/Elev= 30
  4700.0  456.65  4742.1  455.37  4752.7  454.41  4805.4  453.44  4815.9  452.51
  4837.0  451.86  4847.6  450.83  4900.3  448.07  4910.8  446.73  4931.9  445.16
  4953.9  444.18  4995.1  442.97  5002.7  440.56  5003.2  439.76  5008.2  439.76
  5008.7  440.56  5013.6  443.59  5058.6  443.21  5115.2  444.98  5129.3  444.25
  5157.6  444.56  5171.8  444.18  5185.9  442.57  5214.2  443.98  5242.5  443.72
  5256.6  442.94  5292.5  444.18  5454.6  448.58  5553.6  452.59  5652.6  455.97
#Mann=3,-1,0
  4700.0    0.05       0  5002.7    0.03       0  5008.7    0.05       0
Bank Sta=4953.9,5292.5
Exp/Cntr=0.3,0.1

Type RM Length L Ch R = 1,8296,475,475,475
BEGIN DESCRIPTION:
XS3270A
END DESCRIPTION:
XS GIS Cut Line= 3
      2801375.26      7041241.02      2801043.27      7041329.99
      2800863.15      7041453.68
#Sta/Elev= 30
  4666.5  455.75  4734.6  453.72  4777.0  451.32  4811.7  450.33  4817.0  449.39
  4822.2  449.34  4880.8  443.31  4897.0  441.62  4937.1  442.89  4966.7  442.51
  4977.3  443.40  4998.1  442.06  5003.7  439.98  5004.2  439.18  5009.2  439.18
  5009.7  439.98  5010.2  440.97  5020.2  441.98  5063.0  443.31  5083.9  443.30
  5105.1  441.96  5141.5  442.25  5155.6  440.30  5170.5  441.74  5177.9  442.97
  5192.2  443.31  5200.3  444.73  5206.4  445.16  5221.3  448.67  5228.7  448.96
#Mann=4,-1,0
  4666.5    0.08       0  4734.6    0.05       0  5003.7    0.03       0
  5009.7    0.05       0
Bank Sta=4880.8,5192.2
Exp/Cntr=0.3,0.1

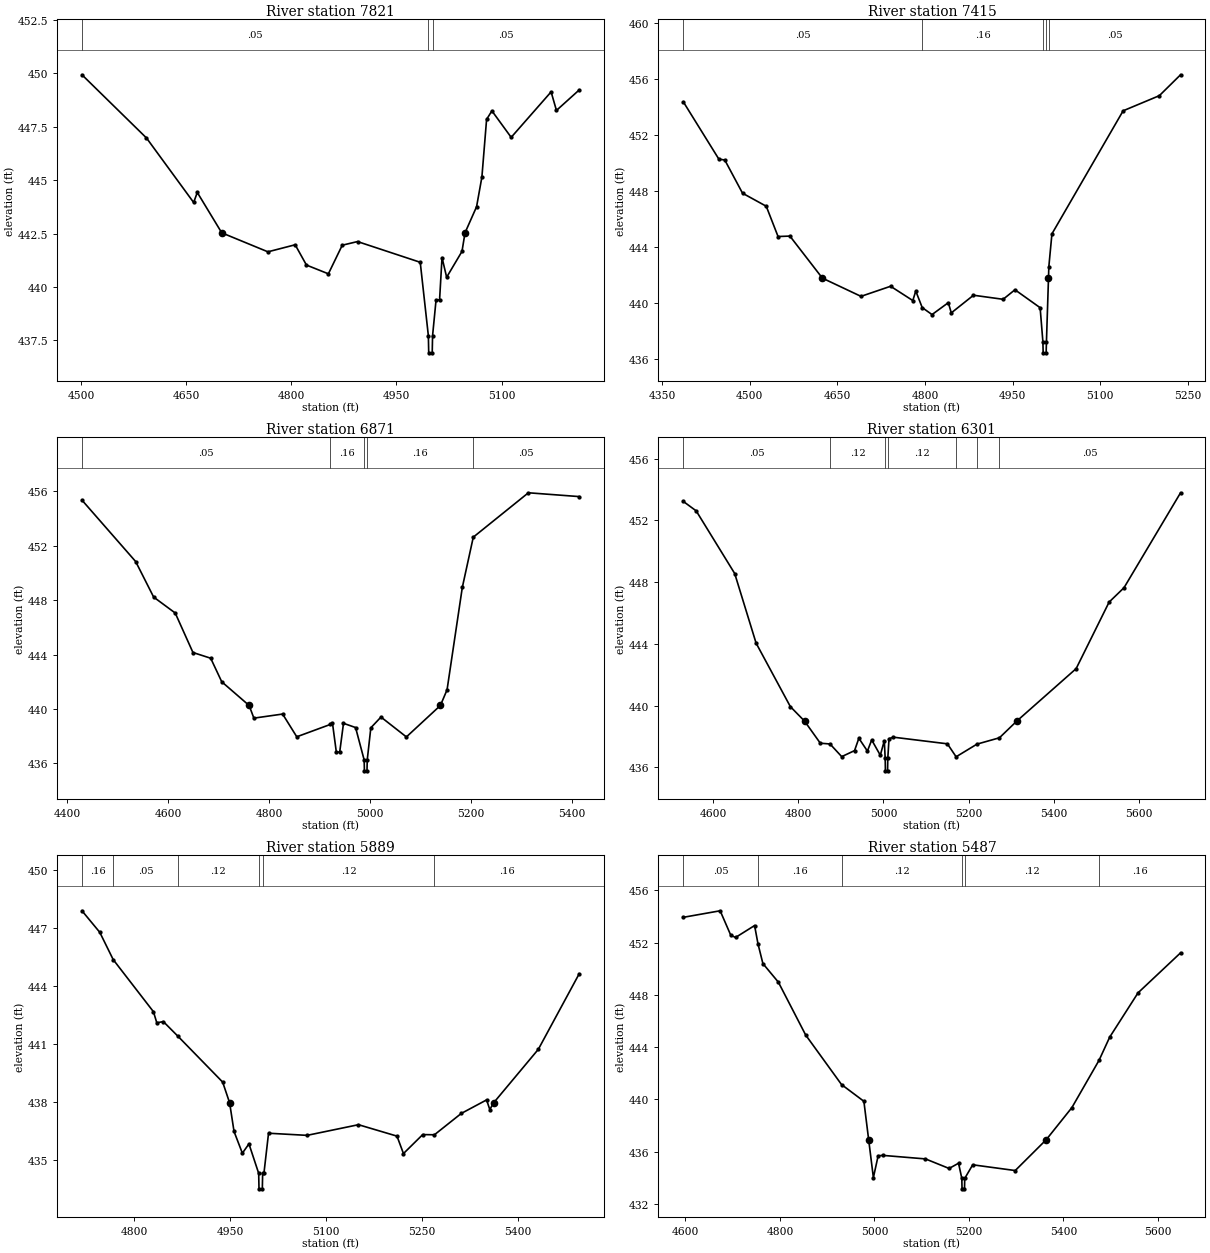
Type RM Length L Ch R = 1,7821,406,406,406
BEGIN DESCRIPTION:
XS3271A
END DESCRIPTION:
XS GIS Cut Line= 3
      2801292.84      7041045.70      2800804.55      7041186.76
      2800672.21      7041338.63
#Sta/Elev= 30
  4501.2  449.94  4593.3  446.98  4660.6  443.96  4665.8  444.43  4700.7  442.54
  4766.6  441.65  4805.5  441.98  4821.6  441.03  4852.9  440.62  4872.7  441.96
  4894.5  442.13  4984.0  441.16  4995.6  437.72  4996.1  436.92  5001.1  436.92
  5001.6  437.72  5006.6  439.40  5011.6  439.40  5015.1  441.38  5021.7  440.46
  5043.6  441.67  5047.9  442.54  5064.4  443.76  5072.0  445.15  5078.7  447.85
  5086.3  448.25  5113.8  447.01  5170.8  449.14  5178.4  448.27  5210.9  449.23
#Mann=3,-1,0
  4501.2    0.05       0  4995.6    0.03       0  5001.6    0.05       0
Bank Sta=4700.7,5047.9
Exp/Cntr=0.3,0.1

Type RM Length L Ch R = 1,7415,544,544,544
BEGIN DESCRIPTION:
UNT 047 in LFCCL Watershed 11.0
END DESCRIPTION:
XS GIS Cut Line= 3
      2801375.04      7040925.01      2800775.00      7040825.00
      2800539.90      7040763.61
#Sta/Elev= 30
  4386.4  454.35  4447.3  450.26  4457.4  450.20  4487.8  447.83  4528.4  446.90
  4548.6  444.74  4568.9  444.77  4624.5  441.77  4690.6  440.47  4741.3  441.19
  4779.3  440.17  4784.4  440.85  4795.4  439.67  4812.2  439.17  4840.1  440.02
  4845.2  439.29  4883.2  440.55  4933.9  440.26  4954.2  440.94  4997.3  439.66
  5002.0  437.24  5002.5  436.44  5007.6  436.44  5008.1  437.24  5011.6  441.76
  5012.2  442.59  5017.5  444.93  5139.4  453.71  5201.4  454.79  5237.7  456.28
#Mann=5,-1,0
  4386.4    0.05       0  4795.4    0.16       0  5002.0    0.07       0
  5008.1    0.16       0  5012.2    0.05       0
Bank Sta=4624.5,5011.6
Exp/Cntr=0.3,0.1

Type RM Length L Ch R = 1,6871,570,570,570
BEGIN DESCRIPTION:
UNT 047 in LFCCL Watershed 10.0
END DESCRIPTION:
XS GIS Cut Line= 3
      2801475.00      7040775.00      2801075.00      7040425.00
      2800624.97      7040475.00
#Sta/Elev= 30
  4429.4  455.34  4535.7  450.83  4571.3  448.22  4614.0  447.05  4649.1  444.15
  4684.2  443.73  4706.1  442.00  4760.3  440.26  4769.7  439.33  4826.6  439.63
  4854.6  437.96  4921.2  438.87  4925.3  438.96  4932.9  436.84  4939.6  436.84
  4947.1  438.95  4971.0  438.64  4988.0  436.26  4988.5  435.46  4993.6  435.46
  4994.1  436.26  5001.2  438.62  5021.3  439.41  5071.6  437.95  5138.9  440.26
  5152.1  441.41  5182.3  448.93  5204.0  452.62  5313.1  455.88  5413.7  455.60
#Mann=5,-1,0
  4429.4    0.05       0  4921.2    0.16       0  4988.0    0.07       0
  4994.1    0.16       0  5204.0    0.05       0
Bank Sta=4760.3,5138.9
Exp/Cntr=0.3,0.1

Type RM Length L Ch R = 1,6301,412,412,412
BEGIN DESCRIPTION:
UNT 047 in LFCCL Watershed 9.0
END DESCRIPTION:
XS GIS Cut Line= 3
      2801775.05      7040025.01      2801325.00      7039975.00
      2800625.01      7040125.00
#Sta/Elev= 30
  4529.6  453.23  4559.8  452.62  4650.4  448.56  4700.7  444.05  4781.2  439.94
  4814.6  439.00  4851.6  437.57  4874.4  437.52  4901.9  436.70  4932.1  437.09
  4942.2  437.89  4962.3  437.06  4972.4  437.78  4992.6  436.79  5002.0  437.73
  5004.1  436.58  5004.6  435.78  5009.7  435.78  5010.2  436.58  5013.1  437.86
  5023.3  437.96  5150.3  437.53  5170.8  436.69  5219.8  437.51  5272.6  437.92
  5313.3  439.00  5452.9  442.40  5530.4  446.71  5565.4  447.64  5698.3  453.79
#Mann=7,-1,0
  4529.6    0.05       0  4874.4    0.12       0  5004.1    0.07       0
  5010.2    0.12       0  5170.8    0.16       0  5219.8     0.1       0
  5272.6    0.05       0
Bank Sta=4814.6,5313.3
Exp/Cntr=0.3,0.1

Type RM Length L Ch R = 1,5889,402,402,402
BEGIN DESCRIPTION:
XS3272A
END DESCRIPTION:
XS GIS Cut Line= 3
      2801688.68      7039806.12      2801414.36      7039740.14
      2800921.36      7039781.80
#Sta/Elev= 30
  4718.3  447.87  4746.1  446.76  4767.1  445.35  4830.0  442.66  4835.2  442.09
  4845.5  442.15  4868.4  441.39  4938.1  439.03  4949.0  437.96  4955.9  436.48
  4968.9  435.36  4979.2  435.84  4994.4  434.32  4994.9  433.52  5000.1  433.52
  5000.6  434.32  5002.6  434.32  5009.8  436.39  5070.0  436.28  5150.3  436.83
  5210.5  436.24  5220.6  435.34  5250.7  436.32  5269.0  436.31  5310.9  437.41
  5350.5  438.11  5355.5  437.61  5361.5  437.96  5431.3  440.72  5495.2  444.62
#Mann=6,-1,0
  4718.3    0.16       0  4767.1    0.05       0  4868.4    0.12       0
  4994.4    0.07       0  5000.6    0.12       0  5269.0    0.16       0
Bank Sta=4949,5361.5
Exp/Cntr=0.3,0.1

Type RM Length L Ch R = 1,5487,663,663,663
BEGIN DESCRIPTION:
UNT 047 in LFCCL Watershed 8.0
END DESCRIPTION:
XS GIS Cut Line= 3
      2801924.98      7039538.89      2801475.00      7039488.89
      2800875.05      7039488.89
#Sta/Elev= 30
  4595.4  453.93  4673.4  454.43  4696.0  452.55  4706.1  452.39  4746.3  453.30
  4753.5  451.90  4763.9  450.39  4796.6  448.97  4854.5  444.92  4930.4  441.13
  4977.7  439.85  4987.8  436.91  4997.8  434.01  5007.9  435.68  5018.0  435.71
  5108.1  435.44  5158.1  434.71  5178.1  435.11  5185.0  433.95  5185.5  433.15
  5190.7  433.15  5191.2  433.95  5208.1  434.99  5298.1  434.55  5363.7  436.91
  5418.1  439.37  5475.6  442.99  5498.1  444.76  5558.1  448.15  5648.1  451.21
#Mann=6,-1,0
  4595.4    0.05       0  4753.5    0.16       0  4930.4    0.12       0
  5185.0    0.07       0  5191.2    0.12       0  5475.6    0.16       0
Bank Sta=4987.8,5363.7
Exp/Cntr=0.3,0.1

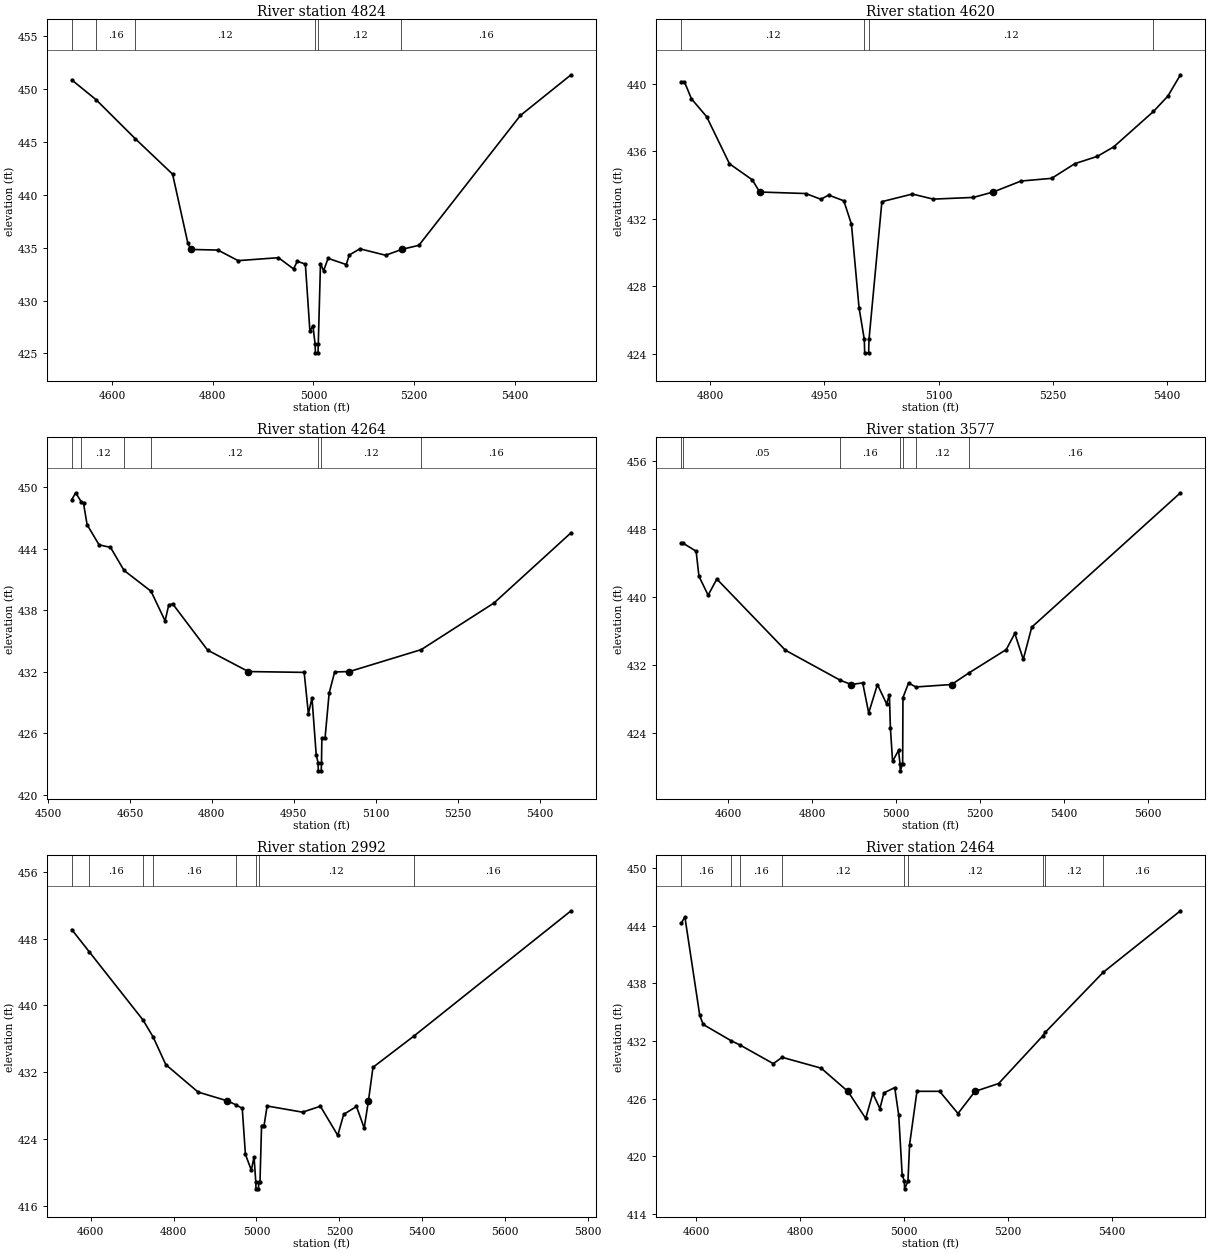
Type RM Length L Ch R = 1,4824,204,204,204
BEGIN DESCRIPTION:
UNT 047 in LFCCL Watershed 7.0
END DESCRIPTION:
XS GIS Cut Line= 3
      2801774.98      7039125.00      2801325.00      7039125.00
      2800875.01      7039424.99
#Sta/Elev= 30
  4520.5  450.86  4568.7  448.99  4646.7  445.29  4720.5  441.95  4750.5  435.48
  4756.7  434.83  4810.5  434.77  4850.5  433.77  4930.5  434.05  4960.5  432.99
  4968.0  433.71  4984.0  433.44  4993.0  427.11  4999.0  427.61  5003.4  425.85
  5003.9  425.05  5009.1  425.05  5009.6  425.85  5014.0  433.50  5020.1  432.81
  5029.1  433.99  5065.1  433.40  5071.1  434.30  5092.2  434.89  5143.2  434.28
  5173.5  434.80  5174.8  434.83  5209.3  435.22  5410.7  447.50  5511.3  451.35
#Mann=6,-1,0
  4520.5    0.05       0  4568.7    0.16       0  4646.7    0.12       0
  5003.4    0.07       0  5009.6    0.12       0  5173.5    0.16       0
Bank Sta=4756.7,5174.8
Exp/Cntr=0.3,0.1

Type RM Length L Ch R = 1,4620,356,356,356
BEGIN DESCRIPTION:
XS3275A
END DESCRIPTION:
XS GIS Cut Line= 3
      2801558.43      7038962.36      2801240.75      7038957.16
      2800908.76      7039019.40
#Sta/Elev= 30
  4762.1  440.12  4766.3  440.12  4775.5  439.11  4795.5  438.05  4825.5  435.26
  4855.5  434.31  4865.1  433.59  4925.6  433.50  4945.6  433.16  4955.6  433.41
  4975.6  433.07  4985.6  431.69  4995.6  426.74  5002.5  424.87  5003.0  424.07
  5008.2  424.07  5008.7  424.87  5025.6  433.02  5065.6  433.47  5093.0  433.17
  5145.6  433.27  5171.7  433.59  5208.3  434.24  5248.5  434.40  5279.0  435.27
  5308.4  435.70  5329.9  436.26  5382.2  438.36  5401.1  439.27  5417.6  440.53
#Mann=4,-1,0
  4762.1    0.12       0  5002.5    0.07       0  5008.7    0.12       0
  5382.2    0.16       0
Bank Sta=4865.1,5171.7
Exp/Cntr=0.3,0.1

Type RM Length L Ch R = 1,4264,687,687,687
BEGIN DESCRIPTION:
UNT 047 in LFCCL Watershed 6.0
END DESCRIPTION:
XS GIS Cut Line= 3
      2801675.00      7038925.00      2801325.00      7038625.00
      2800874.95      7038574.99
#Sta/Elev= 30
  4543.7  448.78  4550.8  449.45  4560.8  448.58  4565.1  448.42  4571.7  446.33
  4593.6  444.37  4614.5  444.12  4639.3  441.87  4688.7  439.84  4714.4  436.95
  4721.0  438.47  4728.1  438.62  4792.3  434.09  4866.8  432.00  4969.0  431.92
  4976.7  427.88  4983.3  429.42  4991.0  423.89  4994.4  423.11  4994.9  422.31
  5000.2  422.31  5000.7  423.11  5001.4  425.51  5007.2  425.51  5014.7  429.90
  5024.8  431.96  5051.8  432.00  5183.2  434.14  5316.6  438.70  5457.5  445.55
#Mann=7,-1,0
  4543.7    0.16       0  4560.8    0.12       0  4639.3    0.16       0
  4688.7    0.12       0  4994.4    0.07       0  5000.7    0.12       0
  5183.2    0.16       0
Bank Sta=4866.8,5051.8
Exp/Cntr=0.3,0.1

Type RM Length L Ch R = 1,3577,585,585,585
BEGIN DESCRIPTION:
UNT 047 in LFCCL Watershed 5.0
END DESCRIPTION:
XS GIS Cut Line= 3
      2801875.00      7038525.00      2801475.00      7038175.00
      2800824.95      7038074.99
#Sta/Elev= 30
  4488.6  446.39  4491.8  446.39  4524.2  445.41  4530.8  442.48  4552.7  440.24
  4573.5  442.14  4736.8  433.77  4867.5  430.24  4893.6  429.74  4920.9  429.93
  4935.2  426.40  4956.0  429.73  4977.9  427.46  4984.5  428.54  4986.9  424.63
  4992.1  420.71  5006.3  422.00  5009.8  420.39  5010.3  419.59  5016.1  420.39
  5016.8  428.20  5030.2  429.92  5047.4  429.45  5132.7  429.74  5173.6  431.09
  5262.9  433.85  5283.2  435.74  5303.4  432.70  5323.6  436.48  5677.8  452.28
#Mann=7,-1,0
  4488.6    0.16       0  4491.8    0.05       0  4867.5    0.16       0
  5009.8    0.07       0  5016.1    0.16       0  5047.4    0.12       0
  5173.6    0.16       0
Bank Sta=4893.6,5132.7
Exp/Cntr=0.3,0.1

Type RM Length L Ch R = 1,2992,528,528,528
BEGIN DESCRIPTION:
UNT 047 in LFCCL Watershed 4.0
END DESCRIPTION:
XS GIS Cut Line= 3
      2801925.04      7037374.97      2801575.00      7037675.00
      2800875.03      7037924.99
#Sta/Elev= 30
  4554.6  449.07  4596.4  446.43  4726.3  438.24  4750.9  436.19  4781.3  432.89
  4859.2  429.60  4929.5  428.55  4949.8  428.09  4965.7  427.65  4973.4  422.13
  4987.6  420.24  4994.2  421.83  4998.4  418.80  4998.9  418.00  5004.9  418.00
  5005.4  418.80  5008.5  418.84  5012.3  425.59  5018.3  425.59  5025.7  427.93
  5111.2  427.19  5154.2  427.90  5196.1  424.41  5210.5  426.93  5241.3  427.87
  5259.9  425.28  5270.1  428.55  5281.1  432.57  5379.7  436.31  5758.9  451.33
#Mann=8,-1,0
  4554.6    0.05       0  4596.4    0.16       0  4726.3    0.12       0
  4750.9    0.16       0  4949.8    0.12       0  4998.4    0.07       0
  5005.4    0.12       0  5379.7    0.16       0
Bank Sta=4929.5,5270.1
Exp/Cntr=0.3,0.1

Type RM Length L Ch R = 1,2464,750,750,750
BEGIN DESCRIPTION:
UNT 047 in LFCCL Watershed 3.0
END DESCRIPTION:
XS GIS Cut Line= 3
      2801575.00      7037025.00      2801225.00      7037325.00
      2800924.98      7037725.02
#Sta/Elev= 30
  4570.7  444.24  4577.8  444.90  4606.4  434.65  4613.0  433.71  4666.6  432.02
  4684.6  431.55  4748.0  429.63  4764.9  430.29  4840.1  429.16  4891.6  426.74
  4925.8  423.93  4939.5  426.53  4953.2  424.96  4960.9  426.58  4981.7  427.14
  4989.4  424.26  4996.0  418.09  5000.1  417.40  5000.7  416.60  5007.2  417.40
  5010.3  421.20  5024.5  426.75  5068.1  426.75  5103.5  424.44  5136.2  426.74
  5181.7  427.56  5266.7  432.52  5271.3  432.88  5382.9  439.13  5531.7  445.54
#Mann=9,-1,0
  4570.7    0.16       0  4666.6    0.12       0  4684.6    0.16       0
  4764.9    0.12       0  5000.1    0.07       0  5007.2    0.12       0
  5266.7    0.16       0  5271.3    0.12       0  5382.9    0.16       0
Bank Sta=4891.6,5136.2
Exp/Cntr=0.3,0.1

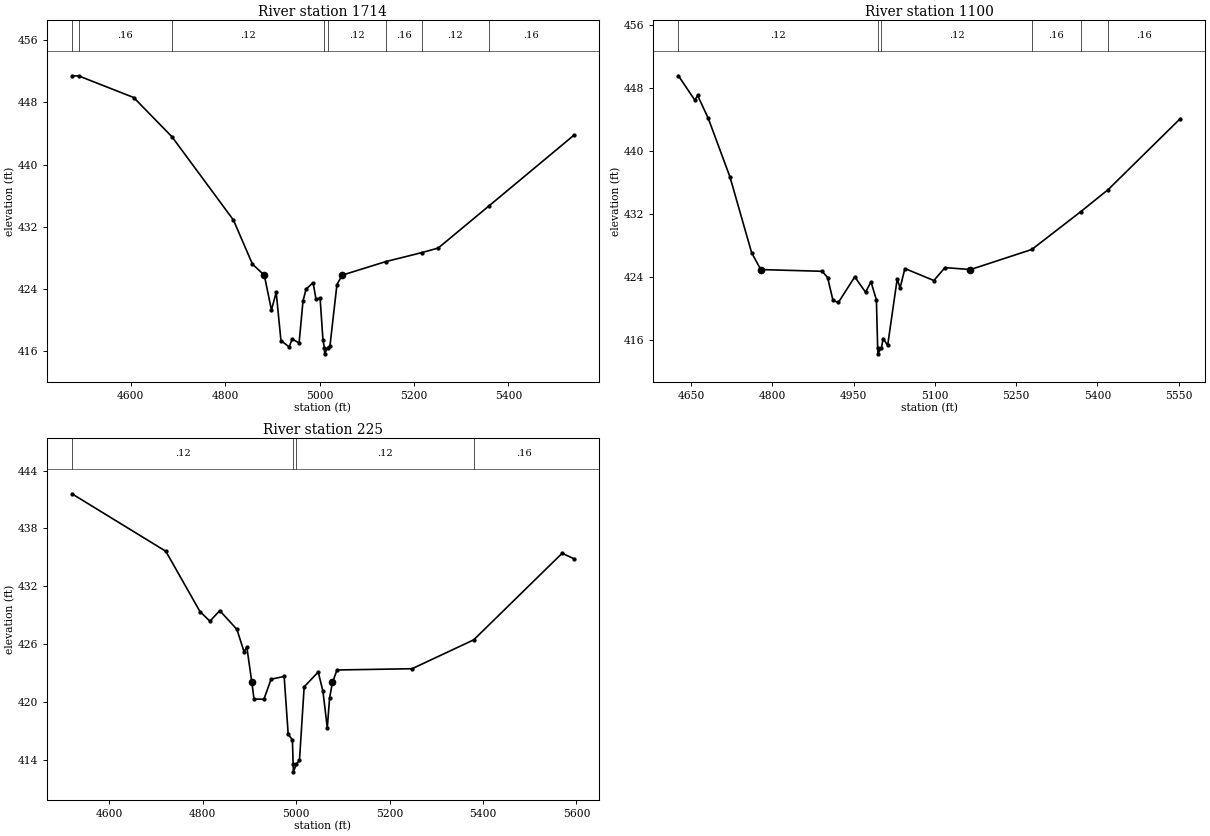
Type RM Length L Ch R = 1,1714,614,614,614
BEGIN DESCRIPTION:
UNT 047 in LFCCL Watershed 2.0
END DESCRIPTION:
XS GIS Cut Line= 3
      2801025.00      7036575.00      2800975.00      7037025.00
      2800625.00      7037525.00
#Sta/Elev= 30
  4475.4  451.44  4489.8  451.42  4606.2  448.64  4687.1  443.60  4817.5  432.86
  4857.7  427.19  4882.8  425.77  4898.0  421.28  4908.0  423.56  4918.1  417.35
  4935.6  416.52  4941.7  417.56  4956.5  417.03  4964.8  422.44  4971.3  423.98
  4986.2  424.80  4992.3  422.69  5001.0  422.83  5007.1  417.39  5010.1  416.44
  5010.6  415.64  5017.2  416.44  5021.9  416.66  5036.7  424.56  5047.8  425.77
  5139.8  427.51  5216.9  428.68  5251.2  429.26  5358.4  434.67  5538.5  443.78
#Mann=8,-1,0
  4475.4    0.05       0  4489.8    0.16       0  4687.1    0.12       0
  5010.1    0.07       0  5017.2    0.12       0  5139.8    0.16       0
  5216.9    0.12       0  5358.4    0.16       0
Bank Sta=4882.8,5047.8
Exp/Cntr=0.3,0.1

Type RM Length L Ch R = 1,1100,875,875,875
BEGIN DESCRIPTION:
XS3273A
END DESCRIPTION:
XS GIS Cut Line= 3
      2800681.72      7036570.03      2800660.89      7036941.53
      2800480.34      7037465.83
#Sta/Elev= 30
  4626.4  449.50  4656.8  446.40  4661.8  447.01  4681.5  444.10  4721.5  436.68
  4761.6  427.05  4778.4  424.92  4891.8  424.70  4901.8  423.91  4911.8  421.00
  4921.8  420.75  4951.9  424.00  4971.9  422.04  4981.9  423.37  4991.9  421.08
  4994.2  415.03  4994.7  414.23  5001.3  415.03  5004.3  416.17  5012.7  415.30
  5030.3  423.73  5035.6  422.57  5044.5  425.05  5098.0  423.53  5118.5  425.17
  5165.6  424.92  5278.9  427.47  5369.1  432.26  5419.9  435.07  5553.0  444.07
#Mann=6,-1,0
  4626.4    0.12       0  4994.2    0.07       0  5001.3    0.12       0
  5278.9    0.16       0  5369.1    0.12       0  5419.9    0.16       0
Bank Sta=4778.4,5165.6
Exp/Cntr=0.3,0.1

Type RM Length L Ch R = 1,225,0,0,0
BEGIN DESCRIPTION:
UNT 047 in LFCCL Watershed 1.0
END DESCRIPTION:
XS GIS Cut Line= 3
      2800496.56      7036429.97      2800246.55      7036829.98
      2800196.55      7037429.99
#Sta/Elev= 30
  4520.6  441.60  4721.4  435.63  4794.5  429.37  4815.7  428.37  4836.9  429.46
  4873.5  427.52  4888.8  425.19  4894.7  425.69  4905.5  422.01  4910.1  420.28
  4931.3  420.26  4946.6  422.34  4974.6  422.63  4983.2  416.64  4992.3  416.03
  4993.8  413.52  4994.3  412.72  5000.9  413.52  5007.4  413.93  5017.4  421.55
  5047.5  423.09  5057.6  421.08  5066.9  417.29  5071.9  420.44  5078.0  422.01
  5087.7  423.30  5248.2  423.43  5380.2  426.43  5569.3  435.42  5594.4  434.86
#Mann=4,-1,0
  4520.6    0.12       0  4993.8    0.07       0  5000.9    0.12       0
  5380.2    0.16       0
Bank Sta=4905.5,5078
Exp/Cntr=0.3,0.1

Chan Stop Cuts=-1