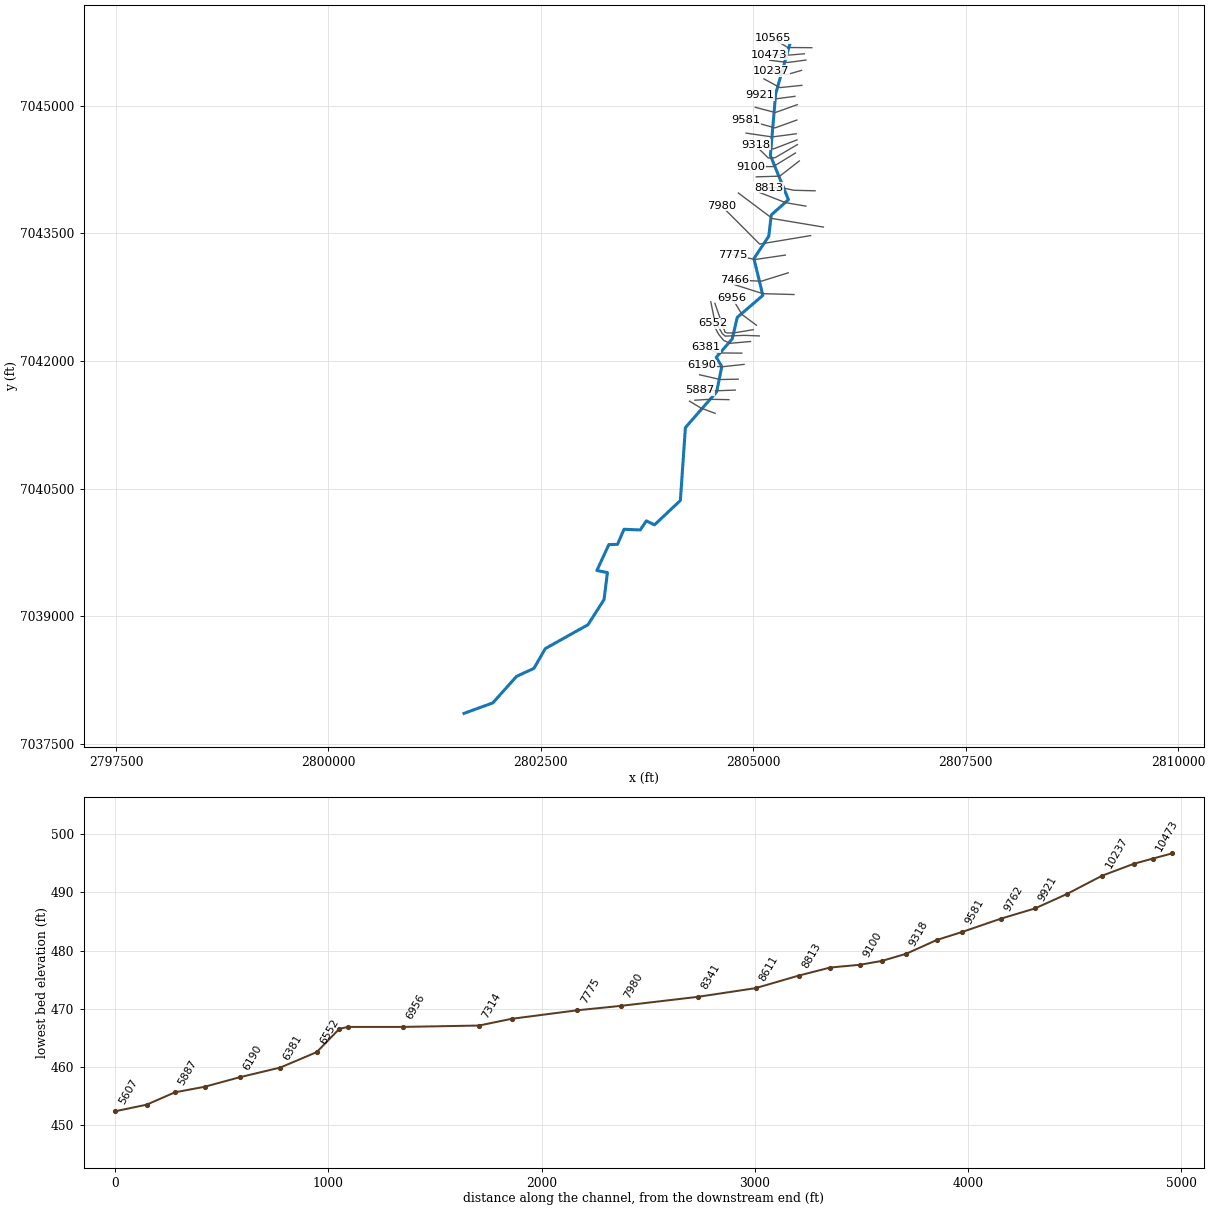
--- UNT 048 in LFCCL Watershed.prj (project) ---

Proj Title=UNT 048 in LFCCL Watershed Base Level Engineering
Current Plan=p01
Default Exp/Contr=0.3,0.1
English Units
Geom File=g01
Flow File=f01
Plan File=p01
BEGIN DESCRIPTION:
UNT 048 in LFCCL Watershed
END DESCRIPTION:

--- UNT 048 in LFCCL Watershed.p01 (plan) ---

Plan Title=Multiple Run
Short Identifier=Multiple
Geom File=g01
Flow File=f01
Subcritical Flow
K Sum by GR= 0
Std Step Tol= 0.01
Critical Tol= 0.01
Num of Std Step Trials= 20
Max Error Tol= 0.3
Flow Tol Ratio= 0.001
Split Flow NTrial= 30
Split Flow Tol= 0.02
Split Flow Ratio= 0.02
Log Output Level= 0
Friction Slope Method= 1
Unsteady Friction Slope Method= 2
Unsteady Bridges Friction Slope Method= 1
Parabolic Critical Depth
Global Vel Dist=  1 , 1 , 1
Global Log Level= 0
CheckData=True
Encroach Param= -1, 0, 0, 0
BEGIN DESCRIPTION:
Multiple Run
END DESCRIPTION:

--- UNT 048 in LFCCL Watershed.f01 (steady flow) ---

Flow Title=Multiple
Number of Profiles=7
Profile Names=10-year,25-year,50-year,1pct_min,100-year,1pct_plu,500-year
River Rch & RM= UNT 048 in LFCCL,Reach-1,10565
     292     372     434     253     504    1006     678
River Rch & RM= UNT 048 in LFCCL,Reach-1,3237
     392     510     603     355     708    1413     976
Boundary for River Rch & Prof#=UNT 048 in LFCCL,Reach-1,1
Up Type=0
Dn Type=3
Dn Slope=0.005
Boundary for River Rch & Prof#=UNT 048 in LFCCL,Reach-1,2
Up Type=0
Dn Type=3
Dn Slope=0.005
Boundary for River Rch & Prof#=UNT 048 in LFCCL,Reach-1,3
Up Type=0
Dn Type=3
Dn Slope=0.005
Boundary for River Rch & Prof#=UNT 048 in LFCCL,Reach-1,4
Up Type=0
Dn Type=3
Dn Slope=0.005
Boundary for River Rch & Prof#=UNT 048 in LFCCL,Reach-1,5
Up Type=0
Dn Type=3
Dn Slope=0.005
Boundary for River Rch & Prof#=UNT 048 in LFCCL,Reach-1,6
Up Type=0
Dn Type=3
Dn Slope=0.005
Boundary for River Rch & Prof#=UNT 048 in LFCCL,Reach-1,7
Up Type=0
Dn Type=3
Dn Slope=0.005

--- UNT 048 in LFCCL Watershed.g01 (geometry) ---

Geom Title=Existing Conditions

River Reach=UNT 048 in LFCCL,Reach-1
Reach XY= 30
      2805429.04      7045721.01      2805263.10      7045140.28
      2805201.25      7044416.54      2805413.65      7043896.78
      2805211.40      7043717.76      2805182.76      7043468.14
      2805007.74      7043204.82      2805112.06      7042772.17
      2804811.04      7042513.41      2804752.57      7042261.70
      2804563.85      7042043.78      2804629.68      7041936.62
      2804568.45      7041638.10      2804201.09      7041218.89
      2804142.06      7040362.22      2803837.65      7040076.12
      2803741.61      7040122.62      2803669.24      7040015.83
      2803478.63      7040024.29      2803402.25      7039847.13
      2803300.46      7039843.90      2803159.55      7039539.16
      2803283.60      7039515.46      2803243.21      7039196.53
      2803054.32      7038902.00      2802552.31      7038621.77
      2802419.03      7038389.74      2802213.99      7038295.43
      2801934.44      7037983.40      2801595.59      7037860.71

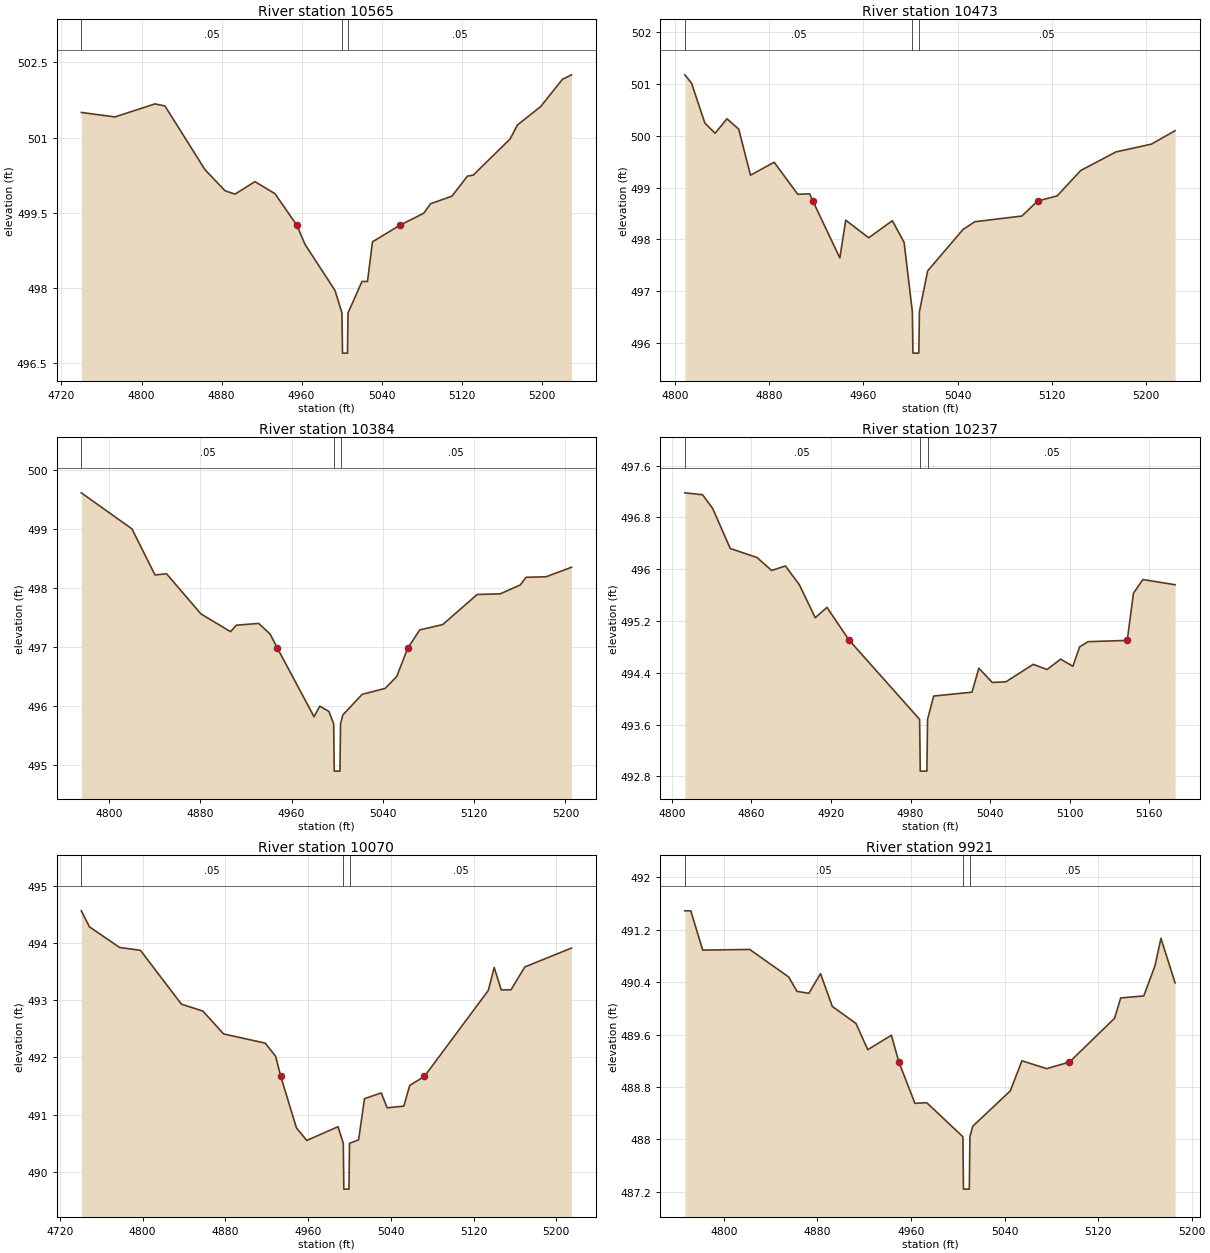
Type RM Length L Ch R = 1,10565,92,92,92
BEGIN DESCRIPTION:
XS3276A
END DESCRIPTION:
XS GIS Cut Line= 3
      2805688.58      7045682.79      2805405.98      7045684.83
      2805228.87      7045792.73
#Sta/Elev= 30
  4739.8  501.50  4773.4  501.41  4813.4  501.67  4823.4  501.63  4863.4  500.36
  4883.4  499.94  4893.4  499.87  4913.4  500.12  4933.4  499.88  4955.3  499.25
  4963.4  498.87  4993.4  497.95  5000.4  497.50  5000.9  496.70  5005.9  496.70
  5006.4  497.50  5020.4  498.13  5025.9  498.13  5030.9  498.92  5058.3  499.25
  5082.1  499.49  5089.0  499.68  5110.3  499.83  5125.8  500.23  5131.6  500.25
  5168.4  500.97  5175.8  501.25  5199.2  501.62  5220.7  502.16  5229.8  502.25
#Mann=3,-1,0
  4739.8    0.05       0  5000.4    0.03       0  5006.4    0.05       0
Bank Sta=4955.3,5058.3
Exp/Cntr=0.3,0.1

Type RM Length L Ch R = 1,10473,89,89,89
BEGIN DESCRIPTION:
XS3278A
END DESCRIPTION:
XS GIS Cut Line= 3
      2805600.55      7045611.10      2805430.56      7045596.76
      2805184.76      7045598.81
#Sta/Elev= 30
  4808.4  501.18  4814.0  501.02  4825.3  500.25  4834.0  500.05  4844.1  500.33
  4854.1  500.13  4864.1  499.24  4884.2  499.49  4904.3  498.87  4914.3  498.88
  4917.1  498.74  4940.0  497.64  4945.0  498.37  4964.5  498.03  4984.6  498.36
  4994.6  497.94  5001.6  496.60  5002.1  495.80  5007.1  495.80  5007.6  496.60
  5014.6  497.39  5044.6  498.19  5054.6  498.34  5094.6  498.45  5108.0  498.74
  5124.6  498.84  5144.6  499.33  5174.6  499.69  5204.6  499.84  5224.8  500.10
#Mann=3,-1,0
  4808.4    0.05       0  5001.6    0.03       0  5007.6    0.05       0
Bank Sta=4917.1,5108
Exp/Cntr=0.3,0.1

Type RM Length L Ch R = 1,10384,147,147,147
BEGIN DESCRIPTION:
XS3277A
END DESCRIPTION:
XS GIS Cut Line= 3
      2805619.03      7045537.37      2805403.93      7045508.70
      2805193.01      7045535.32
#Sta/Elev= 30
  4775.7  499.61  4820.1  499.00  4840.3  498.22  4850.4  498.24  4880.6  497.56
  4906.5  497.26  4911.6  497.37  4931.1  497.40  4941.2  497.22  4947.6  496.98
  4979.7  495.82  4984.7  496.00  4992.7  495.91  4996.9  495.70  4997.4  494.90
  5002.4  494.90  5002.9  495.70  5004.9  495.85  5021.9  496.20  5042.0  496.30
  5052.1  496.50  5061.8  496.98  5072.3  497.29  5092.4  497.38  5122.7  497.89
  5142.8  497.90  5160.4  498.05  5165.4  498.18  5183.1  498.19  5205.3  498.35
#Mann=3,-1,0
  4775.7    0.05       0  4996.9    0.03       0  5002.9    0.05       0
Bank Sta=4947.6,5061.8
Exp/Cntr=0.3,0.1

Type RM Length L Ch R = 1,10237,167,167,167
BEGIN DESCRIPTION:
XS3279A
END DESCRIPTION:
XS GIS Cut Line= 3
      2805567.80      7045416.54      2805385.50      7045363.28
      2805211.45      7045408.33
#Sta/Elev= 30
  4809.8  497.18  4823.1  497.15  4830.7  496.94  4844.0  496.32  4864.2  496.18
  4875.2  495.98  4885.6  496.05  4896.1  495.76  4908.1  495.25  4916.9  495.41
  4933.8  494.90  4986.8  493.68  4987.3  492.88  4992.3  492.88  4992.8  493.68
  4997.4  494.04  5026.3  494.10  5031.5  494.47  5041.6  494.25  5051.9  494.26
  5072.5  494.53  5082.9  494.45  5093.2  494.61  5102.4  494.50  5107.5  494.80
  5113.9  494.88  5143.4  494.90  5148.1  495.63  5155.2  495.84  5179.5  495.76
#Mann=3,-1,0
  4809.8    0.05       0  4986.8    0.03       0  4992.8    0.05       0
Bank Sta=4933.8,5143.4
Exp/Cntr=0.3,0.1

Type RM Length L Ch R = 1,10070,149,149,149
BEGIN DESCRIPTION:
XS3280A
END DESCRIPTION:
XS GIS Cut Line= 3
      2805571.86      7045240.39      2805313.81      7045213.77
      2805125.37      7045316.18
#Sta/Elev= 30
  4740.8  494.56  4748.7  494.28  4777.9  493.92  4798.0  493.87  4837.6  492.93
  4858.3  492.81  4878.4  492.41  4918.6  492.25  4928.7  492.02  4933.6  491.67
  4948.8  490.77  4958.8  490.55  4989.0  490.79  4994.1  490.50  4994.6  489.70
  4999.6  489.70  5000.1  490.50  5008.9  490.56  5014.6  491.28  5030.8  491.38
  5036.5  491.12  5052.6  491.15  5058.3  491.51  5072.6  491.67  5134.3  493.17
  5140.0  493.57  5146.8  493.18  5156.2  493.18  5169.6  493.58  5214.7  493.91
#Mann=3,-1,0
  4740.8    0.05       0  4994.1    0.03       0  5000.1    0.05       0
Bank Sta=4933.6,5072.6
Exp/Cntr=0.3,0.1

Type RM Length L Ch R = 1,9921,159,159,159
BEGIN DESCRIPTION:
XS3281A
END DESCRIPTION:
XS GIS Cut Line= 3
      2805489.94      7045111.36      2805242.13      7045078.59
      2805079.15      7045123.41
#Sta/Elev= 30
  4766.8  491.49  4771.8  491.49  4782.0  490.89  4822.2  490.90  4855.5  490.48
  4862.6  490.26  4872.7  490.23  4882.7  490.53  4892.8  490.03  4913.0  489.77
  4923.1  489.37  4943.3  489.59  4949.7  489.18  4963.4  488.55  4973.5  488.56
  5004.4  488.04  5004.9  487.24  5009.9  487.24  5010.4  488.04  5012.8  488.20
  5044.9  488.74  5054.9  489.20  5076.0  489.08  5095.5  489.18  5134.1  489.85
  5139.3  490.16  5159.0  490.19  5168.6  490.65  5173.7  491.07  5185.8  490.39
#Mann=3,-1,0
  4766.8    0.05       0  5004.4    0.03       0  5010.4    0.05       0
Bank Sta=4949.7,5095.5
Exp/Cntr=0.3,0.1

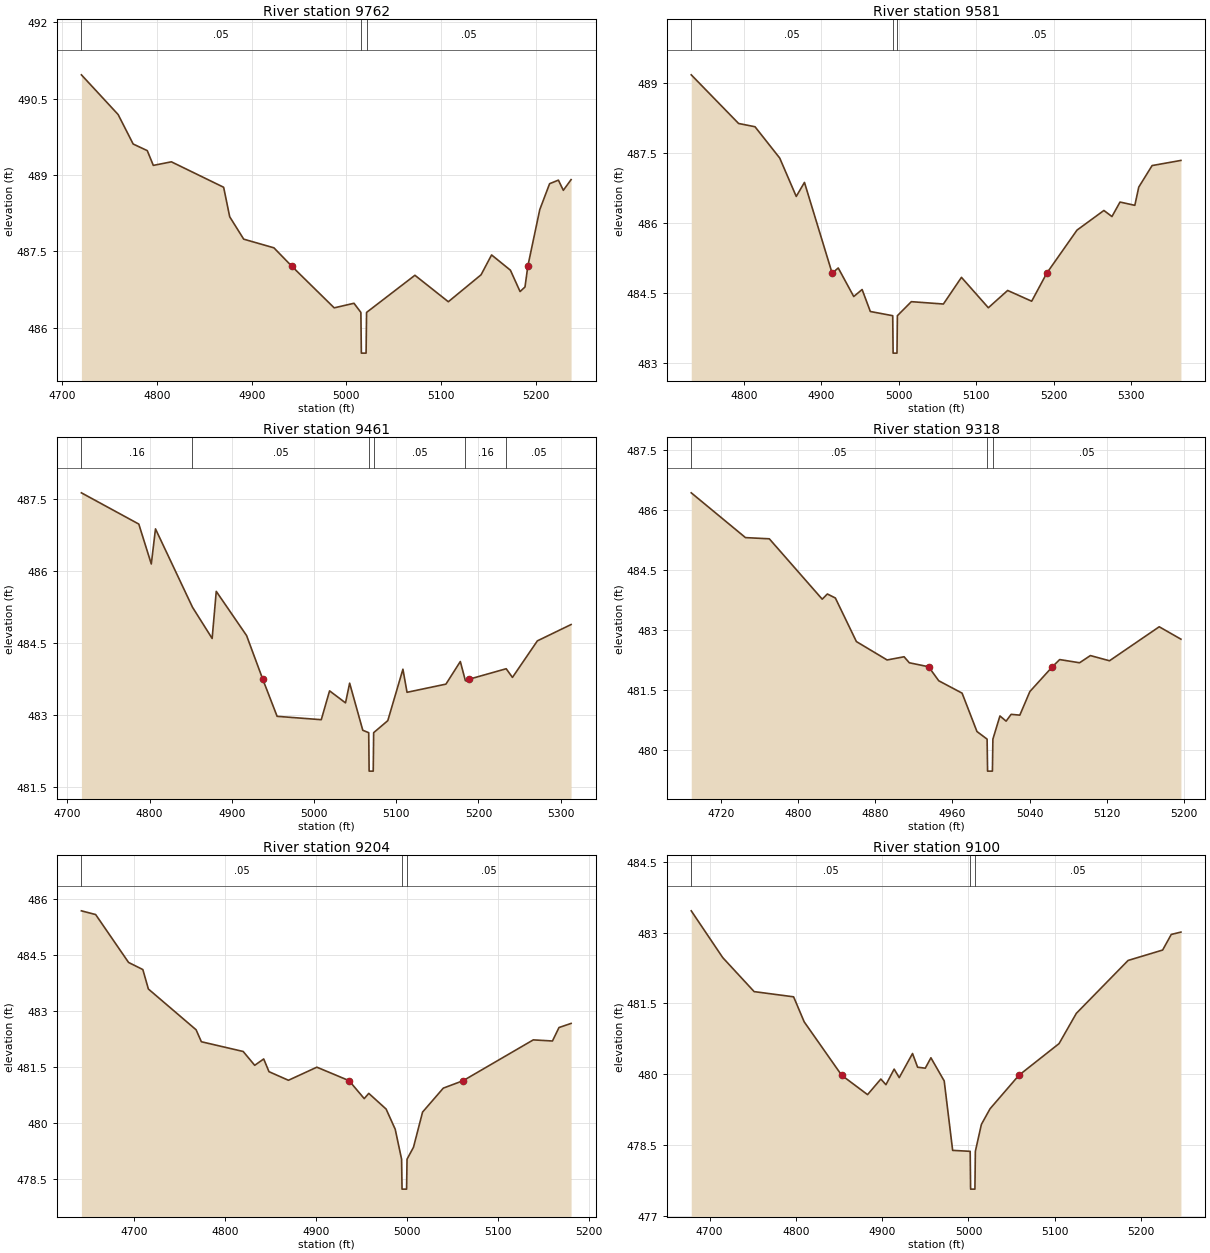
Type RM Length L Ch R = 1,9762,181,181,181
BEGIN DESCRIPTION:
XS3282A
END DESCRIPTION:
XS GIS Cut Line= 3
      2805516.55      7045013.04      2805258.51      7044920.88
      2805023.00      7044982.32
#Sta/Elev= 30
  4720.1  490.97  4758.9  490.19  4774.8  489.61  4789.7  489.48  4796.1  489.19
  4815.2  489.26  4870.4  488.76  4876.8  488.18  4891.6  487.74  4923.5  487.57
  4942.3  487.21  4987.2  486.39  5008.1  486.48  5015.4  486.30  5015.9  485.50
  5020.9  485.50  5021.4  486.30  5072.5  487.03  5107.8  486.51  5142.4  487.04
  5153.5  487.43  5173.4  487.13  5183.6  486.71  5188.8  486.80  5191.8  487.21
  5204.4  488.32  5214.8  488.83  5224.1  488.90  5229.3  488.70  5237.5  488.91
#Mann=3,-1,0
  4720.1    0.05       0  5015.4    0.03       0  5021.4    0.05       0
Bank Sta=4942.3,5191.8
Exp/Cntr=0.3,0.1

Type RM Length L Ch R = 1,9581,120,120,120
BEGIN DESCRIPTION:
XS3283A
END DESCRIPTION:
XS GIS Cut Line= 3
      2805512.46      7044832.81      2805256.47      7044740.65
      2804909.13      7044834.63
#Sta/Elev= 30
  4732.3  489.17  4793.4  488.13  4814.6  488.06  4846.5  487.39  4867.8  486.57
  4878.4  486.87  4914.1  484.93  4922.0  485.04  4942.0  484.43  4952.8  484.58
  4963.4  484.11  4992.3  484.02  4992.8  483.22  4997.8  483.22  4998.3  484.02
  5016.3  484.32  5057.7  484.27  5081.0  484.84  5115.7  484.19  5140.6  484.56
  5171.6  484.33  5191.1  484.93  5230.1  485.85  5264.8  486.27  5275.2  486.14
  5285.6  486.45  5304.7  486.38  5309.8  486.77  5327.0  487.23  5364.2  487.34
#Mann=3,-1,0
  4732.3    0.05       0  4992.3    0.03       0  4998.3    0.05       0
Bank Sta=4914.1,5191.1
Exp/Cntr=0.3,0.1

Type RM Length L Ch R = 1,9461,143,143,143
BEGIN DESCRIPTION:
XS3284A
END DESCRIPTION:
XS GIS Cut Line= 3
      2805504.25      7044671.01      2805221.65      7044634.15
      2804914.43      7044679.21
#Sta/Elev= 30
  4717.1  487.62  4786.9  486.97  4802.1  486.14  4807.2  486.87  4852.2  485.24
  4876.1  484.59  4881.1  485.57  4918.0  484.65  4937.7  483.74  4955.1  482.97
  5008.8  482.90  5018.9  483.50  5038.3  483.25  5043.3  483.66  5059.3  482.68
  5066.5  482.63  5067.0  481.83  5072.0  481.83  5072.5  482.63  5089.7  482.88
  5108.1  483.95  5113.1  483.47  5160.4  483.64  5177.9  484.11  5184.1  483.71
  5188.1  483.74  5233.7  483.96  5241.3  483.78  5271.6  484.54  5312.6  484.88
#Mann=6,-1,0
  4717.1    0.16       0  4852.2    0.05       0  5066.5    0.03       0
  5072.5    0.05       0  5184.1    0.16       0  5233.7    0.05       0
Bank Sta=4937.7,5188.1
Exp/Cntr=0.3,0.1

Type RM Length L Ch R = 1,9318,114,114,114
BEGIN DESCRIPTION:
XS3285A
END DESCRIPTION:
XS GIS Cut Line= 3
      2805514.49      7044599.32      2805235.99      7044492.83
      2805033.22      7044544.03
#Sta/Elev= 30
  4689.5  486.43  4745.7  485.31  4770.4  485.28  4825.2  483.77  4830.5  483.90
  4838.8  483.80  4860.6  482.71  4892.4  482.25  4910.0  482.33  4915.4  482.18
  4935.4  482.08  4945.9  481.73  4970.1  481.42  4985.5  480.46  4996.0  480.27
  4996.5  479.47  5001.5  479.47  5002.0  480.27  5009.3  480.85  5015.7  480.72
  5020.9  480.89  5029.9  480.87  5040.3  481.46  5063.6  482.08  5071.2  482.26
  5091.8  482.18  5103.0  482.36  5122.8  482.23  5174.3  483.08  5196.8  482.77
#Mann=3,-1,0
  4689.5    0.05       0  4996.0    0.03       0  5002.0    0.05       0
Bank Sta=4935.4,5063.6
Exp/Cntr=0.3,0.1

Type RM Length L Ch R = 1,9204,104,104,104
BEGIN DESCRIPTION:
XS3286A
END DESCRIPTION:
XS GIS Cut Line= 4
      2805518.59      7044544.01      2805256.47      7044390.42
      2805176.59      7044386.32      2805065.96      7044494.91
#Sta/Elev= 30
  4641.9  485.68  4657.6  485.58  4693.8  484.30  4709.5  484.11  4715.6  483.59
  4768.1  482.50  4773.9  482.18  4819.9  481.92  4832.6  481.55  4842.5  481.72
  4848.3  481.38  4869.7  481.15  4901.0  481.50  4936.4  481.14  4953.1  480.66
  4958.1  480.80  4977.2  480.38  4987.2  479.84  4994.2  479.04  4994.7  478.24
  4999.7  478.24  5000.2  479.04  5007.3  479.36  5017.3  480.30  5040.1  480.94
  5062.0  481.14  5139.1  482.23  5160.2  482.20  5167.4  482.56  5180.7  482.67
#Mann=3,-1,0
  4641.9    0.05       0  4994.2    0.03       0  5000.2    0.05       0
Bank Sta=4936.4,5062
Exp/Cntr=0.3,0.1

Type RM Length L Ch R = 1,9100,139,139,139
BEGIN DESCRIPTION:
XS3287A
END DESCRIPTION:
XS GIS Cut Line= 3
      2805496.06      7044445.70      2805235.99      7044285.97
      2804973.81      7044283.92
#Sta/Elev= 30
  4678.8  483.46  4715.3  482.47  4751.7  481.75  4797.4  481.64  4809.7  481.11
  4853.1  479.98  4883.1  479.57  4898.5  479.90  4904.4  479.78  4913.9  480.11
  4919.8  479.93  4935.2  480.44  4941.1  480.15  4950.0  480.13  4956.5  480.35
  4971.9  479.86  4981.7  478.39  5002.0  478.37  5002.5  477.57  5007.5  477.57
  5008.0  478.37  5015.0  478.94  5025.0  479.27  5058.5  479.98  5105.0  480.65
  5125.0  481.29  5185.0  482.41  5225.0  482.63  5235.0  482.96  5246.2  483.01
#Mann=3,-1,0
  4678.8    0.05       0  5002.0    0.03       0  5008.0    0.05       0
Bank Sta=4853.1,5058.5
Exp/Cntr=0.3,0.1

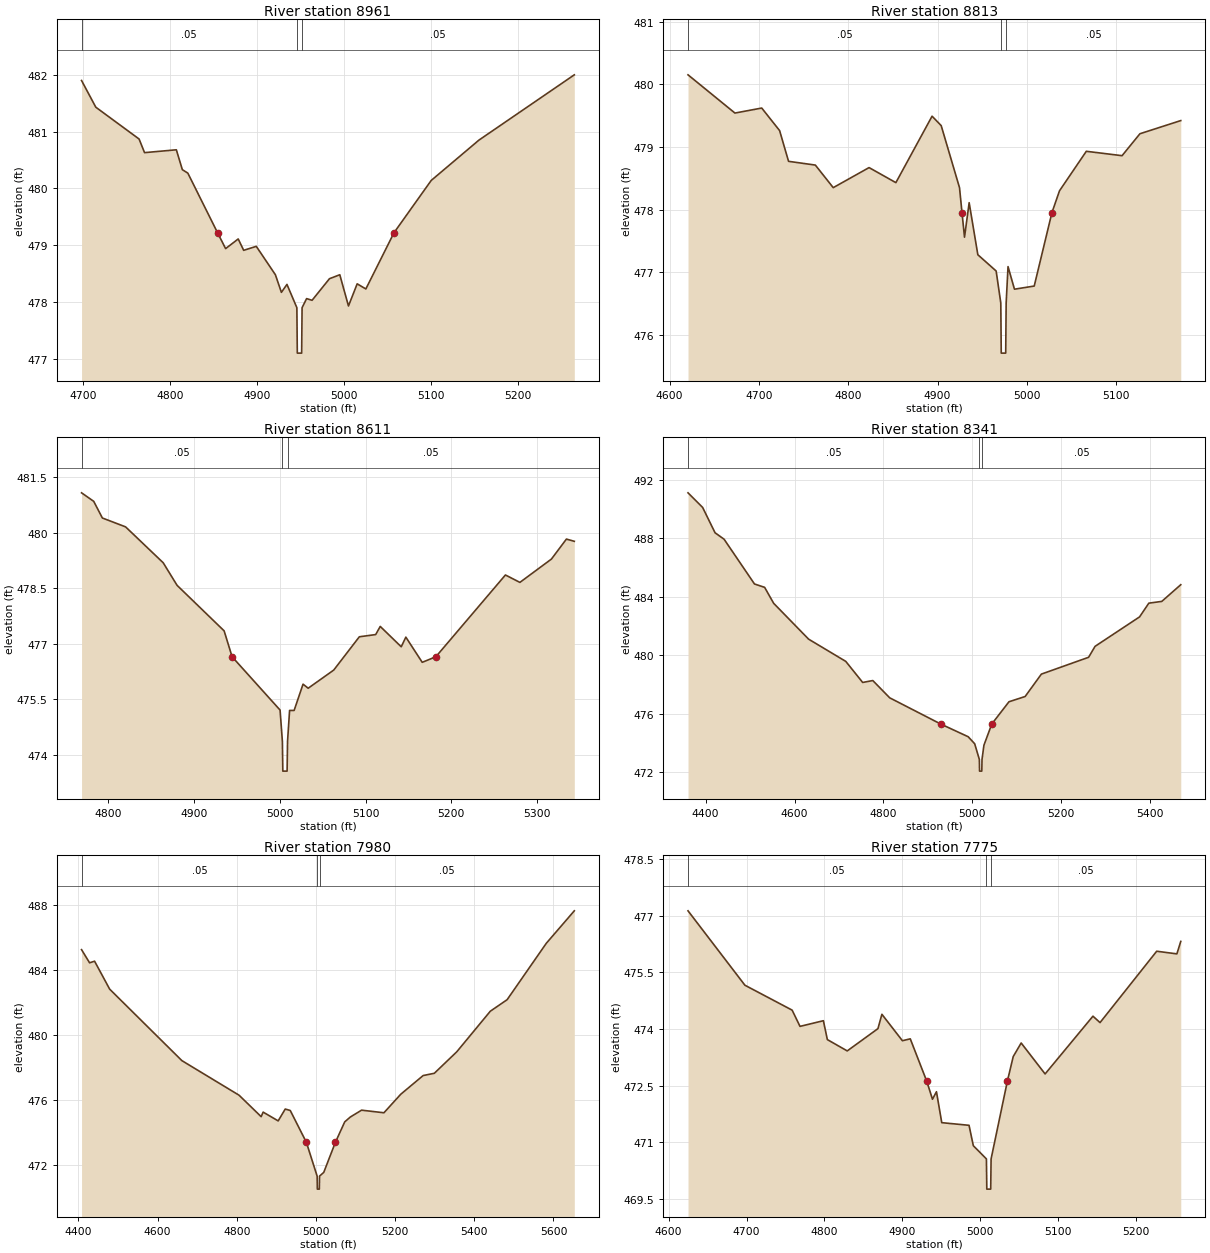
Type RM Length L Ch R = 1,8961,148,148,148
BEGIN DESCRIPTION:
XS3288A
END DESCRIPTION:
XS GIS Cut Line= 3
      2805541.15      7044351.51      2805311.77      7044173.32
      2805035.25      7044165.13
#Sta/Elev= 30
  4698.0  481.90  4714.4  481.43  4764.2  480.87  4770.5  480.63  4807.1  480.68
  4814.0  480.33  4820.3  480.27  4854.5  479.22  4863.8  478.94  4878.3  479.11
  4884.6  478.91  4899.1  478.98  4921.1  478.48  4928.0  478.17  4934.4  478.31
  4945.8  477.90  4946.3  477.10  4951.3  477.10  4951.8  477.90  4957.0  478.06
  4963.3  478.03  4983.3  478.41  4995.2  478.48  5005.2  477.93  5015.2  478.32
  5025.2  478.23  5057.6  479.22  5100.4  480.14  5155.3  480.85  5265.1  482.00
#Mann=3,-1,0
  4698.0    0.05       0  4945.8    0.03       0  4951.8    0.05       0
Bank Sta=4854.5,5057.6
Exp/Cntr=0.3,0.1

Type RM Length L Ch R = 1,8813,202,202,202
BEGIN DESCRIPTION:
XS3289A
END DESCRIPTION:
XS GIS Cut Line= 4
      2805727.49      7044001.28      2805475.62      7044007.42
      2805346.58      7044036.10      2805179.32      7044036.10
#Sta/Elev= 30
  4620.7  480.15  4673.2  479.54  4703.2  479.62  4723.2  479.26  4733.2  478.77
  4763.2  478.71  4783.2  478.35  4823.3  478.67  4853.3  478.43  4893.8  479.49
  4904.0  479.34  4924.5  478.35  4927.3  477.95  4930.1  477.56  4935.3  478.11
  4945.0  477.28  4965.5  477.02  4970.7  476.51  4971.2  475.71  4976.2  475.71
  4976.7  476.51  4978.8  477.09  4986.0  476.73  5008.1  476.78  5027.9  477.95
  5036.4  478.30  5066.4  478.93  5106.4  478.86  5126.4  479.21  5172.1  479.42
#Mann=3,-1,0
  4620.7    0.05       0  4970.7    0.03       0  4976.7    0.05       0
Bank Sta=4927.3,5027.9
Exp/Cntr=0.3,0.1

Type RM Length L Ch R = 1,8611,270,270,270
BEGIN DESCRIPTION:
XS3290A
END DESCRIPTION:
XS GIS Cut Line= 3
      2805618.98      7043821.04      2805379.35      7043862.01
      2805070.12      7043982.83
#Sta/Elev= 30
  4768.6  481.08  4782.8  480.85  4792.9  480.40  4820.0  480.16  4863.9  479.19
  4880.1  478.58  4935.0  477.35  4944.3  476.65  5000.3  475.21  5003.0  474.36
  5003.5  473.56  5008.5  473.56  5009.0  474.36  5011.4  475.20  5016.7  475.20
  5027.1  475.91  5033.1  475.80  5062.9  476.29  5092.8  477.19  5111.9  477.25
  5117.2  477.47  5141.7  476.92  5147.1  477.18  5166.2  476.50  5182.1  476.65
  5263.3  478.86  5280.2  478.66  5317.0  479.29  5334.5  479.83  5343.7  479.77
#Mann=3,-1,0
  4768.6    0.05       0  5003.0    0.03       0  5009.0    0.05       0
Bank Sta=4944.3,5182.1
Exp/Cntr=0.3,0.1

Type RM Length L Ch R = 1,8341,361,361,361
BEGIN DESCRIPTION:
UNT 048 in LFCCL Watershed 21.0
END DESCRIPTION:
XS GIS Cut Line= 3
      2805824.96      7043575.01      2805225.00      7043675.00
      2804825.03      7043974.98
#Sta/Elev= 30
  4360.5  491.09  4393.4  490.09  4421.3  488.36  4441.6  487.92  4510.0  484.86
  4532.8  484.63  4553.1  483.54  4631.7  481.09  4715.3  479.57  4753.3  478.13
  4776.1  478.26  4814.1  477.08  4928.8  475.29  4990.6  474.42  5005.2  473.94
  5015.7  472.87  5016.2  472.07  5021.2  472.07  5021.7  472.87  5026.0  473.84
  5043.7  475.29  5082.3  476.81  5118.7  477.17  5155.2  478.70  5261.4  479.85
  5276.0  480.60  5376.0  482.61  5396.9  483.55  5426.0  483.67  5468.7  484.81
#Mann=3,-1,0
  4360.5    0.05       0  5015.7    0.03       0  5021.7    0.05       0
Bank Sta=4928.8,5043.7
Exp/Cntr=0.3,0.1

Type RM Length L Ch R = 1,7980,205,205,205
BEGIN DESCRIPTION:
UNT 048 in LFCCL Watershed 20.0
END DESCRIPTION:
XS GIS Cut Line= 3
      2805674.99      7043475.00      2805075.00      7043375.00
      2804624.97      7043825.03
#Sta/Elev= 30
  4408.0  485.26  4428.3  484.45  4440.9  484.55  4479.0  482.83  4661.4  478.43
  4805.9  476.30  4861.7  474.98  4866.7  475.26  4904.7  474.72  4922.5  475.45
  4935.2  475.36  4975.9  473.40  5003.1  471.32  5003.6  470.52  5008.6  470.52
  5009.1  471.32  5019.8  471.55  5049.2  473.40  5072.8  474.66  5087.0  474.96
  5115.3  475.38  5171.8  475.22  5214.3  476.36  5270.8  477.51  5299.1  477.65
  5355.7  478.97  5440.5  481.47  5483.0  482.18  5581.9  485.65  5652.7  487.65
#Mann=3,-1,0
  4408.0    0.05       0  5003.1    0.03       0  5009.1    0.05       0
Bank Sta=4975.9,5049.2
Exp/Cntr=0.3,0.1

Type RM Length L Ch R = 1,7775,309,309,309
BEGIN DESCRIPTION:
XS3291A
END DESCRIPTION:
XS GIS Cut Line= 3
      2805377.20      7043245.79      2805020.42      7043193.70
      2804754.79      7043251.00
#Sta/Elev= 30
  4624.9  477.13  4697.9  475.16  4758.5  474.50  4768.6  474.07  4798.6  474.22
  4803.7  473.72  4829.2  473.42  4868.6  474.01  4873.7  474.39  4900.0  473.69
  4910.1  473.74  4931.2  472.62  4938.6  472.14  4943.7  472.34  4950.5  471.52
  4985.5  471.45  4991.0  470.91  5007.8  470.56  5008.3  469.76  5013.3  469.76
  5013.8  470.56  5034.7  472.62  5042.2  473.27  5052.4  473.63  5083.1  472.81
  5144.5  474.34  5153.6  474.17  5226.3  476.06  5252.2  475.99  5257.2  476.32
#Mann=3,-1,0
  4624.9    0.05       0  5007.8    0.03       0  5013.8    0.05       0
Bank Sta=4931.2,5034.7
Exp/Cntr=0.3,0.1

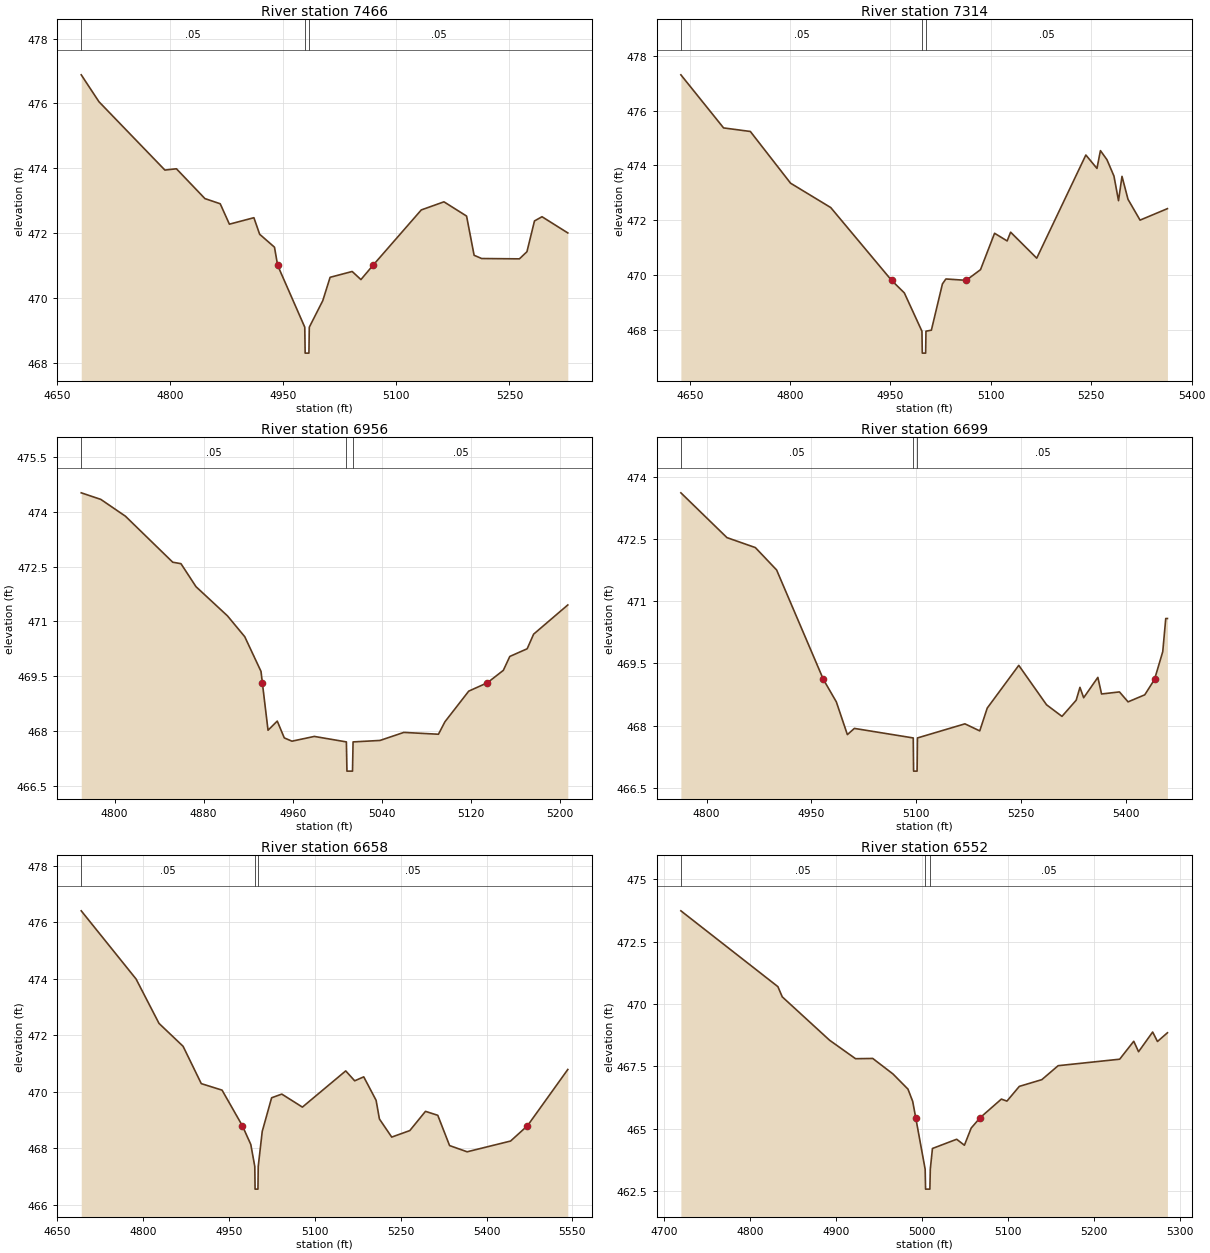
Type RM Length L Ch R = 1,7466,152,152,152
BEGIN DESCRIPTION:
XS3292A
END DESCRIPTION:
XS GIS Cut Line= 3
      2805411.02      7043037.45      2805093.34      7042938.50
      2804780.87      7042954.12
#Sta/Elev= 30
  4681.8  476.88  4705.3  476.05  4792.8  473.94  4808.1  473.98  4845.9  473.06
  4866.2  472.90  4878.4  472.27  4910.9  472.47  4918.5  471.96  4938.2  471.56
  4942.4  471.00  4978.4  469.09  4978.9  468.29  4983.9  468.29  4984.4  469.09
  5002.3  469.91  5012.0  470.63  5041.3  470.81  5052.9  470.56  5068.9  471.00
  5133.0  472.71  5163.1  472.96  5193.1  472.52  5203.1  471.31  5213.1  471.21
  5263.2  471.20  5273.2  471.42  5283.2  472.37  5293.2  472.50  5327.4  472.00
#Mann=3,-1,0
  4681.8    0.05       0  4978.4    0.03       0  4984.4    0.05       0
Bank Sta=4942.4,5068.9
Exp/Cntr=0.3,0.1

Type RM Length L Ch R = 1,7314,358,358,358
BEGIN DESCRIPTION:
XS3293A
END DESCRIPTION:
XS GIS Cut Line= 3
      2805478.79      7042782.25      2805111.57      7042792.66
      2804768.87      7042901.70
#Sta/Elev= 30
  4636.8  477.31  4700.6  475.37  4740.6  475.24  4800.7  473.35  4860.7  472.46
  4951.6  469.80  4970.7  469.34  4997.0  467.94  4997.5  467.14  5002.5  467.14
  5003.0  467.94  5011.1  467.98  5027.6  469.67  5032.8  469.85  5063.1  469.80
  5084.5  470.19  5105.5  471.52  5124.3  471.24  5129.5  471.56  5168.5  470.61
  5241.9  474.38  5258.5  473.89  5263.7  474.54  5273.4  474.21  5283.9  473.61
  5290.7  472.71  5295.9  473.60  5304.9  472.76  5322.9  472.00  5363.8  472.42
#Mann=3,-1,0
  4636.8    0.05       0  4997.0    0.03       0  5003.0    0.05       0
Bank Sta=4951.6,5063.1
Exp/Cntr=0.3,0.1

Type RM Length L Ch R = 1,6956,257,257,257
BEGIN DESCRIPTION:
XS3297A
END DESCRIPTION:
XS GIS Cut Line= 3
      2805036.89      7042421.59      2804867.65      7042547.44
      2804751.27      7042741.40
#Sta/Elev= 30
  4770.1  474.52  4787.7  474.34  4809.8  473.88  4852.3  472.62  4859.7  472.58
  4873.2  471.95  4901.5  471.15  4917.0  470.58  4931.6  469.63  4932.8  469.32
  4937.9  468.02  4946.2  468.27  4952.5  467.81  4959.4  467.72  4979.5  467.85
  5008.3  467.70  5008.8  466.90  5013.8  466.90  5014.3  467.70  5038.5  467.74
  5059.9  467.96  5091.0  467.91  5096.8  468.25  5118.2  469.09  5135.0  469.32
  5149.3  469.66  5155.1  470.04  5170.7  470.25  5176.5  470.65  5207.2  471.45
#Mann=3,-1,0
  4770.1    0.05       0  5008.3    0.03       0  5014.3    0.05       0
Bank Sta=4932.8,5135
Exp/Cntr=0.3,0.1

Type RM Length L Ch R = 1,6699,41,41,41
BEGIN DESCRIPTION:
XS3296A
END DESCRIPTION:
XS GIS Cut Line= 5
      2805000.02      7042369.49      2804780.84      7042332.59
      2804698.38      7042330.42      2804667.99      7042339.10
      2804548.37      7042678.06
#Sta/Elev= 30
  4763.3  473.61  4829.2  472.53  4869.8  472.29  4900.2  471.75  4967.1  469.11
  4985.6  468.57  5001.4  467.78  5011.4  467.93  5095.6  467.70  5096.1  466.90
  5101.1  466.90  5101.6  467.70  5169.5  468.04  5190.7  467.87  5201.4  468.42
  5246.5  469.45  5286.2  468.50  5308.3  468.22  5328.6  468.61  5334.0  468.92
  5339.3  468.67  5359.6  469.16  5364.9  468.76  5390.5  468.81  5402.8  468.57
  5426.7  468.74  5440.6  469.11  5452.4  469.78  5456.7  470.58  5459.1  470.58
#Mann=3,-1,0
  4763.3    0.05       0  5095.6    0.03       0  5101.6    0.05       0
Bank Sta=4967.1,5440.6
Exp/Cntr=0.3,0.1

Type RM Length L Ch R = 1,6658,106,106,106
BEGIN DESCRIPTION:
Mapping XS 5ab2f062
END DESCRIPTION:
XS GIS Cut Line= 6
      2805070.78      7042295.92      2804892.87      7042302.43
      2804669.34      7042293.75      2804634.62      7042324.13
      2804543.48      7042482.56      2804500.08      7042697.38
#Sta/Elev= 30
  4691.7  476.40  4787.5  473.99  4827.6  472.42  4869.7  471.61  4901.5  470.29
  4937.8  470.06  4973.3  468.80  4988.0  468.14  4995.0  467.36  4995.5  466.56
  5000.5  466.56  5001.0  467.36  5008.0  468.60  5024.4  469.79  5042.2  469.92
  5078.2  469.46  5153.9  470.74  5169.6  470.39  5185.4  470.53  5207.0  469.70
  5212.8  469.04  5234.3  468.40  5265.9  468.63  5293.3  469.31  5314.8  469.17
  5335.4  468.10  5366.1  467.88  5442.0  468.26  5471.5  468.80  5542.0  470.79
#Mann=3,-1,0
  4691.7    0.05       0  4995.0    0.03       0  5001.0    0.05       0
Bank Sta=4973.3,5471.5
Exp/Cntr=0.3,0.1

Type RM Length L Ch R = 1,6552,171,171,171
BEGIN DESCRIPTION:
XS3294A
END DESCRIPTION:
XS GIS Cut Line= 5
      2804967.44      7042230.59      2804726.59      7042208.90
      2804650.63      7042243.62      2804592.04      7042315.23
      2804522.57      7042446.40
#Sta/Elev= 30
  4719.2  473.73  4832.1  470.69  4837.2  470.28  4892.3  468.54  4922.5  467.80
  4942.5  467.81  4966.0  467.19  4983.5  466.58  4989.0  466.09  4992.5  465.44
  5003.5  463.37  5004.0  462.57  5009.0  462.57  5009.5  463.37  5012.0  464.20
  5040.2  464.57  5049.2  464.33  5057.1  465.02  5067.7  465.44  5092.2  466.18
  5098.7  466.10  5113.1  466.69  5139.3  466.96  5158.3  467.52  5229.9  467.78
  5246.3  468.50  5251.9  468.08  5268.3  468.87  5273.9  468.49  5285.5  468.84
#Mann=3,-1,0
  4719.2    0.05       0  5003.5    0.03       0  5009.5    0.05       0
Bank Sta=4992.5,5067.7
Exp/Cntr=0.3,0.1

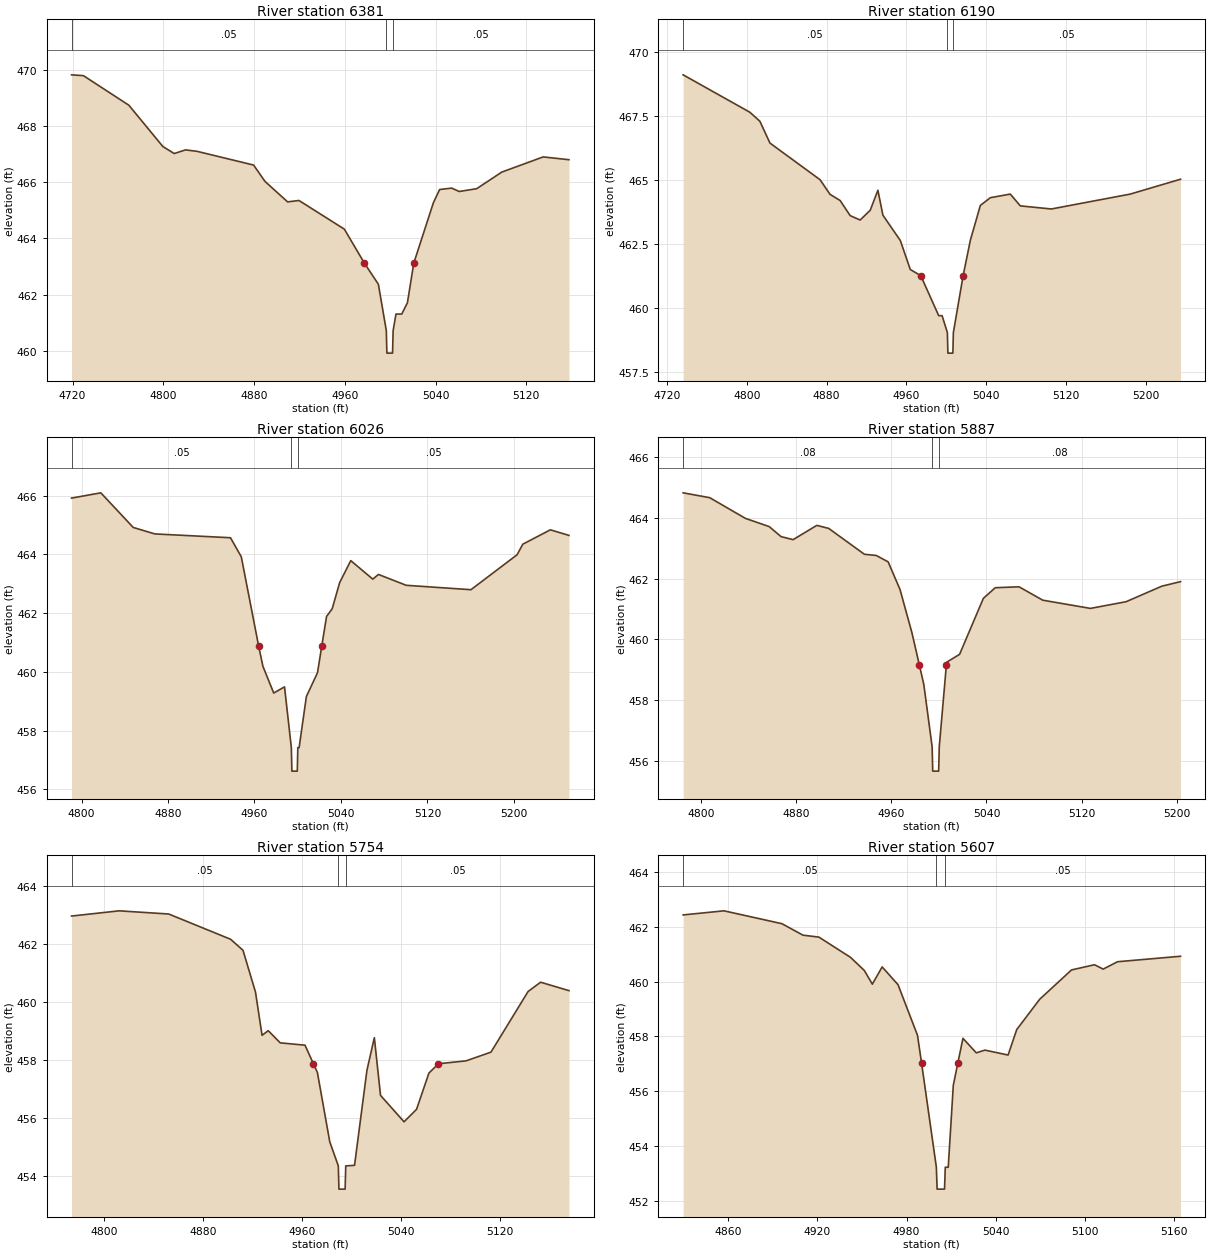
Type RM Length L Ch R = 1,6381,191,191,191
BEGIN DESCRIPTION:
XS3298A
END DESCRIPTION:
XS GIS Cut Line= 3
      2804865.50      7042093.88      2804579.02      7042096.05
      2804441.38      7042160.57
#Sta/Elev= 30
  4719.1  469.82  4729.6  469.79  4769.6  468.74  4799.6  467.27  4809.6  467.02
  4819.6  467.15  4829.6  467.10  4879.6  466.61  4889.6  466.03  4909.6  465.30
  4919.6  465.35  4959.6  464.33  4977.3  463.12  4989.6  462.37  4996.6  460.72
  4997.1  459.92  5002.1  459.92  5002.6  460.72  5005.1  461.31  5010.2  461.31
  5015.2  461.71  5020.8  463.12  5038.1  465.27  5043.6  465.74  5054.2  465.79
  5060.9  465.67  5076.3  465.77  5098.4  466.36  5134.9  466.90  5157.6  466.80
#Mann=3,-1,0
  4719.1    0.05       0  4996.6    0.03       0  5002.6    0.05       0
Bank Sta=4977.3,5020.8
Exp/Cntr=0.3,0.1

Type RM Length L Ch R = 1,6190,164,164,164
BEGIN DESCRIPTION:
XS3299A
END DESCRIPTION:
XS GIS Cut Line= 3
      2804891.56      7041961.50      2804633.27      7041933.29
      2804394.58      7041948.48
#Sta/Elev= 30
  4736.1  469.10  4803.1  467.64  4813.1  467.29  4823.2  466.44  4873.5  465.01
  4883.5  464.44  4893.6  464.20  4903.7  463.61  4913.7  463.44  4923.8  463.82
  4931.5  464.60  4936.5  463.63  4954.0  462.64  4964.0  461.51  4974.5  461.27
  4992.5  459.71  4995.9  459.71  5001.2  459.05  5001.7  458.25  5006.7  458.25
  5007.2  459.05  5017.0  461.27  5024.3  462.66  5034.3  464.01  5044.3  464.31
  5064.3  464.45  5074.4  463.99  5105.5  463.87  5184.6  464.45  5235.1  465.03
#Mann=3,-1,0
  4736.1    0.05       0  5001.2    0.03       0  5007.2    0.05       0
Bank Sta=4974.5,5017
Exp/Cntr=0.3,0.1

Type RM Length L Ch R = 1,6026,139,139,139
BEGIN DESCRIPTION:
XS3300A
END DESCRIPTION:
XS GIS Cut Line= 3
      2804822.10      7041787.89      2804611.57      7041783.55
      2804368.20      7041839.54
#Sta/Elev= 30
  4790.7  465.92  4817.8  466.10  4847.8  464.92  4867.8  464.70  4937.8  464.57
  4947.8  463.92  4963.8  460.89  4967.8  460.19  4977.8  459.28  4987.8  459.49
  4994.1  457.42  4994.6  456.62  4999.6  456.62  5000.1  457.42  5001.3  457.42
  5008.0  459.16  5018.3  459.97  5022.3  460.89  5026.7  461.89  5031.9  462.15
  5038.8  463.04  5049.1  463.79  5069.5  463.16  5074.7  463.32  5100.4  462.95
  5160.3  462.80  5203.0  463.99  5208.3  464.35  5233.8  464.84  5251.0  464.65
#Mann=3,-1,0
  4790.7    0.05       0  4994.1    0.03       0  5000.1    0.05       0
Bank Sta=4963.8,5022.3
Exp/Cntr=0.3,0.1

Type RM Length L Ch R = 1,5887,133,133,133
BEGIN DESCRIPTION:
XS3301A
END DESCRIPTION:
XS GIS Cut Line= 3
      2804787.38      7041659.85      2804561.66      7041651.17
      2804369.24      7041659.82
#Sta/Elev= 30
  4784.8  464.82  4807.2  464.66  4837.2  463.98  4857.2  463.71  4867.2  463.38
  4877.3  463.28  4897.3  463.75  4907.3  463.65  4937.3  462.80  4947.3  462.76
  4957.3  462.55  4967.3  461.64  4977.3  460.22  4983.5  459.17  4987.3  458.52
  4994.3  456.47  4994.8  455.67  4999.8  455.67  5000.3  456.47  5006.3  459.17
  5006.5  459.25  5017.4  459.51  5037.4  461.35  5047.4  461.70  5067.4  461.73
  5087.4  461.29  5127.5  461.02  5157.5  461.24  5187.5  461.75  5203.3  461.90
#Mann=3,-1,0
  4784.8    0.08       0  4994.3    0.07       0  5000.3    0.08       0
Bank Sta=4983.5,5006.3
Exp/Cntr=0.3,0.1

Type RM Length L Ch R = 1,5754,147,147,147
BEGIN DESCRIPTION:
XS3302A
END DESCRIPTION:
XS GIS Cut Line= 3
      2804713.52      7041547.00      2804490.04      7041551.34
      2804312.10      7041540.49
#Sta/Elev= 30
  4774.0  462.95  4812.5  463.13  4852.5  463.02  4902.5  462.15  4912.5  461.77
  4922.6  460.33  4927.9  458.84  4932.9  459.00  4942.6  458.58  4962.6  458.50
  4969.4  457.86  4972.6  457.56  4982.6  455.17  4989.5  454.34  4990.0  453.54
  4995.0  453.54  4995.5  454.34  5002.6  454.36  5012.6  457.63  5018.6  458.76
  5023.6  456.77  5042.6  455.86  5052.7  456.29  5062.7  457.54  5070.4  457.86
  5092.7  457.96  5112.8  458.26  5142.8  460.35  5152.9  460.67  5175.8  460.38
#Mann=3,-1,0
  4774.0    0.05       0  4989.5    0.03       0  4995.5    0.05       0
Bank Sta=4969.4,5070.4
Exp/Cntr=0.3,0.1

Type RM Length L Ch R = 1,5607,127,127,127
BEGIN DESCRIPTION:
XS3303A
END DESCRIPTION:
XS GIS Cut Line= 3
      2804550.77      7041386.43      2804385.87      7041447.18
      2804249.58      7041529.39
#Sta/Elev= 30
  4829.6  462.44  4857.1  462.59  4896.1  462.12  4910.3  461.70  4921.0  461.63
  4942.3  460.89  4951.6  460.41  4957.0  459.91  4963.6  460.54  4974.3  459.89
  4987.4  458.04  4990.1  457.04  5000.1  453.22  5000.6  452.42  5005.6  452.42
  5006.1  453.22  5008.1  453.22  5011.5  456.21  5014.6  457.04  5018.0  457.93
  5027.0  457.40  5032.8  457.50  5048.4  457.32  5054.2  458.25  5069.7  459.36
  5091.1  460.43  5106.6  460.62  5112.4  460.46  5122.1  460.73  5164.5  460.93
#Mann=3,-1,0
  4829.6    0.05       0  5000.1    0.03       0  5006.1    0.05       0
Bank Sta=4990.1,5014.6
Exp/Cntr=0.3,0.1