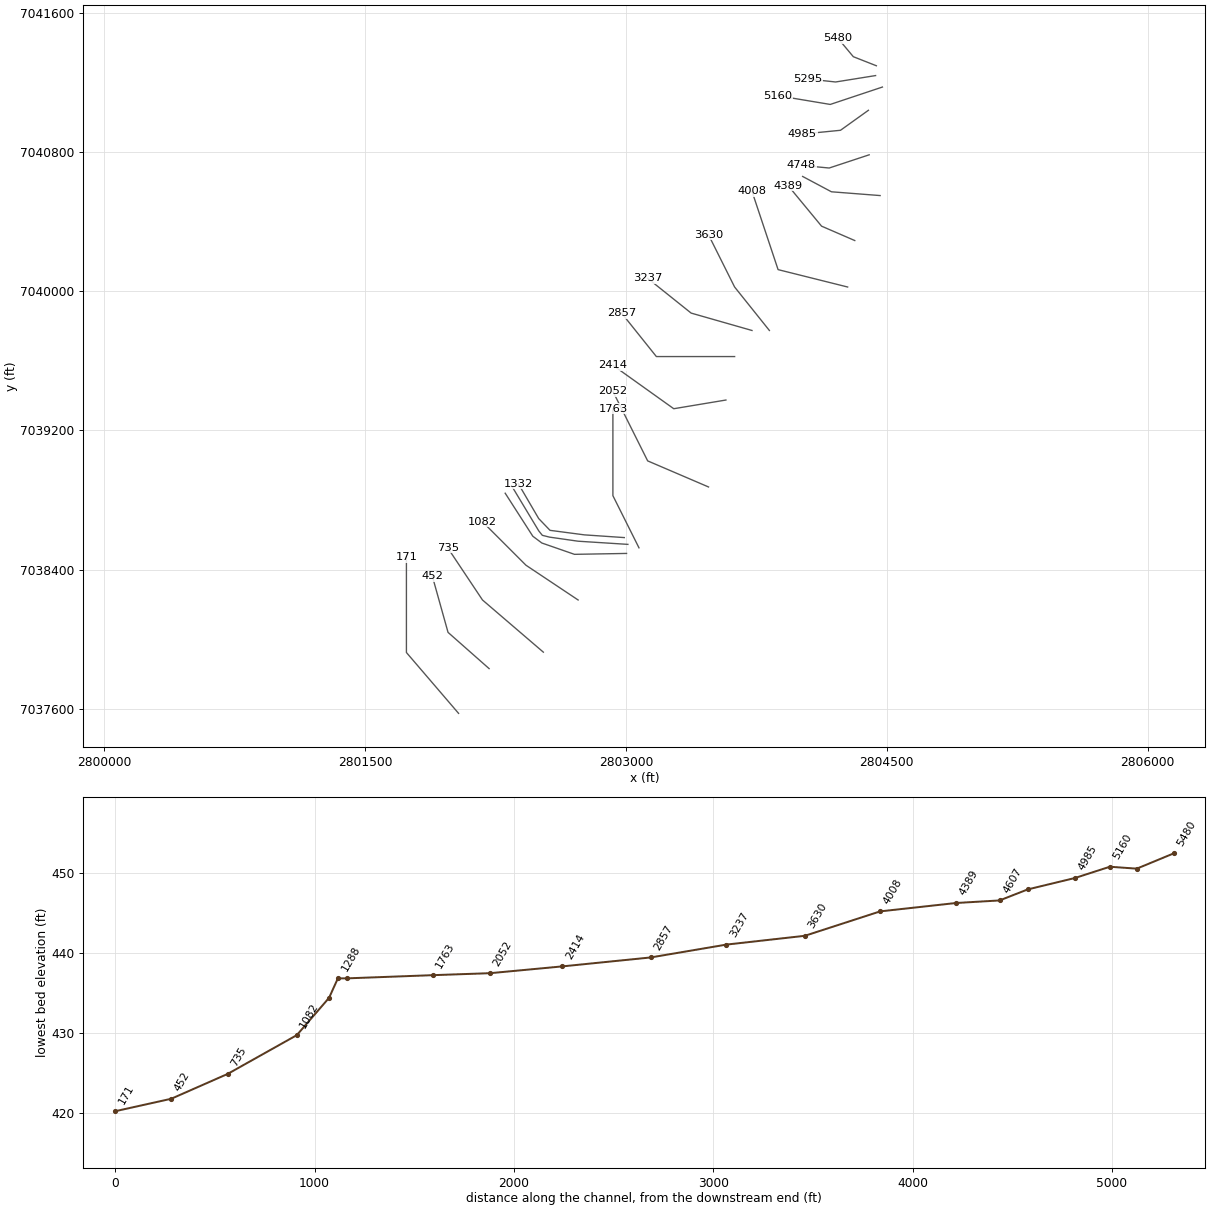
HEC-RAS study UNT 048 in LFCCL Watershed.prj: UNT 048 in LFCCL Watershed Base Level Engineering

--- UNT 048 in LFCCL Watershed.g01 (geometry) --- (continued)

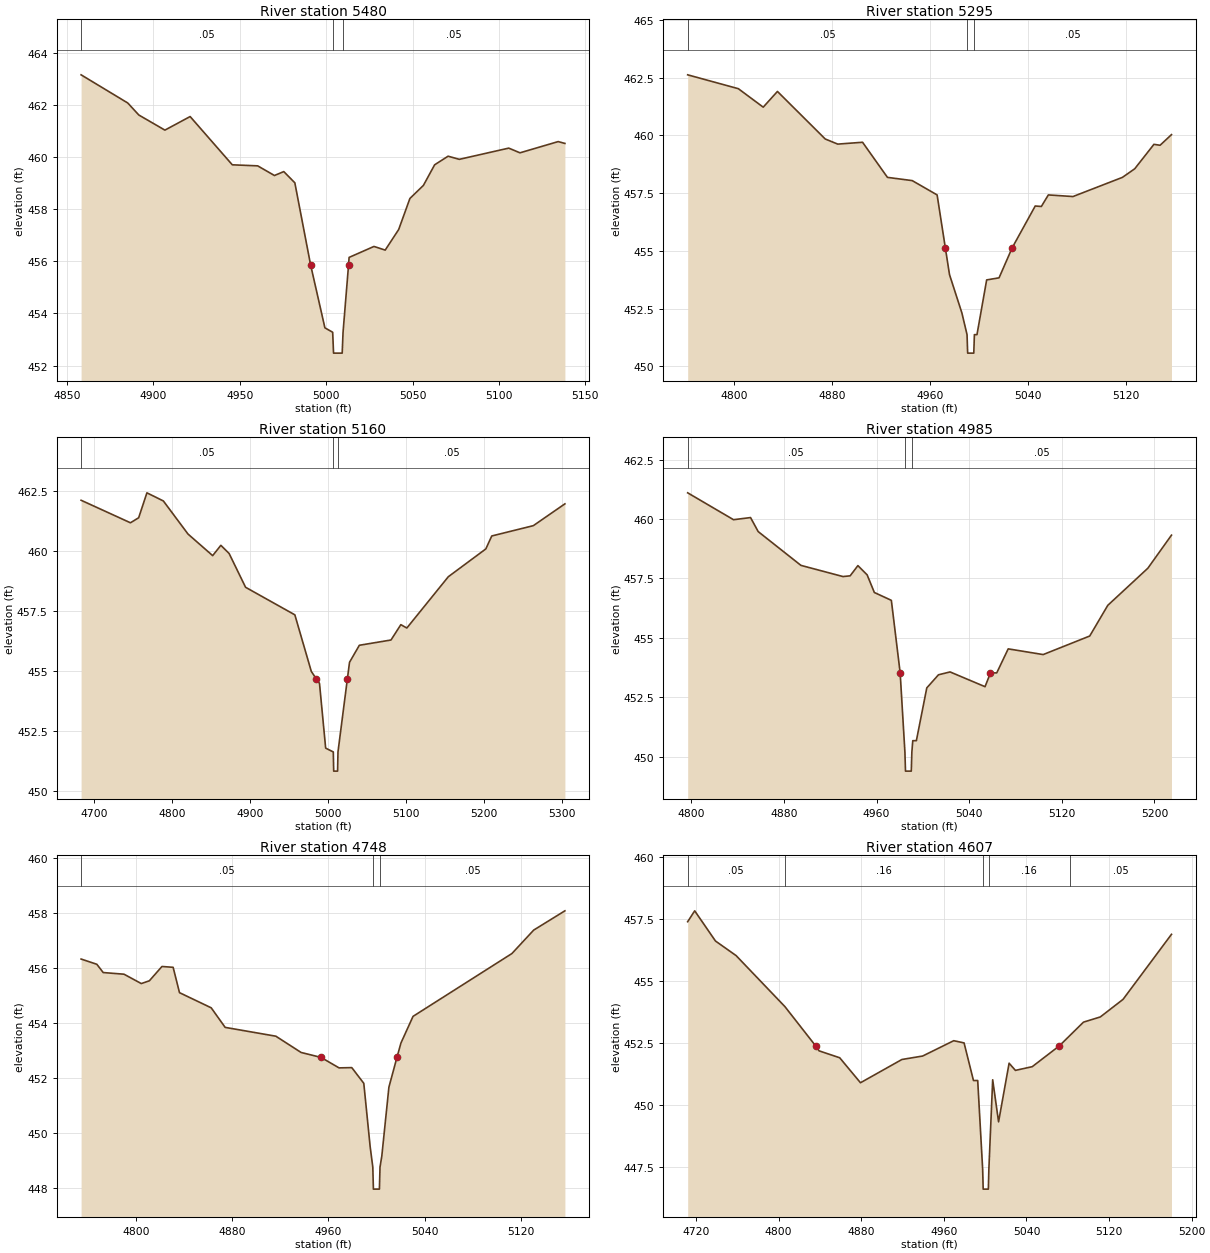
Type RM Length L Ch R = 1,5480,185,185,185
BEGIN DESCRIPTION:
XS3304A
END DESCRIPTION:
XS GIS Cut Line= 3
      2804440.14      7041297.43      2804307.75      7041349.52
      2804219.37      7041455.15
#Sta/Elev= 30
  4858.2  463.15  4885.2  462.07  4891.6  461.61  4906.7  461.03  4921.3  461.55
  4945.7  459.70  4960.4  459.66  4970.1  459.29  4975.5  459.44  4981.9  459.01
  4991.0  455.87  4999.3  453.45  5003.8  453.28  5004.3  452.48  5009.3  452.48
  5009.8  453.28  5013.0  455.87  5013.3  456.15  5027.7  456.57  5034.2  456.43
  5042.0  457.22  5048.5  458.41  5056.3  458.91  5062.8  459.70  5070.6  460.03
  5077.1  459.91  5105.7  460.34  5112.2  460.16  5134.3  460.59  5138.2  460.52
#Mann=3,-1,0
  4858.2    0.05       0  5003.8    0.03       0  5009.8    0.05       0
Bank Sta=4991,5013
Exp/Cntr=0.3,0.1

Type RM Length L Ch R = 1,5295,135,135,135
BEGIN DESCRIPTION:
XS3305A
END DESCRIPTION:
XS GIS Cut Line= 3
      2804435.81      7041241.02      2804205.75      7041204.12
      2804045.19      7041221.48
#Sta/Elev= 30
  4762.3  462.62  4803.6  462.02  4823.9  461.22  4835.5  461.90  4874.5  459.84
  4884.7  459.62  4904.9  459.70  4925.2  458.18  4945.4  458.04  4965.7  457.42
  4972.4  455.13  4975.8  453.97  4985.9  452.31  4990.1  451.37  4990.6  450.57
  4995.6  450.57  4996.1  451.37  4998.2  451.37  5006.1  453.74  5016.2  453.83
  5026.9  455.13  5045.7  456.94  5050.7  456.92  5056.4  457.42  5076.5  457.35
  5116.8  458.18  5126.8  458.55  5142.5  459.61  5147.5  459.57  5156.8  460.03
#Mann=3,-1,0
  4762.3    0.05       0  4990.1    0.03       0  4996.1    0.05       0
Bank Sta=4972.4,5026.9
Exp/Cntr=0.3,0.1

Type RM Length L Ch R = 1,5160,175,175,175
BEGIN DESCRIPTION:
UNT 048 in LFCCL Watershed 14.0
END DESCRIPTION:
XS GIS Cut Line= 3
      2804475.04      7041175.01      2804175.00      7041075.00
      2803875.01      7041125.00
#Sta/Elev= 30
  4683.0  462.11  4746.3  461.17  4756.8  461.38  4767.4  462.42  4788.5  462.08
  4820.1  460.70  4851.7  459.80  4862.2  460.23  4872.8  459.89  4893.9  458.48
  4957.1  457.33  4978.2  454.97  4984.4  454.67  4988.7  454.47  4996.6  451.77
  5006.4  451.61  5006.9  450.81  5011.9  450.81  5012.4  451.61  5024.5  454.67
  5027.2  455.35  5039.8  456.06  5080.4  456.28  5093.0  456.92  5100.7  456.78
  5153.9  458.92  5202.0  460.08  5209.6  460.62  5262.9  461.05  5303.4  461.96
#Mann=3,-1,0
  4683.0    0.05       0  5006.4    0.03       0  5012.4    0.05       0
Bank Sta=4984.4,5024.5
Exp/Cntr=0.3,0.1

Type RM Length L Ch R = 1,4985,237,237,237
BEGIN DESCRIPTION:
XS3306A
END DESCRIPTION:
XS GIS Cut Line= 3
      2804394.53      7041041.34      2804233.97      7040926.34
      2804014.74      7040904.64
#Sta/Elev= 30
  4796.9  461.10  4836.5  459.97  4851.2  460.06  4857.8  459.47  4894.7  458.05
  4931.0  457.58  4937.2  457.61  4943.9  458.04  4951.9  457.65  4958.1  456.91
  4972.8  456.58  4980.4  453.53  4984.5  450.20  4985.0  449.40  4990.0  449.40
  4990.5  450.20  4991.3  450.68  4994.4  450.68  5003.4  452.90  5013.5  453.45
  5023.5  453.57  5053.7  452.95  5058.4  453.53  5063.8  453.53  5073.7  454.54
  5103.9  454.30  5144.1  455.08  5159.7  456.37  5194.3  457.93  5214.7  459.32
#Mann=3,-1,0
  4796.9    0.05       0  4984.5    0.03       0  4990.5    0.05       0
Bank Sta=4980.4,5058.4
Exp/Cntr=0.3,0.1

Type RM Length L Ch R = 1,4748,141,141,141
BEGIN DESCRIPTION:
XS3307A
END DESCRIPTION:
XS GIS Cut Line= 3
      2804398.90      7040785.29      2804168.86      7040709.33
      2804009.13      7040724.44
#Sta/Elev= 30
  4754.1  456.32  4767.2  456.13  4772.5  455.83  4789.8  455.77  4804.2  455.43
  4810.9  455.53  4821.4  456.05  4830.7  456.02  4836.0  455.10  4862.4  454.55
  4874.0  453.84  4916.2  453.52  4937.2  452.93  4953.8  452.75  4968.8  452.37
  4979.4  452.38  4989.4  451.81  4994.7  449.51  4996.9  448.77  4997.4  447.97
  5002.4  447.97  5002.9  448.77  5004.4  449.17  5010.3  451.67  5017.0  452.75
  5020.3  453.27  5030.4  454.24  5112.7  456.52  5130.8  457.37  5156.8  458.07
#Mann=3,-1,0
  4754.1    0.05       0  4996.9    0.03       0  5002.9    0.05       0
Bank Sta=4953.8,5017
Exp/Cntr=0.3,0.1

Type RM Length L Ch R = 1,4607,218,218,218
BEGIN DESCRIPTION:
XS3308A
END DESCRIPTION:
XS GIS Cut Line= 3
      2804461.80      7040550.91      2804181.88      7040572.61
      2804016.25      7040660.80
#Sta/Elev= 30
  4712.0  457.40  4718.8  457.84  4738.9  456.62  4758.9  456.03  4806.1  453.97
  4835.9  452.38  4839.2  452.18  4859.2  451.90  4879.3  450.89  4919.4  451.83
  4939.5  451.97  4969.6  452.59  4979.6  452.50  4988.7  450.98  4992.8  450.98
  4997.6  447.39  4998.1  446.59  5003.1  446.59  5003.6  447.39  5007.3  451.01
  5013.0  449.31  5023.2  451.68  5029.3  451.39  5045.6  451.54  5071.8  452.38
  5081.8  452.79  5095.2  453.34  5111.5  453.55  5133.5  454.26  5180.4  456.89
#Mann=5,-1,0
  4712.0    0.05       0  4806.1    0.16       0  4997.6    0.07       0
  5003.6    0.16       0  5081.8    0.05       0
Bank Sta=4835.9,5071.8
Exp/Cntr=0.3,0.1

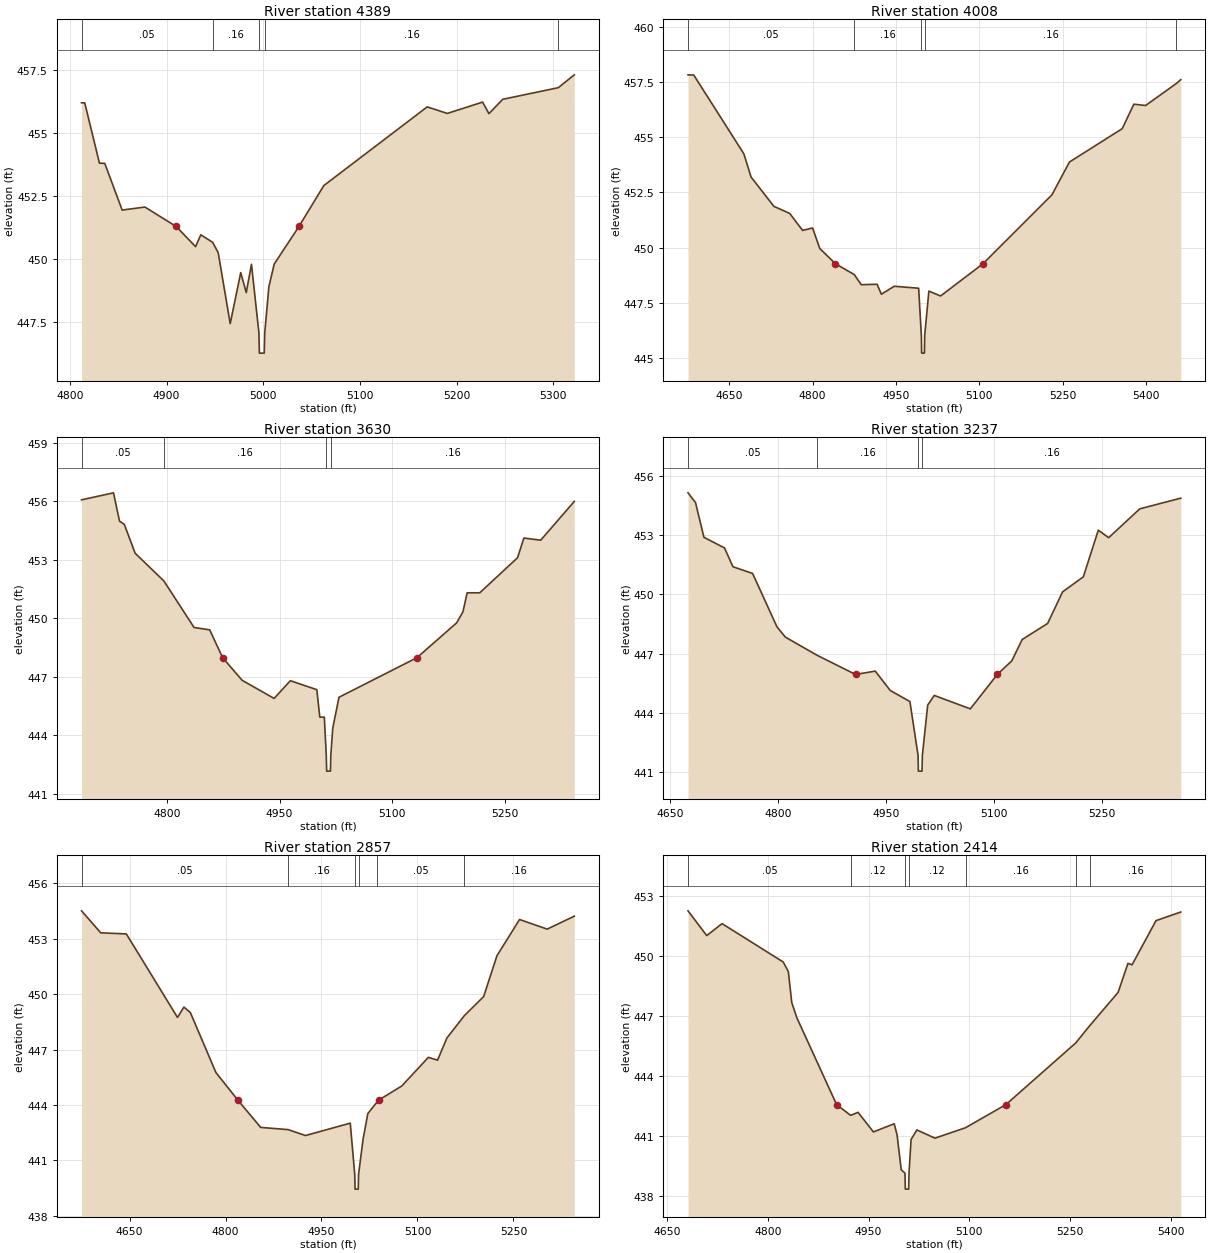
Type RM Length L Ch R = 1,4389,381,381,381
BEGIN DESCRIPTION:
UNT 048 in LFCCL Watershed 12.0
END DESCRIPTION:
XS GIS Cut Line= 3
      2804316.02      7040292.22      2804125.00      7040375.00
      2803933.17      7040607.35
#Sta/Elev= 30
  4812.1  456.19  4815.4  456.19  4830.6  453.80  4836.1  453.79  4854.1  451.94
  4877.6  452.06  4909.9  451.29  4930.0  450.49  4935.4  450.96  4947.7  450.66
  4953.4  450.25  4965.8  447.44  4976.7  449.46  4982.4  448.67  4987.8  449.79
  4995.5  447.07  4996.0  446.27  5001.0  446.27  5001.5  447.07  5005.8  448.90
  5011.3  449.80  5036.9  451.29  5062.6  452.91  5169.5  456.03  5190.3  455.77
  5226.8  456.22  5233.3  455.76  5247.6  456.33  5305.0  456.79  5321.6  457.30
#Mann=5,-1,0
  4812.1    0.05       0  4947.7    0.16       0  4995.5    0.07       0
  5001.5    0.16       0  5305.0    0.05       0
Bank Sta=4909.9,5036.9
Exp/Cntr=0.3,0.1

Type RM Length L Ch R = 1,4008,378,378,378
BEGIN DESCRIPTION:
UNT 048 in LFCCL Watershed 11.0
END DESCRIPTION:
XS GIS Cut Line= 3
      2804275.02      7040024.99      2803875.00      7040125.00
      2803724.99      7040575.02
#Sta/Elev= 30
  4575.9  457.83  4586.2  457.82  4676.4  454.25  4689.3  453.20  4730.5  451.87
  4758.9  451.55  4782.1  450.78  4800.1  450.89  4813.0  449.96  4841.2  449.27
  4875.0  448.78  4887.7  448.32  4916.1  448.34  4923.8  447.89  4947.0  448.25
  4990.9  448.16  4995.8  446.02  4996.3  445.22  5001.3  445.22  5001.8  446.02
  5009.3  448.03  5030.4  447.81  5106.7  449.27  5230.7  452.39  5262.3  453.88
  5357.2  455.39  5378.2  456.50  5399.3  456.44  5454.8  457.44  5462.6  457.61
#Mann=5,-1,0
  4575.9    0.05       0  4875.0    0.16       0  4995.8    0.07       0
  5001.8    0.16       0  5454.8    0.05       0
Bank Sta=4841.2,5106.7
Exp/Cntr=0.3,0.1

Type RM Length L Ch R = 1,3630,393,393,393
BEGIN DESCRIPTION:
UNT 048 in LFCCL Watershed 10.0
END DESCRIPTION:
XS GIS Cut Line= 3
      2803825.02      7039774.98      2803625.00      7040025.00
      2803475.00      7040325.00
#Sta/Elev= 30
  4686.5  456.08  4729.0  456.44  4737.0  454.99  4743.4  454.82  4757.8  453.34
  4796.0  451.92  4836.2  449.53  4857.0  449.41  4874.2  447.98  4900.2  446.82
  4942.7  445.89  4964.3  446.80  4999.5  446.34  5003.5  444.93  5009.5  444.93
  5012.1  442.96  5012.6  442.16  5017.6  442.16  5018.1  442.96  5020.7  444.36
  5029.0  445.95  5132.7  447.98  5185.6  449.77  5194.0  450.34  5199.5  451.31
  5216.3  451.31  5266.6  453.11  5275.0  454.12  5297.4  454.01  5342.1  456.00
#Mann=4,-1,0
  4686.5    0.05       0  4796.0    0.16       0  5012.1    0.07       0
  5018.1    0.16       0
Bank Sta=4874.2,5132.7
Exp/Cntr=0.3,0.1

Type RM Length L Ch R = 1,3237,380,380,380
BEGIN DESCRIPTION:
UNT 048 in LFCCL Watershed 9.0
END DESCRIPTION:
XS GIS Cut Line= 3
      2803724.99      7039775.00      2803375.00      7039875.00
      2803124.96      7040075.03
#Sta/Elev= 30
  4674.7  455.14  4685.1  454.65  4696.8  452.89  4725.4  452.35  4737.1  451.40
  4764.4  451.06  4798.2  448.36  4809.9  447.84  4854.0  446.92  4907.3  445.95
  4934.7  446.12  4955.5  445.14  4982.8  444.58  4994.1  441.86  4994.6  441.06
  4999.6  441.06  5000.1  441.86  5007.5  444.40  5016.6  444.89  5066.7  444.21
  5104.1  445.95  5124.3  446.64  5138.7  447.72  5174.0  448.53  5194.8  450.13
  5223.6  450.89  5244.4  453.25  5258.8  452.87  5302.0  454.33  5358.9  454.87
#Mann=4,-1,0
  4674.7    0.05       0  4854.0    0.16       0  4994.1    0.07       0
  5000.1    0.16       0
Bank Sta=4907.3,5104.1
Exp/Cntr=0.3,0.1

Type RM Length L Ch R = 1,2857,443,443,443
BEGIN DESCRIPTION:
UNT 048 in LFCCL Watershed 8.0
END DESCRIPTION:
XS GIS Cut Line= 3
      2803625.04      7039625.00      2803175.00      7039625.00
      2802975.00      7039875.00
#Sta/Elev= 30
  4575.0  454.51  4605.0  453.32  4645.0  453.26  4725.0  448.74  4735.0  449.30
  4745.0  449.01  4785.0  445.76  4819.0  444.28  4855.0  442.79  4897.9  442.67
  4925.0  442.35  4995.0  443.02  5002.0  440.25  5002.5  439.45  5007.5  439.45
  5008.0  440.25  5015.0  442.14  5022.5  443.54  5037.5  444.19  5040.0  444.28
  5075.5  445.03  5117.1  446.58  5131.5  446.43  5145.9  447.62  5173.4  448.84
  5203.5  449.87  5224.3  452.08  5259.6  454.04  5302.8  453.52  5345.2  454.22
#Mann=6,-1,0
  4575.0    0.05       0  4897.9    0.16       0  5002.0    0.07       0
  5008.0    0.16       0  5037.5    0.05       0  5173.4    0.16       0
Bank Sta=4819,5040
Exp/Cntr=0.3,0.1

Type RM Length L Ch R = 1,2414,362,362,362
BEGIN DESCRIPTION:
UNT 048 in LFCCL Watershed 7.0
END DESCRIPTION:
XS GIS Cut Line= 3
      2803575.00      7039375.00      2803275.00      7039325.00
      2802924.96      7039575.03
#Sta/Elev= 30
  4681.0  452.25  4708.9  451.01  4731.7  451.61  4822.9  449.69  4830.5  449.21
  4835.6  447.66  4843.2  446.90  4902.4  442.56  4923.3  442.02  4934.4  442.17
  4957.3  441.19  4988.2  441.60  4992.5  441.05  4998.7  439.30  5004.3  439.13
  5004.8  438.33  5009.8  438.33  5010.3  439.13  5013.4  440.81  5022.0  441.29
  5049.0  440.88  5094.5  441.40  5154.8  442.56  5258.7  445.64  5280.0  446.52
  5321.9  448.17  5336.6  449.62  5342.7  449.55  5378.4  451.76  5415.3  452.19
#Mann=7,-1,0
  4681.0    0.05       0  4923.3    0.12       0  5004.3    0.07       0
  5010.3    0.12       0  5094.5    0.16       0  5258.7    0.12       0
  5280.0    0.16       0
Bank Sta=4902.4,5154.8
Exp/Cntr=0.3,0.1

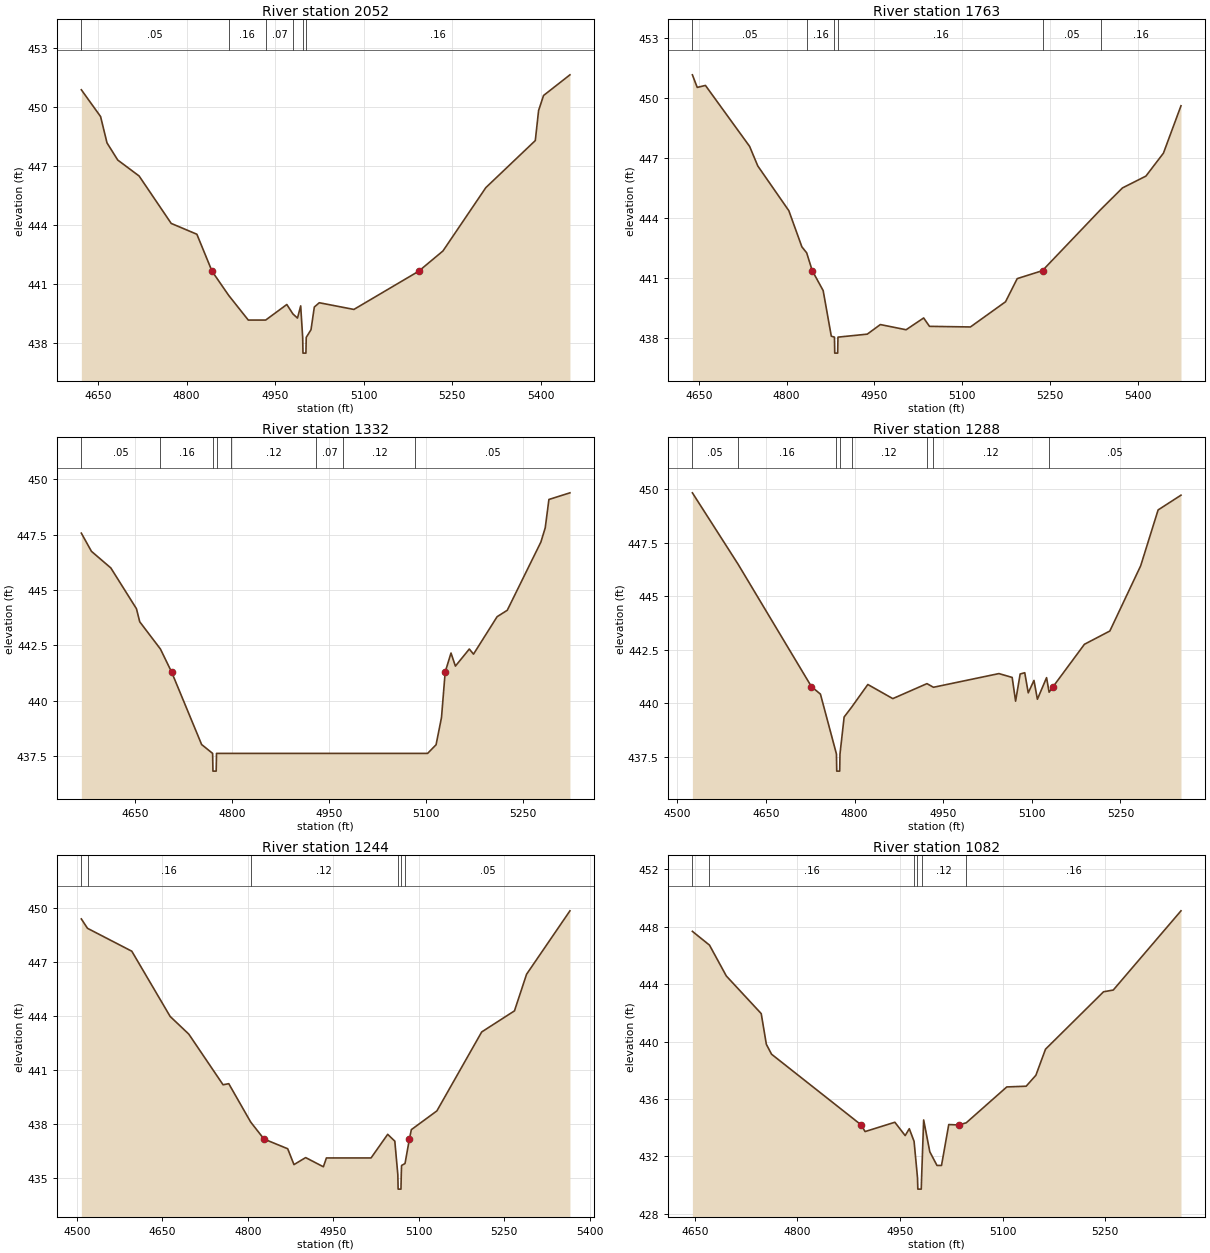
Type RM Length L Ch R = 1,2052,289,289,289
BEGIN DESCRIPTION:
UNT 048 in LFCCL Watershed 6.0
END DESCRIPTION:
XS GIS Cut Line= 3
      2803475.01      7038875.00      2803125.00      7039025.00
      2802925.01      7039424.99
#Sta/Elev= 30
  4621.7  450.86  4654.3  449.50  4665.2  448.16  4683.4  447.29  4719.6  446.48
  4774.0  444.07  4817.5  443.52  4843.2  441.64  4871.5  440.41  4904.6  439.16
  4934.1  439.16  4969.9  439.95  4980.3  439.47  4988.0  439.26  4993.4  439.88
  4996.8  438.28  4997.3  437.48  5002.3  437.48  5002.8  438.28  5010.9  438.67
  5016.5  439.82  5024.9  440.04  5083.6  439.70  5193.3  441.64  5234.5  442.67
  5307.2  445.89  5391.0  448.28  5396.6  449.81  5405.0  450.57  5449.7  451.62
#Mann=6,-1,0
  4621.7    0.05       0  4871.5    0.16       0  4934.1    0.07       0
  4980.3    0.16       0  4996.8    0.07       0  5002.8    0.16       0
Bank Sta=4843.2,5193.3
Exp/Cntr=0.3,0.1

Type RM Length L Ch R = 1,1763,431,431,431
BEGIN DESCRIPTION:
UNT 048 in LFCCL Watershed 5.0
END DESCRIPTION:
XS GIS Cut Line= 3
      2803074.98      7038525.04      2802925.00      7038825.00
      2802925.00      7039325.04
#Sta/Elev= 30
  4638.8  451.16  4647.1  450.53  4661.1  450.63  4736.6  447.58  4750.6  446.60
  4803.7  444.36  4826.0  442.55  4834.2  442.25  4843.7  441.36  4862.4  440.36
  4876.3  438.08  4881.7  438.03  4882.2  437.23  4887.2  437.23  4887.7  438.03
  4937.8  438.18  4960.2  438.66  5004.2  438.40  5034.2  438.99  5044.2  438.57
  5114.2  438.54  5174.2  439.80  5194.2  440.96  5237.5  441.36  5238.9  441.41
  5336.7  444.41  5374.2  445.50  5414.2  446.09  5444.2  447.24  5474.2  449.61
#Mann=6,-1,0
  4638.8    0.05       0  4834.2    0.16       0  4881.7    0.07       0
  4887.7    0.16       0  5238.9    0.05       0  5336.7    0.16       0
Bank Sta=4843.7,5237.5
Exp/Cntr=0.3,0.1

Type RM Length L Ch R = 1,1332,44,44,44
BEGIN DESCRIPTION:
XS3309A
END DESCRIPTION:
XS GIS Cut Line= 5
      2802990.52      7038583.89      2802761.31      7038599.52
      2802563.39      7038625.56      2802498.29      7038693.27
      2802381.13      7038893.75
#Sta/Elev= 30
  4567.2  447.57  4582.8  446.75  4612.8  446.00  4652.4  444.16  4657.5  443.57
  4689.5  442.34  4706.8  441.30  4753.2  438.03  4770.2  437.63  4770.7  436.83
  4775.7  436.83  4776.2  437.63  4799.3  437.63  4929.3  437.63  4972.5  437.63
  5083.7  437.63  5102.6  437.63  5115.7  438.02  5124.1  439.25  5129.8  441.30
  5138.8  442.16  5145.6  441.57  5167.1  442.34  5173.6  442.11  5210.1  443.80
  5225.8  444.09  5277.8  447.17  5284.5  447.81  5290.2  449.09  5322.7  449.39
#Mann=8,-1,0
  4567.2    0.05       0  4689.5    0.16       0  4770.2    0.07       0
  4776.2    0.16       0  4799.3    0.12       0  4929.3    0.07       0
  4972.5    0.12       0  5083.7    0.05       0
Bank Sta=4706.8,5129.8
Exp/Cntr=0.3,0.1

Type RM Length L Ch R = 1,1288,44,44,44
BEGIN DESCRIPTION:
XS3310A
END DESCRIPTION:
XS GIS Cut Line= 6
      2803011.26      7038544.84      2802724.85      7038563.06
      2802560.79      7038586.50      2802519.12      7038596.92
      2802498.29      7038622.96      2802344.65      7038878.16
#Sta/Elev= 30
  4525.5  449.84  4602.9  446.50  4727.0  440.78  4742.2  440.43  4769.3  437.63
  4769.8  436.83  4774.8  436.83  4775.3  437.63  4782.3  439.36  4795.0  439.82
  4822.4  440.88  4864.7  440.22  4922.5  440.92  4933.5  440.75  5044.3  441.39
  5066.7  441.21  5072.5  440.10  5080.2  441.37  5088.0  441.43  5093.9  440.49
  5103.6  441.07  5109.4  440.19  5124.9  441.20  5129.2  440.52  5136.0  440.78
  5189.0  442.76  5232.0  443.38  5284.2  446.43  5313.7  449.04  5352.4  449.73
#Mann=8,-1,0
  4525.5    0.05       0  4602.9    0.16       0  4769.3    0.07       0
  4775.3    0.16       0  4795.0    0.12       0  4922.5    0.07       0
  4933.5    0.12       0  5129.2    0.05       0
Bank Sta=4727,5136
Exp/Cntr=0.3,0.1

Type RM Length L Ch R = 1,1244,162,162,162
BEGIN DESCRIPTION:
XS3311A
END DESCRIPTION:
XS GIS Cut Line= 5
      2803003.52      7038492.75      2802704.02      7038487.54
      2802516.52      7038552.65      2802464.43      7038591.71
      2802305.60      7038839.07
#Sta/Elev= 30
  4508.1  449.39  4518.9  448.87  4596.6  447.60  4663.9  443.98  4696.6  443.00
  4756.7  440.19  4766.7  440.25  4805.2  438.12  4828.5  437.18  4870.1  436.64
  4881.1  435.76  4901.6  436.15  4932.7  435.64  4938.0  436.13  5016.3  436.13
  5045.5  437.44  5058.0  437.06  5063.3  435.20  5063.8  434.40  5068.8  434.40
  5069.3  435.20  5069.8  435.71  5075.9  435.82  5083.6  437.18  5087.0  437.70
  5131.8  438.74  5210.4  443.12  5267.9  444.29  5289.1  446.32  5365.2  449.84
#Mann=6,-1,0
  4508.1    0.05       0  4518.9    0.16       0  4805.2    0.12       0
  5063.3    0.07       0  5069.3    0.12       0  5075.9    0.05       0
Bank Sta=4828.5,5083.6
Exp/Cntr=0.3,0.1

Type RM Length L Ch R = 1,1082,347,347,347
BEGIN DESCRIPTION:
UNT 048 in LFCCL Watershed 3.0
END DESCRIPTION:
XS GIS Cut Line= 3
      2802724.98      7038225.01      2802425.00      7038425.00
      2802174.99      7038675.01
#Sta/Elev= 30
  4646.6  447.68  4671.6  446.72  4696.2  444.57  4747.2  441.95  4754.7  439.81
  4762.3  439.12  4893.4  434.19  4899.0  433.73  4942.5  434.38  4957.6  433.45
  4963.6  433.93  4970.6  433.05  4975.6  430.52  4976.1  429.72  4981.1  429.72
  4981.6  430.52  4984.6  434.54  4993.6  432.32  5004.1  431.37  5010.7  431.37
  5021.3  434.22  5035.8  434.19  5046.8  434.34  5106.1  436.84  5134.4  436.89
  5148.6  437.65  5162.7  439.47  5247.5  443.47  5261.7  443.59  5360.7  449.11
#Mann=6,-1,0
  4646.6    0.05       0  4671.6    0.16       0  4970.6    0.12       0
  4975.6    0.07       0  4981.6    0.12       0  5046.8    0.16       0
Bank Sta=4893.4,5035.8
Exp/Cntr=0.3,0.1

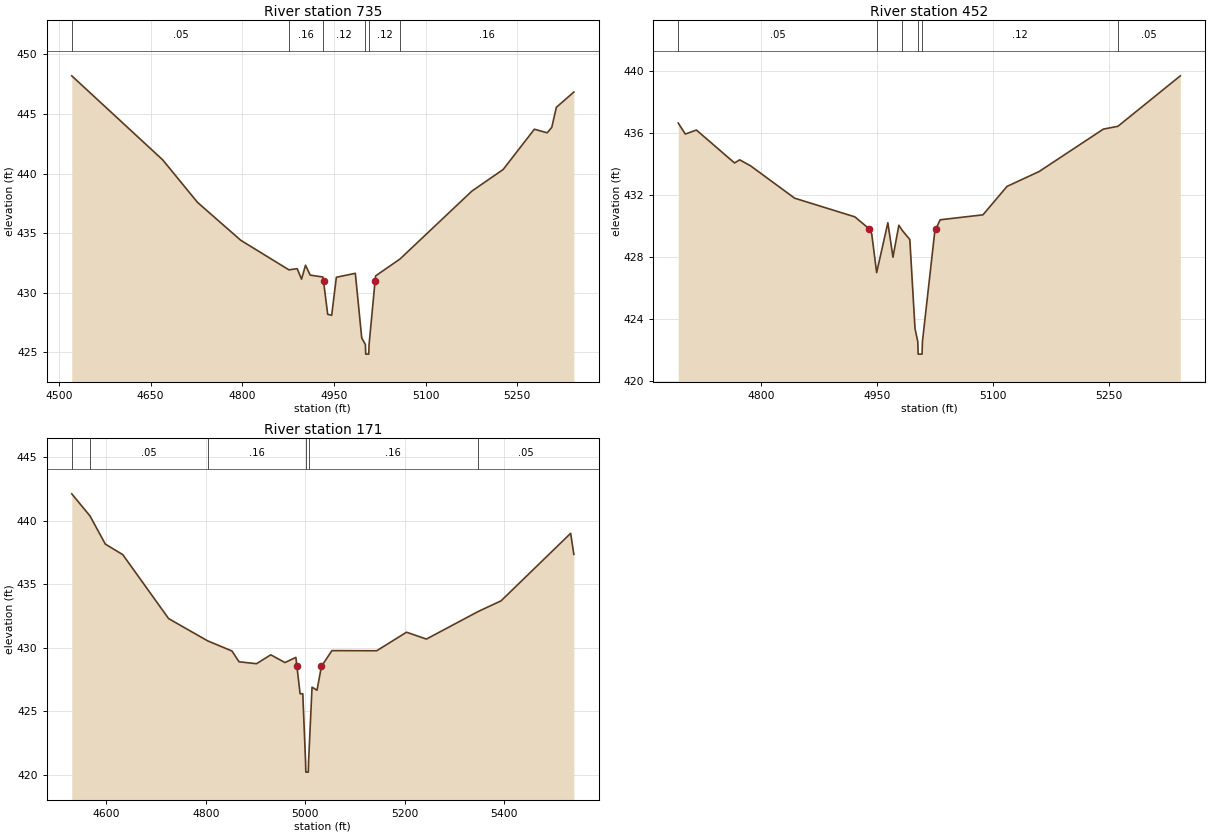
Type RM Length L Ch R = 1,735,283,283,283
BEGIN DESCRIPTION:
UNT 048 in LFCCL Watershed 2.0
END DESCRIPTION:
XS GIS Cut Line= 3
      2802525.03      7037924.98      2802175.00      7038225.00
      2801974.98      7038525.03
#Sta/Elev= 30
  4520.9  448.21  4669.7  441.16  4726.7  437.59  4797.5  434.41  4876.3  431.93
  4889.7  432.03  4896.9  431.15  4903.4  432.32  4911.1  431.49  4931.8  431.33
  4932.9  430.97  4939.7  428.20  4946.2  428.12  4953.9  431.31  4984.9  431.64
  4995.4  426.22  5001.4  425.66  5001.9  424.86  5006.9  424.86  5007.4  425.66
  5017.2  430.97  5018.0  431.42  5058.0  432.84  5175.7  438.54  5226.8  440.35
  5277.9  443.73  5298.9  443.43  5306.4  443.89  5313.9  445.57  5342.5  446.85
#Mann=6,-1,0
  4520.9    0.05       0  4876.3    0.16       0  4931.8    0.12       0
  5001.4    0.07       0  5007.4    0.12       0  5058.0    0.16       0
Bank Sta=4932.9,5017.2
Exp/Cntr=0.3,0.1

Type RM Length L Ch R = 1,452,281,281,281
BEGIN DESCRIPTION:
XS3274A
END DESCRIPTION:
XS GIS Cut Line= 3
      2802212.99      7037830.41      2801976.86      7038038.75
      2801886.83      7038360.80
#Sta/Elev= 30
  4693.0  436.63  4702.2  435.92  4716.5  436.18  4765.8  434.06  4772.5  434.26
  4786.7  433.87  4843.6  431.79  4921.4  430.59  4939.9  429.82  4943.2  429.50
  4949.6  427.00  4964.1  430.21  4970.7  427.99  4978.3  430.05  4982.8  429.71
  4992.5  429.13  4999.2  423.40  5002.8  422.55  5003.3  421.75  5008.3  421.75
  5008.8  422.55  5024.8  429.66  5026.3  429.82  5031.7  430.40  5087.1  430.72
  5118.2  432.55  5159.8  433.51  5242.8  436.24  5261.6  436.42  5342.3  439.67
#Mann=6,-1,0
  4693.0    0.05       0  4949.6    0.16       0  4982.8    0.12       0
  5002.8    0.07       0  5008.8    0.12       0  5261.6    0.05       0
Bank Sta=4939.9,5026.3
Exp/Cntr=0.3,0.1

Type RM Length L Ch R = 1,171,0,0,0
BEGIN DESCRIPTION:
UNT 048 in LFCCL Watershed 1.0
END DESCRIPTION:
XS GIS Cut Line= 3
      2802037.51      7037572.91      2801737.50      7037922.92
      2801737.50      7038471.43
#Sta/Elev= 30
  4530.4  442.11  4567.0  440.37  4597.9  438.15  4633.0  437.32  4725.2  432.28
  4803.6  430.53  4852.5  429.73  4866.8  428.88  4901.9  428.73  4930.5  429.43
  4959.0  428.82  4981.0  429.23  4983.1  428.52  4989.5  426.36  4994.9  426.36
  5000.5  420.99  5001.0  420.19  5006.0  420.19  5006.5  420.99  5013.5  426.88
  5023.5  426.64  5032.4  428.52  5053.5  429.76  5143.5  429.75  5203.5  431.21
  5243.5  430.67  5347.5  432.84  5393.5  433.68  5533.5  439.00  5539.9  437.34
#Mann=6,-1,0
  4530.4    0.16       0  4567.0    0.05       0  4803.6    0.16       0
  5000.5    0.07       0  5006.5    0.16       0  5347.5    0.05       0
Bank Sta=4983.1,5032.4
Exp/Cntr=0.3,0.1

Chan Stop Cuts=-1