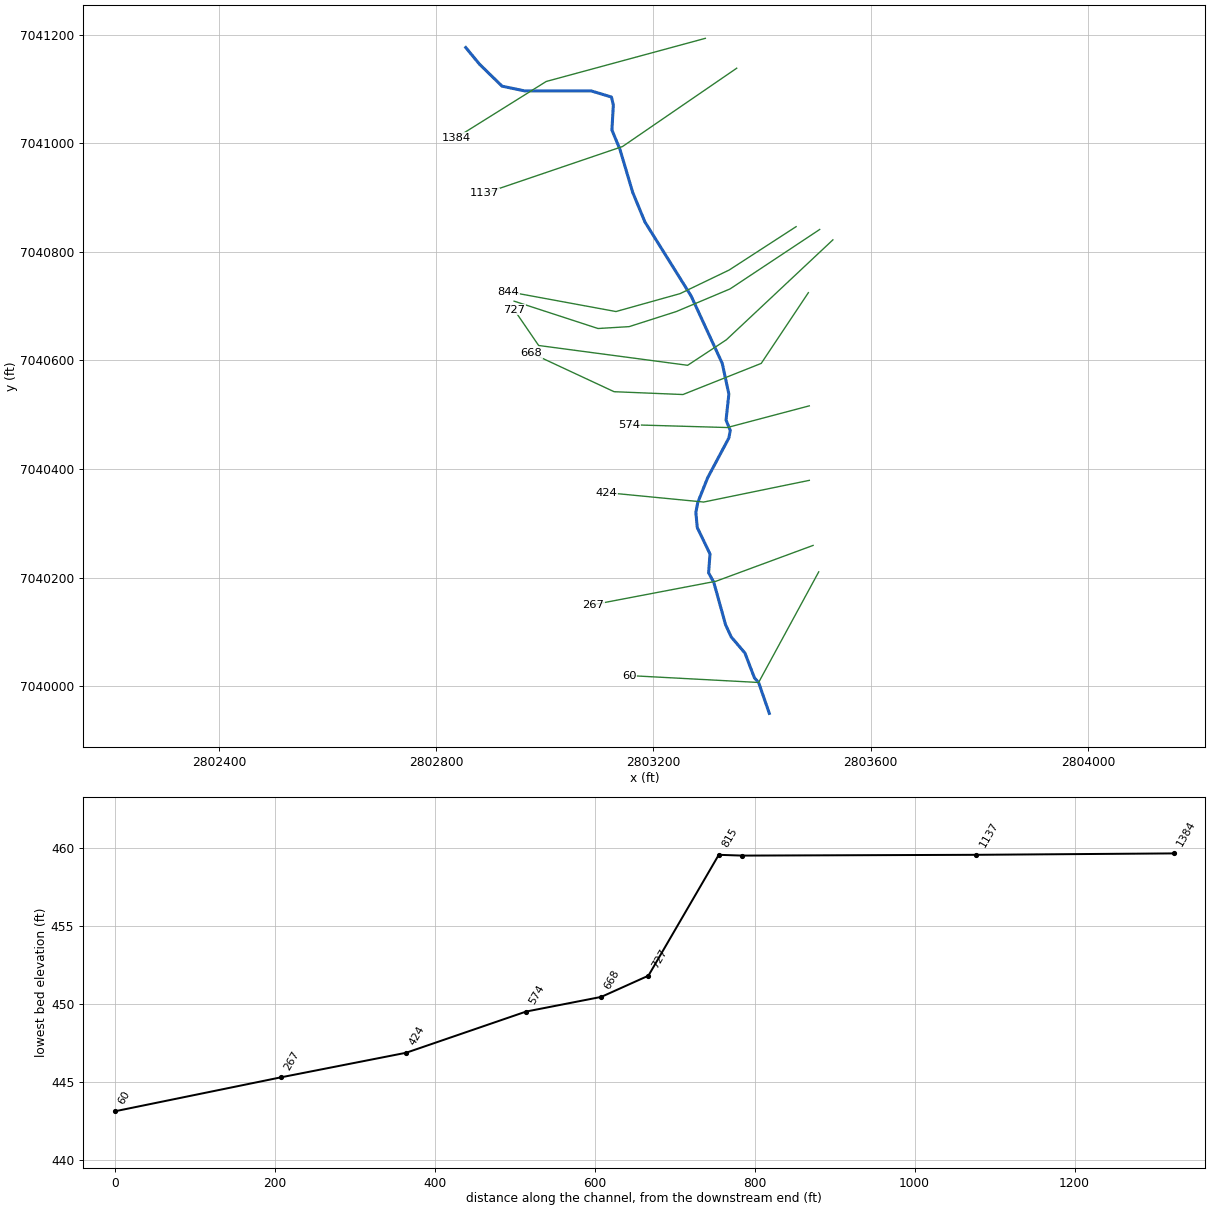
--- UNT 049 in LFCCL Watershed.prj (project) ---

Proj Title=UNT 049 in LFCCL Watershed Base Level Engineering
Current Plan=p01
Default Exp/Contr=0.3,0.1
English Units
Geom File=g01
Flow File=f01
Plan File=p01
BEGIN DESCRIPTION:
UNT 049 in LFCCL Watershed
END DESCRIPTION:

--- UNT 049 in LFCCL Watershed.p01 (plan) ---

Plan Title=Multiple Run
Short Identifier=Multiple
Geom File=g01
Flow File=f01
Subcritical Flow
K Sum by GR= 0
Std Step Tol= 0.01
Critical Tol= 0.01
Num of Std Step Trials= 20
Max Error Tol= 0.3
Flow Tol Ratio= 0.001
Split Flow NTrial= 30
Split Flow Tol= 0.02
Split Flow Ratio= 0.02
Log Output Level= 0
Friction Slope Method= 1
Unsteady Friction Slope Method= 2
Unsteady Bridges Friction Slope Method= 1
Parabolic Critical Depth
Global Vel Dist=  1 , 1 , 1
Global Log Level= 0
CheckData=True
Encroach Param= -1, 0, 0, 0
BEGIN DESCRIPTION:
Multiple Run
END DESCRIPTION:

--- UNT 049 in LFCCL Watershed.f01 (steady flow) ---

Flow Title=Multiple
Number of Profiles=7
Profile Names=10-year,25-year,50-year,1pct_min,100-year,1pct_plu,500-year
River Rch & RM= UNT 049 in LFCCL,Reach-1,1384
      48      53      57      30      61     121      69
Boundary for River Rch & Prof#=UNT 049 in LFCCL,Reach-1,1
Up Type=0
Dn Type=3
Dn Slope=0.005
Boundary for River Rch & Prof#=UNT 049 in LFCCL,Reach-1,2
Up Type=0
Dn Type=3
Dn Slope=0.005
Boundary for River Rch & Prof#=UNT 049 in LFCCL,Reach-1,3
Up Type=0
Dn Type=3
Dn Slope=0.005
Boundary for River Rch & Prof#=UNT 049 in LFCCL,Reach-1,4
Up Type=0
Dn Type=3
Dn Slope=0.005
Boundary for River Rch & Prof#=UNT 049 in LFCCL,Reach-1,5
Up Type=0
Dn Type=3
Dn Slope=0.005
Boundary for River Rch & Prof#=UNT 049 in LFCCL,Reach-1,6
Up Type=0
Dn Type=3
Dn Slope=0.005
Boundary for River Rch & Prof#=UNT 049 in LFCCL,Reach-1,7
Up Type=0
Dn Type=3
Dn Slope=0.005

--- UNT 049 in LFCCL Watershed.g01 (geometry) ---

Geom Title=Existing Conditions

River Reach=UNT 049 in LFCCL,Reach-1
Reach XY= 30
      2802854.54      7041176.04      2802879.79      7041145.42
      2802921.38      7041104.86      2802963.04      7041096.17
      2803085.44      7041096.17      2803122.77      7041084.89
      2803126.24      7041070.13      2803123.63      7041024.13
      2803138.39      7040988.54      2803161.83      7040909.54
      2803184.40      7040854.86      2803269.47      7040718.57
      2803326.76      7040594.44      2803338.91      7040538.02
      2803333.70      7040490.27      2803341.52      7040471.17
      2803338.91      7040457.29      2803299.79      7040383.83
      2803281.62      7040338.36      2803278.15      7040320.13
      2803280.75      7040292.36      2803304.19      7040243.74
      2803301.58      7040209.02      2803311.13      7040191.66
      2803332.83      7040113.54      2803343.25      7040090.97
      2803368.42      7040061.45      2803386.04      7040015.55
      2803393.67      7040007.16      2803413.37      7039950.27

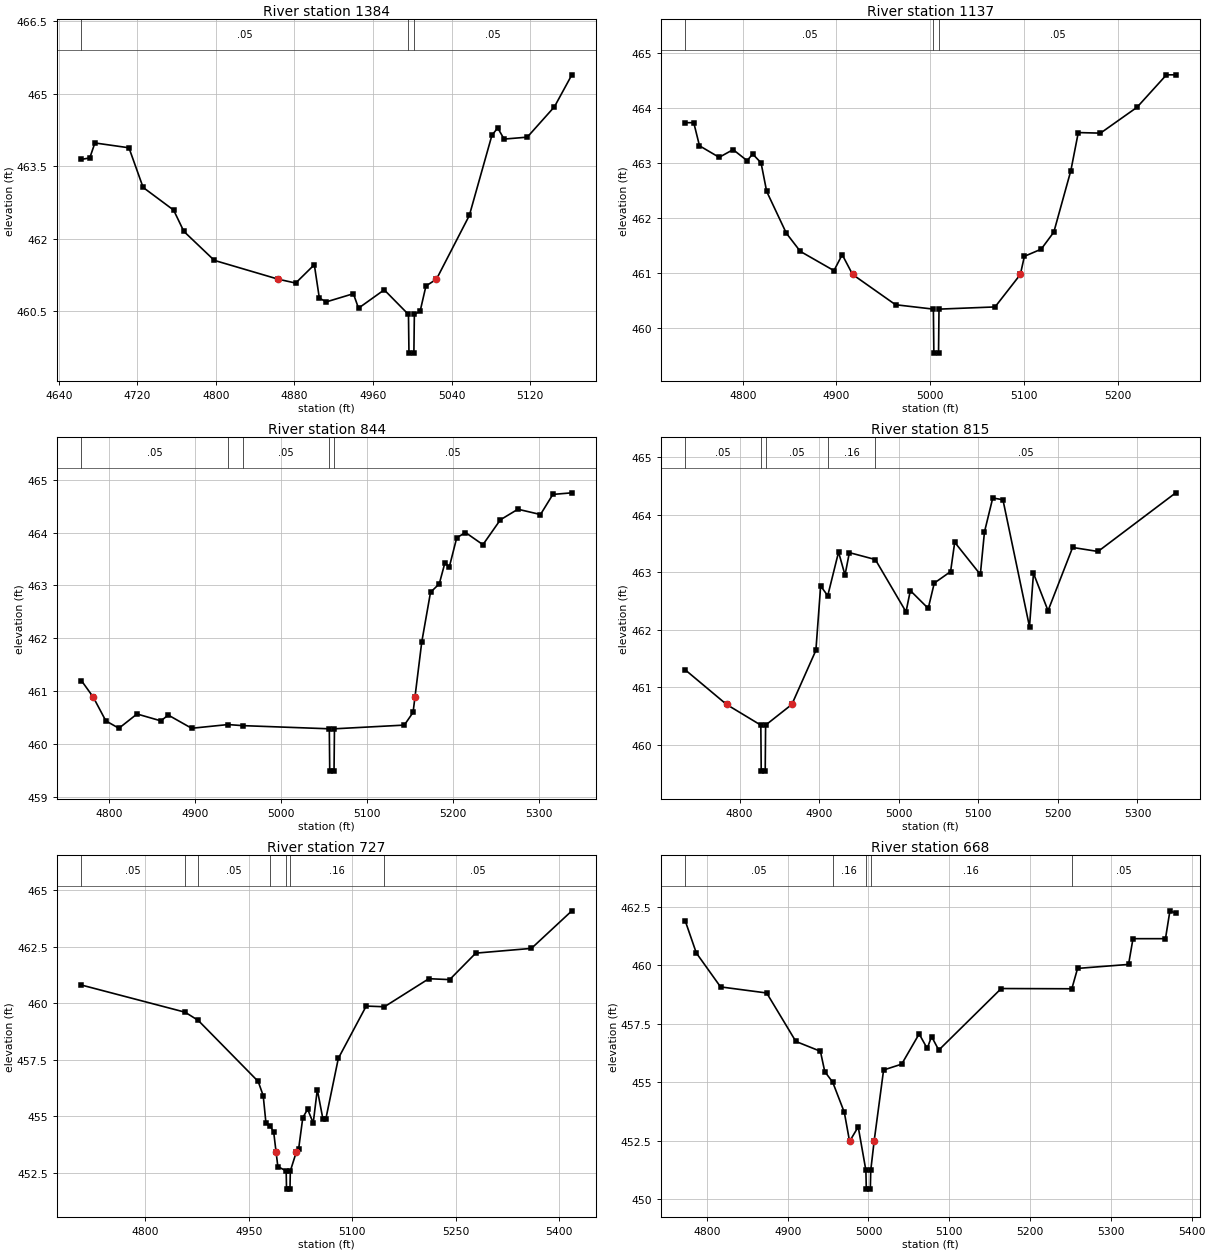
Type RM Length L Ch R = 1,1384,247,247,247
BEGIN DESCRIPTION:
XS3312A
END DESCRIPTION:
XS GIS Cut Line= 3
      2803295.62      7041192.95      2803002.62      7041113.51
      2802836.48      7041009.68
#Sta/Elev= 30
  4663.0  463.64  4671.5  463.67  4676.7  463.98  4711.4  463.88  4725.8  463.06
  4756.9  462.59  4767.3  462.15  4798.3  461.55  4863.5  461.16  4881.2  461.08
  4900.2  461.46  4905.3  460.77  4912.3  460.69  4940.0  460.86  4945.2  460.56
  4971.4  460.94  4996.1  460.43  4996.6  459.63  5001.6  459.63  5002.1  460.43
  5008.0  460.50  5013.9  461.02  5024.6  461.16  5058.1  462.48  5081.1  464.14
  5087.0  464.29  5093.5  464.06  5117.1  464.10  5144.8  464.73  5162.5  465.39
#Mann=3,-1,0
  4663.0    0.05       0  4996.1    0.03       0  5002.1    0.05       0
Bank Sta=4863.5,5024.6
Exp/Cntr=0.3,0.1

Type RM Length L Ch R = 1,1137,293,293,293
BEGIN DESCRIPTION:
XS3313A
END DESCRIPTION:
XS GIS Cut Line= 3
      2803353.34      7041137.95      2803143.24      7040993.83
      2802889.02      7040907.36
#Sta/Elev= 30
  4738.7  463.73  4747.7  463.73  4753.8  463.31  4774.8  463.10  4789.7  463.24
  4804.6  463.04  4810.6  463.16  4819.5  463.00  4825.5  462.48  4846.5  461.72
  4861.4  461.39  4897.3  461.04  4906.1  461.33  4917.2  460.97  4963.0  460.42
  5003.4  460.34  5003.9  459.54  5008.9  459.54  5009.4  460.34  5069.2  460.38
  5096.2  460.97  5100.5  461.30  5118.4  461.43  5131.9  461.74  5150.1  462.86
  5158.0  463.55  5181.7  463.54  5220.7  464.01  5252.1  464.60  5262.0  464.60
#Mann=3,-1,0
  4738.7    0.05       0  5003.4    0.03       0  5009.4    0.05       0
Bank Sta=4917.2,5096.2
Exp/Cntr=0.3,0.1

Type RM Length L Ch R = 1,844,29,29,29
BEGIN DESCRIPTION:
XS3314A
END DESCRIPTION:
XS GIS Cut Line= 5
      2803462.67      7040846.25      2803339.42      7040766.40
      2803249.15      7040723.00      2803131.09      7040690.01
      2802933.22      7040726.46
#Sta/Elev= 30
  4767.9  461.20  4781.6  460.89  4796.3  460.44  4811.5  460.30  4832.6  460.57
  4860.4  460.44  4868.9  460.55  4896.2  460.30  4938.5  460.37  4955.5  460.35
  5056.4  460.29  5056.9  459.49  5061.9  459.49  5062.4  460.29  5143.7  460.36
  5153.9  460.60  5156.1  460.89  5164.0  461.93  5174.2  462.87  5184.4  463.03
  5191.0  463.43  5196.1  463.35  5204.7  463.90  5214.9  464.00  5235.2  463.77
  5255.5  464.24  5275.9  464.44  5302.2  464.34  5316.6  464.72  5338.7  464.75
#Mann=5,-1,0
  4767.9    0.05       0  4938.5    0.16       0  4955.5    0.05       0
  5056.4    0.03       0  5062.4    0.05       0
Bank Sta=4781.6,5156.1
Exp/Cntr=0.3,0.1

Type RM Length L Ch R = 1,815,88,88,88
BEGIN DESCRIPTION:
XS3315A
END DESCRIPTION:
XS GIS Cut Line= 6
      2803506.12      7040841.07      2803341.16      7040731.68
      2803242.20      7040690.01      2803155.40      7040662.23
      2803098.11      7040658.76      2802943.55      7040709.12
#Sta/Elev= 30
  4731.7  461.30  4783.5  460.70  4826.6  460.34  4827.1  459.54  4832.1  459.54
  4832.6  460.34  4865.6  460.70  4895.8  461.64  4901.8  462.76  4910.7  462.59
  4924.3  463.35  4932.4  462.95  4937.9  463.34  4970.5  463.22  5009.1  462.31
  5014.5  462.68  5037.0  462.37  5044.6  462.81  5065.1  463.01  5070.3  463.52
  5102.5  462.96  5107.7  463.70  5118.1  464.29  5130.9  464.26  5164.3  462.05
  5169.3  462.98  5187.6  462.33  5218.5  463.43  5250.4  463.36  5348.1  464.38
#Mann=5,-1,0
  4731.7    0.05       0  4826.6    0.03       0  4832.6    0.05       0
  4910.7    0.16       0  4970.5    0.05       0
Bank Sta=4783.5,4865.6
Exp/Cntr=0.3,0.1

Type RM Length L Ch R = 1,727,59,59,59
BEGIN DESCRIPTION:
XS3316A
END DESCRIPTION:
XS GIS Cut Line= 5
      2803530.42      7040821.98      2803334.22      7040637.93
      2803263.04      7040591.05      2802988.73      7040627.51
      2802943.59      7040693.48
#Sta/Elev= 30
  4707.5  460.81  4857.7  459.61  4876.7  459.25  4963.7  456.55  4971.0  455.92
  4975.0  454.70  4981.5  454.56  4986.2  454.31  4989.6  453.44  4992.2  452.79
  5004.3  452.59  5004.8  451.79  5009.8  451.79  5010.3  452.59  5019.1  453.44
  5022.4  453.58  5028.4  454.95  5035.4  455.32  5043.5  454.71  5049.4  456.19
  5057.6  454.88  5061.7  454.88  5079.9  457.57  5120.3  459.88  5146.7  459.85
  5211.1  461.09  5241.3  461.05  5279.1  462.22  5359.8  462.43  5418.4  464.09
#Mann=7,-1,0
  4707.5    0.05       0  4857.7    0.16       0  4876.7    0.05       0
  4981.5    0.16       0  5004.3    0.07       0  5010.3    0.16       0
  5146.7    0.05       0
Bank Sta=4989.6,5019.1
Exp/Cntr=0.3,0.1

Type RM Length L Ch R = 1,668,94,94,94
BEGIN DESCRIPTION:
XS3317A
END DESCRIPTION:
XS GIS Cut Line= 5
      2803485.26      7040724.74      2803398.45      7040594.52
      2803254.36      7040537.23      2803127.62      7040542.44
      2802974.80      7040613.64
#Sta/Elev= 30
  4773.3  461.88  4786.9  460.52  4816.9  459.07  4874.0  458.81  4910.1  456.74
  4940.5  456.32  4945.9  455.45  4955.7  455.00  4970.1  453.71  4976.6  452.47
  4987.3  453.09  4996.8  451.23  4997.3  450.43  5002.3  450.43  5002.8  451.23
  5007.0  452.48  5018.7  455.52  5041.1  455.77  5062.7  457.06  5072.7  456.44
  5078.1  456.95  5087.0  456.37  5164.3  459.00  5251.7  458.99  5258.8  459.86
  5321.9  460.03  5327.4  461.13  5367.6  461.13  5373.1  462.32  5380.3  462.22
#Mann=5,-1,0
  4773.3    0.05       0  4955.7    0.16       0  4996.8    0.07       0
  5002.8    0.16       0  5251.7    0.05       0
Bank Sta=4976.6,5007
Exp/Cntr=0.3,0.1

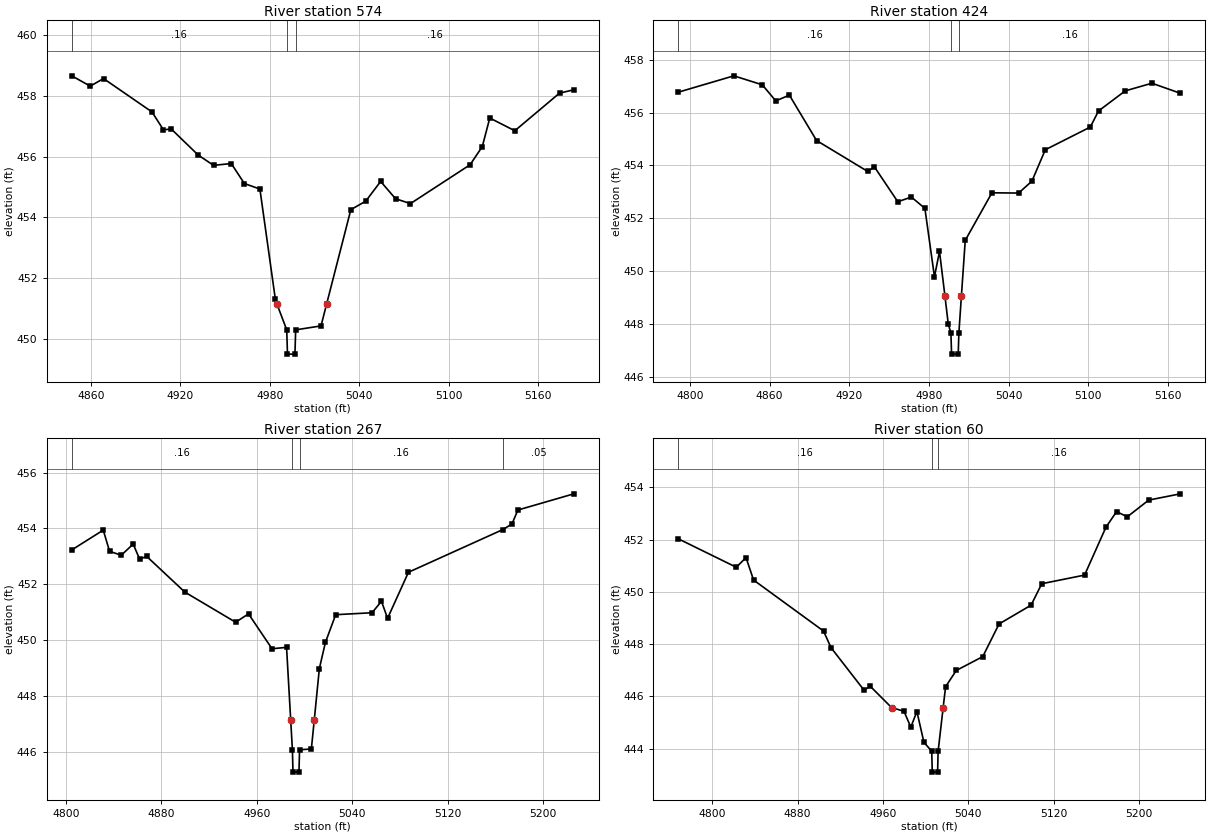
Type RM Length L Ch R = 1,574,150,150,150
BEGIN DESCRIPTION:
XS3320A
END DESCRIPTION:
XS GIS Cut Line= 3
      2803486.98      7040516.39      2803335.95      7040476.47
      2803155.44      7040481.68
#Sta/Elev= 30
  4847.1  458.66  4859.5  458.32  4868.4  458.57  4900.9  457.47  4908.6  456.88
  4913.8  456.91  4931.9  456.05  4942.2  455.71  4954.1  455.77  4962.9  455.11
  4973.3  454.93  4983.6  451.32  4984.8  451.13  4991.3  450.29  4991.8  449.49
  4996.8  449.49  4997.3  450.29  5014.3  450.42  5018.0  451.13  5034.3  454.25
  5044.3  454.53  5054.3  455.18  5064.3  454.61  5074.3  454.45  5114.3  455.73
  5122.5  456.33  5127.5  457.27  5144.3  456.85  5174.3  458.09  5183.9  458.20
#Mann=3,-1,0
  4847.1    0.16       0  4991.3    0.07       0  4997.3    0.16       0
Bank Sta=4984.8,5018
Exp/Cntr=0.3,0.1

Type RM Length L Ch R = 1,424,157,157,157
BEGIN DESCRIPTION:
XS3319A
END DESCRIPTION:
XS GIS Cut Line= 3
      2803487.03      7040379.25      2803292.55      7040339.32
      2803113.73      7040356.68
#Sta/Elev= 30
  4791.2  456.77  4833.1  457.39  4854.5  457.05  4864.7  456.44  4874.9  456.66
  4895.4  454.94  4933.9  453.77  4939.0  453.94  4956.6  452.62  4966.8  452.80
  4977.0  452.37  4984.2  449.78  4988.0  450.74  4992.1  449.05  4994.6  447.99
  4996.6  447.65  4997.1  446.85  5002.1  446.85  5002.6  447.65  5004.5  449.05
  5007.4  451.16  5027.5  452.96  5047.6  452.95  5057.6  453.40  5067.7  454.59
  5101.6  455.45  5107.8  456.06  5127.9  456.82  5148.0  457.11  5169.4  456.73
#Mann=3,-1,0
  4791.2    0.16       0  4996.6    0.07       0  5002.6    0.16       0
Bank Sta=4992.1,5004.5
Exp/Cntr=0.3,0.1

Type RM Length L Ch R = 1,267,207,207,207
BEGIN DESCRIPTION:
XS3318A
END DESCRIPTION:
XS GIS Cut Line= 3
      2803493.94      7040259.46      2803315.12      7040193.48
      2803088.81      7040150.29
#Sta/Elev= 30
  4804.8  453.23  4831.2  453.94  4836.5  453.18  4846.3  453.04  4856.3  453.44
  4861.7  452.90  4867.6  453.00  4899.6  451.72  4942.2  450.64  4953.0  450.94
  4972.7  449.69  4984.9  449.74  4988.4  447.12  4989.8  446.07  4990.3  445.27
  4995.3  445.27  4995.8  446.07  5005.7  446.10  5008.1  447.12  5012.4  448.98
  5017.5  449.92  5026.1  450.91  5056.6  450.98  5064.5  451.39  5069.6  450.78
  5087.1  452.43  5166.3  453.96  5173.9  454.16  5178.9  454.66  5225.8  455.24
#Mann=4,-1,0
  4804.8    0.16       0  4989.8    0.07       0  4995.8    0.16       0
  5166.3    0.05       0
Bank Sta=4988.4,5008.1
Exp/Cntr=0.3,0.1

Type RM Length L Ch R = 1,60,0,0,0
BEGIN DESCRIPTION:
UNT 049 in LFCCL Watershed 1.0
END DESCRIPTION:
XS GIS Cut Line= 3
      2803504.35      7040210.83      2803393.67      7040007.16
      2803155.41      7040019.87
#Sta/Elev= 30
  4768.2  452.03  4822.6  450.94  4831.7  451.31  4838.8  450.45  4904.3  448.50
  4911.4  447.86  4942.4  446.23  4948.0  446.39  4968.1  445.57  4979.7  445.43
  4986.1  444.82  4991.8  445.42  4998.4  444.24  5005.7  443.90  5006.2  443.10
  5011.2  443.10  5011.7  443.90  5016.4  445.57  5018.7  446.37  5028.7  446.99
  5053.5  447.52  5068.8  448.77  5098.8  449.49  5108.8  450.31  5148.9  450.64
  5168.9  452.47  5178.9  453.07  5188.9  452.87  5209.0  453.51  5238.6  453.75
#Mann=3,-1,0
  4768.2    0.16       0  5005.7    0.07       0  5011.7    0.16       0
Bank Sta=4968.1,5016.4
Exp/Cntr=0.3,0.1

Chan Stop Cuts=-1