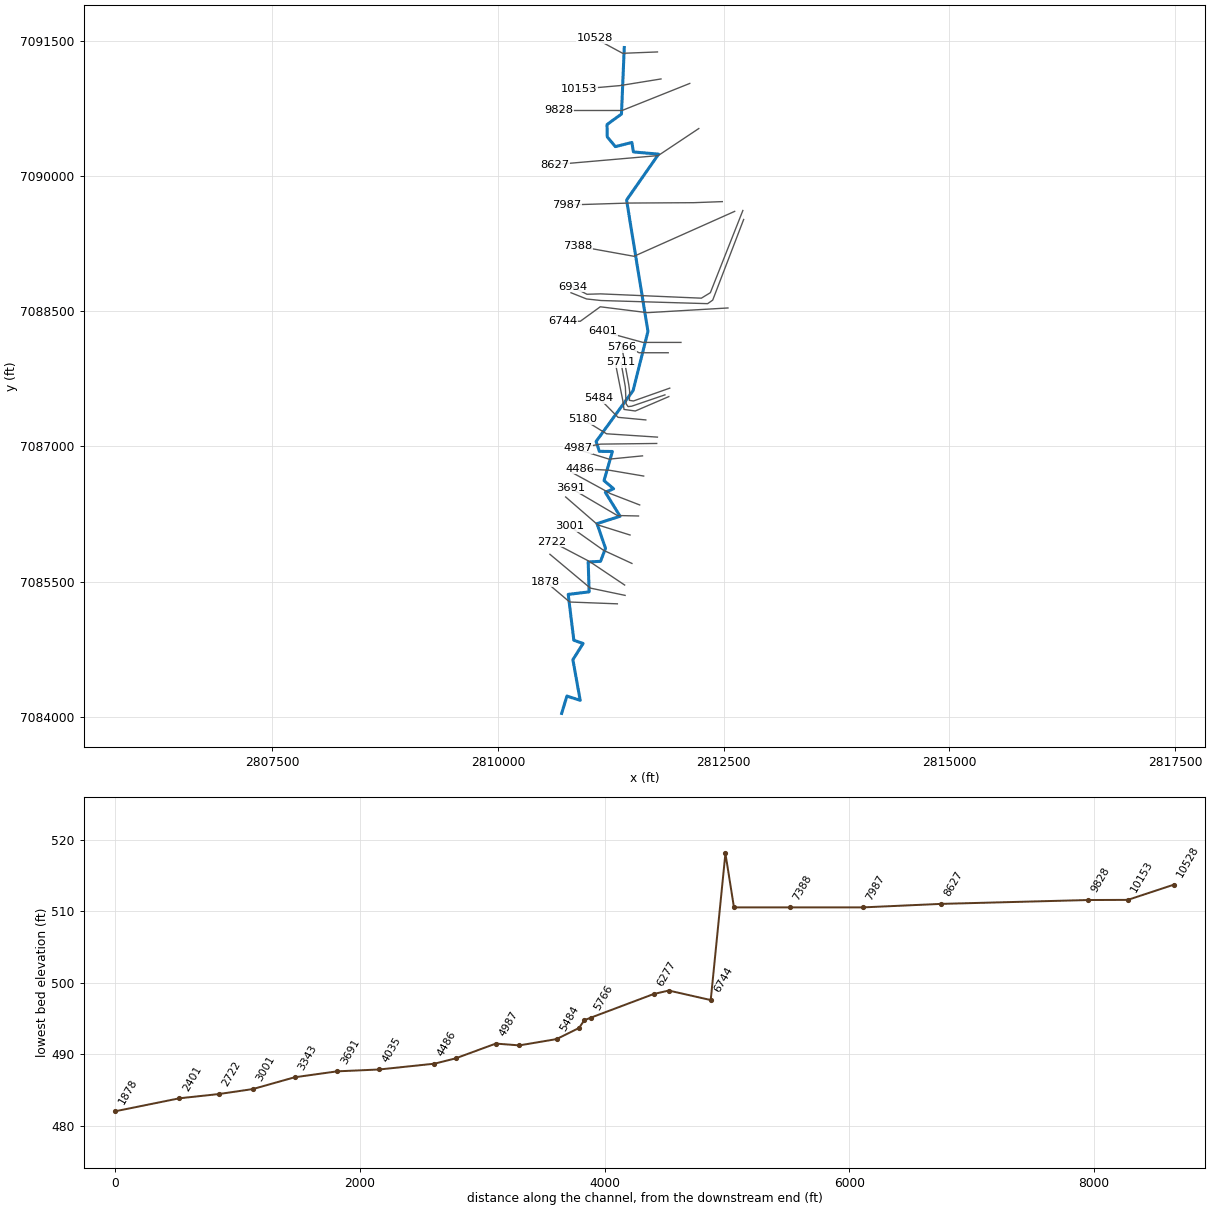
--- UNT 052 in LFCCL Watershed.prj (project) ---

Proj Title=UNT 052 in LFCCL Watershed Base Level Engineering
Current Plan=p01
Default Exp/Contr=0.3,0.1
English Units
Geom File=g01
Flow File=f01
Plan File=p01
BEGIN DESCRIPTION:
UNT 052 in LFCCL Watershed
END DESCRIPTION:

--- UNT 052 in LFCCL Watershed.p01 (plan) ---

Plan Title=Multiple Run
Short Identifier=Multiple
Geom File=g01
Flow File=f01
Subcritical Flow
K Sum by GR= 0
Std Step Tol= 0.01
Critical Tol= 0.01
Num of Std Step Trials= 20
Max Error Tol= 0.3
Flow Tol Ratio= 0.001
Split Flow NTrial= 30
Split Flow Tol= 0.02
Split Flow Ratio= 0.02
Log Output Level= 0
Friction Slope Method= 1
Unsteady Friction Slope Method= 2
Unsteady Bridges Friction Slope Method= 1
Parabolic Critical Depth
Global Vel Dist=  1 , 1 , 1
Global Log Level= 0
CheckData=True
Encroach Param= -1, 0, 0, 0
BEGIN DESCRIPTION:
Multiple Run
END DESCRIPTION:

--- UNT 052 in LFCCL Watershed.f01 (steady flow) ---

Flow Title=Multiple
Number of Profiles=7
Profile Names=10-year,25-year,50-year,1pct_min,100-year,1pct_plu,500-year
River Rch & RM= UNT 052 in LFCCL,Reach-1,10528
     712     948    1136     675    1347    2688    1890
River Rch & RM= UNT 052 in LFCCL,Reach-1,9828
     872    1169    1410     841    1678    3349    2375
Boundary for River Rch & Prof#=UNT 052 in LFCCL,Reach-1,1
Up Type=0
Dn Type=3
Dn Slope=0.005
Boundary for River Rch & Prof#=UNT 052 in LFCCL,Reach-1,2
Up Type=0
Dn Type=3
Dn Slope=0.005
Boundary for River Rch & Prof#=UNT 052 in LFCCL,Reach-1,3
Up Type=0
Dn Type=3
Dn Slope=0.005
Boundary for River Rch & Prof#=UNT 052 in LFCCL,Reach-1,4
Up Type=0
Dn Type=3
Dn Slope=0.005
Boundary for River Rch & Prof#=UNT 052 in LFCCL,Reach-1,5
Up Type=0
Dn Type=3
Dn Slope=0.005
Boundary for River Rch & Prof#=UNT 052 in LFCCL,Reach-1,6
Up Type=0
Dn Type=3
Dn Slope=0.005
Boundary for River Rch & Prof#=UNT 052 in LFCCL,Reach-1,7
Up Type=0
Dn Type=3
Dn Slope=0.005

--- UNT 052 in LFCCL Watershed.g01 (geometry) ---

Geom Title=Existing Conditions

River Reach=UNT 052 in LFCCL,Reach-1
Reach XY= 30
      2811399.14      7091423.18      2811368.37      7090685.99
      2811208.11      7090569.32      2811210.67      7090432.14
      2811300.42      7090324.45      2811483.76      7090370.60
      2811500.42      7090265.47      2811779.92      7090241.11
      2811424.78      7089732.13      2811661.59      7088275.49
      2811497.30      7087620.19      2811087.29      7087055.17
      2811123.12      7086945.89      2811267.82      7086944.43
      2811174.95      7086621.23      2811281.15      7086531.37
      2811189.48      7086491.70      2811352.88      7086226.19
      2811097.27      7086144.40      2811191.21      7085871.49
      2811136.48      7085726.41      2810999.46      7085719.63
      2811009.90      7085387.94      2810778.17      7085359.88
      2810840.57      7084851.16      2810943.02      7084815.59
      2810829.92      7084635.49      2810910.95      7084185.52
      2810763.58      7084232.52      2810705.59      7084040.71

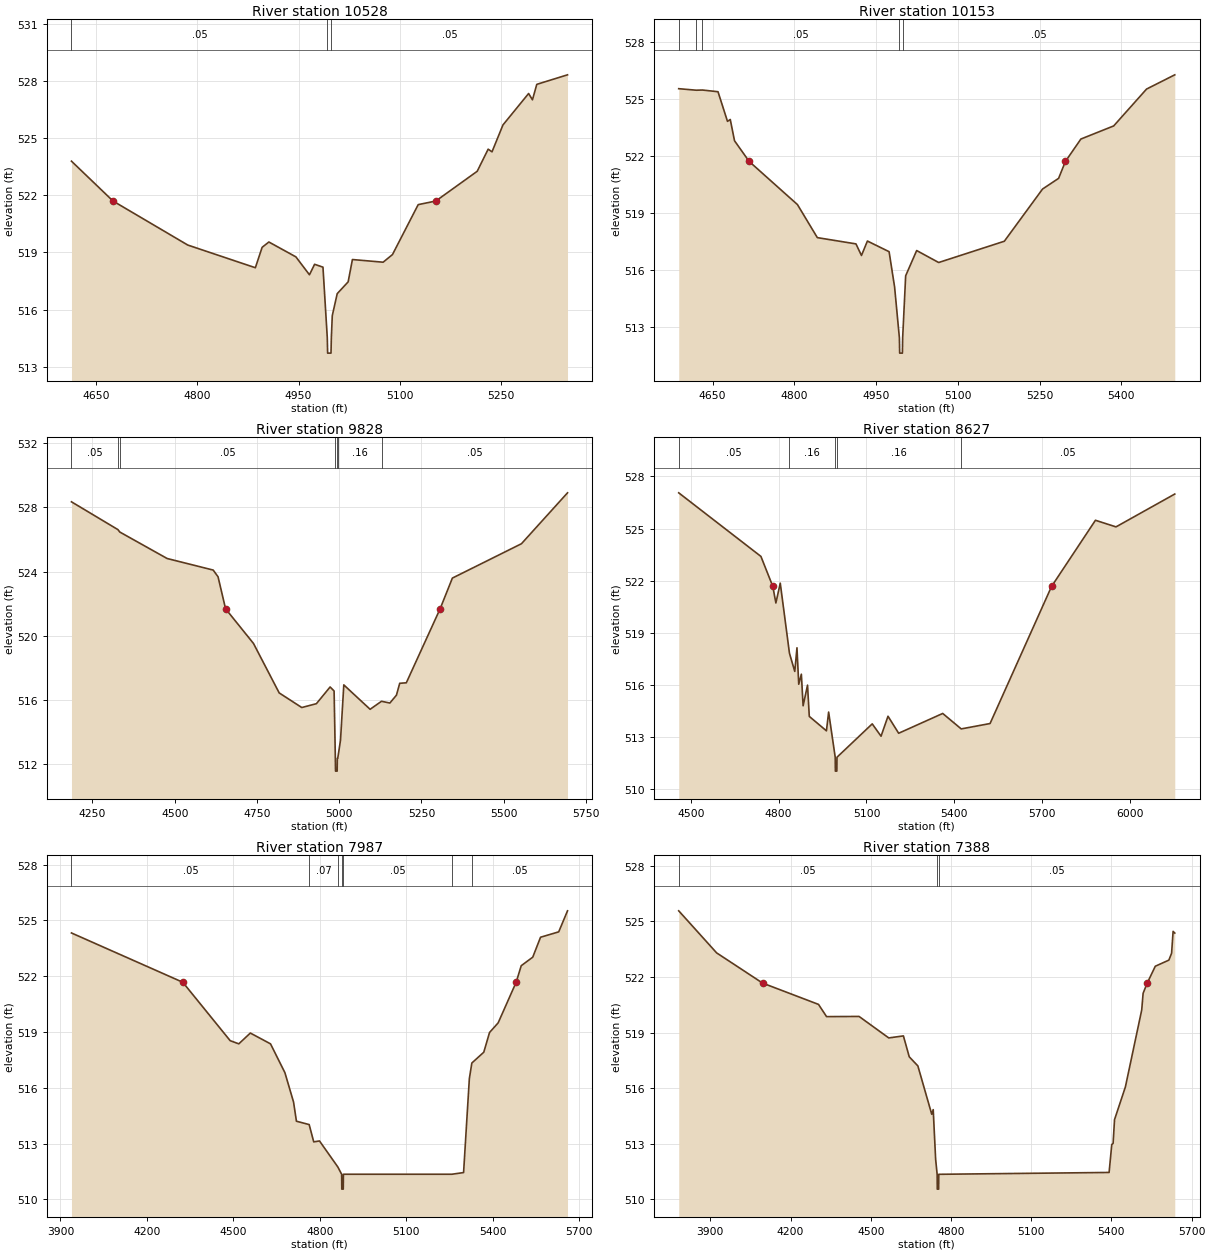
Type RM Length L Ch R = 1,10528,375,375,375
BEGIN DESCRIPTION:
UNT 052 in LFCCL Watershed 10.0
END DESCRIPTION:
XS GIS Cut Line= 3
      2811767.10      7091374.15      2811381.19      7091359.08
      2811074.96      7091525.02
#Sta/Elev= 30
  4613.8  523.79  4675.3  521.70  4786.0  519.39  4886.1  518.20  4896.1  519.27
  4906.1  519.55  4946.1  518.77  4966.2  517.83  4973.8  518.38  4986.2  518.23
  4992.6  514.52  4993.1  513.72  4998.1  513.72  4998.6  514.52  5000.0  515.69
  5007.3  516.84  5023.5  517.46  5029.8  518.63  5075.3  518.49  5089.1  518.89
  5127.2  521.51  5153.3  521.70  5214.6  523.26  5230.8  524.42  5236.5  524.28
  5252.7  525.69  5290.7  527.34  5296.4  527.01  5302.8  527.82  5348.3  528.32
#Mann=3,-1,0
  4613.8    0.05       0  4992.6    0.03       0  4998.6    0.05       0
Bank Sta=4675.3,5153.3
Exp/Cntr=0.3,0.1

Type RM Length L Ch R = 1,10153,325,325,325
BEGIN DESCRIPTION:
XS3321A
END DESCRIPTION:
XS GIS Cut Line= 3
      2811806.13      7091074.66      2811350.44      7091000.89
      2810903.37      7090961.82
#Sta/Elev= 30
  4587.8  525.52  4620.2  525.44  4631.2  525.45  4659.9  525.36  4677.3  523.80
  4682.4  523.90  4690.2  522.78  4717.1  521.69  4805.7  519.42  4842.2  517.68
  4913.1  517.35  4923.2  516.74  4934.1  517.50  4973.9  516.94  4984.0  515.08
  4992.8  512.40  4993.3  511.60  4998.3  511.60  4998.8  512.40  5004.3  515.67
  5024.5  517.00  5064.9  516.37  5185.4  517.49  5255.6  520.24  5285.0  520.80
  5297.5  521.69  5325.9  522.87  5386.1  523.56  5446.4  525.50  5498.2  526.25
#Mann=5,-1,0
  4587.8    0.05       0  4620.2    0.08       0  4631.2    0.05       0
  4992.8    0.03       0  4998.8    0.05       0
Bank Sta=4717.1,5297.5
Exp/Cntr=0.3,0.1

Type RM Length L Ch R = 1,9828,1201,1201,1201
BEGIN DESCRIPTION:
UNT 052 in LFCCL Watershed 9.0
END DESCRIPTION:
XS GIS Cut Line= 3
      2812125.00      7091025.00      2811375.00      7090725.00
      2810674.97      7090725.00
#Sta/Elev= 30
  4186.1  528.35  4327.3  526.62  4332.9  526.47  4476.9  524.82  4616.9  524.10
  4631.7  523.68  4654.5  521.69  4739.4  519.53  4817.5  516.45  4886.2  515.54
  4930.6  515.78  4972.3  516.82  4984.4  516.57  4988.2  512.38  4988.7  511.58
  4993.7  511.58  4994.2  512.38  4995.5  512.38  5003.9  513.51  5013.9  516.95
  5093.9  515.43  5128.5  515.93  5153.9  515.82  5173.9  516.31  5183.9  517.05
  5203.9  517.08  5306.7  521.69  5343.9  523.60  5553.9  525.74  5693.9  528.91
#Mann=7,-1,0
  4186.1    0.05       0  4327.3    0.08       0  4332.9    0.05       0
  4988.2    0.07       0  4994.2    0.05       0  4995.5    0.16       0
  5128.5    0.05       0
Bank Sta=4654.5,5306.7
Exp/Cntr=0.3,0.1

Type RM Length L Ch R = 1,8627,640,640,640
BEGIN DESCRIPTION:
UNT 052 in LFCCL Watershed 7.0
END DESCRIPTION:
XS GIS Cut Line= 3
      2812224.99      7090524.99      2811775.00      7090225.00
      2810624.96      7090125.00
#Sta/Elev= 30
  4458.5  527.06  4739.4  523.40  4780.1  521.67  4790.5  520.72  4805.5  521.86
  4837.0  517.82  4855.1  516.78  4862.6  518.14  4868.6  516.04  4877.6  516.62
  4883.6  514.80  4898.7  515.99  4904.7  514.19  4963.3  513.36  4970.8  514.44
  4993.3  511.84  4993.8  511.04  4998.9  511.04  4999.4  511.84  5119.8  513.76
  5149.9  513.05  5173.7  514.20  5210.1  513.22  5360.7  514.36  5423.9  513.47
  5522.5  513.78  5732.6  521.67  5882.6  525.48  5952.9  525.10  6153.7  526.99
#Mann=5,-1,0
  4458.5    0.05       0  4837.0    0.16       0  4993.3    0.07       0
  4999.4    0.16       0  5423.9    0.05       0
Bank Sta=4780.1,5732.6
Exp/Cntr=0.3,0.1

Type RM Length L Ch R = 1,7987,599,599,599
BEGIN DESCRIPTION:
XS3325A
END DESCRIPTION:
XS GIS Cut Line= 4
      2812485.53      7089714.69      2812168.70      7089702.86
      2811450.26      7089698.80      2810764.51      7089677.10
#Sta/Elev= 30
  3938.5  524.32  4324.9  521.67  4489.3  518.53  4519.3  518.36  4559.3  518.94
  4629.3  518.36  4679.3  516.81  4709.3  515.23  4719.3  514.20  4763.5  514.02
  4779.3  513.09  4799.3  513.14  4862.6  511.75  4876.2  511.35  4876.7  510.55
  4881.8  510.55  4882.3  511.35  5258.8  511.35  5299.4  511.44  5319.4  516.49
  5328.1  517.33  5369.5  517.91  5389.5  518.97  5419.5  519.49  5481.8  521.67
  5499.5  522.56  5539.5  523.02  5566.5  524.09  5629.6  524.38  5660.1  525.51
#Mann=7,-1,0
  3938.5    0.05       0  4763.5    0.07       0  4862.6    0.05       0
  4876.2   0.033       0  4882.3    0.05       0  5258.8    0.07       0
  5328.1    0.05       0
Bank Sta=4324.9,5481.8
Exp/Cntr=0.3,0.1

Type RM Length L Ch R = 1,7388,454,454,454
BEGIN DESCRIPTION:
XS3324A
END DESCRIPTION:
XS GIS Cut Line= 3
      2812622.36      7089606.51      2811506.69      7089108.52
      2810883.31      7089220.98
#Sta/Elev= 30
  3781.7  525.57  3923.5  523.30  4095.4  521.67  4304.5  520.52  4334.6  519.86
  4456.2  519.87  4567.3  518.71  4622.0  518.82  4643.9  517.69  4676.1  517.20
  4728.0  514.59  4733.5  514.84  4742.5  512.17  4748.2  511.35  4748.7  510.55
  4753.8  510.55  4754.3  511.35  5391.3  511.45  5401.2  512.95  5406.3  513.02
  5411.6  514.30  5452.3  516.07  5513.3  520.22  5518.5  521.12  5533.9  521.67
  5564.1  522.58  5614.9  522.91  5625.0  523.28  5630.7  524.46  5636.9  524.37
#Mann=3,-1,0
  3781.7    0.05       0  4748.2   0.033       0  4754.3    0.05       0
Bank Sta=4095.4,5533.9
Exp/Cntr=0.3,0.1

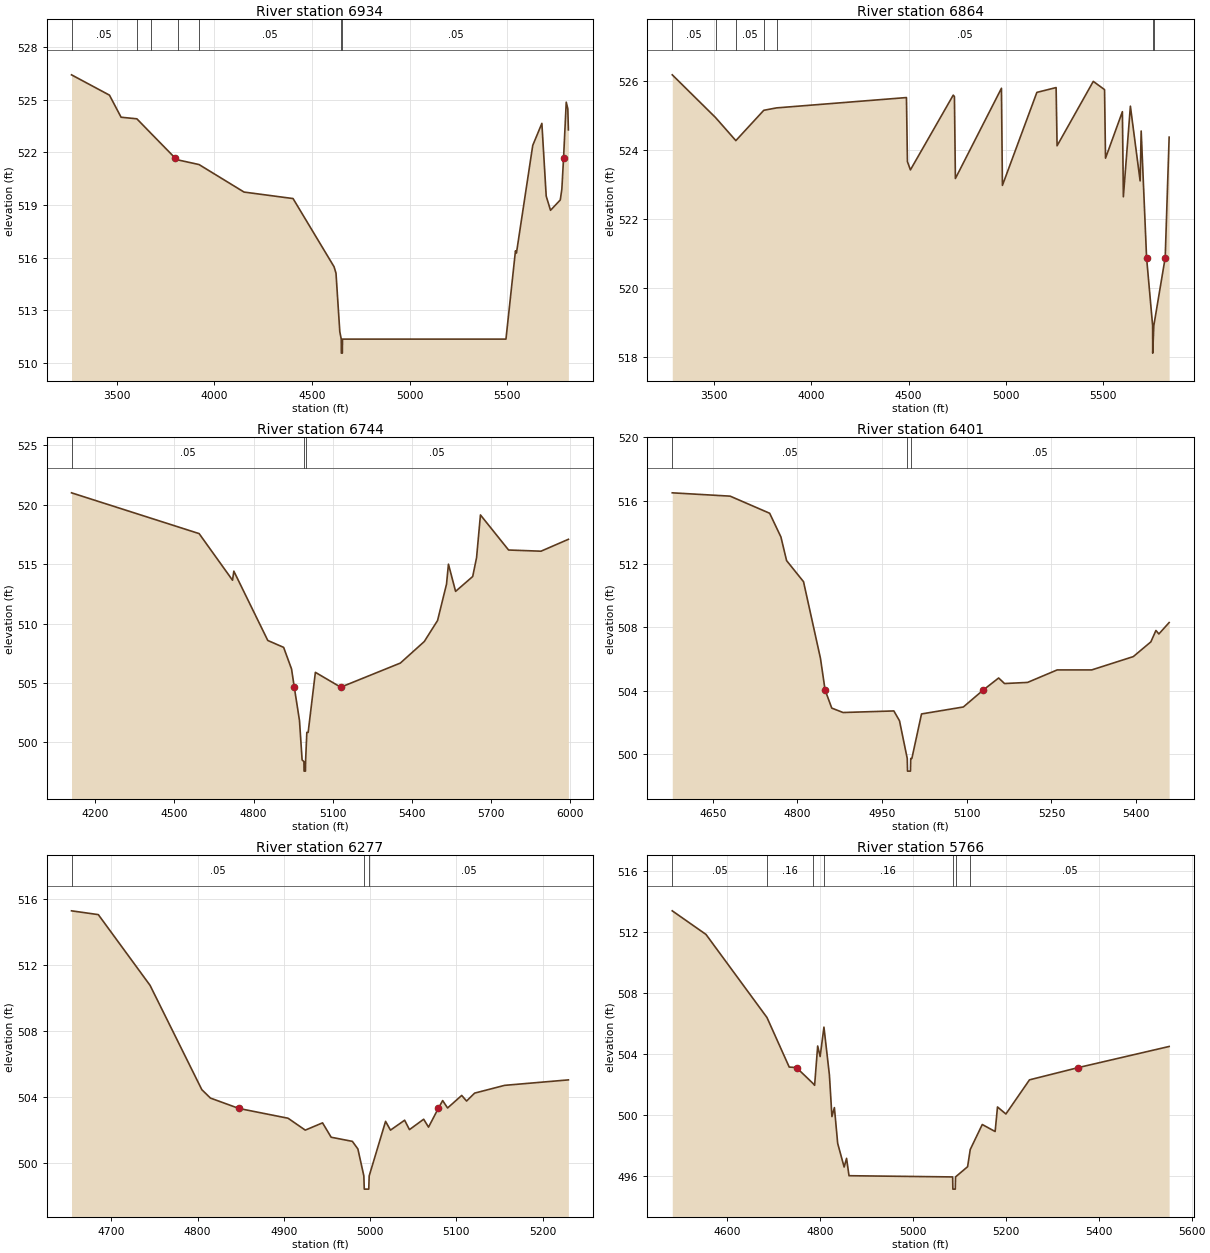
Type RM Length L Ch R = 1,6934,70,70,70
BEGIN DESCRIPTION:
XS3323A
END DESCRIPTION:
XS GIS Cut Line= 6
      2812713.29      7089616.36      2812353.04      7088704.88
      2812253.21      7088644.11      2811137.76      7088691.86
      2810985.85      7088687.52      2810825.18      7088770.14
#Sta/Elev= 30
  3267.4  526.43  3461.9  525.27  3521.4  524.01  3602.3  523.92  3675.6  523.08
  3799.4  521.67  3814.7  521.57  3920.8  521.31  4151.5  519.74  4402.6  519.37
  4612.7  515.48  4622.7  515.11  4642.2  511.77  4649.6  511.35  4650.1  510.55
  4655.3  510.55  4655.8  511.35  5493.6  511.35  5542.3  516.39  5547.3  516.26
  5630.8  522.40  5677.6  523.66  5699.8  519.51  5721.9  518.70  5771.9  519.29
  5780.0  519.91  5788.7  521.67  5802.5  524.87  5810.6  524.49  5813.5  523.29
#Mann=7,-1,0
  3267.4    0.05       0  3602.3    0.08       0  3675.6    0.05       0
  3814.7    0.08       0  3920.8    0.05       0  4649.6    0.03       0
  4655.8    0.05       0
Bank Sta=3799.4,5788.7
Exp/Cntr=0.3,0.1

Type RM Length L Ch R = 1,6864,120,120,120
BEGIN DESCRIPTION:
XS3322A
END DESCRIPTION:
XS GIS Cut Line= 6
      2812721.95      7089516.48      2812379.08      7088622.41
      2812322.66      7088583.35      2811142.10      7088618.07
      2810981.51      7088635.43      2810808.97      7088704.45
#Sta/Elev= 30
  3284.3  526.18  3506.9  524.94  3611.4  524.27  3755.1  525.15  3820.8  525.22
  4489.1  525.52  4494.1  523.66  4509.5  523.42  4729.7  525.59  4735.9  525.55
  4740.9  523.17  4977.8  525.79  4982.8  522.97  5160.0  525.67  5259.0  525.81
  5264.0  524.12  5450.2  525.99  5508.2  525.75  5513.2  523.76  5600.0  525.11
  5605.0  522.64  5641.1  525.27  5691.2  523.10  5696.6  524.55  5724.4  520.87
  5755.5  518.90  5756.0  518.10  5761.7  518.90  5820.2  520.87  5840.5  524.37
#Mann=7,-1,0
  3284.3    0.05       0  3506.9    0.08       0  3611.4    0.05       0
  3755.1    0.08       0  3820.8    0.05       0  5755.5    0.03       0
  5761.7    0.05       0
Bank Sta=5724.4,5820.2
Exp/Cntr=0.3,0.1

Type RM Length L Ch R = 1,6744,343,343,343
BEGIN DESCRIPTION:
XS3326A
END DESCRIPTION:
XS GIS Cut Line= 5
      2812548.31      7088535.61      2811654.25      7088483.52
      2811133.42      7088548.63      2810912.07      7088388.04
      2810721.09      7088388.04
#Sta/Elev= 30
  4109.6  521.00  4593.7  517.57  4720.4  513.65  4725.4  514.41  4854.2  508.58
  4914.3  508.00  4944.3  506.18  4954.7  504.65  4974.4  501.85  4984.4  498.53
  4991.3  498.39  4991.8  497.59  4997.0  497.59  4997.5  498.39  5002.3  500.85
  5007.3  500.85  5034.7  505.90  5130.9  504.65  5357.1  506.68  5447.8  508.49
  5498.2  510.26  5532.2  513.32  5539.5  515.00  5566.6  512.71  5631.5  513.96
  5646.2  515.55  5660.9  519.14  5767.6  516.19  5890.6  516.09  5994.5  517.09
#Mann=3,-1,0
  4109.6    0.05       0  4991.3    0.03       0  4997.5    0.05       0
Bank Sta=4954.7,5130.9
Exp/Cntr=0.3,0.1

Type RM Length L Ch R = 1,6401,124,124,124
BEGIN DESCRIPTION:
XS3327A
END DESCRIPTION:
XS GIS Cut Line= 3
      2812027.51      7088153.66      2811606.51      7088153.66
      2811163.79      7088275.20
#Sta/Elev= 30
  4578.3  516.49  4680.8  516.28  4750.8  515.20  4770.8  513.70  4780.8  512.21
  4810.8  510.88  4840.8  506.04  4849.0  504.04  4860.8  502.90  4880.8  502.62
  4970.8  502.72  4980.8  502.10  4994.5  499.72  4995.0  498.92  5000.2  498.92
  5000.7  499.72  5002.7  499.72  5019.8  502.53  5093.9  502.97  5129.1  504.04
  5156.4  504.80  5166.8  504.45  5207.6  504.52  5260.1  505.31  5321.3  505.31
  5394.9  506.15  5426.0  507.08  5435.0  507.80  5440.2  507.58  5458.4  508.30
#Mann=3,-1,0
  4578.3    0.05       0  4994.5    0.03       0  5000.7    0.05       0
Bank Sta=4849,5129.1
Exp/Cntr=0.3,0.1

Type RM Length L Ch R = 1,6277,511,511,511
BEGIN DESCRIPTION:
XS3331A
END DESCRIPTION:
XS GIS Cut Line= 3
      2811886.07      7088039.08      2811563.11      7088039.08
      2811338.71      7088156.46
#Sta/Elev= 30
  4653.7  515.27  4684.8  515.04  4744.8  510.76  4804.8  504.45  4814.8  503.94
  4847.9  503.31  4904.8  502.72  4924.8  502.00  4944.8  502.44  4954.8  501.57
  4979.4  501.32  4985.8  500.86  4992.7  499.23  4993.2  498.43  4998.4  498.43
  4998.9  499.23  5017.9  502.53  5023.6  502.00  5040.0  502.60  5045.6  502.03
  5062.1  502.66  5067.7  502.18  5079.0  503.31  5084.1  503.79  5089.8  503.34
  5106.2  504.10  5111.8  503.76  5121.2  504.24  5156.0  504.71  5229.9  505.04
#Mann=3,-1,0
  4653.7    0.05       0  4992.7    0.03       0  4998.9    0.05       0
Bank Sta=4847.9,5079
Exp/Cntr=0.3,0.1

Type RM Length L Ch R = 1,5766,55,55,55
BEGIN DESCRIPTION:
XS3330A
END DESCRIPTION:
XS GIS Cut Line= 6
      2811903.43      7087646.73      2811500.61      7087504.36
      2811455.47      7087511.30      2811458.94      7087612.00
      2811448.53      7087688.39      2811372.28      7088100.79
#Sta/Elev= 30
  4481.3  513.40  4554.0  511.85  4685.3  506.40  4733.2  503.15  4749.0  503.11
  4783.9  502.09  4787.9  501.95  4794.5  504.53  4799.8  503.84  4808.0  505.77
  4819.8  502.62  4825.2  499.90  4830.5  500.49  4837.6  498.14  4851.5  496.59
  4856.7  497.16  4862.0  496.02  5085.2  495.94  5085.7  495.14  5090.9  495.14
  5091.4  495.94  5117.4  496.61  5123.1  497.74  5149.0  499.38  5176.7  498.92
  5181.8  500.53  5199.9  500.07  5250.7  502.31  5355.2  503.11  5551.5  504.50
#Mann=7,-1,0
  4481.3    0.05       0  4685.3    0.16       0  4783.9    0.05       0
  4808.0    0.16       0  5085.2    0.07       0  5091.4    0.16       0
  5123.1    0.05       0
Bank Sta=4749,5355.2
Exp/Cntr=0.3,0.1

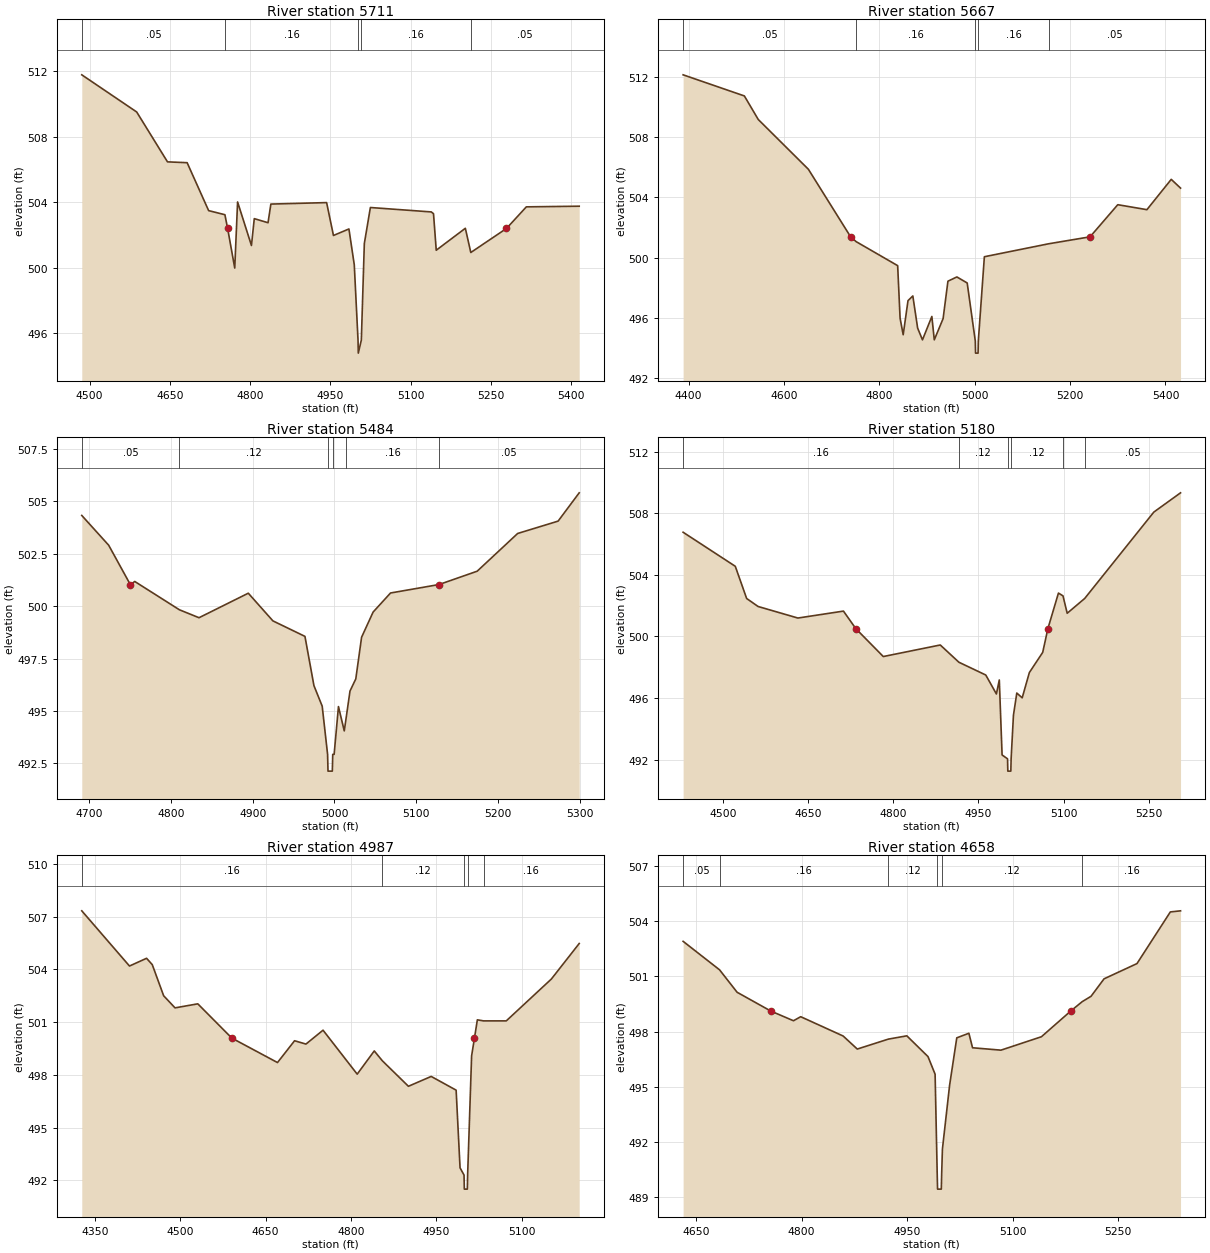
Type RM Length L Ch R = 1,5711,44,44,44
BEGIN DESCRIPTION:
XS3328A
END DESCRIPTION:
XS GIS Cut Line= 6
      2811849.61      7087572.08      2811480.64      7087446.20
      2811441.58      7087441.86      2811419.88      7087472.24
      2811411.20      7087658.87      2811363.67      7087931.11
#Sta/Elev= 30
  4485.5  511.78  4588.1  509.51  4645.7  506.46  4682.4  506.41  4722.6  503.48
  4753.0  503.23  4758.1  502.39  4771.4  499.97  4776.7  504.01  4802.6  501.35
  4807.9  502.99  4833.6  502.74  4838.9  503.88  4943.1  503.97  4955.9  501.96
  4984.8  502.36  4994.8  500.17  5001.8  495.57  5002.3  494.77  5008.0  495.57
  5013.6  501.47  5024.9  503.67  5138.8  503.40  5142.9  503.29  5148.0  501.06
  5202.4  502.40  5212.6  500.92  5279.3  502.39  5316.4  503.71  5415.2  503.75
#Mann=5,-1,0
  4485.5    0.05       0  4753.0    0.16       0  5001.8    0.07       0
  5008.0    0.16       0  5212.6    0.05       0
Bank Sta=4758.1,5279.3
Exp/Cntr=0.3,0.1

Type RM Length L Ch R = 1,5667,183,183,183
BEGIN DESCRIPTION:
XS3329A
END DESCRIPTION:
XS GIS Cut Line= 5
      2811892.95      7087552.96      2811521.44      7087393.25
      2811396.44      7087410.61      2811382.55      7087511.30
      2811302.68      7087914.13
#Sta/Elev= 30
  4388.7  512.13  4517.1  510.73  4546.2  509.17  4651.3  505.87  4739.9  501.39
  4751.5  501.07  4838.5  499.48  4843.6  495.99  4850.1  494.90  4860.2  497.16
  4870.3  497.47  4880.4  495.34  4890.5  494.56  4910.2  496.11  4915.3  494.56
  4933.8  495.97  4943.9  498.45  4962.7  498.73  4984.3  498.33  5001.3  494.48
  5001.8  493.68  5007.1  493.68  5007.6  494.48  5020.3  500.07  5155.2  500.93
  5241.9  501.39  5300.0  503.52  5361.1  503.19  5412.1  505.20  5431.6  504.62
#Mann=5,-1,0
  4388.7    0.05       0  4751.5    0.16       0  5001.3    0.07       0
  5007.6    0.16       0  5155.2    0.05       0
Bank Sta=4739.9,5241.9
Exp/Cntr=0.3,0.1

Type RM Length L Ch R = 1,5484,304,304,304
BEGIN DESCRIPTION:
XS3332A
END DESCRIPTION:
XS GIS Cut Line= 3
      2811637.81      7087294.28      2811330.47      7087322.93
      2811119.76      7087536.24
#Sta/Elev= 30
  4690.9  504.33  4723.8  502.91  4750.3  501.03  4755.7  501.18  4810.3  499.83
  4834.3  499.45  4894.6  500.62  4924.7  499.30  4963.9  498.56  4974.9  496.21
  4985.0  495.23  4991.6  492.93  4992.1  492.13  4997.4  492.13  4997.9  492.93
  4999.6  492.93  5004.9  495.21  5012.0  494.05  5014.3  494.67  5019.0  495.95
  5026.1  496.53  5033.2  498.52  5047.3  499.72  5068.6  500.63  5127.4  501.03
  5128.4  501.04  5174.6  501.67  5224.1  503.47  5273.6  504.06  5299.4  505.41
#Mann=6,-1,0
  4690.9    0.05       0  4810.3    0.12       0  4991.6    0.07       0
  4997.9    0.12       0  5014.3    0.16       0  5128.4    0.05       0
Bank Sta=4750.3,5127.4
Exp/Cntr=0.3,0.1

Type RM Length L Ch R = 1,5180,193,193,193
BEGIN DESCRIPTION:
XS3333A
END DESCRIPTION:
XS GIS Cut Line= 3
      2811766.58      7087103.58      2811202.87      7087140.64
      2810938.63      7087303.85
#Sta/Elev= 30
  4430.3  506.76  4522.1  504.55  4542.1  502.46  4562.2  501.94  4632.3  501.19
  4712.5  501.64  4734.3  500.50  4782.6  498.69  4882.9  499.44  4915.7  498.32
  4963.0  497.49  4981.7  496.26  4986.8  497.17  4991.7  492.30  5001.3  492.05
  5001.8  491.25  5007.1  491.25  5007.6  492.05  5011.7  494.88  5017.6  496.32
  5027.1  496.01  5039.7  497.65  5063.2  498.96  5072.3  500.50  5090.9  502.81
  5098.9  502.63  5106.3  501.50  5137.1  502.46  5258.8  508.07  5305.8  509.32
#Mann=6,-1,0
  4430.3    0.16       0  4915.7    0.12       0  5001.3    0.07       0
  5007.6    0.12       0  5098.9    0.16       0  5137.1    0.05       0
Bank Sta=4734.3,5072.3
Exp/Cntr=0.3,0.1

Type RM Length L Ch R = 1,4987,329,329,329
BEGIN DESCRIPTION:
XS3334A
END DESCRIPTION:
XS GIS Cut Line= 3
      2811758.77      7087033.27      2811137.76      7087026.06
      2810888.89      7086981.99
#Sta/Elev= 30
  4327.0  507.33  4410.8  504.19  4440.8  504.63  4450.8  504.27  4470.8  502.50
  4490.8  501.81  4530.8  502.04  4590.6  500.09  4670.8  498.70  4700.8  499.94
  4720.8  499.75  4750.8  500.54  4810.8  498.04  4840.8  499.36  4855.0  498.80
  4900.8  497.35  4940.8  497.91  4984.6  497.13  4991.5  492.71  4998.5  492.30
  4999.0  491.50  5004.3  491.50  5004.8  492.30  5011.8  499.08  5016.8  500.09
  5021.9  501.13  5032.7  501.07  5072.7  501.07  5151.9  503.45  5200.8  505.47
#Mann=5,-1,0
  4327.0    0.16       0  4855.0    0.12       0  4998.5    0.07       0
  5004.8    0.12       0  5032.7    0.16       0
Bank Sta=4590.6,5016.8
Exp/Cntr=0.3,0.1

Type RM Length L Ch R = 1,4658,172,172,172
BEGIN DESCRIPTION:
XS3335A
END DESCRIPTION:
XS GIS Cut Line= 3
      2811601.34      7086895.85      2811231.51      7086859.39
      2810911.17      7086958.36
#Sta/Elev= 30
  4631.7  502.91  4683.5  501.36  4708.4  500.14  4756.2  499.12  4788.5  498.59
  4798.8  498.81  4859.1  497.76  4879.2  497.05  4923.3  497.59  4949.6  497.77
  4979.7  496.64  4989.8  495.68  4992.8  490.23  4993.3  489.43  4998.6  489.43
  4999.1  490.23  5000.2  491.61  5010.4  495.08  5020.6  497.66  5037.8  497.91
  5043.0  497.12  5083.4  496.99  5140.9  497.72  5182.6  499.12  5198.9  499.63
  5211.4  499.92  5229.9  500.87  5276.7  501.70  5324.1  504.51  5338.6  504.57
#Mann=6,-1,0
  4631.7    0.05       0  4683.5    0.16       0  4923.3    0.12       0
  4992.8    0.07       0  4999.1    0.12       0  5198.9    0.16       0
Bank Sta=4756.2,5182.6
Exp/Cntr=0.3,0.1

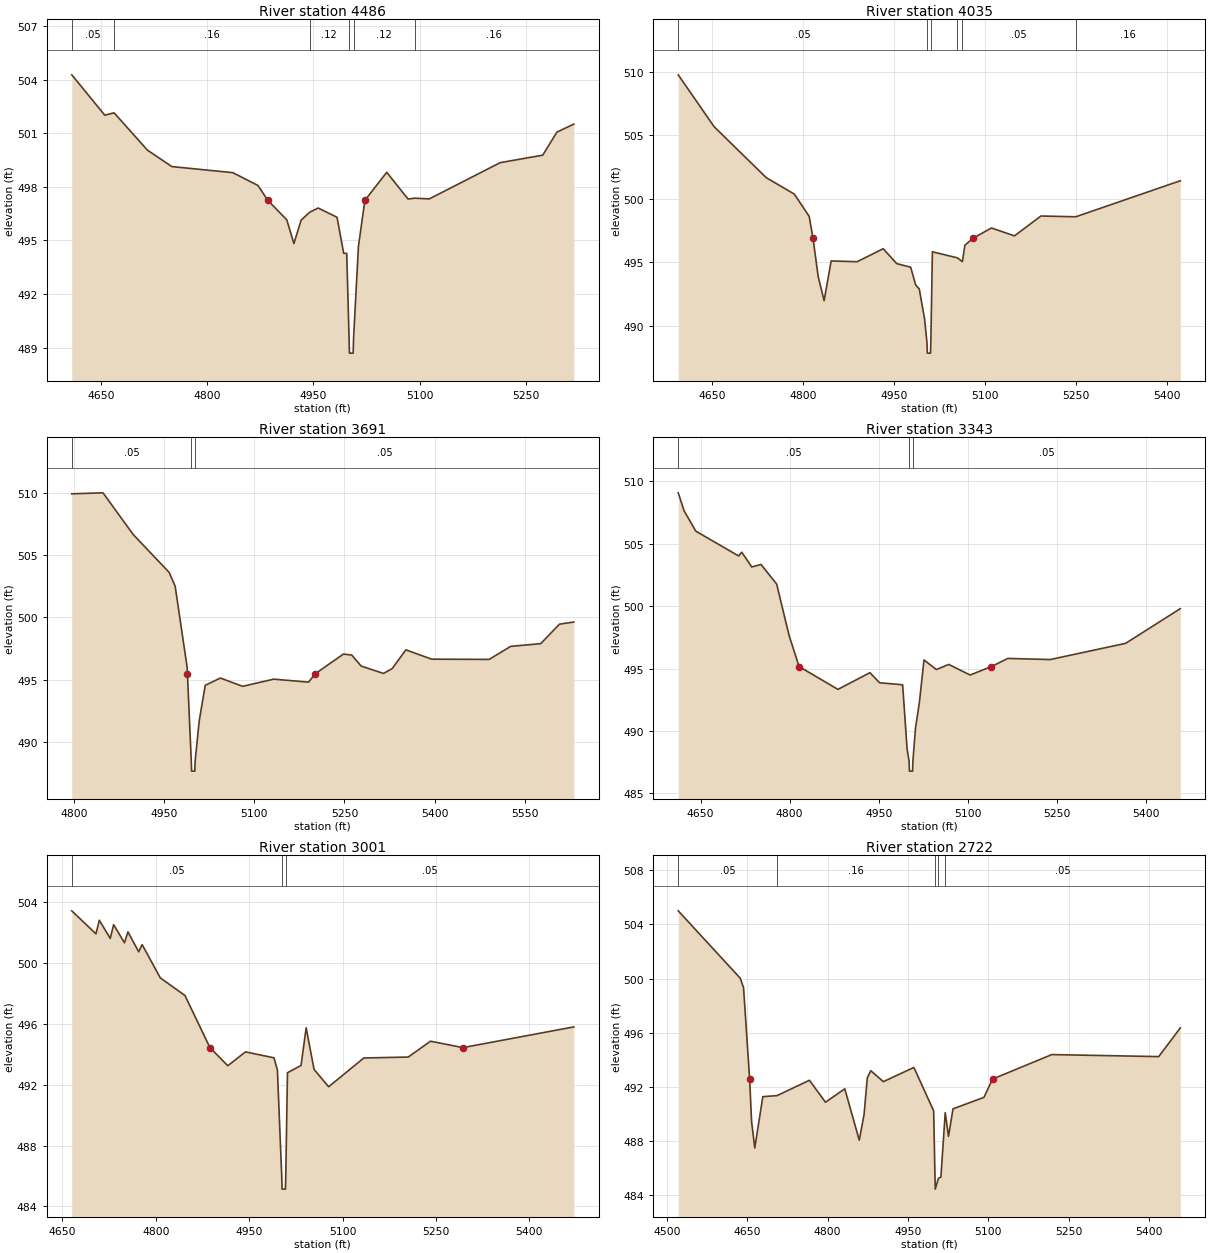
Type RM Length L Ch R = 1,4486,451,451,451
BEGIN DESCRIPTION:
XS3336A
END DESCRIPTION:
XS GIS Cut Line= 3
      2811614.28      7086671.90      2811231.51      7086737.00
      2810911.16      7086752.62
#Sta/Elev= 30
  4608.8  504.28  4655.4  502.02  4668.6  502.15  4715.7  500.06  4750.1  499.14
  4836.2  498.80  4871.8  498.08  4885.6  497.25  4912.4  496.16  4922.5  494.83
  4932.7  496.14  4944.7  496.58  4956.7  496.82  4983.4  496.30  4992.8  494.28
  4997.1  494.28  5000.4  489.49  5000.9  488.69  5006.2  488.69  5006.7  489.49
  5013.6  494.66  5022.7  497.25  5053.6  498.82  5083.7  497.32  5092.8  497.37
  5113.7  497.33  5213.8  499.36  5273.9  499.78  5293.9  501.07  5317.8  501.52
#Mann=6,-1,0
  4608.8    0.05       0  4668.6    0.16       0  4944.7    0.12       0
  5000.4    0.07       0  5006.7    0.12       0  5092.8    0.16       0
Bank Sta=4885.6,5022.7
Exp/Cntr=0.3,0.1

Type RM Length L Ch R = 1,4035,344,344,344
BEGIN DESCRIPTION:
XS3337A
END DESCRIPTION:
XS GIS Cut Line= 4
      2811570.10      7086351.56      2811247.14      7086476.58
      2811140.37      7086536.48      2810825.23      7086708.37
#Sta/Elev= 30
  4594.8  509.74  4653.9  505.67  4739.7  501.67  4786.2  500.37  4810.7  498.62
  4817.0  496.90  4825.5  493.90  4835.3  492.00  4846.9  495.12  4889.8  495.06
  4932.7  496.08  4955.0  494.91  4978.0  494.63  4986.3  493.22  4992.1  492.93
  5000.9  490.57  5004.9  488.68  5005.4  487.88  5010.7  487.88  5011.2  488.68
  5013.8  495.84  5054.6  495.37  5063.2  495.07  5067.4  496.36  5080.8  496.90
  5111.1  497.71  5149.1  497.09  5192.7  498.65  5250.2  498.59  5422.5  501.42
#Mann=6,-1,0
  4594.8    0.05       0  5004.9    0.03       0  5011.2    0.05       0
  5054.6    0.16       0  5063.2    0.05       0  5250.2    0.16       0
Bank Sta=4817,5080.8
Exp/Cntr=0.3,0.1

Type RM Length L Ch R = 1,3691,348,348,348
BEGIN DESCRIPTION:
XS3343A
END DESCRIPTION:
XS GIS Cut Line= 3
      2811557.03      7086229.18      2811322.66      7086234.39
      2810804.43      7086539.08
#Sta/Elev= 30
  4796.3  509.96  4848.3  510.04  4898.4  506.69  4958.4  503.63  4968.4  502.51
  4988.4  495.96  4988.8  495.47  4995.2  488.42  4995.7  487.62  5001.1  487.62
  5001.6  488.42  5008.4  491.66  5018.4  494.53  5043.6  495.12  5080.7  494.45
  5132.4  495.03  5190.4  494.79  5201.7  495.47  5248.4  497.05  5262.3  496.97
  5278.0  496.08  5315.1  495.49  5329.6  495.88  5352.3  497.39  5395.2  496.64
  5490.9  496.62  5526.8  497.67  5576.8  497.89  5608.0  499.46  5631.9  499.63
#Mann=3,-1,0
  4796.3    0.05       0  4995.2    0.03       0  5001.6    0.05       0
Bank Sta=4988.8,5201.7
Exp/Cntr=0.3,0.1

Type RM Length L Ch R = 1,3343,342,342,342
BEGIN DESCRIPTION:
XS3342A
END DESCRIPTION:
XS GIS Cut Line= 3
      2811463.25      7086018.26      2811106.51      7086130.23
      2810749.94      7086439.95
#Sta/Elev= 30
  4612.2  509.09  4622.1  507.65  4641.8  506.02  4714.1  504.03  4719.3  504.33
  4736.1  503.15  4751.7  503.35  4778.1  501.78  4799.0  497.66  4815.9  495.17
  4881.4  493.34  4935.3  494.68  4951.5  493.87  4990.4  493.71  4997.9  488.58
  5001.3  487.59  5001.8  486.79  5007.2  486.79  5007.7  487.59  5012.1  490.24
  5018.7  492.31  5026.4  495.70  5047.2  494.93  5068.1  495.34  5104.2  494.49
  5140.0  495.17  5167.8  495.82  5239.1  495.73  5366.3  497.03  5458.4  499.81
#Mann=3,-1,0
  4612.2    0.05       0  5001.3    0.03       0  5007.7    0.05       0
Bank Sta=4815.9,5140
Exp/Cntr=0.3,0.1

Type RM Length L Ch R = 1,3001,279,279,279
BEGIN DESCRIPTION:
XS3341A
END DESCRIPTION:
XS GIS Cut Line= 3
      2811484.09      7085703.15      2811169.01      7085848.98
      2810794.04      7086114.58
#Sta/Elev= 30
  4664.9  503.41  4703.7  501.90  4709.2  502.79  4726.7  501.60  4732.2  502.50
  4749.6  501.31  4755.1  502.03  4772.5  500.72  4778.0  501.19  4807.1  499.01
  4846.8  497.85  4886.9  494.43  4915.6  493.24  4944.0  494.15  4989.8  493.76
  4995.3  492.96  5002.3  485.94  5002.8  485.14  5008.2  485.14  5008.7  485.94
  5011.5  492.78  5033.3  493.26  5041.5  495.73  5054.2  493.00  5077.6  491.86
  5134.2  493.75  5205.6  493.81  5241.2  494.85  5293.4  494.43  5471.6  495.79
#Mann=3,-1,0
  4664.9    0.05       0  5002.3    0.03       0  5008.7    0.05       0
Bank Sta=4886.9,5293.4
Exp/Cntr=0.3,0.1

Type RM Length L Ch R = 1,2722,321,321,321
BEGIN DESCRIPTION:
XS3339A
END DESCRIPTION:
XS GIS Cut Line= 3
      2811403.38      7085463.56      2811015.37      7085723.98
      2810599.32      7085942.40
#Sta/Elev= 30
  4521.3  505.00  4637.1  500.02  4643.2  499.32  4654.6  492.57  4658.2  489.43
  4664.2  487.48  4679.2  491.27  4705.8  491.35  4766.2  492.48  4796.2  490.86
  4832.2  491.85  4859.2  488.06  4868.2  489.96  4874.2  492.66  4880.7  493.19
  4904.2  492.38  4961.2  493.43  4998.1  490.22  5000.6  485.24  5001.1  484.44
  5007.0  485.24  5011.6  485.33  5019.7  490.09  5025.8  488.34  5034.2  490.37
  5092.0  491.22  5108.0  492.57  5218.6  494.38  5418.2  494.23  5458.5  496.35
#Mann=5,-1,0
  4521.3    0.05       0  4705.8    0.16       0  5000.6    0.07       0
  5007.0    0.16       0  5019.7    0.05       0
Bank Sta=4654.6,5108
Exp/Cntr=0.3,0.1

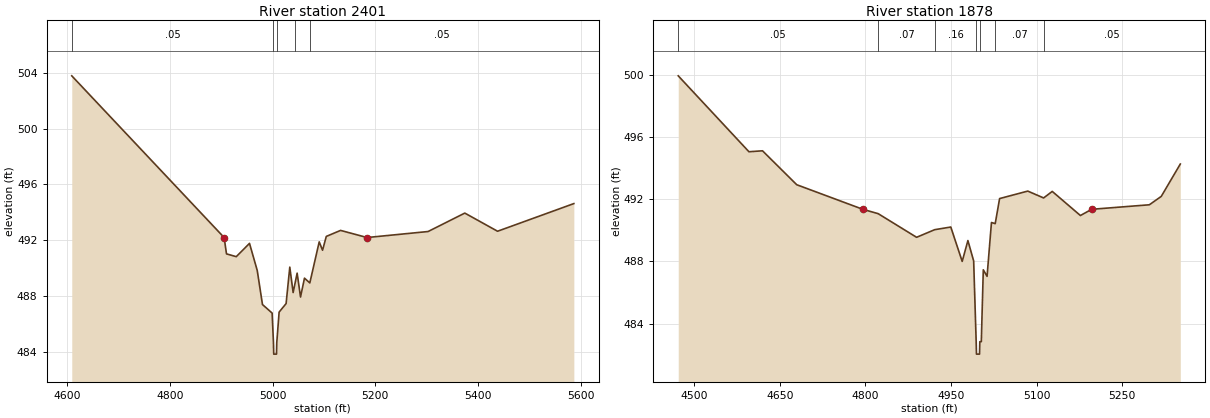
Type RM Length L Ch R = 1,2401,523,523,523
BEGIN DESCRIPTION:
XS3340A
END DESCRIPTION:
XS GIS Cut Line= 3
      2811408.62      7085348.97      2811023.18      7085429.70
      2810575.24      7085804.72
#Sta/Elev= 30
  4608.7  503.78  4905.5  492.20  4910.1  491.03  4929.1  490.83  4954.9  491.78
  4970.0  489.84  4980.2  487.40  4999.0  486.79  5001.6  484.65  5002.1  483.85
  5007.5  483.85  5008.0  484.65  5012.6  486.86  5026.2  487.47  5033.4  490.08
  5039.9  488.26  5042.7  488.76  5047.7  489.65  5054.3  487.94  5062.0  489.29
  5072.4  488.95  5090.7  491.89  5097.2  491.29  5104.5  492.28  5132.3  492.71
  5183.9  492.20  5302.8  492.63  5374.3  493.95  5438.1  492.65  5586.7  494.63
#Mann=5,-1,0
  4608.7    0.05       0  5001.6    0.03       0  5008.0    0.05       0
  5042.7    0.16       0  5072.4    0.05       0
Bank Sta=4905.5,5183.9
Exp/Cntr=0.3,0.1

Type RM Length L Ch R = 1,1878,0,0,0
BEGIN DESCRIPTION:
XS3338A
END DESCRIPTION:
XS GIS Cut Line= 3
      2811322.68      7085255.23      2810794.66      7085275.37
      2810525.75      7085502.65
#Sta/Elev= 30
  4471.6  499.93  4595.6  495.05  4619.4  495.11  4679.4  492.93  4795.3  491.35
  4822.2  491.07  4889.6  489.55  4921.4  490.04  4949.6  490.21  4969.6  488.00
  4979.6  489.34  4989.7  488.03  4994.1  482.84  4994.6  482.04  5000.0  482.04
  5000.5  482.84  5003.1  482.84  5006.6  487.46  5013.2  487.04  5020.9  490.50
  5027.5  490.43  5035.2  492.04  5084.6  492.52  5112.4  492.08  5127.5  492.50
  5176.9  490.95  5196.7  491.35  5297.8  491.64  5318.7  492.18  5352.1  494.26
#Mann=7,-1,0
  4471.6    0.05       0  4822.2    0.07       0  4921.4    0.16       0
  4994.1    0.07       0  5000.5    0.16       0  5027.5    0.07       0
  5112.4    0.05       0
Bank Sta=4795.3,5196.7
Exp/Cntr=0.3,0.1

Chan Stop Cuts=-1