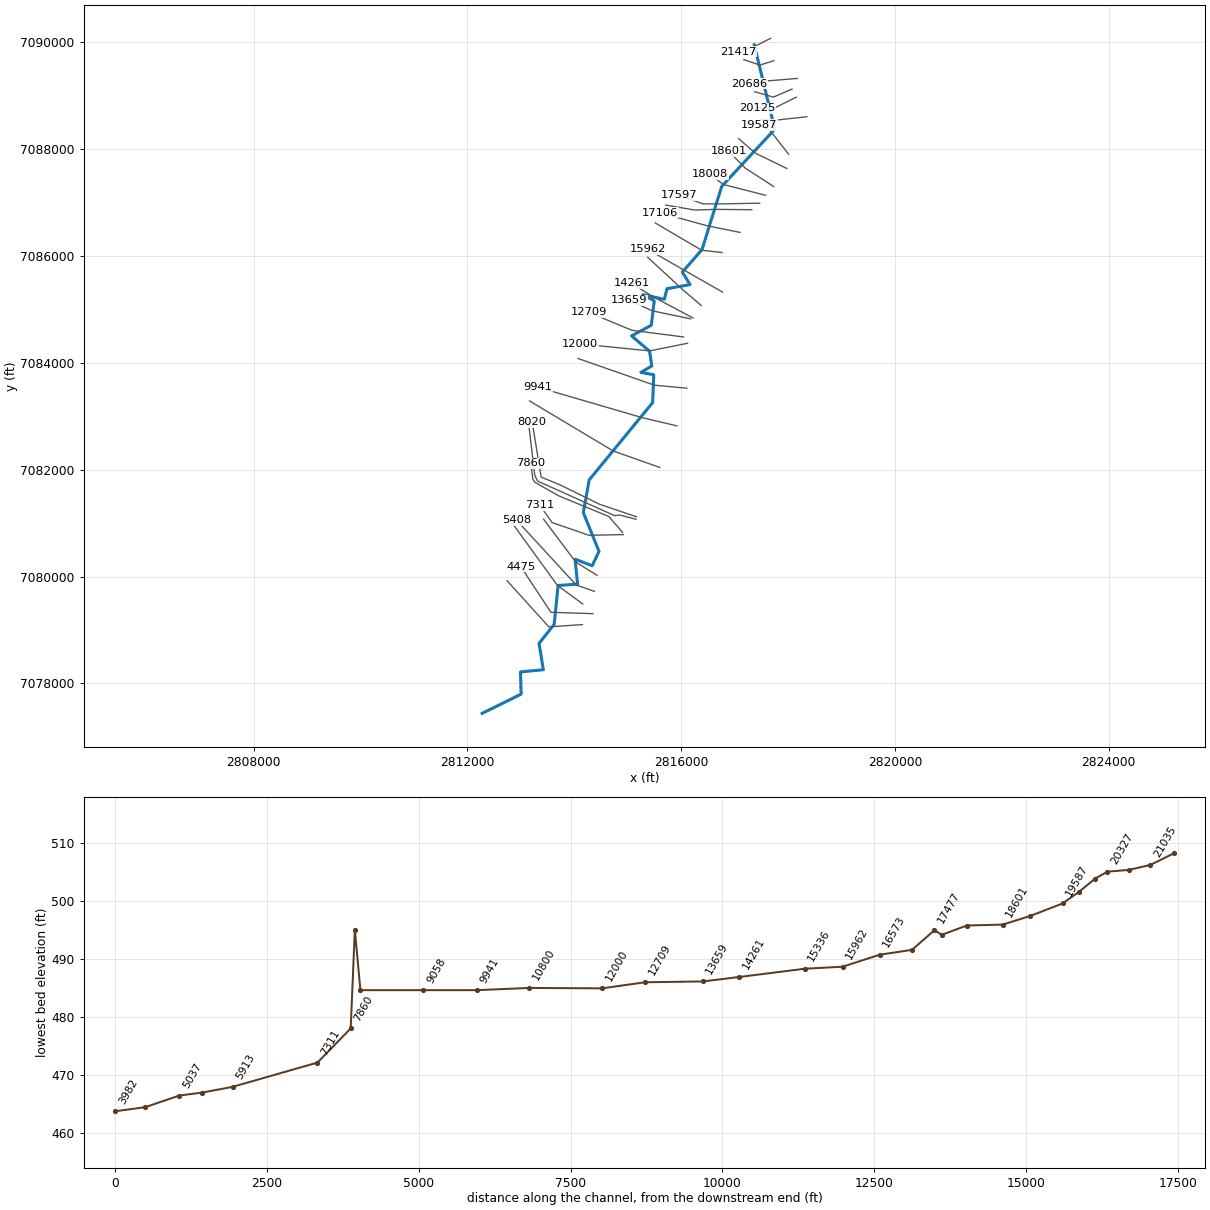
--- UNT 053 in LFCCL Watershed.prj (project) ---

Proj Title=UNT 053 in LFCCL Watershed Base Level Engineering
Current Plan=p01
Default Exp/Contr=0.3,0.1
English Units
Geom File=g01
Flow File=f01
Plan File=p01
Y Axis Title=Elevation
X Axis Title(PF)=Main Channel Distance
X Axis Title(XS)=Station
BEGIN DESCRIPTION:
UNT 053 in LFCCL Watershed
END DESCRIPTION:
DSS Export Rating Curves= 0
DSS Export Rating Curve Sorted= 0
DSS Export Volume Flow Curves= 0
DXF OffsetX= 0
DXF OffsetY= 0
DXF ScaleX= 1
DXF ScaleY= 10

--- UNT 053 in LFCCL Watershed.p01 (plan) ---

Plan Title=Multiple Run
Short Identifier=Multiple
Geom File=g01
Flow File=f01
Subcritical Flow
K Sum by GR= 0
Std Step Tol= 0.01
Critical Tol= 0.01
Num of Std Step Trials= 20
Max Error Tol= 0.3
Flow Tol Ratio= 0.001
Split Flow NTrial= 30
Split Flow Tol= 0.02
Split Flow Ratio= 0.02
Log Output Level= 0
Friction Slope Method= 1
Unsteady Friction Slope Method= 2
Unsteady Bridges Friction Slope Method= 1
Parabolic Critical Depth
Global Vel Dist=  1 , 1 , 1
Global Log Level= 0
CheckData=True
Encroach Param= -1, 0, 0, 0
BEGIN DESCRIPTION:
Multiple Run
END DESCRIPTION:

--- UNT 053 in LFCCL Watershed.f01 (steady flow) ---

Flow Title=Multiple
Program Version=5.07
Number of Profiles= 7
Profile Names=10-year,25-year,50-year,1pct_min,100-year,1pct_plu,500-year
River Rch & RM=UNT 053 in LFCCL,Reach-1         ,21417
     592     779     928     549    1095    2184    1518
River Rch & RM=UNT 053 in LFCCL,Reach-1         ,19052
     990    1343    1631     980    1956    3903    2810
River Rch & RM=UNT 053 in LFCCL,Reach-1         ,15962
    1063    1438    1742    1044    2084    4158    2976
River Rch & RM=UNT 053 in LFCCL,Reach-1         ,12709
    1701    2358    2906    1768    3528    7039    5195
Boundary for River Rch & Prof#=UNT 053 in LFCCL,Reach-1         , 1
Up Type= 0
Dn Type= 3
Dn Slope=0.005
Boundary for River Rch & Prof#=UNT 053 in LFCCL,Reach-1         , 2
Up Type= 0
Dn Type= 3
Dn Slope=0.005
Boundary for River Rch & Prof#=UNT 053 in LFCCL,Reach-1         , 3
Up Type= 0
Dn Type= 3
Dn Slope=0.005
Boundary for River Rch & Prof#=UNT 053 in LFCCL,Reach-1         , 4
Up Type= 0
Dn Type= 3
Dn Slope=0.005
Boundary for River Rch & Prof#=UNT 053 in LFCCL,Reach-1         , 5
Up Type= 0
Dn Type= 3
Dn Slope=0.005
Boundary for River Rch & Prof#=UNT 053 in LFCCL,Reach-1         , 6
Up Type= 0
Dn Type= 3
Dn Slope=0.005
Boundary for River Rch & Prof#=UNT 053 in LFCCL,Reach-1         , 7
Up Type= 0
Dn Type= 3
Dn Slope=0.005
DSS Import GetInterval= 0
DSS Import GetPeak= 0
DSS Import FillOption= 0

--- UNT 053 in LFCCL Watershed.g01 (geometry) ---

Geom Title=Existing Conditions

River Reach=UNT 053 in LFCCL,Reach-1
Reach XY= 30
      2817367.69      7089954.53      2817752.05      7088373.22
      2816758.73      7087303.56      2816390.61      7086122.39
      2816021.89      7085699.30      2816167.20      7085466.01
      2815735.21      7085388.90      2815684.80      7085190.21
      2815284.44      7085277.20      2815495.99      7085161.54
      2815440.63      7084704.84      2815071.91      7084506.14
      2815409.00      7084218.48      2815449.53      7083942.68
      2815245.89      7083823.07      2815487.09      7083778.58
      2815466.33      7083257.62      2814278.14      7081809.80
      2814169.02      7081197.76      2814461.98      7080472.83
      2814334.74      7080203.49      2814013.82      7080326.91
      2814061.93      7079858.95      2813697.29      7079834.85
      2813622.96      7079106.06      2813339.86      7078750.38
      2813421.15      7078257.68      2812992.68      7078216.47
      2813005.13      7077800.86      2812275.59      7077440.71

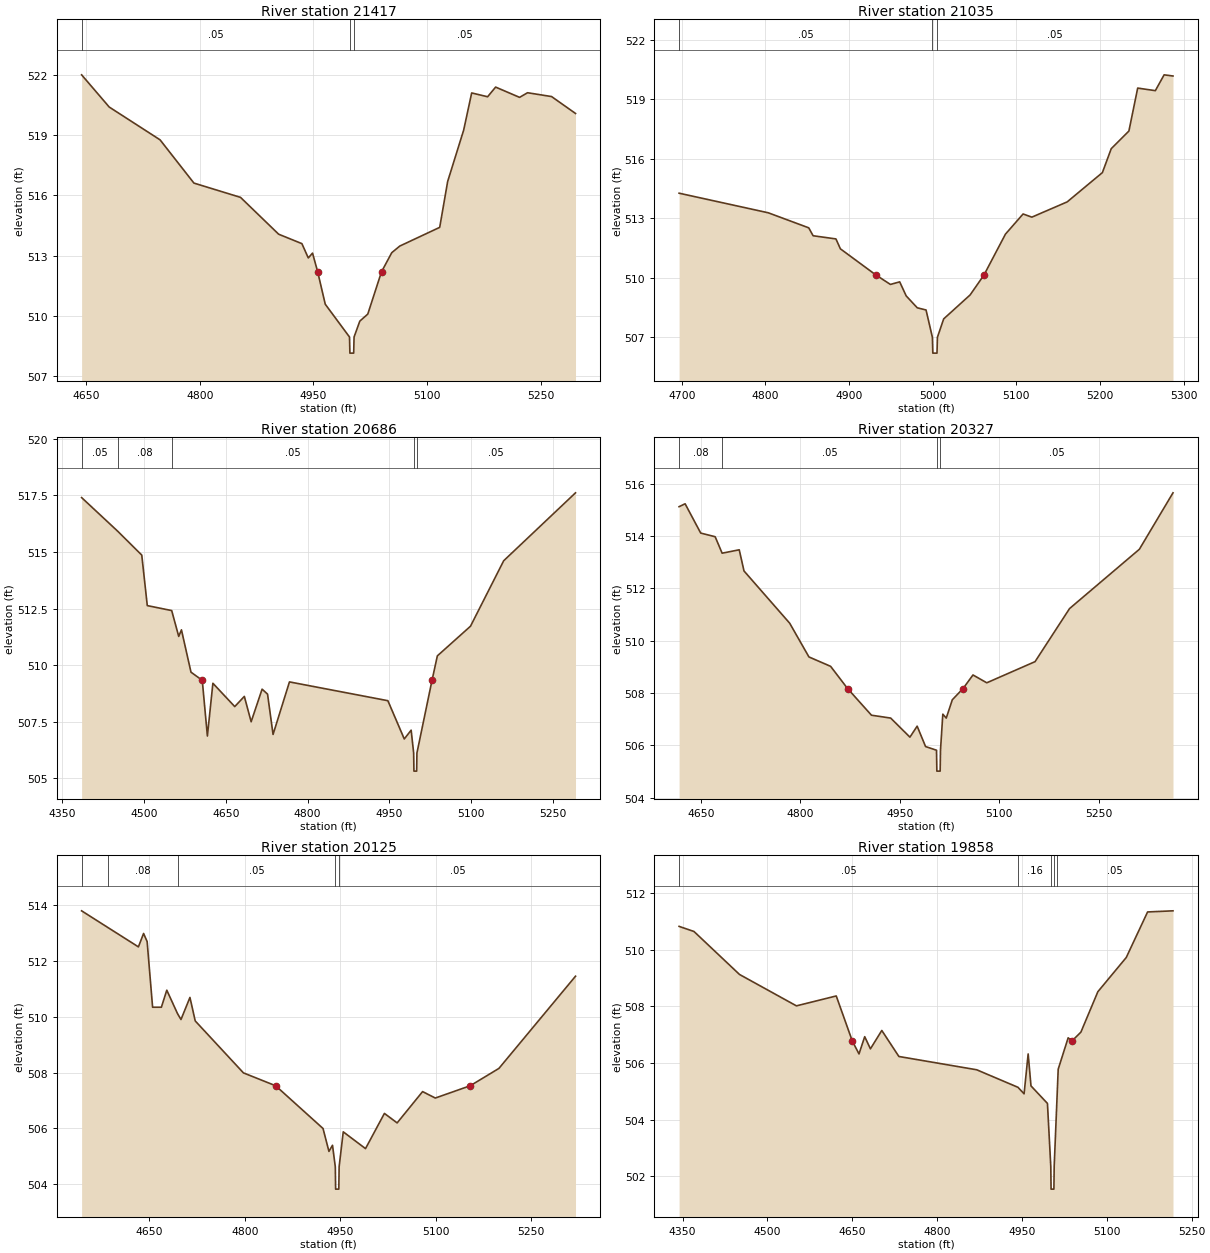
Type RM Length L Ch R = 1,21417,382,382,382
BEGIN DESCRIPTION:
UNT 053 in LFCCL Watershed 27.0
END DESCRIPTION:
XS GIS Cut Line= 3
      2817675.04      7090075.02      2817375.00      7089925.00
      2817074.99      7089825.00
#Sta/Elev= 30
  4644.1  521.99  4680.5  520.39  4747.6  518.76  4792.3  516.61  4853.8  515.90
  4904.1  514.07  4934.8  513.60  4943.2  512.89  4948.8  513.13  4955.6  512.20
  4965.6  510.59  4997.6  508.96  4998.1  508.16  5003.1  508.16  5003.6  508.96
  5011.2  509.75  5021.7  510.10  5039.8  512.20  5053.3  513.15  5063.9  513.48
  5116.6  514.41  5127.1  516.69  5148.2  519.24  5158.8  521.09  5179.8  520.90
  5190.4  521.38  5222.0  520.87  5232.5  521.10  5264.2  520.91  5295.8  520.07
#Mann=3,-1,0
  4644.1    0.05       0  4997.6    0.03       0  5003.6    0.05       0
Bank Sta=4955.6,5039.8
Exp/Cntr=0.3,0.1

Type RM Length L Ch R = 1,21035,349,349,349
BEGIN DESCRIPTION:
UNT 053 in LFCCL Watershed 26.0
END DESCRIPTION:
XS GIS Cut Line= 3
      2817736.76      7089656.43      2817475.00      7089575.00
      2817174.97      7089675.01
#Sta/Elev= 30
  4696.8  514.26  4803.4  513.27  4851.8  512.51  4857.0  512.11  4884.3  511.95
  4889.6  511.45  4932.0  510.13  4949.4  509.65  4960.5  509.78  4968.3  509.07
  4981.5  508.47  4992.0  508.36  4999.6  506.98  5000.1  506.18  5005.1  506.18
  5005.6  506.98  5013.1  507.91  5044.7  509.12  5061.3  510.13  5086.9  512.19
  5108.0  513.21  5118.5  513.05  5160.7  513.82  5202.8  515.30  5213.4  516.51
  5234.5  517.40  5245.0  519.57  5266.1  519.44  5276.6  520.24  5287.2  520.18
#Mann=3,-1,0
  4696.8    0.05       0  4999.6    0.03       0  5005.6    0.05       0
Bank Sta=4932,5061.3
Exp/Cntr=0.3,0.1

Type RM Length L Ch R = 1,20686,359,359,359
BEGIN DESCRIPTION:
UNT 053 in LFCCL Watershed 25.0
END DESCRIPTION:
XS GIS Cut Line= 3
      2818175.05      7089325.00      2817575.00      7089275.00
      2817274.97      7089224.99
#Sta/Elev= 30
  4385.4  517.40  4451.4  515.92  4495.8  514.86  4505.9  512.63  4550.7  512.41
  4563.6  511.27  4568.6  511.56  4586.1  509.69  4606.8  509.33  4616.2  506.87
  4626.3  509.20  4666.4  508.17  4684.0  508.62  4696.5  507.50  4716.6  508.94
  4726.6  508.72  4736.7  506.94  4766.8  509.26  4947.4  508.43  4977.5  506.74
  4990.1  507.13  4994.7  506.12  4995.2  505.32  5000.2  505.32  5000.7  506.12
  5028.4  509.33  5038.2  510.41  5099.0  511.72  5159.9  514.61  5291.7  517.61
#Mann=5,-1,0
  4385.4    0.05       0  4451.4    0.08       0  4550.7    0.05       0
  4994.7    0.03       0  5000.7    0.05       0
Bank Sta=4606.8,5028.4
Exp/Cntr=0.3,0.1

Type RM Length L Ch R = 1,20327,202,202,202
BEGIN DESCRIPTION:
UNT 053 in LFCCL Watershed 24.0
END DESCRIPTION:
XS GIS Cut Line= 3
      2818074.99      7089125.00      2817725.00      7088975.00
      2817374.99      7089075.00
#Sta/Elev= 30
  4617.4  515.13  4626.5  515.24  4650.0  514.12  4671.8  513.98  4682.3  513.35
  4708.1  513.48  4715.3  512.67  4784.2  510.67  4813.2  509.38  4845.9  509.02
  4871.5  508.17  4907.5  507.15  4936.5  507.04  4965.5  506.31  4976.4  506.73
  4989.1  505.95  5005.6  505.81  5006.1  505.01  5011.1  505.01  5011.6  505.81
  5015.1  507.19  5020.3  507.04  5029.4  507.74  5045.6  508.17  5060.6  508.69
  5081.4  508.39  5154.2  509.20  5206.2  511.23  5311.5  513.50  5362.2  515.66
#Mann=4,-1,0
  4617.4    0.08       0  4682.3    0.05       0  5005.6    0.03       0
  5011.6    0.05       0
Bank Sta=4871.5,5045.6
Exp/Cntr=0.3,0.1

Type RM Length L Ch R = 1,20125,267,267,267
BEGIN DESCRIPTION:
XS3344A
END DESCRIPTION:
XS GIS Cut Line= 3
      2818154.97      7088974.45      2817759.25      7088778.20
      2817424.70      7088768.55
#Sta/Elev= 30
  4543.6  513.79  4585.1  513.19  4632.9  512.50  4641.0  512.98  4646.6  512.69
  4655.2  510.34  4669.0  510.34  4677.5  510.95  4694.4  510.11  4699.8  509.90
  4713.9  510.69  4722.2  509.85  4798.0  507.99  4848.6  507.53  4923.1  506.00
  4932.4  505.18  4938.0  505.40  4942.4  504.63  4942.9  503.83  4947.9  503.83
  4948.4  504.63  4954.9  505.88  4989.9  505.28  5019.6  506.54  5039.6  506.20
  5079.6  507.32  5099.6  507.09  5154.5  507.53  5199.6  508.15  5320.0  511.45
#Mann=5,-1,0
  4543.6    0.05       0  4585.1    0.08       0  4694.4    0.05       0
  4942.4    0.03       0  4948.4    0.05       0
Bank Sta=4848.6,5154.5
Exp/Cntr=0.3,0.1

Type RM Length L Ch R = 1,19858,271,271,271
BEGIN DESCRIPTION:
XS3345A
END DESCRIPTION:
XS GIS Cut Line= 3
      2818351.12      7088607.70      2817707.78      7088536.93
      2817482.58      7088553.01
#Sta/Elev= 30
  4343.9  510.83  4370.2  510.65  4450.7  509.13  4551.3  508.02  4621.7  508.37
  4650.0  506.78  4661.9  506.32  4672.0  506.93  4682.1  506.50  4702.2  507.15
  4732.4  506.23  4869.9  505.76  4942.9  505.14  4953.7  504.91  4960.9  506.32
  4965.9  505.19  4995.0  504.57  5000.9  502.34  5001.4  501.54  5006.4  501.54
  5006.9  502.34  5012.4  505.00  5014.0  505.78  5031.6  506.89  5038.4  506.78
  5054.1  507.09  5084.1  508.52  5134.3  509.73  5172.0  511.34  5216.9  511.38
#Mann=5,-1,0
  4343.9    0.05       0  4942.9    0.16       0  5000.9    0.07       0
  5006.9    0.16       0  5012.4    0.05       0
Bank Sta=4650,5038.4
Exp/Cntr=0.3,0.1

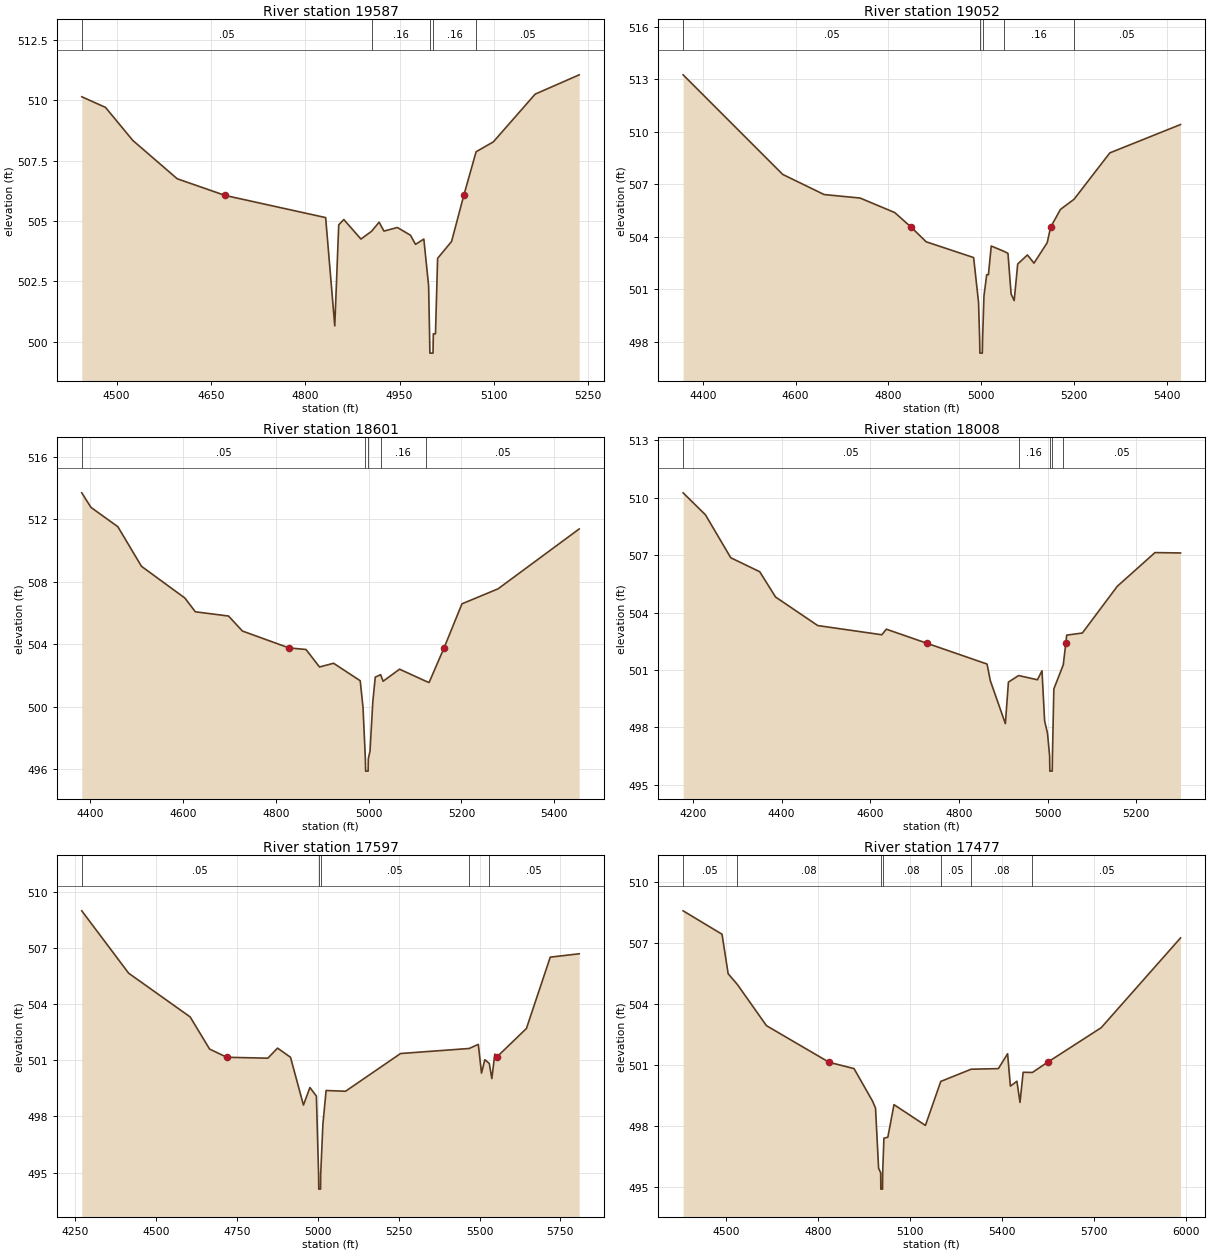
Type RM Length L Ch R = 1,19587,535,535,535
BEGIN DESCRIPTION:
XS3346A
END DESCRIPTION:
XS GIS Cut Line= 3
      2818010.17      7087906.41      2817665.96      7088347.13
      2817460.12      7088453.27
#Sta/Elev= 30
  4444.8  510.15  4482.5  509.71  4525.9  508.34  4596.5  506.75  4672.5  506.06
  4832.5  505.14  4847.0  500.65  4853.3  504.84  4861.4  505.06  4888.6  504.25
  4905.4  504.57  4917.5  504.95  4925.2  504.58  4946.5  504.73  4967.3  504.41
  4975.4  504.03  4988.6  504.25  4996.2  502.31  4997.7  500.32  4998.2  499.52
  5003.2  499.52  5003.7  500.32  5007.1  500.32  5010.5  503.45  5032.7  504.15
  5052.1  506.06  5071.7  507.87  5099.1  508.28  5165.6  510.26  5235.6  511.06
#Mann=5,-1,0
  4444.8    0.05       0  4905.4    0.16       0  4997.7    0.07       0
  5003.7    0.16       0  5071.7    0.05       0
Bank Sta=4672.5,5052.1
Exp/Cntr=0.3,0.1

Type RM Length L Ch R = 1,19052,451,451,451
BEGIN DESCRIPTION:
XS3347A
END DESCRIPTION:
XS GIS Cut Line= 3
      2817977.97      7087639.42      2817389.31      7087925.71
      2817074.06      7088199.14
#Sta/Elev= 30
  4357.5  513.26  4572.1  507.57  4661.3  506.42  4738.9  506.22  4813.6  505.39
  4849.1  504.55  4881.3  503.72  4983.5  502.82  4994.1  500.27  4996.5  498.16
  4997.0  497.36  5002.3  497.36  5002.8  498.16  5005.8  500.63  5011.7  501.84
  5015.4  501.84  5021.5  503.48  5049.4  503.17  5057.5  503.06  5064.3  500.74
  5070.9  500.36  5078.5  502.45  5099.4  502.97  5113.6  502.50  5142.1  503.67
  5149.3  504.55  5170.6  505.57  5199.9  506.15  5277.0  508.80  5429.4  510.42
#Mann=5,-1,0
  4357.5    0.05       0  4996.5    0.03       0  5002.8    0.05       0
  5049.4    0.16       0  5199.9    0.05       0
Bank Sta=4849.1,5149.3
Exp/Cntr=0.3,0.1

Type RM Length L Ch R = 1,18601,593,593,593
BEGIN DESCRIPTION:
XS3348A
END DESCRIPTION:
XS GIS Cut Line= 3
      2817730.30      7087301.63      2817199.51      7087645.84
      2816890.65      7087957.91
#Sta/Elev= 30
  4381.9  513.68  4401.7  512.75  4459.7  511.51  4510.5  508.98  4604.1  506.95
  4626.6  506.07  4698.1  505.80  4728.0  504.84  4828.5  503.76  4865.0  503.66
  4894.1  502.54  4924.4  502.78  4981.8  501.66  4987.8  499.96  4992.9  496.68
  4993.4  495.88  4998.8  495.88  4999.3  496.68  5002.9  497.16  5008.9  500.31
  5014.2  501.89  5025.7  502.05  5031.2  501.63  5066.6  502.40  5122.5  501.64
  5130.2  501.55  5162.4  503.76  5201.0  506.58  5278.8  507.54  5453.6  511.37
#Mann=5,-1,0
  4381.9    0.05       0  4992.9    0.03       0  4999.3    0.05       0
  5025.7    0.16       0  5122.5    0.05       0
Bank Sta=4828.5,5162.4
Exp/Cntr=0.3,0.1

Type RM Length L Ch R = 1,18008,411,411,411
BEGIN DESCRIPTION:
XS3349A
END DESCRIPTION:
XS GIS Cut Line= 3
      2817579.12      7087137.56      2816787.74      7087340.23
      2816546.48      7087526.80
#Sta/Elev= 30
  4178.1  510.25  4228.5  509.10  4285.6  506.86  4350.9  506.13  4386.6  504.81
  4481.7  503.32  4626.2  502.84  4636.5  503.13  4728.7  502.39  4863.6  501.31
  4871.0  500.44  4904.9  498.20  4911.8  500.37  4934.8  500.71  4977.2  500.49
  4987.5  500.96  4993.4  498.35  4999.9  497.70  5004.7  496.52  5005.2  495.72
  5010.6  495.72  5011.1  496.52  5014.2  500.01  5035.5  501.27  5041.2  502.39
  5043.2  502.82  5078.5  502.93  5157.3  505.37  5242.4  507.13  5300.0  507.11
#Mann=5,-1,0
  4178.1    0.05       0  4934.8    0.16       0  5004.7    0.07       0
  5011.1    0.16       0  5035.5    0.05       0
Bank Sta=4728.7,5041.2
Exp/Cntr=0.3,0.1

Type RM Length L Ch R = 1,17597,120,120,120
BEGIN DESCRIPTION:
XS3350A
END DESCRIPTION:
XS GIS Cut Line= 4
      2817469.73      7086989.59      2816758.79      7086976.72
      2816407.89      7086976.72      2815960.82      7087136.41
#Sta/Elev= 30
  4271.3  509.01  4416.1  505.67  4606.1  503.33  4666.1  501.61  4719.3  501.17
  4846.1  501.12  4876.1  501.66  4916.1  501.17  4956.1  498.61  4976.1  499.55
  4996.1  499.09  5002.9  494.91  5003.4  494.11  5008.9  494.11  5009.4  494.91
  5016.1  497.57  5026.1  499.39  5086.1  499.35  5256.1  501.37  5468.1  501.64
  5496.3  501.86  5506.2  500.32  5516.5  501.04  5530.2  500.84  5538.1  500.03
  5547.3  501.34  5552.7  501.17  5644.9  502.71  5718.6  506.53  5808.0  506.71
#Mann=5,-1,0
  4271.3    0.05       0  5002.9    0.03       0  5009.4    0.05       0
  5468.1    0.08       0  5530.2    0.05       0
Bank Sta=4719.3,5552.7
Exp/Cntr=0.3,0.1

Type RM Length L Ch R = 1,17477,371,371,371
BEGIN DESCRIPTION:
XS3351A
END DESCRIPTION:
XS GIS Cut Line= 4
      2817321.72      7086867.34      2816665.50      7086873.78
      2816251.93      7086861.79      2815709.51      7086954.04
#Sta/Elev= 30
  4361.0  508.58  4487.7  507.43  4507.7  505.49  4537.8  504.96  4632.4  502.94
  4836.5  501.14  4917.7  500.83  4977.7  499.24  4987.7  498.89  4997.7  495.94
  5004.5  495.71  5005.0  494.91  5010.5  494.91  5011.0  495.71  5015.0  497.41
  5027.8  497.46  5047.8  499.06  5150.2  498.04  5200.2  500.20  5299.2  500.80
  5387.9  500.83  5417.9  501.56  5427.0  499.97  5448.2  500.21  5458.3  499.17
  5468.5  500.65  5498.6  500.64  5547.9  501.14  5722.8  502.84  5981.2  507.25
#Mann=7,-1,0
  4361.0    0.05       0  4537.8    0.08       0  5004.5    0.07       0
  5011.0    0.08       0  5200.2    0.05       0  5299.2    0.08       0
  5498.6    0.05       0
Bank Sta=4836.5,5547.9
Exp/Cntr=0.3,0.1

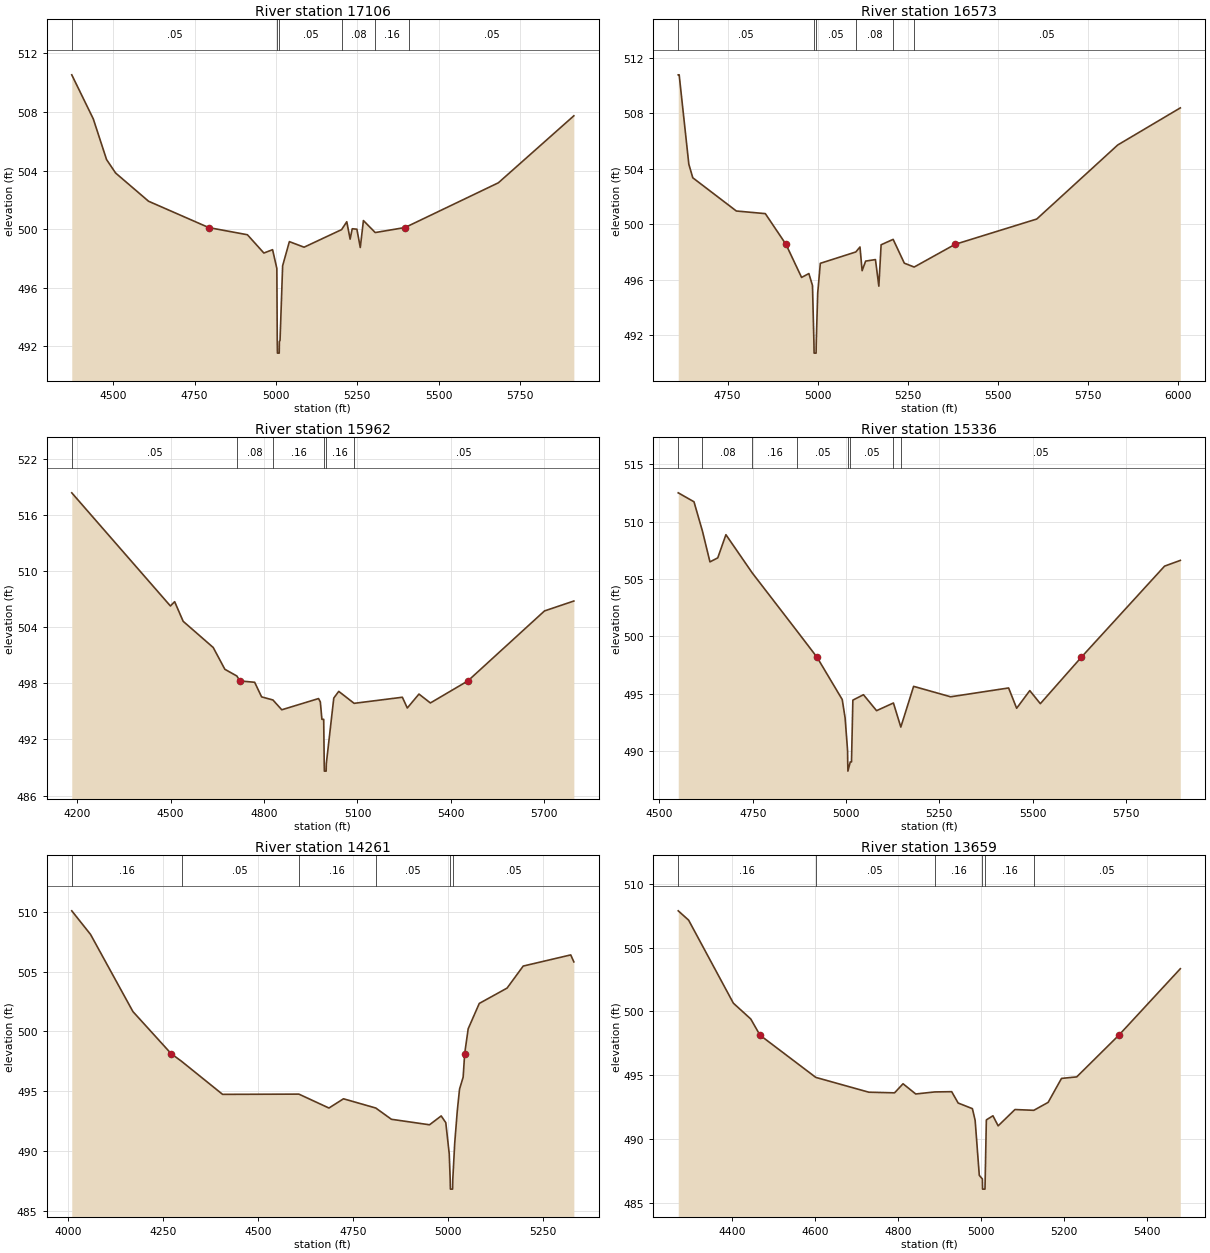
Type RM Length L Ch R = 1,17106,533,533,533
BEGIN DESCRIPTION:
XS3352A
END DESCRIPTION:
XS GIS Cut Line= 3
      2817099.75      7086442.71      2816482.13      7086568.17
      2815602.21      7086810.44
#Sta/Elev= 30
  4372.8  510.54  4438.9  507.53  4479.7  504.75  4507.5  503.83  4608.8  501.90
  4793.8  500.10  4912.6  499.61  4963.2  498.36  4989.9  498.59  5003.0  497.31
  5004.3  492.32  5004.8  491.52  5010.3  491.52  5010.8  492.32  5012.8  492.38
  5020.8  497.49  5041.5  499.14  5086.7  498.76  5202.0  499.96  5217.9  500.50
  5228.2  499.31  5234.7  500.02  5249.0  499.99  5259.4  498.74  5269.1  500.58
  5305.4  499.76  5395.7  500.10  5408.8  500.23  5683.7  503.16  5915.7  507.74
#Mann=6,-1,0
  4372.8    0.05       0  5004.3    0.03       0  5010.8    0.05       0
  5202.0    0.08       0  5305.4    0.16       0  5408.8    0.05       0
Bank Sta=4793.8,5395.7
Exp/Cntr=0.3,0.1

Type RM Length L Ch R = 1,16573,611,611,611
BEGIN DESCRIPTION:
XS3353A
END DESCRIPTION:
XS GIS Cut Line= 3
      2816765.18      7086066.33      2816385.62      7086108.15
      2815513.78      7086619.92
#Sta/Elev= 30
  4613.0  510.79  4615.6  510.79  4642.4  504.33  4653.4  503.35  4774.2  500.95
  4854.6  500.76  4911.9  498.54  4955.2  496.15  4975.4  496.43  4985.4  495.57
  4989.4  491.48  4989.9  490.68  4995.4  490.68  4995.9  491.48  4999.9  495.02
  5007.2  497.17  5105.6  497.99  5117.2  498.35  5123.1  496.64  5132.9  497.33
  5160.1  497.44  5169.5  495.52  5175.8  498.51  5209.2  498.90  5240.2  497.18
  5267.5  496.90  5380.9  498.54  5607.6  500.37  5832.2  505.72  6005.8  508.40
#Mann=6,-1,0
  4613.0    0.05       0  4989.4    0.03       0  4995.9    0.05       0
  5105.6    0.08       0  5209.2    0.16       0  5267.5    0.05       0
Bank Sta=4911.9,5380.9
Exp/Cntr=0.3,0.1

Type RM Length L Ch R = 1,15962,626,626,626
BEGIN DESCRIPTION:
UNT 053 in LFCCL Watershed 16.0
END DESCRIPTION:
XS GIS Cut Line= 3
      2816775.03      7085324.98      2816075.00      7085725.00
      2815374.99      7086125.01
#Sta/Elev= 30
  4182.5  518.37  4499.3  506.27  4512.9  506.73  4540.3  504.63  4636.8  501.83
  4674.2  499.50  4712.8  498.78  4722.2  498.26  4769.9  498.11  4792.2  496.55
  4828.5  496.22  4857.0  495.17  4975.1  496.37  4980.8  496.01  4985.9  494.15
  4991.6  494.15  4993.3  489.41  4993.8  488.61  4999.5  488.61  5000.0  489.41
  5024.0  496.42  5039.9  497.14  5089.3  495.86  5244.3  496.51  5260.1  495.36
  5297.6  496.85  5334.3  495.90  5454.8  498.26  5700.7  505.74  5795.0  506.80
#Mann=6,-1,0
  4182.5    0.05       0  4712.8    0.08       0  4828.5    0.16       0
  4993.3    0.07       0  5000.0    0.16       0  5089.3    0.05       0
Bank Sta=4722.2,5454.8
Exp/Cntr=0.3,0.1

Type RM Length L Ch R = 1,15336,1075,1075,1075
BEGIN DESCRIPTION:
UNT 053 in LFCCL Watershed 15.0
END DESCRIPTION:
XS GIS Cut Line= 3
      2816374.97      7085075.02      2816025.00      7085375.00
      2815375.02      7085974.98
#Sta/Elev= 30
  4550.4  512.52  4592.6  511.74  4615.4  509.17  4635.4  506.50  4656.3  506.85
  4678.2  508.87  4748.5  505.55  4869.2  500.45  4922.3  498.19  4989.9  494.50
  4997.6  492.90  5004.2  490.06  5004.6  489.06  5005.1  488.26  5011.4  489.06
  5014.7  489.06  5018.4  494.45  5046.8  494.92  5081.9  493.53  5127.1  494.20
  5146.9  492.10  5181.2  495.65  5280.4  494.74  5435.8  495.51  5457.3  493.74
  5492.5  495.28  5520.8  494.14  5630.7  498.19  5853.7  506.13  5895.9  506.63
#Mann=8,-1,0
  4550.4    0.05       0  4615.4    0.08       0  4748.5    0.16       0
  4869.2    0.05       0  5004.6    0.03       0  5011.4    0.05       0
  5127.1    0.16       0  5146.9    0.05       0
Bank Sta=4922.3,5630.7
Exp/Cntr=0.3,0.1

Type RM Length L Ch R = 1,14261,602,602,602
BEGIN DESCRIPTION:
UNT 053 in LFCCL Watershed 14.0
END DESCRIPTION:
XS GIS Cut Line= 3
      2816218.59      7084842.44      2815468.58      7085242.45
      2815069.27      7085492.02
#Sta/Elev= 30
  4010.4  510.07  4059.8  508.10  4171.3  501.66  4271.8  498.15  4299.2  497.51
  4407.2  494.75  4607.9  494.77  4687.0  493.61  4725.3  494.38  4810.2  493.61
  4851.3  492.67  4951.6  492.21  4982.3  492.95  4994.4  492.39  5003.5  489.78
  5006.0  487.64  5006.5  486.84  5012.3  486.84  5012.8  487.64  5017.9  490.68
  5024.7  493.39  5030.6  495.19  5040.1  496.19  5044.1  498.15  5053.3  500.22
  5082.5  502.34  5155.6  503.62  5198.1  505.46  5323.1  506.39  5331.3  505.81
#Mann=6,-1,0
  4010.4    0.16       0  4299.2    0.05       0  4607.9    0.16       0
  4810.2    0.05       0  5006.0    0.03       0  5012.8    0.05       0
Bank Sta=4271.8,5044.1
Exp/Cntr=0.3,0.1

Type RM Length L Ch R = 1,13659,950,950,950
BEGIN DESCRIPTION:
UNT 053 in LFCCL Watershed 13.0
END DESCRIPTION:
XS GIS Cut Line= 3
      2816174.99      7084825.00      2815460.40      7084974.71
      2815024.96      7085175.02
#Sta/Elev= 30
  4269.9  507.89  4294.9  507.16  4402.7  500.65  4444.6  499.41  4466.9  498.14
  4601.3  494.83  4728.9  493.67  4791.0  493.62  4811.4  494.33  4842.0  493.53
  4887.6  493.69  4928.6  493.71  4944.2  492.82  4978.5  492.38  4985.1  491.46
  4995.1  487.15  5002.5  486.87  5003.0  486.07  5008.8  486.07  5009.3  486.87
  5012.1  491.50  5028.0  491.82  5040.5  491.03  5081.0  492.31  5126.4  492.25
  5160.9  492.87  5193.1  494.75  5229.8  494.87  5331.3  498.14  5479.3  503.35
#Mann=6,-1,0
  4269.9    0.16       0  4601.3    0.05       0  4887.6    0.16       0
  5002.5    0.07       0  5009.3    0.16       0  5126.4    0.05       0
Bank Sta=4466.9,5331.3
Exp/Cntr=0.3,0.1

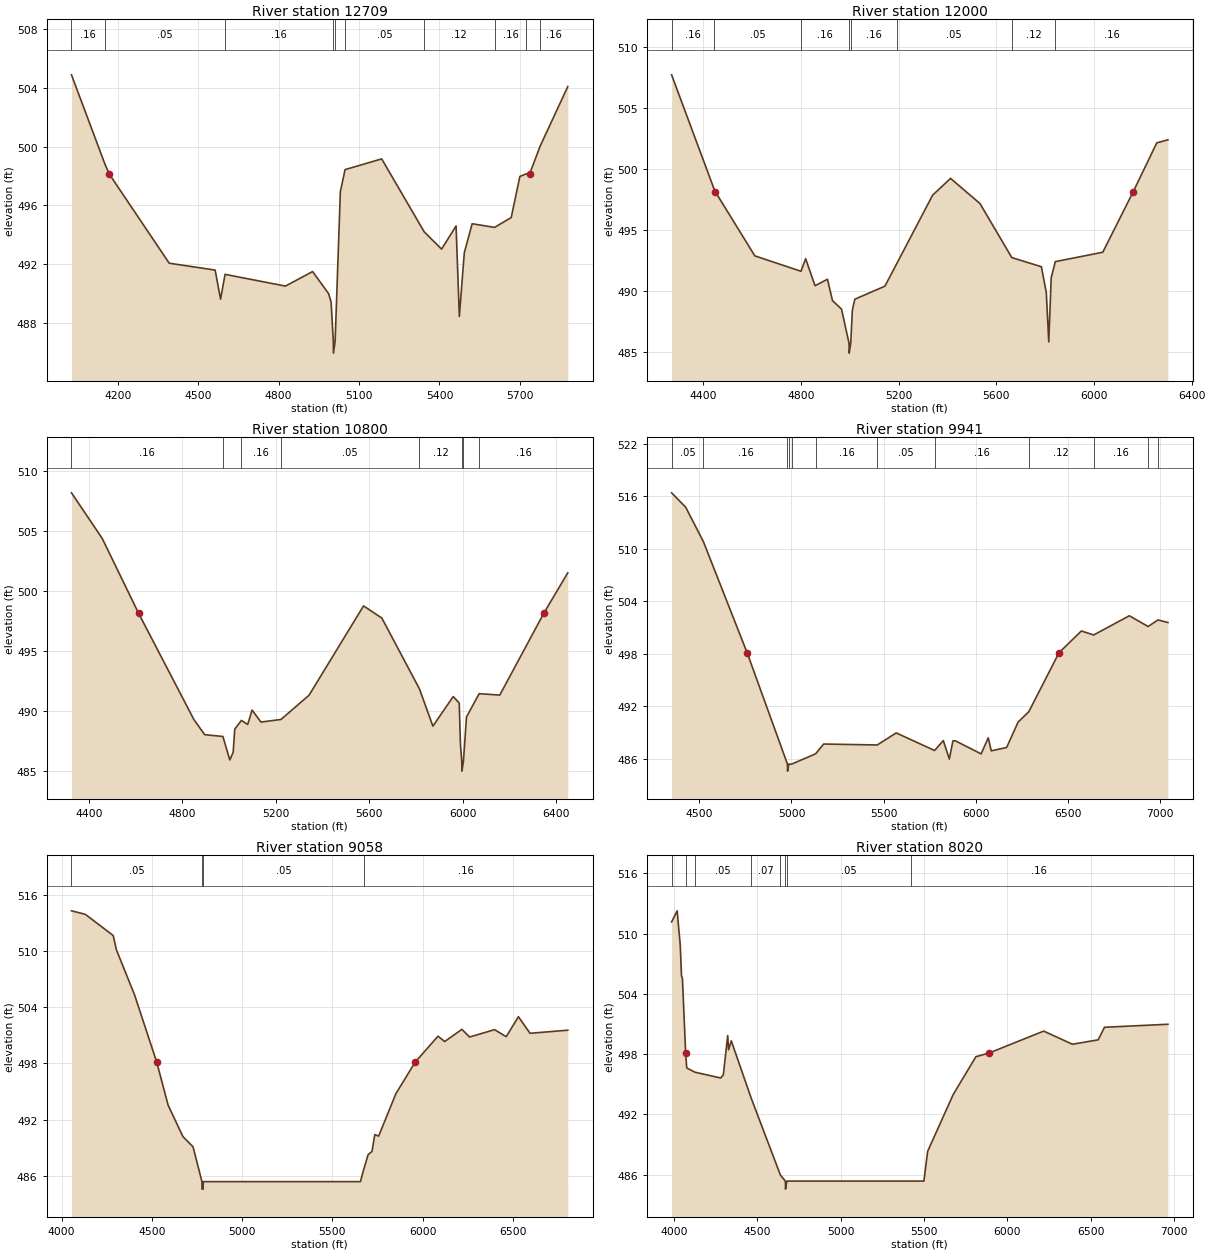
Type RM Length L Ch R = 1,12709,709,709,709
BEGIN DESCRIPTION:
double XS3354A
END DESCRIPTION:
XS GIS Cut Line= 3
      2816046.60      7084485.54      2815081.79      7084609.94
      2814269.97      7084946.44
#Sta/Elev= 30
  4027.2  504.90  4152.3  498.80  4168.8  498.12  4391.8  492.06  4563.2  491.59
  4583.4  489.61  4600.2  491.30  4825.4  490.50  4926.8  491.49  4986.7  489.98
  4995.9  489.40  5004.0  486.73  5004.5  485.93  5010.8  486.73  5030.3  496.94
  5048.0  498.44  5184.5  499.17  5343.0  494.20  5407.9  493.02  5462.0  494.60
  5474.2  488.43  5492.7  492.77  5522.0  494.75  5605.6  494.50  5667.7  495.17
  5700.0  497.97  5723.6  498.15  5736.0  498.12  5775.2  500.02  5878.8  504.10
#Mann=10,-1,0
  4027.2    0.16       0  4152.3    0.05       0  4600.2    0.16       0
  5004.0    0.07       0  5010.8    0.16       0  5048.0    0.05       0
  5343.0    0.12       0  5605.6    0.16       0  5723.6    0.12       0
  5775.2    0.16       0
Bank Sta=4168.8,5736
Exp/Cntr=0.3,0.1

Type RM Length L Ch R = 1,12000,1200,1200,1200
BEGIN DESCRIPTION:
double XS3355A
END DESCRIPTION:
XS GIS Cut Line= 3
      2816120.41      7084368.35      2815412.94      7084225.12
      2814109.64      7084356.16
#Sta/Elev= 30
  4271.1  507.75  4445.4  498.34  4450.6  498.12  4611.9  492.87  4800.6  491.61
  4819.8  492.64  4858.2  490.42  4909.2  490.95  4929.6  489.20  4966.8  488.49
  4997.5  485.68  4998.0  484.88  5004.3  485.68  5011.0  488.40  5021.0  489.31
  5144.1  490.38  5192.2  492.21  5339.6  497.86  5413.0  499.24  5533.6  497.17
  5663.7  492.73  5784.8  491.98  5804.9  489.87  5815.0  485.80  5825.0  491.08
  5841.9  492.40  6036.1  493.17  6160.2  498.12  6257.2  502.16  6302.8  502.41
#Mann=8,-1,0
  4271.1    0.16       0  4445.4    0.05       0  4800.6    0.16       0
  4997.5    0.07       0  5004.3    0.16       0  5192.2    0.05       0
  5663.7    0.12       0  5841.9    0.16       0
Bank Sta=4450.6,6160.2
Exp/Cntr=0.3,0.1

Type RM Length L Ch R = 1,10800,859,859,859
BEGIN DESCRIPTION:
double XS3356A
END DESCRIPTION:
XS GIS Cut Line= 3
      2816105.84      7083527.20      2815498.18      7083583.63
      2814070.27      7084082.75
#Sta/Elev= 30
  4325.8  508.16  4457.2  504.36  4613.0  498.11  4848.9  489.27  4895.5  487.99
  4973.4  487.84  5003.0  485.88  5017.4  486.52  5024.2  488.45  5052.6  489.18
  5079.5  488.84  5098.3  490.04  5136.3  489.04  5221.9  489.26  5342.0  491.28
  5575.0  498.73  5653.5  497.71  5814.2  491.81  5871.7  488.70  5958.6  491.17
  5984.3  490.63  5989.6  487.14  5995.3  485.75  5995.8  484.95  6002.2  485.75
  6015.4  489.47  6069.7  491.41  6157.7  491.29  6345.9  498.11  6448.7  501.49
#Mann=8,-1,0
  4325.8    0.16       0  4973.4    0.12       0  5052.6    0.16       0
  5221.9    0.05       0  5814.2    0.12       0  5995.3    0.07       0
  6002.2    0.12       0  6069.7    0.16       0
Bank Sta=4613,6345.9
Exp/Cntr=0.3,0.1

Type RM Length L Ch R = 1,9941,883,883,883
BEGIN DESCRIPTION:
double XS3357A
END DESCRIPTION:
XS GIS Cut Line= 3
      2815920.94      7082821.47      2815275.09      7082974.25
      2813323.65      7083543.71
#Sta/Elev= 30
  4348.7  516.40  4425.4  514.75  4521.6  510.81  4759.0  498.11  4978.2  485.37
  4978.7  484.57  4985.1  485.37  5000.8  485.37  5131.2  486.55  5174.8  487.67
  5465.8  487.56  5569.1  488.94  5777.4  486.93  5825.0  488.06  5857.7  485.95
  5877.1  488.04  5891.2  488.03  6030.3  486.54  6069.0  488.38  6085.4  486.89
  6168.8  487.27  6231.3  490.18  6289.2  491.36  6453.4  498.11  6575.0  500.60
  6641.8  500.14  6835.5  502.34  6937.6  501.11  6990.9  501.86  7045.2  501.57
#Mann=12,-1,0
  4348.7    0.05       0  4521.6    0.16       0  4978.2    0.07       0
  4985.1    0.16       0  5000.8    0.05       0  5131.2    0.16       0
  5465.8    0.05       0  5777.4    0.16       0  6289.2    0.12       0
  6641.8    0.16       0  6937.6    0.05       0  6990.9    0.16       0
Bank Sta=4759,6453.4
Exp/Cntr=0.3,0.1

Type RM Length L Ch R = 1,9058,1038,1038,1038
BEGIN DESCRIPTION:
double XS3359A
END DESCRIPTION:
XS GIS Cut Line= 3
      2815599.73      7082043.70      2814729.95      7082350.99
      2813162.24      7083288.49
#Sta/Elev= 30
  4054.6  514.27  4131.0  513.90  4285.6  511.64  4303.5  510.11  4404.0  505.30
  4527.0  498.11  4589.9  493.53  4671.7  490.18  4727.8  489.09  4777.3  485.37
  4777.8  484.57  4783.8  484.57  4784.3  485.37  5654.9  485.37  5672.3  486.60
  5697.7  488.25  5719.1  488.59  5734.7  490.39  5756.1  490.23  5851.4  494.75
  5957.9  498.11  6084.8  500.89  6121.8  500.32  6217.1  501.62  6259.9  500.80
  6398.0  501.59  6462.6  500.84  6530.3  502.97  6594.5  501.20  6803.7  501.53
#Mann=4,-1,0
  4054.6    0.05       0  4777.3   0.033       0  4784.3    0.05       0
  5672.3    0.16       0
Bank Sta=4527,5957.9
Exp/Cntr=0.3,0.1

Type RM Length L Ch R = 1,8020,92,92,92
BEGIN DESCRIPTION:
XS3358A
END DESCRIPTION:
XS GIS Cut Line= 5
      2815163.98      7081120.09      2814469.53      7081356.20
      2813733.42      7081717.31      2813379.26      7081863.14
      2813212.66      7082890.50
#Sta/Elev= 30
  3985.7  511.16  4019.0  512.27  4037.4  508.89  4045.1  505.77  4050.4  505.61
  4070.0  498.11  4070.1  498.09  4076.5  496.63  4125.6  496.21  4280.4  495.63
  4296.1  495.96  4322.2  499.86  4327.5  498.44  4343.7  499.33  4463.3  493.62
  4638.4  485.97  4668.1  485.37  4669.0  484.57  4677.2  485.37  5419.7  485.37
  5499.1  485.37  5521.6  488.33  5675.0  493.99  5811.0  497.75  5889.1  498.11
  6217.8  500.30  6390.0  498.99  6544.6  499.43  6582.5  500.68  6962.9  500.98
#Mann=8,-1,0
  3985.7    0.05       0  4070.1    0.08       0  4125.6    0.05       0
  4463.3    0.07       0  4638.4    0.05       0  4668.1   0.033       0
  4677.2    0.05       0  5419.7    0.16       0
Bank Sta=4070,5889.1
Exp/Cntr=0.3,0.1

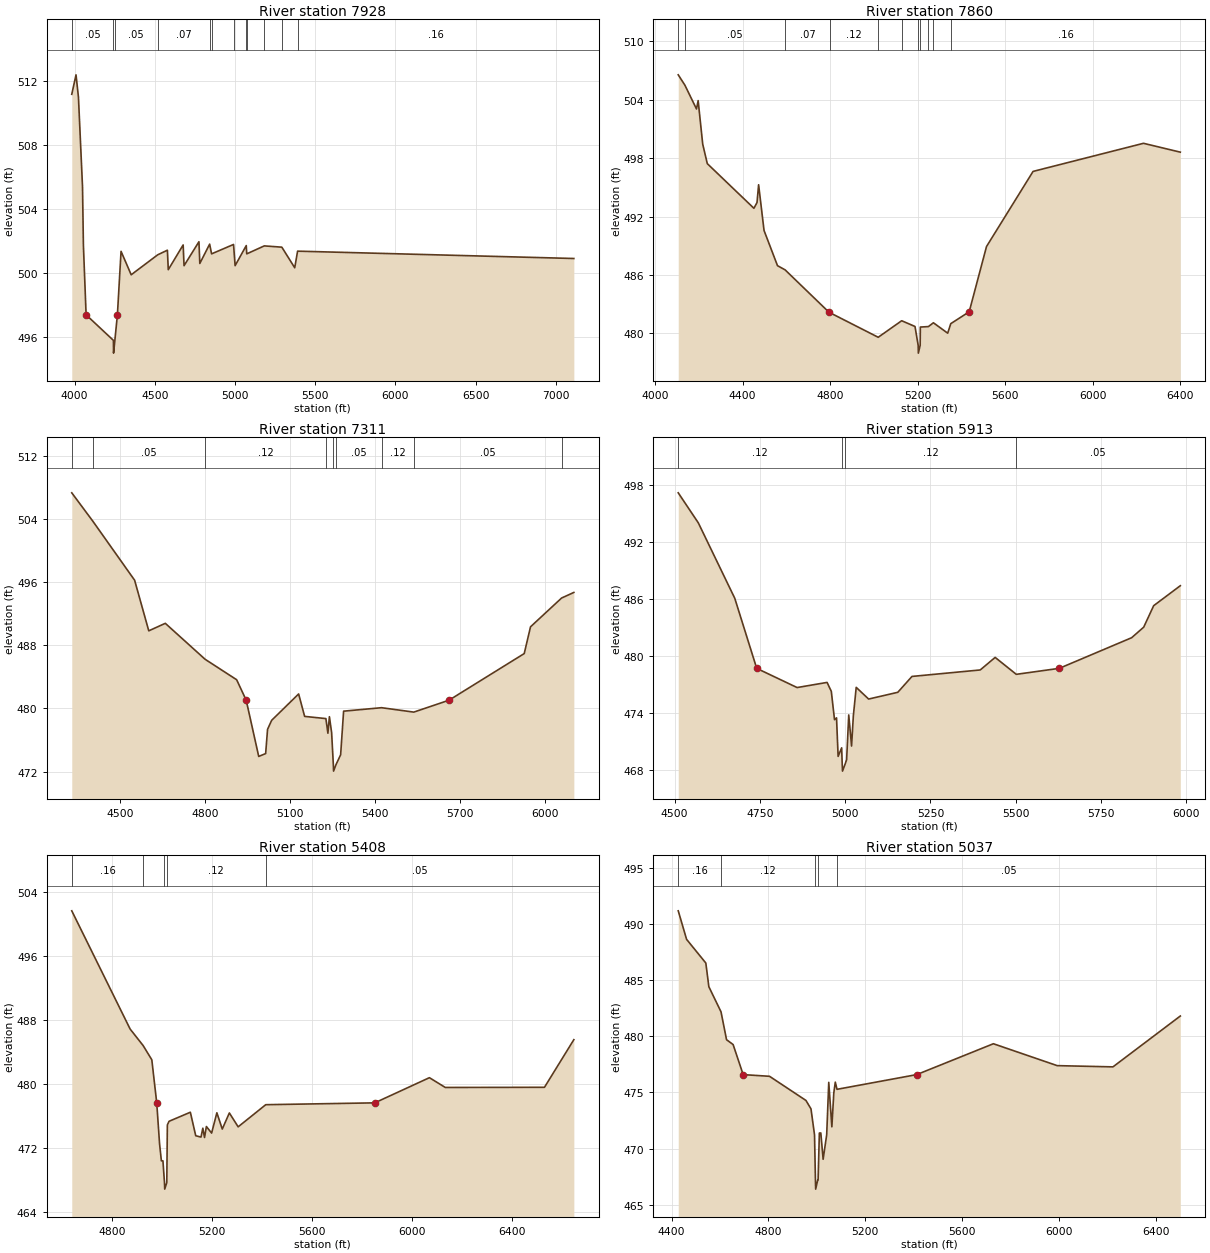
Type RM Length L Ch R = 1,7928,68,68,68
BEGIN DESCRIPTION:
XS3360A
END DESCRIPTION:
XS GIS Cut Line= 6
      2815155.26      7081073.22      2814855.82      7081151.34
      2814751.65      7081142.66      2813310.68      7081789.36
      2813258.60      7081902.20      2813141.41      7082904.81
#Sta/Elev= 30
  3982.3  511.18  4008.8  512.40  4023.9  511.01  4049.3  505.39  4054.9  501.70
  4071.7  497.36  4241.9  495.76  4242.8  494.96  4251.0  495.76  4266.8  497.36
  4289.6  501.34  4352.8  499.87  4517.9  501.12  4578.5  501.41  4584.0  500.19
  4676.8  501.74  4682.3  500.44  4775.2  501.94  4780.7  500.58  4841.9  501.79
  4854.0  501.18  4990.9  501.77  5000.7  500.44  5070.2  501.70  5073.2  501.18
  5182.6  501.68  5292.0  501.60  5372.4  500.31  5390.3  501.35  7112.6  500.89
#Mann=12,-1,0
  3982.3    0.05       0  4241.9    0.07       0  4251.0    0.05       0
  4517.9    0.07       0  4841.9    0.05       0  4854.0    0.12       0
  4990.9    0.07       0  5070.2    0.05       0  5073.2    0.12       0
  5182.6    0.07       0  5292.0    0.12       0  5390.3    0.16       0
Bank Sta=4071.7,4266.8
Exp/Cntr=0.3,0.1

Type RM Length L Ch R = 1,7860,549,549,549
BEGIN DESCRIPTION:
XS3361A
END DESCRIPTION:
XS GIS Cut Line= 6
      2814903.54      7080825.84      2814647.48      7081125.30
      2813709.98      7081511.58      2813258.60      7081767.66
      2813223.87      7081824.08      2813185.04      7082121.79
#Sta/Elev= 30
  4105.7  506.57  4136.3  505.50  4189.1  503.06  4196.7  503.92  4217.6  499.44
  4238.5  497.44  4451.5  492.85  4465.7  493.44  4473.0  495.27  4497.8  490.57
  4559.3  486.95  4594.0  486.52  4792.4  482.21  4799.3  482.11  5019.5  479.59
  5126.7  481.29  5187.6  480.70  5202.1  478.76  5202.9  477.96  5211.2  478.76
  5212.0  480.64  5249.0  480.69  5271.7  481.08  5337.0  480.01  5351.1  480.99
  5435.2  482.21  5514.4  488.92  5727.1  496.64  6231.7  499.53  6399.9  498.62
#Mann=11,-1,0
  4105.7    0.08       0  4136.3    0.05       0  4594.0    0.07       0
  4799.3    0.12       0  5019.5    0.07       0  5126.7    0.12       0
  5202.1    0.07       0  5211.2    0.12       0  5249.0    0.07       0
  5271.7    0.12       0  5351.1    0.16       0
Bank Sta=4792.4,5435.2
Exp/Cntr=0.3,0.1

Type RM Length L Ch R = 1,7311,1398,1398,1398
BEGIN DESCRIPTION:
XS3362A
END DESCRIPTION:
XS GIS Cut Line= 4
      2814916.62      7080786.75      2814274.22      7080773.73
      2813584.12      7081012.45      2813354.05      7081338.01
#Sta/Elev= 30
  4329.6  507.30  4403.9  503.71  4551.3  496.24  4601.3  489.83  4659.6  490.78
  4800.0  486.23  4911.3  483.64  4945.0  481.05  4989.2  473.93  5013.6  474.29
  5020.4  477.36  5034.8  478.50  5130.0  481.84  5151.2  479.00  5226.2  478.72
  5233.3  476.87  5238.6  478.96  5246.4  476.95  5252.5  472.87  5253.3  472.07
  5261.6  472.87  5278.2  474.14  5288.7  479.66  5422.6  480.10  5536.3  479.54
  5660.7  481.05  5925.9  486.95  5948.2  490.34  6057.7  493.98  6101.0  494.69
#Mann=9,-1,0
  4329.6    0.08       0  4403.9    0.05       0  4800.0    0.12       0
  5226.2    0.05       0  5252.5    0.07       0  5261.6    0.05       0
  5422.6    0.12       0  5536.3    0.05       0  6057.7    0.16       0
Bank Sta=4945,5660.7
Exp/Cntr=0.3,0.1

Type RM Length L Ch R = 1,5913,505,505,505
BEGIN DESCRIPTION:
UNT 053 in LFCCL Watershed 3.0
END DESCRIPTION:
XS GIS Cut Line= 3
      2814424.98      7080025.01      2814025.00      7080275.00
      2813424.99      7081075.02
#Sta/Elev= 30
  4510.8  497.15  4569.7  493.99  4676.5  486.06  4740.8  478.69  4859.2  476.67
  4947.1  477.21  4959.5  476.27  4968.9  473.29  4974.8  473.48  4979.5  469.43
  4989.8  470.33  4991.4  468.68  4992.3  467.88  5000.6  468.68  5004.4  469.09
  5010.6  473.79  5018.9  470.52  5024.1  473.69  5032.5  476.69  5068.9  475.46
  5154.4  476.17  5196.0  477.84  5396.0  478.52  5439.8  479.84  5501.7  478.06
  5627.8  478.69  5839.8  481.91  5875.2  483.02  5904.4  485.28  5982.5  487.38
#Mann=4,-1,0
  4510.8    0.12       0  4991.4    0.07       0  5000.6    0.12       0
  5501.7    0.05       0
Bank Sta=4740.8,5627.8
Exp/Cntr=0.3,0.1

Type RM Length L Ch R = 1,5408,371,371,371
BEGIN DESCRIPTION:
UNT 053 in LFCCL Watershed 2.0
END DESCRIPTION:
XS GIS Cut Line= 3
      2814375.02      7079724.99      2814034.08      7079844.83
      2812920.04      7081055.87
#Sta/Elev= 30
  4639.1  501.60  4872.3  486.86  4924.5  484.79  4959.1  483.02  4978.7  477.65
  4990.1  472.53  4997.3  470.42  5003.5  470.42  5009.7  467.69  5010.6  466.89
  5018.9  467.69  5021.2  474.90  5028.0  475.35  5113.1  476.48  5134.6  473.55
  5155.6  473.38  5163.0  474.49  5169.8  473.33  5177.2  474.70  5198.1  473.88
  5219.1  476.41  5240.7  474.38  5269.0  476.39  5304.2  474.66  5414.5  477.42
  5850.1  477.65  6068.7  480.79  6132.2  479.57  6528.6  479.59  6646.0  485.53
#Mann=5,-1,0
  4639.1    0.16       0  4924.5    0.12       0  5009.7    0.07       0
  5018.9    0.12       0  5414.5    0.05       0
Bank Sta=4978.7,5850.1
Exp/Cntr=0.3,0.1

Type RM Length L Ch R = 1,5037,562,562,562
BEGIN DESCRIPTION:
XS3363A
END DESCRIPTION:
XS GIS Cut Line= 3
      2814157.02      7079489.02      2813683.94      7079836.23
      2812809.95      7081039.99
#Sta/Elev= 30
  4427.2  491.18  4461.7  488.64  4541.2  486.53  4553.7  484.42  4604.0  482.18
  4626.8  479.70  4653.9  479.27  4695.5  476.59  4804.4  476.44  4954.8  474.29
  4975.7  473.54  4990.3  471.23  4994.1  467.19  4995.0  466.39  5003.4  467.19
  5005.0  467.20  5010.3  471.39  5016.3  471.39  5025.9  469.05  5040.6  471.24
  5049.1  475.90  5061.9  471.94  5070.0  474.97  5076.1  475.92  5083.2  475.28
  5412.4  476.59  5729.3  479.34  5992.9  477.39  6223.3  477.28  6501.6  481.81
#Mann=5,-1,0
  4427.2    0.16       0  4604.0    0.12       0  4994.1    0.07       0
  5003.4    0.12       0  5083.2    0.05       0
Bank Sta=4695.5,5412.4
Exp/Cntr=0.3,0.1

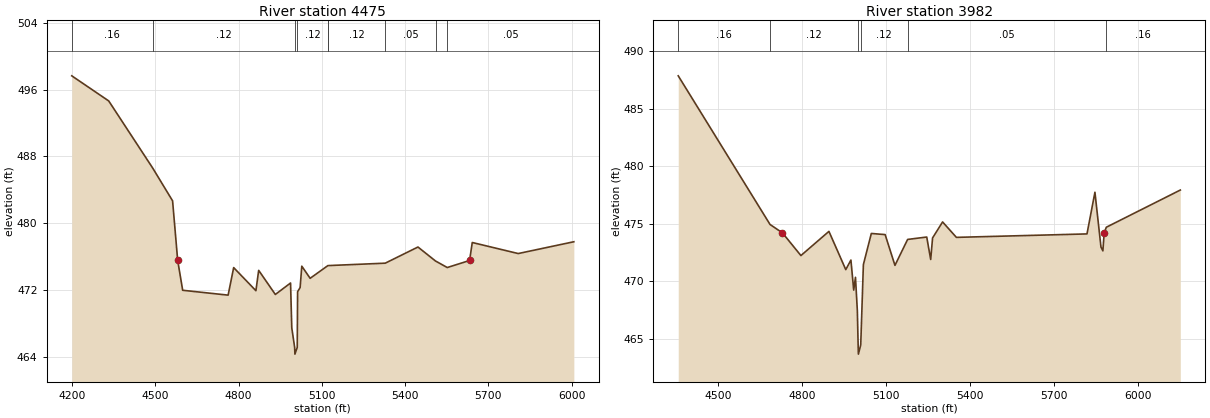
Type RM Length L Ch R = 1,4475,493,493,493
BEGIN DESCRIPTION:
UNT 053 in LFCCL Watershed 1.0
END DESCRIPTION:
XS GIS Cut Line= 3
      2814348.03      7079306.72      2813562.41      7079332.76
      2812999.10      7080186.40
#Sta/Elev= 30
  4199.1  497.64  4332.2  494.64  4491.0  486.60  4562.3  482.70  4580.7  475.57
  4598.7  472.01  4762.4  471.43  4782.4  474.72  4862.5  471.96  4872.5  474.39
  4932.5  471.51  4987.3  472.88  4991.7  467.53  5002.1  465.18  5003.0  464.38
  5011.4  465.18  5012.7  471.84  5021.8  472.34  5027.8  474.89  5057.9  473.44
  5121.8  474.96  5122.1  474.96  5328.5  475.25  5446.3  477.18  5509.5  475.51
  5551.9  474.73  5632.3  475.57  5642.0  477.72  5807.5  476.40  6007.9  477.81
#Mann=9,-1,0
  4199.1    0.16       0  4491.0    0.12       0  5002.1    0.07       0
  5011.4    0.12       0  5121.8    0.16       0  5122.1    0.12       0
  5328.5    0.05       0  5509.5    0.12       0  5551.9    0.05       0
Bank Sta=4580.7,5632.3
Exp/Cntr=0.3,0.1

Type RM Length L Ch R = 1,3982,0,0,0
BEGIN DESCRIPTION:
XS3364A
END DESCRIPTION:
XS GIS Cut Line= 3
      2814152.65      7079102.72      2813523.35      7079059.32
      2812742.12      7079923.02
#Sta/Elev= 30
  4356.1  487.85  4684.4  474.94  4728.8  474.21  4794.8  472.24  4895.0  474.34
  4955.2  471.02  4973.6  471.85  4983.6  469.24  4989.9  470.35  4996.6  467.44
  4999.4  464.48  5000.3  463.68  5008.7  464.48  5018.2  471.46  5046.6  474.16
  5096.0  474.06  5131.1  471.39  5176.4  473.64  5244.7  473.85  5258.9  471.90
  5265.6  473.77  5301.4  475.16  5350.8  473.82  5817.8  474.12  5846.2  477.74
  5867.8  472.98  5874.6  472.65  5879.3  474.21  5886.9  474.70  6151.5  477.93
#Mann=6,-1,0
  4356.1    0.16       0  4684.4    0.12       0  4999.4    0.07       0
  5008.7    0.12       0  5176.4    0.05       0  5886.9    0.16       0
Bank Sta=4728.8,5879.3
Exp/Cntr=0.3,0.1

Chan Stop Cuts=-1