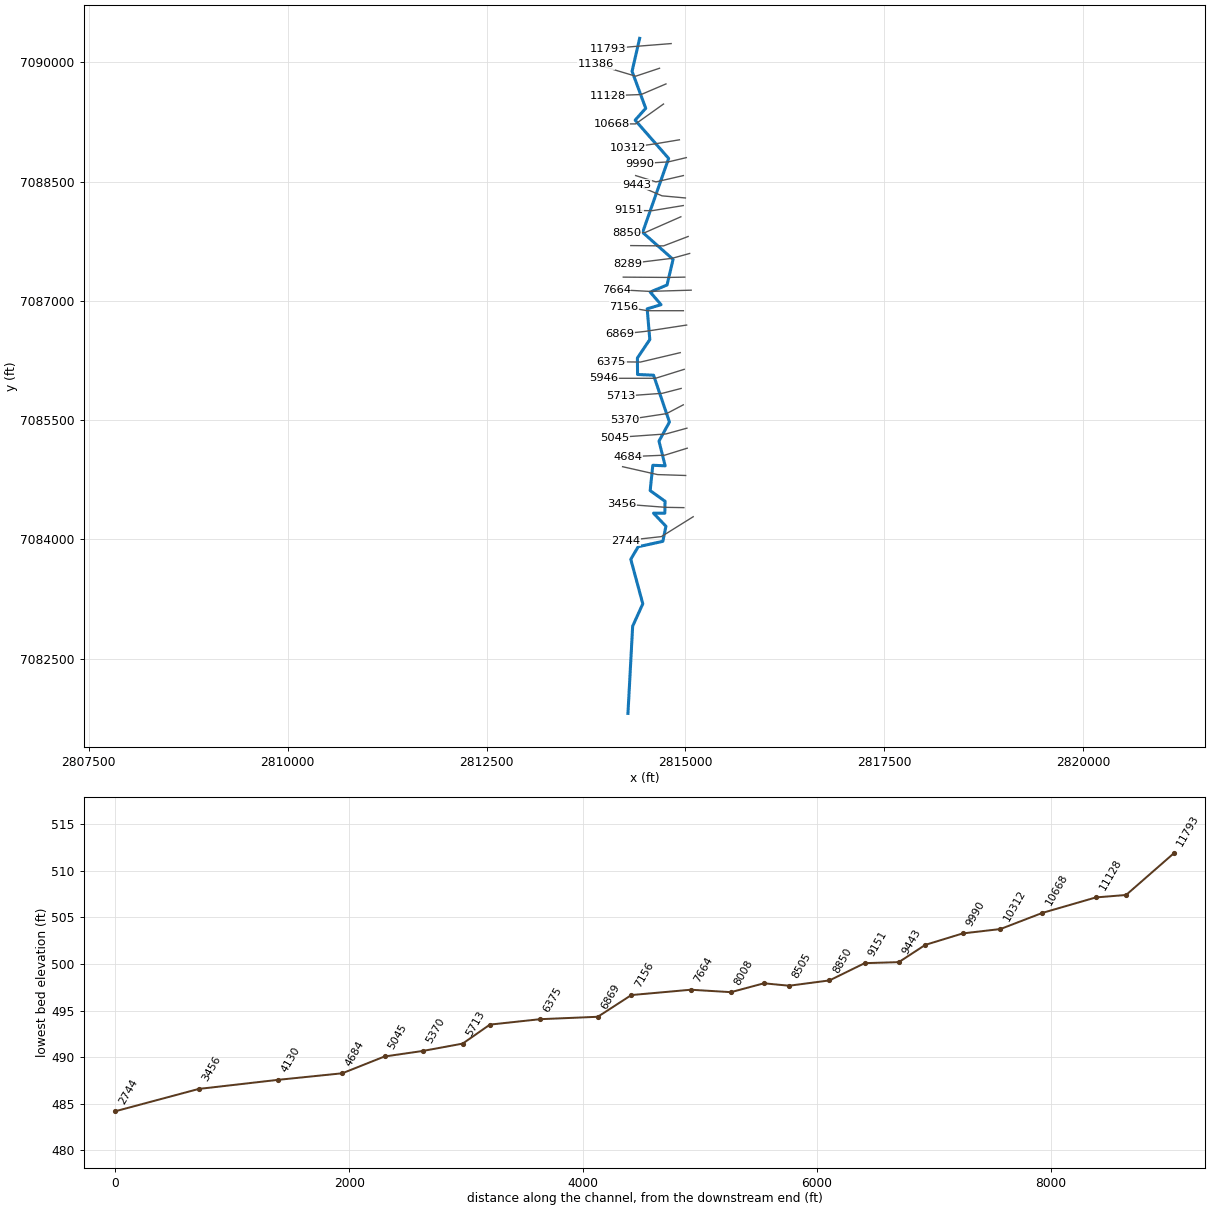
--- UNT 054 in LFCCL Watershed.prj (project) ---

Proj Title=UNT 054 in LFCCL Watershed Base Level Engineering
Current Plan=p01
Default Exp/Contr=0.3,0.1
English Units
Geom File=g01
Flow File=f01
Plan File=p01
BEGIN DESCRIPTION:
UNT 054 in LFCCL Watershed
END DESCRIPTION:

--- UNT 054 in LFCCL Watershed.p01 (plan) ---

Plan Title=Multiple Run
Short Identifier=Multiple
Geom File=g01
Flow File=f01
Subcritical Flow
K Sum by GR= 0
Std Step Tol= 0.01
Critical Tol= 0.01
Num of Std Step Trials= 20
Max Error Tol= 0.3
Flow Tol Ratio= 0.001
Split Flow NTrial= 30
Split Flow Tol= 0.02
Split Flow Ratio= 0.02
Log Output Level= 0
Friction Slope Method= 1
Unsteady Friction Slope Method= 2
Unsteady Bridges Friction Slope Method= 1
Parabolic Critical Depth
Global Vel Dist=  1 , 1 , 1
Global Log Level= 0
CheckData=True
Encroach Param= -1, 0, 0, 0
BEGIN DESCRIPTION:
Multiple Run
END DESCRIPTION:

--- UNT 054 in LFCCL Watershed.f01 (steady flow) ---

Flow Title=Multiple
Number of Profiles=7
Profile Names=10-year,25-year,50-year,1pct_min,100-year,1pct_plu,500-year
River Rch & RM= UNT 054 in LFCCL,Reach-1,11793
     510     665     787     462     922    1839    1261
River Rch & RM= UNT 054 in LFCCL,Reach-1,11386
     691     917    1097     650    1298    2589    1812
River Rch & RM= UNT 054 in LFCCL,Reach-1,6375
     818    1092    1312     780    1557    3107    2189
Boundary for River Rch & Prof#=UNT 054 in LFCCL,Reach-1,1
Up Type=0
Dn Type=3
Dn Slope=0.005
Boundary for River Rch & Prof#=UNT 054 in LFCCL,Reach-1,2
Up Type=0
Dn Type=3
Dn Slope=0.005
Boundary for River Rch & Prof#=UNT 054 in LFCCL,Reach-1,3
Up Type=0
Dn Type=3
Dn Slope=0.005
Boundary for River Rch & Prof#=UNT 054 in LFCCL,Reach-1,4
Up Type=0
Dn Type=3
Dn Slope=0.005
Boundary for River Rch & Prof#=UNT 054 in LFCCL,Reach-1,5
Up Type=0
Dn Type=3
Dn Slope=0.005
Boundary for River Rch & Prof#=UNT 054 in LFCCL,Reach-1,6
Up Type=0
Dn Type=3
Dn Slope=0.005
Boundary for River Rch & Prof#=UNT 054 in LFCCL,Reach-1,7
Up Type=0
Dn Type=3
Dn Slope=0.005

--- UNT 054 in LFCCL Watershed.g01 (geometry) ---

Geom Title=Existing Conditions

River Reach=UNT 054 in LFCCL,Reach-1
Reach XY= 30
      2814425.04      7090301.32      2814329.83      7089886.32
      2814501.57      7089421.25      2814368.61      7089272.05
      2814789.59      7088790.67      2814462.60      7087860.61
      2814845.33      7087520.58      2814769.62      7087199.02
      2814557.91      7087109.33      2814694.30      7086950.71
      2814519.76      7086899.03      2814552.86      7086512.08
      2814396.97      7086280.28      2814398.91      7086072.83
      2814600.15      7086063.53      2814799.80      7085475.09
      2814668.23      7085234.11      2814745.79      7084923.87
      2814590.67      7084930.80      2814557.43      7084612.25
      2814744.40      7084477.91      2814741.63      7084326.95
      2814598.98      7084328.33      2814755.48      7084163.52
      2814716.70      7083973.78      2814406.47      7083905.92
      2814313.67      7083748.03      2814464.64      7083188.50
      2814337.22      7082905.96      2814278.14      7081809.80

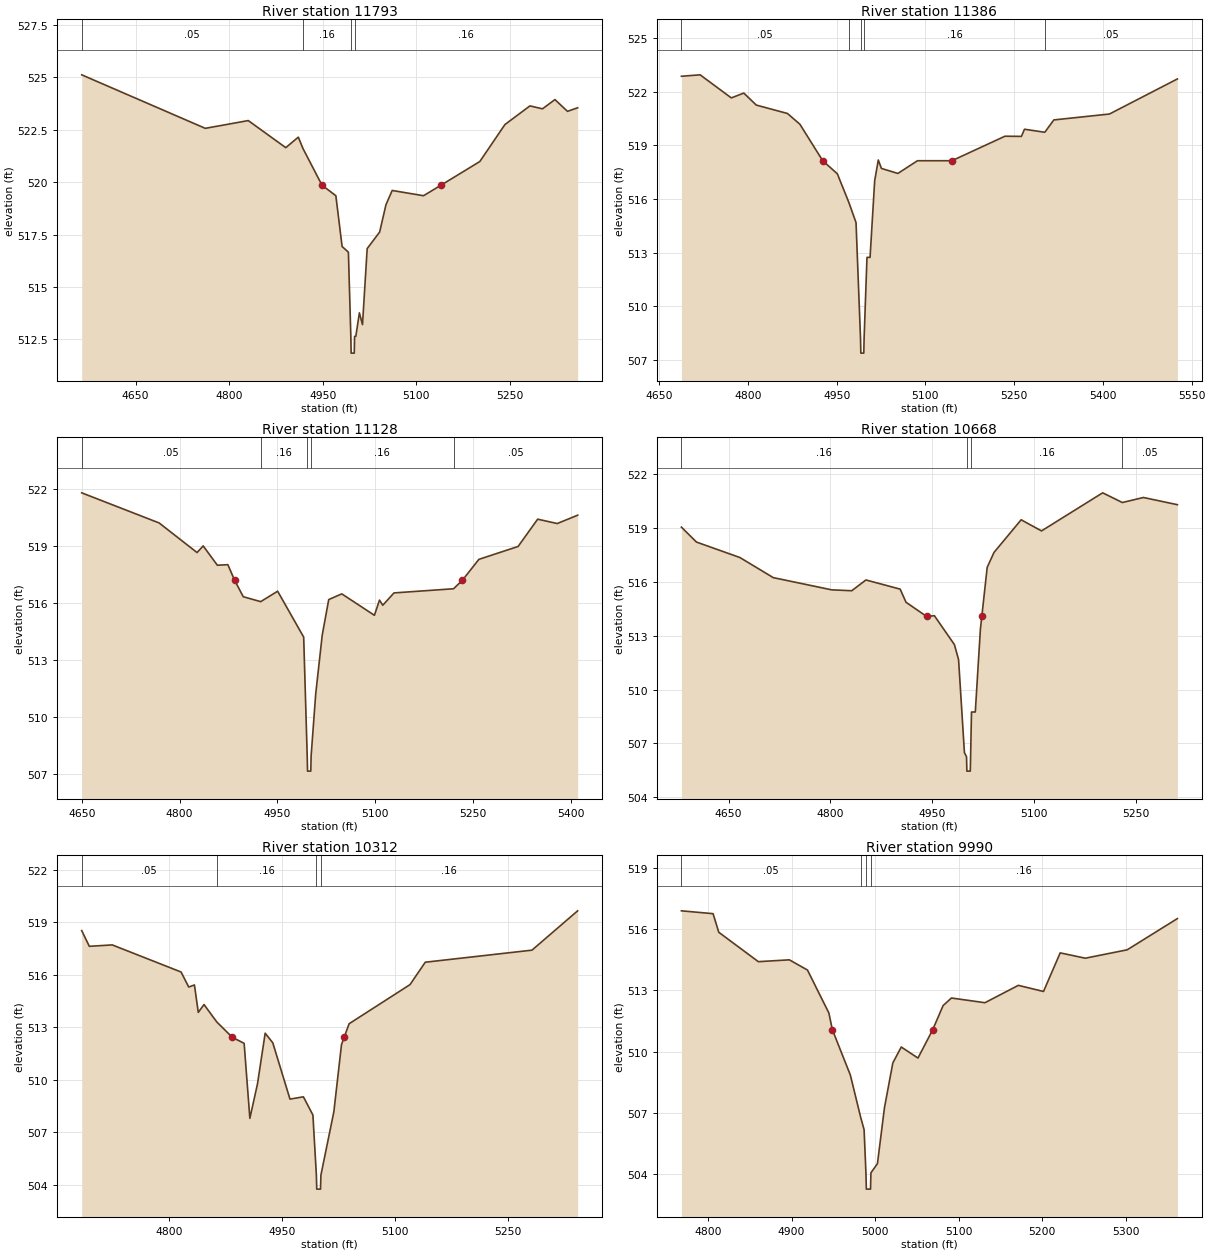
Type RM Length L Ch R = 1,11793,407,407,407
BEGIN DESCRIPTION:
UNT 054 in LFCCL Watershed 12.0
END DESCRIPTION:
XS GIS Cut Line= 3
      2814821.13      7090235.31      2814386.15      7090200.97
      2814028.77      7090170.55
#Sta/Elev= 30
  4563.5  525.11  4761.6  522.56  4830.5  522.93  4890.6  521.64  4910.7  522.14
  4918.0  521.61  4948.7  519.85  4970.9  519.35  4980.9  516.93  4991.0  516.66
  4994.9  512.65  4995.4  511.85  5000.4  511.85  5000.9  512.65  5002.9  512.65
  5008.6  513.77  5013.6  513.21  5021.1  516.83  5041.1  517.62  5051.2  518.92
  5061.2  519.60  5111.4  519.35  5139.4  519.85  5201.7  520.98  5241.9  522.74
  5282.0  523.63  5302.1  523.49  5322.1  523.93  5342.2  523.37  5358.5  523.54
#Mann=4,-1,0
  4563.5    0.05       0  4918.0    0.16       0  4994.9    0.07       0
  5000.9    0.16       0
Bank Sta=4948.7,5139.4
Exp/Cntr=0.3,0.1

Type RM Length L Ch R = 1,11386,258,258,258
BEGIN DESCRIPTION:
UNT 054 in LFCCL Watershed 11.0
END DESCRIPTION:
XS GIS Cut Line= 3
      2814674.97      7089924.99      2814375.00      7089825.00
      2813875.01      7089975.00
#Sta/Elev= 30
  4687.7  522.86  4719.3  522.94  4772.0  521.65  4793.1  521.92  4814.2  521.25
  4866.9  520.78  4887.9  520.18  4926.5  518.14  4951.2  517.41  4970.9  515.79
  4982.8  514.68  4990.4  508.19  4990.9  507.39  4995.9  507.39  4996.4  508.19
  5001.3  512.74  5006.5  512.74  5014.3  517.02  5020.4  518.18  5025.7  517.71
  5053.5  517.43  5086.6  518.14  5144.8  518.14  5234.5  519.51  5262.3  519.50
  5267.5  519.90  5301.8  519.73  5317.1  520.42  5411.1  520.75  5525.9  522.71
#Mann=5,-1,0
  4687.7    0.05       0  4970.9    0.16       0  4990.4    0.07       0
  4996.4    0.16       0  5301.8    0.05       0
Bank Sta=4926.5,5144.8
Exp/Cntr=0.3,0.1

Type RM Length L Ch R = 1,11128,460,460,460
BEGIN DESCRIPTION:
XS3365A
END DESCRIPTION:
XS GIS Cut Line= 3
      2814756.24      7089727.86      2814443.38      7089594.33
      2814023.72      7089579.07
#Sta/Elev= 30
  4650.0  521.81  4768.7  520.22  4826.8  518.66  4836.2  519.01  4857.9  517.99
  4874.0  518.02  4884.3  517.20  4897.6  516.33  4924.3  516.07  4950.3  516.62
  4990.2  514.20  4995.6  507.93  4996.1  507.13  5001.1  507.13  5001.6  507.93
  5008.6  511.19  5018.6  514.30  5028.6  516.18  5048.6  516.48  5098.6  515.35
  5106.4  516.15  5111.4  515.88  5128.6  516.53  5219.9  516.75  5233.5  517.20
  5258.7  518.30  5318.8  518.98  5348.8  520.42  5378.8  520.19  5410.1  520.63
#Mann=5,-1,0
  4650.0    0.05       0  4924.3    0.16       0  4995.6    0.07       0
  5001.6    0.16       0  5219.9    0.05       0
Bank Sta=4884.3,5233.5
Exp/Cntr=0.3,0.1

Type RM Length L Ch R = 1,10668,356,356,356
BEGIN DESCRIPTION:
UNT 054 in LFCCL Watershed 9.0
END DESCRIPTION:
XS GIS Cut Line= 3
      2814725.00      7089475.00      2814375.00      7089225.00
      2814075.02      7089225.00
#Sta/Elev= 30
  4580.6  519.04  4602.7  518.21  4666.6  517.35  4715.8  516.23  4801.8  515.55
  4831.3  515.50  4852.2  516.10  4902.6  515.59  4911.2  514.86  4941.5  514.07
  4953.0  514.11  4982.5  512.50  4988.6  511.66  4997.2  506.49  5000.3  506.26
  5000.8  505.46  5005.8  505.46  5006.3  506.26  5007.6  508.75  5013.2  508.75
  5020.7  513.35  5022.8  514.07  5030.7  516.80  5040.7  517.63  5080.7  519.45
  5110.7  518.83  5200.7  520.95  5229.7  520.41  5260.7  520.69  5310.7  520.29
#Mann=4,-1,0
  4580.6    0.16       0  5000.3    0.07       0  5006.3    0.16       0
  5229.7    0.05       0
Bank Sta=4941.5,5022.8
Exp/Cntr=0.3,0.1

Type RM Length L Ch R = 1,10312,322,322,322
BEGIN DESCRIPTION:
UNT 054 in LFCCL Watershed 8.0
END DESCRIPTION:
XS GIS Cut Line= 3
      2814924.98      7089025.00      2814625.00      7088975.00
      2814274.97      7088925.00
#Sta/Elev= 30
  4684.2  518.53  4694.3  517.63  4724.7  517.71  4816.0  516.16  4826.1  515.30
  4833.7  515.42  4838.8  513.85  4846.4  514.30  4863.2  513.31  4884.0  512.42
  4899.6  512.08  4907.2  507.79  4917.3  509.76  4927.5  512.66  4937.6  512.11
  4960.4  508.89  4978.2  509.02  4990.8  507.98  4995.4  504.54  4995.9  503.74
  5000.9  503.74  5001.4  504.54  5018.6  508.17  5028.7  512.00  5032.2  512.42
  5038.8  513.20  5119.6  515.44  5139.8  516.72  5281.3  517.41  5341.9  519.66
#Mann=4,-1,0
  4684.2    0.05       0  4863.2    0.16       0  4995.4    0.07       0
  5001.4    0.16       0
Bank Sta=4884,5032.2
Exp/Cntr=0.3,0.1

Type RM Length L Ch R = 1,9990,321,321,321
BEGIN DESCRIPTION:
UNT 054 in LFCCL Watershed 7.0
END DESCRIPTION:
XS GIS Cut Line= 3
      2815011.85      7088800.73      2814786.76      7088747.32
      2814424.99      7088725.00
#Sta/Elev= 30
  4768.2  516.90  4806.1  516.76  4812.9  515.85  4860.3  514.41  4897.4  514.50
  4919.1  514.00  4944.7  511.90  4948.9  511.08  4970.5  508.85  4982.6  506.82
  4986.9  506.18  4989.1  504.07  4989.6  503.27  4994.6  503.27  4995.1  504.07
  5002.9  504.52  5011.3  507.26  5021.3  509.45  5031.4  510.23  5051.4  509.69
  5069.1  511.08  5081.5  512.26  5091.5  512.63  5131.6  512.40  5171.6  513.25
  5201.7  512.95  5221.7  514.84  5251.8  514.58  5301.9  514.99  5362.0  516.52
#Mann=4,-1,0
  4768.2    0.05       0  4982.6    0.16       0  4989.1    0.07       0
  4995.1    0.16       0
Bank Sta=4948.9,5069.1
Exp/Cntr=0.3,0.1

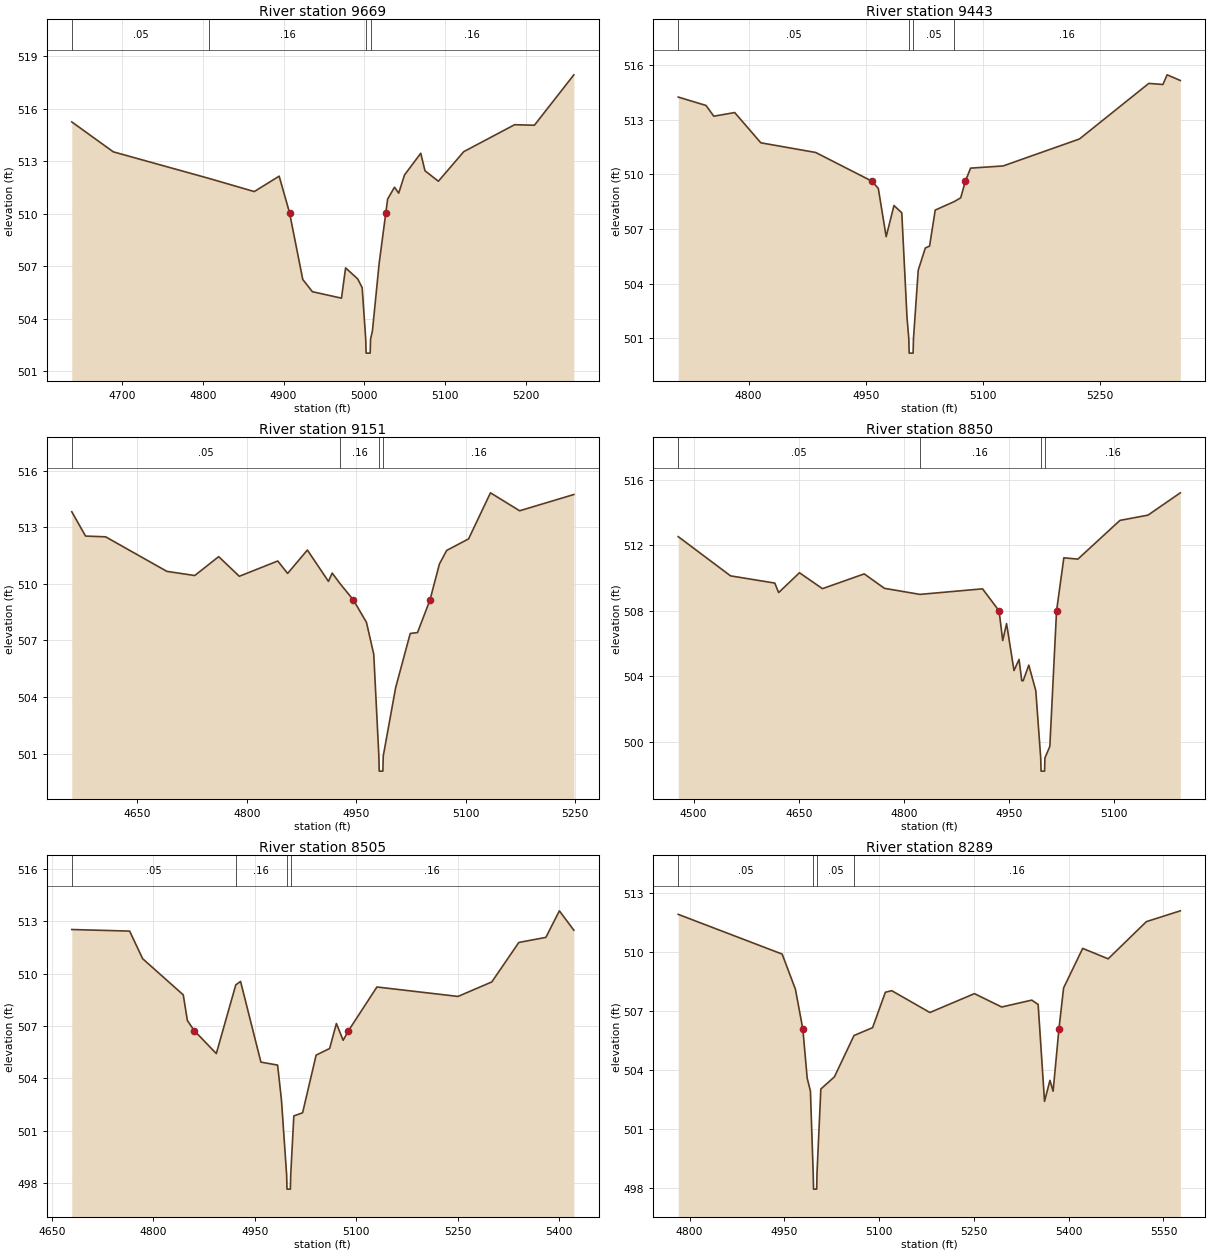
Type RM Length L Ch R = 1,9669,226,226,226
BEGIN DESCRIPTION:
UNT 054 in LFCCL Watershed 6.0
END DESCRIPTION:
XS GIS Cut Line= 3
      2814975.04      7088575.01      2814630.33      7088495.50
      2814374.98      7088575.01
#Sta/Elev= 30
  4638.0  515.25  4689.4  513.54  4807.9  512.02  4863.8  511.27  4894.6  512.15
  4907.4  510.07  4923.8  506.25  4935.7  505.55  4971.7  505.18  4976.8  506.91
  4991.8  506.28  4997.3  505.78  5001.7  502.84  5002.2  502.04  5007.2  502.04
  5007.7  502.84  5010.0  503.31  5018.3  507.16  5026.6  510.07  5028.8  510.84
  5037.3  511.52  5042.5  511.18  5049.7  512.22  5069.8  513.46  5075.0  512.46
  5091.6  511.86  5123.0  513.55  5185.9  515.09  5210.4  515.06  5259.2  517.94
#Mann=4,-1,0
  4638.0    0.05       0  4807.9    0.16       0  5001.7    0.07       0
  5007.7    0.16       0
Bank Sta=4907.4,5026.6
Exp/Cntr=0.3,0.1

Type RM Length L Ch R = 1,9443,292,292,292
BEGIN DESCRIPTION:
XS3367A
END DESCRIPTION:
XS GIS Cut Line= 3
      2815000.46      7088293.29      2814706.64      7088320.00
      2814386.16      7088457.35
#Sta/Elev= 30
  4709.7  514.24  4745.3  513.78  4755.3  513.19  4782.1  513.39  4815.6  511.73
  4885.9  511.20  4957.8  509.63  4966.2  509.23  4976.3  506.58  4986.3  508.29
  4996.3  507.89  5003.0  502.15  5005.3  500.99  5005.8  500.19  5010.8  500.19
  5011.3  500.99  5017.4  504.74  5026.5  505.96  5031.9  506.06  5039.2  508.04
  5063.8  508.51  5071.8  508.71  5077.9  509.63  5084.5  510.34  5126.2  510.46
  5224.1  511.94  5313.0  514.99  5331.1  514.93  5336.5  515.46  5353.4  515.15
#Mann=4,-1,0
  4709.7    0.05       0  5005.3    0.03       0  5011.3    0.05       0
  5063.8    0.16       0
Bank Sta=4957.8,5077.9
Exp/Cntr=0.3,0.1

Type RM Length L Ch R = 1,9151,301,301,301
BEGIN DESCRIPTION:
XS3366A
END DESCRIPTION:
XS GIS Cut Line= 3
      2814973.67      7088197.90      2814580.73      7088133.05
      2814290.72      7088136.86
#Sta/Elev= 30
  4560.2  513.82  4579.1  512.53  4606.6  512.49  4690.6  510.66  4728.8  510.44
  4761.6  511.44  4789.9  510.40  4842.6  511.21  4856.1  510.55  4883.2  511.79
  4912.1  510.13  4917.2  510.57  4928.0  510.01  4946.2  509.15  4964.2  507.96
  4974.2  506.27  4981.2  500.88  4981.7  500.08  4986.7  500.08  4987.2  500.88
  5004.2  504.50  5024.2  507.37  5034.2  507.42  5051.3  509.15  5064.2  511.05
  5074.2  511.77  5104.2  512.38  5134.2  514.82  5174.2  513.87  5248.5  514.73
#Mann=4,-1,0
  4560.2    0.05       0  4928.0    0.16       0  4981.2    0.07       0
  4987.2    0.16       0
Bank Sta=4946.2,5051.3
Exp/Cntr=0.3,0.1

Type RM Length L Ch R = 1,8850,345,345,345
BEGIN DESCRIPTION:
XS3368A
END DESCRIPTION:
XS GIS Cut Line= 3
      2814943.23      7088056.75      2814492.98      7087858.34
      2814268.91      7087858.34
#Sta/Elev= 30
  4478.0  512.52  4552.6  510.13  4615.7  509.69  4621.2  509.11  4650.9  510.32
  4683.7  509.35  4743.3  510.25  4772.1  509.37  4822.8  509.00  4912.0  509.34
  4935.6  508.00  4940.8  506.19  4946.3  507.22  4956.9  504.36  4964.1  505.04
  4968.0  503.74  4970.0  503.74  4978.0  504.69  4988.0  503.13  4995.0  499.03
  4995.5  498.23  5000.5  498.23  5001.0  499.03  5008.0  499.74  5017.6  508.00
  5028.0  511.23  5048.0  511.15  5108.0  513.51  5148.0  513.83  5194.1  515.19
#Mann=4,-1,0
  4478.0    0.05       0  4822.8    0.16       0  4995.0    0.07       0
  5001.0    0.16       0
Bank Sta=4935.6,5017.6
Exp/Cntr=0.3,0.1

Type RM Length L Ch R = 1,8505,216,216,216
BEGIN DESCRIPTION:
XS3369A
END DESCRIPTION:
XS GIS Cut Line= 3
      2815034.77      7087808.74      2814725.72      7087690.46
      2814313.64      7087694.28
#Sta/Elev= 30
  4679.1  512.52  4764.7  512.43  4784.0  510.85  4844.1  508.78  4850.2  507.31
  4860.4  506.73  4893.0  505.42  4921.8  509.35  4928.9  509.55  4959.0  504.93
  4983.7  504.76  4989.4  502.77  4997.1  498.46  4997.6  497.66  5002.6  497.66
  5003.1  498.46  5007.7  501.85  5020.7  502.03  5040.7  505.33  5060.7  505.71
  5070.7  507.14  5080.7  506.18  5088.6  506.73  5130.7  509.23  5250.7  508.69
  5300.7  509.52  5340.7  511.78  5380.7  512.07  5400.7  513.59  5422.1  512.48
#Mann=4,-1,0
  4679.1    0.05       0  4921.8    0.16       0  4997.1    0.07       0
  5003.1    0.16       0
Bank Sta=4860.4,5088.6
Exp/Cntr=0.3,0.1

Type RM Length L Ch R = 1,8289,281,281,281
BEGIN DESCRIPTION:
XS3370A
END DESCRIPTION:
XS GIS Cut Line= 3
      2815053.80      7087595.07      2814832.55      7087534.03
      2814271.65      7087465.35
#Sta/Elev= 30
  4782.1  511.89  4946.6  509.87  4967.6  508.08  4979.3  506.06  4986.2  503.56
  4991.3  502.91  4995.7  498.72  4996.2  497.92  5001.2  497.92  5001.7  498.72
  5007.8  503.01  5029.3  503.63  5060.3  505.73  5089.7  506.13  5109.9  507.93
  5120.0  508.01  5180.4  506.90  5250.9  507.86  5294.0  507.18  5341.6  507.53
  5351.7  507.31  5361.8  502.38  5370.4  503.45  5375.4  502.90  5384.6  506.06
  5392.0  508.15  5422.2  510.16  5462.5  509.63  5523.0  511.52  5576.7  512.07
#Mann=4,-1,0
  4782.1    0.05       0  4995.7    0.03       0  5001.7    0.05       0
  5060.3    0.16       0
Bank Sta=4979.3,5384.6
Exp/Cntr=0.3,0.1

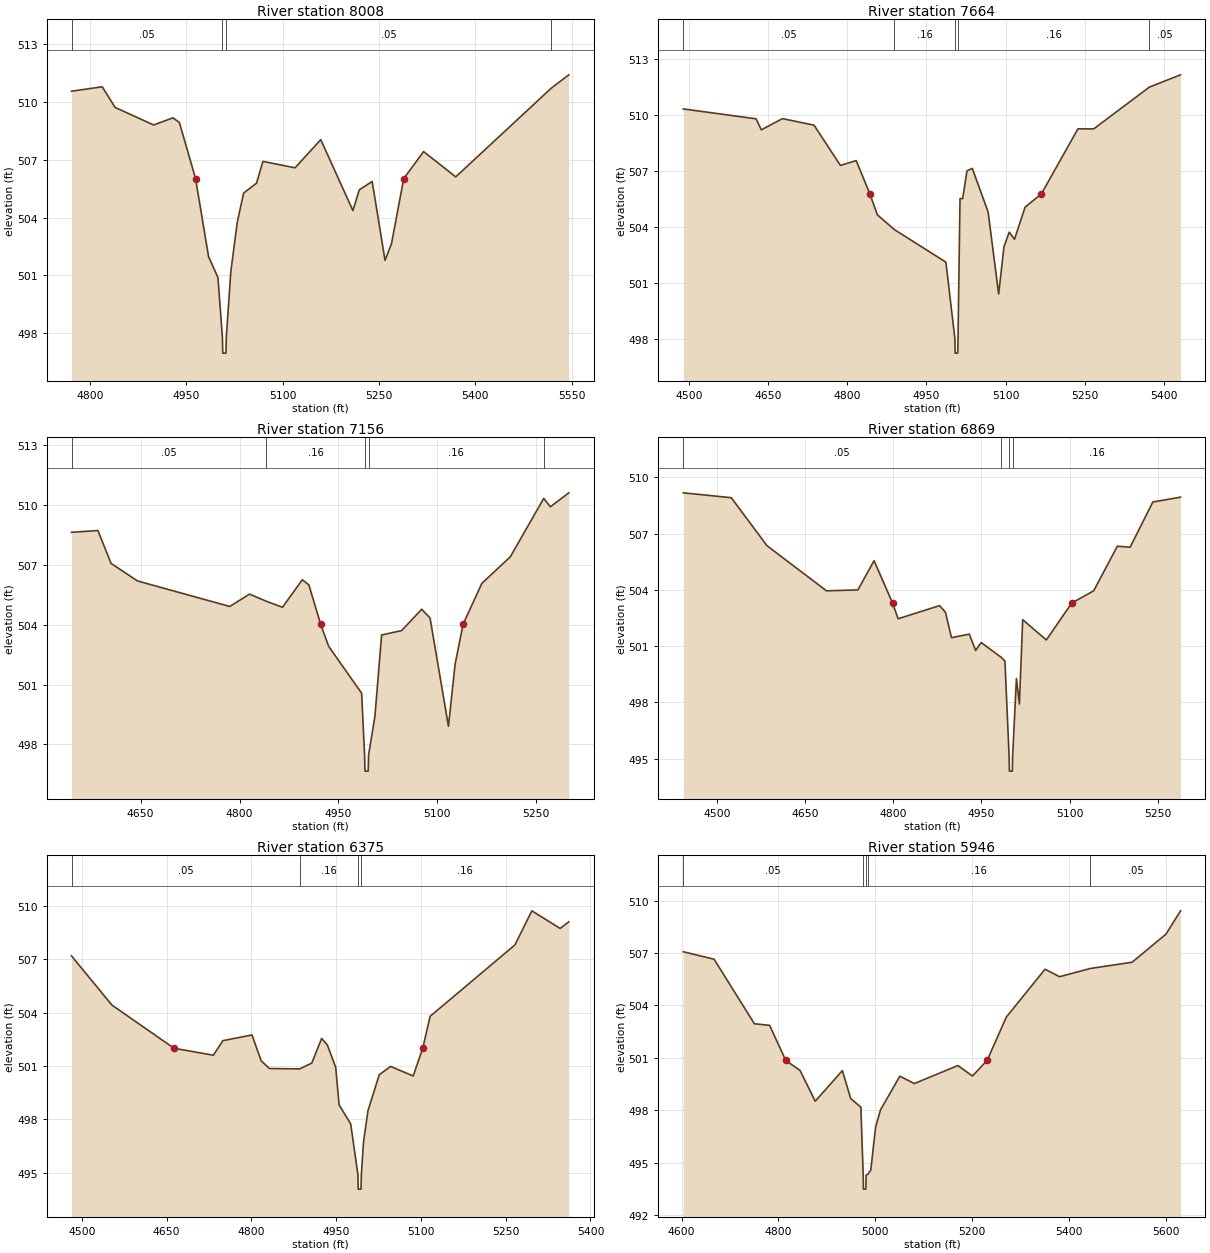
Type RM Length L Ch R = 1,8008,344,344,344
BEGIN DESCRIPTION:
XS3371A
END DESCRIPTION:
XS GIS Cut Line= 3
      2814992.78      7087297.48      2814779.13      7087293.67
      2814219.13      7087297.48
#Sta/Elev= 30
  4771.7  510.55  4819.5  510.78  4839.5  509.71  4899.5  508.80  4929.5  509.17
  4939.5  508.93  4964.7  506.02  4984.9  501.98  4999.5  500.89  5006.5  497.77
  5007.0  496.97  5012.0  496.97  5012.5  497.77  5019.5  501.18  5029.5  503.74
  5039.5  505.27  5059.5  505.78  5069.5  506.91  5119.5  506.58  5159.5  508.04
  5209.5  504.36  5219.5  505.44  5239.5  505.87  5259.5  501.78  5269.5  502.64
  5288.6  506.02  5319.5  507.42  5369.5  506.11  5518.2  510.71  5545.4  511.40
#Mann=4,-1,0
  4771.7    0.05       0  5006.5    0.03       0  5012.5    0.05       0
  5518.2    0.05       0
Bank Sta=4964.7,5288.6
Exp/Cntr=0.3,0.1

Type RM Length L Ch R = 1,7664,508,508,508
BEGIN DESCRIPTION:
XS3372A
END DESCRIPTION:
XS GIS Cut Line= 3
      2815072.90      7087133.42      2814546.39      7087118.16
      2814130.55      7087141.05
#Sta/Elev= 30
  4488.7  510.33  4626.7  509.80  4636.7  509.21  4676.7  509.81  4736.7  509.46
  4786.7  507.30  4816.7  507.56  4842.6  505.77  4856.8  504.65  4889.0  503.86
  4986.8  502.11  5003.8  498.03  5004.3  497.23  5009.3  497.23  5009.8  498.03
  5013.6  505.52  5018.6  505.52  5026.8  507.01  5036.9  507.14  5066.9  504.80
  5086.9  500.40  5096.9  502.93  5107.0  503.72  5117.0  503.34  5137.0  505.06
  5167.9  505.77  5237.2  509.26  5267.2  509.26  5372.7  511.50  5431.9  512.16
#Mann=5,-1,0
  4488.7    0.05       0  4889.0    0.16       0  5003.8    0.07       0
  5009.8    0.16       0  5372.7    0.05       0
Bank Sta=4842.6,5167.9
Exp/Cntr=0.3,0.1

Type RM Length L Ch R = 1,7156,287,287,287
BEGIN DESCRIPTION:
UNT 054 in LFCCL Watershed 3.0
END DESCRIPTION:
XS GIS Cut Line= 3
      2814975.03      7086875.00      2814525.00      7086875.00
      2814224.96      7086925.01
#Sta/Elev= 30
  4545.2  508.64  4585.2  508.73  4605.2  507.08  4645.2  506.20  4785.2  504.92
  4815.2  505.54  4840.7  505.18  4865.2  504.88  4895.2  506.26  4905.2  506.00
  4923.0  504.03  4935.2  502.92  4985.2  500.57  4989.7  497.46  4990.2  496.66
  4995.2  496.66  4995.7  497.46  5005.4  499.42  5015.5  503.49  5045.9  503.71
  5076.3  504.78  5089.0  504.34  5116.9  498.91  5127.0  502.03  5139.1  504.03
  5167.6  506.08  5210.7  507.41  5261.4  510.34  5271.5  509.92  5299.4  510.62
#Mann=5,-1,0
  4545.2    0.05       0  4840.7    0.16       0  4989.7    0.07       0
  4995.7    0.16       0  5261.4    0.05       0
Bank Sta=4923,5139.1
Exp/Cntr=0.3,0.1

Type RM Length L Ch R = 1,6869,494,494,494
BEGIN DESCRIPTION:
XS3373A
END DESCRIPTION:
XS GIS Cut Line= 3
      2815015.69      7086694.66      2814492.98      7086614.53
      2814178.14      7086580.39
#Sta/Elev= 30
  4443.0  509.18  4524.6  508.92  4585.3  506.36  4686.5  503.95  4739.9  504.00
  4767.4  505.56  4798.8  503.30  4808.3  502.46  4878.7  503.16  4888.8  502.81
  4899.0  501.45  4929.3  501.64  4940.1  500.77  4949.5  501.19  4983.7  500.40
  4989.9  500.20  4997.0  495.13  4997.5  494.33  5002.5  494.33  5003.0  495.13
  5009.4  499.27  5014.5  497.91  5020.1  502.41  5060.3  501.33  5103.5  503.30
  5140.8  503.95  5181.0  506.33  5202.8  506.28  5241.4  508.69  5288.5  508.95
#Mann=4,-1,0
  4443.0    0.05       0  4983.7    0.16       0  4997.0    0.07       0
  5003.0    0.16       0
Bank Sta=4798.8,5103.5
Exp/Cntr=0.3,0.1

Type RM Length L Ch R = 1,6375,429,429,429
BEGIN DESCRIPTION:
XS3374A
END DESCRIPTION:
XS GIS Cut Line= 3
      2814935.58      7086347.46      2814435.75      7086229.18
      2814069.70      7086233.00
#Sta/Elev= 30
  4481.9  507.20  4553.5  504.43  4663.4  502.00  4732.8  501.61  4749.7  502.43
  4801.1  502.75  4817.4  501.30  4831.9  500.86  4885.7  500.84  4907.0  501.17
  4924.4  502.56  4934.6  502.18  4949.3  500.92  4955.2  498.82  4975.8  497.74
  4988.6  494.87  4989.1  494.07  4994.1  494.07  4994.6  494.87  4998.4  496.71
  5006.3  498.48  5026.3  500.51  5046.3  500.98  5086.3  500.44  5103.2  502.00
  5116.3  503.80  5266.3  507.82  5296.3  509.74  5346.3  508.75  5361.6  509.12
#Mann=4,-1,0
  4481.9    0.05       0  4885.7    0.16       0  4988.6    0.07       0
  4994.6    0.16       0
Bank Sta=4663.4,5103.2
Exp/Cntr=0.3,0.1

Type RM Length L Ch R = 1,5946,233,233,233
BEGIN DESCRIPTION:
UNT 054 in LFCCL Watershed 2.0
END DESCRIPTION:
XS GIS Cut Line= 3
      2814985.17      7086137.62      2814625.00      7086025.00
      2813974.97      7086025.00
#Sta/Elev= 30
  4603.7  507.07  4667.4  506.64  4750.6  502.95  4782.0  502.86  4815.5  500.85
  4844.9  500.28  4876.3  498.52  4932.4  500.27  4949.6  498.67  4970.6  498.18
  4975.4  494.29  4975.9  493.49  4980.9  493.49  4981.4  494.29  4985.0  494.34
  4991.1  494.58  5001.1  497.05  5011.1  498.02  5051.1  499.95  5081.1  499.53
  5171.1  500.56  5201.1  499.96  5231.4  500.85  5271.1  503.33  5351.1  506.07
  5381.1  505.64  5444.2  506.11  5531.1  506.47  5601.1  508.08  5631.1  509.41
#Mann=5,-1,0
  4603.7    0.05       0  4975.4    0.07       0  4981.4    0.05       0
  4985.0    0.16       0  5444.2    0.05       0
Bank Sta=4815.5,5231.4
Exp/Cntr=0.3,0.1

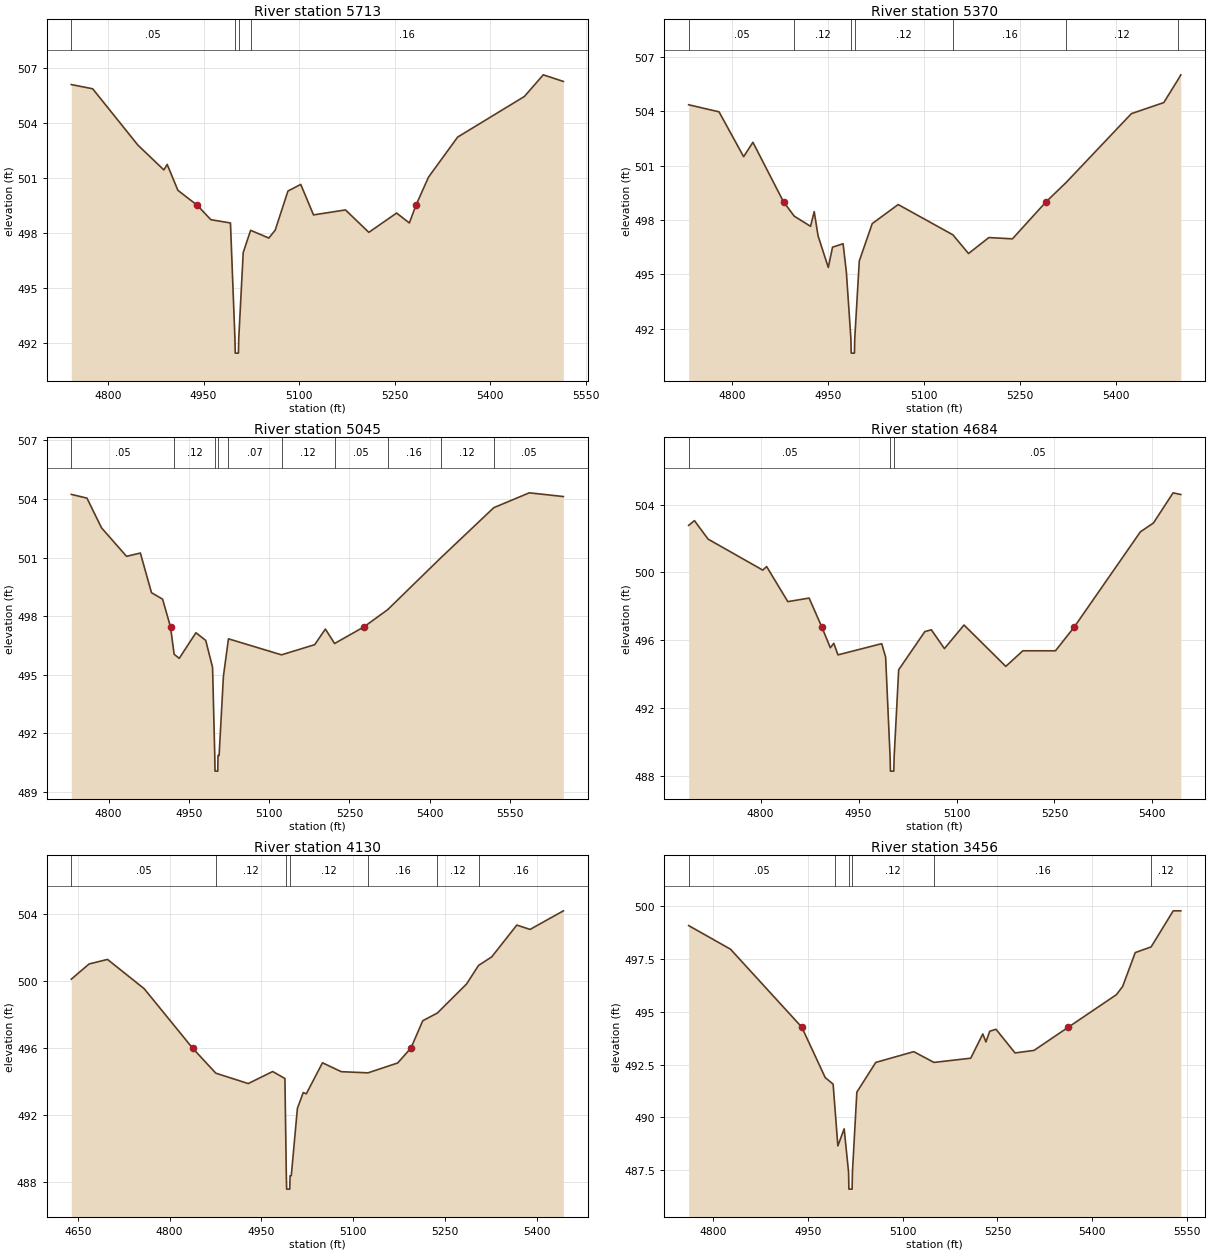
Type RM Length L Ch R = 1,5713,343,343,343
BEGIN DESCRIPTION:
XS3375A
END DESCRIPTION:
XS GIS Cut Line= 3
      2814947.03      7085897.25      2814710.45      7085836.20
      2814183.96      7085798.05
#Sta/Elev= 30
  4742.5  506.08  4776.1  505.85  4847.1  502.78  4887.8  501.43  4893.0  501.73
  4909.8  500.32  4940.3  499.50  4961.5  498.72  4992.3  498.54  4999.3  492.25
  4999.8  491.45  5004.8  491.45  5005.3  492.25  5012.3  496.93  5023.9  498.14
  5052.5  497.72  5062.5  498.15  5082.5  500.28  5102.6  500.64  5122.6  498.98
  5172.8  499.25  5209.4  498.03  5253.0  499.08  5273.0  498.54  5283.3  499.50
  5303.1  501.04  5348.8  503.22  5453.5  505.43  5483.1  506.61  5514.7  506.25
#Mann=4,-1,0
  4742.5    0.05       0  4999.3    0.03       0  5005.3    0.05       0
  5023.9    0.16       0
Bank Sta=4940.3,5283.3
Exp/Cntr=0.3,0.1

Type RM Length L Ch R = 1,5370,325,325,325
BEGIN DESCRIPTION:
XS3376A
END DESCRIPTION:
XS GIS Cut Line= 3
      2814973.69      7085691.21      2814763.87      7085580.57
      2814238.72      7085500.66
#Sta/Elev= 30
  4732.7  504.35  4780.1  503.96  4818.5  501.49  4833.0  502.28  4880.8  499.00
  4897.5  498.21  4923.0  497.65  4928.7  498.46  4934.7  497.13  4950.7  495.38
  4957.3  496.50  4973.8  496.69  4978.9  495.13  4986.0  491.46  4986.5  490.66
  4991.5  490.66  4992.0  491.46  4999.1  495.74  5019.3  497.80  5059.8  498.85
  5145.3  497.18  5169.6  496.15  5201.4  497.03  5238.2  496.96  5290.7  499.00
  5321.9  500.06  5423.9  503.86  5474.5  504.47  5497.0  505.75  5501.1  506.00
#Mann=7,-1,0
  4732.7    0.05       0  4897.5    0.12       0  4986.0    0.07       0
  4992.0    0.12       0  5145.3    0.16       0  5321.9    0.12       0
  5497.0    0.16       0
Bank Sta=4880.8,5290.7
Exp/Cntr=0.3,0.1

Type RM Length L Ch R = 1,5045,361,361,361
BEGIN DESCRIPTION:
XS3377A
END DESCRIPTION:
XS GIS Cut Line= 3
      2815019.50      7085397.44      2814756.24      7085324.94
      2814111.43      7085279.16
#Sta/Elev= 30
  4730.3  504.23  4759.6  504.04  4786.8  502.52  4833.6  501.06  4859.4  501.23
  4880.2  499.20  4900.9  498.87  4915.7  497.45  4922.5  496.05  4932.0  495.84
  4963.2  497.15  4981.5  496.76  4994.3  495.38  4998.4  490.87  4998.9  490.07
  5004.0  490.07  5004.5  490.87  5006.5  490.87  5014.6  494.93  5024.0  496.84
  5123.1  496.02  5185.1  496.54  5205.1  497.34  5222.3  496.60  5277.1  497.45
  5321.4  498.33  5420.6  500.98  5519.7  503.55  5586.1  504.31  5649.8  504.12
#Mann=10,-1,0
  4730.3    0.05       0  4922.5    0.12       0  4998.4    0.07       0
  5004.5    0.12       0  5024.0    0.07       0  5123.1    0.12       0
  5222.3    0.05       0  5321.4    0.16       0  5420.6    0.12       0
  5519.7    0.05       0
Bank Sta=4915.7,5277.1
Exp/Cntr=0.3,0.1

Type RM Length L Ch R = 1,4684,554,554,554
BEGIN DESCRIPTION:
XS3378A
END DESCRIPTION:
XS GIS Cut Line= 3
      2815023.36      7085145.64      2814740.98      7085057.87
      2814283.18      7085038.79
#Sta/Elev= 30
  4689.7  502.77  4698.5  503.05  4719.4  501.96  4803.2  500.13  4809.1  500.34
  4841.6  498.27  4874.2  498.48  4893.7  496.77  4906.7  495.55  4912.0  495.81
  4918.4  495.13  4985.4  495.79  4991.4  495.00  4998.3  489.07  4998.8  488.27
  5003.9  488.27  5004.4  489.07  5011.4  494.25  5051.4  496.50  5061.4  496.61
  5081.5  495.50  5111.5  496.89  5175.5  494.45  5201.6  495.37  5251.6  495.37
  5280.3  496.77  5381.7  502.39  5401.7  502.91  5431.8  504.69  5443.6  504.59
#Mann=3,-1,0
  4689.7    0.05       0  4998.3    0.03       0  5004.4    0.05       0
Bank Sta=4893.7,5280.3
Exp/Cntr=0.3,0.1

Type RM Length L Ch R = 1,4130,674,674,674
BEGIN DESCRIPTION:
XS3379A
END DESCRIPTION:
XS GIS Cut Line= 3
      2815004.23      7084802.24      2814649.41      7084813.69
      2814210.69      7084912.87
#Sta/Elev= 30
  4639.1  500.09  4668.3  501.00  4698.4  501.27  4758.4  499.52  4837.4  495.98
  4875.5  494.48  4928.5  493.86  4968.5  494.58  4988.5  494.16  4990.8  488.36
  4991.3  487.56  4996.4  487.56  4996.9  488.36  4998.9  488.36  5008.9  492.38
  5018.4  493.32  5023.5  493.25  5049.9  495.10  5080.6  494.57  5124.3  494.50
  5172.9  495.09  5194.6  495.98  5213.9  497.61  5237.8  498.07  5285.7  499.81
  5305.1  500.91  5326.7  501.42  5367.7  503.32  5389.4  503.06  5443.9  504.17
#Mann=7,-1,0
  4639.1    0.05       0  4875.5    0.12       0  4990.8    0.07       0
  4996.9    0.12       0  5124.3    0.16       0  5237.8    0.12       0
  5305.1    0.16       0
Bank Sta=4837.4,5194.6
Exp/Cntr=0.3,0.1

Type RM Length L Ch R = 1,3456,712,712,712
BEGIN DESCRIPTION:
XS3380A
END DESCRIPTION:
XS GIS Cut Line= 3
      2814981.32      7084397.81      2814752.42      7084401.63
      2814203.05      7084443.59
#Sta/Elev= 30
  4760.7  499.09  4827.0  497.97  4940.0  494.27  4977.1  491.88  4989.6  491.57
  4991.8  490.71  4997.1  488.64  5007.1  489.45  5014.1  487.39  5014.6  486.59
  5019.7  486.59  5020.2  487.39  5027.2  491.19  5057.2  492.60  5117.4  493.11
  5149.4  492.60  5207.7  492.80  5226.8  493.95  5231.8  493.57  5237.8  494.08
  5247.8  494.17  5277.9  493.05  5308.0  493.17  5362.3  494.27  5438.4  495.81
  5448.4  496.20  5468.4  497.81  5493.6  498.08  5528.6  499.79  5540.6  499.79
#Mann=6,-1,0
  4760.7    0.05       0  4991.8    0.12       0  5014.1    0.07       0
  5020.2    0.12       0  5149.4    0.16       0  5493.6    0.12       0
Bank Sta=4940,5362.3
Exp/Cntr=0.3,0.1

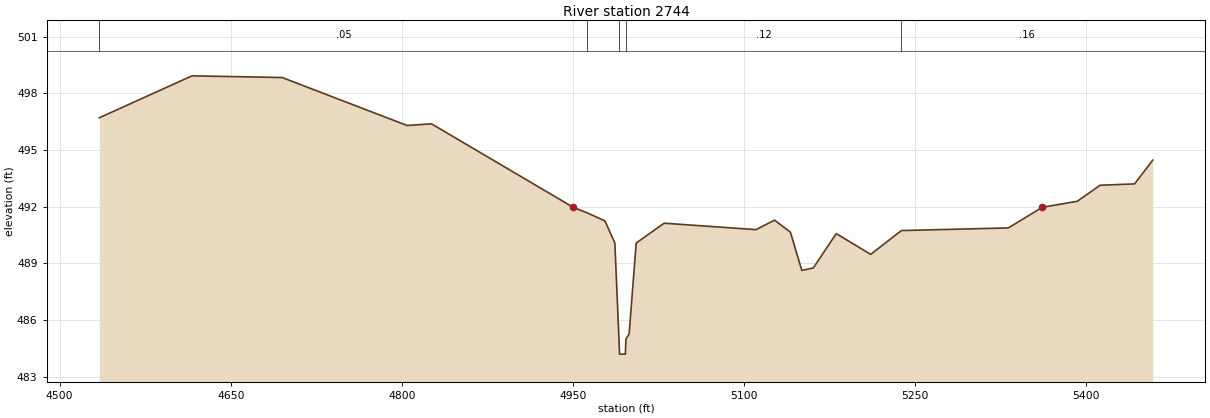
Type RM Length L Ch R = 1,2744,0,0,0
BEGIN DESCRIPTION:
UNT 054 in LFCCL Watershed 1.0
END DESCRIPTION:
XS GIS Cut Line= 3
      2815098.32      7084283.43      2814698.29      7084033.41
      2814249.19      7083983.51
#Sta/Elev= 30
  4534.8  496.71  4616.1  498.93  4695.1  498.84  4804.7  496.30  4826.0  496.39
  4950.3  491.97  4962.8  491.67  4978.1  491.25  4986.8  490.08  4990.4  485.00
  4990.9  484.20  4996.0  484.20  4996.5  485.00  4999.3  485.26  5005.5  490.08
  5030.0  491.13  5110.5  490.79  5126.8  491.29  5140.7  490.66  5150.7  488.63
  5160.8  488.76  5180.9  490.58  5211.1  489.48  5238.0  490.74  5331.8  490.88
  5361.5  491.97  5392.2  492.29  5412.3  493.14  5442.5  493.21  5458.4  494.47
#Mann=5,-1,0
  4534.8    0.05       0  4962.8    0.12       0  4990.4    0.07       0
  4996.5    0.12       0  5238.0    0.16       0
Bank Sta=4950.3,5361.5
Exp/Cntr=0.3,0.1

Chan Stop Cuts=-1