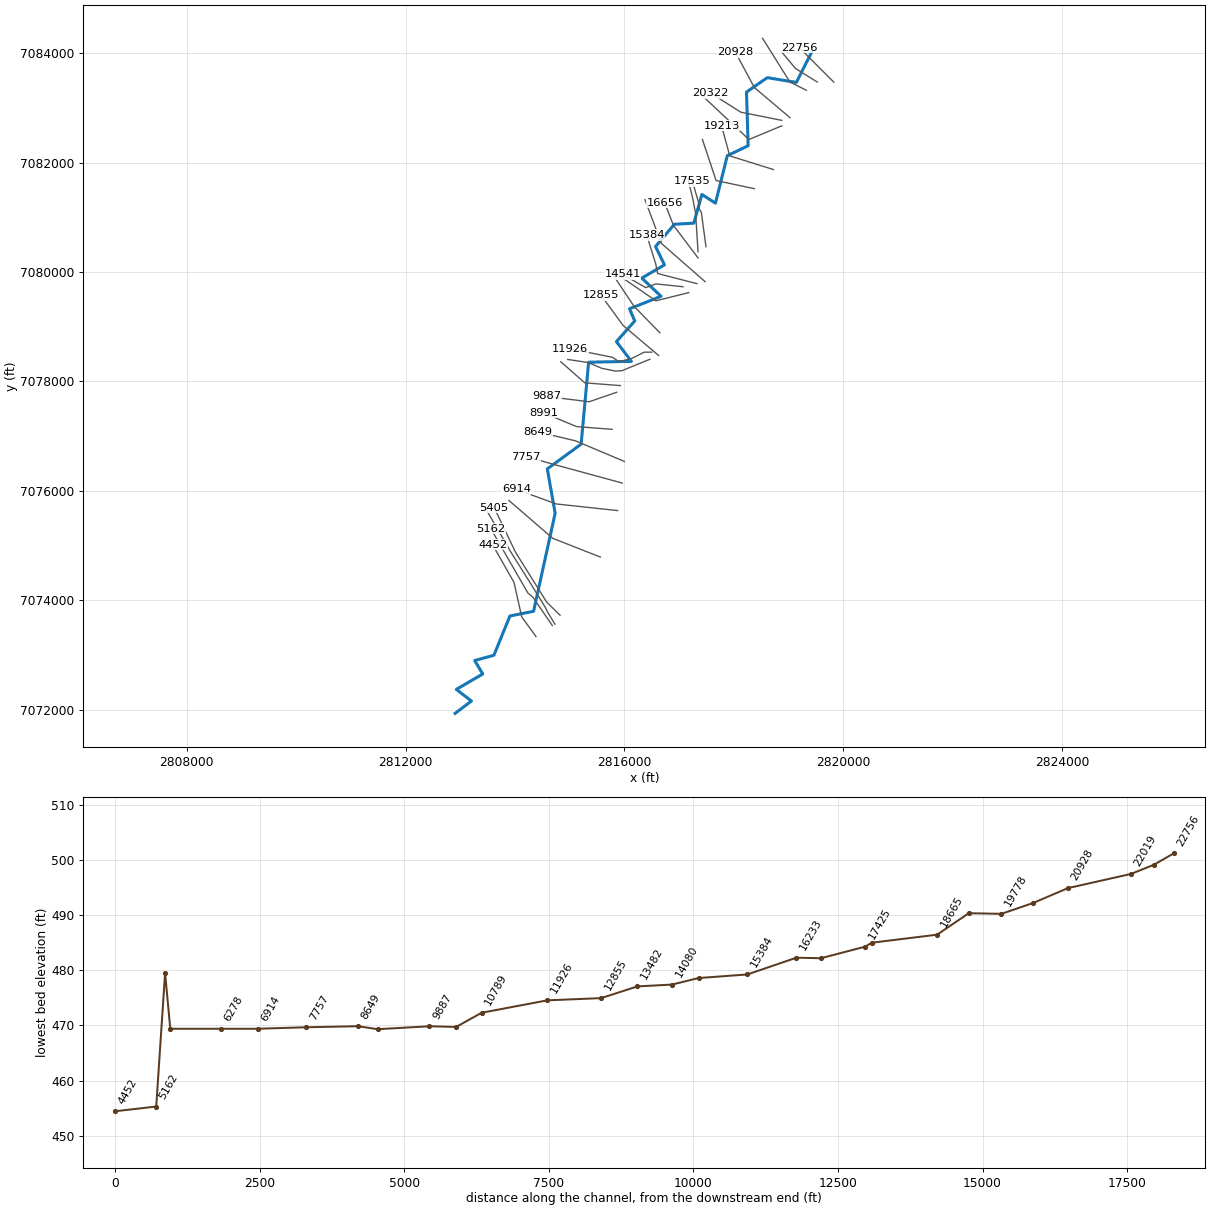
--- UNT 055 in LFCCL Watershed.prj (project) ---

Proj Title=UNT 055 in LFCCL Watershed Base Level Engineering
Current Plan=p01
Default Exp/Contr=0.3,0.1
English Units
Geom File=g01
Flow File=f01
Plan File=p01
BEGIN DESCRIPTION:
UNT 055 in LFCCL Watershed
END DESCRIPTION:

--- UNT 055 in LFCCL Watershed.p01 (plan) ---

Plan Title=Multiple Run
Short Identifier=Multiple
Geom File=g01
Flow File=f01
Subcritical Flow
K Sum by GR= 0
Std Step Tol= 0.01
Critical Tol= 0.01
Num of Std Step Trials= 20
Max Error Tol= 0.3
Flow Tol Ratio= 0.001
Split Flow NTrial= 30
Split Flow Tol= 0.02
Split Flow Ratio= 0.02
Log Output Level= 0
Friction Slope Method= 1
Unsteady Friction Slope Method= 2
Unsteady Bridges Friction Slope Method= 1
Parabolic Critical Depth
Global Vel Dist=  1 , 1 , 1
Global Log Level= 0
CheckData=True
Encroach Param= -1, 0, 0, 0
BEGIN DESCRIPTION:
Multiple Run
END DESCRIPTION:

--- UNT 055 in LFCCL Watershed.f01 (steady flow) ---

Flow Title=Multiple
Number of Profiles=7
Profile Names=10-year,25-year,50-year,1pct_min,100-year,1pct_plu,500-year
River Rch & RM= UNT 055 in LFCCL,Reach-1,22756
     667     886    1061     630    1257    2509    1761
River Rch & RM= UNT 055 in LFCCL,Reach-1,20928
    1138    1553    1894    1142    2279    4547    3296
River Rch & RM= UNT 055 in LFCCL,Reach-1,13482
    1455    2002    2455    1487    2967    5921    4331
Boundary for River Rch & Prof#=UNT 055 in LFCCL,Reach-1,1
Up Type=0
Dn Type=3
Dn Slope=0.005
Boundary for River Rch & Prof#=UNT 055 in LFCCL,Reach-1,2
Up Type=0
Dn Type=3
Dn Slope=0.005
Boundary for River Rch & Prof#=UNT 055 in LFCCL,Reach-1,3
Up Type=0
Dn Type=3
Dn Slope=0.005
Boundary for River Rch & Prof#=UNT 055 in LFCCL,Reach-1,4
Up Type=0
Dn Type=3
Dn Slope=0.005
Boundary for River Rch & Prof#=UNT 055 in LFCCL,Reach-1,5
Up Type=0
Dn Type=3
Dn Slope=0.005
Boundary for River Rch & Prof#=UNT 055 in LFCCL,Reach-1,6
Up Type=0
Dn Type=3
Dn Slope=0.005
Boundary for River Rch & Prof#=UNT 055 in LFCCL,Reach-1,7
Up Type=0
Dn Type=3
Dn Slope=0.005

--- UNT 055 in LFCCL Watershed.g01 (geometry) ---

Geom Title=Existing Conditions

River Reach=UNT 055 in LFCCL,Reach-1
Reach XY= 30
      2819435.56      7084051.44      2819142.56      7083469.34
      2818610.08      7083555.38      2818230.99      7083292.26
      2818260.88      7082311.41      2817879.91      7082128.20
      2817663.54      7081261.00      2817415.42      7081420.02
      2817268.04      7080894.93      2816913.03      7080875.17
      2816569.09      7080468.39      2816731.83      7080132.25
      2816316.92      7079891.44      2816669.29      7079558.19
      2816092.34      7079328.51      2816189.79      7079107.64
      2815853.75      7078728.93      2816127.11      7078367.98
      2815345.51      7078352.06      2815208.83      7076853.89
      2814590.46      7076401.38      2814733.77      7075589.27
      2814339.66      7073797.83      2813907.06      7073711.58
      2813615.12      7072993.67      2813263.17      7072896.74
      2813410.91      7072651.11      2812927.86      7072369.27
      2813204.58      7072156.03      2812905.59      7071930.71

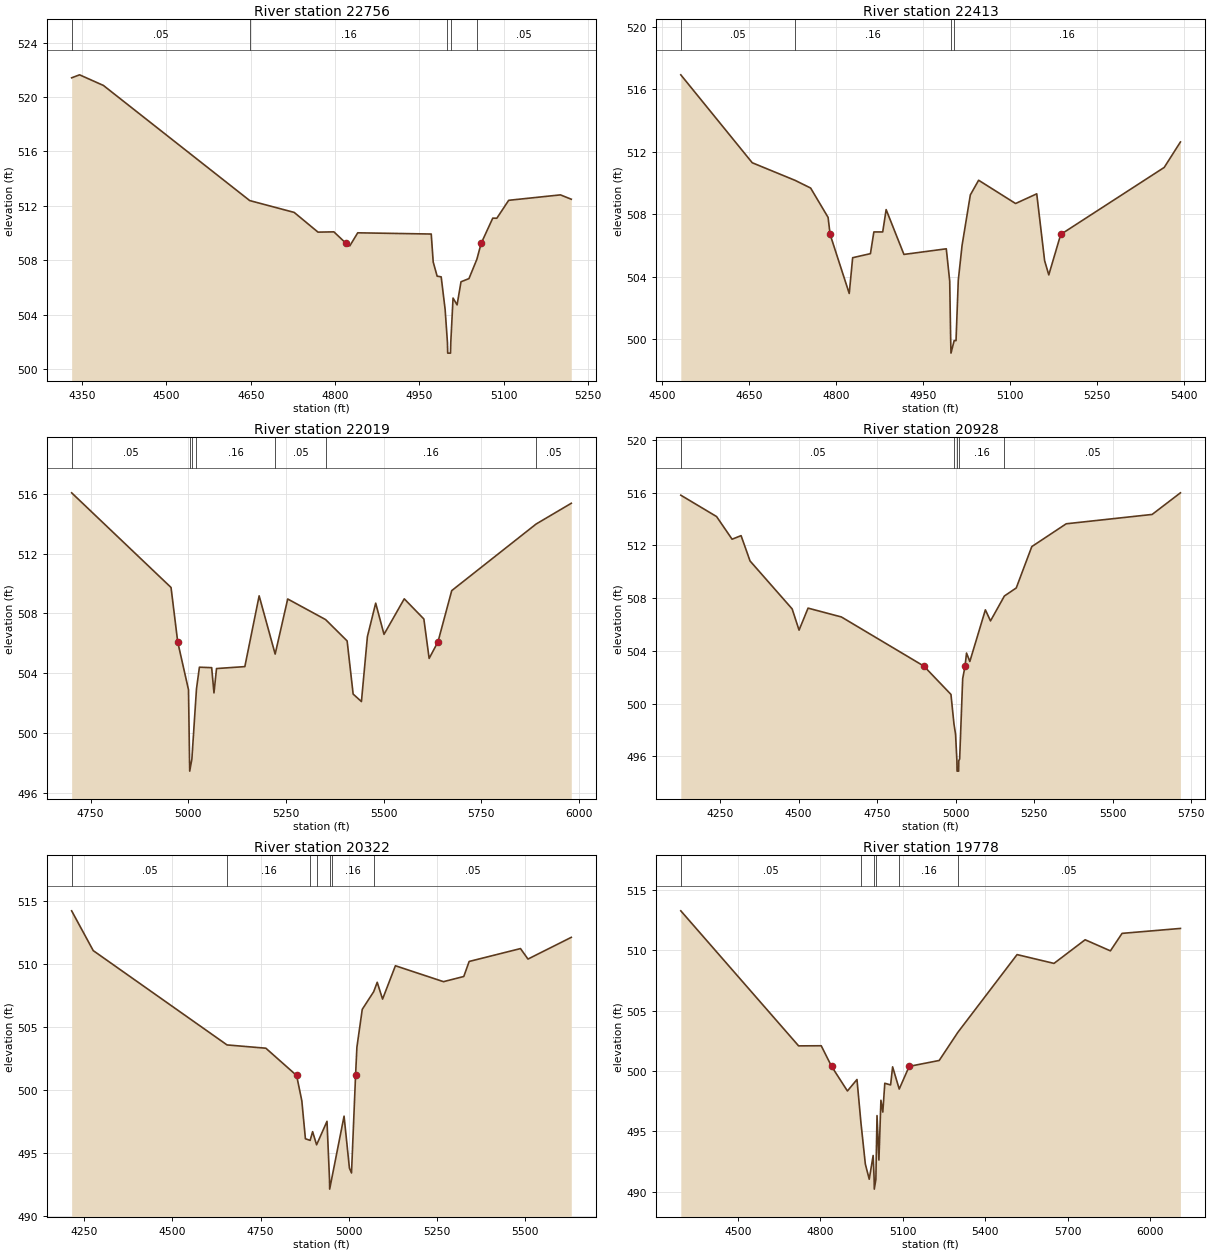
Type RM Length L Ch R = 1,22756,343,343,343
BEGIN DESCRIPTION:
UNT 055 in LFCCL Watershed 34.0
END DESCRIPTION:
XS GIS Cut Line= 3
      2819824.98      7083475.02      2819375.00      7083925.00
      2819199.10      7084106.47
#Sta/Elev= 30
  4331.3  521.41  4345.4  521.63  4387.8  520.85  4648.2  512.38  4727.3  511.51
  4769.7  510.06  4798.0  510.08  4819.7  509.23  4826.3  509.05  4840.4  510.01
  4971.2  509.92  4974.7  507.86  4981.7  506.82  4988.9  506.77  4995.9  504.38
  5000.0  501.96  5000.5  501.16  5005.5  501.16  5006.0  501.96  5010.0  505.21
  5017.2  504.71  5024.2  506.41  5038.3  506.64  5052.4  508.06  5060.0  509.23
  5080.7  511.09  5087.9  511.08  5109.0  512.40  5201.1  512.80  5220.4  512.48
#Mann=5,-1,0
  4331.3    0.05       0  4648.2    0.16       0  5000.0    0.07       0
  5006.0    0.16       0  5052.4    0.05       0
Bank Sta=4819.7,5060
Exp/Cntr=0.3,0.1

Type RM Length L Ch R = 1,22413,394,394,394
BEGIN DESCRIPTION:
UNT 055 in LFCCL Watershed 33.0
END DESCRIPTION:
XS GIS Cut Line= 3
      2819525.03      7083474.98      2819125.00      7083725.00
      2818874.97      7084025.04
#Sta/Elev= 30
  4532.3  516.92  4655.6  511.29  4729.7  510.16  4756.4  509.67  4786.5  507.79
  4790.0  506.70  4823.0  502.92  4828.9  505.21  4859.6  505.47  4865.5  506.86
  4880.8  506.86  4886.7  508.29  4917.4  505.42  4990.5  505.78  4996.4  503.71
  4998.1  499.90  4998.6  499.10  5004.1  499.90  5007.3  499.90  5011.2  503.76
  5017.7  505.99  5032.0  509.23  5046.3  510.17  5110.1  508.68  5146.6  509.30
  5160.2  505.02  5167.4  504.11  5188.0  506.70  5366.6  510.99  5394.6  512.62
#Mann=4,-1,0
  4532.3    0.05       0  4729.7    0.16       0  4998.1    0.07       0
  5004.1    0.16       0
Bank Sta=4790,5188
Exp/Cntr=0.3,0.1

Type RM Length L Ch R = 1,22019,1091,1091,1091
BEGIN DESCRIPTION:
UNT 055 in LFCCL Watershed 32.0
END DESCRIPTION:
XS GIS Cut Line= 3
      2819325.02      7083324.99      2819025.00      7083475.00
      2818525.01      7084274.98
#Sta/Elev= 30
  4701.6  516.08  4956.0  509.74  4973.1  506.09  5000.7  502.89  5003.3  498.24
  5003.8  497.44  5009.3  498.24  5021.1  502.94  5028.6  504.40  5060.0  504.37
  5065.9  502.68  5072.4  504.31  5144.9  504.44  5181.5  509.18  5222.5  505.28
  5254.6  508.97  5351.6  507.59  5406.7  506.16  5422.1  502.60  5443.3  502.10
  5458.6  506.45  5479.8  508.69  5501.1  506.60  5552.9  508.98  5603.1  507.63
  5616.6  504.99  5639.1  506.09  5674.4  509.53  5890.4  513.99  5980.4  515.38
#Mann=7,-1,0
  4701.6    0.05       0  5003.3    0.03       0  5009.3    0.05       0
  5021.1    0.16       0  5222.5    0.05       0  5351.6    0.16       0
  5890.4    0.05       0
Bank Sta=4973.1,5639.1
Exp/Cntr=0.3,0.1

Type RM Length L Ch R = 1,20928,606,606,606
BEGIN DESCRIPTION:
UNT 055 in LFCCL Watershed 30.0
END DESCRIPTION:
XS GIS Cut Line= 3
      2819025.02      7082824.98      2818375.00      7083375.00
      2818025.02      7084024.96
#Sta/Elev= 30
  4125.3  515.81  4239.1  514.19  4288.5  512.47  4317.1  512.74  4345.6  510.82
  4479.6  507.18  4501.6  505.57  4530.2  507.24  4636.2  506.57  4898.7  502.84
  4984.9  500.69  4994.4  498.46  4999.5  497.67  5003.8  495.67  5004.3  494.87
  5009.3  494.87  5009.8  495.67  5012.5  495.78  5022.2  501.89  5029.7  502.84
  5034.4  503.83  5044.9  503.19  5094.4  507.11  5110.7  506.27  5154.9  508.16
  5192.6  508.77  5242.1  511.91  5351.6  513.64  5625.0  514.35  5715.0  515.99
#Mann=5,-1,0
  4125.3    0.05       0  4994.4    0.16       0  5003.8    0.07       0
  5009.8    0.16       0  5154.9    0.05       0
Bank Sta=4898.7,5029.7
Exp/Cntr=0.3,0.1

Type RM Length L Ch R = 1,20322,544,544,544
BEGIN DESCRIPTION:
UNT 055 in LFCCL Watershed 29.0
END DESCRIPTION:
XS GIS Cut Line= 3
      2818875.00      7082775.00      2818125.00      7082925.00
      2817574.98      7083275.01
#Sta/Elev= 30
  4214.3  514.20  4275.5  511.05  4654.9  503.58  4765.0  503.32  4852.2  501.16
  4867.0  499.16  4877.2  496.15  4890.6  496.02  4897.6  496.71  4908.9  495.67
  4938.4  497.53  4945.5  492.96  4946.0  492.16  4951.6  492.96  4986.8  497.94
  5002.0  493.82  5007.9  493.44  5019.4  501.16  5023.2  503.40  5038.4  506.40
  5070.9  507.80  5080.8  508.54  5096.0  507.21  5132.4  509.85  5268.7  508.59
  5326.3  509.00  5341.5  510.19  5487.1  511.21  5508.3  510.38  5631.1  512.10
#Mann=7,-1,0
  4214.3    0.05       0  4654.9    0.16       0  4890.6    0.05       0
  4908.9    0.16       0  4945.5    0.07       0  4951.6    0.16       0
  5070.9    0.05       0
Bank Sta=4852.2,5019.4
Exp/Cntr=0.3,0.1

Type RM Length L Ch R = 1,19778,565,565,565
BEGIN DESCRIPTION:
UNT 055 in LFCCL Watershed 28.0
END DESCRIPTION:
XS GIS Cut Line= 3
      2818875.00      7082675.00      2818275.00      7082425.00
      2817424.97      7083225.03
#Sta/Elev= 30
  4292.0  513.29  4720.5  502.09  4802.8  502.10  4840.4  500.39  4898.1  498.35
  4932.8  499.30  4947.3  495.70  4963.2  492.29  4977.4  491.03  4991.6  493.00
  4995.3  491.01  4995.8  490.21  5001.5  491.01  5005.7  496.31  5012.6  492.62
  5019.9  497.58  5026.8  496.60  5034.0  498.99  5055.1  498.85  5062.4  500.35
  5086.5  498.51  5122.7  500.39  5231.9  500.88  5299.3  503.20  5515.1  509.66
  5649.4  508.93  5762.7  510.89  5854.6  509.97  5897.0  511.42  6109.3  511.83
#Mann=6,-1,0
  4292.0    0.05       0  4947.3    0.12       0  4995.3    0.07       0
  5001.5    0.12       0  5086.5    0.16       0  5299.3    0.05       0
Bank Sta=4840.4,5122.7
Exp/Cntr=0.3,0.1

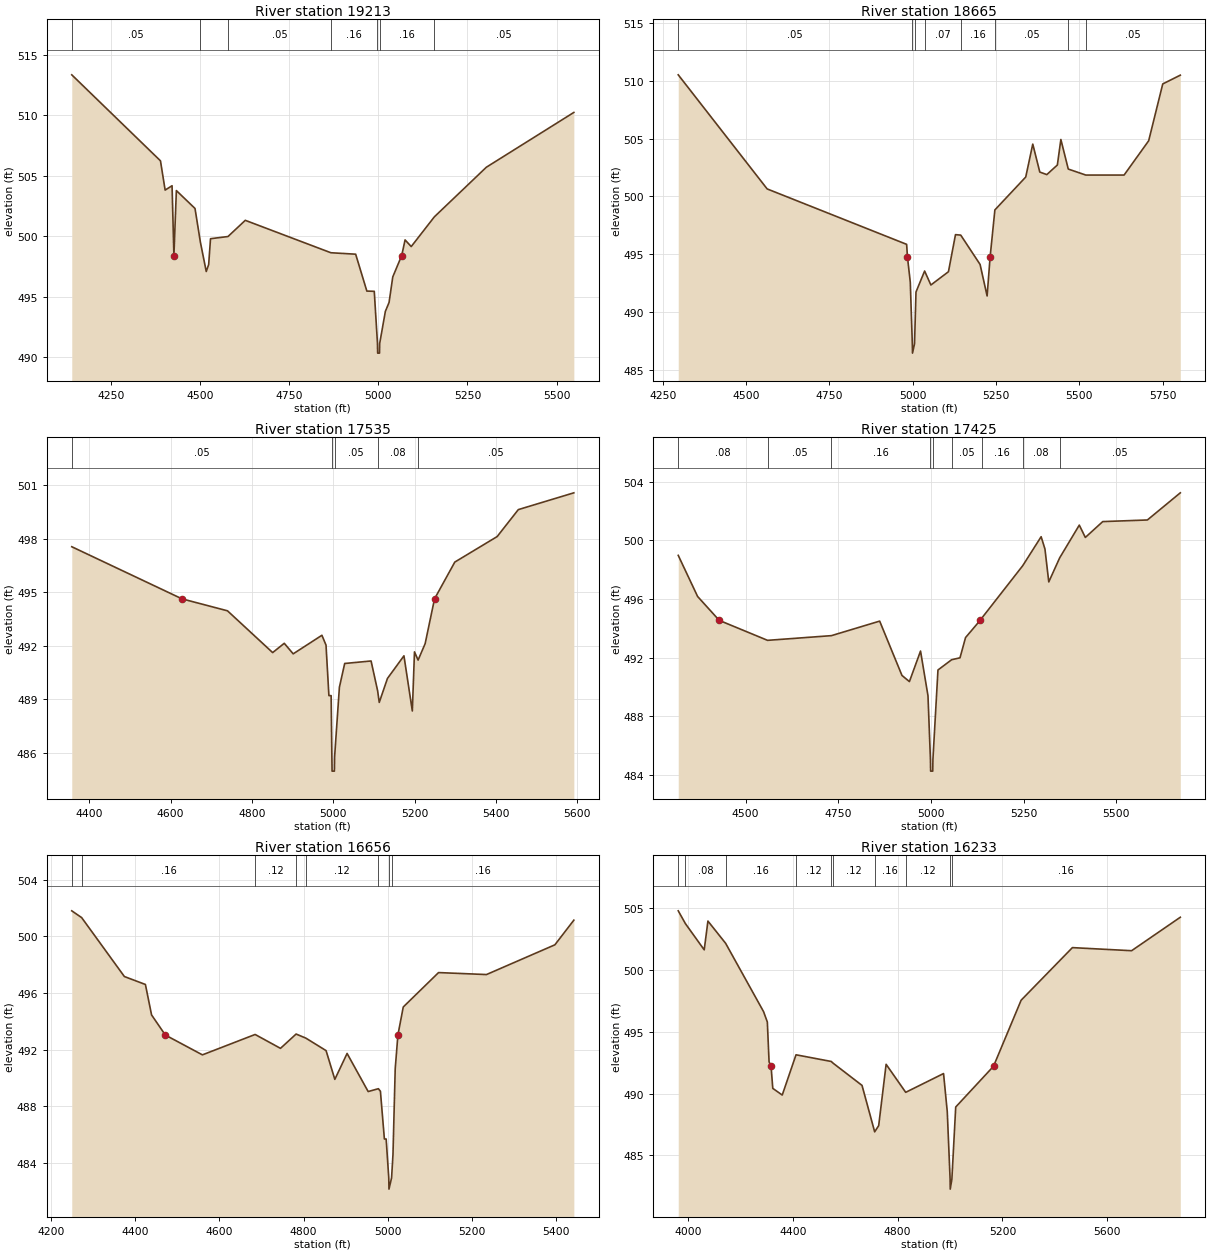
Type RM Length L Ch R = 1,19213,548,548,548
BEGIN DESCRIPTION:
UNT 055 in LFCCL Watershed 27.0
END DESCRIPTION:
XS GIS Cut Line= 3
      2818725.01      7081875.00      2817925.00      7082125.00
      2817774.99      7082675.05
#Sta/Elev= 30
  4140.0  513.33  4388.8  506.22  4401.9  503.80  4421.3  504.16  4426.5  498.39
  4433.4  503.76  4485.7  502.28  4500.8  499.49  4517.2  497.07  4524.0  497.64
  4529.2  499.78  4578.2  499.96  4626.7  501.30  4866.8  498.62  4936.3  498.50
  4967.7  495.45  4988.5  495.43  4997.5  491.12  4998.0  490.32  5003.2  490.32
  5003.7  491.12  5019.6  493.77  5030.0  494.51  5040.4  496.62  5065.5  498.39
  5074.9  499.68  5092.2  499.13  5157.1  501.59  5302.9  505.69  5548.3  510.22
#Mann=7,-1,0
  4140.0    0.05       0  4500.8    0.16       0  4578.2    0.05       0
  4866.8    0.16       0  4997.5    0.07       0  5003.7    0.16       0
  5157.1    0.05       0
Bank Sta=4426.5,5065.5
Exp/Cntr=0.3,0.1

Type RM Length L Ch R = 1,18665,1130,1130,1130
BEGIN DESCRIPTION:
UNT 055 in LFCCL Watershed 26.0
END DESCRIPTION:
XS GIS Cut Line= 3
      2818375.04      7081524.99      2817675.00      7081675.00
      2817425.00      7082425.00
#Sta/Elev= 30
  4296.2  510.53  4563.0  500.65  4981.5  495.85  4984.1  494.72  4992.5  492.57
  4998.6  487.23  4999.1  486.43  5005.2  487.23  5009.6  491.72  5035.5  493.54
  5054.3  492.33  5107.0  493.48  5128.1  496.69  5143.9  496.65  5201.9  494.11
  5223.0  491.38  5231.9  494.72  5246.3  498.83  5338.9  501.68  5360.0  504.53
  5381.1  502.11  5402.1  501.89  5433.8  502.72  5444.3  504.93  5466.5  502.37
  5519.1  501.85  5634.0  501.85  5707.8  504.82  5750.0  509.74  5802.7  510.50
#Mann=8,-1,0
  4296.2    0.05       0  4998.6    0.03       0  5005.2    0.05       0
  5035.5    0.07       0  5143.9    0.16       0  5246.3    0.05       0
  5466.5    0.16       0  5519.1    0.05       0
Bank Sta=4984.1,5231.9
Exp/Cntr=0.3,0.1

Type RM Length L Ch R = 1,17535,110,110,110
BEGIN DESCRIPTION:
XS3381A
END DESCRIPTION:
XS GIS Cut Line= 5
      2817490.13      7080465.50      2817405.53      7081094.00
      2817369.27      7081150.40      2817361.21      7081251.11
      2817240.37      7081666.02
#Sta/Elev= 30
  4357.2  497.54  4628.3  494.62  4740.1  493.95  4851.1  491.61  4879.6  492.13
  4901.6  491.54  4972.2  492.58  4982.3  492.03  4989.4  489.20  4994.9  489.20
  4996.7  485.77  4997.2  484.97  5002.9  484.97  5003.4  485.77  5015.2  489.67
  5028.2  491.00  5093.1  491.14  5109.2  489.47  5113.2  488.82  5133.3  490.16
  5173.9  491.43  5194.5  488.34  5199.8  491.65  5208.7  491.19  5226.0  492.11
  5249.1  494.62  5298.9  496.68  5403.1  498.11  5455.1  499.62  5591.6  500.56
#Mann=5,-1,0
  4357.2    0.05       0  4996.7    0.04       0  5003.4    0.05       0
  5109.2    0.08       0  5208.7    0.05       0
Bank Sta=4628.3,5249.1
Exp/Cntr=0.3,0.1

Type RM Length L Ch R = 1,17425,769,769,769
BEGIN DESCRIPTION:
XS3382A
END DESCRIPTION:
XS GIS Cut Line= 4
      2817345.10      7080372.88      2817300.78      7081073.86
      2817252.44      7081327.65      2817159.93      7081709.77
#Sta/Elev= 30
  4318.4  498.97  4370.6  496.17  4429.0  494.54  4559.3  493.18  4731.5  493.50
  4861.6  494.49  4921.7  490.79  4941.8  490.37  4971.8  492.45  4991.9  489.40
  4998.5  485.07  4999.0  484.27  5004.7  484.27  5005.2  485.07  5018.8  491.16
  5055.7  491.86  5078.2  491.99  5093.2  493.37  5132.5  494.54  5136.2  494.67
  5247.2  498.26  5297.0  500.24  5307.3  499.40  5317.6  497.16  5347.0  498.80
  5399.9  501.03  5416.2  500.19  5463.1  501.27  5583.5  501.38  5672.3  503.23
#Mann=9,-1,0
  4318.4    0.08       0  4559.3    0.05       0  4731.5    0.16       0
  4998.5    0.07       0  5005.2    0.16       0  5055.7    0.05       0
  5136.2    0.16       0  5247.2    0.08       0  5347.0    0.05       0
Bank Sta=4429,5132.5
Exp/Cntr=0.3,0.1

Type RM Length L Ch R = 1,16656,423,423,423
BEGIN DESCRIPTION:
UNT 055 in LFCCL Watershed 23.0
END DESCRIPTION:
XS GIS Cut Line= 3
      2817345.09      7080260.10      2816897.93      7080852.28
      2816733.01      7081270.61
#Sta/Elev= 30
  4249.9  501.81  4273.4  501.33  4374.8  497.17  4424.7  496.61  4439.3  494.46
  4472.0  493.04  4560.0  491.64  4685.1  493.08  4745.3  492.10  4782.4  493.11
  4805.6  492.82  4853.5  491.94  4874.3  489.91  4903.4  491.74  4953.4  489.05
  4977.7  489.25  4982.5  489.07  4991.9  485.70  4996.1  485.70  5002.3  482.96
  5002.8  482.16  5009.0  482.96  5012.3  484.60  5017.6  490.65  5024.0  493.04
  5036.7  495.02  5120.5  497.45  5234.2  497.31  5396.6  499.41  5441.6  501.15
#Mann=8,-1,0
  4249.9    0.08       0  4273.4    0.16       0  4685.1    0.12       0
  4782.4    0.16       0  4805.6    0.12       0  4977.7    0.16       0
  5002.3    0.07       0  5009.0    0.16       0
Bank Sta=4472,5024
Exp/Cntr=0.3,0.1

Type RM Length L Ch R = 1,16233,849,849,849
BEGIN DESCRIPTION:
UNT 055 in LFCCL Watershed 22.0
END DESCRIPTION:
XS GIS Cut Line= 3
      2817474.99      7079825.00      2816675.00      7080525.00
      2816375.00      7081324.99
#Sta/Elev= 30
  3962.1  504.80  3989.6  503.76  4061.3  501.64  4075.5  503.97  4143.1  502.17
  4288.1  496.63  4302.4  495.79  4309.0  492.57  4316.6  492.21  4323.2  490.42
  4359.3  489.88  4411.9  493.14  4546.3  492.60  4554.2  492.45  4664.0  490.66
  4712.3  486.90  4727.6  487.40  4756.0  492.37  4830.8  490.10  4975.3  491.62
  4989.5  488.54  5000.4  483.06  5000.9  482.26  5007.1  483.06  5021.8  488.91
  5166.1  492.21  5271.6  497.56  5467.4  501.82  5693.5  501.57  5879.5  504.28
#Mann=10,-1,0
  3962.1    0.05       0  3989.6    0.08       0  4143.1    0.16       0
  4411.9    0.12       0  4546.3    0.16       0  4554.2    0.12       0
  4712.3    0.16       0  4830.8    0.12       0  5000.4    0.07       0
  5007.1    0.16       0
Bank Sta=4316.6,5166.1
Exp/Cntr=0.3,0.1

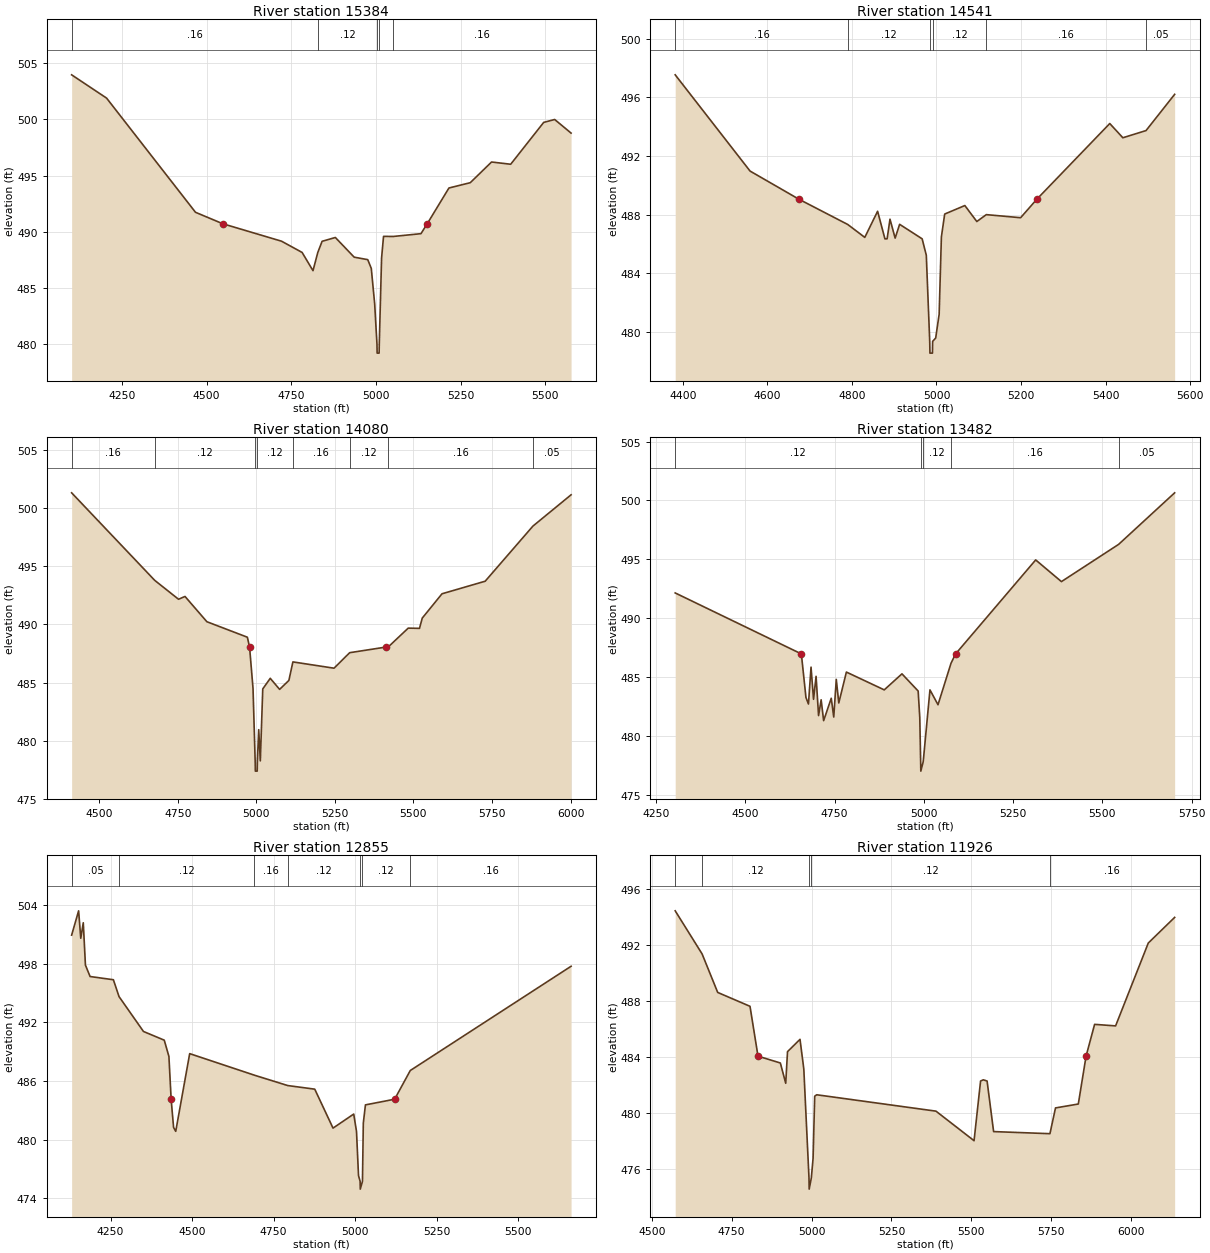
Type RM Length L Ch R = 1,15384,843,843,843
BEGIN DESCRIPTION:
XS3383A
END DESCRIPTION:
XS GIS Cut Line= 4
      2817324.96      7079788.74      2816607.87      7079974.06
      2816571.62      7080151.32      2816406.43      7080679.10
#Sta/Elev= 30
  4101.4  503.96  4204.6  501.89  4467.1  491.74  4547.8  490.72  4721.1  489.17
  4781.9  488.17  4814.0  486.55  4828.2  488.17  4840.9  489.16  4880.0  489.50
  4935.6  487.75  4975.7  487.53  4986.1  486.75  4996.1  483.61  5002.9  480.02
  5003.4  479.22  5009.2  479.22  5009.7  480.02  5016.5  487.67  5022.3  489.60
  5050.7  489.59  5132.8  489.84  5151.3  490.72  5215.4  493.90  5278.3  494.37
  5341.2  496.21  5397.7  496.01  5495.1  499.73  5527.6  499.99  5576.0  498.78
#Mann=5,-1,0
  4101.4    0.16       0  4828.2    0.12       0  5002.9    0.07       0
  5009.7    0.12       0  5050.7    0.16       0
Bank Sta=4547.8,5151.3
Exp/Cntr=0.3,0.1

Type RM Length L Ch R = 1,14541,461,461,461
BEGIN DESCRIPTION:
XS3384A
END DESCRIPTION:
XS GIS Cut Line= 4
      2817071.13      7079732.35      2816575.64      7079784.72
      2816390.33      7079716.23      2815968.63      7079957.20
#Sta/Elev= 30
  4381.9  497.54  4559.0  490.98  4674.0  489.07  4790.0  487.34  4830.4  486.46
  4860.7  488.24  4878.0  486.36  4883.2  486.36  4890.0  487.70  4902.2  486.41
  4912.8  487.35  4966.1  486.36  4975.9  485.24  4984.0  479.37  4984.5  478.57
  4990.4  478.57  4990.9  479.37  4998.1  479.60  5006.3  481.22  5011.6  486.49
  5019.4  488.05  5067.1  488.63  5095.4  487.54  5117.9  488.01  5199.0  487.80
  5237.7  489.07  5409.9  494.22  5440.9  493.25  5495.7  493.74  5563.4  496.21
#Mann=6,-1,0
  4381.9    0.16       0  4790.0    0.12       0  4984.0    0.07       0
  4990.9    0.12       0  5117.9    0.16       0  5495.7    0.05       0
Bank Sta=4674,5237.7
Exp/Cntr=0.3,0.1

Type RM Length L Ch R = 1,14080,598,598,598
BEGIN DESCRIPTION:
UNT 055 in LFCCL Watershed 19.0
END DESCRIPTION:
XS GIS Cut Line= 3
      2817175.01      7079625.00      2816575.00      7079475.00
      2815775.00      7080025.00
#Sta/Elev= 30
  4412.5  501.29  4677.0  493.77  4752.7  492.15  4773.3  492.39  4842.9  490.22
  4971.7  488.89  4978.7  488.04  4989.7  484.49  4996.6  478.19  4997.1  477.39
  5003.0  477.39  5003.5  478.19  5007.8  480.95  5012.9  478.27  5020.7  484.45
  5044.5  485.36  5074.3  484.41  5103.8  485.18  5116.6  486.77  5247.5  486.23
  5297.2  487.56  5411.8  488.04  5419.4  488.04  5483.6  489.67  5519.4  489.65
  5528.2  490.53  5591.1  492.62  5728.5  493.70  5880.3  498.43  6001.8  501.12
#Mann=8,-1,0
  4412.5    0.16       0  4677.0    0.12       0  4996.6    0.07       0
  5003.5    0.12       0  5116.6    0.16       0  5297.2    0.12       0
  5419.4    0.16       0  5880.3    0.05       0
Bank Sta=4978.7,5411.8
Exp/Cntr=0.3,0.1

Type RM Length L Ch R = 1,13482,627,627,627
BEGIN DESCRIPTION:
UNT 055 in LFCCL Watershed 18.0
END DESCRIPTION:
XS GIS Cut Line= 3
      2816648.13      7078890.41      2816175.00      7079375.00
      2815774.98      7079975.03
#Sta/Elev= 30
  4304.0  492.16  4657.2  486.99  4670.1  483.29  4677.1  482.74  4684.3  485.87
  4691.3  483.14  4698.4  485.09  4705.4  481.76  4712.6  483.10  4719.6  481.33
  4740.9  483.23  4747.9  481.64  4755.0  484.83  4762.0  482.83  4783.3  485.45
  4889.3  483.94  4938.9  485.30  4984.3  483.84  4988.8  481.56  4991.2  477.85
  4991.7  477.05  4998.4  477.85  5017.3  483.94  5039.8  482.68  5076.4  486.21
  5089.1  486.99  5313.3  494.96  5385.4  493.12  5545.6  496.28  5702.4  500.65
#Mann=5,-1,0
  4304.0    0.12       0  4991.2    0.07       0  4998.4    0.12       0
  5076.4    0.16       0  5545.6    0.05       0
Bank Sta=4657.2,5089.1
Exp/Cntr=0.3,0.1

Type RM Length L Ch R = 1,12855,929,929,929
BEGIN DESCRIPTION:
UNT 055 in LFCCL Watershed 17.0
END DESCRIPTION:
XS GIS Cut Line= 3
      2816625.00      7078475.00      2815975.00      7079025.00
      2815575.03      7079574.96
#Sta/Elev= 30
  4130.7  500.95  4152.1  503.44  4158.7  500.63  4166.4  502.22  4173.0  497.88
  4187.3  496.71  4258.7  496.38  4276.1  494.65  4351.0  491.08  4414.7  490.19
  4429.0  488.52  4435.8  484.14  4443.3  481.25  4449.9  480.85  4492.7  488.81
  4691.4  486.60  4793.3  485.54  4876.2  485.17  4932.2  481.18  4995.7  482.62
  5004.2  480.85  5010.4  476.31  5015.3  475.73  5015.8  474.93  5022.5  475.73
  5025.1  481.69  5031.6  483.56  5121.2  484.14  5169.1  487.08  5662.2  497.76
#Mann=7,-1,0
  4130.7    0.05       0  4276.1    0.12       0  4691.4    0.16       0
  4793.3    0.12       0  5015.3    0.07       0  5022.5    0.12       0
  5169.1    0.16       0
Bank Sta=4435.8,5121.2
Exp/Cntr=0.3,0.1

Type RM Length L Ch R = 1,11926,1137,1137,1137
BEGIN DESCRIPTION:
XS3385A
END DESCRIPTION:
XS GIS Cut Line= 6
      2816499.05      7078535.86      2816362.13      7078535.86
      2816128.47      7078419.04      2815902.88      7078362.64
      2815777.99      7078443.21      2815009.28      7078596.14
#Sta/Elev= 30
  4573.3  494.41  4657.5  491.33  4706.3  488.58  4807.4  487.59  4832.4  484.03
  4902.4  483.54  4919.2  482.09  4924.8  484.35  4963.9  485.23  4975.8  483.11
  4992.0  475.33  4992.6  474.53  4999.3  475.33  5004.8  476.73  5009.9  481.17
  5016.3  481.27  5389.4  480.10  5508.6  477.99  5529.0  482.25  5537.6  482.34
  5549.4  482.25  5569.8  478.64  5746.1  478.49  5763.5  480.33  5834.9  480.61
  5859.2  484.03  5885.9  486.30  5951.6  486.19  6053.9  492.11  6136.4  493.94
#Mann=5,-1,0
  4573.3    0.05       0  4657.5    0.12       0  4992.0    0.07       0
  4999.3    0.12       0  5746.1    0.16       0
Bank Sta=4832.4,5859.2
Exp/Cntr=0.3,0.1

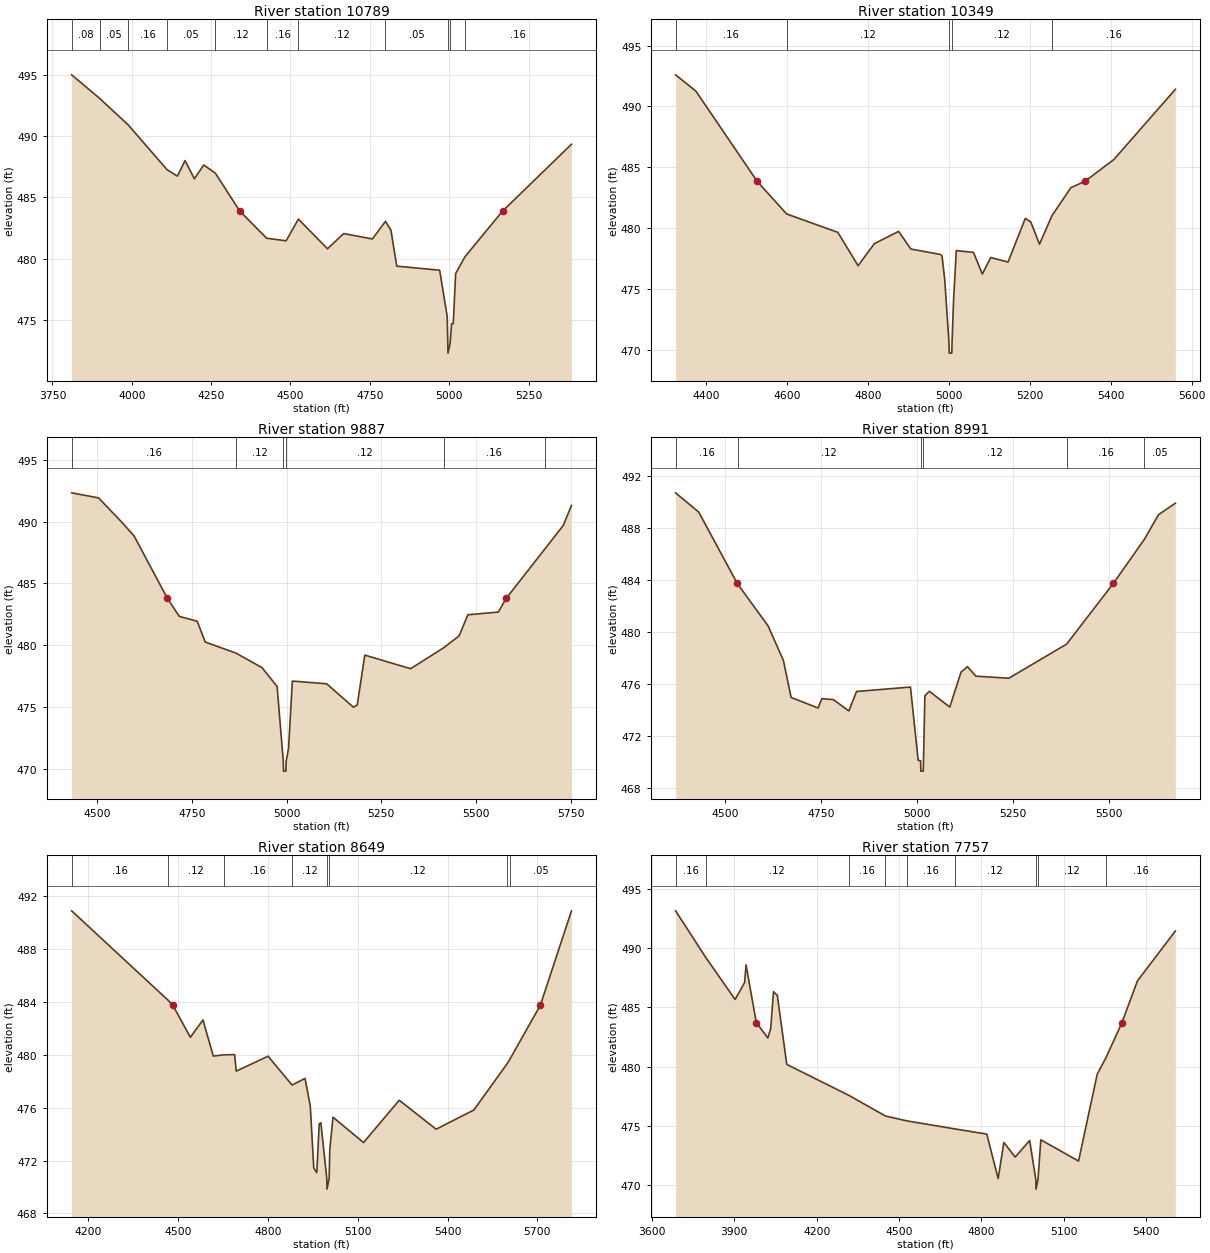
Type RM Length L Ch R = 1,10789,440,440,440
BEGIN DESCRIPTION:
XS3386A
END DESCRIPTION:
XS GIS Cut Line= 6
      2816466.84      7078406.94      2815955.25      7078197.47
      2815838.42      7078189.41      2815584.62      7078241.78
      2815334.85      7078346.52      2814964.23      7078402.92
#Sta/Elev= 30
  3810.5  495.00  3898.9  493.07  3989.1  490.90  4111.0  487.26  4143.8  486.73
  4167.8  488.00  4197.2  486.51  4226.6  487.64  4263.0  486.98  4340.5  483.87
  4424.8  481.66  4486.2  481.45  4525.0  483.22  4616.7  480.80  4667.7  482.04
  4758.1  481.60  4799.3  483.04  4816.5  482.32  4834.9  479.38  4970.0  479.05
  4993.8  475.28  4995.7  473.08  4996.3  472.28  5003.1  473.08  5007.6  474.69
  5012.9  474.69  5020.4  478.77  5049.9  480.15  5168.1  483.87  5385.3  489.33
#Mann=11,-1,0
  3810.5    0.08       0  3898.9    0.05       0  3989.1    0.16       0
  4111.0    0.05       0  4263.0    0.12       0  4424.8    0.16       0
  4525.0    0.12       0  4799.3    0.05       0  4995.7    0.04       0
  5003.1    0.05       0  5049.9    0.16       0
Bank Sta=4340.5,5168.1
Exp/Cntr=0.3,0.1

Type RM Length L Ch R = 1,10349,462,462,462
BEGIN DESCRIPTION:
UNT 055 in LFCCL Watershed 14.0
END DESCRIPTION:
XS GIS Cut Line= 3
      2815925.01      7077925.00      2815275.00      7077975.00
      2814836.80      7078361.32
#Sta/Elev= 30
  4323.7  492.59  4373.9  491.25  4525.5  483.83  4598.4  481.15  4724.9  479.64
  4775.0  476.90  4815.2  478.71  4875.3  479.72  4905.4  478.27  4979.0  477.82
  4982.7  477.69  4989.4  475.72  4999.9  470.51  5000.5  469.71  5006.8  469.71
  5007.3  470.51  5011.2  474.08  5017.9  478.14  5060.5  477.99  5082.3  476.21
  5103.2  477.57  5145.9  477.20  5188.6  480.79  5202.3  480.48  5223.7  478.67
  5254.7  481.02  5301.5  483.32  5336.1  483.83  5407.7  485.63  5559.8  491.40
#Mann=5,-1,0
  4323.7    0.16       0  4598.4    0.12       0  4999.9    0.07       0
  5007.3    0.12       0  5254.7    0.16       0
Bank Sta=4525.5,5336.1
Exp/Cntr=0.3,0.1

Type RM Length L Ch R = 1,9887,896,896,896
BEGIN DESCRIPTION:
XS3387A
END DESCRIPTION:
XS GIS Cut Line= 3
      2815858.53      7077802.65      2815354.99      7077629.44
      2814573.44      7077726.13
#Sta/Elev= 30
  4432.2  492.33  4503.3  491.92  4565.7  489.92  4597.0  488.85  4685.2  483.79
  4716.6  482.34  4763.8  481.95  4784.9  480.27  4867.0  479.36  4935.2  478.19
  4974.8  476.67  4991.2  470.63  4991.8  469.83  4998.1  469.83  4998.7  470.63
  5005.0  471.65  5015.1  477.11  5105.8  476.89  5176.3  475.00  5186.4  475.17
  5206.5  479.21  5327.4  478.11  5414.6  479.80  5455.7  480.77  5478.6  482.47
  5559.2  482.69  5579.7  483.79  5682.5  487.81  5730.5  489.69  5752.2  491.31
#Mann=6,-1,0
  4432.2    0.16       0  4867.0    0.12       0  4991.2    0.07       0
  4998.7    0.12       0  5414.6    0.16       0  5682.5    0.05       0
Bank Sta=4685.2,5579.7
Exp/Cntr=0.3,0.1

Type RM Length L Ch R = 1,8991,342,342,342
BEGIN DESCRIPTION:
UNT 055 in LFCCL Watershed 12.0
END DESCRIPTION:
XS GIS Cut Line= 3
      2815775.02      7077125.00      2815125.00      7077175.00
      2814525.03      7077424.99
#Sta/Elev= 30
  4370.5  490.72  4430.7  489.24  4531.0  483.75  4532.7  483.68  4611.2  480.49
  4651.3  477.82  4671.4  474.97  4741.6  474.16  4751.6  474.88  4781.7  474.80
  4821.8  473.93  4841.9  475.43  4982.3  475.77  5002.4  470.13  5008.7  470.10
  5009.3  469.30  5015.6  469.30  5016.2  470.10  5019.9  475.11  5031.6  475.44
  5084.7  474.23  5114.0  476.92  5130.8  477.34  5152.4  476.61  5238.6  476.45
  5389.2  479.08  5510.9  483.75  5591.3  487.13  5628.6  489.04  5672.4  489.92
#Mann=6,-1,0
  4370.5    0.16       0  4532.7    0.12       0  5008.7    0.07       0
  5016.2    0.12       0  5389.2    0.16       0  5591.3    0.05       0
Bank Sta=4531,5510.9
Exp/Cntr=0.3,0.1

Type RM Length L Ch R = 1,8649,892,892,892
BEGIN DESCRIPTION:
UNT 055 in LFCCL Watershed 11.0
END DESCRIPTION:
XS GIS Cut Line= 3
      2815999.55      7076537.70      2815101.19      7076916.38
      2814424.96      7077075.01
#Sta/Elev= 30
  4144.3  490.88  4465.0  484.15  4482.2  483.74  4540.9  481.32  4582.9  482.63
  4617.5  479.90  4651.8  479.99  4688.6  480.01  4694.1  478.76  4800.4  479.89
  4880.5  477.71  4923.9  478.21  4941.4  476.13  4953.0  471.44  4963.1  471.09
  4971.3  474.78  4976.7  474.86  4996.6  470.64  4997.2  469.84  5004.4  470.64
  5006.6  472.86  5017.4  475.28  5119.2  473.36  5238.6  476.56  5361.8  474.37
  5487.8  475.82  5599.6  479.34  5608.4  479.67  5709.9  483.74  5813.8  490.87
#Mann=8,-1,0
  4144.3    0.16       0  4465.0    0.12       0  4651.8    0.16       0
  4880.5    0.12       0  4996.6    0.07       0  5004.4    0.12       0
  5599.6    0.16       0  5608.4    0.05       0
Bank Sta=4482.2,5709.9
Exp/Cntr=0.3,0.1

Type RM Length L Ch R = 1,7757,843,843,843
BEGIN DESCRIPTION:
UNT 055 in LFCCL Watershed 10.0
END DESCRIPTION:
XS GIS Cut Line= 3
      2815959.23      7076142.91      2814718.48      7076481.30
      2814202.85      7076626.32
#Sta/Elev= 30
  3685.9  493.17  3795.2  489.25  3902.8  485.68  3937.4  487.11  3942.6  488.60
  3980.0  483.73  4022.0  482.43  4032.3  483.19  4042.7  486.33  4056.6  486.03
  4091.1  480.19  4317.8  477.57  4450.6  475.83  4530.5  475.41  4703.8  474.74
  4820.1  474.30  4861.6  470.54  4882.3  473.59  4923.7  472.36  4976.4  473.76
  4998.9  470.45  4999.5  469.65  5006.8  470.45  5017.1  473.82  5154.6  472.02
  5222.7  479.37  5254.6  480.76  5313.0  483.73  5369.3  487.25  5507.6  491.47
#Mann=9,-1,0
  3685.9    0.16       0  3795.2    0.12       0  4317.8    0.16       0
  4450.6    0.12       0  4530.5    0.16       0  4703.8    0.12       0
  4998.9    0.07       0  5006.8    0.12       0  5254.6    0.16       0
Bank Sta=3980,5313
Exp/Cntr=0.3,0.1

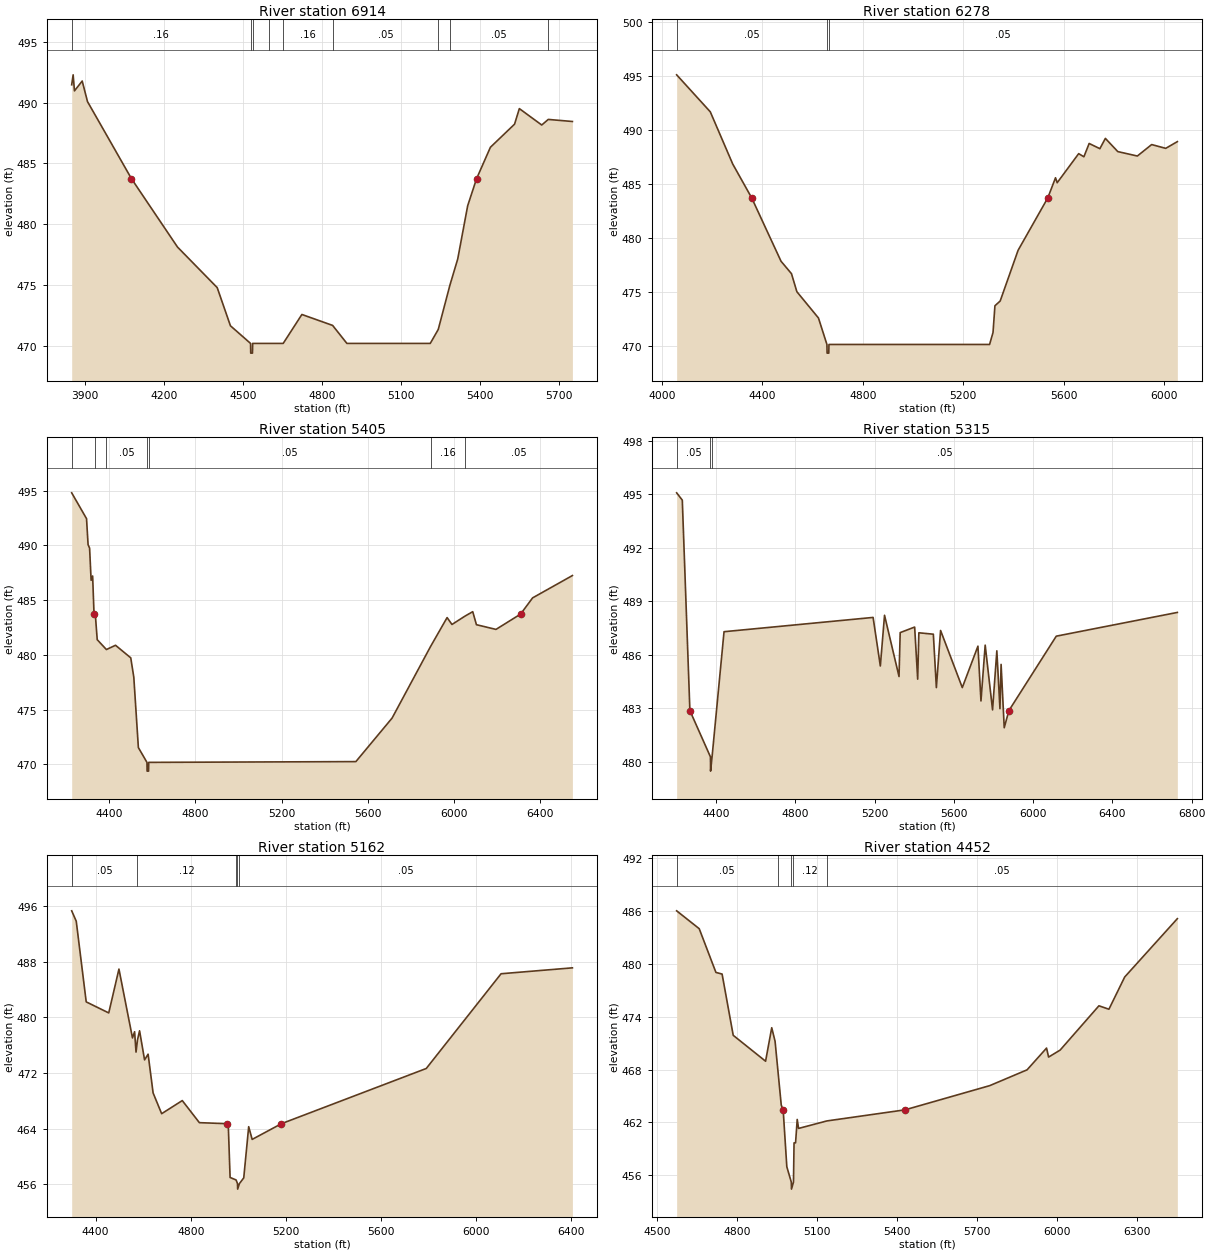
Type RM Length L Ch R = 1,6914,636,636,636
BEGIN DESCRIPTION:
XS3388A
END DESCRIPTION:
XS GIS Cut Line= 3
      2815874.69      7075639.33      2814754.74      7075760.19
      2814025.56      7076026.08
#Sta/Elev= 30
  3848.5  491.46  3854.0  492.28  3859.0  490.96  3888.4  491.77  3908.5  490.08
  4075.7  483.73  4250.5  478.11  4401.4  474.77  4451.7  471.63  4528.1  470.18
  4528.8  469.38  4535.4  469.38  4536.1  470.18  4599.3  470.18  4652.2  470.18
  4723.2  472.56  4840.0  471.66  4894.2  470.18  5211.0  470.18  5241.4  471.33
  5285.9  474.99  5315.3  477.12  5353.2  481.51  5386.9  483.73  5439.6  486.32
  5531.3  488.22  5549.5  489.50  5634.6  488.15  5659.4  488.61  5751.1  488.44
#Mann=9,-1,0
  3848.5    0.16       0  4528.1   0.033       0  4536.1    0.16       0
  4599.3    0.05       0  4652.2    0.16       0  4840.0    0.05       0
  5241.4    0.12       0  5285.9    0.05       0  5659.4    0.16       0
Bank Sta=4075.7,5386.9
Exp/Cntr=0.3,0.1

Type RM Length L Ch R = 1,6278,873,873,873
BEGIN DESCRIPTION:
XS3389A
END DESCRIPTION:
XS GIS Cut Line= 3
      2815560.45      7074789.31      2814690.28      7075131.73
      2813889.32      7075824.02
#Sta/Elev= 30
  4058.9  495.12  4192.8  491.70  4282.2  486.87  4357.9  483.73  4474.5  477.88
  4516.1  476.73  4537.6  475.06  4623.6  472.63  4657.3  470.18  4658.0  469.38
  4664.7  469.38  4665.4  470.18  5305.0  470.18  5318.7  471.29  5326.3  473.76
  5347.2  474.20  5418.5  478.89  5536.6  483.73  5567.6  485.60  5574.2  485.14
  5659.8  487.83  5680.6  487.54  5701.5  488.77  5744.2  488.29  5766.1  489.24
  5815.5  488.02  5893.4  487.61  5950.4  488.67  6006.4  488.32  6052.7  488.94
#Mann=3,-1,0
  4058.9    0.05       0  4657.3   0.033       0  4665.4    0.05       0
Bank Sta=4357.9,5536.6
Exp/Cntr=0.3,0.1

Type RM Length L Ch R = 1,5405,90,90,90
BEGIN DESCRIPTION:
XS3390A
END DESCRIPTION:
XS GIS Cut Line= 5
      2814823.20      7073725.78      2814577.48      7073967.48
      2814323.68      7074374.36      2814009.45      7074877.93
      2813619.35      7075694.33
#Sta/Elev= 30
  4226.8  494.81  4295.6  492.45  4302.8  490.07  4309.8  489.76  4316.9  486.82
  4323.9  487.21  4330.4  483.73  4336.8  483.58  4345.2  481.39  4387.8  480.49
  4430.1  480.88  4500.8  479.73  4514.9  477.96  4536.1  471.53  4575.9  470.18
  4576.6  469.38  4583.4  469.38  4584.1  470.18  5545.0  470.25  5713.1  474.23
  5891.5  480.77  5968.2  483.41  5990.8  482.78  6050.9  483.54  6087.1  483.95
  6104.2  482.76  6195.0  482.33  6309.1  483.73  6364.8  485.21  6549.4  487.25
#Mann=7,-1,0
  4226.8    0.05       0  4336.8    0.08       0  4387.8    0.05       0
  4575.9   0.033       0  4584.1    0.05       0  5891.5    0.16       0
  6050.9    0.05       0
Bank Sta=4330.4,6309.1
Exp/Cntr=0.3,0.1

Type RM Length L Ch R = 1,5315,153,153,153
BEGIN DESCRIPTION:
XS3391A
END DESCRIPTION:
XS GIS Cut Line= 6
      2814730.55      7073560.62      2814593.59      7073786.19
      2814553.31      7073870.79      2814307.57      7074269.62
      2813920.83      7074885.99      2813433.37      7075727.95
#Sta/Elev= 30
  4201.3  495.08  4229.8  494.67  4268.1  482.88  4371.8  480.29  4372.5  479.49
  4380.0  480.29  4440.4  487.30  5192.6  488.10  5229.1  485.38  5250.3  488.22
  5323.4  484.79  5329.3  487.25  5402.3  487.56  5417.6  484.64  5423.5  487.24
  5496.6  487.16  5511.9  484.17  5533.1  487.37  5642.7  484.17  5721.6  486.49
  5736.9  483.42  5758.2  486.55  5795.4  482.92  5817.0  486.23  5832.7  482.99
  5838.5  485.47  5854.3  481.92  5877.9  482.88  6116.9  487.05  6727.9  488.38
#Mann=3,-1,0
  4201.3    0.05       0  4371.8    0.03       0  4380.0    0.05       0
Bank Sta=4268.1,5877.9
Exp/Cntr=0.3,0.1

Type RM Length L Ch R = 1,5162,710,710,710
BEGIN DESCRIPTION:
XS3392A
END DESCRIPTION:
XS GIS Cut Line= 4
      2814682.24      7073536.40      2814327.71      7074056.11
      2814235.05      7074132.65      2813559.12      7075307.49
#Sta/Elev= 30
  4299.6  495.35  4318.7  493.86  4360.6  482.24  4455.3  480.65  4498.2  486.96
  4555.1  477.05  4564.0  477.94  4570.0  475.01  4576.1  476.75  4584.9  478.08
  4605.9  473.89  4620.8  474.71  4641.8  469.13  4677.7  466.14  4764.4  468.03
  4836.3  464.85  4954.4  464.70  4958.2  464.11  4965.4  456.96  4990.6  456.60
  4996.5  456.08  4997.2  455.28  5004.7  456.08  5022.8  456.90  5043.6  464.27
  5058.2  462.44  5181.1  464.70  5790.0  472.65  6104.5  486.29  6404.3  487.14
#Mann=5,-1,0
  4299.6    0.05       0  4576.1    0.12       0  4990.6    0.05       0
  4996.5    0.03       0  5004.7    0.05       0
Bank Sta=4954.4,5181.1
Exp/Cntr=0.3,0.1

Type RM Length L Ch R = 1,4452,656,656,656
BEGIN DESCRIPTION:
XS3394A
END DESCRIPTION:
XS GIS Cut Line= 4
      2814383.12      7073336.18      2814122.68      7073695.58
      2813982.06      7074325.79      2813592.36      7075011.66
#Sta/Elev= 30
  4574.6  486.02  4659.3  483.99  4721.9  479.03  4745.1  478.84  4786.8  471.89
  4908.2  468.95  4931.3  472.75  4943.8  471.22  4954.3  467.94  4967.0  463.97
  4974.2  463.43  4987.9  456.97  5004.7  455.23  5005.4  454.43  5012.9  455.23
  5015.0  459.68  5020.7  459.68  5026.9  462.34  5032.0  461.32  5138.1  462.17
  5431.4  463.43  5749.4  466.18  5889.2  467.97  5962.3  470.44  5970.0  469.42
  6013.2  470.21  6158.8  475.24  6196.3  474.85  6255.5  478.51  6453.0  485.13
#Mann=5,-1,0
  4574.6    0.05       0  4954.3    0.12       0  5004.7    0.07       0
  5012.9    0.12       0  5138.1    0.05       0
Bank Sta=4974.2,5431.4
Exp/Cntr=0.3,0.1