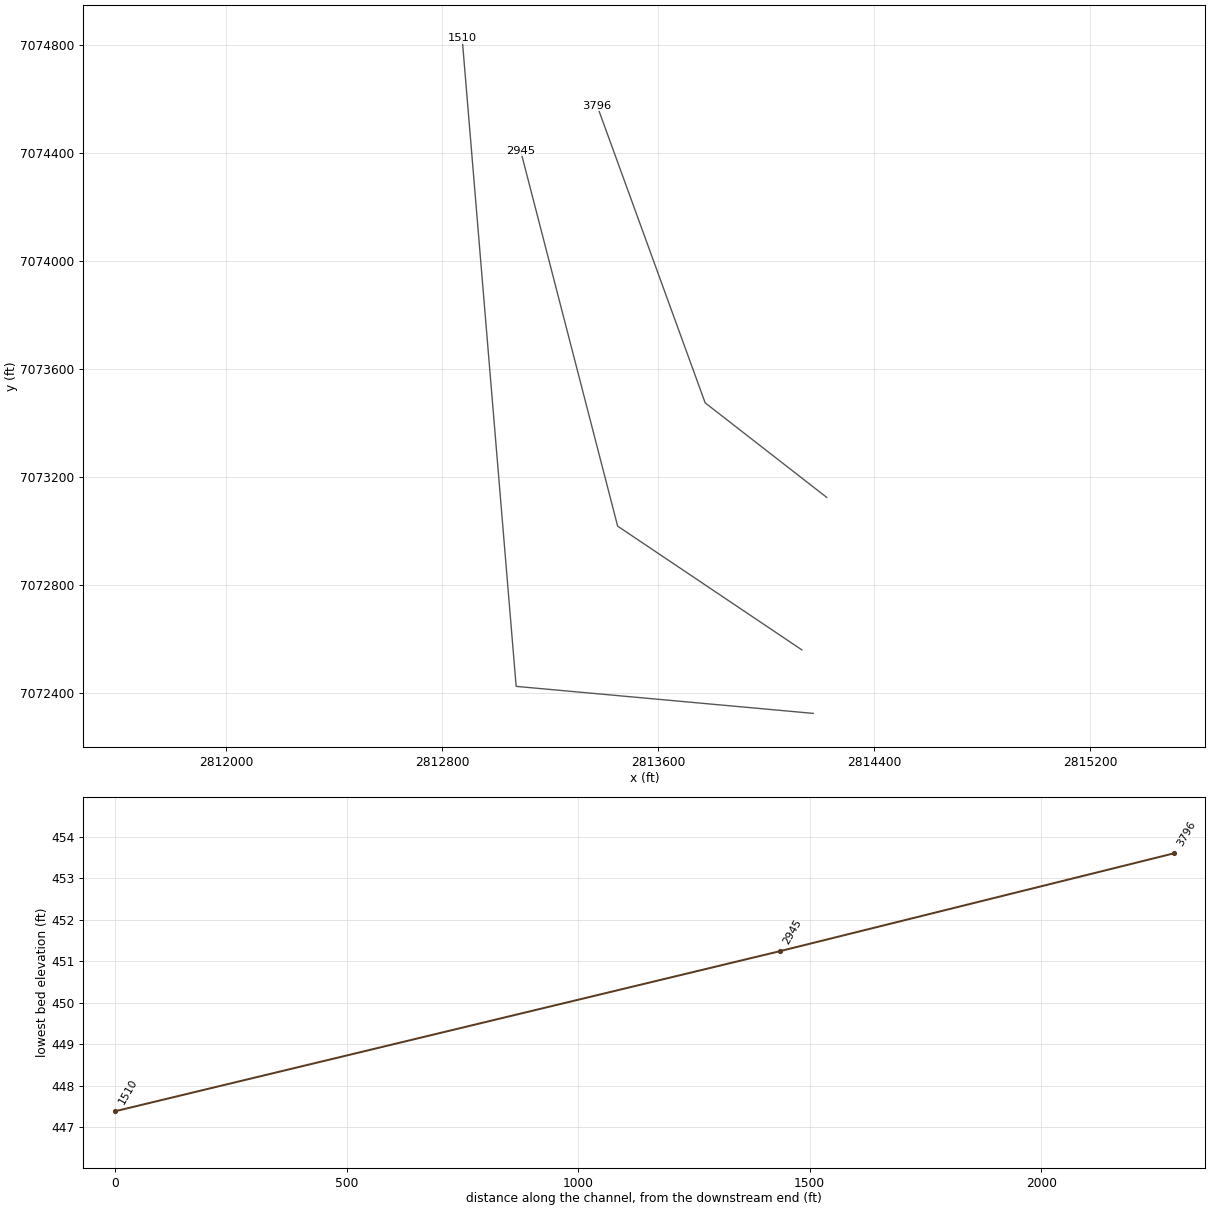
HEC-RAS study UNT 055 in LFCCL Watershed.prj: UNT 055 in LFCCL Watershed Base Level Engineering

--- UNT 055 in LFCCL Watershed.g01 (geometry) --- (continued)

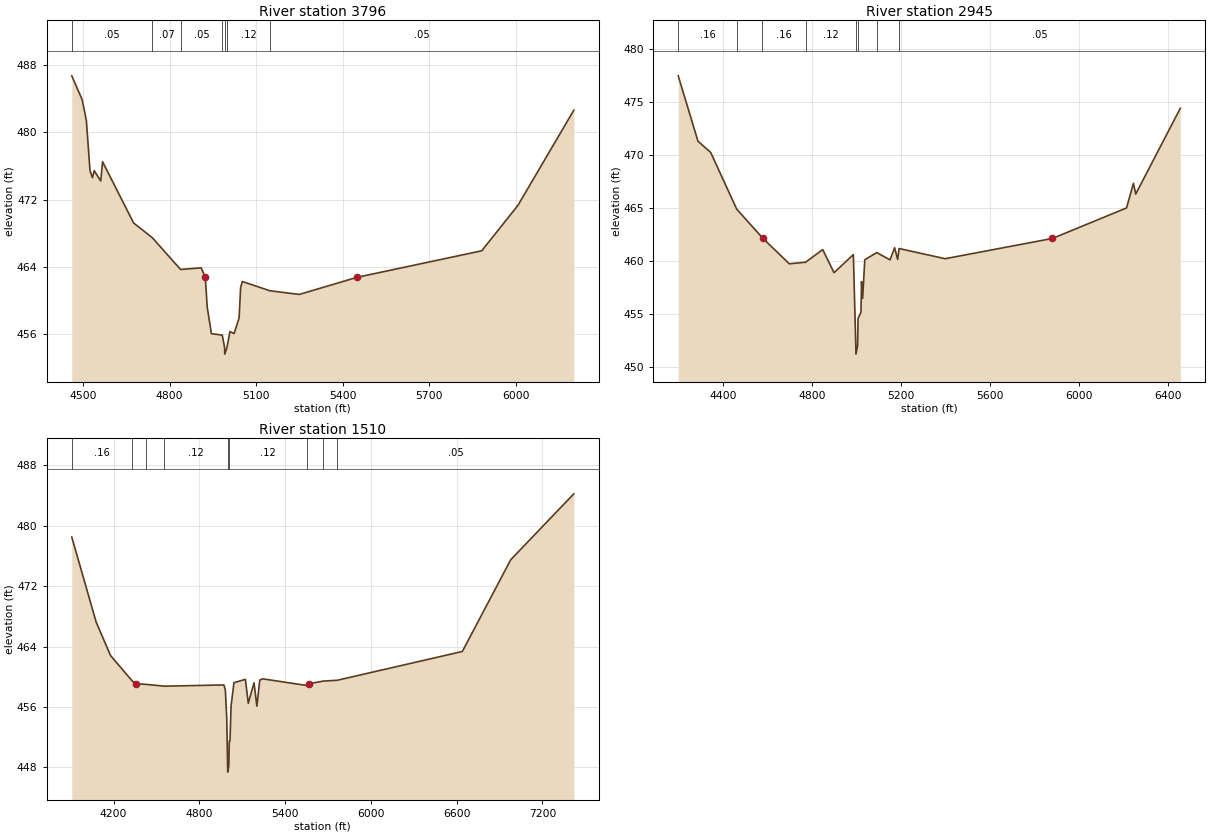
Type RM Length L Ch R = 1,3796,851,851,851
BEGIN DESCRIPTION:
UNT 055 in LFCCL Watershed 3.0
END DESCRIPTION:
XS GIS Cut Line= 3
      2814225.00      7073125.00      2813775.00      7073475.00
      2813374.99      7074575.04
#Sta/Elev= 30
  4460.6  486.75  4496.8  483.90  4511.3  481.40  4523.9  475.44  4532.1  474.62
  4538.4  475.45  4561.0  474.22  4567.4  476.51  4675.1  469.22  4739.8  467.47
  4837.8  463.68  4909.4  463.88  4923.6  462.74  4930.2  459.18  4944.7  456.04
  4982.5  455.86  4990.3  454.40  4991.0  453.60  4998.6  454.40  5009.0  456.29
  5023.4  456.05  5040.7  457.91  5046.0  461.53  5052.0  462.25  5147.2  461.15
  5249.5  460.71  5448.5  462.74  5881.9  465.91  6007.6  471.33  6201.2  482.66
#Mann=7,-1,0
  4460.6    0.05       0  4739.8    0.07       0  4837.8    0.05       0
  4982.5    0.12       0  4990.3    0.07       0  4998.6    0.12       0
  5147.2    0.05       0
Bank Sta=4923.6,5448.5
Exp/Cntr=0.3,0.1

Type RM Length L Ch R = 1,2945,1435,1435,1435
BEGIN DESCRIPTION:
XS3393A
END DESCRIPTION:
XS GIS Cut Line= 3
      2814133.08      7072560.18      2813450.81      7073018.50
      2813091.44      7074409.10
#Sta/Elev= 30
  4199.4  477.49  4288.1  471.33  4345.1  470.27  4462.6  464.91  4575.2  462.28
  4580.6  462.15  4699.1  459.76  4772.1  459.91  4849.2  461.10  4900.2  458.92
  4987.1  460.63  4998.0  452.04  4998.7  451.24  5006.3  452.04  5008.2  454.61
  5021.3  455.18  5023.7  458.08  5028.9  456.50  5038.4  460.14  5092.4  460.82
  5152.0  460.13  5172.6  461.28  5186.3  460.17  5192.8  461.20  5399.9  460.24
  5882.2  462.15  6215.8  465.03  6246.8  467.35  6257.1  466.34  6457.6  474.43
#Mann=8,-1,0
  4199.4    0.16       0  4462.6    0.12       0  4575.2    0.16       0
  4772.1    0.12       0  4998.0    0.07       0  5006.3    0.12       0
  5092.4    0.08       0  5192.8    0.05       0
Bank Sta=4580.6,5882.2
Exp/Cntr=0.3,0.1

Type RM Length L Ch R = 1,1510,0,0,0
BEGIN DESCRIPTION:
UNT 055 in LFCCL Watershed 1.0
END DESCRIPTION:
XS GIS Cut Line= 3
      2814175.03      7072325.00      2813075.00      7072425.00
      2812875.00      7074825.02
#Sta/Elev= 30
  3907.4  478.50  4078.1  467.24  4178.5  462.82  4331.7  459.42  4356.5  459.08
  4425.6  459.00  4554.7  458.76  4971.8  458.92  4981.8  458.28  4991.9  454.50
  4997.8  448.18  4998.5  447.38  5006.1  448.18  5009.5  451.49  5014.5  451.49
  5022.0  456.12  5042.1  459.22  5122.3  459.66  5142.4  456.49  5182.6  459.21
  5202.6  456.11  5222.7  459.56  5242.8  459.73  5550.8  458.85  5566.1  459.08
  5666.8  459.43  5764.8  459.54  6640.1  463.35  6978.8  475.50  7420.3  484.22
#Mann=9,-1,0
  3907.4    0.16       0  4331.7    0.12       0  4425.6    0.07       0
  4554.7    0.12       0  4997.8    0.07       0  5006.1    0.12       0
  5550.8    0.05       0  5666.8    0.08       0  5764.8    0.05       0
Bank Sta=4356.5,5566.1
Exp/Cntr=0.3,0.1

Chan Stop Cuts=-1