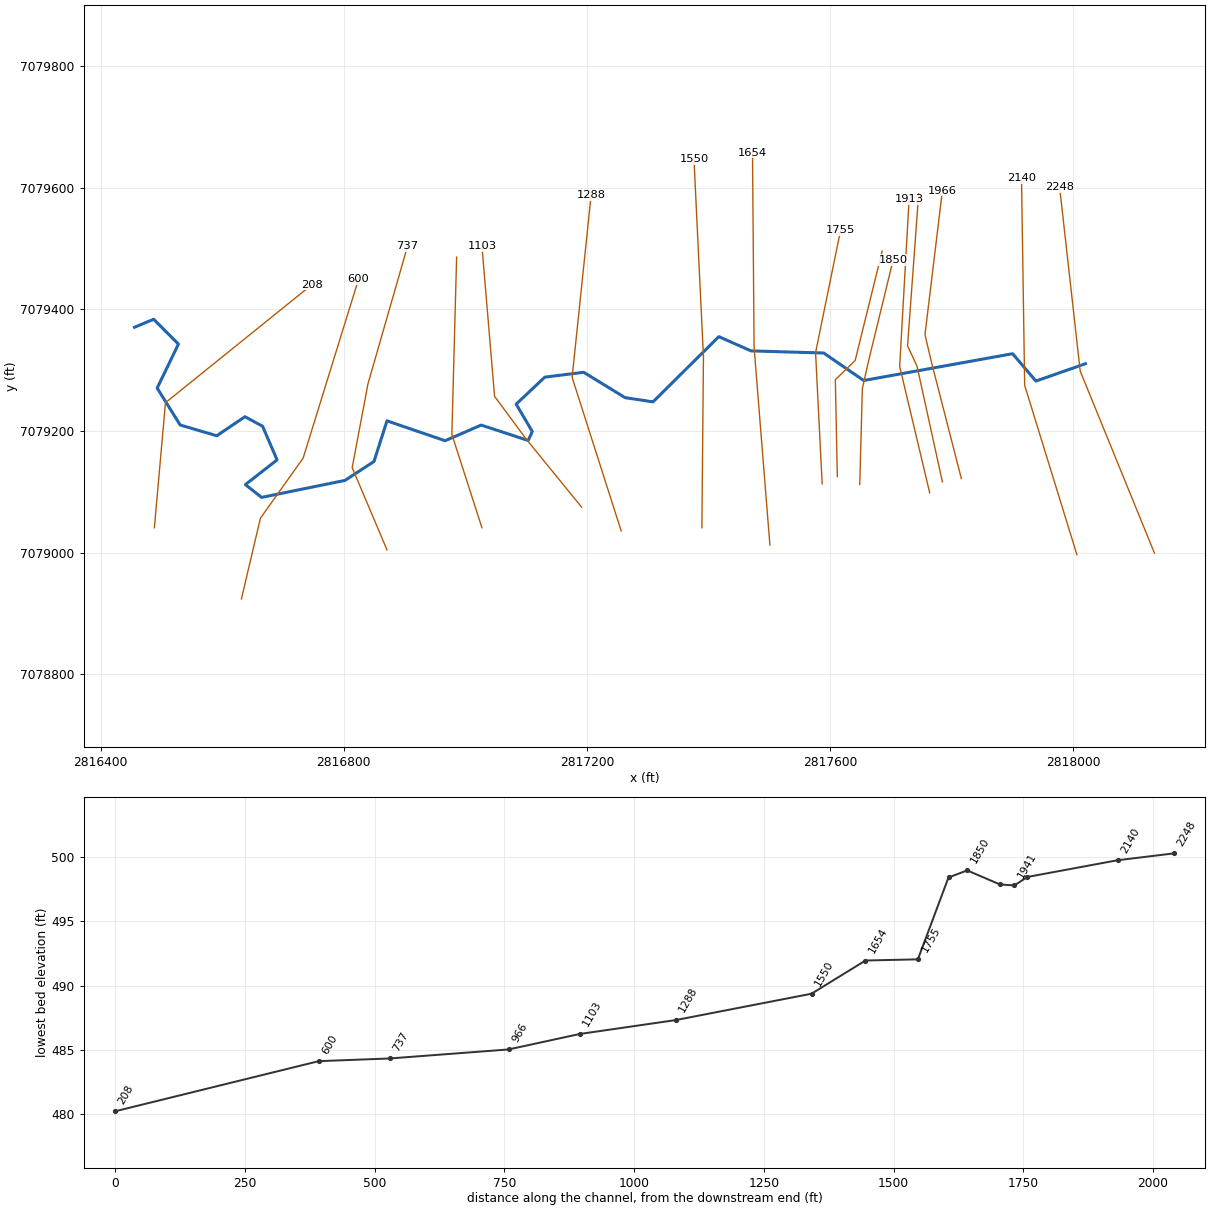
--- UNT 056 in LFCCL Watershed.prj (project) ---

Proj Title=UNT 056 in LFCCL Watershed Base Level Engineering
Current Plan=p01
Default Exp/Contr=0.3,0.1
English Units
Geom File=g01
Flow File=f01
Plan File=p01
BEGIN DESCRIPTION:
UNT 056 in LFCCL Watershed
END DESCRIPTION:

--- UNT 056 in LFCCL Watershed.p01 (plan) ---

Plan Title=Multiple Run
Short Identifier=Multiple
Geom File=g01
Flow File=f01
Subcritical Flow
K Sum by GR= 0
Std Step Tol= 0.01
Critical Tol= 0.01
Num of Std Step Trials= 20
Max Error Tol= 0.3
Flow Tol Ratio= 0.001
Split Flow NTrial= 30
Split Flow Tol= 0.02
Split Flow Ratio= 0.02
Log Output Level= 0
Friction Slope Method= 1
Unsteady Friction Slope Method= 2
Unsteady Bridges Friction Slope Method= 1
Parabolic Critical Depth
Global Vel Dist=  1 , 1 , 1
Global Log Level= 0
CheckData=True
Encroach Param= -1, 0, 0, 0
BEGIN DESCRIPTION:
Multiple Run
END DESCRIPTION:

--- UNT 056 in LFCCL Watershed.f01 (steady flow) ---

Flow Title=Multiple
Number of Profiles=7
Profile Names=10-year,25-year,50-year,1pct_min,100-year,1pct_plu,500-year
River Rch & RM= UNT 056 in LFCCL,Reach-1,2248
     211     260     298     170     339     676     436
Boundary for River Rch & Prof#=UNT 056 in LFCCL,Reach-1,1
Up Type=0
Dn Type=3
Dn Slope=0.005
Boundary for River Rch & Prof#=UNT 056 in LFCCL,Reach-1,2
Up Type=0
Dn Type=3
Dn Slope=0.005
Boundary for River Rch & Prof#=UNT 056 in LFCCL,Reach-1,3
Up Type=0
Dn Type=3
Dn Slope=0.005
Boundary for River Rch & Prof#=UNT 056 in LFCCL,Reach-1,4
Up Type=0
Dn Type=3
Dn Slope=0.005
Boundary for River Rch & Prof#=UNT 056 in LFCCL,Reach-1,5
Up Type=0
Dn Type=3
Dn Slope=0.005
Boundary for River Rch & Prof#=UNT 056 in LFCCL,Reach-1,6
Up Type=0
Dn Type=3
Dn Slope=0.005
Boundary for River Rch & Prof#=UNT 056 in LFCCL,Reach-1,7
Up Type=0
Dn Type=3
Dn Slope=0.005

--- UNT 056 in LFCCL Watershed.g01 (geometry) ---

Geom Title=Existing Conditions

River Reach=UNT 056 in LFCCL,Reach-1
Reach XY= 30
      2818020.59      7079310.71      2817939.08      7079282.19
      2817900.66      7079327.17      2817655.61      7079283.09
      2817589.82      7079328.34      2817470.23      7079331.83
      2817417.18      7079355.24      2817308.85      7079247.93
      2817262.95      7079254.89      2817194.79      7079296.62
      2817130.78      7079288.60      2817083.68      7079244.18
      2817110.21      7079199.14      2817103.45      7079184.40
      2817026.09      7079209.73      2816966.73      7079183.95
      2816871.09      7079216.71      2816849.67      7079149.84
      2816801.92      7079118.65      2816664.69      7079090.71
      2816638.01      7079111.74      2816690.13      7079152.43
      2816666.35      7079207.80      2816637.30      7079223.52
      2816590.87      7079192.15      2816530.75      7079209.85
      2816492.82      7079270.60      2816527.86      7079342.97
      2816487.07      7079383.90      2816455.59      7079370.71

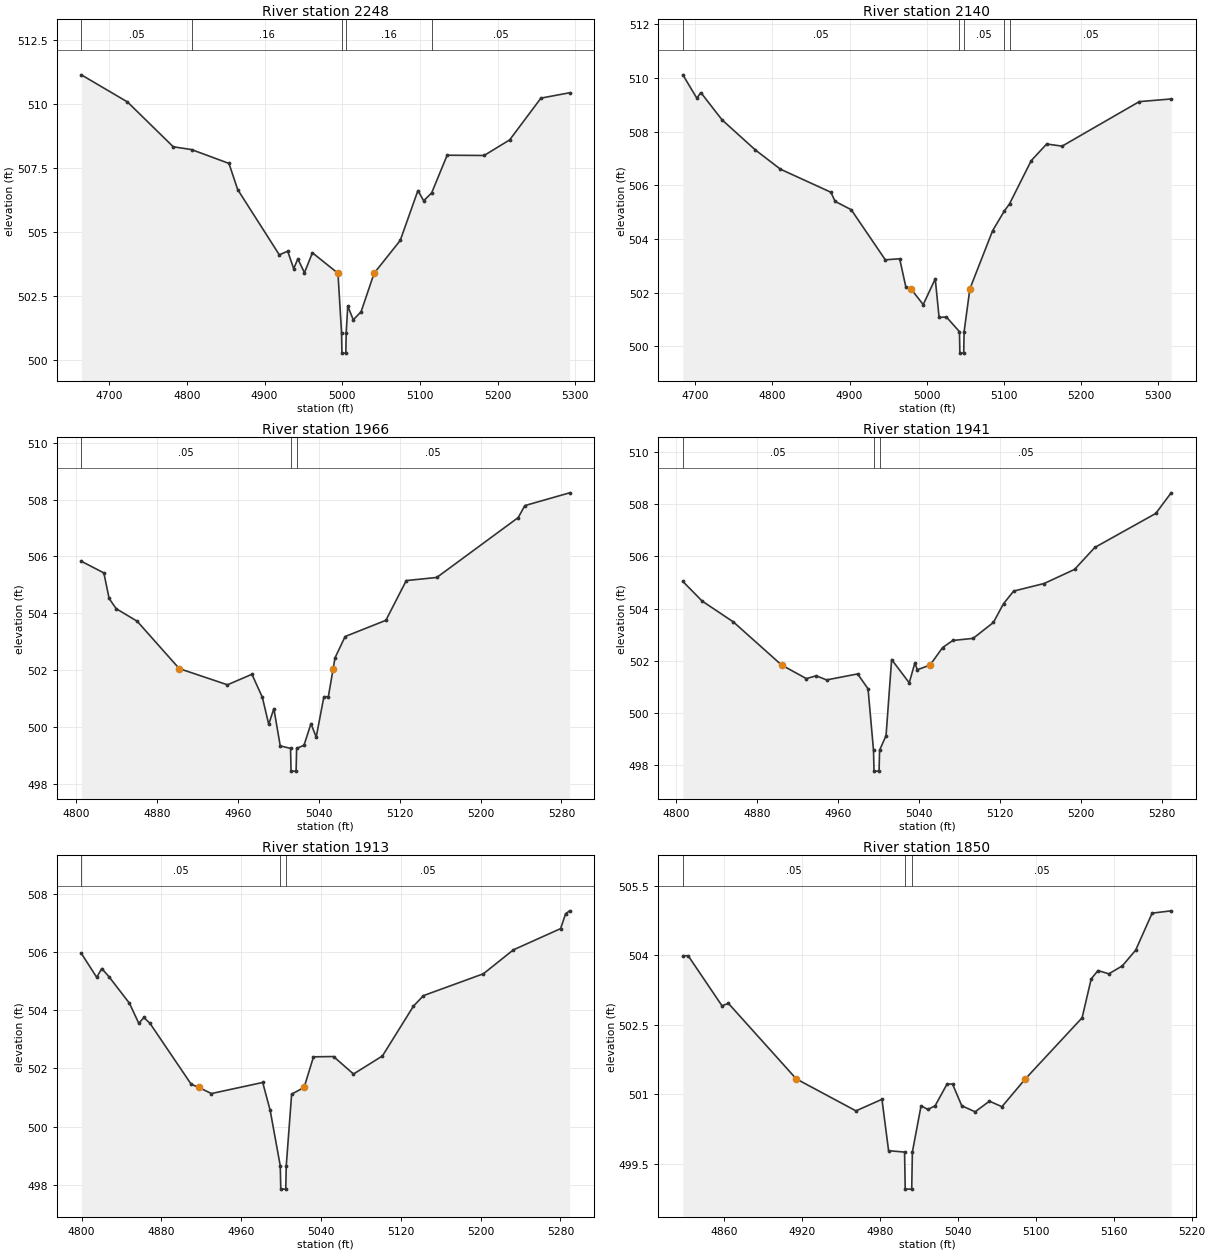
Type RM Length L Ch R = 1,2248,108,108,108
BEGIN DESCRIPTION:
UNT 056 in LFCCL Watershed 4.0
END DESCRIPTION:
XS GIS Cut Line= 3
      2818134.10      7078999.09      2818011.93      7079298.70
      2817978.02      7079601.65
#Sta/Elev= 30
  4664.2  511.14  4723.6  510.08  4782.5  508.33  4806.1  508.22  4854.2  507.68
  4865.4  506.66  4919.0  504.11  4929.8  504.25  4937.5  503.57  4942.9  503.95
  4951.4  503.41  4961.6  504.19  4994.5  503.39  4999.1  501.07  4999.6  500.27
  5004.6  500.27  5005.1  501.07  5007.1  502.11  5014.2  501.57  5024.3  501.89
  5041.0  503.39  5074.6  504.67  5097.4  506.62  5104.8  506.22  5115.1  506.53
  5135.0  508.00  5182.6  507.99  5215.5  508.60  5255.7  510.23  5292.6  510.44
#Mann=5,-1,0
  4664.2    0.05       0  4806.1    0.16       0  4999.1    0.07       0
  5005.1    0.16       0  5115.1    0.05       0
Bank Sta=4994.5,5041
Exp/Cntr=0.3,0.1

Type RM Length L Ch R = 1,2140,174,174,174
BEGIN DESCRIPTION:
XS3395A
END DESCRIPTION:
XS GIS Cut Line= 3
      2818006.50      7078996.48      2817920.55      7079275.15
      2817915.34      7079616.29
#Sta/Elev= 30
  4683.9  510.12  4702.0  509.25  4707.2  509.46  4734.7  508.44  4777.8  507.32
  4810.4  506.60  4875.8  505.74  4881.2  505.40  4902.1  505.09  4946.3  503.22
  4964.9  503.26  4972.8  502.22  4979.4  502.14  4995.4  501.55  5011.0  502.51
  5016.0  501.07  5025.4  501.09  5042.4  500.54  5042.9  499.74  5047.9  499.74
  5048.4  500.54  5055.9  502.14  5085.4  504.31  5100.3  505.03  5107.3  505.31
  5135.4  506.92  5155.4  507.54  5175.4  507.46  5275.4  509.12  5316.7  509.22
#Mann=5,-1,0
  4683.9    0.05       0  5042.4    0.03       0  5048.4    0.05       0
  5100.3    0.16       0  5107.3    0.05       0
Bank Sta=4979.4,5055.9
Exp/Cntr=0.3,0.1

Type RM Length L Ch R = 1,1966,25,25,25
BEGIN DESCRIPTION:
XS3404A
END DESCRIPTION:
XS GIS Cut Line= 4
      2817816.38      7079121.54      2817766.90      7079314.22
      2817756.49      7079358.49      2817785.13      7079595.46
#Sta/Elev= 30
  4805.0  505.83  4827.3  505.42  4832.5  504.52  4839.5  504.16  4860.2  503.72
  4901.9  502.05  4949.6  501.48  4973.8  501.85  4984.1  501.04  4990.4  500.09
  4995.5  500.64  5001.8  499.33  5012.0  499.24  5012.5  498.44  5017.5  498.44
  5018.0  499.24  5025.3  499.35  5032.2  500.11  5037.4  499.64  5045.0  501.06
  5049.4  501.06  5054.2  502.05  5056.0  502.43  5066.0  503.18  5106.3  503.75
  5126.5  505.15  5156.7  505.26  5237.3  507.37  5243.8  507.79  5288.1  508.24
#Mann=3,-1,0
  4805.0    0.05       0  5012.0    0.03       0  5018.0    0.05       0
Bank Sta=4901.9,5054.2
Exp/Cntr=0.3,0.1

Type RM Length L Ch R = 1,1941,28,28,28
BEGIN DESCRIPTION:
XS3403A
END DESCRIPTION:
XS GIS Cut Line= 4
      2817785.14      7079116.26      2817743.47      7079306.40
      2817727.84      7079340.26      2817746.06      7079590.15
#Sta/Elev= 30
  4806.5  505.04  4825.5  504.29  4856.4  503.49  4904.1  501.84  4928.6  501.32
  4938.3  501.43  4948.5  501.27  4979.2  501.50  4989.5  500.93  4994.9  498.58
  4995.4  497.78  5000.4  497.78  5000.9  498.58  5007.3  499.14  5012.8  502.05
  5030.2  501.16  5035.7  501.91  5038.3  501.66  5050.8  501.84  5063.2  502.51
  5073.3  502.78  5093.3  502.86  5113.4  503.47  5123.4  504.19  5133.4  504.67
  5163.5  504.96  5193.6  505.50  5213.6  506.34  5273.8  507.64  5289.0  508.43
#Mann=3,-1,0
  4806.5    0.05       0  4994.9    0.03       0  5000.9    0.05       0
Bank Sta=4904.1,5050.8
Exp/Cntr=0.3,0.1

Type RM Length L Ch R = 1,1913,63,63,63
BEGIN DESCRIPTION:
XS3396A
END DESCRIPTION:
XS GIS Cut Line= 3
      2817764.29      7079098.10      2817714.82      7079306.40
      2817730.38      7079581.26
#Sta/Elev= 30
  4799.8  505.95  4815.2  505.13  4820.3  505.43  4827.5  505.15  4848.0  504.24
  4857.4  503.55  4862.5  503.75  4868.6  503.55  4909.9  501.46  4917.5  501.35
  4930.2  501.14  4981.6  501.52  4989.1  500.56  4999.2  498.66  4999.7  497.86
  5004.7  497.86  5005.2  498.66  5010.6  501.12  5023.1  501.35  5032.5  502.40
  5052.6  502.41  5072.6  501.81  5101.6  502.43  5132.7  504.14  5142.7  504.50
  5202.8  505.25  5232.8  506.07  5280.2  506.80  5285.2  507.31  5289.2  507.41
#Mann=3,-1,0
  4799.8    0.05       0  4999.2    0.03       0  5005.2    0.05       0
Bank Sta=4917.5,5023.1
Exp/Cntr=0.3,0.1

Type RM Length L Ch R = 1,1850,36,36,36
BEGIN DESCRIPTION:
Mapping XS b2fa6fe5
END DESCRIPTION:
XS GIS Cut Line= 4
      2817649.12      7079111.88      2817653.46      7079270.32
      2817664.32      7079318.07      2817704.10      7079481.53
#Sta/Elev= 30
  4828.4  503.99  4832.5  503.99  4858.5  502.91  4863.5  502.96  4915.7  501.33
  4961.6  500.64  4981.6  500.89  4986.7  499.78  4999.0  499.75  4999.5  498.95
  5004.5  498.95  5005.0  499.75  5011.7  500.75  5016.9  500.67  5022.5  500.75
  5031.7  501.22  5035.9  501.22  5043.0  500.75  5053.3  500.62  5064.3  500.85
  5073.9  500.73  5091.9  501.33  5135.6  502.65  5142.6  503.49  5147.8  503.67
  5156.2  503.60  5166.5  503.77  5176.8  504.11  5189.5  504.91  5204.1  504.96
#Mann=3,-1,0
  4828.4    0.05       0  4999.0    0.03       0  5005.0    0.05       0
Bank Sta=4915.7,5091.9
Exp/Cntr=0.3,0.1

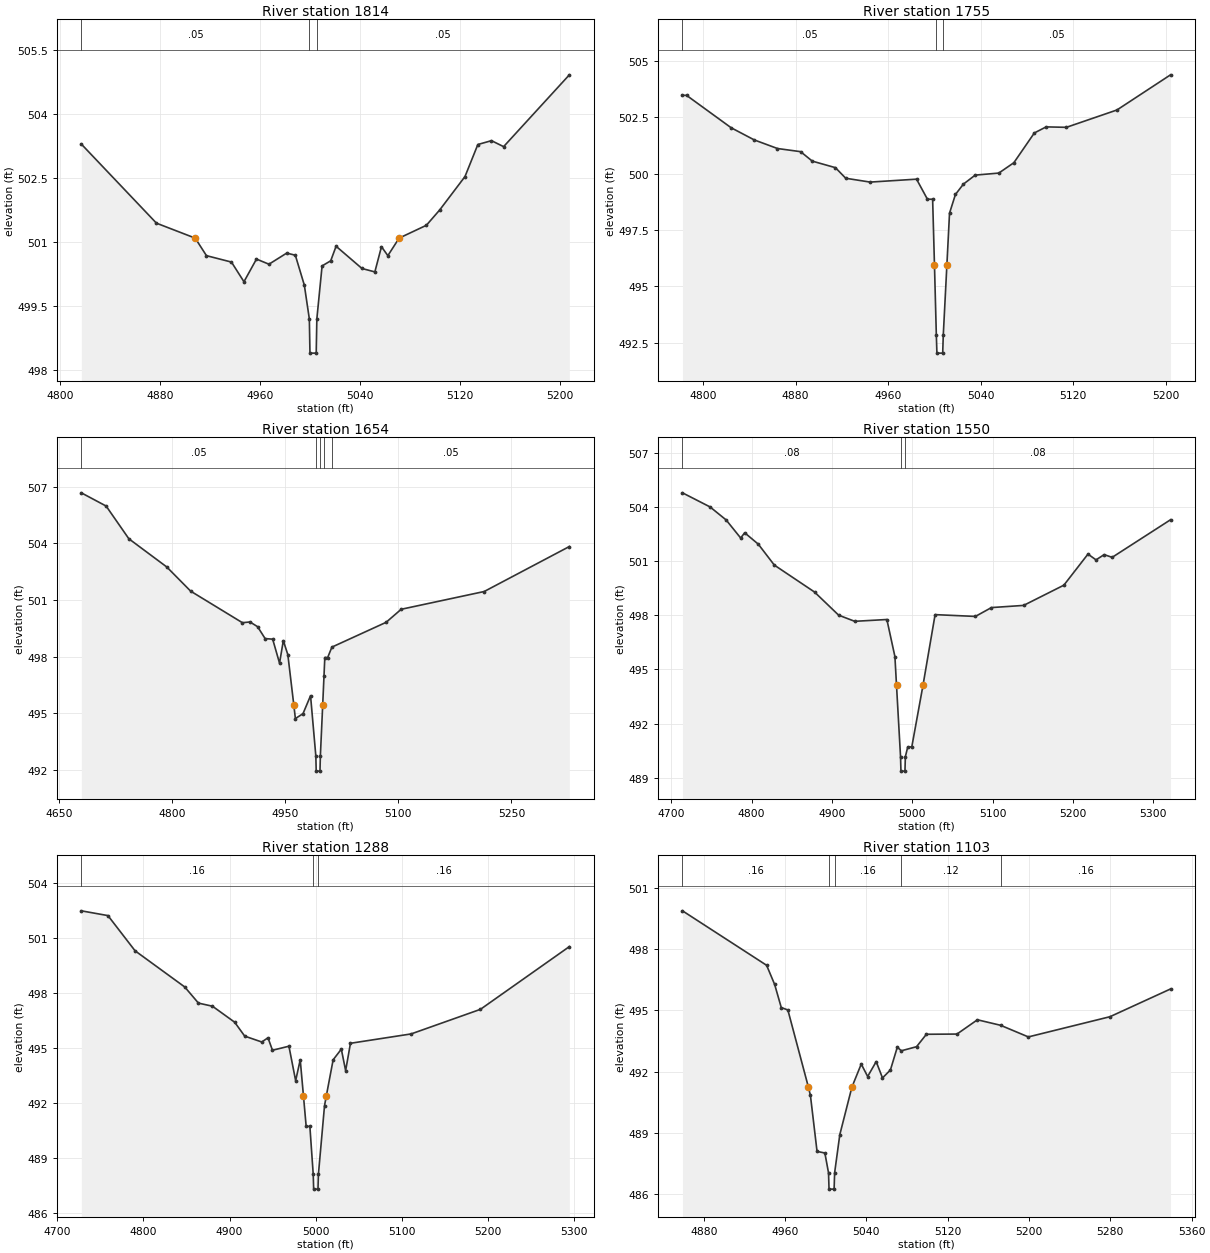
Type RM Length L Ch R = 1,1814,59,59,59
BEGIN DESCRIPTION:
Mapping XS 15fc62d5
END DESCRIPTION:
XS GIS Cut Line= 4
      2817612.23      7079124.90      2817608.98      7079284.43
      2817641.53      7079315.90      2817686.02      7079496.04
#Sta/Elev= 30
  4817.1  503.29  4877.2  501.44  4908.2  501.09  4917.2  500.68  4937.2  500.53
  4947.2  500.07  4957.2  500.60  4967.2  500.48  4981.4  500.74  4988.3  500.69
  4995.5  499.99  4999.5  499.20  5000.0  498.40  5005.0  498.40  5005.5  499.20
  5009.7  500.44  5016.6  500.56  5020.9  500.90  5041.6  500.38  5051.9  500.30
  5057.2  500.89  5062.3  500.68  5071.3  501.09  5093.1  501.39  5103.8  501.75
  5124.0  502.53  5134.3  503.28  5145.2  503.37  5154.9  503.23  5207.5  504.91
#Mann=3,-1,0
  4817.1    0.05       0  4999.5    0.03       0  5005.5    0.05       0
Bank Sta=4908.2,5071.3
Exp/Cntr=0.3,0.1

Type RM Length L Ch R = 1,1755,101,101,101
BEGIN DESCRIPTION:
Mapping XS 4989a715
END DESCRIPTION:
XS GIS Cut Line= 3
      2817587.28      7079112.99      2817576.42      7079328.92
      2817617.58      7079530.35
#Sta/Elev= 30
  4782.2  503.48  4785.7  503.48  4824.3  502.04  4844.3  501.50  4864.3  501.12
  4884.3  500.98  4894.4  500.56  4914.4  500.27  4923.3  499.80  4944.4  499.63
  4984.5  499.76  4993.9  498.87  4998.4  498.87  5000.0  495.93  5001.6  492.84
  5002.1  492.04  5007.1  492.04  5007.6  492.84  5010.7  495.93  5013.0  498.25
  5018.1  499.08  5025.0  499.54  5035.2  499.94  5055.6  500.03  5068.6  500.49
  5086.3  501.81  5096.5  502.08  5114.0  502.06  5157.7  502.83  5204.0  504.39
#Mann=3,-1,0
  4782.2    0.05       0  5001.6    0.03       0  5007.6    0.05       0
Bank Sta=5000,5010.7
Exp/Cntr=0.3,0.1

Type RM Length L Ch R = 1,1654,104,104,104
BEGIN DESCRIPTION:
XS3397A
END DESCRIPTION:
XS GIS Cut Line= 3
      2817501.28      7079012.17      2817475.24      7079337.65
      2817472.63      7079657.92
#Sta/Elev= 30
  4679.9  506.67  4712.8  505.97  4742.9  504.24  4793.1  502.75  4824.8  501.47
  4893.4  499.80  4903.4  499.84  4913.5  499.59  4923.5  498.96  4933.5  498.93
  4942.6  497.66  4947.6  498.85  4953.6  498.11  4961.5  495.45  4963.6  494.73
  4973.7  494.99  4983.7  495.94  4990.7  492.75  4991.2  491.95  4996.2  491.95
  4996.7  492.75  4999.8  495.45  5001.5  496.97  5002.6  497.96  5006.4  497.96
  5012.0  498.51  5083.8  499.82  5103.8  500.51  5213.8  501.45  5326.7  503.83
#Mann=5,-1,0
  4679.9    0.05       0  4990.7    0.03       0  4996.7    0.05       0
  5001.5    0.08       0  5012.0    0.05       0
Bank Sta=4961.5,4999.8
Exp/Cntr=0.3,0.1

Type RM Length L Ch R = 1,1550,262,262,262
BEGIN DESCRIPTION:
XS3398A
END DESCRIPTION:
XS GIS Cut Line= 3
      2817389.30      7079040.74      2817391.90      7079322.03
      2817376.28      7079647.55
#Sta/Elev= 30
  4714.1  504.77  4748.4  503.99  4768.4  503.27  4786.5  502.27  4791.5  502.56
  4808.4  501.93  4828.4  500.77  4878.4  499.28  4908.4  498.00  4928.4  497.66
  4968.4  497.76  4978.4  495.71  4980.4  494.11  4985.4  490.17  4985.9  489.37
  4990.9  489.37  4991.4  490.17  4994.4  490.71  4999.4  490.71  5013.3  494.11
  5028.4  498.03  5078.5  497.93  5098.5  498.42  5138.5  498.54  5188.6  499.66
  5218.6  501.38  5228.6  501.06  5238.7  501.35  5248.7  501.20  5321.3  503.28
#Mann=3,-1,0
  4714.1    0.08       0  4985.4    0.07       0  4991.4    0.08       0
Bank Sta=4980.4,5013.3
Exp/Cntr=0.3,0.1

Type RM Length L Ch R = 1,1288,185,185,185
BEGIN DESCRIPTION:
XS3399A
END DESCRIPTION:
XS GIS Cut Line= 3
      2817256.50      7079035.53      2817175.76      7079288.17
      2817207.00      7079587.61
#Sta/Elev= 30
  4728.0  502.49  4758.9  502.23  4790.4  500.31  4848.0  498.34  4863.9  497.46
  4880.2  497.29  4905.9  496.42  4917.6  495.66  4937.4  495.34  4944.6  495.57
  4949.8  494.89  4968.9  495.11  4976.7  493.23  4982.0  494.37  4985.8  492.38
  4988.9  490.74  4993.2  490.74  4997.1  488.12  4997.6  487.32  5002.6  487.32
  5003.1  488.12  5010.2  491.87  5012.2  492.38  5020.2  494.37  5029.7  494.95
  5034.7  493.78  5040.3  495.27  5110.7  495.78  5191.1  497.12  5294.3  500.54
#Mann=3,-1,0
  4728.0    0.16       0  4997.1    0.07       0  5003.1    0.16       0
Bank Sta=4985.8,5012.2
Exp/Cntr=0.3,0.1

Type RM Length L Ch R = 1,1103,137,137,137
BEGIN DESCRIPTION:
XS3405A
END DESCRIPTION:
XS GIS Cut Line= 4
      2817191.39      7079074.63      2817100.24      7079186.61
      2817048.15      7079256.92      2817027.32      7079504.36
#Sta/Elev= 30
  4859.0  499.88  4941.8  497.21  4949.7  496.27  4956.2  495.14  4962.7  495.02
  4982.9  491.24  4984.9  490.83  4991.4  488.09  4999.1  488.01  5002.7  487.04
  5003.2  486.24  5008.2  486.24  5008.7  487.04  5013.8  488.91  5025.7  491.24
  5034.9  492.37  5041.2  491.76  5049.6  492.49  5055.8  491.69  5063.6  492.08
  5070.4  493.20  5074.3  493.02  5089.3  493.22  5099.0  493.83  5129.1  493.84
  5149.2  494.54  5172.0  494.27  5199.3  493.70  5279.6  494.69  5339.2  496.05
#Mann=5,-1,0
  4859.0    0.16       0  5002.7    0.07       0  5008.7    0.16       0
  5074.3    0.12       0  5172.0    0.16       0
Bank Sta=4982.9,5025.7
Exp/Cntr=0.3,0.1

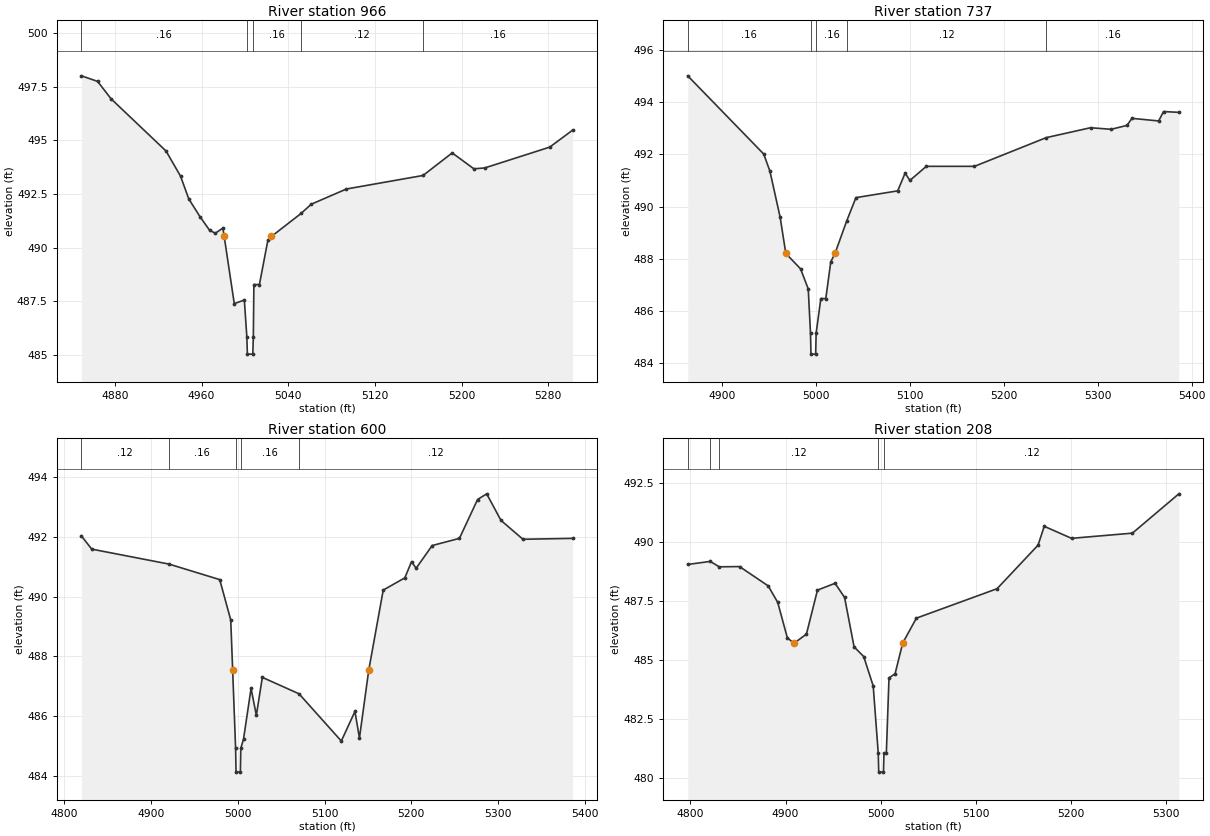
Type RM Length L Ch R = 1,966,229,229,229
BEGIN DESCRIPTION:
XS3400A
END DESCRIPTION:
XS GIS Cut Line= 3
      2817027.32      7079040.78      2816977.84      7079194.42
      2816985.66      7079486.11
#Sta/Elev= 30
  4849.2  498.00  4864.1  497.74  4876.5  496.93  4927.2  494.50  4940.6  493.33
  4948.2  492.27  4958.7  491.43  4967.4  490.81  4972.7  490.67  4979.7  490.91
  4980.9  490.52  4990.2  487.39  4999.5  487.56  5001.8  485.84  5002.3  485.04
  5007.3  485.04  5007.8  485.84  5008.3  488.28  5013.4  488.28  5021.2  490.34
  5024.5  490.52  5051.8  491.59  5061.2  492.02  5093.7  492.73  5164.4  493.36
  5191.3  494.41  5211.3  493.67  5221.3  493.71  5281.3  494.68  5302.4  495.47
#Mann=5,-1,0
  4849.2    0.16       0  5001.8    0.07       0  5007.8    0.16       0
  5051.8    0.12       0  5164.4    0.16       0
Bank Sta=4980.9,5024.5
Exp/Cntr=0.3,0.1

Type RM Length L Ch R = 1,737,137,137,137
BEGIN DESCRIPTION:
XS3401A
END DESCRIPTION:
XS GIS Cut Line= 4
      2816871.08      7079004.30      2816813.78      7079139.74
      2816839.82      7079277.76      2816904.91      7079504.27
#Sta/Elev= 30
  4863.2  495.01  4944.2  492.01  4950.8  491.35  4961.7  489.58  4967.7  488.20
  4983.4  487.61  4991.6  486.84  4994.0  485.14  4994.5  484.34  4999.5  484.34
  5000.0  485.14  5005.0  486.47  5010.3  486.47  5015.6  487.88  5020.1  488.20
  5032.5  489.44  5042.4  490.34  5086.9  490.60  5094.8  491.28  5099.9  491.00
  5117.4  491.54  5168.7  491.54  5245.1  492.64  5292.3  493.02  5314.3  492.96
  5331.2  493.11  5336.4  493.38  5364.9  493.28  5370.1  493.64  5386.4  493.61
#Mann=5,-1,0
  4863.2    0.16       0  4994.0    0.07       0  5000.0    0.16       0
  5032.5    0.12       0  5245.1    0.16       0
Bank Sta=4967.7,5020.1
Exp/Cntr=0.3,0.1

Type RM Length L Ch R = 1,600,392,392,392
BEGIN DESCRIPTION:
XS3402A
END DESCRIPTION:
XS GIS Cut Line= 4
      2816631.48      7078923.56      2816662.74      7079056.40
      2816733.05      7079155.36      2816824.19      7079449.60
#Sta/Elev= 30
  4819.9  492.03  4831.7  491.59  4920.7  491.09  4979.2  490.57  4991.9  489.22
  4994.1  487.54  4997.5  484.93  4998.0  484.13  5003.0  484.13  5003.5  484.93
  5006.6  485.23  5015.3  486.93  5021.4  486.03  5028.3  487.30  5070.6  486.75
  5119.3  485.17  5135.0  486.16  5140.2  485.27  5150.9  487.54  5167.6  490.22
  5192.5  490.63  5200.2  491.17  5205.5  490.95  5224.0  491.71  5255.4  491.95
  5276.3  493.25  5286.8  493.44  5303.3  492.55  5328.6  491.92  5385.8  491.95
#Mann=5,-1,0
  4819.9    0.12       0  4920.7    0.16       0  4997.5    0.07       0
  5003.5    0.16       0  5070.6    0.12       0
Bank Sta=4994.1,5150.9
Exp/Cntr=0.3,0.1

Type RM Length L Ch R = 1,208,0,0,0
BEGIN DESCRIPTION:
UNT 056 in LFCCL Watershed 1.0
END DESCRIPTION:
XS GIS Cut Line= 3
      2816488.25      7079040.73      2816506.49      7079246.51
      2816747.58      7079440.93
#Sta/Elev= 30
  4797.1  489.06  4820.8  489.19  4830.2  488.96  4851.6  488.97  4881.7  488.15
  4891.7  487.45  4901.8  485.95  4908.7  485.71  4921.9  486.10  4933.5  487.97
  4952.0  488.26  4962.0  487.66  4972.0  485.56  4982.1  485.15  4992.1  483.90
  4997.4  481.04  4997.9  480.24  5002.9  480.24  5003.4  481.04  5005.9  481.04
  5008.7  484.24  5015.1  484.42  5023.1  485.72  5037.5  486.78  5122.3  488.03
  5165.4  489.88  5171.9  490.68  5200.6  490.17  5264.6  490.39  5313.4  492.06
#Mann=5,-1,0
  4797.1    0.12       0  4820.8    0.16       0  4830.2    0.12       0
  4997.4    0.07       0  5003.4    0.12       0
Bank Sta=4908.7,5023.1
Exp/Cntr=0.3,0.1

Chan Stop Cuts=-1