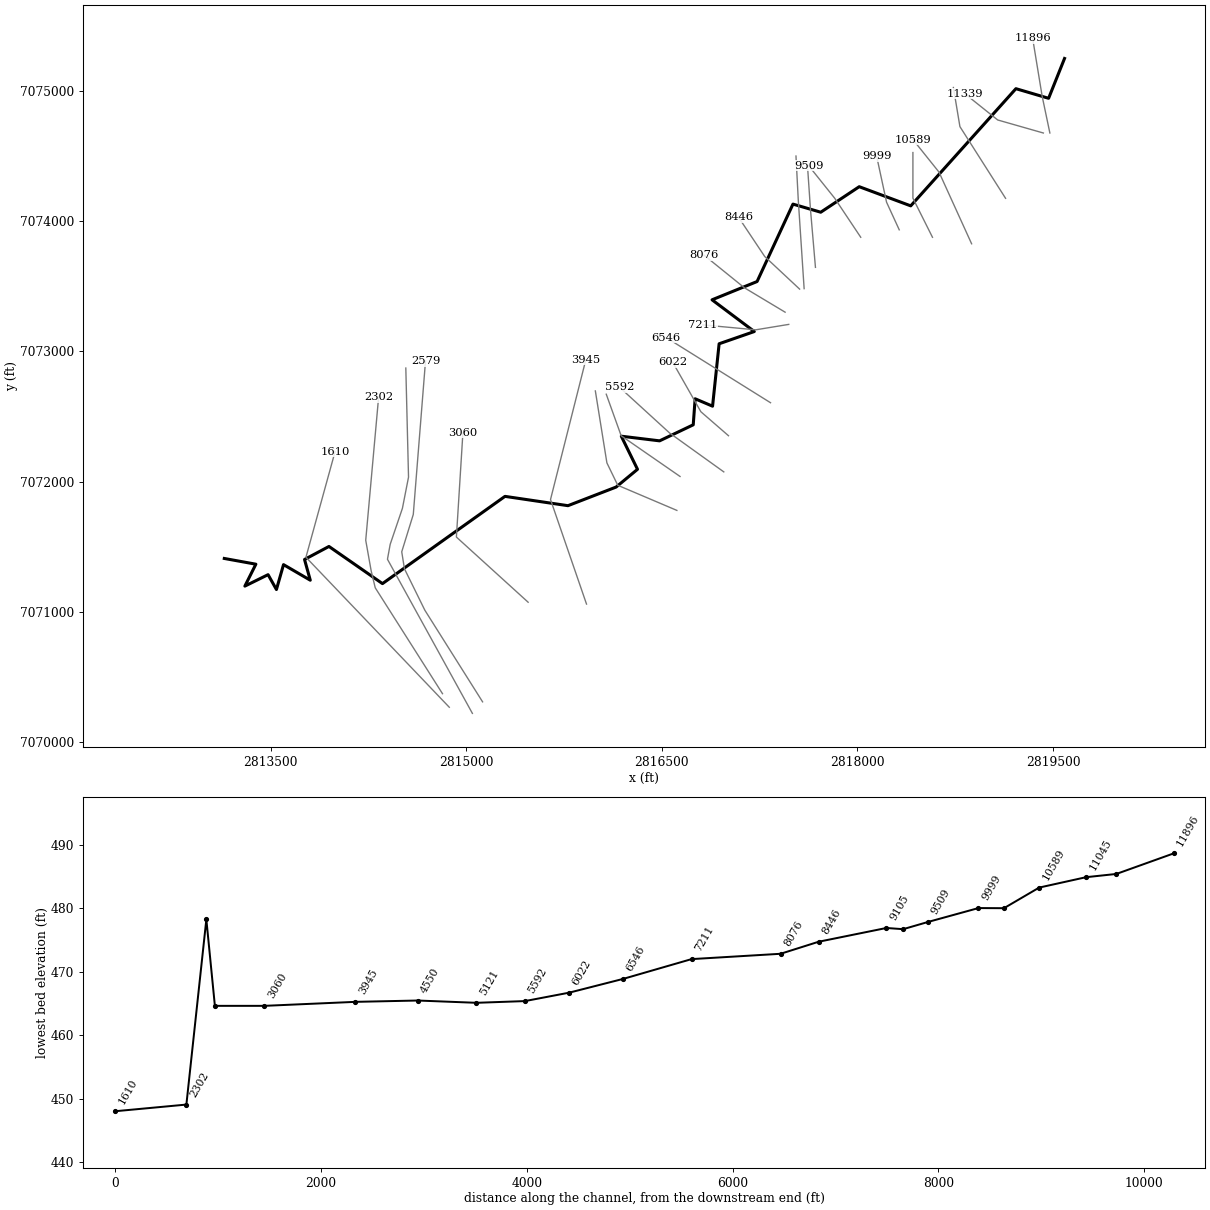
--- UNT 057 in LFCCL Watershed.prj (project) ---

Proj Title=UNT 057 in LFCCL Watershed Base Level Engineering
Current Plan=p01
Default Exp/Contr=0.3,0.1
English Units
Geom File=g01
Flow File=f01
Plan File=p01
BEGIN DESCRIPTION:
UNT 057 in LFCCL Watershed
END DESCRIPTION:

--- UNT 057 in LFCCL Watershed.p01 (plan) ---

Plan Title=Multiple Run
Short Identifier=Multiple
Geom File=g01
Flow File=f01
Subcritical Flow
K Sum by GR= 0
Std Step Tol= 0.01
Critical Tol= 0.01
Num of Std Step Trials= 20
Max Error Tol= 0.3
Flow Tol Ratio= 0.001
Split Flow NTrial= 30
Split Flow Tol= 0.02
Split Flow Ratio= 0.02
Log Output Level= 0
Friction Slope Method= 1
Unsteady Friction Slope Method= 2
Unsteady Bridges Friction Slope Method= 1
Parabolic Critical Depth
Global Vel Dist=  1 , 1 , 1
Global Log Level= 0
CheckData=True
Encroach Param= -1, 0, 0, 0
BEGIN DESCRIPTION:
Multiple Run
END DESCRIPTION:

--- UNT 057 in LFCCL Watershed.f01 (steady flow) ---

Flow Title=Multiple
Number of Profiles=7
Profile Names=10-year,25-year,50-year,1pct_min,100-year,1pct_plu,500-year
River Rch & RM= UNT 057 in LFCCL,Reach-1,11896
     544     713     848     500     997    1990    1376
River Rch & RM= UNT 057 in LFCCL,Reach-1,10589
     808    1085    1310     783    1562    3117    2219
River Rch & RM= UNT 057 in LFCCL,Reach-1,3945
    1132    1550    1894    1146    2286    4562    3326
Boundary for River Rch & Prof#=UNT 057 in LFCCL,Reach-1,1
Up Type=0
Dn Type=3
Dn Slope=0.005
Boundary for River Rch & Prof#=UNT 057 in LFCCL,Reach-1,2
Up Type=0
Dn Type=3
Dn Slope=0.005
Boundary for River Rch & Prof#=UNT 057 in LFCCL,Reach-1,3
Up Type=0
Dn Type=3
Dn Slope=0.005
Boundary for River Rch & Prof#=UNT 057 in LFCCL,Reach-1,4
Up Type=0
Dn Type=3
Dn Slope=0.005
Boundary for River Rch & Prof#=UNT 057 in LFCCL,Reach-1,5
Up Type=0
Dn Type=3
Dn Slope=0.005
Boundary for River Rch & Prof#=UNT 057 in LFCCL,Reach-1,6
Up Type=0
Dn Type=3
Dn Slope=0.005
Boundary for River Rch & Prof#=UNT 057 in LFCCL,Reach-1,7
Up Type=0
Dn Type=3
Dn Slope=0.005

--- UNT 057 in LFCCL Watershed.g01 (geometry) ---

Geom Title=Existing Conditions

River Reach=UNT 057 in LFCCL,Reach-1
Reach XY= 30
      2819587.46      7075246.89      2819465.27      7074941.30
      2819214.71      7075015.08      2818408.27      7074116.04
      2818013.45      7074263.05      2817718.44      7074067.26
      2817505.45      7074129.43      2817230.29      7073535.45
      2816885.01      7073395.22      2817209.12      7073151.81
      2816939.25      7073057.88      2816888.98      7072578.99
      2816755.36      7072635.87      2816740.81      7072436.11
      2816482.84      7072313.08      2816189.16      7072348.80
      2816313.51      7072094.80      2816149.47      7071958.54
      2815780.38      7071815.67      2815297.52      7071887.11
      2814358.25      7071217.72      2813948.04      7071502.83
      2813760.71      7071402.93      2813804.78      7071243.81
      2813599.69      7071363.36      2813545.30      7071172.41
      2813481.24      7071286.46      2813303.28      7071198.53
      2813387.70      7071366.74      2813145.59      7071410.71

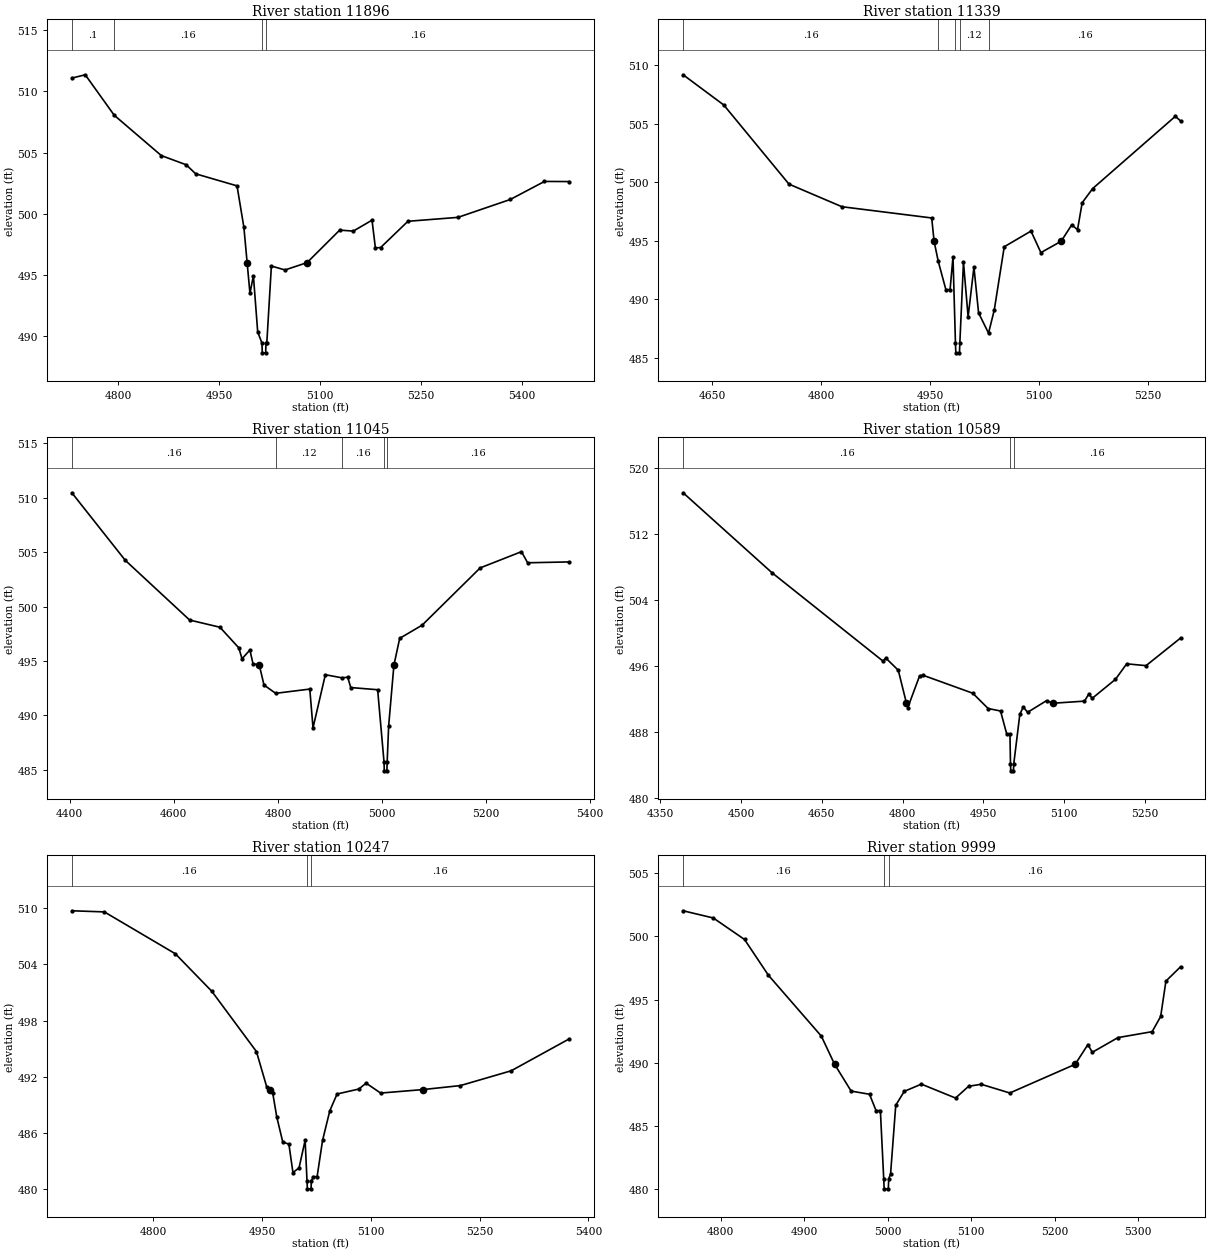
Type RM Length L Ch R = 1,11896,557,557,557
BEGIN DESCRIPTION:
UNT 057 in LFCCL Watershed 19.0
END DESCRIPTION:
XS GIS Cut Line= 3
      2819475.00      7074675.00      2819415.67      7074958.30
      2819342.98      7075401.33
#Sta/Elev= 30
  4731.5  511.07  4751.4  511.34  4794.4  508.04  4864.3  504.75  4901.2  504.00
  4915.4  503.26  4976.7  502.28  4986.9  498.89  4991.7  496.02  4995.9  493.51
  5001.0  494.95  5007.4  490.36  5013.7  489.46  5014.2  488.66  5019.2  488.66
  5019.7  489.46  5020.9  489.46  5027.7  495.74  5048.0  495.42  5080.7  496.02
  5129.1  498.67  5149.3  498.59  5177.1  499.48  5182.1  497.22  5189.9  497.25
  5230.4  499.39  5304.7  499.71  5382.4  501.17  5433.1  502.64  5469.9  502.63
#Mann=4,-1,0
  4731.5     0.1       0  4794.4    0.16       0  5013.7    0.07       0
  5019.7    0.16       0
Bank Sta=4991.7,5080.7
Exp/Cntr=0.3,0.1

Type RM Length L Ch R = 1,11339,294,294,294
BEGIN DESCRIPTION:
UNT 057 in LFCCL Watershed 18.0
END DESCRIPTION:
XS GIS Cut Line= 3
      2819425.01      7074675.00      2819075.00      7074775.00
      2818824.98      7074975.02
#Sta/Elev= 30
  4610.4  509.17  4666.3  506.59  4756.0  499.83  4828.8  497.90  4952.3  496.94
  4955.6  494.95  4961.3  493.24  4971.8  490.82  4977.6  490.82  4981.6  493.61
  4985.0  486.22  4985.5  485.42  4990.5  485.42  4991.0  486.22  4996.0  493.15
  5002.4  488.50  5010.4  492.74  5016.8  488.83  5030.5  487.10  5038.4  489.09
  5052.1  494.48  5088.9  495.82  5102.5  493.98  5130.4  494.95  5144.9  496.35
  5152.9  495.94  5159.3  498.24  5173.7  499.45  5287.4  505.62  5294.6  505.23
#Mann=5,-1,0
  4610.4    0.16       0  4961.3    0.12       0  4985.0    0.07       0
  4991.0    0.12       0  5030.5    0.16       0
Bank Sta=4955.6,5130.4
Exp/Cntr=0.3,0.1

Type RM Length L Ch R = 1,11045,456,456,456
BEGIN DESCRIPTION:
UNT 057 in LFCCL Watershed 17.0
END DESCRIPTION:
XS GIS Cut Line= 3
      2819135.41      7074173.97      2818785.42      7074723.96
      2818735.42      7075023.92
#Sta/Elev= 30
  4404.0  510.45  4506.6  504.25  4630.4  498.76  4688.6  498.10  4725.0  496.20
  4731.0  495.20  4746.2  496.01  4752.1  494.76  4764.3  494.62  4773.3  492.79
  4795.7  492.03  4861.3  492.42  4867.5  488.86  4891.2  493.74  4923.4  493.45
  4934.1  493.51  4940.1  492.56  4991.7  492.36  5004.0  485.71  5004.5  484.91
  5009.5  484.91  5010.0  485.71  5012.9  489.05  5023.0  494.62  5034.1  497.08
  5077.2  498.29  5188.8  503.55  5268.1  505.04  5280.0  504.02  5360.0  504.10
#Mann=5,-1,0
  4404.0    0.16       0  4795.7    0.12       0  4923.4    0.16       0
  5004.0    0.07       0  5010.0    0.16       0
Bank Sta=4764.3,5023
Exp/Cntr=0.3,0.1

Type RM Length L Ch R = 1,10589,342,342,342
BEGIN DESCRIPTION:
UNT 057 in LFCCL Watershed 16.0
END DESCRIPTION:
XS GIS Cut Line= 3
      2818874.99      7073825.03      2818625.00      7074375.00
      2818424.99      7074625.02
#Sta/Elev= 30
  4392.3  517.05  4557.0  507.36  4763.5  496.61  4769.0  496.97  4792.1  495.49
  4807.3  491.48  4809.7  490.94  4831.7  494.81  4838.2  494.88  4930.5  492.70
  4959.1  490.84  4982.1  490.54  4993.7  487.72  4999.6  487.72  5000.6  484.07
  5001.1  483.27  5006.1  483.27  5006.6  484.07  5018.0  490.16  5024.4  491.02
  5032.4  490.38  5067.7  491.80  5079.0  491.48  5138.1  491.74  5146.1  492.60
  5152.5  492.08  5195.7  494.39  5216.5  496.27  5252.5  496.05  5316.6  499.40
#Mann=3,-1,0
  4392.3    0.16       0  5000.6    0.07       0  5006.6    0.16       0
Bank Sta=4807.3,5079
Exp/Cntr=0.3,0.1

Type RM Length L Ch R = 1,10247,248,248,248
BEGIN DESCRIPTION:
UNT 057 in LFCCL Watershed 15.0
END DESCRIPTION:
XS GIS Cut Line= 3
      2818575.02      7073874.96      2818425.00      7074175.00
      2818425.00      7074525.04
#Sta/Elev= 30
  4688.0  509.72  4732.8  509.60  4830.6  505.13  4880.9  501.12  4942.4  494.68
  4956.4  490.95  4960.5  490.62  4964.8  490.27  4970.4  487.70  4978.7  485.01
  4987.1  484.80  4992.7  481.76  5001.1  482.26  5009.5  485.21  5012.1  480.82
  5012.6  480.02  5017.6  480.02  5018.1  480.82  5020.7  481.32  5026.0  481.32
  5033.5  485.19  5043.5  488.36  5053.5  490.15  5083.5  490.68  5093.5  491.31
  5113.5  490.25  5171.6  490.62  5223.5  491.05  5293.5  492.63  5373.5  496.04
#Mann=3,-1,0
  4688.0    0.16       0  5012.1    0.07       0  5018.1    0.16       0
Bank Sta=4960.5,5171.6
Exp/Cntr=0.3,0.1

Type RM Length L Ch R = 1,9999,490,490,490
BEGIN DESCRIPTION:
UNT 057 in LFCCL Watershed 14.0
END DESCRIPTION:
XS GIS Cut Line= 3
      2818320.20      7073932.22      2818222.96      7074144.06
      2818146.57      7074498.23
#Sta/Elev= 30
  4755.2  502.03  4791.3  501.46  4828.7  499.76  4857.3  496.93  4920.6  492.12
  4936.5  489.89  4956.3  487.77  4978.3  487.52  4986.1  486.23  4991.3  486.23
  4995.3  480.84  4995.8  480.04  5000.8  480.04  5001.3  480.84  5003.5  481.21
  5009.7  486.65  5019.9  487.75  5040.4  488.32  5081.3  487.22  5096.9  488.15
  5112.0  488.31  5146.2  487.62  5224.5  489.89  5239.7  491.45  5245.0  490.84
  5275.7  492.00  5316.6  492.47  5326.8  493.67  5333.1  496.47  5350.6  497.60
#Mann=3,-1,0
  4755.2    0.16       0  4995.3    0.07       0  5001.3    0.16       0
Bank Sta=4936.5,5224.5
Exp/Cntr=0.3,0.1

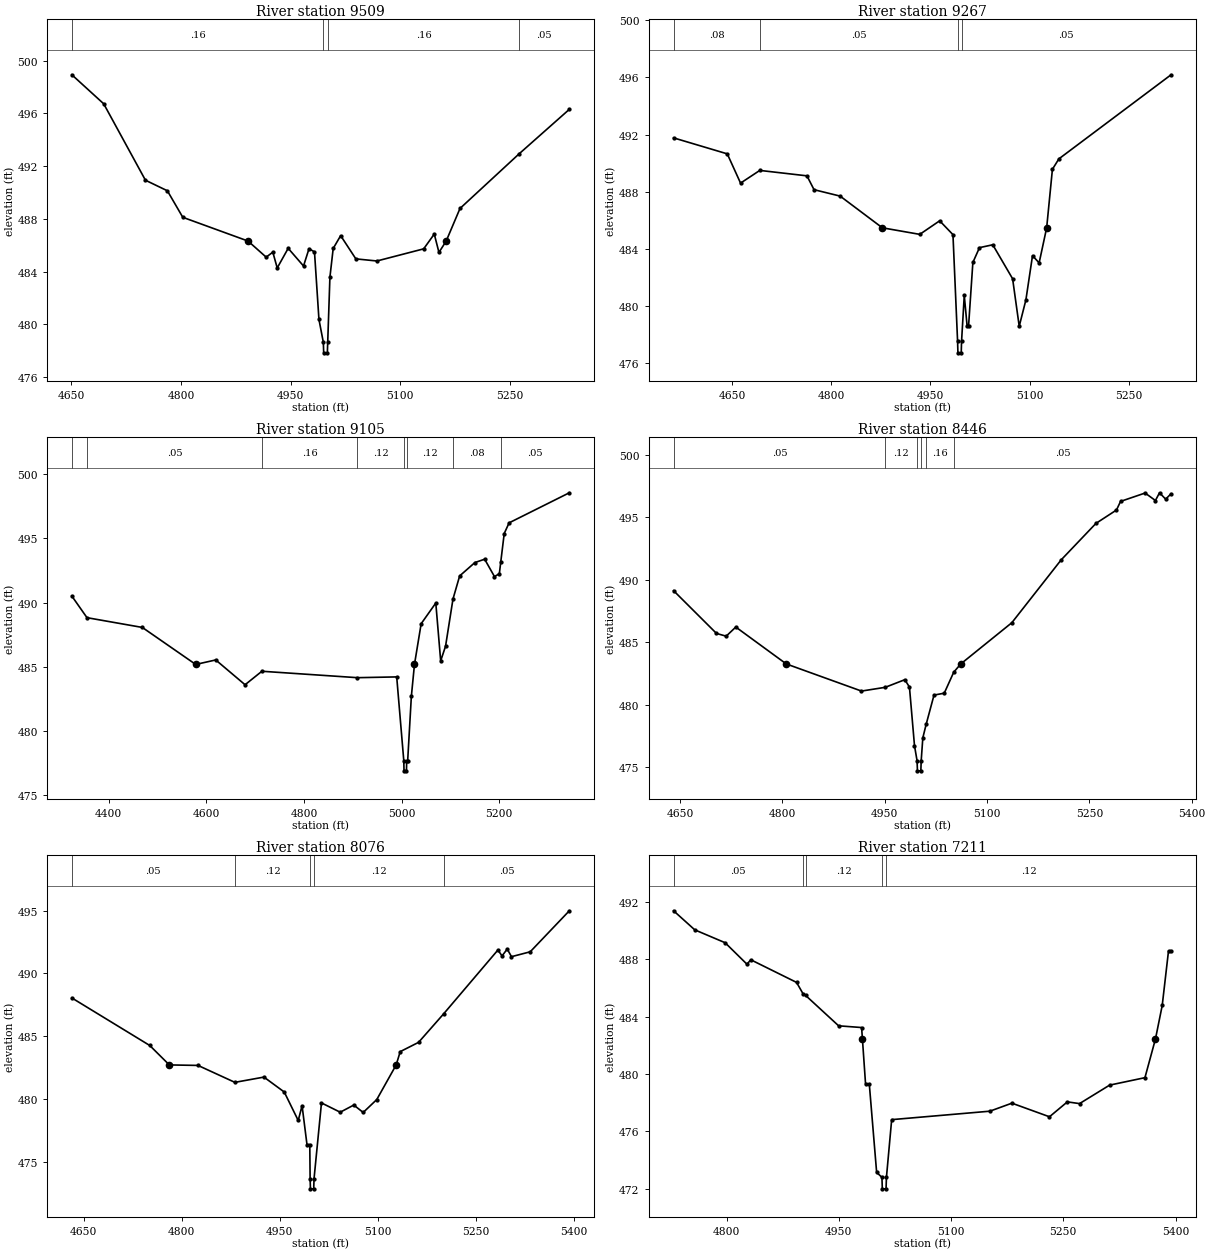
Type RM Length L Ch R = 1,9509,242,242,242
BEGIN DESCRIPTION:
UNT 057 in LFCCL Watershed 13.0
END DESCRIPTION:
XS GIS Cut Line= 3
      2818025.02      7073874.97      2817825.00      7074175.00
      2817625.03      7074424.96
#Sta/Elev= 30
  4650.5  498.92  4694.1  496.72  4751.2  490.93  4781.2  490.13  4802.3  488.12
  4891.6  486.32  4916.4  485.10  4925.5  485.48  4931.5  484.28  4946.5  485.77
  4967.5  484.43  4975.0  485.74  4982.5  485.50  4988.6  480.38  4994.6  478.65
  4995.1  477.85  5000.1  477.85  5000.6  478.65  5003.6  483.58  5008.1  485.76
  5018.3  486.73  5039.1  484.97  5067.9  484.81  5131.9  485.73  5146.4  486.85
  5152.8  485.46  5162.7  486.32  5181.6  488.79  5262.7  492.94  5331.2  496.30
#Mann=4,-1,0
  4650.5    0.16       0  4994.6    0.07       0  5000.6    0.16       0
  5262.7    0.05       0
Bank Sta=4891.6,5162.7
Exp/Cntr=0.3,0.1

Type RM Length L Ch R = 1,9267,162,162,162
BEGIN DESCRIPTION:
XS3406A
END DESCRIPTION:
XS GIS Cut Line= 3
      2817677.82      7073644.07      2817639.63      7074088.50
      2817618.80      7074394.02
#Sta/Elev= 30
  4561.6  491.77  4642.8  490.65  4662.9  488.60  4692.0  489.49  4763.3  489.11
  4774.0  488.14  4813.5  487.69  4877.3  485.47  4933.9  485.01  4964.0  485.96
  4984.1  484.99  4991.1  477.51  4991.6  476.71  4996.6  476.71  4997.1  477.51
  5001.2  480.73  5005.5  478.59  5007.7  478.59  5014.2  483.04  5024.2  484.08
  5044.3  484.28  5074.3  481.90  5084.3  478.57  5094.4  480.42  5104.4  483.52
  5114.4  483.01  5125.8  485.47  5134.5  489.57  5144.3  490.30  5313.9  496.19
#Mann=4,-1,0
  4561.6    0.08       0  4692.0    0.05       0  4991.1    0.04       0
  4997.1    0.05       0
Bank Sta=4877.3,5125.8
Exp/Cntr=0.3,0.1

Type RM Length L Ch R = 1,9105,659,659,659
BEGIN DESCRIPTION:
XS3407A
END DESCRIPTION:
XS GIS Cut Line= 3
      2817591.01      7073480.88      2817545.88      7074164.89
      2817528.51      7074498.24
#Sta/Elev= 30
  4324.3  490.50  4355.3  488.82  4468.7  488.06  4578.1  485.18  4619.1  485.53
  4679.2  483.60  4713.7  484.65  4909.4  484.15  4989.9  484.21  5004.4  477.70
  5004.9  476.90  5009.9  476.90  5010.4  477.70  5012.4  477.70  5019.9  482.69
  5026.3  485.18  5040.0  488.35  5070.0  489.96  5080.0  485.46  5090.0  486.60
  5105.2  490.27  5118.9  492.07  5150.1  493.11  5170.1  493.37  5190.2  492.02
  5200.2  492.24  5203.0  493.12  5210.2  495.37  5220.2  496.20  5343.6  498.54
#Mann=8,-1,0
  4324.3    0.08       0  4355.3    0.05       0  4713.7    0.16       0
  4909.4    0.12       0  5004.4    0.07       0  5010.4    0.12       0
  5105.2    0.08       0  5203.0    0.05       0
Bank Sta=4578.1,5026.3
Exp/Cntr=0.3,0.1

Type RM Length L Ch R = 1,8446,370,370,370
BEGIN DESCRIPTION:
XS3408A
END DESCRIPTION:
XS GIS Cut Line= 3
      2817556.30      7073477.39      2817288.93      7073727.39
      2817087.54      7074029.48
#Sta/Elev= 30
  4640.6  489.14  4703.5  485.72  4717.7  485.50  4731.8  486.23  4805.8  483.28
  4916.0  481.11  4950.8  481.41  4979.5  482.02  4986.3  481.43  4993.7  476.74
  4997.5  475.53  4998.0  474.73  5003.0  474.73  5003.5  475.53  5005.9  477.37
  5010.8  478.45  5022.3  480.79  5037.3  480.94  5051.2  482.62  5061.5  483.28
  5136.4  486.58  5208.6  491.60  5259.6  494.52  5289.7  495.59  5295.7  496.28
  5331.7  496.95  5346.8  496.35  5352.8  496.97  5361.8  496.46  5369.7  496.89
#Mann=6,-1,0
  4640.6    0.05       0  4950.8    0.12       0  4997.5    0.07       0
  5003.5    0.12       0  5010.8    0.16       0  5051.2    0.05       0
Bank Sta=4805.8,5061.5
Exp/Cntr=0.3,0.1

Type RM Length L Ch R = 1,8076,865,865,865
BEGIN DESCRIPTION:
XS3409A
END DESCRIPTION:
XS GIS Cut Line= 3
      2817445.16      7073300.32      2817132.68      7073487.81
      2816823.65      7073737.81
#Sta/Elev= 30
  4631.7  488.05  4751.0  484.26  4781.0  482.71  4824.9  482.67  4881.4  481.32
  4925.9  481.74  4957.0  480.55  4978.4  478.28  4984.3  479.46  4991.8  476.36
  4996.1  476.36  4996.6  473.63  4997.1  472.83  5002.1  472.83  5002.6  473.63
  5014.0  479.68  5042.7  478.94  5063.5  479.51  5077.9  478.92  5098.7  479.95
  5128.4  482.71  5134.6  483.77  5162.7  484.51  5200.9  486.77  5284.2  491.87
  5290.6  491.40  5298.5  491.95  5305.0  491.34  5333.7  491.73  5393.6  495.00
#Mann=5,-1,0
  4631.7    0.05       0  4881.4    0.12       0  4996.6    0.07       0
  5002.6    0.12       0  5200.9    0.05       0
Bank Sta=4781,5128.4
Exp/Cntr=0.3,0.1

Type RM Length L Ch R = 1,7211,665,665,665
BEGIN DESCRIPTION:
XS3410A
END DESCRIPTION:
XS GIS Cut Line= 3
      2817472.96      7073206.56      2817219.49      7073164.89
      2816813.25      7073203.09
#Sta/Elev= 30
  4729.1  491.40  4757.4  490.07  4798.0  489.17  4827.2  487.67  4832.3  487.98
  4893.5  486.40  4902.1  485.61  4905.6  485.49  4949.7  483.37  4980.4  483.25
  4981.5  482.46  4985.7  479.30  4990.7  479.30  5000.5  473.14  5007.6  472.79
  5008.1  471.99  5013.1  471.99  5013.6  472.79  5020.6  476.82  5151.8  477.41
  5181.3  477.97  5231.5  477.02  5255.4  478.06  5271.7  477.94  5311.9  479.23
  5359.1  479.75  5373.2  482.46  5382.2  484.79  5390.6  488.60  5394.0  488.60
#Mann=5,-1,0
  4729.1    0.05       0  4902.1    0.16       0  4905.6    0.12       0
  5007.6    0.07       0  5013.6    0.12       0
Bank Sta=4981.5,5373.2
Exp/Cntr=0.3,0.1

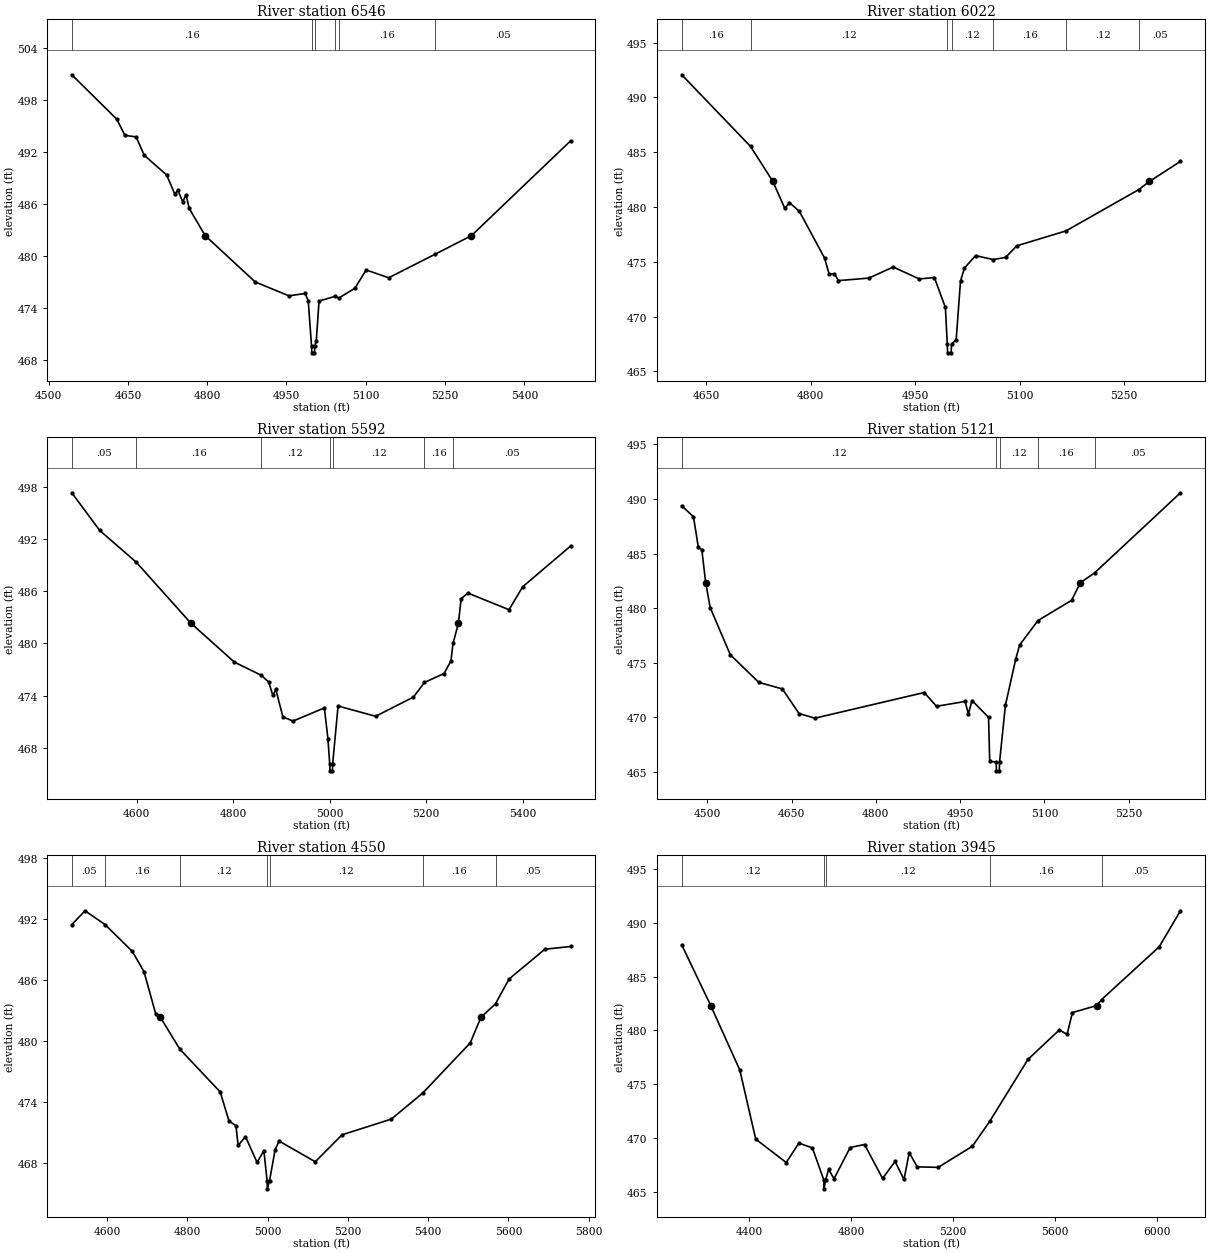
Type RM Length L Ch R = 1,6546,524,524,524
BEGIN DESCRIPTION:
UNT 057 in LFCCL Watershed 8.0
END DESCRIPTION:
XS GIS Cut Line= 3
      2817333.30      7072605.58      2816933.33      7072855.56
      2816533.30      7073105.58
#Sta/Elev= 30
  4543.9  500.87  4629.0  495.76  4644.4  493.90  4665.6  493.72  4680.9  491.61
  4723.4  489.33  4738.7  487.15  4744.6  487.56  4754.0  486.23  4759.9  487.09
  4766.0  485.49  4796.2  482.36  4890.8  477.03  4954.6  475.43  4985.2  475.70
  4991.1  474.88  4997.4  469.67  4997.9  468.87  5003.0  468.87  5003.5  469.67
  5006.4  470.26  5011.6  474.83  5042.4  475.38  5048.6  475.16  5079.5  476.31
  5100.7  478.41  5143.3  477.51  5231.2  480.22  5299.9  482.36  5487.3  493.26
#Mann=6,-1,0
  4543.9    0.16       0  4997.4    0.07       0  5003.5    0.16       0
  5042.4    0.12       0  5048.6    0.16       0  5231.2    0.05       0
Bank Sta=4796.2,5299.9
Exp/Cntr=0.3,0.1

Type RM Length L Ch R = 1,6022,430,430,430
BEGIN DESCRIPTION:
XS3411A
END DESCRIPTION:
XS GIS Cut Line= 3
      2817011.13      7072352.41      2816799.35      7072536.42
      2816584.05      7072914.92
#Sta/Elev= 30
  4614.7  492.07  4713.5  485.53  4745.5  482.34  4762.7  479.87  4769.3  480.41
  4783.6  479.61  4819.7  475.35  4826.3  473.88  4833.9  473.92  4839.7  473.29
  4883.3  473.52  4918.3  474.53  4955.8  473.44  4977.4  473.57  4993.2  470.84
  4995.9  467.50  4996.4  466.70  5001.5  466.70  5002.0  467.50  5008.7  467.90
  5014.9  473.26  5020.6  474.44  5036.5  475.57  5062.0  475.21  5079.7  475.41
  5095.6  476.46  5166.5  477.83  5271.0  481.60  5286.2  482.34  5330.7  484.17
#Mann=7,-1,0
  4614.7    0.16       0  4713.5    0.12       0  4995.9    0.07       0
  5002.0    0.12       0  5062.0    0.16       0  5166.5    0.12       0
  5271.0    0.05       0
Bank Sta=4745.5,5286.2
Exp/Cntr=0.3,0.1

Type RM Length L Ch R = 1,5592,471,471,471
BEGIN DESCRIPTION:
UNT 057 in LFCCL Watershed 6.0
END DESCRIPTION:
XS GIS Cut Line= 3
      2816975.03      7072074.98      2816559.77      7072373.23
      2816175.00      7072725.00
#Sta/Elev= 30
  4466.0  497.28  4523.7  492.96  4599.5  489.31  4712.3  482.33  4802.5  477.85
  4857.8  476.35  4873.7  475.56  4882.3  474.02  4888.4  474.71  4903.1  471.56
  4924.0  471.08  4988.9  472.59  4996.3  469.08  5000.0  466.17  5000.5  465.37
  5005.6  465.37  5006.1  466.17  5017.3  472.81  5095.0  471.63  5173.3  473.83
  5196.2  475.51  5236.8  476.54  5251.0  477.99  5255.3  479.99  5266.6  482.33
  5272.0  485.12  5286.1  485.77  5371.3  483.86  5399.6  486.50  5498.6  491.16
#Mann=7,-1,0
  4466.0    0.05       0  4599.5    0.16       0  4857.8    0.12       0
  5000.0    0.07       0  5006.1    0.12       0  5196.2    0.16       0
  5255.3    0.05       0
Bank Sta=4712.3,5266.6
Exp/Cntr=0.3,0.1

Type RM Length L Ch R = 1,5121,571,571,571
BEGIN DESCRIPTION:
XS3412A
END DESCRIPTION:
XS GIS Cut Line= 3
      2816639.66      7072039.87      2816188.24      7072352.39
      2816074.00      7072670.87
#Sta/Elev= 30
  4454.6  489.37  4475.5  488.36  4484.2  485.55  4490.3  485.35  4497.2  482.33
  4505.2  480.05  4541.0  475.73  4591.7  473.20  4633.6  472.60  4663.3  470.35
  4691.4  469.92  4886.0  472.27  4907.9  471.01  4958.6  471.45  4964.7  470.32
  4971.1  471.54  5000.5  470.00  5002.6  465.97  5014.0  465.90  5014.5  465.10
  5019.6  465.10  5020.1  465.90  5030.5  471.10  5048.9  475.34  5055.9  476.63
  5088.4  478.86  5148.2  480.71  5163.9  482.33  5189.3  483.23  5342.0  490.56
#Mann=5,-1,0
  4454.6    0.12       0  5014.0    0.07       0  5020.1    0.12       0
  5088.4    0.16       0  5189.3    0.05       0
Bank Sta=4497.2,5163.9
Exp/Cntr=0.3,0.1

Type RM Length L Ch R = 1,4550,605,605,605
BEGIN DESCRIPTION:
XS3417A
END DESCRIPTION:
XS GIS Cut Line= 4
      2816615.32      7071779.48      2816162.20      7071972.18
      2816078.86      7072144.06      2815990.33      7072696.10
#Sta/Elev= 30
  4512.3  491.43  4545.2  492.79  4595.0  491.44  4663.1  488.80  4692.2  486.80
  4721.3  482.67  4733.0  482.32  4781.5  479.19  4882.1  474.98  4903.8  472.14
  4921.3  471.66  4926.7  469.72  4944.9  470.60  4974.0  468.05  4990.8  469.22
  4998.9  466.26  4999.4  465.46  5005.0  466.26  5018.9  469.31  5028.6  470.16
  5118.9  468.12  5185.6  470.77  5308.1  472.31  5386.2  474.86  5504.9  479.80
  5531.6  482.32  5567.9  483.65  5601.8  486.09  5690.8  489.01  5754.8  489.28
#Mann=7,-1,0
  4512.3    0.05       0  4595.0    0.16       0  4781.5    0.12       0
  4998.9    0.07       0  5005.0    0.12       0  5386.2    0.16       0
  5567.9    0.05       0
Bank Sta=4733,5531.6
Exp/Cntr=0.3,0.1

Type RM Length L Ch R = 1,3945,885,885,885
BEGIN DESCRIPTION:
XS3416A
END DESCRIPTION:
XS GIS Cut Line= 3
      2815922.60      7071060.77      2815646.57      7071862.81
      2815917.41      7072935.74
#Sta/Elev= 30
  4136.8  487.97  4250.4  482.32  4364.3  476.32  4426.8  469.88  4546.3  467.70
  4596.0  469.51  4648.9  469.06  4694.0  466.05  4694.5  465.25  4700.5  466.05
  4712.4  467.06  4733.7  466.19  4797.0  469.10  4853.3  469.38  4923.9  466.22
  4973.0  467.80  5007.9  466.12  5028.5  468.62  5059.5  467.30  5142.0  467.25
  5276.1  469.22  5344.0  471.54  5493.6  477.30  5616.7  480.05  5647.3  479.64
  5668.0  481.67  5763.1  482.32  5782.5  482.88  6008.3  487.80  6091.6  491.15
#Mann=5,-1,0
  4136.8    0.12       0  4694.0    0.07       0  4700.5    0.12       0
  5344.0    0.16       0  5782.5    0.05       0
Bank Sta=4250.4,5763.1
Exp/Cntr=0.3,0.1

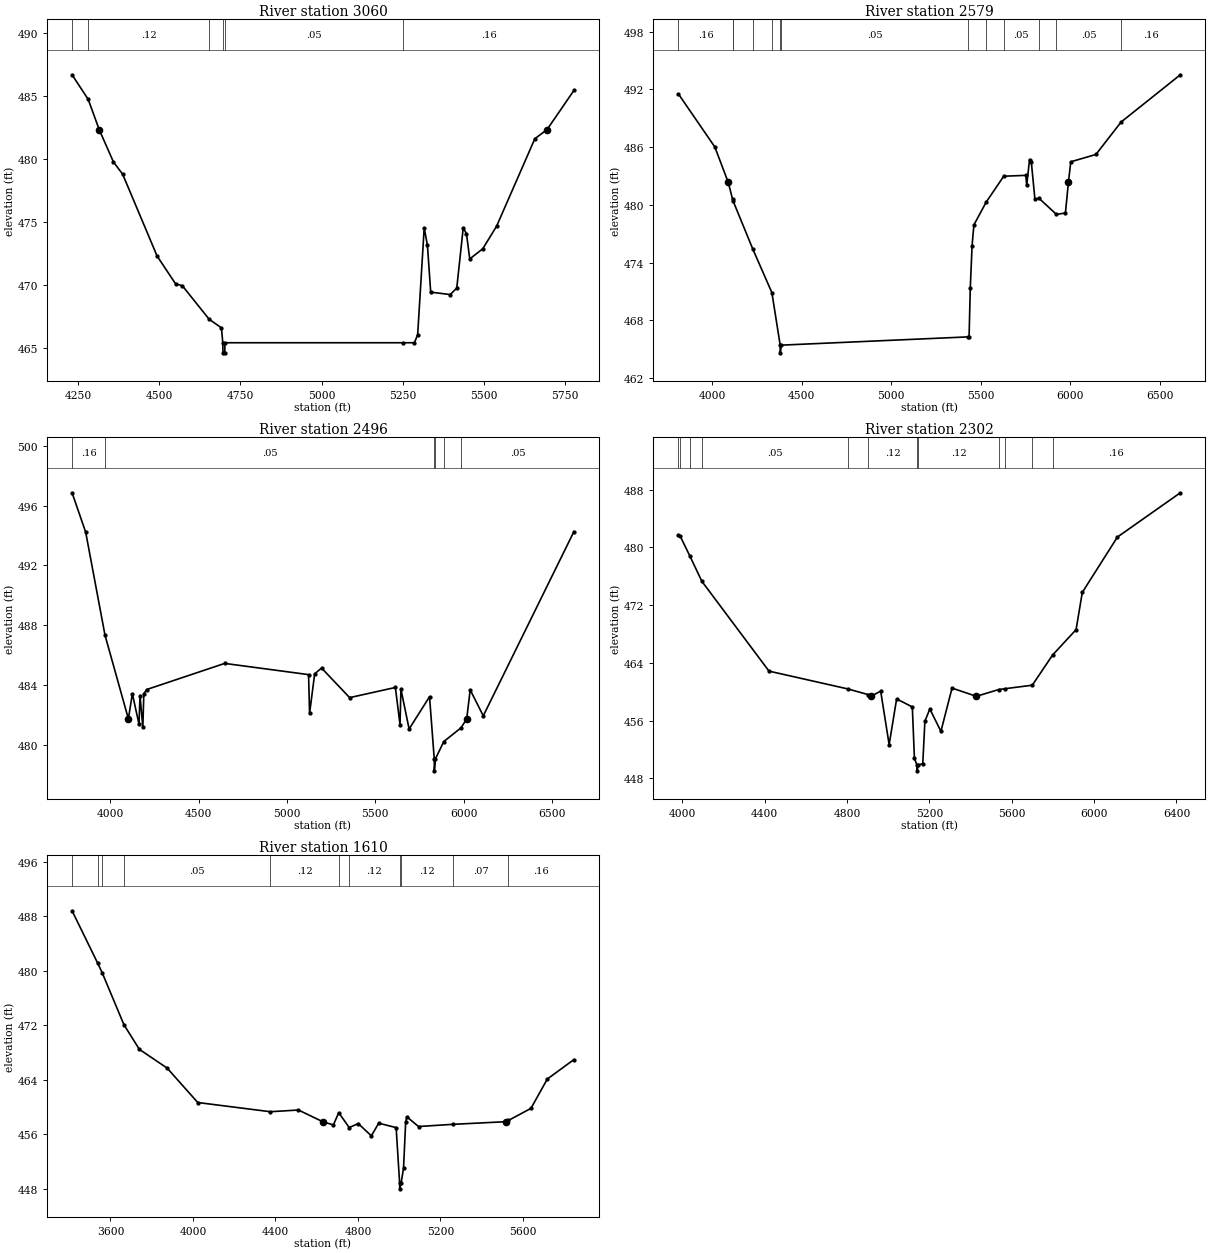
Type RM Length L Ch R = 1,3060,481,481,481
BEGIN DESCRIPTION:
UNT 057 in LFCCL Watershed 2.0
END DESCRIPTION:
XS GIS Cut Line= 3
      2815474.99      7071075.01      2814925.00      7071575.00
      2814975.00      7072375.05
#Sta/Elev= 30
  4232.1  486.66  4281.8  484.71  4315.5  482.32  4359.5  479.75  4387.8  478.78
  4493.9  472.29  4550.7  470.09  4571.6  469.94  4653.8  467.29  4691.9  466.60
  4696.1  465.42  4696.6  464.62  4702.2  464.62  4702.7  465.42  5252.1  465.42
  5286.0  465.42  5296.0  466.06  5316.1  474.53  5326.1  473.14  5336.1  469.43
  5396.2  469.24  5416.3  469.75  5436.3  474.54  5446.3  474.05  5456.3  472.06
  5496.4  472.87  5539.0  474.66  5656.7  481.59  5694.4  482.32  5777.0  485.42
#Mann=6,-1,0
  4232.1    0.16       0  4281.8    0.12       0  4653.8    0.05       0
  4696.1   0.033       0  4702.7    0.05       0  5252.1    0.16       0
Bank Sta=4315.5,5694.4
Exp/Cntr=0.3,0.1

Type RM Length L Ch R = 1,2579,83,83,83
BEGIN DESCRIPTION:
XS3415A
END DESCRIPTION:
XS GIS Cut Line= 6
      2815125.74      7070310.72      2814683.03      7071013.85
      2814526.78      7071331.56      2814505.95      7071461.77
      2814594.49      7071748.23      2814688.23      7072925.28
#Sta/Elev= 30
  3810.3  491.51  4013.5  486.01  4088.7  482.32  4112.6  480.58  4116.2  480.37
  4225.8  475.40  4332.4  470.88  4378.8  465.42  4379.3  464.62  4385.5  465.42
  5431.4  466.28  5434.7  466.28  5441.5  471.39  5451.5  475.76  5461.6  477.91
  5530.0  480.27  5628.3  482.97  5751.8  483.06  5756.8  482.01  5772.6  484.70
  5782.6  484.45  5802.7  480.58  5824.9  480.69  5923.2  479.00  5973.2  479.15
  5989.9  482.32  6003.1  484.47  6143.7  485.23  6284.4  488.60  6615.5  493.51
#Mann=13,-1,0
  3810.3    0.16       0  4112.6    0.05       0  4116.2    0.16       0
  4225.8    0.12       0  4332.4    0.05       0  4378.8    0.04       0
  4385.5    0.05       0  5431.4    0.16       0  5530.0    0.08       0
  5628.3    0.05       0  5824.9    0.16       0  5923.2    0.05       0
  6284.4    0.16       0
Bank Sta=4088.7,5989.9
Exp/Cntr=0.3,0.1

Type RM Length L Ch R = 1,2496,194,194,194
BEGIN DESCRIPTION:
XS3414A
END DESCRIPTION:
XS GIS Cut Line= 6
      2815047.63      7070222.16      2814396.57      7071404.48
      2814417.40      7071519.06      2814511.15      7071795.10
      2814558.03      7072034.68      2814537.23      7072871.65
#Sta/Elev= 30
  3784.6  496.86  3861.7  494.22  3970.9  487.33  4103.2  481.73  4125.7  483.41
  4163.3  481.37  4169.0  483.29  4184.9  481.16  4190.6  483.41  4206.5  483.69
  4648.0  485.44  5122.7  484.69  5128.3  482.09  5157.1  484.74  5196.1  485.13
  5355.0  483.15  5613.8  483.83  5640.0  481.34  5645.1  483.72  5691.5  481.05
  5807.0  483.21  5833.7  479.05  5834.2  478.25  5840.4  479.05  5887.6  480.21
  5985.4  481.13  6017.3  481.73  6037.1  483.67  6111.0  481.93  6623.9  494.26
#Mann=6,-1,0
  3784.6    0.16       0  3970.9    0.05       0  5833.7    0.04       0
  5840.4    0.05       0  5887.6    0.16       0  5985.4    0.05       0
Bank Sta=4103.2,6017.3
Exp/Cntr=0.3,0.1

Type RM Length L Ch R = 1,2302,692,692,692
BEGIN DESCRIPTION:
XS3413A
END DESCRIPTION:
XS GIS Cut Line= 5
      2814818.47      7070373.19      2814302.82      7071185.73
      2814271.57      7071315.93      2814229.90      7071550.31
      2814328.86      7072649.27
#Sta/Elev= 30
  3980.9  481.70  3990.0  481.51  4036.3  478.80  4094.5  475.30  4420.6  462.86
  4804.3  460.39  4903.2  459.60  4915.8  459.37  4963.1  460.09  5004.2  452.69
  5040.6  459.01  5116.8  457.90  5127.0  450.79  5139.4  449.85  5139.9  449.05
  5146.1  449.85  5167.6  450.06  5177.8  455.91  5201.8  457.62  5255.7  454.52
  5309.7  460.51  5428.0  459.37  5536.4  460.31  5566.0  460.42  5699.5  460.91
  5797.9  465.08  5912.3  468.61  5942.4  473.76  6113.1  481.43  6418.6  487.56
#Mann=12,-1,0
  3980.9    0.16       0  3990.0    0.05       0  4036.3    0.16       0
  4094.5    0.05       0  4804.3    0.07       0  4903.2    0.12       0
  5139.4    0.07       0  5146.1    0.12       0  5536.4    0.07       0
  5566.0    0.12       0  5699.5    0.05       0  5797.9    0.16       0
Bank Sta=4915.8,5428
Exp/Cntr=0.3,0.1

Type RM Length L Ch R = 1,1610,0,0,0
BEGIN DESCRIPTION:
UNT 057 in LFCCL Watershed 1.0
END DESCRIPTION:
XS GIS Cut Line= 3
      2814870.52      7070269.07      2813771.57      7071420.10
      2813995.18      7072231.34
#Sta/Elev= 30
  3414.1  488.78  3539.0  481.05  3559.7  479.72  3665.5  472.07  3740.3  468.46
  3874.9  465.71  4023.4  460.66  4375.5  459.31  4511.5  459.56  4629.1  457.85
  4681.0  457.37  4706.8  459.17  4757.5  456.99  4801.5  457.57  4865.0  455.77
  4900.6  457.63  4985.2  456.98  5002.1  448.80  5002.6  448.00  5008.8  448.80
  5021.0  451.00  5031.3  457.78  5036.9  458.57  5093.6  457.14  5259.5  457.46
  5519.3  457.85  5529.3  458.03  5638.7  459.80  5717.9  464.10  5847.0  466.96
#Mann=11,-1,0
  3414.1    0.16       0  3539.0    0.05       0  3559.7    0.16       0
  3665.5    0.05       0  4375.5    0.12       0  4706.8    0.16       0
  4757.5    0.12       0  5002.1    0.07       0  5008.8    0.12       0
  5259.5    0.07       0  5529.3    0.16       0
Bank Sta=4629.1,5519.3
Exp/Cntr=0.3,0.1

Chan Stop Cuts=-1