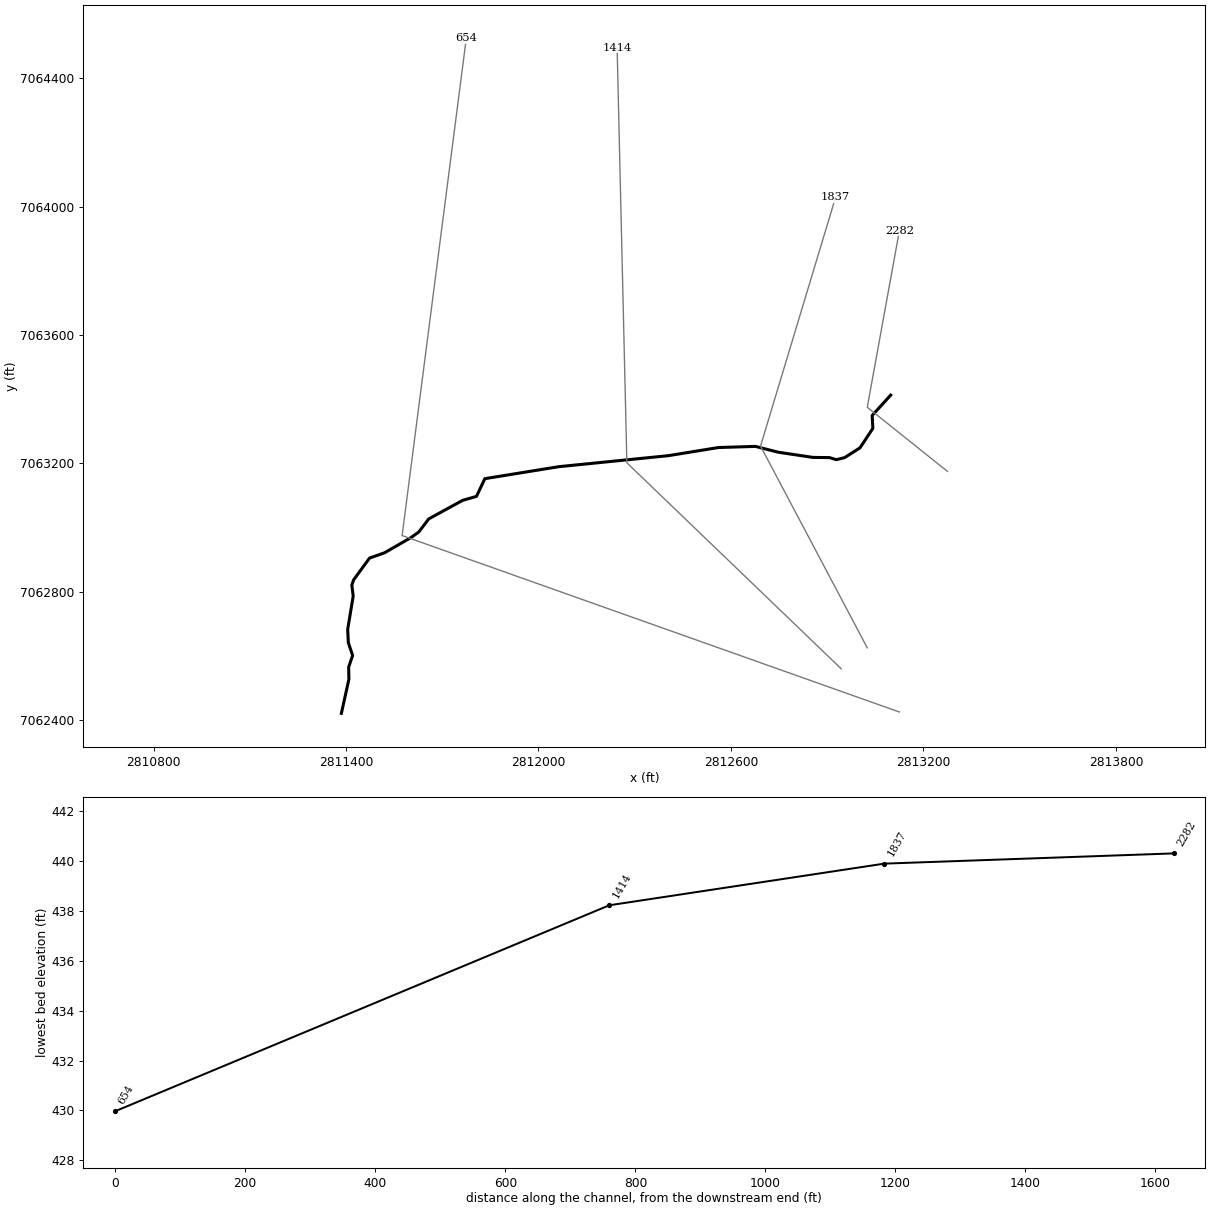
--- UNT 058 in LFCCL Watershed.prj (project) ---

Proj Title=UNT 058 in LFCCL Watershed Base Level Engineering
Current Plan=p01
Default Exp/Contr=0.3,0.1
English Units
Geom File=g01
Flow File=f01
Plan File=p01
BEGIN DESCRIPTION:
UNT 058 in LFCCL Watershed
END DESCRIPTION:

--- UNT 058 in LFCCL Watershed.p01 (plan) ---

Plan Title=Multiple Run
Short Identifier=Multiple
Geom File=g01
Flow File=f01
Subcritical Flow
K Sum by GR= 0
Std Step Tol= 0.01
Critical Tol= 0.01
Num of Std Step Trials= 20
Max Error Tol= 0.3
Flow Tol Ratio= 0.001
Split Flow NTrial= 30
Split Flow Tol= 0.02
Split Flow Ratio= 0.02
Log Output Level= 0
Friction Slope Method= 1
Unsteady Friction Slope Method= 2
Unsteady Bridges Friction Slope Method= 1
Parabolic Critical Depth
Global Vel Dist=  1 , 1 , 1
Global Log Level= 0
CheckData=True
Encroach Param= -1, 0, 0, 0
BEGIN DESCRIPTION:
Multiple Run
END DESCRIPTION:

--- UNT 058 in LFCCL Watershed.f01 (steady flow) ---

Flow Title=Multiple
Number of Profiles=7
Profile Names=10-year,25-year,50-year,1pct_min,100-year,1pct_plu,500-year
River Rch & RM= UNT 058 in LFCCL,Reach-1,2282
     755    1013    1222     731    1458    2909    2071
River Rch & RM= UNT 058 in LFCCL,Reach-1,654
     922    1252    1522     917    1829    3650    2638
Boundary for River Rch & Prof#=UNT 058 in LFCCL,Reach-1,1
Up Type=0
Dn Type=3
Dn Slope=0.005
Boundary for River Rch & Prof#=UNT 058 in LFCCL,Reach-1,2
Up Type=0
Dn Type=3
Dn Slope=0.005
Boundary for River Rch & Prof#=UNT 058 in LFCCL,Reach-1,3
Up Type=0
Dn Type=3
Dn Slope=0.005
Boundary for River Rch & Prof#=UNT 058 in LFCCL,Reach-1,4
Up Type=0
Dn Type=3
Dn Slope=0.005
Boundary for River Rch & Prof#=UNT 058 in LFCCL,Reach-1,5
Up Type=0
Dn Type=3
Dn Slope=0.005
Boundary for River Rch & Prof#=UNT 058 in LFCCL,Reach-1,6
Up Type=0
Dn Type=3
Dn Slope=0.005
Boundary for River Rch & Prof#=UNT 058 in LFCCL,Reach-1,7
Up Type=0
Dn Type=3
Dn Slope=0.005

--- UNT 058 in LFCCL Watershed.g01 (geometry) ---

Geom Title=Existing Conditions

River Reach=UNT 058 in LFCCL,Reach-1
Reach XY= 30
      2813097.91      7063412.74      2813040.25      7063349.34
      2813042.42      7063309.19      2813002.27      7063248.43
      2812954.53      7063218.05      2812928.48      7063211.54
      2812907.27      7063218.02      2812855.46      7063218.64
      2812746.94      7063234.92      2812676.39      7063253.01
      2812560.63      7063249.39      2812405.08      7063224.06
      2812063.22      7063189.70      2811832.89      7063152.37
      2811806.82      7063097.15      2811763.56      7063084.75
      2811657.77      7063026.82      2811627.06      7062986.23
      2811601.98      7062968.35      2811520.24      7062921.34
      2811473.43      7062904.84      2811423.76      7062836.87
      2811418.24      7062820.72      2811422.46      7062786.34
      2811405.29      7062682.74      2811407.37      7062640.79
      2811420.72      7062601.36      2811408.33      7062564.94
      2811409.05      7062527.03      2811385.59      7062420.71

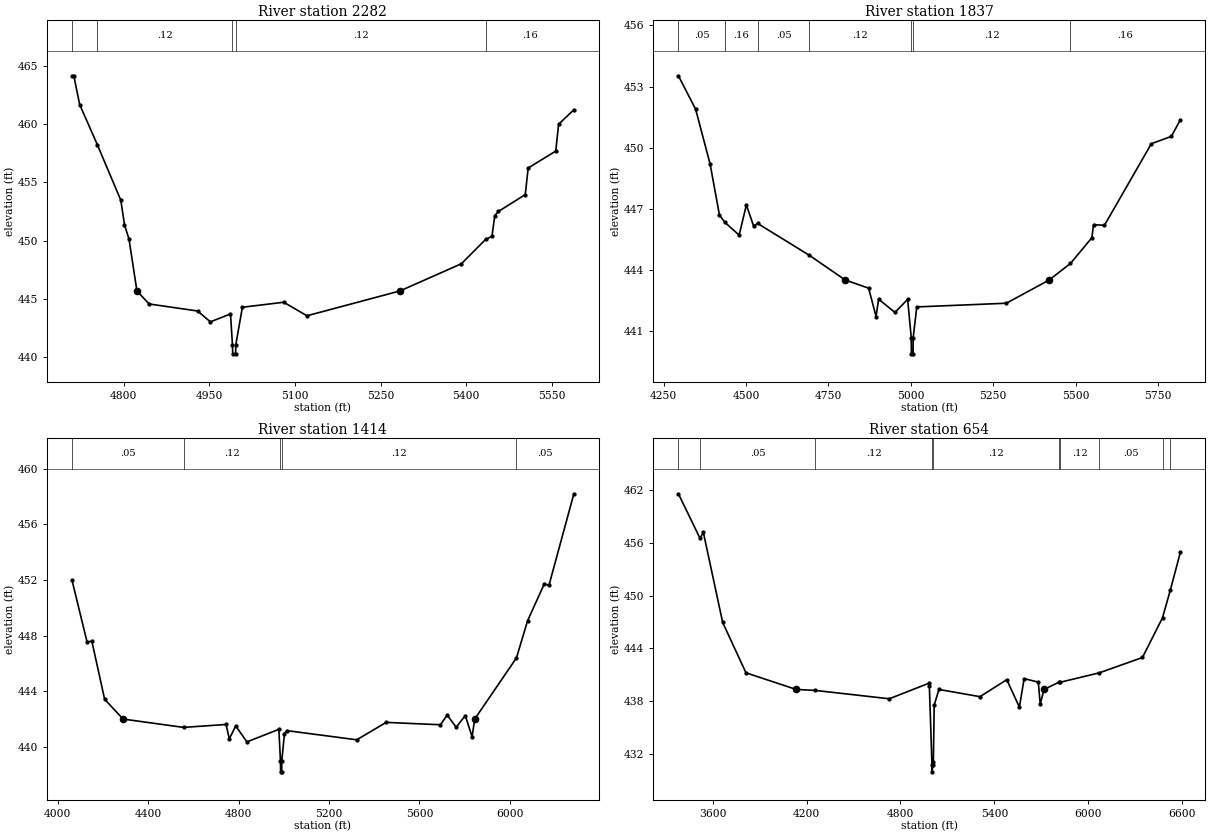
Type RM Length L Ch R = 1,2282,445,445,445
BEGIN DESCRIPTION:
UNT 058 in LFCCL Watershed 4.0
END DESCRIPTION:
XS GIS Cut Line= 3
      2813274.97      7063175.03      2813025.00      7063375.00
      2813124.99      7063924.97
#Sta/Elev= 30
  4709.5  464.13  4712.7  464.13  4723.1  461.66  4754.0  458.22  4795.1  453.47
  4801.5  451.38  4809.5  450.12  4823.3  445.70  4844.7  444.58  4929.6  443.98
  4952.0  443.05  4987.2  443.73  4990.6  441.11  4991.1  440.31  4996.1  440.31
  4996.6  441.11  5008.0  444.30  5080.4  444.73  5121.1  443.57  5284.1  445.70
  5391.7  448.03  5434.2  450.12  5445.1  450.37  5450.1  452.15  5456.5  452.51
  5503.5  453.95  5508.6  456.23  5556.9  457.68  5561.9  459.98  5588.6  461.22
#Mann=5,-1,0
  4709.5    0.16       0  4754.0    0.12       0  4990.6    0.07       0
  4996.6    0.12       0  5434.2    0.16       0
Bank Sta=4823.3,5284.1
Exp/Cntr=0.3,0.1

Type RM Length L Ch R = 1,1837,423,423,423
BEGIN DESCRIPTION:
UNT 058 in LFCCL Watershed 3.0
END DESCRIPTION:
XS GIS Cut Line= 3
      2813025.00      7062625.00      2812692.25      7063253.94
      2812926.49      7064030.43
#Sta/Elev= 30
  4295.0  453.53  4347.2  451.89  4391.2  449.20  4419.5  446.70  4436.3  446.34
  4479.2  445.72  4501.2  447.20  4523.2  446.16  4535.4  446.29  4692.2  444.73
  4800.9  443.52  4872.0  443.12  4894.6  441.73  4902.3  442.58  4952.0  441.93
  4990.4  442.57  5001.3  440.70  5001.8  439.90  5006.8  439.90  5007.3  440.70
  5018.1  442.20  5289.7  442.38  5419.9  443.52  5484.3  444.33  5549.2  445.59
  5554.4  446.23  5587.4  446.20  5729.7  450.20  5790.5  450.56  5817.6  451.37
#Mann=7,-1,0
  4295.0    0.05       0  4436.3    0.16       0  4535.4    0.05       0
  4692.2    0.12       0  5001.3    0.07       0  5007.3    0.12       0
  5484.3    0.16       0
Bank Sta=4800.9,5419.9
Exp/Cntr=0.3,0.1

Type RM Length L Ch R = 1,1414,760,760,760
BEGIN DESCRIPTION:
UNT 058 in LFCCL Watershed 2.0
END DESCRIPTION:
XS GIS Cut Line= 3
      2812943.95      7062559.53      2812275.58      7063201.86
      2812245.20      7064495.22
#Sta/Elev= 30
  4062.5  452.00  4129.4  447.55  4150.5  447.61  4207.1  443.44  4288.7  442.02
  4556.2  441.42  4744.5  441.63  4758.7  440.59  4787.0  441.53  4836.6  440.38
  4977.9  441.28  4985.1  439.03  4985.6  438.23  4990.6  438.23  4991.1  439.03
  5002.6  440.96  5012.6  441.19  5322.7  440.53  5452.8  441.78  5692.8  441.61
  5722.8  442.30  5762.8  441.43  5802.8  442.27  5832.9  440.75  5844.6  442.02
  6029.3  446.41  6078.3  449.07  6152.9  451.74  6173.0  451.61  6283.2  458.19
#Mann=5,-1,0
  4062.5    0.05       0  4556.2    0.12       0  4985.1    0.07       0
  4991.1    0.12       0  6029.3    0.05       0
Bank Sta=4288.7,5844.6
Exp/Cntr=0.3,0.1

Type RM Length L Ch R = 1,654,0,0,0
BEGIN DESCRIPTION:
UNT 058 in LFCCL Watershed 1.0
END DESCRIPTION:
XS GIS Cut Line= 3
      2813125.04      7062424.99      2811575.00      7062975.00
      2811775.00      7064525.02
#Sta/Elev= 30
  3380.7  461.56  3519.0  456.49  3539.9  457.19  3663.4  446.95  3812.4  441.22
  4133.5  439.33  4255.6  439.22  4728.3  438.27  4979.1  440.02  4984.4  439.76
  5001.1  430.77  5001.6  429.97  5007.3  430.77  5010.0  431.05  5015.3  437.55
  5045.6  439.33  5307.8  438.51  5479.2  440.44  5559.8  437.32  5590.1  440.56
  5680.8  440.16  5692.8  437.67  5717.5  439.33  5809.8  440.13  5816.9  440.13
  6071.1  441.22  6346.3  442.96  6474.6  447.48  6524.6  450.63  6588.3  454.89
#Mann=10,-1,0
  3380.7    0.16       0  3519.0    0.05       0  4255.6    0.12       0
  5001.1    0.07       0  5007.3    0.12       0  5809.8    0.05       0
  5816.9    0.12       0  6071.1    0.05       0  6474.6    0.16       0
  6524.6    0.05       0
Bank Sta=4133.5,5717.5
Exp/Cntr=0.3,0.1

Chan Stop Cuts=-1