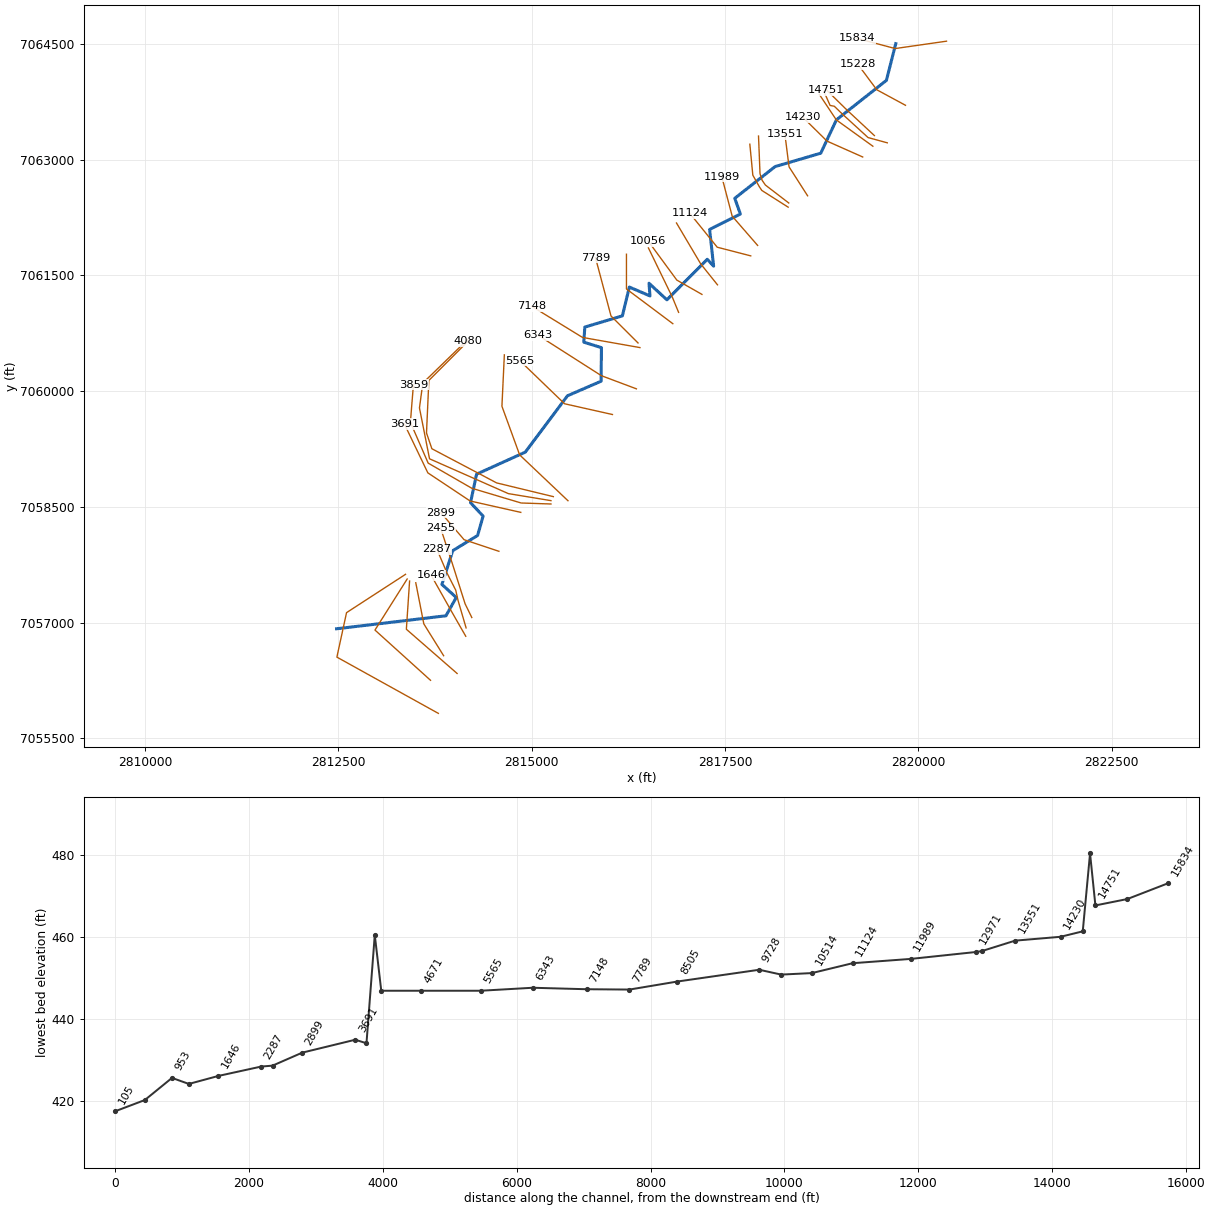
--- UNT 059 in LFCCL Watershed.prj (project) ---

Proj Title=UNT 059 in LFCCL Watershed Base Level Engineering
Current Plan=p01
Default Exp/Contr=0.3,0.1
English Units
Geom File=g01
Flow File=f01
Plan File=p01
BEGIN DESCRIPTION:
UNT 059 in LFCCL Watershed
END DESCRIPTION:

--- UNT 059 in LFCCL Watershed.p01 (plan) ---

Plan Title=Multiple Run
Short Identifier=Multiple
Geom File=g01
Flow File=f01
Subcritical Flow
K Sum by GR= 0
Std Step Tol= 0.01
Critical Tol= 0.01
Num of Std Step Trials= 20
Max Error Tol= 0.3
Flow Tol Ratio= 0.001
Split Flow NTrial= 30
Split Flow Tol= 0.02
Split Flow Ratio= 0.02
Log Output Level= 0
Friction Slope Method= 1
Unsteady Friction Slope Method= 2
Unsteady Bridges Friction Slope Method= 1
Parabolic Critical Depth
Global Vel Dist=  1 , 1 , 1
Global Log Level= 0
CheckData=True
Encroach Param= -1, 0, 0, 0
BEGIN DESCRIPTION:
Multiple Run
END DESCRIPTION:

--- UNT 059 in LFCCL Watershed.f01 (steady flow) ---

Flow Title=Multiple
Number of Profiles=7
Profile Names=10-year,25-year,50-year,1pct_min,100-year,1pct_plu,500-year
River Rch & RM= UNT 059 in LFCCL,Reach-1,15834
     486     633     748     440     877    1750    1201
River Rch & RM= UNT 059 in LFCCL,Reach-1,15228
     975    1325    1612     971    1937    3864    2791
River Rch & RM= UNT 059 in LFCCL,Reach-1,11989
    1106    1509    1841    1111    2217    4424    3212
River Rch & RM= UNT 059 in LFCCL,Reach-1,7148
    1245    1707    2089    1265    2523    5035    3675
River Rch & RM= UNT 059 in LFCCL,Reach-1,4671
    1517    2104    2593    1580    3152    6290    4656
Boundary for River Rch & Prof#=UNT 059 in LFCCL,Reach-1,1
Up Type=0
Dn Type=3
Dn Slope=0.005
Boundary for River Rch & Prof#=UNT 059 in LFCCL,Reach-1,2
Up Type=0
Dn Type=3
Dn Slope=0.005
Boundary for River Rch & Prof#=UNT 059 in LFCCL,Reach-1,3
Up Type=0
Dn Type=3
Dn Slope=0.005
Boundary for River Rch & Prof#=UNT 059 in LFCCL,Reach-1,4
Up Type=0
Dn Type=3
Dn Slope=0.005
Boundary for River Rch & Prof#=UNT 059 in LFCCL,Reach-1,5
Up Type=0
Dn Type=3
Dn Slope=0.005
Boundary for River Rch & Prof#=UNT 059 in LFCCL,Reach-1,6
Up Type=0
Dn Type=3
Dn Slope=0.005
Boundary for River Rch & Prof#=UNT 059 in LFCCL,Reach-1,7
Up Type=0
Dn Type=3
Dn Slope=0.005

--- UNT 059 in LFCCL Watershed.g01 (geometry) ---

Geom Title=Existing Conditions

River Reach=UNT 059 in LFCCL,Reach-1
Reach XY= 30
      2819708.73      7064504.28      2819587.82      7064028.47
      2818940.84      7063516.54      2818738.56      7063084.56
      2818147.97      7062910.90      2817626.25      7062499.83
      2817698.75      7062296.02      2817300.71      7062096.32
      2817352.69      7061620.32      2817270.62      7061709.23
      2816748.11      7061183.98      2816516.95      7061398.73
      2816529.26      7061234.59      2816262.54      7061349.49
      2816172.26      7060976.07      2815686.68      7060831.09
      2815673.00      7060635.49      2815901.43      7060564.36
      2815897.33      7060129.39      2815462.36      7059940.64
      2814916.60      7059210.22      2814286.03      7058924.34
      2814208.07      7058555.03      2814370.58      7058381.29
      2814299.55      7058129.62      2813978.37      7057933.44
      2813837.77      7057495.78      2814023.21      7057326.29
      2813889.92      7057089.14      2812475.59      7056920.71

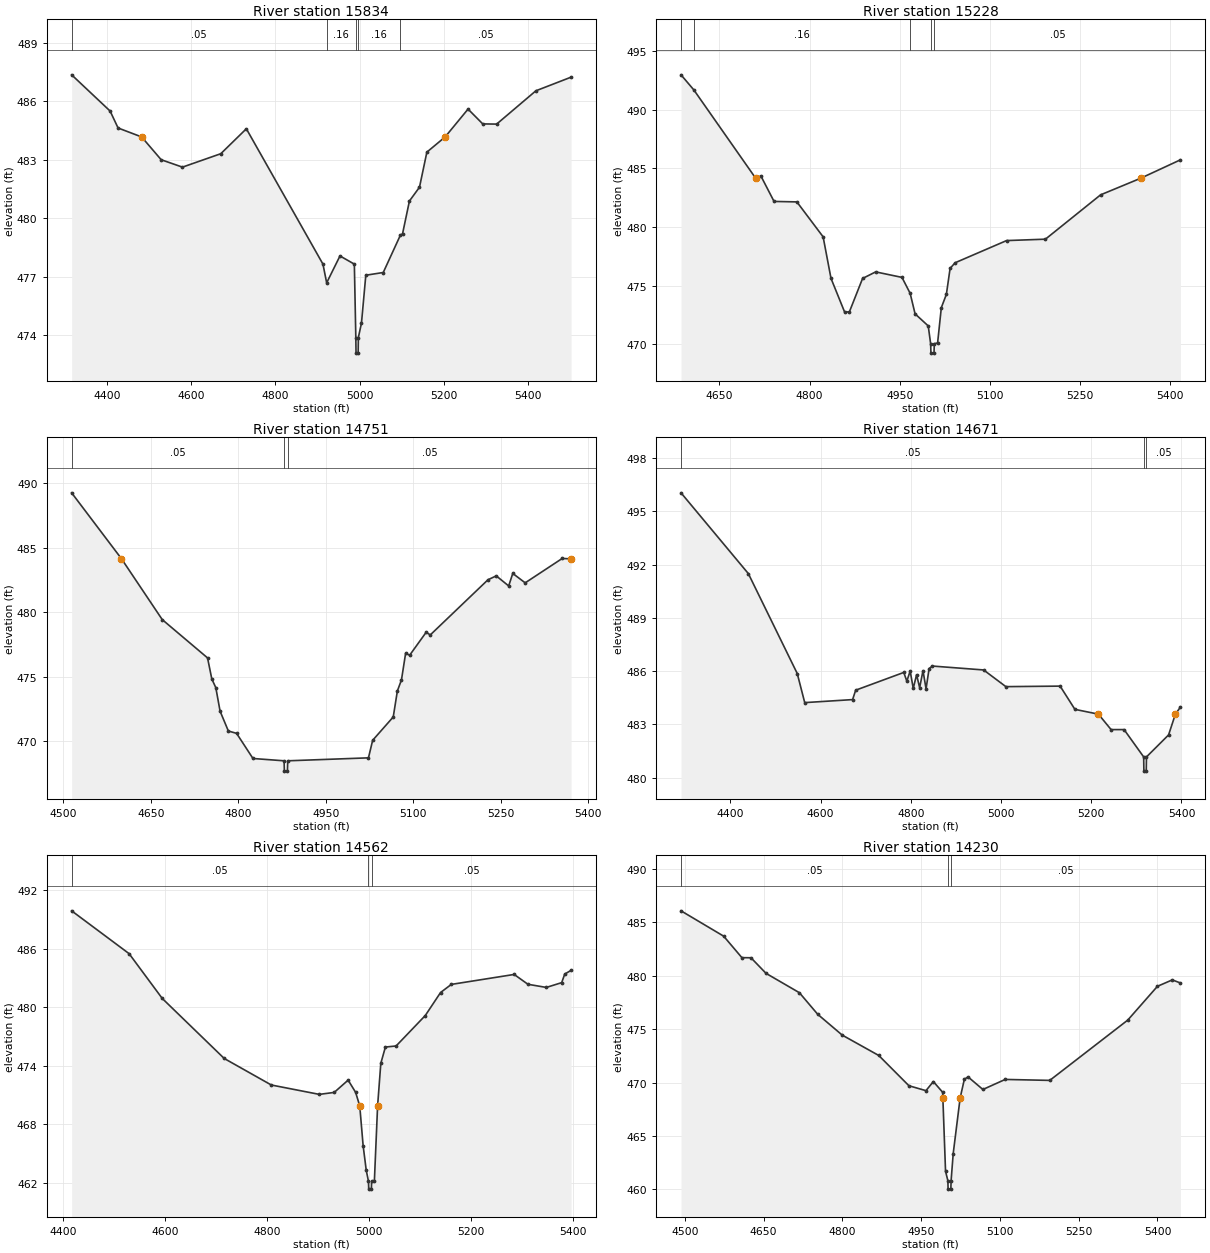
Type RM Length L Ch R = 1,15834,606,606,606
BEGIN DESCRIPTION:
UNT 059 in LFCCL Watershed 21.0
END DESCRIPTION:
XS GIS Cut Line= 3
      2820365.35      7064536.22      2819701.29      7064440.73
      2819204.31      7064573.11
#Sta/Elev= 30
  4316.6  487.36  4407.9  485.50  4426.8  484.63  4482.8  484.17  4529.1  483.00
  4579.6  482.62  4670.6  483.31  4731.2  484.59  4913.0  477.64  4921.8  476.68
  4953.4  478.06  4987.5  477.64  4991.0  473.87  4991.5  473.07  4996.5  473.07
  4997.0  473.87  5004.4  474.61  5014.7  477.07  5056.1  477.21  5096.6  479.12
  5101.9  479.20  5118.2  480.88  5142.1  481.59  5159.6  483.39  5202.9  484.17
  5257.3  485.60  5292.2  484.84  5325.2  484.83  5418.3  486.54  5501.8  487.24
#Mann=5,-1,0
  4316.6    0.05       0  4921.8    0.16       0  4991.0    0.07       0
  4997.0    0.16       0  5096.6    0.05       0
Bank Sta=4482.8,5202.9
Exp/Cntr=0.3,0.1

Type RM Length L Ch R = 1,15228,477,477,477
BEGIN DESCRIPTION:
XS3420A
END DESCRIPTION:
XS GIS Cut Line= 3
      2819834.60      7063705.40      2819462.88      7063906.74
      2819219.49      7064235.14
#Sta/Elev= 30
  4586.0  492.98  4607.4  491.69  4710.3  484.16  4719.0  484.35  4740.9  482.18
  4778.9  482.14  4822.6  479.16  4835.7  475.62  4858.5  472.73  4866.4  472.77
  4888.3  475.61  4910.1  476.17  4953.9  475.70  4967.5  474.34  4975.7  472.59
  4997.6  471.56  5001.6  470.04  5002.1  469.24  5007.2  469.24  5007.7  470.04
  5013.2  470.11  5019.4  473.12  5027.8  474.25  5034.0  476.47  5042.4  476.95
  5128.0  478.84  5192.7  478.96  5284.5  482.74  5351.4  484.16  5417.5  485.73
#Mann=5,-1,0
  4586.0    0.05       0  4607.4    0.16       0  4967.5    0.05       0
  5001.6   0.033       0  5007.7    0.05       0
Bank Sta=4710.3,5351.4
Exp/Cntr=0.3,0.1

Type RM Length L Ch R = 1,14751,80,80,80
BEGIN DESCRIPTION:
Mapping XS f44fe152
END DESCRIPTION:
XS GIS Cut Line= 3
      2819432.30      7063312.69      2819078.12      7063643.43
      2818812.49      7063903.86
#Sta/Elev= 30
  4514.2  489.26  4599.5  484.16  4669.6  479.43  4747.3  476.46  4754.6  474.83
  4761.5  474.15  4768.8  472.33  4783.0  470.79  4797.1  470.61  4825.2  468.66
  4878.6  468.48  4879.1  467.68  4884.3  467.68  4884.8  468.48  5023.3  468.71
  5030.5  470.07  5065.8  471.88  5072.9  473.90  5079.9  474.75  5087.0  476.81
  5094.0  476.67  5122.3  478.45  5129.3  478.24  5228.3  482.52  5242.5  482.82
  5263.8  482.04  5270.8  483.01  5292.1  482.28  5355.6  484.17  5370.8  484.14
#Mann=3,-1,0
  4514.2    0.05       0  4878.6    0.03       0  4884.8    0.05       0
Bank Sta=4599.5,5370.8
Exp/Cntr=0.3,0.1

Type RM Length L Ch R = 1,14671,109,109,109
BEGIN DESCRIPTION:
Mapping XS 273cb1d3
END DESCRIPTION:
XS GIS Cut Line= 6
      2819598.91      7063218.97      2819350.52      7063287.15
      2819015.62      7063593.95      2818914.06      7063692.91
      2818859.37      7063703.33      2818779.33      7063884.06
#Sta/Elev= 30
  4290.8  496.05  4440.0  491.50  4548.4  485.87  4565.0  484.23  4671.1  484.40
  4677.9  484.93  4784.5  485.93  4791.3  485.44  4798.7  486.01  4805.5  485.03
  4812.9  485.80  4819.7  485.07  4827.1  486.03  4833.9  485.01  4840.7  486.15
  4848.1  486.29  4961.5  486.07  5010.8  485.13  5131.0  485.16  5163.8  483.85
  5215.9  483.58  5244.0  482.71  5272.8  482.71  5316.2  481.17  5316.7  480.37
  5321.9  480.37  5322.4  481.17  5371.4  482.41  5386.5  483.58  5397.7  483.98
#Mann=3,-1,0
  4290.8    0.05       0  5316.2    0.03       0  5322.4    0.05       0
Bank Sta=5215.9,5386.5
Exp/Cntr=0.3,0.1

Type RM Length L Ch R = 1,14562,332,332,332
BEGIN DESCRIPTION:
XS3421A
END DESCRIPTION:
XS GIS Cut Line= 3
      2819412.56      7063174.89      2818940.14      7063515.65
      2818720.36      7063846.15
#Sta/Elev= 30
  4417.5  489.88  4530.2  485.49  4595.2  480.90  4716.7  474.75  4809.1  472.03
  4903.2  471.07  4932.4  471.27  4959.7  472.53  4974.4  471.28  4982.5  469.88
  4989.1  465.83  4995.2  463.30  4999.6  462.16  5000.1  461.36  5005.3  461.36
  5005.8  462.16  5011.2  462.20  5017.5  469.88  5023.8  474.25  5032.8  475.92
  5053.8  476.03  5111.0  479.15  5141.0  481.51  5162.1  482.34  5285.3  483.36
  5312.4  482.35  5348.4  482.03  5378.5  482.52  5384.5  483.40  5396.9  483.78
#Mann=3,-1,0
  4417.5    0.05       0  4999.6    0.03       0  5005.8    0.05       0
Bank Sta=4982.5,5017.5
Exp/Cntr=0.3,0.1

Type RM Length L Ch R = 1,14230,679,679,679
BEGIN DESCRIPTION:
XS3422A
END DESCRIPTION:
XS GIS Cut Line= 3
      2819280.92      7063035.49      2818820.10      7063240.73
      2818502.56      7063554.40
#Sta/Elev= 30
  4492.9  486.06  4574.1  483.69  4608.8  481.68  4626.1  481.67  4654.8  480.21
  4718.3  478.40  4753.2  476.38  4799.7  474.44  4869.4  472.53  4926.8  469.70
  4959.2  469.24  4973.3  470.09  4991.0  469.09  4991.4  468.56  4996.5  461.70
  5000.9  460.83  5001.4  460.03  5006.6  460.03  5007.1  460.83  5011.1  463.36
  5024.3  468.56  5032.3  470.30  5039.3  470.53  5067.6  469.35  5110.1  470.29
  5194.9  470.20  5343.4  475.84  5399.9  479.00  5428.2  479.60  5443.7  479.31
#Mann=3,-1,0
  4492.9    0.05       0  5000.9    0.03       0  5007.1    0.05       0
Bank Sta=4991.4,5024.3
Exp/Cntr=0.3,0.1

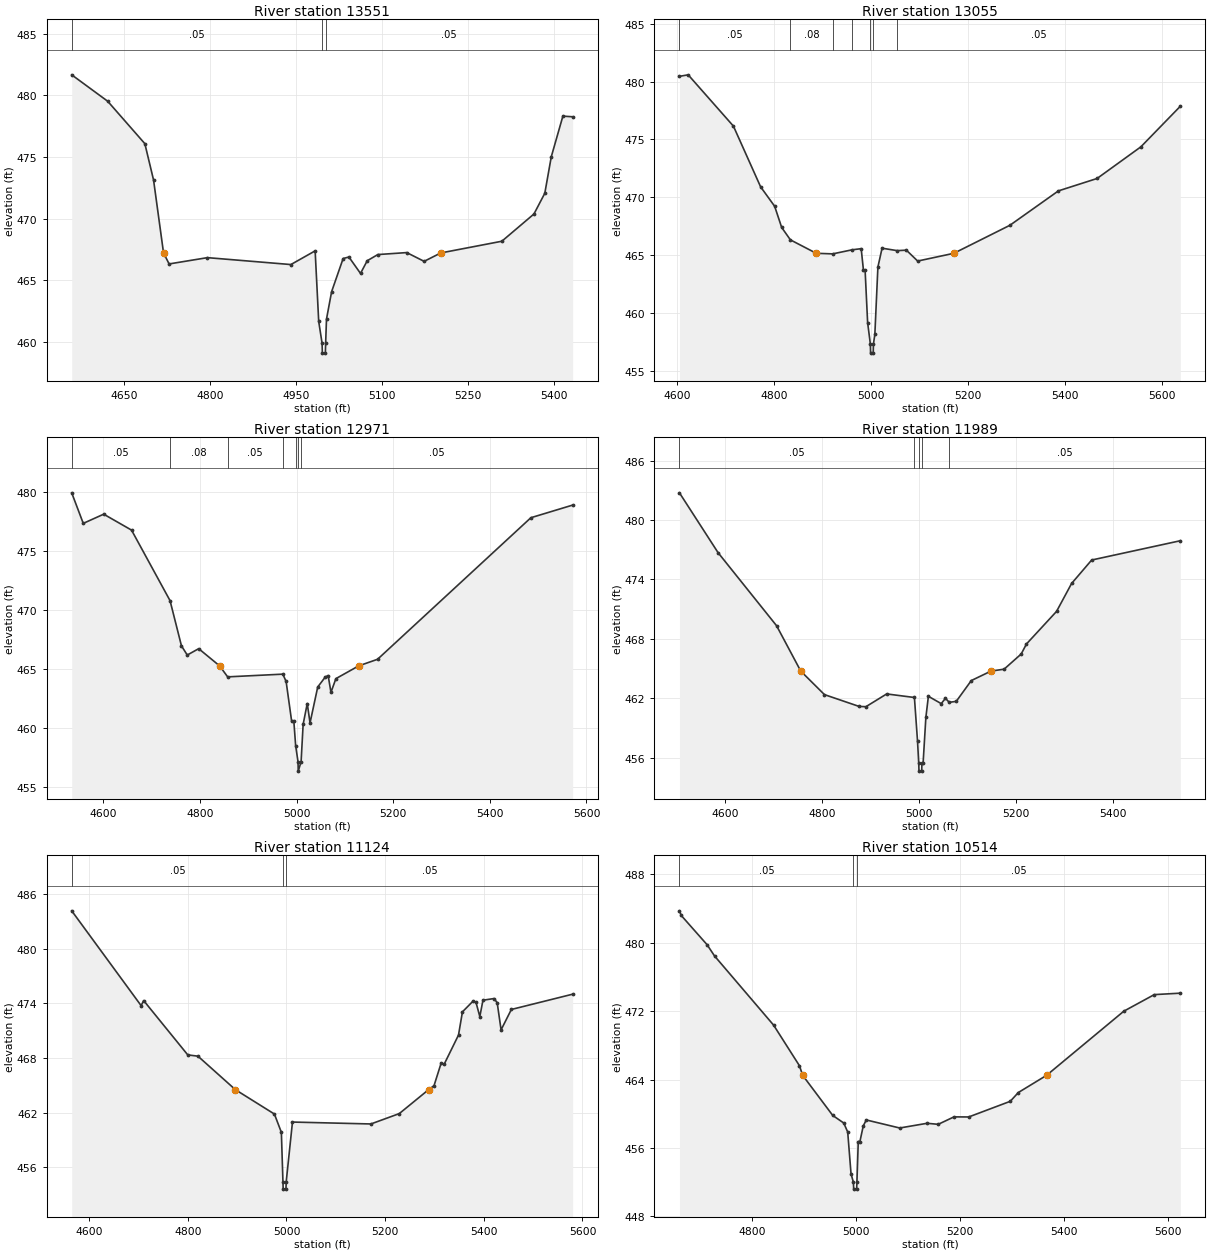
Type RM Length L Ch R = 1,13551,496,496,496
BEGIN DESCRIPTION:
XS3424A
END DESCRIPTION:
XS GIS Cut Line= 3
      2818568.39      7062532.15      2818328.33      7062907.72
      2818274.35      7063331.87
#Sta/Elev= 30
  4558.5  481.65  4621.2  479.51  4686.0  476.07  4701.2  473.12  4718.6  467.21
  4728.3  466.32  4795.1  466.83  4940.6  466.27  4982.9  467.38  4989.1  461.66
  4995.0  459.89  4995.5  459.09  5000.7  459.09  5001.2  459.89  5002.7  461.85
  5011.6  464.07  5031.7  466.76  5041.8  466.88  5062.0  465.55  5073.7  466.58
  5092.2  467.08  5142.6  467.24  5172.9  466.53  5201.9  467.21  5308.4  468.16
  5364.4  470.37  5383.3  472.05  5394.6  475.01  5414.8  478.30  5431.8  478.25
#Mann=3,-1,0
  4558.5    0.05       0  4995.0    0.03       0  5001.2    0.05       0
Bank Sta=4718.6,5201.9
Exp/Cntr=0.3,0.1

Type RM Length L Ch R = 1,13055,84,84,84
BEGIN DESCRIPTION:
XS3423A
END DESCRIPTION:
XS GIS Cut Line= 5
      2818324.48      7062439.17      2818022.43      7062671.52
      2817979.84      7062733.47      2817952.73      7062818.66
      2817933.37      7063306.52
#Sta/Elev= 30
  4604.1  480.45  4622.1  480.58  4715.5  476.15  4771.6  470.91  4800.6  469.23
  4815.1  467.40  4833.1  466.33  4886.5  465.17  4920.4  465.12  4960.3  465.47
  4979.2  465.57  4983.9  463.70  4987.3  463.70  4992.5  459.18  4998.1  457.35
  4998.6  456.55  5004.0  456.55  5004.5  457.35  5007.4  458.16  5013.7  463.98
  5022.3  465.61  5053.4  465.40  5072.5  465.44  5095.8  464.50  5170.5  465.17
  5286.2  467.59  5386.3  470.56  5466.1  471.63  5556.4  474.36  5638.0  477.87
#Mann=7,-1,0
  4604.1    0.05       0  4833.1    0.08       0  4920.4    0.05       0
  4960.3    0.08       0  4998.1    0.07       0  5004.5    0.08       0
  5053.4    0.05       0
Bank Sta=4886.5,5170.5
Exp/Cntr=0.3,0.1

Type RM Length L Ch R = 1,12971,982,982,982
BEGIN DESCRIPTION:
XS3425A
END DESCRIPTION:
XS GIS Cut Line= 5
      2818316.68      7062385.00      2817975.96      7062601.82
      2817944.99      7062648.28      2817859.80      7062799.30
      2817821.18      7063200.96
#Sta/Elev= 30
  4534.8  479.92  4558.7  477.33  4601.0  478.11  4658.6  476.76  4738.3  470.78
  4761.9  466.95  4773.9  466.17  4797.6  466.71  4840.9  465.25  4857.5  464.32
  4971.7  464.55  4978.5  463.93  4990.0  460.54  4994.5  460.54  4998.2  458.50
  5003.1  457.13  5003.6  456.33  5009.5  457.13  5013.7  460.29  5022.2  462.06
  5028.0  460.42  5043.9  463.46  5059.6  464.31  5065.5  464.43  5071.3  463.01
  5081.5  464.17  5128.6  465.25  5167.7  465.81  5485.0  477.81  5571.4  478.88
#Mann=7,-1,0
  4534.8    0.05       0  4738.3    0.08       0  4857.5    0.05       0
  4971.7    0.08       0  4998.2    0.05       0  5003.1    0.04       0
  5009.5    0.05       0
Bank Sta=4840.9,5128.6
Exp/Cntr=0.3,0.1

Type RM Length L Ch R = 1,11989,865,865,865
BEGIN DESCRIPTION:
XS3426A
END DESCRIPTION:
XS GIS Cut Line= 3
      2817921.78      7061889.31      2817592.62      7062268.81
      2817457.60      7062781.88
#Sta/Elev= 30
  4506.0  482.75  4585.7  476.70  4706.3  469.32  4756.1  464.74  4805.0  462.36
  4876.3  461.17  4890.5  461.14  4933.3  462.43  4990.5  462.07  4996.9  457.67
  4999.4  455.43  4999.9  454.63  5005.5  454.63  5006.0  455.43  5008.4  455.43
  5014.1  460.05  5019.3  462.19  5045.8  461.45  5054.5  461.99  5062.3  461.58
  5076.8  461.68  5107.8  463.78  5148.5  464.74  5175.4  464.93  5210.6  466.46
  5221.6  467.48  5283.6  470.77  5314.6  473.59  5356.0  475.96  5538.9  477.91
#Mann=5,-1,0
  4506.0    0.05       0  4990.5    0.07       0  4999.4    0.07       0
  5006.0    0.07       0  5062.3    0.05       0
Bank Sta=4756.1,5148.5
Exp/Cntr=0.3,0.1

Type RM Length L Ch R = 1,11124,610,610,610
BEGIN DESCRIPTION:
XS3427A
END DESCRIPTION:
XS GIS Cut Line= 3
      2817832.65      7061753.82      2817399.01      7061866.10
      2817042.76      7062307.54
#Sta/Elev= 30
  4564.8  484.17  4705.5  473.75  4710.6  474.31  4800.0  468.34  4820.6  468.20
  4896.5  464.52  4975.6  461.84  4989.7  459.83  4992.9  454.39  4993.4  453.59
  4999.0  453.59  4999.5  454.39  5012.2  460.96  5171.2  460.75  5228.7  461.89
  5288.1  464.52  5299.1  464.96  5313.5  467.43  5319.9  467.34  5348.7  470.52
  5356.7  473.07  5377.5  474.21  5384.0  474.14  5391.9  472.55  5398.3  474.35
  5420.6  474.53  5427.1  474.08  5435.0  471.09  5455.8  473.33  5580.0  475.01
#Mann=3,-1,0
  4564.8    0.05       0  4992.9    0.03       0  4999.5    0.05       0
Bank Sta=4896.5,5288.1
Exp/Cntr=0.3,0.1

Type RM Length L Ch R = 1,10514,458,458,458
BEGIN DESCRIPTION:
XS3428A
END DESCRIPTION:
XS GIS Cut Line= 3
      2817402.87      7061378.23      2817186.04      7061649.26
      2816872.38      7062179.78
#Sta/Elev= 30
  4660.2  483.73  4663.6  483.19  4713.3  479.77  4727.7  478.45  4841.3  470.36
  4890.9  465.62  4897.2  464.49  4955.0  459.80  4976.2  458.91  4983.8  457.86
  4990.2  452.96  4994.8  451.98  4995.3  451.18  5001.0  451.18  5001.5  451.98
  5004.1  456.75  5007.3  456.75  5013.7  458.57  5019.5  459.27  5083.8  458.33
  5136.5  458.88  5157.9  458.76  5188.2  459.63  5216.5  459.62  5296.4  461.45
  5312.0  462.48  5366.3  464.49  5514.8  471.99  5573.4  473.93  5623.6  474.10
#Mann=3,-1,0
  4660.2    0.05       0  4994.8    0.03       0  5001.5    0.05       0
Bank Sta=4897.2,5366.3
Exp/Cntr=0.3,0.1

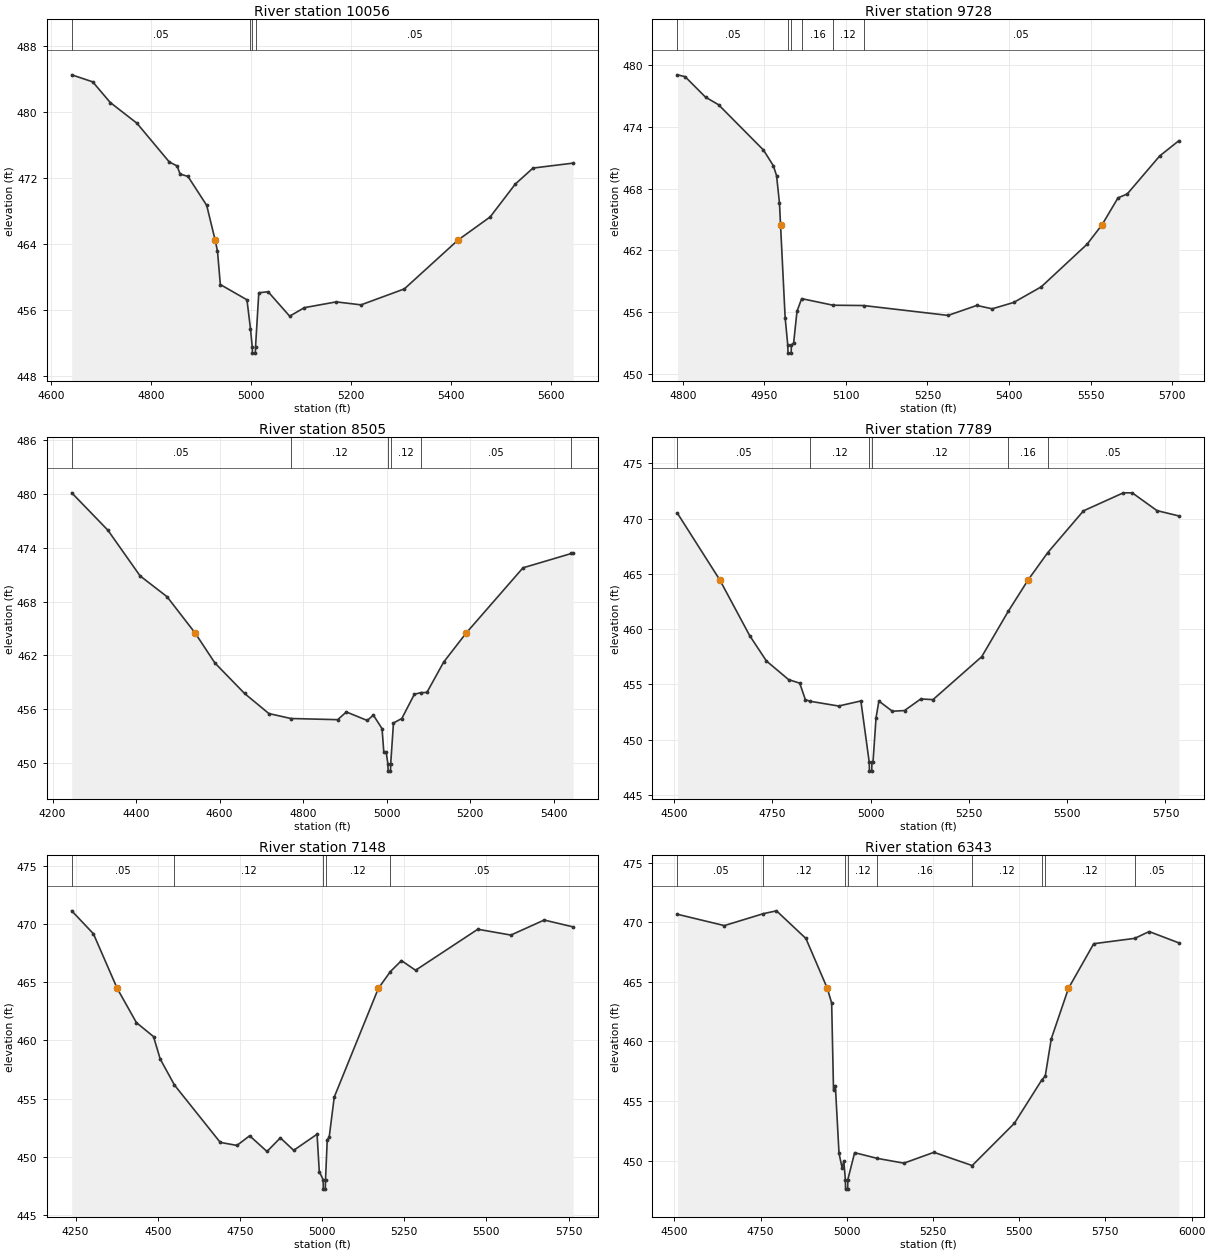
Type RM Length L Ch R = 1,10056,328,328,328
BEGIN DESCRIPTION:
XS3429A
END DESCRIPTION:
XS GIS Cut Line= 3
      2817201.51      7061254.31      2816876.27      7061440.16
      2816504.52      7061947.43
#Sta/Elev= 30
  4641.6  484.48  4683.6  483.63  4718.7  481.13  4772.0  478.63  4836.8  473.94
  4852.6  473.45  4858.4  472.48  4874.2  472.19  4911.7  468.69  4928.6  464.49
  4933.3  463.16  4939.0  459.11  4992.3  457.26  4999.3  453.78  5002.8  451.61
  5003.3  450.81  5009.0  450.81  5009.5  451.61  5016.0  458.11  5034.6  458.24
  5077.8  455.28  5107.1  456.31  5171.0  457.01  5220.6  456.65  5307.3  458.58
  5414.7  464.49  5479.1  467.29  5529.3  471.26  5564.8  473.20  5645.1  473.80
#Mann=4,-1,0
  4641.6    0.05       0  4999.3    0.16       0  5002.8    0.07       0
  5009.5    0.05       0
Bank Sta=4928.6,5414.7
Exp/Cntr=0.3,0.1

Type RM Length L Ch R = 1,9728,1223,1223,1223
BEGIN DESCRIPTION:
XS3430A
END DESCRIPTION:
XS GIS Cut Line= 3
      2816899.51      7061021.94      2816818.18      7061219.45
      2816509.21      7061856.70
#Sta/Elev= 30
  4790.3  479.06  4804.4  478.88  4841.9  476.89  4865.9  476.15  4948.5  471.74
  4966.6  470.22  4972.5  469.26  4977.9  466.57  4979.8  464.49  4988.3  455.44
  4993.1  452.79  4993.6  451.99  4999.3  451.99  4999.8  452.79  5003.9  452.97
  5010.1  456.07  5018.7  457.29  5076.4  456.65  5132.4  456.62  5287.9  455.66
  5340.7  456.63  5368.9  456.30  5408.5  456.92  5459.2  458.44  5543.5  462.59
  5571.1  464.49  5600.2  467.09  5617.2  467.47  5676.9  471.17  5712.1  472.65
#Mann=6,-1,0
  4790.3    0.05       0  4993.1    0.03       0  4999.8    0.05       0
  5018.7    0.16       0  5076.4    0.12       0  5132.4    0.05       0
Bank Sta=4979.8,5571.1
Exp/Cntr=0.3,0.1

Type RM Length L Ch R = 1,8505,716,716,716
BEGIN DESCRIPTION:
UNT 059 in LFCCL Watershed 11.0
END DESCRIPTION:
XS GIS Cut Line= 3
      2816825.02      7060874.98      2816225.00      7061325.00
      2816225.00      7061774.97
#Sta/Elev= 30
  4246.0  480.11  4332.5  475.95  4409.6  470.86  4474.2  468.54  4541.6  464.48
  4588.7  461.16  4659.6  457.77  4717.9  455.53  4770.5  454.98  4882.5  454.85
  4903.3  455.71  4953.3  454.76  4967.9  455.36  4988.7  453.85  4992.9  451.24
  4998.5  451.24  5002.7  449.92  5003.2  449.12  5008.9  449.12  5009.4  449.92
  5016.0  454.48  5036.0  454.98  5066.0  457.68  5081.6  457.86  5096.0  457.88
  5136.0  461.25  5189.7  464.48  5326.0  471.76  5442.1  473.36  5446.0  473.37
#Mann=6,-1,0
  4246.0    0.05       0  4770.5    0.12       0  5002.7    0.07       0
  5009.4    0.12       0  5081.6    0.05       0  5442.1    0.16       0
Bank Sta=4541.6,5189.7
Exp/Cntr=0.3,0.1

Type RM Length L Ch R = 1,7789,641,641,641
BEGIN DESCRIPTION:
UNT 059 in LFCCL Watershed 10.0
END DESCRIPTION:
XS GIS Cut Line= 3
      2816374.99      7060625.01      2816025.00      7060975.00
      2815824.61      7061729.59
#Sta/Elev= 30
  4508.3  470.49  4615.9  464.47  4692.1  459.42  4734.6  457.13  4791.1  455.44
  4819.4  455.12  4833.6  453.64  4844.5  453.49  4918.4  453.05  4975.0  453.51
  4996.3  447.96  4996.8  447.16  5002.6  447.16  5003.1  447.96  5005.8  447.96
  5013.6  451.99  5020.8  453.50  5055.0  452.58  5086.0  452.64  5127.4  453.69
  5158.5  453.63  5282.6  457.52  5349.8  461.61  5400.7  464.47  5450.4  466.93
  5541.3  470.71  5642.8  472.34  5665.4  472.34  5728.4  470.73  5784.0  470.25
#Mann=6,-1,0
  4508.3    0.05       0  4844.5    0.12       0  4996.3    0.07       0
  5003.1    0.12       0  5349.8    0.16       0  5450.4    0.05       0
Bank Sta=4615.9,5400.7
Exp/Cntr=0.3,0.1

Type RM Length L Ch R = 1,7148,805,805,805
BEGIN DESCRIPTION:
XS3431A
END DESCRIPTION:
XS GIS Cut Line= 3
      2816399.96      7060565.06      2815656.53      7060696.71
      2815000.00      7061100.00
#Sta/Elev= 30
  4238.3  471.12  4304.3  469.15  4376.5  464.47  4435.0  461.53  4487.1  460.33
  4507.4  458.41  4550.9  456.17  4690.2  451.25  4741.0  450.99  4779.6  451.82
  4832.4  450.47  4873.0  451.64  4913.6  450.57  4984.7  451.95  4991.5  448.75
  5003.3  448.04  5003.8  447.24  5009.8  447.24  5010.4  448.04  5015.7  451.47
  5021.6  451.70  5037.0  455.14  5171.3  464.47  5207.9  465.91  5241.5  466.85
  5284.4  466.02  5473.8  469.54  5574.4  469.04  5675.8  470.33  5763.8  469.74
#Mann=5,-1,0
  4238.3    0.05       0  4550.9    0.12       0  5003.3    0.07       0
  5010.4    0.12       0  5207.9    0.05       0
Bank Sta=4376.5,5171.3
Exp/Cntr=0.3,0.1

Type RM Length L Ch R = 1,6343,778,778,778
BEGIN DESCRIPTION:
XS3432A
END DESCRIPTION:
XS GIS Cut Line= 3
      2816353.54      7060030.68      2815900.48      7060201.07
      2815083.44      7060723.82
#Sta/Elev= 30
  4508.9  470.67  4644.9  469.72  4757.8  470.72  4796.1  470.96  4881.4  468.64
  4943.4  464.46  4956.1  463.22  4961.5  455.89  4966.8  456.29  4977.4  450.62
  4986.3  449.39  4991.4  449.96  4995.9  448.40  4996.4  447.60  5002.5  447.60
  5003.0  448.40  5022.7  450.66  5088.5  450.18  5165.6  449.78  5252.7  450.69
  5363.6  449.58  5486.1  453.13  5565.8  456.78  5575.4  457.08  5593.0  460.22
  5642.9  464.46  5716.1  468.20  5835.1  468.65  5876.8  469.22  5962.9  468.27
#Mann=9,-1,0
  4508.9    0.05       0  4757.8    0.12       0  4995.9    0.07       0
  5003.0    0.12       0  5088.5    0.16       0  5363.6    0.12       0
  5565.8    0.16       0  5575.4    0.12       0  5835.1    0.05       0
Bank Sta=4943.4,5642.9
Exp/Cntr=0.3,0.1

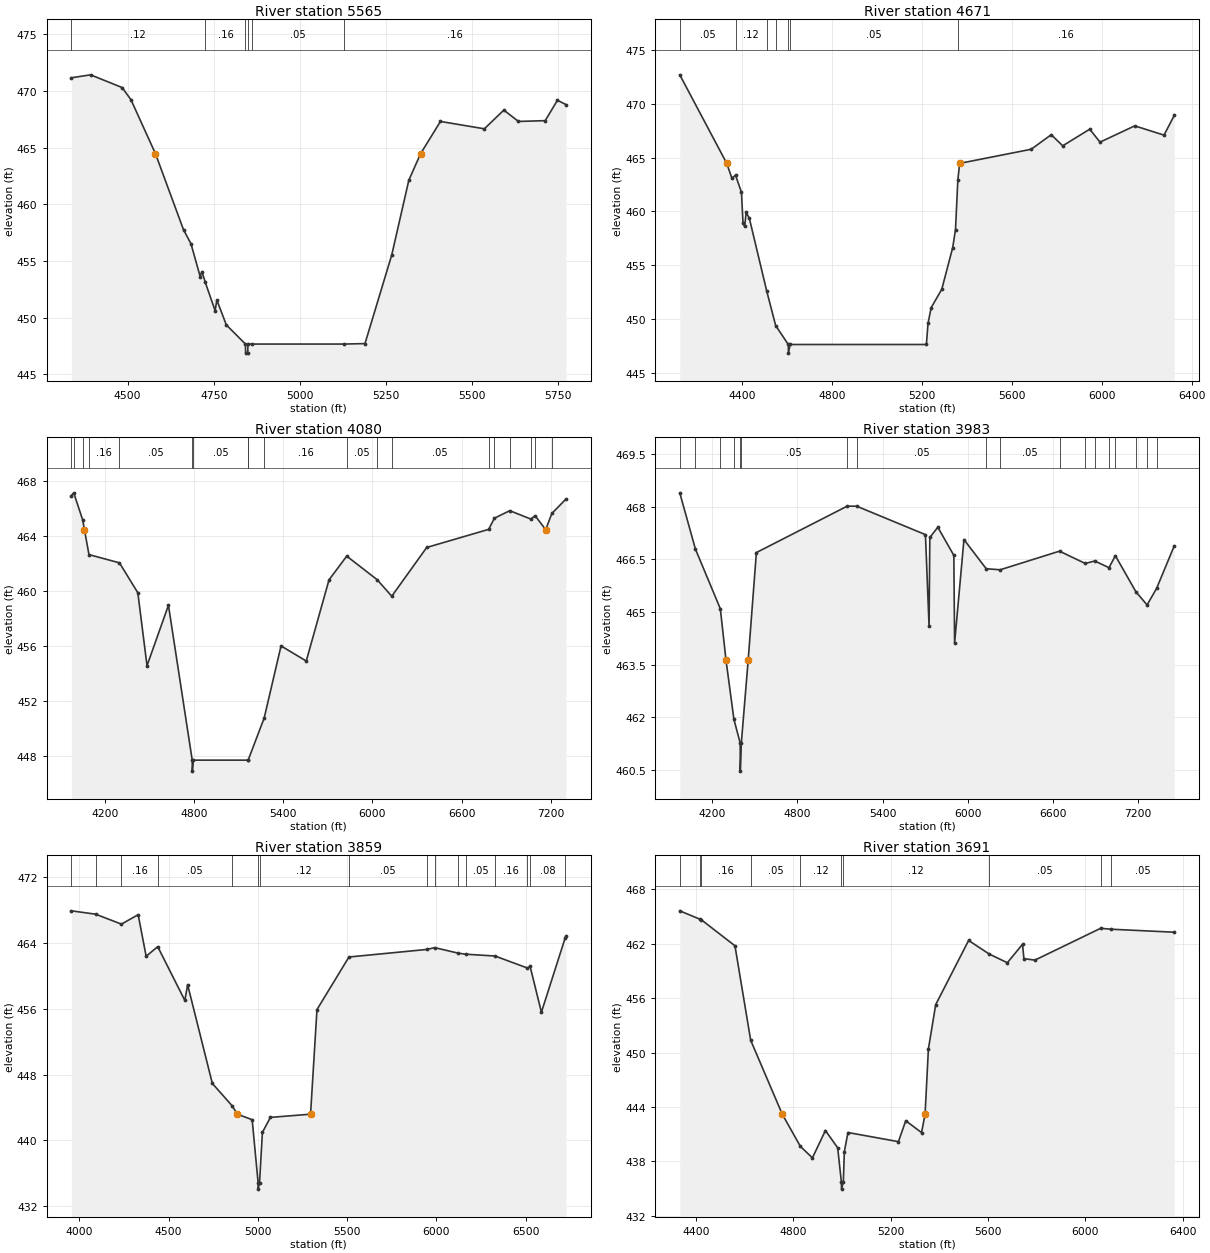
Type RM Length L Ch R = 1,5565,894,894,894
BEGIN DESCRIPTION:
XS3433A
END DESCRIPTION:
XS GIS Cut Line= 3
      2816043.74      7059697.68      2815424.20      7059837.08
      2814848.60      7060393.36
#Sta/Elev= 30
  4336.9  471.15  4392.5  471.41  4484.2  470.29  4509.9  469.21  4580.9  464.46
  4662.4  457.75  4684.1  456.51  4710.8  453.62  4715.9  454.05  4725.7  453.10
  4754.1  450.62  4759.2  451.55  4786.6  449.36  4842.2  447.67  4842.7  446.87
  4848.8  446.87  4849.4  447.67  4860.0  447.67  5127.6  447.67  5189.2  447.71
  5266.9  455.53  5316.5  462.12  5350.7  464.46  5408.3  467.30  5535.7  466.65
  5592.3  468.30  5634.7  467.30  5712.4  467.37  5747.9  469.17  5772.4  468.79
#Mann=6,-1,0
  4336.9    0.12       0  4725.7    0.16       0  4842.2   0.033       0
  4849.4    0.16       0  4860.0    0.05       0  5127.6    0.16       0
Bank Sta=4580.9,5350.7
Exp/Cntr=0.3,0.1

Type RM Length L Ch R = 1,4671,591,591,591
BEGIN DESCRIPTION:
XS3434A
END DESCRIPTION:
XS GIS Cut Line= 4
      2815468.39      7058580.49      2814843.37      7059174.26
      2814614.21      7059804.47      2814645.43      7060470.56
#Sta/Elev= 30
  4123.1  472.67  4332.1  464.46  4355.0  463.08  4371.1  463.37  4397.5  461.78
  4404.4  458.93  4411.7  458.61  4418.5  459.92  4432.7  459.36  4509.6  452.65
  4549.6  449.43  4605.9  447.67  4606.5  446.87  4613.8  447.67  5220.1  447.67
  5227.3  449.62  5241.4  451.09  5288.5  452.79  5337.1  456.65  5349.6  458.33
  5360.0  462.91  5368.0  464.46  5686.3  465.77  5775.5  467.12  5826.5  466.09
  5946.6  467.63  5992.4  466.43  6146.8  467.94  6277.0  467.08  6322.6  468.90
#Mann=7,-1,0
  4123.1    0.05       0  4371.1    0.12       0  4509.6    0.16       0
  4549.6    0.05       0  4605.9   0.033       0  4613.8    0.05       0
  5360.0    0.16       0
Bank Sta=4332.1,5368
Exp/Cntr=0.3,0.1

Type RM Length L Ch R = 1,4080,97,97,97
BEGIN DESCRIPTION:
XS3436A
END DESCRIPTION:
XS GIS Cut Line= 6
      2815279.18      7058633.45      2814545.63      7058811.41
      2813707.96      7059254.12      2813638.51      7059458.11
      2813668.89      7060139.53      2814177.47      7060648.85
#Sta/Elev= 30
  3976.5  466.94  3992.3  467.14  4052.9  465.15  4064.0  464.46  4094.8  462.64
  4299.8  462.04  4423.3  459.86  4485.0  454.55  4629.1  458.95  4788.9  447.67
  4789.6  446.87  4797.0  447.67  5164.1  447.67  5165.0  447.67  5272.9  450.74
  5386.1  455.99  5555.7  454.89  5708.7  460.80  5827.9  462.53  6032.8  460.81
  6130.6  459.61  6365.6  463.16  6782.4  464.48  6820.6  465.29  6924.0  465.84
  7065.6  465.23  7094.5  465.47  7165.8  464.46  7207.1  465.64  7301.4  466.68
#Mann=19,-1,0
  3976.5    0.05       0  3992.3    0.16       0  4052.9    0.12       0
  4094.8    0.16       0  4299.8    0.05       0  4788.9   0.033       0
  4797.0    0.05       0  5164.1    0.08       0  5165.0    0.05       0
  5272.9    0.16       0  5827.9    0.05       0  6032.8    0.16       0
  6130.6    0.05       0  6782.4    0.08       0  6820.6    0.05       0
  6924.0    0.08       0  7065.6    0.05       0  7094.5    0.08       0
  7207.1    0.05       0
Bank Sta=4064,7165.8
Exp/Cntr=0.3,0.1

Type RM Length L Ch R = 1,3983,124,124,124
BEGIN DESCRIPTION:
XS3435A
END DESCRIPTION:
XS GIS Cut Line= 6
      2815248.78      7058581.37      2814697.54      7058672.52
      2813677.57      7059123.91      2813547.37      7059783.63
      2813590.77      7060104.81      2814168.81      7060667.32
#Sta/Elev= 30
  3972.1  468.39  4082.3  466.79  4257.8  465.09  4297.7  463.63  4353.7  461.94
  4397.6  461.27  4398.3  460.47  4405.7  461.27  4453.9  463.63  4511.7  466.69
  5150.8  468.01  5217.7  468.01  5702.3  467.20  5727.8  464.59  5733.1  467.12
  5789.5  467.41  5902.2  466.61  5907.5  464.11  5973.4  467.06  6130.2  466.23
  6228.3  466.20  6646.3  466.73  6827.5  466.38  6894.6  466.45  6995.0  466.26
  7039.8  466.60  7184.9  465.57  7263.1  465.20  7330.1  465.67  7454.4  466.88
#Mann=18,-1,0
  3972.1    0.16       0  4082.3    0.12       0  4257.8    0.16       0
  4353.7    0.05       0  4397.6    0.04       0  4405.7    0.05       0
  5150.8    0.08       0  5217.7    0.05       0  6130.2    0.16       0
  6228.3    0.05       0  6646.3    0.08       0  6827.5    0.05       0
  6894.6    0.08       0  6995.0    0.05       0  7039.8    0.08       0
  7184.9    0.05       0  7263.1    0.08       0  7330.1    0.05       0
Bank Sta=4297.7,4453.9
Exp/Cntr=0.3,0.1

Type RM Length L Ch R = 1,3859,168,168,168
BEGIN DESCRIPTION:
XS3437A
END DESCRIPTION:
XS GIS Cut Line= 6
      2815248.76      7058537.97      2814862.47      7058550.99
      2814224.45      7058741.97      2813660.21      7059067.49
      2813430.18      7059597.00      2813469.11      7060081.54
#Sta/Elev= 30
  3955.3  467.93  4091.2  467.52  4235.5  466.31  4329.3  467.46  4373.9  462.40
  4438.8  463.57  4590.7  457.02  4606.2  458.94  4744.7  446.92  4855.5  444.20
  4884.9  443.18  4967.7  442.51  5000.9  434.86  5001.6  434.06  5009.0  434.86
  5025.0  440.97  5069.9  442.79  5294.7  443.18  5330.6  455.91  5509.7  462.31
  5946.1  463.23  5990.2  463.45  6123.1  462.77  6164.2  462.65  6327.7  462.43
  6509.2  460.97  6524.3  461.16  6587.6  455.59  6721.0  464.66  6724.6  464.81
#Mann=16,-1,0
  3955.3    0.16       0  4091.2    0.12       0  4235.5    0.16       0
  4438.8    0.05       0  4855.5    0.12       0  5000.9    0.07       0
  5009.0    0.12       0  5509.7    0.05       0  5946.1    0.08       0
  5990.2    0.05       0  6123.1    0.08       0  6164.2    0.05       0
  6327.7    0.16       0  6509.2    0.05       0  6524.3    0.08       0
  6721.0    0.05       0
Bank Sta=4884.9,5294.7
Exp/Cntr=0.3,0.1

Type RM Length L Ch R = 1,3691,792,792,792
BEGIN DESCRIPTION:
XS3438A
END DESCRIPTION:
XS GIS Cut Line= 4
      2814858.09      7058429.47      2814202.75      7058577.03
      2813655.87      7058941.62      2813352.04      7059575.33
#Sta/Elev= 30
  4333.7  465.64  4416.1  464.72  4421.0  464.68  4560.5  461.78  4625.1  451.35
  4754.7  443.20  4829.3  439.64  4878.7  438.37  4932.2  441.39  4982.6  439.48
  4997.7  435.72  4998.4  434.92  5005.8  435.72  5009.8  439.04  5024.8  441.17
  5232.1  440.16  5262.2  442.47  5327.2  441.16  5341.7  443.20  5355.3  450.39
  5385.4  455.29  5520.6  462.37  5605.2  460.87  5679.7  459.91  5742.1  461.95
  5747.7  460.36  5793.0  460.20  6062.9  463.71  6106.0  463.61  6365.5  463.28
#Mann=10,-1,0
  4333.7    0.16       0  4416.1    0.05       0  4421.0    0.16       0
  4625.1    0.05       0  4829.3    0.12       0  4997.7    0.07       0
  5005.8    0.12       0  5605.2    0.05       0  6062.9    0.08       0
  6106.0    0.05       0
Bank Sta=4754.7,5341.7
Exp/Cntr=0.3,0.1

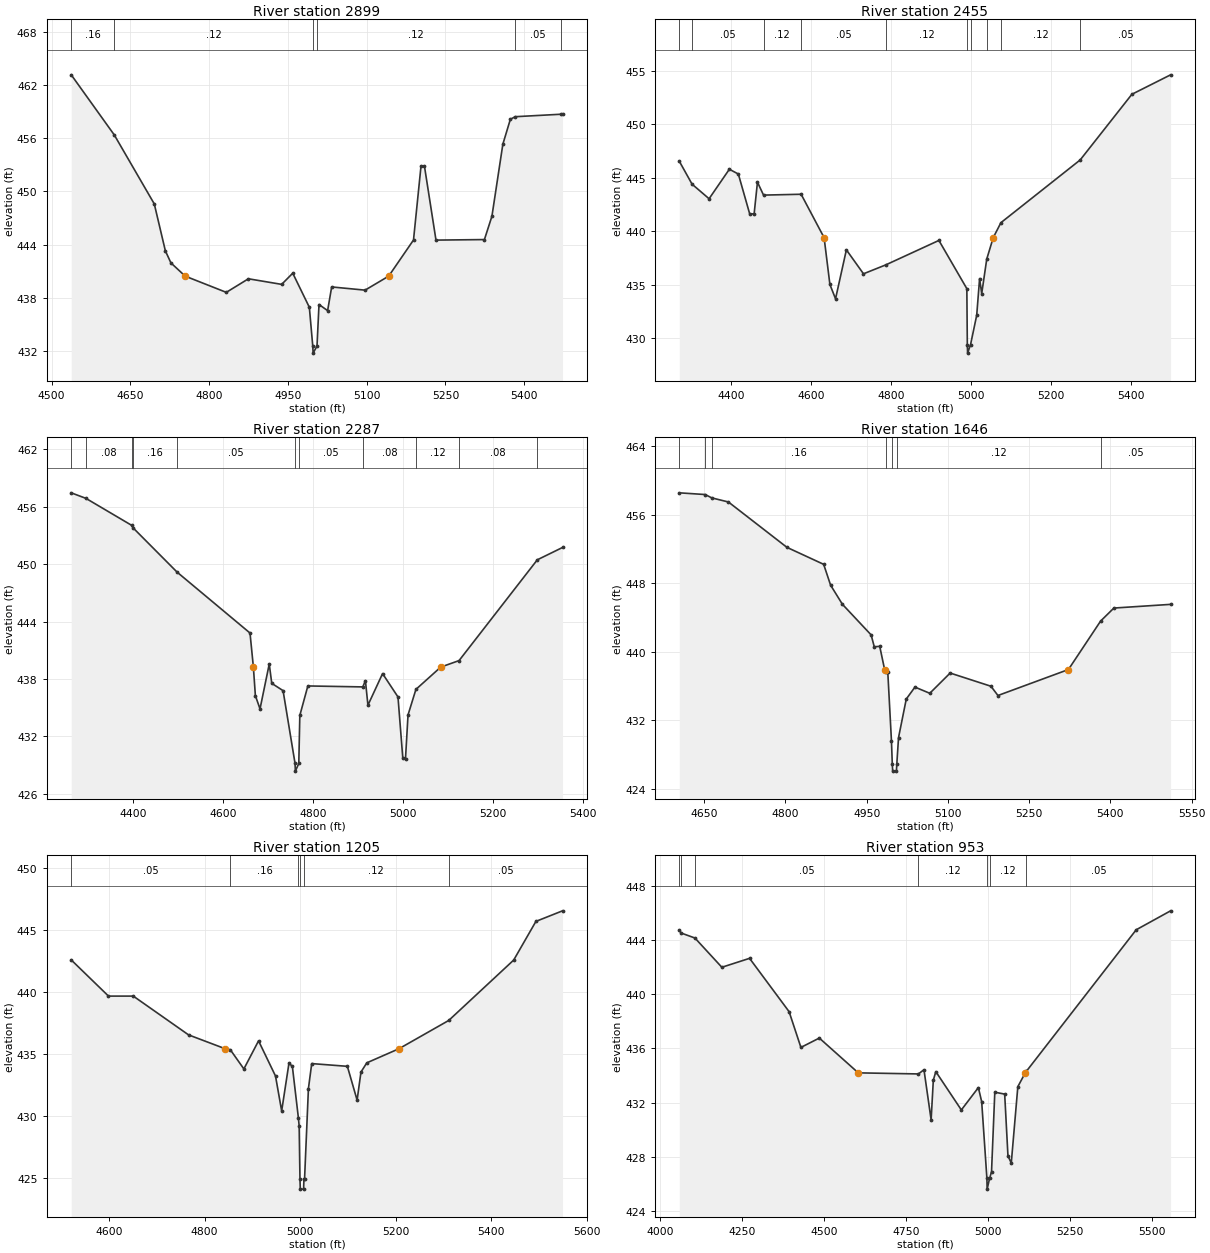
Type RM Length L Ch R = 1,2899,444,444,444
BEGIN DESCRIPTION:
UNT 059 in LFCCL Watershed 3.0
END DESCRIPTION:
XS GIS Cut Line= 3
      2814575.02      7057924.99      2814125.00      7058075.00
      2813825.03      7058424.97
#Sta/Elev= 30
  4537.5  463.14  4619.4  456.37  4695.6  448.59  4716.7  443.30  4727.3  441.94
  4754.4  440.45  4832.7  438.62  4874.8  440.15  4938.1  439.52  4959.2  440.78
  4990.8  436.94  4997.3  432.57  4998.0  431.77  5005.4  432.57  5009.2  437.25
  5025.6  436.56  5033.3  439.23  5096.9  438.87  5141.9  440.45  5189.1  444.52
  5203.4  452.86  5210.0  452.82  5231.9  444.51  5324.1  444.57  5338.4  447.20
  5359.2  455.32  5373.5  458.13  5382.8  458.42  5470.6  458.70  5472.8  458.70
#Mann=6,-1,0
  4537.5    0.16       0  4619.4    0.12       0  4997.3    0.07       0
  5005.4    0.12       0  5382.8    0.05       0  5470.6    0.16       0
Bank Sta=4754.4,5141.9
Exp/Cntr=0.3,0.1

Type RM Length L Ch R = 1,2455,168,168,168
BEGIN DESCRIPTION:
XS3441A
END DESCRIPTION:
XS GIS Cut Line= 4
      2814224.45      7057066.62      2814137.64      7057244.57
      2813977.05      7057752.38      2813820.81      7058225.45
#Sta/Elev= 30
  4269.5  446.55  4301.5  444.40  4344.0  443.04  4394.7  445.80  4417.2  445.35
  4445.7  441.61  4456.7  441.63  4465.0  444.59  4480.2  443.38  4574.2  443.46
  4631.7  439.40  4646.2  435.02  4660.3  433.68  4687.4  438.26  4730.2  436.02
  4785.7  436.85  4918.8  439.14  4988.7  434.63  4989.9  429.40  4990.6  428.60
  4998.0  429.40  5013.4  432.15  5020.6  435.57  5025.9  434.17  5038.5  437.40
  5054.7  439.40  5073.9  440.80  5272.2  446.67  5401.5  452.81  5498.3  454.63
#Mann=10,-1,0
  4269.5    0.16       0  4301.5    0.05       0  4480.2    0.12       0
  4574.2    0.05       0  4785.7    0.12       0  4989.9    0.07       0
  4998.0    0.12       0  5038.5    0.08       0  5073.9    0.12       0
  5272.2    0.05       0
Bank Sta=4631.7,5054.7
Exp/Cntr=0.3,0.1

Type RM Length L Ch R = 1,2287,641,641,641
BEGIN DESCRIPTION:
XS3442A
END DESCRIPTION:
XS GIS Cut Line= 5
      2814150.67      7056932.04      2814046.50      7057287.97
      2814016.12      7057422.52      2813903.27      7057643.87
      2813773.49      7057951.02
#Sta/Elev= 30
  4263.0  457.46  4295.7  456.88  4396.9  454.07  4400.3  453.80  4498.1  449.17
  4659.9  442.81  4667.4  439.25  4671.8  436.27  4682.1  434.88  4702.6  439.57
  4708.2  437.55  4733.3  436.79  4759.9  429.18  4760.6  428.38  4768.2  429.18
  4770.5  434.20  4788.3  437.28  4910.3  437.18  4916.1  437.83  4921.7  435.27
  4954.2  438.57  4988.4  436.13  4999.1  429.75  5005.1  429.69  5010.7  434.25
  5028.2  436.92  5083.3  439.25  5124.0  439.93  5297.7  450.46  5353.7  451.75
#Mann=11,-1,0
  4263.0    0.05       0  4295.7    0.08       0  4396.9    0.05       0
  4400.3    0.16       0  4498.1    0.05       0  4759.9    0.07       0
  4768.2    0.05       0  4910.3    0.08       0  5028.2    0.12       0
  5124.0    0.08       0  5297.7    0.05       0
Bank Sta=4667.4,5083.3
Exp/Cntr=0.3,0.1

Type RM Length L Ch R = 1,1646,441,441,441
BEGIN DESCRIPTION:
XS3440A
END DESCRIPTION:
XS GIS Cut Line= 3
      2814146.31      7056823.59      2813955.35      7057157.76
      2813699.64      7057612.85
#Sta/Elev= 30
  4604.2  458.55  4652.0  458.35  4664.2  457.96  4694.9  457.48  4802.9  452.19
  4870.7  450.21  4883.5  447.78  4905.3  445.55  4958.3  441.98  4964.1  440.60
  4974.2  440.64  4983.2  437.94  4985.5  437.61  4989.1  437.61  4995.8  429.65
  4997.4  426.89  4998.1  426.09  5005.0  426.09  5005.7  426.89  5008.9  430.00
  5023.2  434.50  5039.2  435.89  5066.6  435.17  5104.2  437.53  5179.5  435.99
  5192.4  434.91  5322.5  437.94  5381.9  443.59  5406.4  445.11  5511.1  445.54
#Mann=7,-1,0
  4604.2    0.16       0  4652.0    0.05       0  4664.2    0.16       0
  4985.5    0.12       0  4997.4    0.07       0  5005.7    0.12       0
  5381.9    0.05       0
Bank Sta=4983.2,5322.5
Exp/Cntr=0.3,0.1

Type RM Length L Ch R = 1,1205,252,252,252
BEGIN DESCRIPTION:
XS3439A
END DESCRIPTION:
XS GIS Cut Line= 3
      2813859.89      7056571.79      2813603.79      7056984.15
      2813499.80      7057517.09
#Sta/Elev= 30
  4520.8  442.58  4598.8  439.67  4650.7  439.67  4766.4  436.55  4842.7  435.44
  4853.9  435.35  4882.2  433.81  4912.9  436.07  4948.4  433.24  4961.3  430.43
  4976.6  434.28  4983.7  434.01  4996.4  429.84  4997.9  429.22  4999.6  424.94
  5000.3  424.14  5007.2  424.14  5007.9  424.94  5009.2  424.94  5017.3  432.23
  5024.2  434.24  5098.8  434.02  5119.2  431.30  5127.3  433.56  5139.5  434.30
  5207.1  435.44  5311.0  437.71  5447.0  442.57  5493.5  445.68  5549.2  446.53
#Mann=6,-1,0
  4520.8    0.05       0  4853.9    0.16       0  4996.4    0.12       0
  4999.6    0.07       0  5007.9    0.12       0  5311.0    0.05       0
Bank Sta=4842.7,5207.1
Exp/Cntr=0.3,0.1

Type RM Length L Ch R = 1,953,406,406,406
BEGIN DESCRIPTION:
Mapping XS 22528439
END DESCRIPTION:
XS GIS Cut Line= 3
      2814034.25      7056341.67      2813378.03      7056914.57
      2813419.70      7057539.57
#Sta/Elev= 30
  4058.7  444.73  4064.4  444.53  4106.4  444.16  4188.4  442.00  4272.9  442.66
  4393.4  438.72  4429.4  436.08  4485.5  436.77  4604.3  434.20  4787.5  434.12
  4804.5  434.43  4826.3  430.73  4833.0  433.66  4840.6  434.29  4918.4  431.46
  4970.3  433.11  4980.4  432.07  4996.3  426.41  4997.0  425.61  5004.6  426.41
  5010.4  426.90  5020.4  432.77  5050.5  432.63  5060.5  428.06  5070.6  427.54
  5090.6  433.18  5113.2  434.20  5116.5  434.31  5451.4  444.77  5556.2  446.17
#Mann=7,-1,0
  4058.7    0.05       0  4064.4    0.16       0  4106.4    0.05       0
  4787.5    0.12       0  4996.3    0.07       0  5004.6    0.12       0
  5116.5    0.05       0
Bank Sta=4604.3,5113.2
Exp/Cntr=0.3,0.1

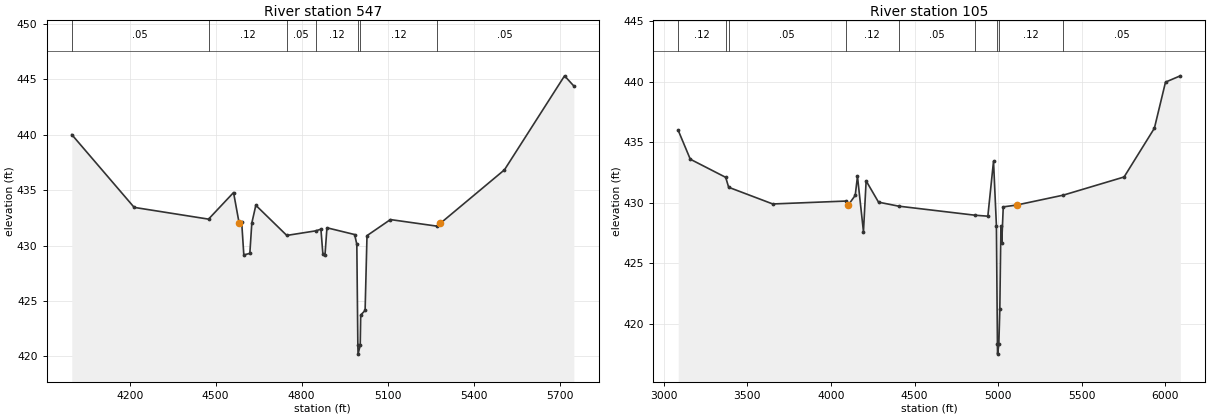
Type RM Length L Ch R = 1,547,442,442,442
BEGIN DESCRIPTION:
Mapping XS b6a19f6e
END DESCRIPTION:
XS GIS Cut Line= 3
      2813690.52      7056253.12      2812971.78      7056904.15
      2813388.44      7057565.60
#Sta/Elev= 30
  3998.0  440.02  4215.7  433.45  4475.1  432.39  4562.4  434.79  4582.0  432.01
  4590.8  432.10  4598.2  429.16  4619.2  429.30  4626.1  432.04  4640.1  433.64
  4748.1  430.92  4848.4  431.33  4867.2  431.48  4874.0  429.24  4881.4  429.17
  4888.2  431.61  4984.8  431.00  4992.4  430.12  4996.0  421.01  4996.7  420.21
  5004.3  421.01  5006.0  423.74  5021.3  424.15  5027.9  430.90  5109.6  432.35
  5271.2  431.76  5283.7  432.01  5507.5  436.84  5717.1  445.32  5749.5  444.40
#Mann=7,-1,0
  3998.0    0.05       0  4475.1    0.12       0  4748.1    0.05       0
  4848.4    0.12       0  4996.0    0.07       0  5004.3    0.12       0
  5271.2    0.05       0
Bank Sta=4582,5283.7
Exp/Cntr=0.3,0.1

Type RM Length L Ch R = 1,105,0,0,0
BEGIN DESCRIPTION:
UNT 059 in LFCCL Watershed 1.0
END DESCRIPTION:
XS GIS Cut Line= 4
      2813791.65      7055824.30      2812479.16      7056553.46
      2812604.16      7057129.85      2813367.10      7057626.36
#Sta/Elev= 30
  3087.3  435.97  3159.3  433.59  3371.0  432.09  3388.7  431.27  3652.4  429.89
  4089.8  430.13  4103.7  429.80  4145.4  430.60  4158.8  432.17  4194.6  427.60
  4210.6  431.80  4284.6  430.04  4404.5  429.71  4861.5  428.96  4938.2  428.88
  4972.1  433.42  4989.4  428.11  4995.5  418.28  4996.2  417.48  5003.8  418.28
  5009.8  421.18  5016.2  428.05  5021.3  426.68  5030.3  429.65  5110.2  429.80
  5389.4  430.62  5752.7  432.12  5933.8  436.15  6000.3  439.96  6088.8  440.48
#Mann=9,-1,0
  3087.3    0.12       0  3371.0    0.16       0  3388.7    0.05       0
  4089.8    0.12       0  4404.5    0.05       0  4861.5    0.12       0
  4995.5    0.07       0  5003.8    0.12       0  5389.4    0.05       0
Bank Sta=4103.7,5110.2
Exp/Cntr=0.3,0.1

Chan Stop Cuts=-1