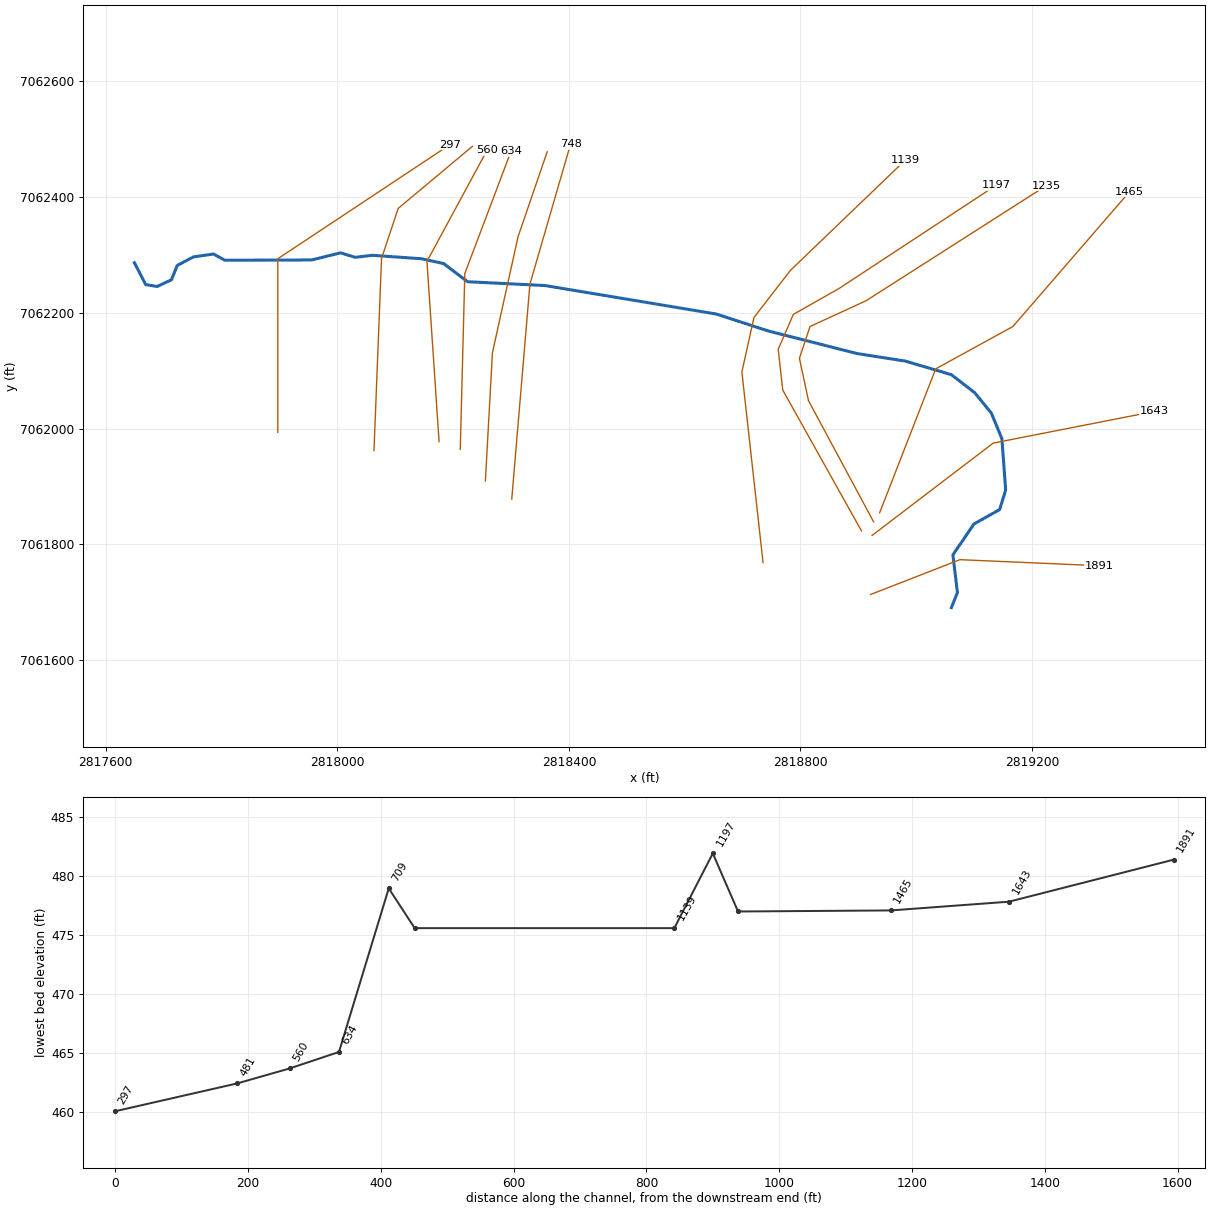
--- UNT 060 in LFCCL Watershed.prj (project) ---

Proj Title=UNT 060 in LFCCL Watershed Base Level Engineering
Current Plan=p01
Default Exp/Contr=0.3,0.1
English Units
Geom File=g01
Flow File=f01
Plan File=p01
BEGIN DESCRIPTION:
UNT 060 in LFCCL Watershed
END DESCRIPTION:

--- UNT 060 in LFCCL Watershed.p01 (plan) ---

Plan Title=Multiple Run
Short Identifier=Multiple
Geom File=g01
Flow File=f01
Subcritical Flow
K Sum by GR= 0
Std Step Tol= 0.01
Critical Tol= 0.01
Num of Std Step Trials= 20
Max Error Tol= 0.3
Flow Tol Ratio= 0.001
Split Flow NTrial= 30
Split Flow Tol= 0.02
Split Flow Ratio= 0.02
Log Output Level= 0
Friction Slope Method= 1
Unsteady Friction Slope Method= 2
Unsteady Bridges Friction Slope Method= 1
Parabolic Critical Depth
Global Vel Dist=  1 , 1 , 1
Global Log Level= 0
CheckData=True
Encroach Param= -1, 0, 0, 0
BEGIN DESCRIPTION:
Multiple Run
END DESCRIPTION:

--- UNT 060 in LFCCL Watershed.f01 (steady flow) ---

Flow Title=Multiple
Number of Profiles=7
Profile Names=10-year,25-year,50-year,1pct_min,100-year,1pct_plu,500-year
River Rch & RM= UNT 060 in LFCCL,Reach-1,1891
     308     393     459     268     534    1065     717
Boundary for River Rch & Prof#=UNT 060 in LFCCL,Reach-1,1
Up Type=0
Dn Type=3
Dn Slope=0.005
Boundary for River Rch & Prof#=UNT 060 in LFCCL,Reach-1,2
Up Type=0
Dn Type=3
Dn Slope=0.005
Boundary for River Rch & Prof#=UNT 060 in LFCCL,Reach-1,3
Up Type=0
Dn Type=3
Dn Slope=0.005
Boundary for River Rch & Prof#=UNT 060 in LFCCL,Reach-1,4
Up Type=0
Dn Type=3
Dn Slope=0.005
Boundary for River Rch & Prof#=UNT 060 in LFCCL,Reach-1,5
Up Type=0
Dn Type=3
Dn Slope=0.005
Boundary for River Rch & Prof#=UNT 060 in LFCCL,Reach-1,6
Up Type=0
Dn Type=3
Dn Slope=0.005
Boundary for River Rch & Prof#=UNT 060 in LFCCL,Reach-1,7
Up Type=0
Dn Type=3
Dn Slope=0.005

--- UNT 060 in LFCCL Watershed.g01 (geometry) ---

Geom Title=Existing Conditions

River Reach=UNT 060 in LFCCL,Reach-1
Reach XY= 30
      2819060.69      7061690.73      2819071.10      7061716.77
      2819063.29      7061781.87      2819099.75      7061835.26
      2819144.02      7061860.00      2819154.44      7061893.85
      2819147.93      7061982.39      2819129.70      7062026.66
      2819101.05      7062061.82      2819060.69      7062093.07
      2818981.26      7062116.51      2818897.93      7062129.53
      2818744.28      7062168.59      2818654.68      7062197.81
      2818358.51      7062247.05      2818224.89      7062253.65
      2818183.65      7062284.99      2818145.71      7062293.24
      2818060.53      7062299.29      2818030.87      7062295.77
      2818005.42      7062303.53      2817955.58      7062291.21
      2817805.59      7062290.71      2817786.11      7062301.48
      2817751.47      7062296.54      2817723.43      7062281.69
      2817713.53      7062256.95      2817688.79      7062245.40
      2817668.99      7062248.70      2817649.51      7062286.45

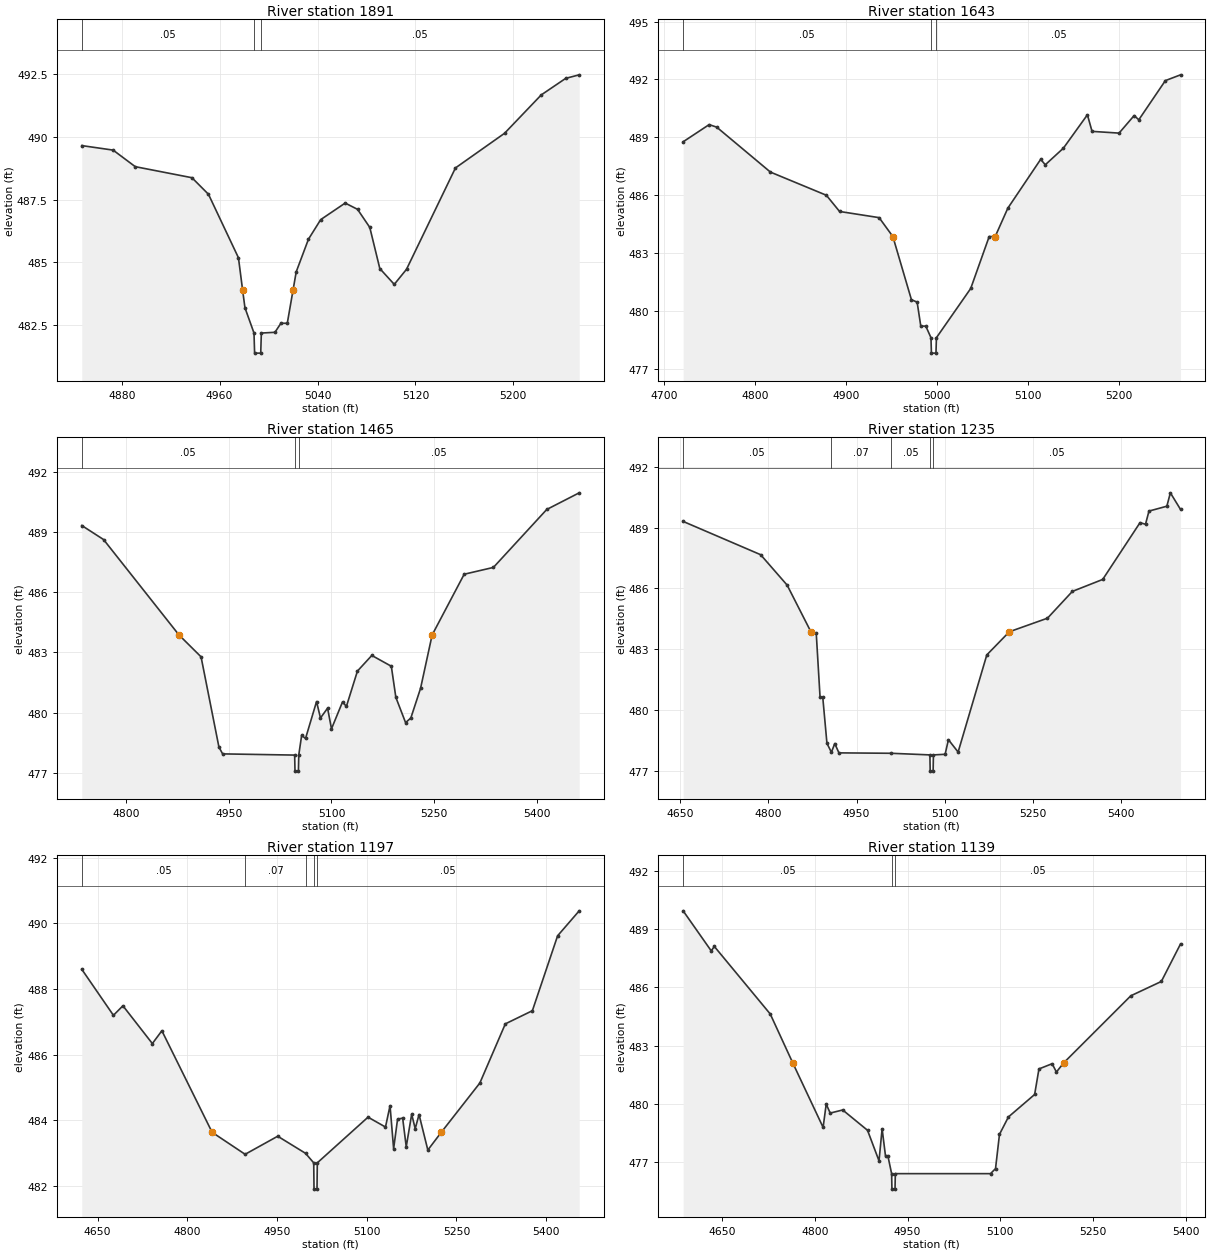
Type RM Length L Ch R = 1,1891,248,248,248
BEGIN DESCRIPTION:
UNT 060 in LFCCL Watershed 3.0
END DESCRIPTION:
XS GIS Cut Line= 3
      2818921.11      7061713.39      2819075.39      7061773.53
      2819315.98      7061763.07
#Sta/Elev= 30
  4847.4  489.65  4873.0  489.47  4891.1  488.81  4937.4  488.37  4950.9  487.71
  4975.4  485.18  4978.8  483.89  4980.7  483.19  4988.1  482.18  4988.6  481.38
  4993.6  481.38  4994.1  482.18  5005.2  482.21  5010.1  482.57  5015.3  482.57
  5020.0  483.89  5022.6  484.62  5032.6  485.92  5042.6  486.70  5062.6  487.36
  5072.7  487.11  5082.7  486.39  5090.9  484.75  5102.7  484.12  5112.7  484.72
  5152.7  488.76  5192.8  490.14  5222.8  491.67  5242.8  492.33  5253.8  492.47
#Mann=3,-1,0
  4847.4    0.05       0  4988.1    0.03       0  4994.1    0.05       0
Bank Sta=4978.8,5020
Exp/Cntr=0.3,0.1

Type RM Length L Ch R = 1,1643,178,178,178
BEGIN DESCRIPTION:
XS3443A
END DESCRIPTION:
XS GIS Cut Line= 3
      2818923.67      7061815.34      2819132.92      7061974.90
      2819411.37      7062029.55
#Sta/Elev= 30
  4721.0  488.77  4749.6  489.66  4757.9  489.53  4817.0  487.20  4878.5  486.00
  4893.0  485.16  4936.5  484.84  4951.6  483.86  4972.0  480.59  4978.3  480.46
  4982.3  479.22  4987.8  479.22  4993.5  478.62  4994.0  477.82  4999.0  477.82
  4999.5  478.62  5037.2  481.17  5057.5  483.86  5064.1  483.86  5078.0  485.33
  5114.1  487.86  5119.2  487.58  5139.1  488.44  5165.5  490.17  5170.6  489.31
  5200.3  489.22  5216.9  490.13  5222.0  489.91  5251.2  491.94  5267.9  492.24
#Mann=3,-1,0
  4721.0    0.05       0  4993.5    0.03       0  4999.5    0.05       0
Bank Sta=4951.6,5064.1
Exp/Cntr=0.3,0.1

Type RM Length L Ch R = 1,1465,230,230,230
BEGIN DESCRIPTION:
XS3452A
END DESCRIPTION:
XS GIS Cut Line= 4
      2818936.79      7061854.63      2819033.54      7062103.04
      2819166.92      7062176.27      2819368.28      7062409.01
#Sta/Elev= 30
  4735.3  489.33  4767.1  488.63  4877.3  483.87  4909.5  482.78  4935.6  478.28
  4941.0  477.94  5046.2  477.88  5046.7  477.08  5051.7  477.08  5052.2  477.88
  5056.4  478.86  5062.1  478.71  5078.2  480.55  5083.9  479.73  5094.3  480.22
  5100.0  479.19  5116.1  480.53  5121.8  480.31  5137.9  482.07  5158.9  482.85
  5187.4  482.31  5194.0  480.76  5208.2  479.50  5215.9  479.73  5230.1  481.21
  5247.0  483.87  5293.8  486.90  5336.5  487.24  5414.4  490.13  5461.8  490.96
#Mann=3,-1,0
  4735.3    0.05       0  5046.2   0.033       0  5052.2    0.05       0
Bank Sta=4877.3,5247
Exp/Cntr=0.3,0.1

Type RM Length L Ch R = 1,1235,38,38,38
BEGIN DESCRIPTION:
XS3445A
END DESCRIPTION:
XS GIS Cut Line= 6
      2818926.32      7061838.91      2818813.87      7062048.12
      2818798.17      7062121.35      2818816.48      7062176.27
      2818913.24      7062220.73      2819224.41      7062419.46
#Sta/Elev= 30
  4655.0  489.30  4786.8  487.66  4831.9  486.16  4872.3  483.86  4881.4  483.79
  4887.9  480.63  4892.5  480.63  4899.6  478.36  4907.2  477.92  4912.9  478.35
  4920.0  477.89  5008.5  477.87  5074.7  477.79  5075.2  476.99  5080.2  476.99
  5080.7  477.79  5100.6  477.82  5106.2  478.54  5122.7  477.93  5171.5  482.72
  5209.8  483.86  5274.7  484.53  5317.0  485.85  5368.6  486.44  5432.1  489.24
  5441.4  489.16  5447.3  489.81  5477.7  490.05  5483.7  490.71  5501.0  489.89
#Mann=5,-1,0
  4655.0    0.05       0  4907.2    0.07       0  5008.5    0.05       0
  5074.7    0.07       0  5080.7    0.05       0
Bank Sta=4872.3,5209.8
Exp/Cntr=0.3,0.1

Type RM Length L Ch R = 1,1197,58,58,58
BEGIN DESCRIPTION:
XS3444A
END DESCRIPTION:
XS GIS Cut Line= 6
      2818905.42      7061823.18      2818769.41      7062066.43
      2818761.56      7062137.04      2818787.71      7062197.19
      2818866.17      7062241.65      2819138.77      7062420.79
#Sta/Elev= 30
  4623.6  488.60  4676.5  487.20  4692.4  487.49  4741.6  486.34  4757.5  486.73
  4841.5  483.64  4896.7  482.97  4951.2  483.52  4997.7  483.00  5011.4  482.71
  5011.9  481.91  5016.9  481.91  5017.4  482.71  5102.2  484.10  5131.4  483.80
  5139.0  484.45  5145.0  483.14  5151.6  484.04  5160.1  484.07  5166.1  483.20
  5175.2  484.19  5181.1  483.75  5187.5  484.18  5202.2  483.10  5224.7  483.64
  5289.2  485.14  5331.8  486.94  5377.0  487.34  5419.2  489.62  5455.3  490.38
#Mann=5,-1,0
  4623.6    0.05       0  4896.7    0.07       0  4997.7    0.05       0
  5011.4    0.03       0  5017.4    0.05       0
Bank Sta=4841.5,5224.7
Exp/Cntr=0.3,0.1

Type RM Length L Ch R = 1,1139,391,391,391
BEGIN DESCRIPTION:
XS3446A
END DESCRIPTION:
XS GIS Cut Line= 5
      2818735.41      7061768.31      2818698.80      7062097.81
      2818719.72      7062191.96      2818782.48      7062273.03
      2818980.60      7062463.32
#Sta/Elev= 30
  4586.7  489.96  4632.2  487.89  4637.2  488.12  4727.7  484.63  4764.2  482.10
  4813.3  478.77  4818.3  479.97  4824.8  479.51  4845.0  479.67  4885.2  478.62
  4903.8  477.04  4908.8  478.70  4914.3  477.29  4918.2  477.29  4924.2  476.38
  4924.7  475.58  4929.7  475.58  4930.2  476.38  5084.3  476.38  5092.4  476.64
  5098.8  478.41  5113.3  479.31  5155.7  480.47  5162.7  481.79  5184.0  482.06
  5191.0  481.63  5202.6  482.10  5311.4  485.57  5360.8  486.31  5391.9  488.25
#Mann=3,-1,0
  4586.7    0.05       0  4924.2   0.033       0  4930.2    0.05       0
Bank Sta=4764.2,5202.6
Exp/Cntr=0.3,0.1

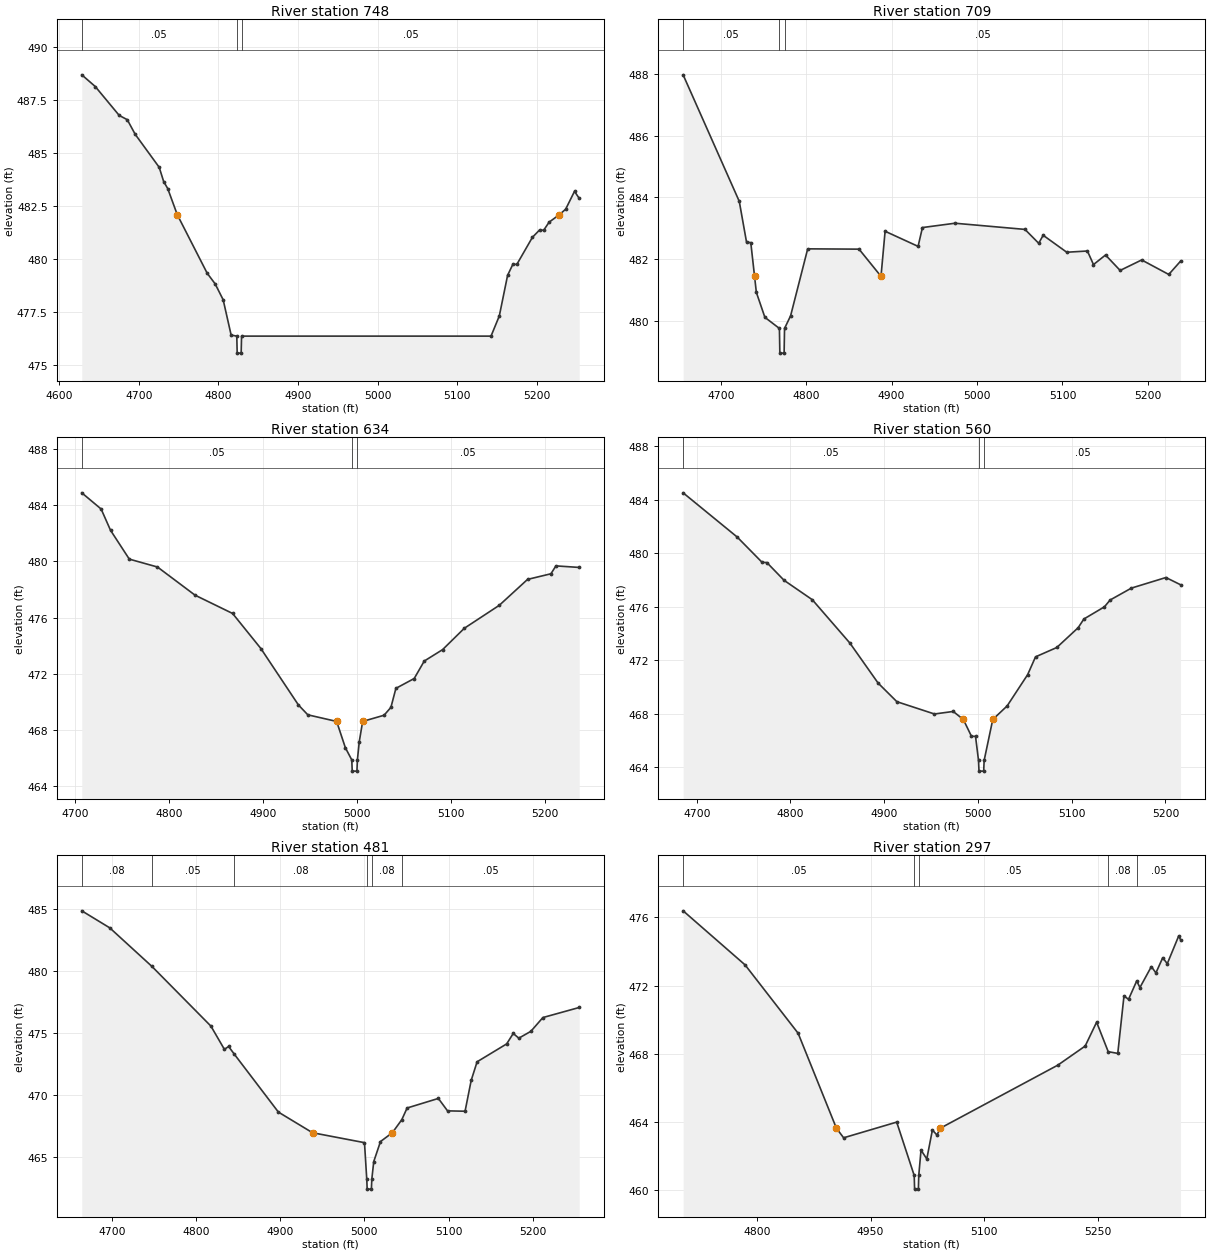
Type RM Length L Ch R = 1,748,39,39,39
BEGIN DESCRIPTION:
XS3451A
END DESCRIPTION:
XS GIS Cut Line= 3
      2818301.29      7061878.15      2818332.67      7062249.49
      2818402.88      7062491.34
#Sta/Elev= 30
  4628.5  488.67  4645.4  488.12  4675.5  486.76  4685.6  486.56  4695.6  485.87
  4725.7  484.32  4731.3  483.65  4736.4  483.32  4748.4  482.09  4785.9  479.34
  4795.9  478.84  4806.0  478.09  4816.0  476.43  4823.1  476.38  4823.6  475.58
  4828.6  475.58  4829.1  476.38  5142.3  476.38  5152.7  477.33  5163.1  479.24
  5169.6  479.75  5174.8  479.76  5194.3  481.03  5203.2  481.37  5208.4  481.36
  5215.2  481.74  5228.0  482.09  5236.0  482.35  5247.1  483.19  5253.0  482.86
#Mann=3,-1,0
  4628.5    0.05       0  4823.1   0.033       0  4829.1    0.05       0
Bank Sta=4748.4,5228
Exp/Cntr=0.3,0.1

Type RM Length L Ch R = 1,709,75,75,75
BEGIN DESCRIPTION:
Mapping XS 846fdbaa
END DESCRIPTION:
XS GIS Cut Line= 4
      2818255.74      7061909.43      2818267.89      7062130.81
      2818312.16      7062331.33      2818362.52      7062478.07
#Sta/Elev= 30
  4656.0  487.97  4721.7  483.87  4730.2  482.55  4735.2  482.53  4739.6  481.44
  4741.7  480.92  4751.7  480.11  4768.7  479.75  4769.2  478.95  4774.2  478.95
  4774.7  479.75  4781.8  480.16  4801.8  482.33  4861.9  482.32  4887.6  481.44
  4892.4  482.90  4931.0  482.41  4936.1  483.02  4974.2  483.16  5056.1  482.96
  5072.2  482.51  5077.4  482.77  5105.0  482.22  5129.2  482.26  5136.3  481.82
  5150.4  482.13  5167.5  481.63  5192.7  481.97  5224.4  481.50  5238.2  481.93
#Mann=3,-1,0
  4656.0    0.05       0  4768.7    0.03       0  4774.7    0.05       0
Bank Sta=4739.6,4887.6
Exp/Cntr=0.3,0.1

Type RM Length L Ch R = 1,634,74,74,74
BEGIN DESCRIPTION:
XS3449A
END DESCRIPTION:
XS GIS Cut Line= 3
      2818212.37      7061964.41      2818220.21      7062267.80
      2818300.20      7062479.39
#Sta/Elev= 30
  4706.9  484.86  4727.5  483.71  4737.5  482.20  4757.5  480.15  4787.5  479.59
  4827.5  477.59  4867.5  476.29  4897.6  473.80  4937.6  469.79  4947.6  469.09
  4978.3  468.62  4987.6  466.75  4994.4  465.89  4994.9  465.09  4999.9  465.09
  5000.4  465.89  5002.4  467.19  5006.0  468.62  5028.8  469.06  5036.1  469.62
  5041.4  470.97  5060.9  471.67  5071.6  472.91  5091.1  473.72  5114.3  475.24
  5151.5  476.87  5181.6  478.71  5206.5  479.11  5211.8  479.67  5236.6  479.56
#Mann=3,-1,0
  4706.9    0.05       0  4994.4    0.03       0  5000.4    0.05       0
Bank Sta=4978.3,5006
Exp/Cntr=0.3,0.1

Type RM Length L Ch R = 1,560,79,79,79
BEGIN DESCRIPTION:
XS3448A
END DESCRIPTION:
XS GIS Cut Line= 3
      2818175.76      7061977.50      2818154.83      7062288.72
      2818258.82      7062481.09
#Sta/Elev= 30
  4685.5  484.50  4743.1  481.20  4769.8  479.30  4774.8  479.29  4793.2  477.96
  4823.3  476.51  4863.4  473.27  4893.5  470.28  4913.5  468.89  4953.6  467.97
  4973.6  468.16  4984.4  467.56  4993.1  466.30  4997.4  466.30  5000.6  464.50
  5001.1  463.70  5006.1  463.70  5006.6  464.50  5015.8  467.56  5031.1  468.57
  5053.0  470.91  5061.4  472.24  5084.1  472.94  5106.9  474.42  5113.0  475.07
  5134.9  475.98  5141.0  476.49  5163.7  477.38  5200.5  478.17  5216.1  477.63
#Mann=3,-1,0
  4685.5    0.05       0  5000.6    0.03       0  5006.6    0.05       0
Bank Sta=4984.4,5015.8
Exp/Cntr=0.3,0.1

Type RM Length L Ch R = 1,481,184,184,184
BEGIN DESCRIPTION:
XS3447A
END DESCRIPTION:
XS GIS Cut Line= 4
      2818063.30      7061961.78      2818076.38      7062293.95
      2818105.15      7062380.25      2818233.30      7062487.49
#Sta/Elev= 30
  4664.5  484.83  4697.7  483.46  4747.7  480.36  4817.8  475.55  4833.8  473.68
  4838.8  473.91  4845.7  473.28  4897.9  468.63  4938.4  466.97  5000.1  466.17
  5002.8  463.23  5003.3  462.43  5008.3  462.43  5008.8  463.23  5011.1  464.65
  5019.1  466.26  5033.2  466.97  5044.4  468.02  5050.7  468.96  5087.8  469.73
  5098.7  468.73  5119.5  468.70  5126.8  471.19  5133.8  472.68  5168.9  474.12
  5176.7  474.96  5183.3  474.58  5197.6  475.13  5211.9  476.24  5255.0  477.05
#Mann=6,-1,0
  4664.5    0.08       0  4747.7    0.05       0  4845.7    0.08       0
  5002.8    0.07       0  5008.8    0.08       0  5044.4    0.05       0
Bank Sta=4938.4,5033.2
Exp/Cntr=0.3,0.1

Type RM Length L Ch R = 1,297,0,0,0
BEGIN DESCRIPTION:
UNT 060 in LFCCL Watershed 1.0
END DESCRIPTION:
XS GIS Cut Line= 3
      2817897.17      7061993.30      2817897.17      7062293.31
      2818193.98      7062490.04
#Sta/Elev= 30
  4702.7  476.39  4784.4  473.22  4854.4  469.21  4904.9  463.64  4914.4  463.08
  4984.4  464.00  5007.5  460.87  5008.0  460.07  5013.0  460.07  5013.5  460.87
  5016.5  462.36  5024.1  461.84  5031.5  463.54  5037.5  463.24  5041.8  463.64
  5196.9  467.34  5233.0  468.46  5248.1  469.86  5263.4  468.13  5276.0  468.03
  5284.2  471.40  5290.2  471.20  5301.0  472.28  5305.2  471.89  5320.3  473.12
  5326.3  472.75  5335.3  473.64  5341.3  473.29  5356.4  474.92  5358.8  474.70
#Mann=5,-1,0
  4702.7    0.05       0  5007.5    0.03       0  5013.5    0.05       0
  5263.4    0.08       0  5301.0    0.05       0
Bank Sta=4904.9,5041.8
Exp/Cntr=0.3,0.1

Chan Stop Cuts=-1