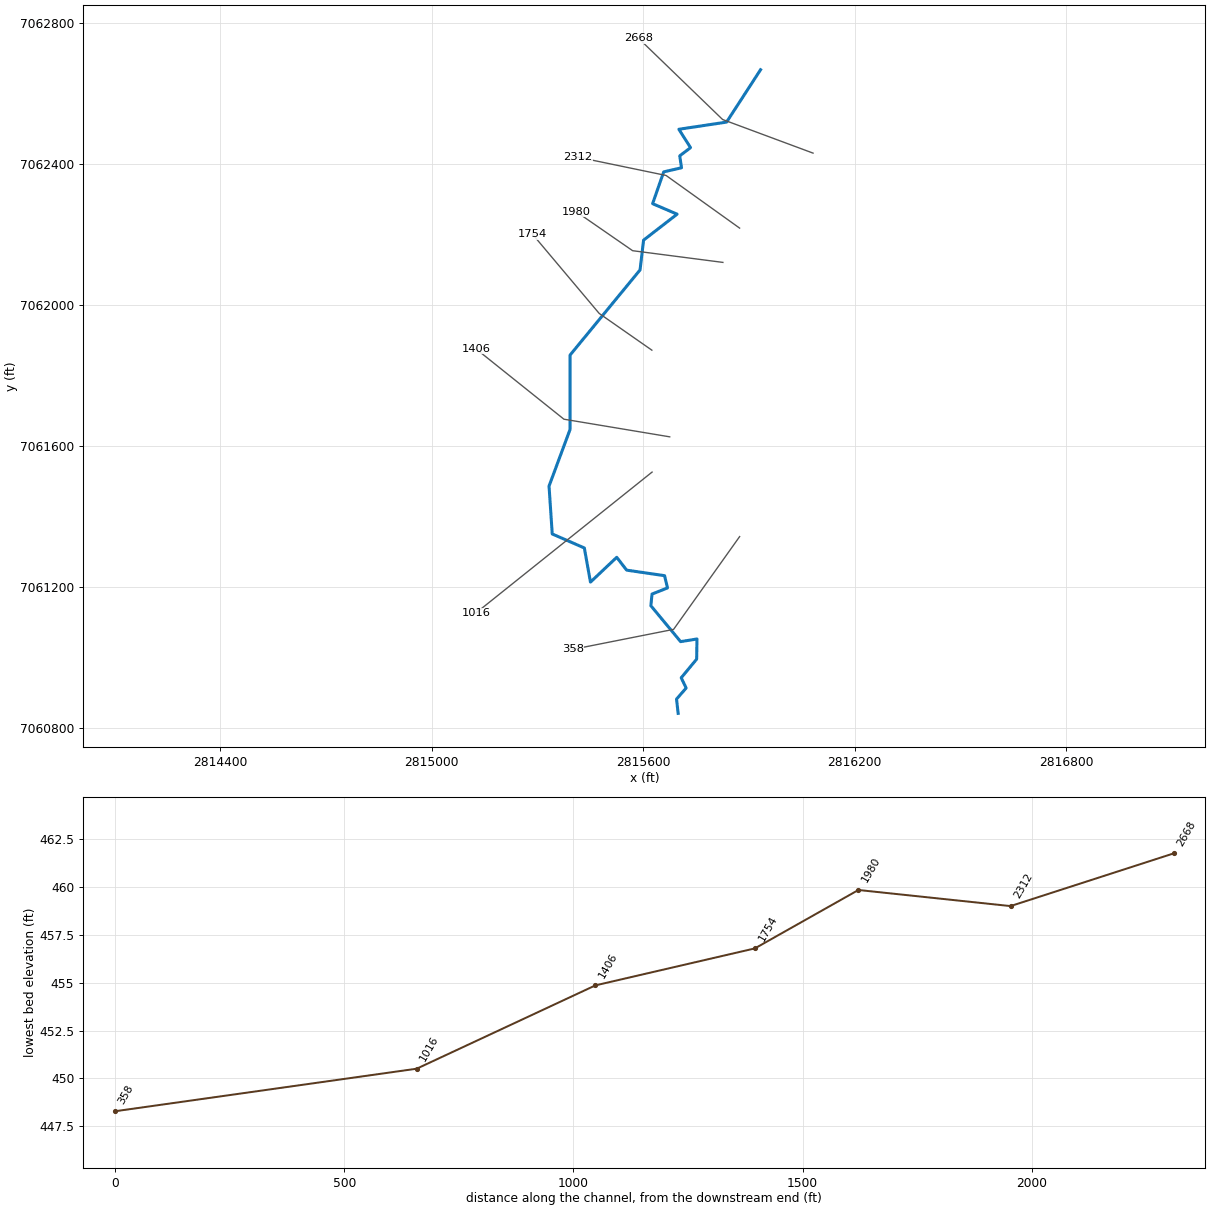
--- UNT 061 in LFCCL Watershed.prj (project) ---

Proj Title=UNT 061 in LFCCL Watershed Base Level Engineering
Current Plan=p01
Default Exp/Contr=0.3,0.1
English Units
Geom File=g01
Flow File=f01
Plan File=p01
BEGIN DESCRIPTION:
UNT 061 in LFCCL Watershed
END DESCRIPTION:

--- UNT 061 in LFCCL Watershed.p01 (plan) ---

Plan Title=Multiple Run
Short Identifier=Multiple
Geom File=g01
Flow File=f01
Subcritical Flow
K Sum by GR= 0
Std Step Tol= 0.01
Critical Tol= 0.01
Num of Std Step Trials= 20
Max Error Tol= 0.3
Flow Tol Ratio= 0.001
Split Flow NTrial= 30
Split Flow Tol= 0.02
Split Flow Ratio= 0.02
Log Output Level= 0
Friction Slope Method= 1
Unsteady Friction Slope Method= 2
Unsteady Bridges Friction Slope Method= 1
Parabolic Critical Depth
Global Vel Dist=  1 , 1 , 1
Global Log Level= 0
CheckData=True
Encroach Param= -1, 0, 0, 0
BEGIN DESCRIPTION:
Multiple Run
END DESCRIPTION:

--- UNT 061 in LFCCL Watershed.f01 (steady flow) ---

Flow Title=Multiple
Number of Profiles=7
Profile Names=10-year,25-year,50-year,1pct_min,100-year,1pct_plu,500-year
River Rch & RM= UNT 061 in LFCCL,Reach-1,2668
     265     331     381     218     434     867     563
Boundary for River Rch & Prof#=UNT 061 in LFCCL,Reach-1,1
Up Type=0
Dn Type=3
Dn Slope=0.005
Boundary for River Rch & Prof#=UNT 061 in LFCCL,Reach-1,2
Up Type=0
Dn Type=3
Dn Slope=0.005
Boundary for River Rch & Prof#=UNT 061 in LFCCL,Reach-1,3
Up Type=0
Dn Type=3
Dn Slope=0.005
Boundary for River Rch & Prof#=UNT 061 in LFCCL,Reach-1,4
Up Type=0
Dn Type=3
Dn Slope=0.005
Boundary for River Rch & Prof#=UNT 061 in LFCCL,Reach-1,5
Up Type=0
Dn Type=3
Dn Slope=0.005
Boundary for River Rch & Prof#=UNT 061 in LFCCL,Reach-1,6
Up Type=0
Dn Type=3
Dn Slope=0.005
Boundary for River Rch & Prof#=UNT 061 in LFCCL,Reach-1,7
Up Type=0
Dn Type=3
Dn Slope=0.005

--- UNT 061 in LFCCL Watershed.g01 (geometry) ---

Geom Title=Existing Conditions

River Reach=UNT 061 in LFCCL,Reach-1
Reach XY= 30
      2815932.67      7062666.18      2815836.32      7062517.66
      2815701.01      7062497.29      2815734.11      7062445.16
      2815703.49      7062421.99      2815708.46      7062388.06
      2815657.98      7062376.48      2815626.53      7062286.28
      2815696.04      7062256.49      2815600.88      7062182.84
      2815590.95      7062098.43      2815392.34      7061856.79
      2815392.34      7061645.77      2815332.76      7061485.24
      2815341.86      7061349.52      2815432.89      7061309.80
      2815450.27      7061212.98      2815524.75      7061283.32
      2815552.88      7061246.91      2815660.46      7061231.19
      2815668.73      7061196.43      2815624.88      7061179.05
      2815621.57      7061145.95      2815705.97      7061044.17
      2815752.31      7061051.61      2815751.49      7060994.52
      2815707.63      7060941.55      2815721.70      7060912.59
      2815694.39      7060881.14      2815698.99      7060840.66

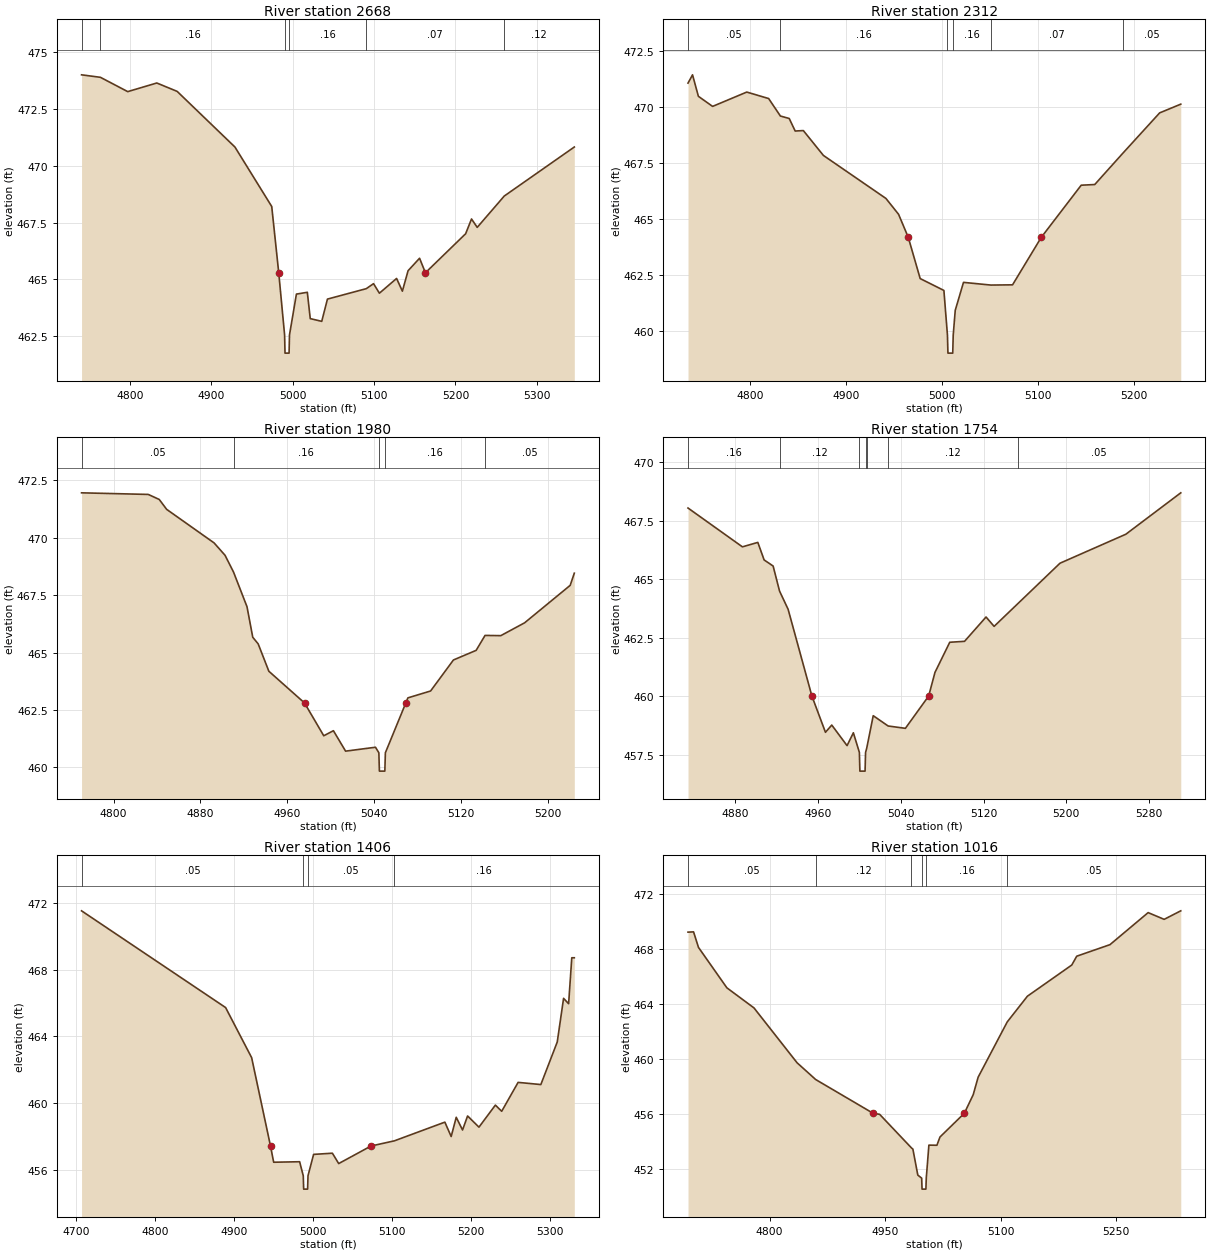
Type RM Length L Ch R = 1,2668,356,356,356
BEGIN DESCRIPTION:
UNT 061 in LFCCL Watershed 6.0
END DESCRIPTION:
XS GIS Cut Line= 3
      2816081.55      7062429.68      2815825.00      7062525.00
      2815586.74      7062755.22
#Sta/Elev= 30
  4740.9  474.01  4764.1  473.90  4797.6  473.27  4833.3  473.65  4858.3  473.28
  4929.2  470.83  4974.4  468.21  4983.0  465.29  4990.2  462.55  4990.7  461.75
  4995.7  461.75  4996.2  462.55  5004.7  464.35  5018.1  464.43  5021.7  463.27
  5035.8  463.15  5042.8  464.13  5090.5  464.59  5099.4  464.81  5106.6  464.39
  5127.7  465.04  5134.8  464.48  5141.8  465.38  5155.9  465.93  5163.1  465.29
  5212.5  467.01  5219.7  467.66  5226.7  467.29  5259.9  468.67  5345.9  470.83
#Mann=6,-1,0
  4740.9    0.05       0  4764.1    0.16       0  4990.2    0.07       0
  4996.2    0.16       0  5090.5    0.07       0  5259.9    0.12       0
Bank Sta=4983,5163.1
Exp/Cntr=0.3,0.1

Type RM Length L Ch R = 1,2312,332,332,332
BEGIN DESCRIPTION:
XS3453A
END DESCRIPTION:
XS GIS Cut Line= 3
      2815873.32      7062216.94      2815664.72      7062366.28
      2815413.42      7062418.43
#Sta/Elev= 30
  4735.4  471.06  4740.1  471.43  4746.2  470.47  4761.0  470.02  4796.6  470.66
  4819.4  470.37  4831.6  469.59  4840.8  469.48  4847.0  468.92  4855.5  468.94
  4876.4  467.83  4941.5  465.91  4954.7  465.20  4964.8  464.17  4977.2  462.33
  5001.9  461.80  5005.6  459.80  5006.1  459.00  5011.1  459.00  5011.6  459.80
  5013.7  460.91  5022.3  462.16  5050.8  462.04  5073.4  462.05  5103.3  464.17
  5144.9  466.50  5159.0  466.53  5188.3  467.93  5226.6  469.73  5248.6  470.12
#Mann=6,-1,0
  4735.4    0.05       0  4831.6    0.16       0  5005.6    0.07       0
  5011.6    0.16       0  5050.8    0.07       0  5188.3    0.05       0
Bank Sta=4964.8,5103.3
Exp/Cntr=0.3,0.1

Type RM Length L Ch R = 1,1980,226,226,226
BEGIN DESCRIPTION:
XS3454A
END DESCRIPTION:
XS GIS Cut Line= 3
      2815825.90      7062119.72      2815569.89      7062152.90
      2815409.36      7062263.86
#Sta/Elev= 30
  4770.6  471.96  4832.0  471.89  4842.1  471.67  4848.9  471.24  4892.5  469.78
  4902.6  469.24  4910.4  468.51  4922.8  467.00  4928.1  465.67  4933.1  465.38
  4942.9  464.19  4975.7  462.81  4993.4  461.38  5002.3  461.60  5013.5  460.71
  5041.0  460.88  5044.1  460.64  5044.6  459.84  5049.6  459.84  5050.1  460.64
  5068.9  462.81  5070.8  463.03  5091.7  463.33  5112.7  464.68  5133.6  465.10
  5141.8  465.75  5156.3  465.74  5178.2  466.30  5220.1  467.93  5223.9  468.46
#Mann=5,-1,0
  4770.6    0.05       0  4910.4    0.16       0  5044.1    0.07       0
  5050.1    0.16       0  5141.8    0.05       0
Bank Sta=4975.7,5068.9
Exp/Cntr=0.3,0.1

Type RM Length L Ch R = 1,1754,348,348,348
BEGIN DESCRIPTION:
UNT 061 in LFCCL Watershed 4.0
END DESCRIPTION:
XS GIS Cut Line= 3
      2815624.43      7061870.77      2815475.00      7061975.00
      2815285.50      7062200.19
#Sta/Elev= 30
  4834.2  468.04  4886.8  466.38  4901.7  466.57  4907.8  465.82  4916.5  465.56
  4922.7  464.49  4931.0  463.71  4954.0  460.00  4967.1  458.45  4973.2  458.76
  4988.0  457.88  4994.1  458.43  4999.9  457.59  5000.4  456.79  5005.4  456.79
  5005.9  457.59  5007.0  457.77  5013.3  459.16  5027.7  458.72  5044.4  458.62
  5066.9  460.00  5073.0  461.01  5087.3  462.30  5101.6  462.34  5122.4  463.38
  5130.2  462.98  5153.1  463.95  5193.9  465.68  5257.6  466.92  5310.7  468.69
#Mann=7,-1,0
  4834.2    0.16       0  4922.7    0.12       0  4999.9    0.07       0
  5005.9    0.12       0  5007.0    0.16       0  5027.7    0.12       0
  5153.1    0.05       0
Bank Sta=4954,5066.9
Exp/Cntr=0.3,0.1

Type RM Length L Ch R = 1,1406,390,390,390
BEGIN DESCRIPTION:
UNT 061 in LFCCL Watershed 3.0
END DESCRIPTION:
XS GIS Cut Line= 3
      2815675.05      7061624.99      2815375.00      7061675.00
      2815125.03      7061874.97
#Sta/Elev= 30
  4706.8  471.52  4889.3  465.73  4922.3  462.73  4946.2  457.44  4950.2  456.47
  4983.1  456.50  4987.7  455.66  4988.2  454.86  4993.2  454.86  4993.7  455.66
  5000.8  456.94  5024.6  457.01  5032.6  456.39  5073.5  457.44  5103.1  457.75
  5167.1  458.87  5175.1  458.01  5181.5  459.16  5189.5  458.40  5195.9  459.24
  5210.3  458.57  5231.1  459.89  5239.1  459.52  5259.9  461.25  5288.7  461.12
  5309.5  463.67  5317.5  466.28  5323.9  465.96  5327.9  468.71  5331.1  468.71
#Mann=4,-1,0
  4706.8    0.05       0  4987.7    0.03       0  4993.7    0.05       0
  5103.1    0.16       0
Bank Sta=4946.2,5073.5
Exp/Cntr=0.3,0.1

Type RM Length L Ch R = 1,1016,658,658,658
BEGIN DESCRIPTION:
UNT 061 in LFCCL Watershed 2.0
END DESCRIPTION:
XS GIS Cut Line= 3
      2815625.02      7061525.02      2815375.00      7061325.00
      2815125.03      7061125.03
#Sta/Elev= 30
  4693.9  469.20  4701.1  469.22  4707.5  468.09  4744.4  465.15  4779.6  463.69
  4835.6  459.70  4859.8  458.48  4934.3  456.03  4942.9  455.95  4984.2  453.51
  4986.1  453.42  4992.5  451.53  4997.5  451.31  4998.0  450.51  5003.0  450.51
  5003.5  451.31  5006.9  453.71  5017.3  453.70  5021.3  454.30  5053.0  456.03
  5064.5  457.38  5070.9  458.65  5108.7  462.67  5134.9  464.54  5192.6  466.81
  5199.0  467.45  5242.2  468.29  5291.8  470.62  5312.6  470.13  5334.2  470.75
#Mann=6,-1,0
  4693.9    0.05       0  4859.8    0.12       0  4984.2    0.16       0
  4997.5    0.07       0  5003.5    0.16       0  5108.7    0.05       0
Bank Sta=4934.3,5053
Exp/Cntr=0.3,0.1

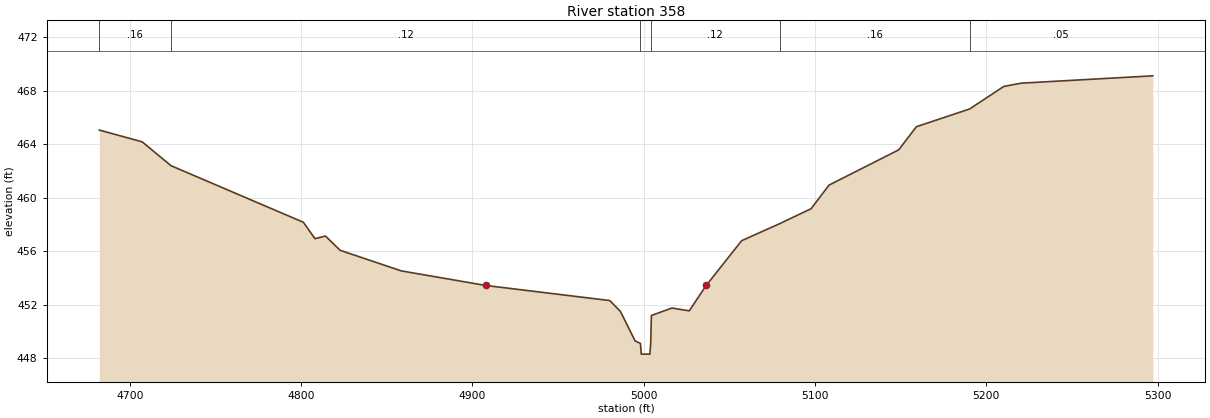
Type RM Length L Ch R = 1,358,0,0,0
BEGIN DESCRIPTION:
XS3455A
END DESCRIPTION:
XS GIS Cut Line= 3
      2815873.34      7061342.07      2815686.06      7061078.93
      2815399.62      7061022.11
#Sta/Elev= 30
  4682.2  465.06  4707.2  464.18  4724.1  462.39  4801.3  458.16  4808.1  456.93
  4814.2  457.13  4822.8  456.06  4858.5  454.52  4907.7  453.43  4980.2  452.30
  4986.4  451.49  4995.0  449.28  4998.1  449.09  4998.6  448.29  5003.6  448.29
  5004.1  449.09  5004.5  451.18  5016.5  451.74  5026.6  451.53  5036.5  453.43
  5057.2  456.78  5079.3  458.05  5097.7  459.17  5108.2  460.94  5148.9  463.58
  5159.2  465.31  5190.3  466.64  5210.3  468.33  5220.4  468.57  5297.2  469.12
#Mann=6,-1,0
  4682.2    0.16       0  4724.1    0.12       0  4998.1    0.07       0
  5004.1    0.12       0  5079.3    0.16       0  5190.3    0.05       0
Bank Sta=4907.7,5036.5
Exp/Cntr=0.3,0.1

Chan Stop Cuts=-1