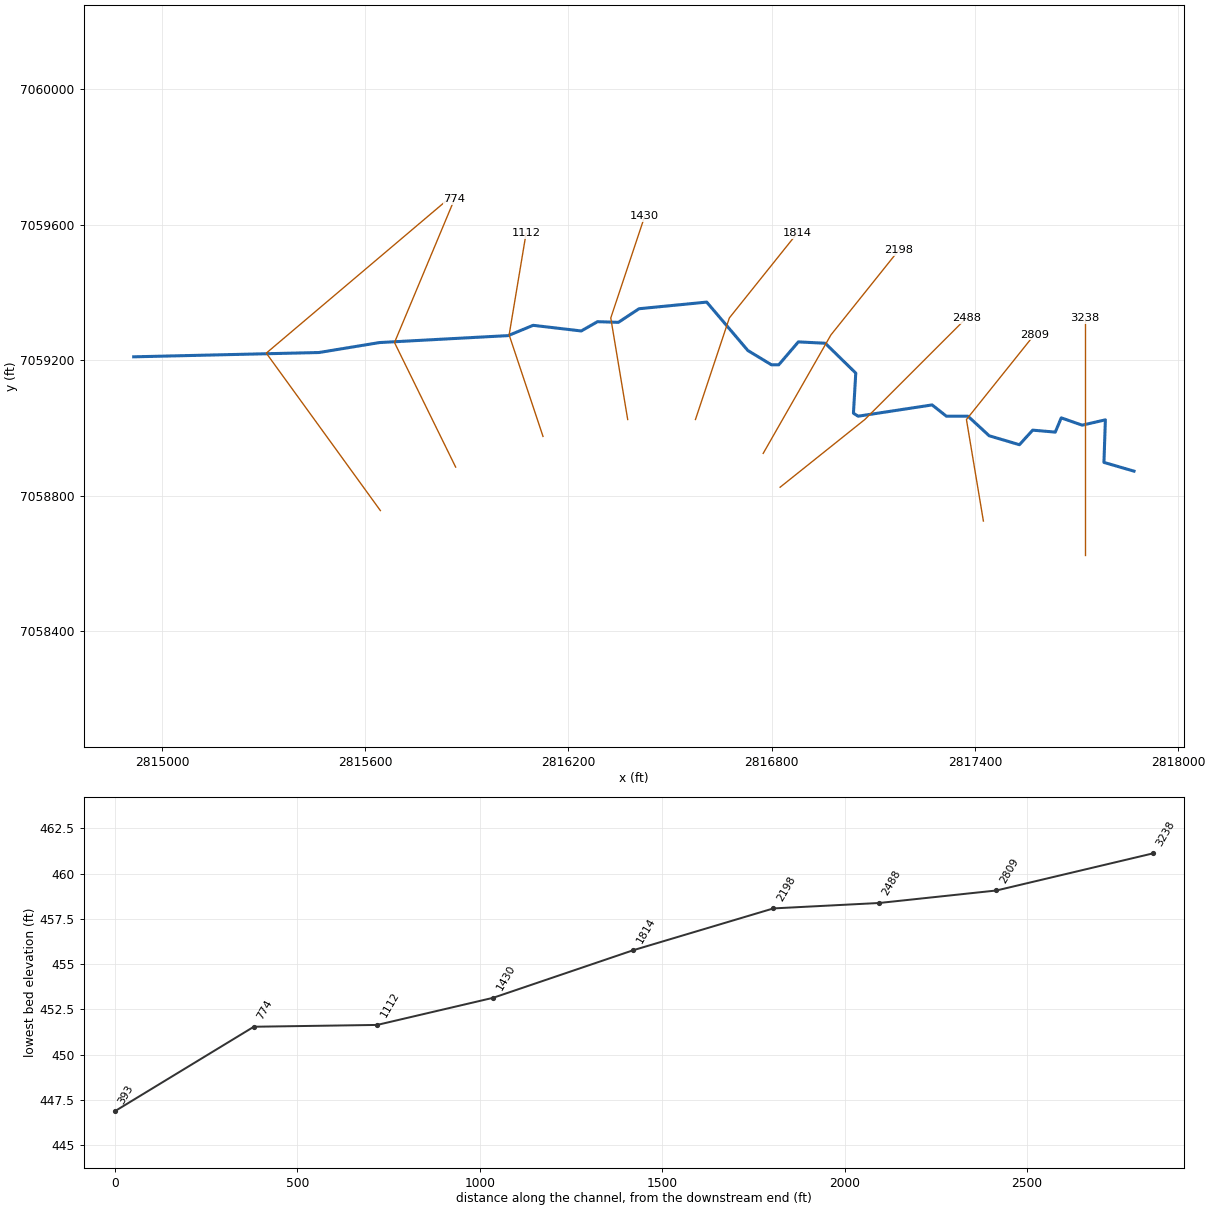
--- UNT 062 in LFCCL Watershed.prj (project) ---

Proj Title=UNT 062 in LFCCL Watershed Base Level Engineering
Current Plan=p01
Default Exp/Contr=0.3,0.1
English Units
Geom File=g01
Flow File=f01
Plan File=p01
BEGIN DESCRIPTION:
UNT 062 in LFCCL Watershed
END DESCRIPTION:

--- UNT 062 in LFCCL Watershed.p01 (plan) ---

Plan Title=Multiple Run
Short Identifier=Multiple
Geom File=g01
Flow File=f01
Subcritical Flow
K Sum by GR= 0
Std Step Tol= 0.01
Critical Tol= 0.01
Num of Std Step Trials= 20
Max Error Tol= 0.3
Flow Tol Ratio= 0.001
Split Flow NTrial= 30
Split Flow Tol= 0.02
Split Flow Ratio= 0.02
Log Output Level= 0
Friction Slope Method= 1
Unsteady Friction Slope Method= 2
Unsteady Bridges Friction Slope Method= 1
Parabolic Critical Depth
Global Vel Dist=  1 , 1 , 1
Global Log Level= 0
CheckData=True
Encroach Param= -1, 0, 0, 0
BEGIN DESCRIPTION:
Multiple Run
END DESCRIPTION:

--- UNT 062 in LFCCL Watershed.f01 (steady flow) ---

Flow Title=Multiple
Number of Profiles=7
Profile Names=10-year,25-year,50-year,1pct_min,100-year,1pct_plu,500-year
River Rch & RM= UNT 062 in LFCCL,Reach-1,3238
     435     566     669     393     784    1565    1074
Boundary for River Rch & Prof#=UNT 062 in LFCCL,Reach-1,1
Up Type=0
Dn Type=3
Dn Slope=0.005
Boundary for River Rch & Prof#=UNT 062 in LFCCL,Reach-1,2
Up Type=0
Dn Type=3
Dn Slope=0.005
Boundary for River Rch & Prof#=UNT 062 in LFCCL,Reach-1,3
Up Type=0
Dn Type=3
Dn Slope=0.005
Boundary for River Rch & Prof#=UNT 062 in LFCCL,Reach-1,4
Up Type=0
Dn Type=3
Dn Slope=0.005
Boundary for River Rch & Prof#=UNT 062 in LFCCL,Reach-1,5
Up Type=0
Dn Type=3
Dn Slope=0.005
Boundary for River Rch & Prof#=UNT 062 in LFCCL,Reach-1,6
Up Type=0
Dn Type=3
Dn Slope=0.005
Boundary for River Rch & Prof#=UNT 062 in LFCCL,Reach-1,7
Up Type=0
Dn Type=3
Dn Slope=0.005

--- UNT 062 in LFCCL Watershed.g01 (geometry) ---

Geom Title=Existing Conditions

River Reach=UNT 062 in LFCCL,Reach-1
Reach XY= 30
      2817869.64      7058872.46      2817780.88      7058898.23
      2817785.16      7059024.00      2817716.57      7059008.32
      2817654.83      7059029.88      2817637.19      7058987.74
      2817570.56      7058993.62      2817531.36      7058950.51
      2817442.18      7058976.96      2817379.47      7059034.78
      2817315.77      7059034.78      2817273.64      7059068.10
      2817055.11      7059034.78      2817041.39      7059043.60
      2817048.25      7059162.17      2816958.10      7059250.37
      2816878.72      7059254.29      2816820.91      7059186.67
      2816799.35      7059186.67      2816729.77      7059228.81
      2816608.26      7059371.88      2816408.36      7059352.28
      2816347.60      7059312.10      2816285.87      7059314.06
      2816237.85      7059286.62      2816095.76      7059303.28
      2816022.26      7059272.90      2815642.05      7059252.33
      2815463.70      7059222.93      2814916.60      7059210.22

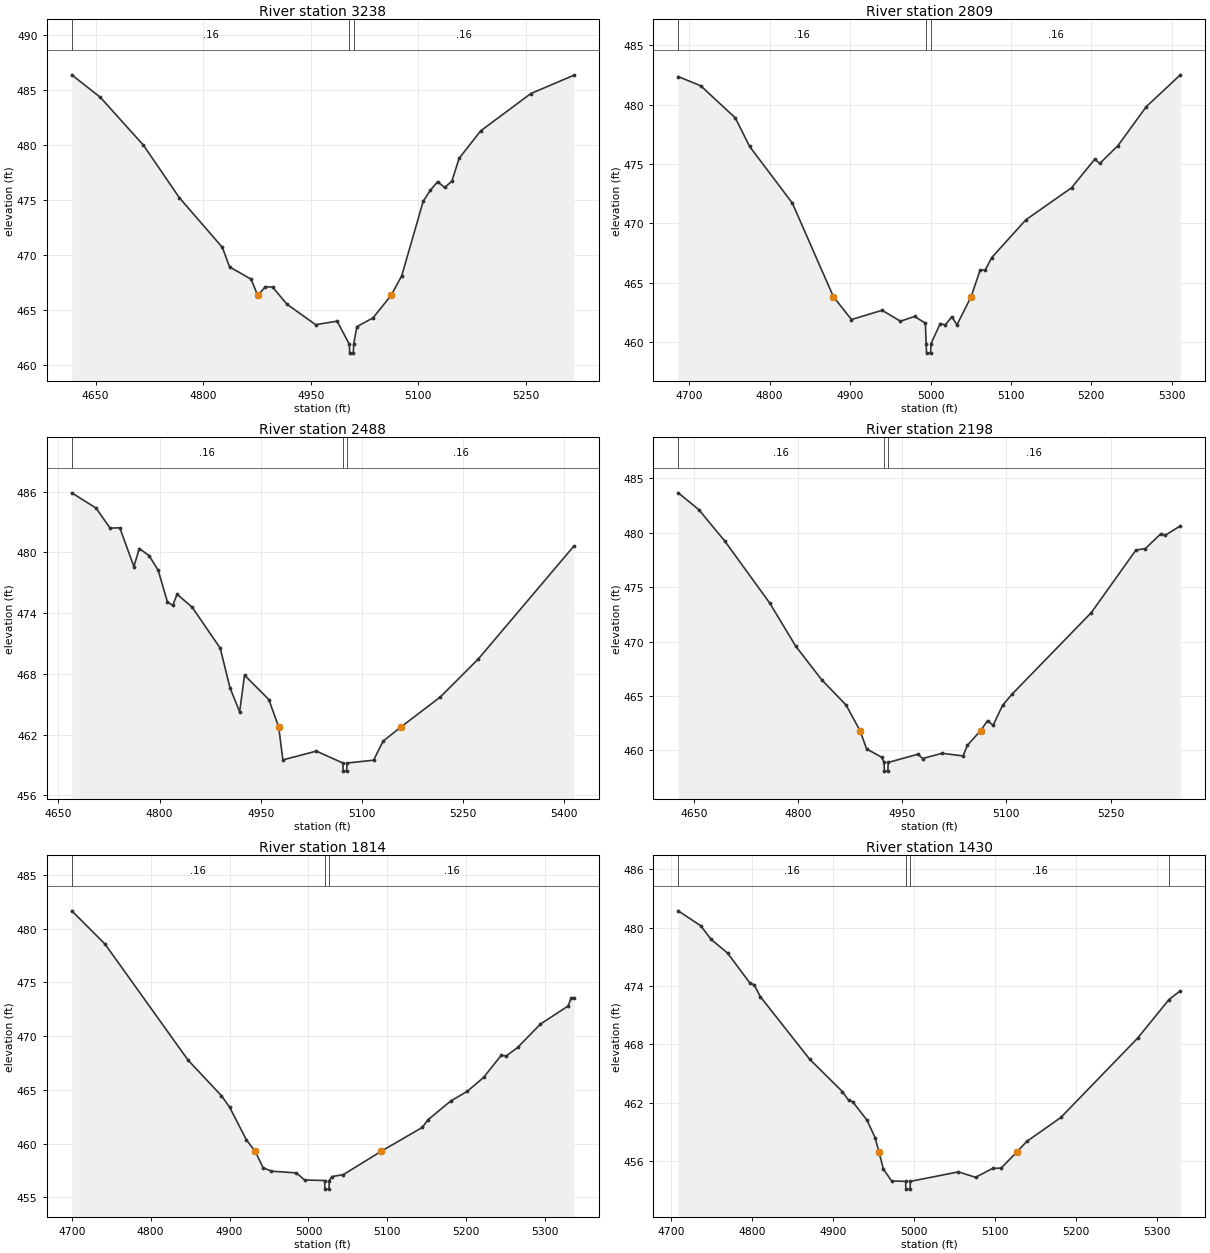
Type RM Length L Ch R = 1,3238,429,429,429
BEGIN DESCRIPTION:
UNT 062 in LFCCL Watershed 8.0
END DESCRIPTION:
XS GIS Cut Line= 3
      2817725.00      7058625.02      2817725.00      7059025.00
      2817725.00      7059325.02
#Sta/Elev= 30
  4616.7  486.37  4656.7  484.32  4716.7  479.98  4766.7  475.22  4826.7  470.71
  4836.7  468.94  4866.7  467.83  4876.0  466.35  4886.7  467.15  4896.7  467.11
  4916.7  465.56  4956.7  463.70  4986.7  464.02  5003.7  461.92  5004.2  461.12
  5009.2  461.12  5009.7  461.92  5014.2  463.52  5036.7  464.32  5061.8  466.35
  5076.7  468.13  5106.7  474.90  5116.7  475.90  5126.7  476.67  5136.7  476.15
  5146.7  476.73  5156.7  478.79  5186.7  481.28  5256.7  484.67  5316.7  486.33
#Mann=3,-1,0
  4616.7    0.16       0  5003.7    0.07       0  5009.7    0.16       0
Bank Sta=4876,5061.8
Exp/Cntr=0.3,0.1

Type RM Length L Ch R = 1,2809,321,321,321
BEGIN DESCRIPTION:
UNT 062 in LFCCL Watershed 7.0
END DESCRIPTION:
XS GIS Cut Line= 3
      2817425.00      7058724.99      2817375.00      7059025.00
      2817575.00      7059275.00
#Sta/Elev= 30
  4686.3  482.37  4714.2  481.60  4757.3  478.89  4775.0  476.49  4828.2  471.71
  4879.2  463.83  4901.7  461.90  4939.8  462.68  4962.6  461.76  4980.3  462.16
  4993.6  461.59  4994.6  459.87  4995.1  459.07  5000.1  459.07  5000.6  459.87
  5012.1  461.56  5018.5  461.45  5026.5  462.14  5032.9  461.45  5050.5  463.83
  5061.7  466.07  5068.1  466.08  5076.1  467.12  5118.5  470.30  5175.3  473.00
  5204.1  475.40  5210.6  475.06  5233.0  476.55  5268.2  479.83  5310.6  482.52
#Mann=3,-1,0
  4686.3    0.16       0  4994.6    0.07       0  5000.6    0.16       0
Bank Sta=4879.2,5050.5
Exp/Cntr=0.3,0.1

Type RM Length L Ch R = 1,2488,290,290,290
BEGIN DESCRIPTION:
UNT 062 in LFCCL Watershed 6.0
END DESCRIPTION:
XS GIS Cut Line= 3
      2816824.99      7058824.99      2817075.00      7059025.00
      2817374.98      7059324.98
#Sta/Elev= 30
  4669.7  485.90  4705.7  484.39  4726.5  482.41  4740.9  482.44  4761.8  478.61
  4769.8  480.39  4784.2  479.70  4797.8  478.25  4811.4  475.14  4819.4  474.76
  4825.8  475.87  4848.2  474.59  4889.8  470.54  4904.2  466.64  4918.6  464.24
  4925.8  467.87  4961.9  465.46  4976.5  462.74  4982.7  459.49  5032.3  460.36
  5071.7  459.18  5072.2  458.38  5077.2  458.38  5077.7  459.18  5117.1  459.46
  5131.3  461.34  5157.6  462.74  5216.1  465.71  5272.7  469.49  5414.1  480.63
#Mann=3,-1,0
  4669.7    0.16       0  5071.7    0.07       0  5077.7    0.16       0
Bank Sta=4976.5,5157.6
Exp/Cntr=0.3,0.1

Type RM Length L Ch R = 1,2198,384,384,384
BEGIN DESCRIPTION:
UNT 062 in LFCCL Watershed 5.0
END DESCRIPTION:
XS GIS Cut Line= 3
      2816774.99      7058924.98      2816975.00      7059275.00
      2817175.00      7059525.00
#Sta/Elev= 30
  4627.2  483.68  4656.7  482.14  4694.2  479.25  4759.0  473.54  4796.4  469.58
  4833.8  466.49  4869.1  464.15  4889.1  461.80  4898.6  460.12  4920.2  459.36
  4923.7  458.88  4924.2  458.08  4929.2  458.08  4929.7  458.88  4972.8  459.64
  4979.2  459.24  5007.3  459.72  5037.5  459.48  5043.9  460.47  5062.8  461.80
  5072.8  462.72  5080.8  462.29  5094.4  464.13  5108.0  465.15  5222.4  472.67
  5286.5  478.41  5300.1  478.55  5322.5  479.92  5328.9  479.78  5350.5  480.64
#Mann=3,-1,0
  4627.2    0.16       0  4923.7    0.07       0  4929.7    0.16       0
Bank Sta=4889.1,5062.8
Exp/Cntr=0.3,0.1

Type RM Length L Ch R = 1,1814,384,384,384
BEGIN DESCRIPTION:
UNT 062 in LFCCL Watershed 4.0
END DESCRIPTION:
XS GIS Cut Line= 3
      2816575.02      7059025.05      2816675.00      7059325.00
      2816874.98      7059574.97
#Sta/Elev= 30
  4700.0  481.66  4742.1  478.57  4847.5  467.76  4889.7  464.46  4900.2  463.37
  4921.3  460.35  4932.5  459.29  4942.4  457.77  4952.9  457.44  4984.6  457.28
  4995.1  456.62  5020.4  456.57  5020.9  455.77  5025.9  455.77  5026.4  456.57
  5029.8  456.94  5044.2  457.12  5092.1  459.29  5144.2  461.51  5151.4  462.22
  5180.3  463.97  5201.1  464.86  5221.9  466.16  5244.3  468.22  5250.7  468.16
  5265.1  468.95  5293.9  471.12  5329.1  472.81  5333.1  473.58  5336.3  473.58
#Mann=3,-1,0
  4700.0    0.16       0  5020.4    0.07       0  5026.4    0.16       0
Bank Sta=4932.5,5092.1
Exp/Cntr=0.3,0.1

Type RM Length L Ch R = 1,1430,318,318,318
BEGIN DESCRIPTION:
UNT 062 in LFCCL Watershed 3.0
END DESCRIPTION:
XS GIS Cut Line= 3
      2816375.01      7059024.96      2816325.00      7059325.00
      2816425.00      7059625.00
#Sta/Elev= 30
  4708.9  481.72  4736.8  480.18  4749.5  478.79  4769.8  477.39  4797.6  474.29
  4802.7  474.14  4810.3  472.91  4871.1  466.50  4911.7  463.16  4919.3  462.28
  4924.4  462.12  4942.1  460.23  4952.2  458.42  4957.0  456.92  4962.4  455.21
  4972.5  453.98  4989.8  453.94  4990.3  453.14  4995.3  453.14  4995.8  453.94
  5055.2  454.91  5076.3  454.35  5097.4  455.27  5107.9  455.30  5126.9  456.92
  5139.6  458.04  5181.7  460.50  5276.6  468.65  5315.2  472.60  5329.3  473.51
#Mann=4,-1,0
  4708.9    0.16       0  4989.8    0.07       0  4995.8    0.16       0
  5315.2    0.05       0
Bank Sta=4957,5126.9
Exp/Cntr=0.3,0.1

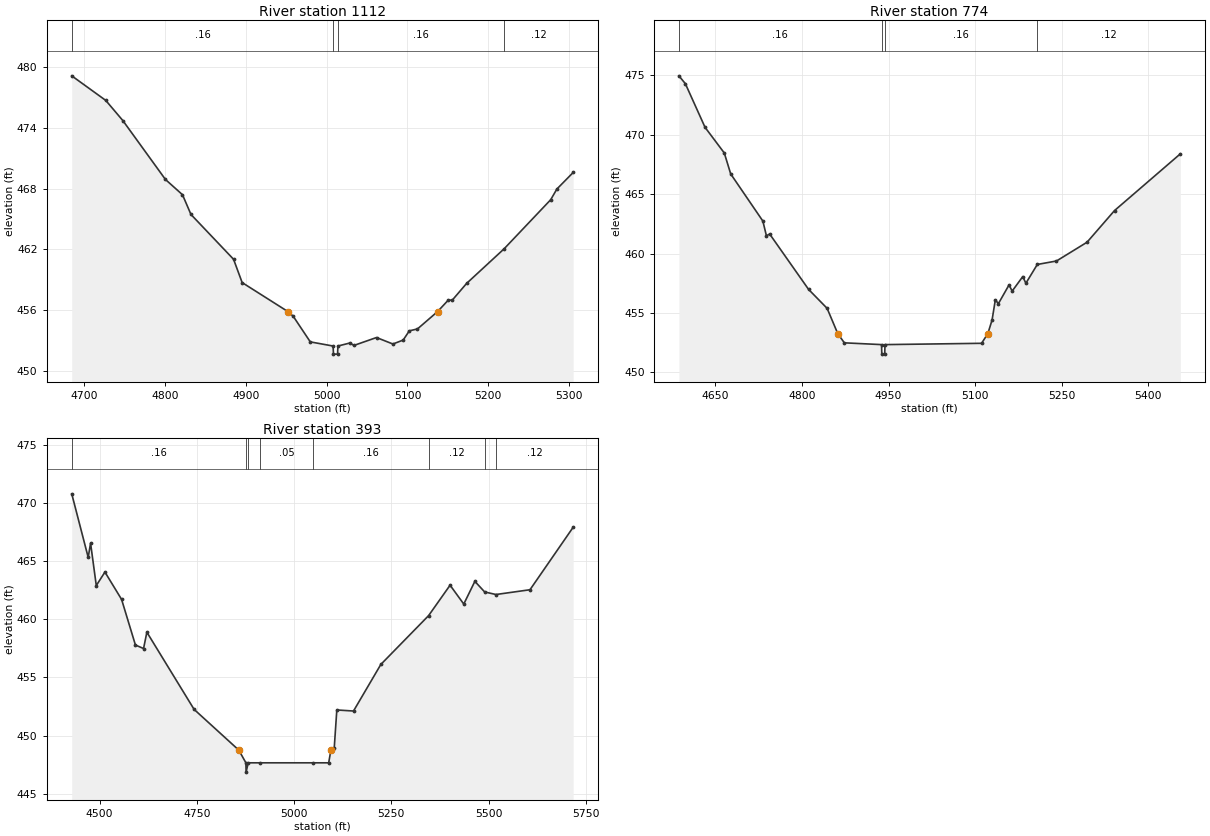
Type RM Length L Ch R = 1,1112,338,338,338
BEGIN DESCRIPTION:
UNT 062 in LFCCL Watershed 2.0
END DESCRIPTION:
XS GIS Cut Line= 3
      2816124.99      7058975.03      2816025.00      7059275.00
      2816074.99      7059574.97
#Sta/Elev= 30
  4684.7  479.14  4726.8  476.71  4747.9  474.72  4800.6  468.90  4821.7  467.39
  4832.2  465.44  4884.9  461.01  4895.5  458.71  4952.2  455.84  4958.7  455.38
  4979.8  452.85  5008.0  452.44  5008.5  451.64  5013.5  451.64  5014.0  452.44
  5028.8  452.74  5033.8  452.50  5061.7  453.28  5082.0  452.64  5094.7  453.03
  5102.3  453.94  5112.4  454.13  5137.2  455.84  5150.4  456.97  5155.5  456.98
  5173.2  458.63  5219.6  462.05  5277.2  466.90  5284.8  467.95  5305.0  469.59
#Mann=4,-1,0
  4684.7    0.16       0  5008.0    0.07       0  5014.0    0.16       0
  5219.6    0.12       0
Bank Sta=4952.2,5137.2
Exp/Cntr=0.3,0.1

Type RM Length L Ch R = 1,774,381,381,381
BEGIN DESCRIPTION:
XS3456A
END DESCRIPTION:
XS GIS Cut Line= 3
      2815867.12      7058884.35      2815686.57      7059252.39
      2815863.66      7059676.03
#Sta/Elev= 30
  4586.7  474.94  4597.9  474.28  4632.0  470.61  4665.4  468.45  4676.5  466.69
  4732.2  462.73  4738.4  461.49  4744.0  461.64  4811.5  456.98  4843.6  455.39
  4862.0  453.27  4873.4  452.49  4937.9  452.34  4938.4  451.54  4943.4  451.54
  4943.9  452.34  5111.3  452.45  5122.2  453.27  5129.5  454.41  5135.1  456.09
  5140.5  455.79  5158.9  457.36  5164.3  456.84  5182.7  458.06  5188.1  457.50
  5207.9  459.08  5241.1  459.37  5294.1  460.95  5341.7  463.61  5455.8  468.38
#Mann=4,-1,0
  4586.7    0.16       0  4937.9    0.07       0  4943.9    0.16       0
  5207.9    0.12       0
Bank Sta=4862,5122.2
Exp/Cntr=0.3,0.1

Type RM Length L Ch R = 1,393,0,0,0
BEGIN DESCRIPTION:
UNT 062 in LFCCL Watershed 1.0
END DESCRIPTION:
XS GIS Cut Line= 3
      2815644.88      7058755.90      2815308.10      7059221.14
      2815853.23      7059682.95
#Sta/Elev= 30
  4428.6  470.78  4470.9  465.32  4477.0  466.54  4491.7  462.90  4513.9  464.06
  4556.7  461.71  4592.3  457.79  4613.2  457.49  4621.7  458.89  4743.1  452.26
  4858.0  448.76  4876.2  447.67  4876.7  446.87  4882.2  447.67  4912.8  447.67
  5049.5  447.67  5089.0  447.67  5094.7  448.76  5103.3  448.95  5109.9  452.21
  5152.8  452.12  5223.0  456.12  5345.9  460.32  5401.0  462.93  5436.2  461.31
  5464.7  463.26  5489.9  462.35  5518.9  462.13  5606.4  462.54  5717.4  467.91
#Mann=8,-1,0
  4428.6    0.16       0  4876.2   0.033       0  4882.2    0.16       0
  4912.8    0.05       0  5049.5    0.16       0  5345.9    0.12       0
  5489.9    0.16       0  5518.9    0.12       0
Bank Sta=4858,5094.7
Exp/Cntr=0.3,0.1

Chan Stop Cuts=-1