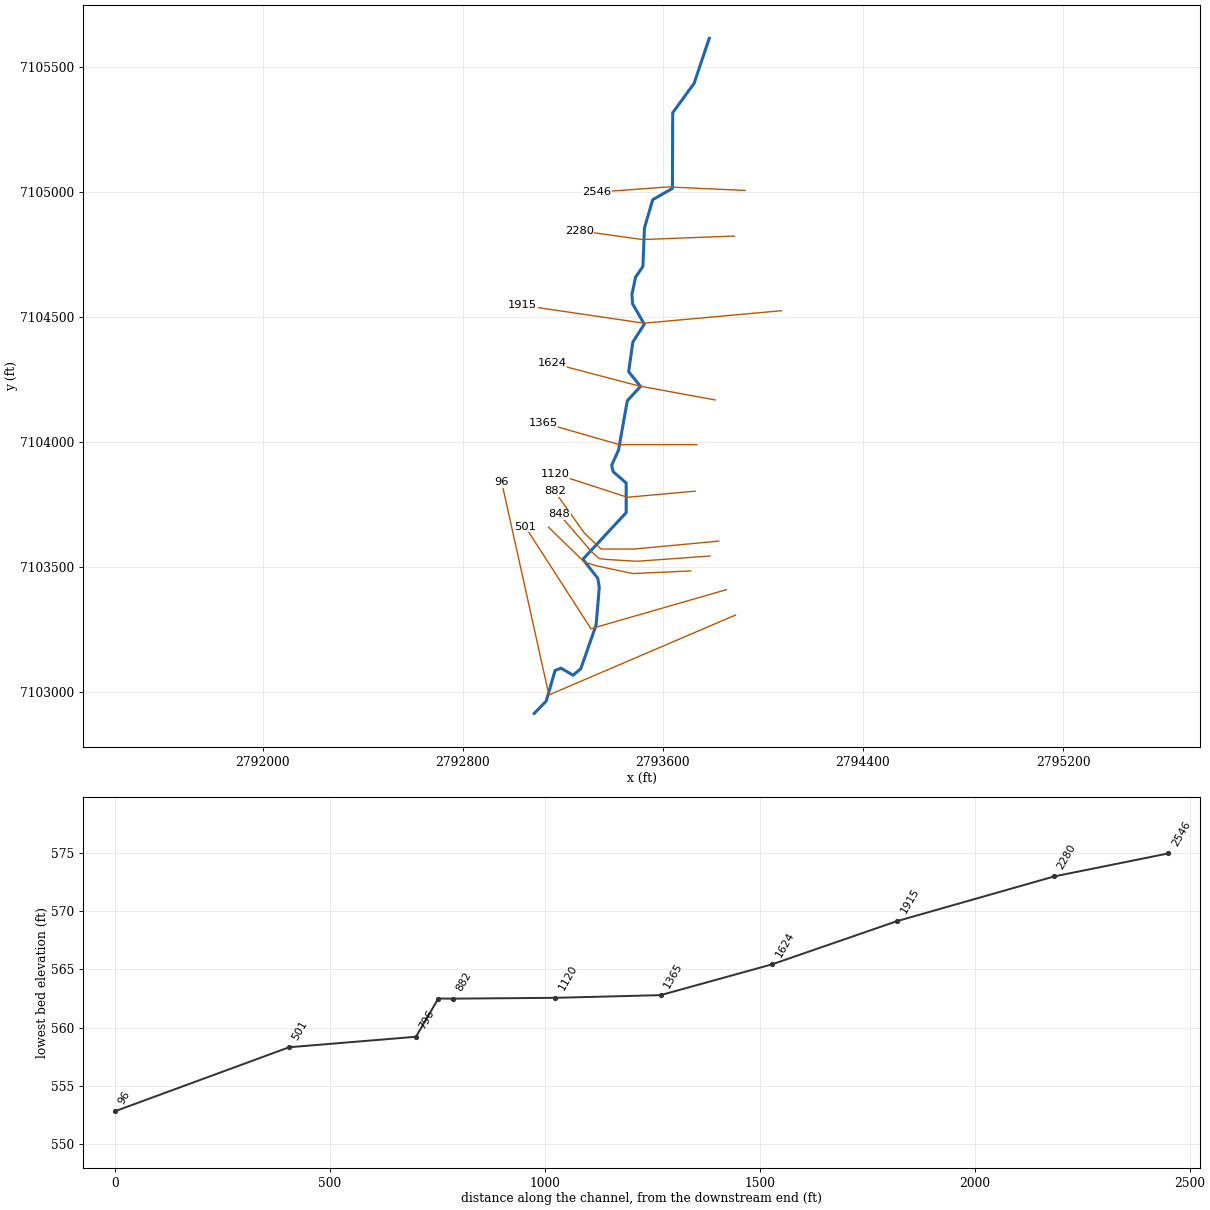
--- UNT 064 in LFCCL Watershed.prj (project) ---

Proj Title=UNT 064 in LFCCL Watershed Base Level Engineering
Current Plan=p01
Default Exp/Contr=0.3,0.1
English Units
Geom File=g01
Flow File=f01
Plan File=p01
BEGIN DESCRIPTION:
UNT 064 in LFCCL Watershed
END DESCRIPTION:

--- UNT 064 in LFCCL Watershed.p01 (plan) ---

Plan Title=Multiple Run
Short Identifier=Multiple
Geom File=g01
Flow File=f01
Subcritical Flow
K Sum by GR= 0
Std Step Tol= 0.01
Critical Tol= 0.01
Num of Std Step Trials= 20
Max Error Tol= 0.3
Flow Tol Ratio= 0.001
Split Flow NTrial= 30
Split Flow Tol= 0.02
Split Flow Ratio= 0.02
Log Output Level= 0
Friction Slope Method= 1
Unsteady Friction Slope Method= 2
Unsteady Bridges Friction Slope Method= 1
Parabolic Critical Depth
Global Vel Dist=  1 , 1 , 1
Global Log Level= 0
CheckData=True
Encroach Param= -1, 0, 0, 0
BEGIN DESCRIPTION:
Multiple Run
END DESCRIPTION:

--- UNT 064 in LFCCL Watershed.f01 (steady flow) ---

Flow Title=Multiple
Number of Profiles=7
Profile Names=10-year,25-year,50-year,1pct_min,100-year,1pct_plu,500-year
River Rch & RM= UNT 064 in LFCCL,Reach-1,2546
     257     322     371     213     425     849     555
Boundary for River Rch & Prof#=UNT 064 in LFCCL,Reach-1,1
Up Type=0
Dn Type=3
Dn Slope=0.005
Boundary for River Rch & Prof#=UNT 064 in LFCCL,Reach-1,2
Up Type=0
Dn Type=3
Dn Slope=0.005
Boundary for River Rch & Prof#=UNT 064 in LFCCL,Reach-1,3
Up Type=0
Dn Type=3
Dn Slope=0.005
Boundary for River Rch & Prof#=UNT 064 in LFCCL,Reach-1,4
Up Type=0
Dn Type=3
Dn Slope=0.005
Boundary for River Rch & Prof#=UNT 064 in LFCCL,Reach-1,5
Up Type=0
Dn Type=3
Dn Slope=0.005
Boundary for River Rch & Prof#=UNT 064 in LFCCL,Reach-1,6
Up Type=0
Dn Type=3
Dn Slope=0.005
Boundary for River Rch & Prof#=UNT 064 in LFCCL,Reach-1,7
Up Type=0
Dn Type=3
Dn Slope=0.005

--- UNT 064 in LFCCL Watershed.g01 (geometry) ---

Geom Title=Existing Conditions

River Reach=UNT 064 in LFCCL,Reach-1
Reach XY= 30
      2793785.59      7105615.71      2793724.92      7105434.99
      2793639.51      7105317.85      2793638.31      7105014.91
      2793559.33      7104969.27      2793526.47      7104856.13
      2793520.23      7104701.75      2793491.04      7104659.60
      2793476.41      7104590.11      2793479.19      7104552.38
      2793525.79      7104470.90      2793480.30      7104399.93
      2793463.28      7104280.52      2793510.72      7104221.74
      2793457.90      7104164.48      2793422.82      7103966.75
      2793395.27      7103905.48      2793401.62      7103880.05
      2793453.41      7103835.14      2793453.51      7103716.41
      2793280.23      7103529.70      2793339.97      7103453.29
      2793345.85      7103415.99      2793333.18      7103266.71
      2793271.96      7103091.40      2793241.00      7103065.25
      2793192.65      7103093.69      2793169.10      7103084.20
      2793133.58      7102961.55      2793085.74      7102912.47

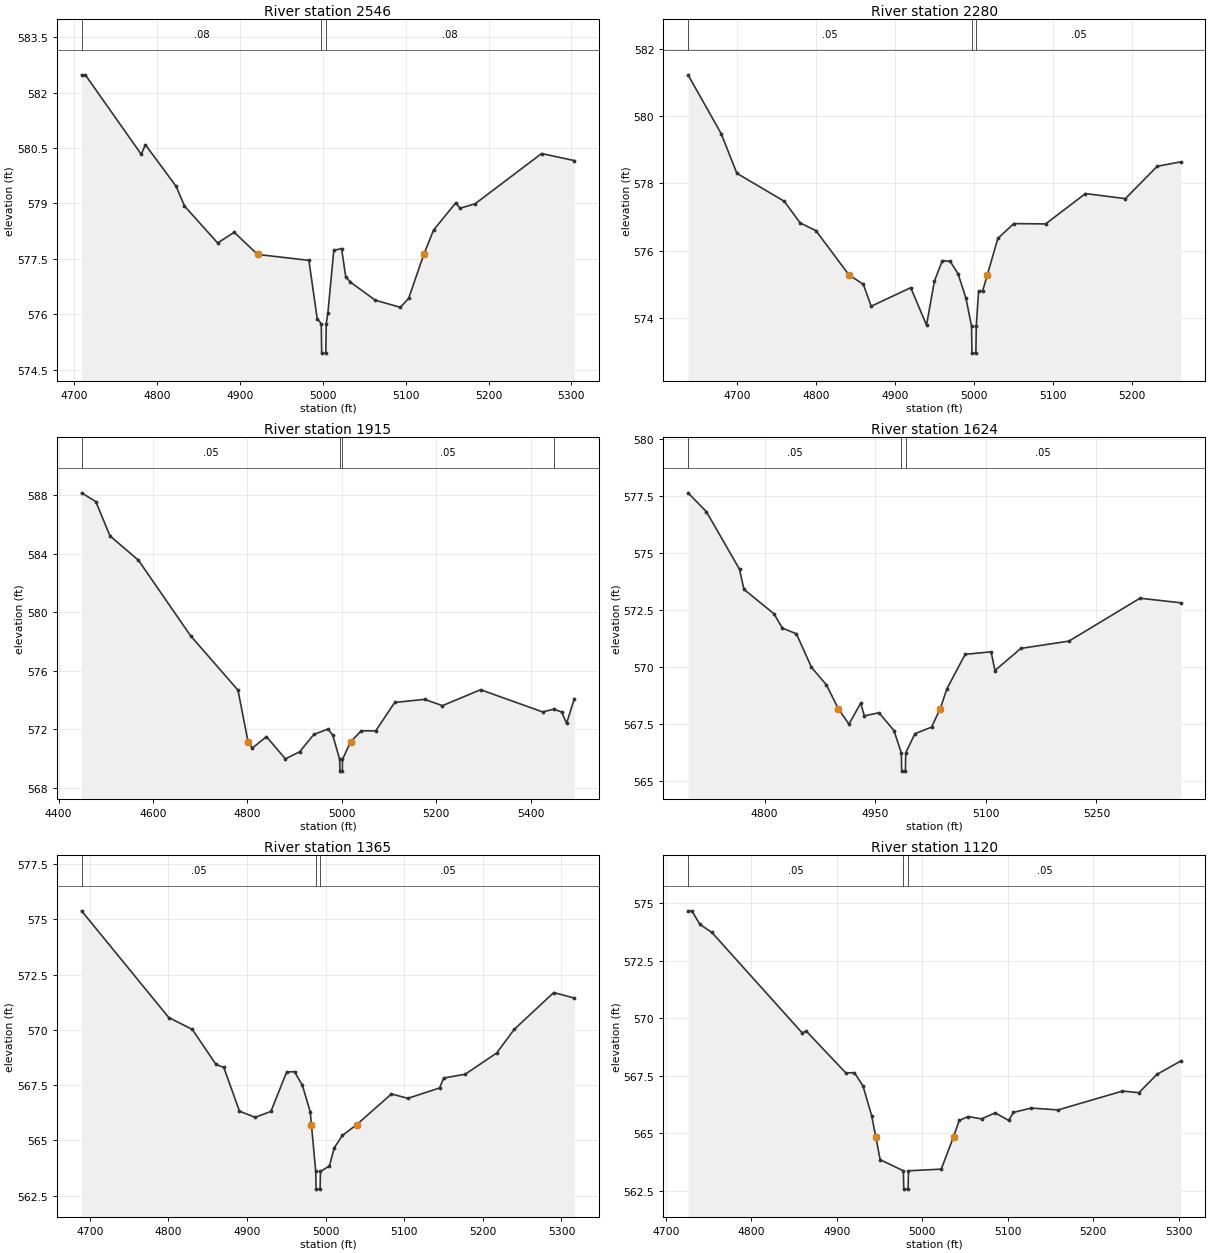
Type RM Length L Ch R = 1,2546,266,266,266
BEGIN DESCRIPTION:
XS3458A
END DESCRIPTION:
XS GIS Cut Line= 3
      2793929.03      7105006.60      2793620.04      7105020.65
      2793335.63      7104999.58
#Sta/Elev= 30
  4709.0  582.48  4713.5  582.48  4781.0  580.33  4786.0  580.59  4823.2  579.46
  4833.2  578.93  4873.2  577.93  4893.2  578.22  4921.4  577.62  4983.3  577.46
  4993.3  575.88  4998.2  575.75  4998.7  574.95  5003.7  574.95  5004.2  575.75
  5006.2  576.04  5013.3  577.73  5022.7  577.78  5027.7  577.02  5033.4  576.87
  5063.5  576.38  5093.6  576.19  5103.6  576.43  5121.9  577.62  5133.7  578.28
  5160.6  579.02  5165.6  578.87  5183.8  578.99  5264.0  580.35  5303.5  580.16
#Mann=3,-1,0
  4709.0    0.08       0  4998.2    0.07       0  5004.2    0.08       0
Bank Sta=4921.4,5121.9
Exp/Cntr=0.3,0.1

Type RM Length L Ch R = 1,2280,365,365,365
BEGIN DESCRIPTION:
XS3459A
END DESCRIPTION:
XS GIS Cut Line= 3
      2793886.88      7104824.05      2793518.23      7104810.00
      2793265.47      7104845.11
#Sta/Elev= 30
  4638.1  581.22  4680.0  579.48  4700.0  578.30  4760.1  577.47  4780.1  576.83
  4800.1  576.60  4841.9  575.29  4860.1  575.01  4870.1  574.36  4920.2  574.91
  4940.2  573.80  4950.2  575.11  4960.2  575.71  4970.2  575.69  4980.2  575.32
  4990.2  574.59  4997.2  573.77  4997.7  572.97  5002.7  572.97  5003.2  573.77
  5006.1  574.81  5011.2  574.81  5017.2  575.29  5030.5  576.37  5050.7  576.81
  5091.0  576.80  5141.5  577.70  5192.0  577.55  5232.4  578.51  5262.2  578.64
#Mann=3,-1,0
  4638.1    0.05       0  4997.2    0.03       0  5003.2    0.05       0
Bank Sta=4841.9,5017.2
Exp/Cntr=0.3,0.1

Type RM Length L Ch R = 1,1915,291,291,291
BEGIN DESCRIPTION:
UNT 064 in LFCCL Watershed 2.0
END DESCRIPTION:
XS GIS Cut Line= 3
      2794075.05      7104525.00      2793525.00      7104475.00
      2793038.64      7104546.50
#Sta/Elev= 30
  4448.6  588.18  4478.8  587.58  4508.9  585.23  4569.1  583.57  4679.6  578.40
  4780.0  574.68  4801.3  571.16  4810.1  570.71  4840.3  571.50  4880.4  569.98
  4910.5  570.46  4940.7  571.65  4970.8  572.02  4980.8  571.60  4995.4  569.94
  4995.9  569.14  5000.9  569.14  5001.4  569.94  5018.8  571.16  5041.3  571.90
  5071.7  571.89  5112.1  573.84  5175.3  574.05  5213.2  573.62  5294.0  574.71
  5425.4  573.19  5448.9  573.38  5465.9  573.18  5476.0  572.41  5492.5  574.08
#Mann=4,-1,0
  4448.6    0.05       0  4995.4    0.03       0  5001.4    0.05       0
  5448.9     0.1       0
Bank Sta=4801.3,5018.8
Exp/Cntr=0.3,0.1

Type RM Length L Ch R = 1,1624,259,259,259
BEGIN DESCRIPTION:
XS3465A
END DESCRIPTION:
XS GIS Cut Line= 3
      2793809.59      7104167.55      2793504.19      7104223.72
      2793158.34      7104314.55
#Sta/Elev= 30
  4696.2  577.63  4721.2  576.80  4766.0  574.28  4772.0  573.40  4812.7  572.33
  4824.1  571.70  4843.2  571.45  4863.6  569.98  4883.9  569.21  4899.9  568.17
  4914.4  567.49  4930.3  568.41  4935.3  567.85  4955.1  567.99  4975.4  567.21
  4985.4  566.23  4985.9  565.43  4990.9  565.43  4991.4  566.23  5003.8  567.07
  5026.4  567.36  5038.2  568.17  5047.2  569.04  5072.0  570.55  5107.2  570.66
  5112.3  569.84  5147.5  570.81  5212.7  571.13  5309.0  573.01  5364.3  572.81
#Mann=3,-1,0
  4696.2    0.05       0  4985.4    0.03       0  4991.4    0.05       0
Bank Sta=4899.9,5038.2
Exp/Cntr=0.3,0.1

Type RM Length L Ch R = 1,1365,245,245,245
BEGIN DESCRIPTION:
XS3464A
END DESCRIPTION:
XS GIS Cut Line= 3
      2793735.93      7103988.50      2793426.96      7103988.50
      2793121.49      7104076.28
#Sta/Elev= 30
  4689.5  575.39  4800.4  570.56  4830.4  570.02  4860.4  568.44  4870.4  568.30
  4890.4  566.32  4910.4  566.04  4930.4  566.31  4950.4  568.09  4960.4  568.11
  4970.4  567.49  4980.4  566.29  4981.9  565.71  4987.4  563.59  4987.9  562.79
  4992.9  562.79  4993.4  563.59  5004.8  563.84  5010.9  564.66  5021.3  565.22
  5039.5  565.71  5083.7  567.10  5104.6  566.90  5144.9  567.37  5150.1  567.82
  5177.4  567.99  5217.5  568.95  5239.8  570.02  5290.1  571.69  5316.3  571.44
#Mann=3,-1,0
  4689.5    0.05       0  4987.4    0.03       0  4993.4    0.05       0
Bank Sta=4981.9,5039.5
Exp/Cntr=0.3,0.1

Type RM Length L Ch R = 1,1120,238,238,238
BEGIN DESCRIPTION:
XS3463A
END DESCRIPTION:
XS GIS Cut Line= 3
      2793728.87      7103802.43      2793458.55      7103777.86
      2793168.55      7103872.20
#Sta/Elev= 30
  4726.1  574.68  4730.6  574.68  4740.0  574.09  4754.0  573.74  4859.5  569.37
  4864.5  569.44  4910.7  567.62  4920.8  567.63  4930.8  567.05  4940.9  565.76
  4945.7  564.84  4950.9  563.84  4978.0  563.36  4978.5  562.56  4983.5  562.56
  4984.0  563.36  5022.3  563.43  5036.7  564.84  5043.3  565.55  5053.8  565.72
  5069.4  565.62  5085.4  565.88  5101.3  565.55  5106.6  565.90  5127.5  566.09
  5159.0  566.01  5234.3  566.83  5253.6  566.76  5274.7  567.56  5302.5  568.14
#Mann=3,-1,0
  4726.1    0.05       0  4978.0    0.03       0  4984.0    0.05       0
Bank Sta=4945.7,5036.7
Exp/Cntr=0.3,0.1

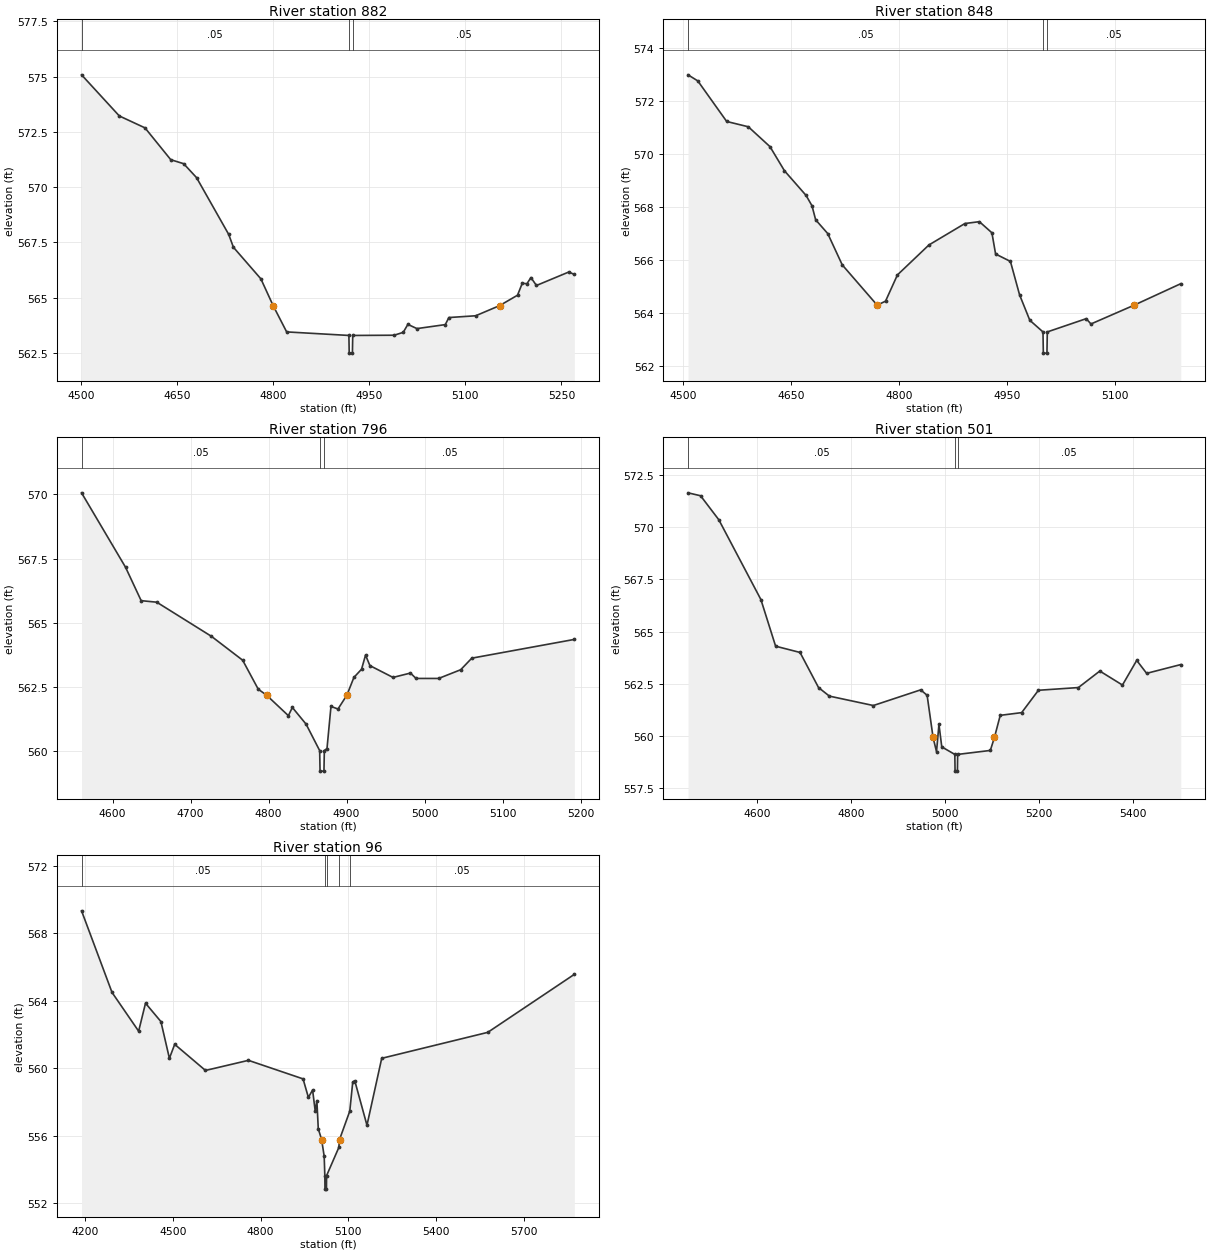
Type RM Length L Ch R = 1,882,34,34,34
BEGIN DESCRIPTION:
XS3462A
END DESCRIPTION:
XS GIS Cut Line= 5
      2793823.61      7103602.32      2793486.64      7103570.73
      2793353.23      7103570.73      2793286.53      7103633.92
      2793168.00      7103801.25
#Sta/Elev= 30
  4501.3  575.08  4560.2  573.22  4600.3  572.68  4640.5  571.24  4660.6  571.06
  4680.7  570.43  4730.9  567.86  4738.2  567.28  4781.1  565.85  4800.2  564.64
  4821.3  563.45  4918.4  563.29  4918.9  562.49  4923.9  562.49  4924.4  563.29
  4989.0  563.30  5003.2  563.43  5010.4  563.79  5024.6  563.60  5068.8  563.78
  5074.4  564.10  5116.2  564.18  5153.6  564.64  5181.5  565.11  5188.9  565.65
  5196.2  565.63  5202.4  565.91  5211.0  565.55  5261.5  566.16  5270.1  566.05
#Mann=3,-1,0
  4501.3    0.05       0  4918.4    0.03       0  4924.4    0.05       0
Bank Sta=4800.2,5153.6
Exp/Cntr=0.3,0.1

Type RM Length L Ch R = 1,848,52,52,52
BEGIN DESCRIPTION:
XS3461A
END DESCRIPTION:
XS GIS Cut Line= 6
      2793788.52      7103542.64      2793497.17      7103521.58
      2793377.81      7103528.60      2793346.21      7103532.11
      2793314.61      7103560.20      2793185.24      7103710.55
#Sta/Elev= 30
  4506.9  573.00  4520.5  572.77  4560.6  571.24  4590.6  571.04  4620.7  570.29
  4640.8  569.38  4670.8  568.45  4679.0  568.06  4684.1  567.53  4700.9  567.01
  4721.0  565.83  4769.5  564.31  4781.1  564.46  4797.6  565.45  4841.3  566.58
  4891.3  567.39  4911.4  567.46  4928.8  567.04  4933.9  566.24  4954.5  565.96
  4967.2  564.70  4981.4  563.74  4999.7  563.30  5000.2  562.50  5005.2  562.50
  5005.7  563.30  5059.7  563.80  5066.3  563.60  5126.3  564.31  5191.0  565.12
#Mann=3,-1,0
  4506.9    0.05       0  4999.7    0.03       0  5005.7    0.05       0
Bank Sta=4769.5,5126.3
Exp/Cntr=0.3,0.1

Type RM Length L Ch R = 1,796,295,295,295
BEGIN DESCRIPTION:
XS3460A
END DESCRIPTION:
XS GIS Cut Line= 5
      2793711.30      7103482.96      2793479.62      7103472.43
      2793332.17      7103504.03      2793286.53      7103518.07
      2793142.56      7103658.52
#Sta/Elev= 30
  4560.3  570.06  4616.7  567.16  4636.7  565.86  4656.7  565.80  4726.8  564.47
  4766.8  563.54  4786.8  562.41  4797.4  562.18  4825.4  561.38  4830.5  561.70
  4848.1  561.05  4865.5  560.02  4866.0  559.22  4871.0  559.22  4871.5  560.02
  4874.9  560.10  4880.0  561.74  4889.0  561.64  4900.4  562.18  4909.4  562.87
  4919.2  563.19  4924.3  563.74  4929.9  563.33  4959.5  562.87  4981.9  563.04
  4989.0  562.83  5018.0  562.83  5046.3  563.17  5060.5  563.62  5191.9  564.35
#Mann=3,-1,0
  4560.3    0.05       0  4865.5    0.03       0  4871.5    0.05       0
Bank Sta=4797.4,4900.4
Exp/Cntr=0.3,0.1

Type RM Length L Ch R = 1,501,405,405,405
BEGIN DESCRIPTION:
Mapping XS 1ec769f0
END DESCRIPTION:
XS GIS Cut Line= 3
      2793854.17      7103407.84      2793312.53      7103251.59
      2793049.87      7103659.88
#Sta/Elev= 30
  4452.8  571.64  4479.5  571.50  4518.4  570.35  4608.0  566.53  4639.3  564.30
  4691.3  564.00  4730.7  562.32  4753.8  561.91  4847.4  561.46  4948.2  562.21
  4961.9  561.95  4974.6  559.93  4981.9  559.25  4987.1  560.56  4993.1  559.48
  5020.9  559.12  5021.4  558.32  5026.4  558.32  5026.9  559.12  5096.5  559.31
  5105.2  559.93  5117.6  560.99  5163.2  561.12  5198.9  562.19  5284.0  562.32
  5329.6  563.11  5377.8  562.44  5408.2  563.62  5429.3  563.00  5502.0  563.42
#Mann=3,-1,0
  4452.8    0.05       0  5020.9    0.03       0  5026.9    0.05       0
Bank Sta=4974.6,5105.2
Exp/Cntr=0.3,0.1

Type RM Length L Ch R = 1,96,0,0,0
BEGIN DESCRIPTION:
UNT 064 in LFCCL Watershed 1.0
END DESCRIPTION:
XS GIS Cut Line= 3
      2793890.67      7103306.29      2793144.41      7102986.23
      2792955.75      7103837.57
#Sta/Elev= 30
  4188.0  569.34  4292.1  564.50  4383.1  562.20  4406.6  563.86  4459.2  562.77
  4488.2  560.59  4506.3  561.42  4611.5  559.87  4758.3  560.47  4945.0  559.37
  4963.2  558.27  4977.6  558.71  4986.7  557.44  4992.2  558.08  4997.0  556.41
  5008.4  555.77  5017.2  554.78  5019.4  553.63  5019.9  552.83  5024.9  552.83
  5025.4  553.63  5067.2  555.30  5069.6  555.77  5104.7  557.46  5114.7  559.17
  5121.7  559.26  5163.4  556.62  5213.8  560.59  5576.2  562.13  5872.0  565.57
#Mann=5,-1,0
  4188.0    0.05       0  5019.4    0.03       0  5025.4    0.05       0
  5067.2    0.16       0  5104.7    0.05       0
Bank Sta=5008.4,5069.6
Exp/Cntr=0.3,0.1

Chan Stop Cuts=-1