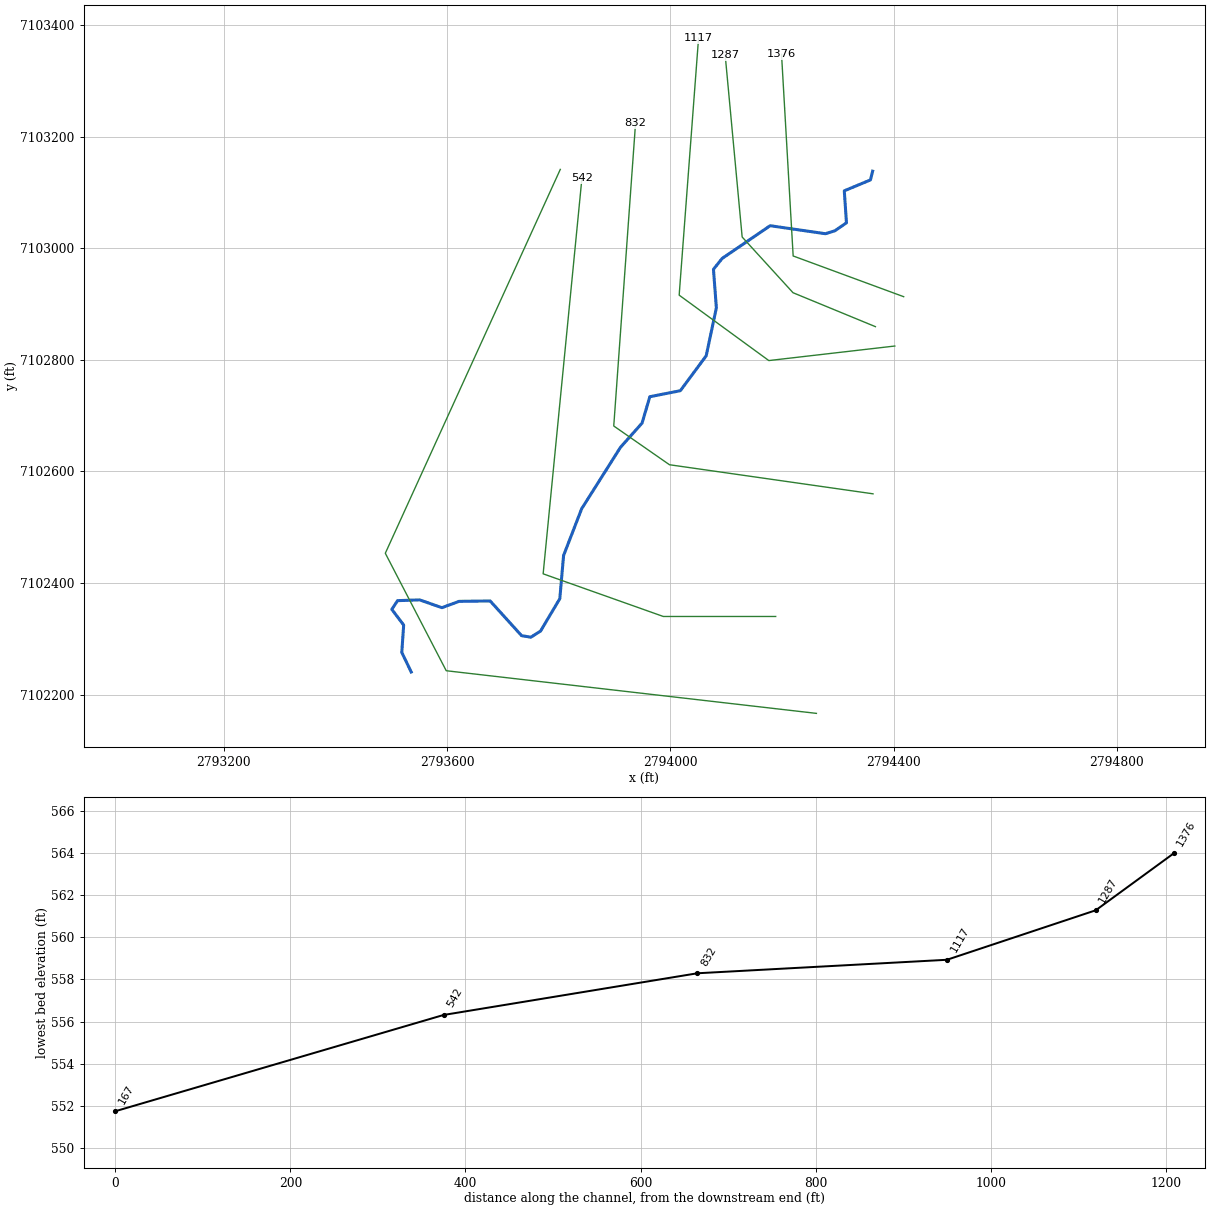
--- UNT 065 in LFCCL Watershed.prj (project) ---

Proj Title=UNT 065 in LFCCL Watershed Base Level Engineering
Current Plan=p01
Default Exp/Contr=0.3,0.1
English Units
Geom File=g01
Flow File=f01
Plan File=p01
BEGIN DESCRIPTION:
UNT 065 in LFCCL Watershed
END DESCRIPTION:

--- UNT 065 in LFCCL Watershed.p01 (plan) ---

Plan Title=Multiple Run
Short Identifier=Multiple
Geom File=g01
Flow File=f01
Subcritical Flow
K Sum by GR= 0
Std Step Tol= 0.01
Critical Tol= 0.01
Num of Std Step Trials= 20
Max Error Tol= 0.3
Flow Tol Ratio= 0.001
Split Flow NTrial= 30
Split Flow Tol= 0.02
Split Flow Ratio= 0.02
Log Output Level= 0
Friction Slope Method= 1
Unsteady Friction Slope Method= 2
Unsteady Bridges Friction Slope Method= 1
Parabolic Critical Depth
Global Vel Dist=  1 , 1 , 1
Global Log Level= 0
CheckData=True
Encroach Param= -1, 0, 0, 0
BEGIN DESCRIPTION:
Multiple Run
END DESCRIPTION:

--- UNT 065 in LFCCL Watershed.f01 (steady flow) ---

Flow Title=Multiple
Number of Profiles=7
Profile Names=10-year,25-year,50-year,1pct_min,100-year,1pct_plu,500-year
River Rch & RM= UNT 065 in LFCCL,Reach-1,1376
     173     210     238     134     268     534     338
Boundary for River Rch & Prof#=UNT 065 in LFCCL,Reach-1,1
Up Type=0
Dn Type=3
Dn Slope=0.005
Boundary for River Rch & Prof#=UNT 065 in LFCCL,Reach-1,2
Up Type=0
Dn Type=3
Dn Slope=0.005
Boundary for River Rch & Prof#=UNT 065 in LFCCL,Reach-1,3
Up Type=0
Dn Type=3
Dn Slope=0.005
Boundary for River Rch & Prof#=UNT 065 in LFCCL,Reach-1,4
Up Type=0
Dn Type=3
Dn Slope=0.005
Boundary for River Rch & Prof#=UNT 065 in LFCCL,Reach-1,5
Up Type=0
Dn Type=3
Dn Slope=0.005
Boundary for River Rch & Prof#=UNT 065 in LFCCL,Reach-1,6
Up Type=0
Dn Type=3
Dn Slope=0.005
Boundary for River Rch & Prof#=UNT 065 in LFCCL,Reach-1,7
Up Type=0
Dn Type=3
Dn Slope=0.005

--- UNT 065 in LFCCL Watershed.g01 (geometry) ---

Geom Title=Existing Conditions

River Reach=UNT 065 in LFCCL,Reach-1
Reach XY= 30
      2794362.22      7103137.93      2794358.31      7103122.31
      2794311.44      7103102.78      2794315.34      7103045.48
      2794294.51      7103031.16      2794277.58      7103025.95
      2794178.62      7103040.28      2794092.69      7102981.68
      2794077.06      7102962.15      2794082.27      7102893.14
      2794064.04      7102807.20      2794017.74      7102744.69
      2793963.09      7102733.94      2793949.11      7102686.56
      2793910.56      7102643.37      2793840.94      7102533.21
      2793808.55      7102449.48      2793801.80      7102372.12
      2793767.32      7102314.13      2793749.95      7102303.10
      2793733.33      7102305.87      2793677.01      7102368.03
      2793621.39      7102367.31      2793590.58      7102355.99
      2793550.71      7102369.96      2793511.11      7102368.57
      2793500.84      7102353.00      2793522.08      7102324.82
      2793518.70      7102275.81      2793535.59      7102240.71

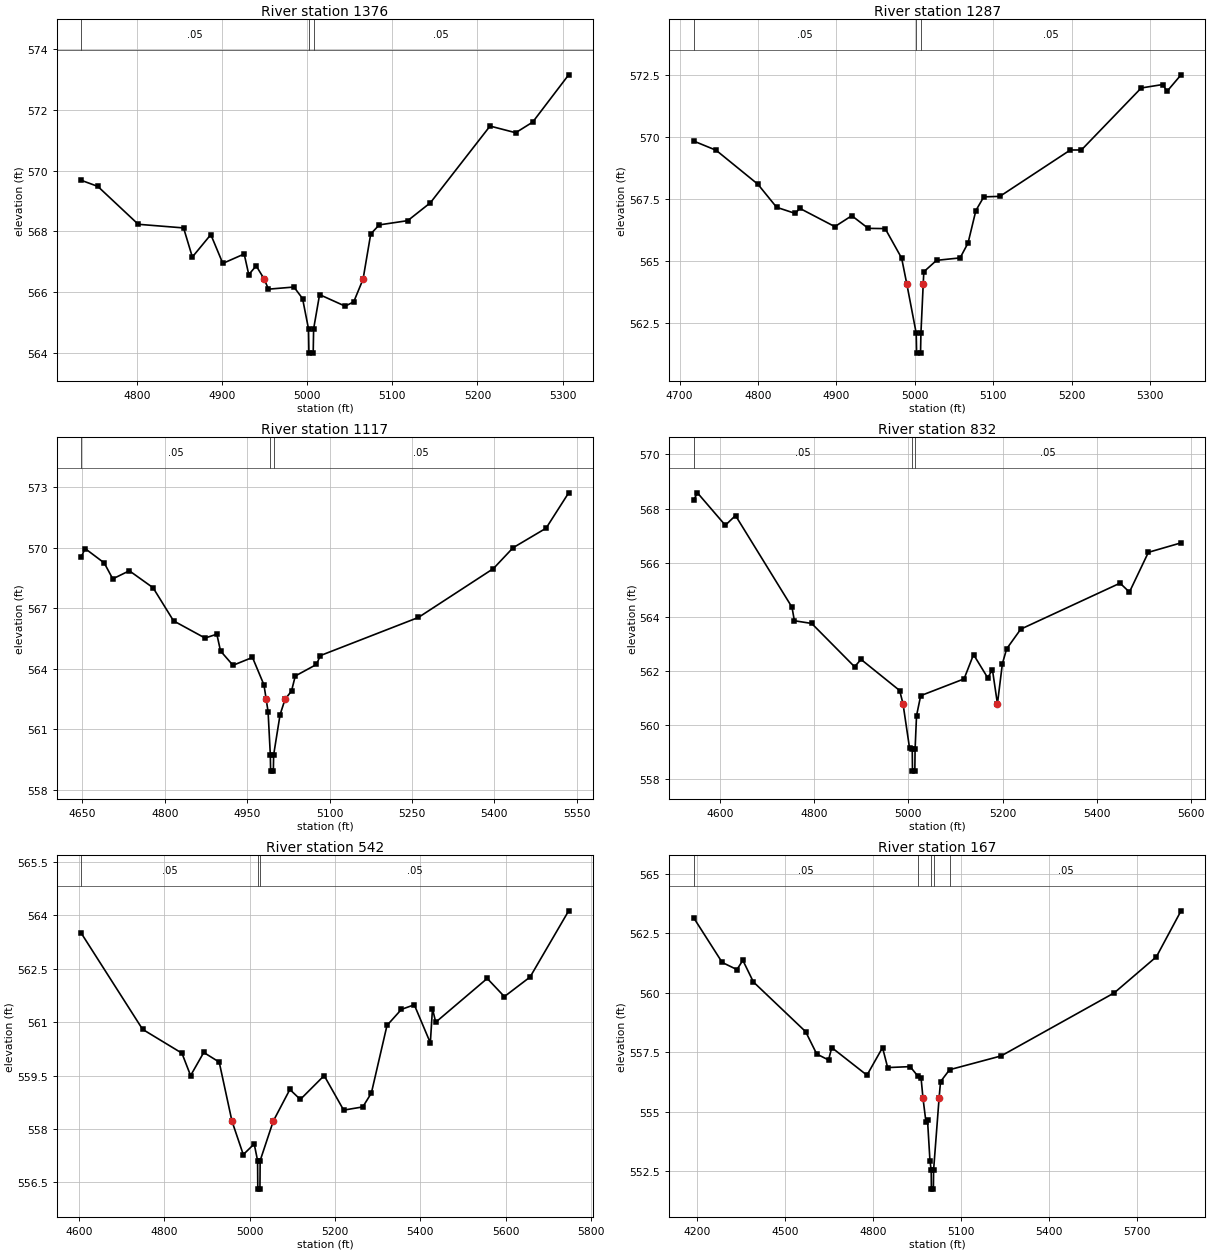
Type RM Length L Ch R = 1,1376,89,89,89
BEGIN DESCRIPTION:
UNT 065 in LFCCL Watershed 1.0
END DESCRIPTION:
XS GIS Cut Line= 3
      2794417.80      7102913.14      2794219.85      7102986.07
      2794199.02      7103347.22
#Sta/Elev= 30
  4734.5  569.68  4753.9  569.48  4801.4  568.23  4854.7  568.11  4865.0  567.15
  4886.7  567.89  4900.8  566.94  4925.9  567.25  4931.3  566.57  4940.0  566.86
  4949.5  566.42  4954.4  566.09  4984.4  566.16  4994.5  565.78  5001.5  564.78
  5002.0  563.98  5007.0  563.98  5007.5  564.78  5014.5  565.91  5044.5  565.53
  5054.6  565.67  5065.6  566.42  5074.6  567.91  5084.6  568.21  5118.1  568.35
  5144.7  568.94  5214.8  571.47  5244.9  571.25  5264.9  571.60  5307.2  573.16
#Mann=3,-1,0
  4734.5    0.05       0  5001.5    0.03       0  5007.5    0.05       0
Bank Sta=4949.5,5065.6
Exp/Cntr=0.3,0.1

Type RM Length L Ch R = 1,1287,170,170,170
BEGIN DESCRIPTION:
Mapping XS f4c88d55
END DESCRIPTION:
XS GIS Cut Line= 4
      2794367.21      7102859.44      2794219.62      7102920.22
      2794128.48      7103020.04      2794098.10      7103345.54
#Sta/Elev= 30
  4718.0  569.83  4746.6  569.46  4799.9  568.09  4823.8  567.16  4847.8  566.91
  4853.2  567.12  4898.1  566.38  4919.7  566.82  4940.7  566.31  4962.3  566.30
  4983.3  565.11  4990.0  564.05  5001.9  562.08  5002.4  561.28  5007.4  561.28
  5007.9  562.08  5010.8  564.05  5011.6  564.56  5027.8  565.02  5057.9  565.12
  5068.0  565.72  5078.0  567.03  5088.1  567.58  5108.6  567.60  5198.5  569.47
  5212.6  569.47  5288.9  571.97  5316.6  572.11  5321.7  571.83  5339.7  572.50
#Mann=3,-1,0
  4718.0    0.05       0  5001.9    0.03       0  5007.9    0.05       0
Bank Sta=4990,5010.8
Exp/Cntr=0.3,0.1

Type RM Length L Ch R = 1,1117,285,285,285
BEGIN DESCRIPTION:
Mapping XS 3a383ae4
END DESCRIPTION:
XS GIS Cut Line= 4
      2794401.92      7102824.73      2794176.22      7102798.69
      2794015.63      7102915.88      2794050.35      7103375.97
#Sta/Elev= 30
  4647.9  569.54  4654.9  569.95  4689.6  569.24  4705.2  568.45  4735.4  568.85
  4778.6  568.01  4815.9  566.37  4873.2  565.52  4894.7  565.71  4901.4  564.88
  4924.1  564.17  4959.6  564.56  4980.5  563.20  4984.6  562.48  4988.0  561.87
  4992.1  559.73  4992.6  558.93  4997.6  558.93  4998.1  559.73  5009.8  561.72
  5018.8  562.48  5030.7  562.90  5037.5  563.64  5076.0  564.21  5083.1  564.65
  5261.7  566.54  5398.3  568.96  5434.0  569.99  5494.2  570.96  5535.3  572.71
#Mann=3,-1,0
  4647.9    0.05       0  4992.1    0.03       0  4998.1    0.05       0
Bank Sta=4984.6,5018.8
Exp/Cntr=0.3,0.1

Type RM Length L Ch R = 1,832,290,290,290
BEGIN DESCRIPTION:
Mapping XS 0020375c
END DESCRIPTION:
XS GIS Cut Line= 4
      2794362.87      7102559.97      2793998.27      7102612.06
      2793898.44      7102681.50      2793937.51      7103224.09
#Sta/Elev= 30
  4544.6  568.31  4552.6  568.58  4611.8  567.38  4633.4  567.74  4753.2  564.35
  4758.3  563.85  4795.0  563.75  4885.9  562.15  4899.7  562.42  4981.6  561.27
  4988.7  560.78  5002.6  559.14  5008.3  559.09  5008.8  558.29  5013.8  558.29
  5014.3  559.09  5017.4  560.34  5026.2  561.08  5118.2  561.70  5138.3  562.60
  5168.4  561.74  5178.4  562.04  5189.0  560.78  5199.5  562.26  5208.5  562.81
  5238.5  563.54  5449.1  565.24  5469.0  564.91  5509.2  566.38  5578.5  566.73
#Mann=3,-1,0
  4544.6    0.05       0  5008.3    0.03       0  5014.3    0.05       0
Bank Sta=4988.7,5189
Exp/Cntr=0.3,0.1

Type RM Length L Ch R = 1,542,375,375,375
BEGIN DESCRIPTION:
Mapping XS 598d6589
END DESCRIPTION:
XS GIS Cut Line= 4
      2794188.59      7102340.24      2793987.22      7102340.24
      2793771.94      7102416.63      2793841.38      7103124.92
#Sta/Elev= 30
  4606.0  563.50  4749.6  560.80  4841.7  560.13  4862.0  559.50  4892.8  560.15
  4929.0  559.88  4958.9  558.22  4985.4  557.28  5011.0  557.58  5018.9  557.11
  5019.4  556.31  5024.4  556.31  5024.9  557.11  5055.6  558.22  5094.5  559.11
  5119.0  558.83  5174.8  559.50  5220.5  558.53  5265.3  558.62  5285.4  559.01
  5322.0  560.91  5355.7  561.36  5385.9  561.49  5423.5  560.42  5428.5  561.38
  5436.1  561.00  5556.7  562.23  5596.9  561.72  5657.1  562.27  5747.5  564.13
#Mann=3,-1,0
  4606.0    0.05       0  5018.9    0.03       0  5024.9    0.05       0
Bank Sta=4958.9,5055.6
Exp/Cntr=0.3,0.1

Type RM Length L Ch R = 1,167,0,0,0
BEGIN DESCRIPTION:
UNT 065 in LFCCL Watershed 2.0
END DESCRIPTION:
XS GIS Cut Line= 4
      2794261.51      7102166.63      2793598.33      7102243.02
      2793489.17      7102453.47      2793802.65      7103141.14
#Sta/Elev= 30
  4188.2  563.15  4285.4  561.27  4335.7  560.97  4355.8  561.36  4391.7  560.45
  4569.7  558.36  4607.5  557.42  4647.7  557.17  4658.7  557.69  4778.6  556.53
  4831.7  557.69  4849.1  556.85  4925.6  556.89  4952.1  556.49  4962.9  556.42
  4969.5  555.56  4979.4  554.58  4985.0  554.63  4993.2  552.94  4997.4  552.54
  4998.1  551.74  5004.9  551.74  5005.6  552.54  5024.3  555.56  5029.3  556.26
  5060.1  556.76  5235.7  557.34  5620.9  559.99  5764.7  561.51  5848.6  563.44
#Mann=5,-1,0
  4188.2    0.05       0  4952.1    0.12       0  4997.4    0.07       0
  5005.6    0.12       0  5060.1    0.05       0
Bank Sta=4969.5,5024.3
Exp/Cntr=0.3,0.1

Chan Stop Cuts=-1