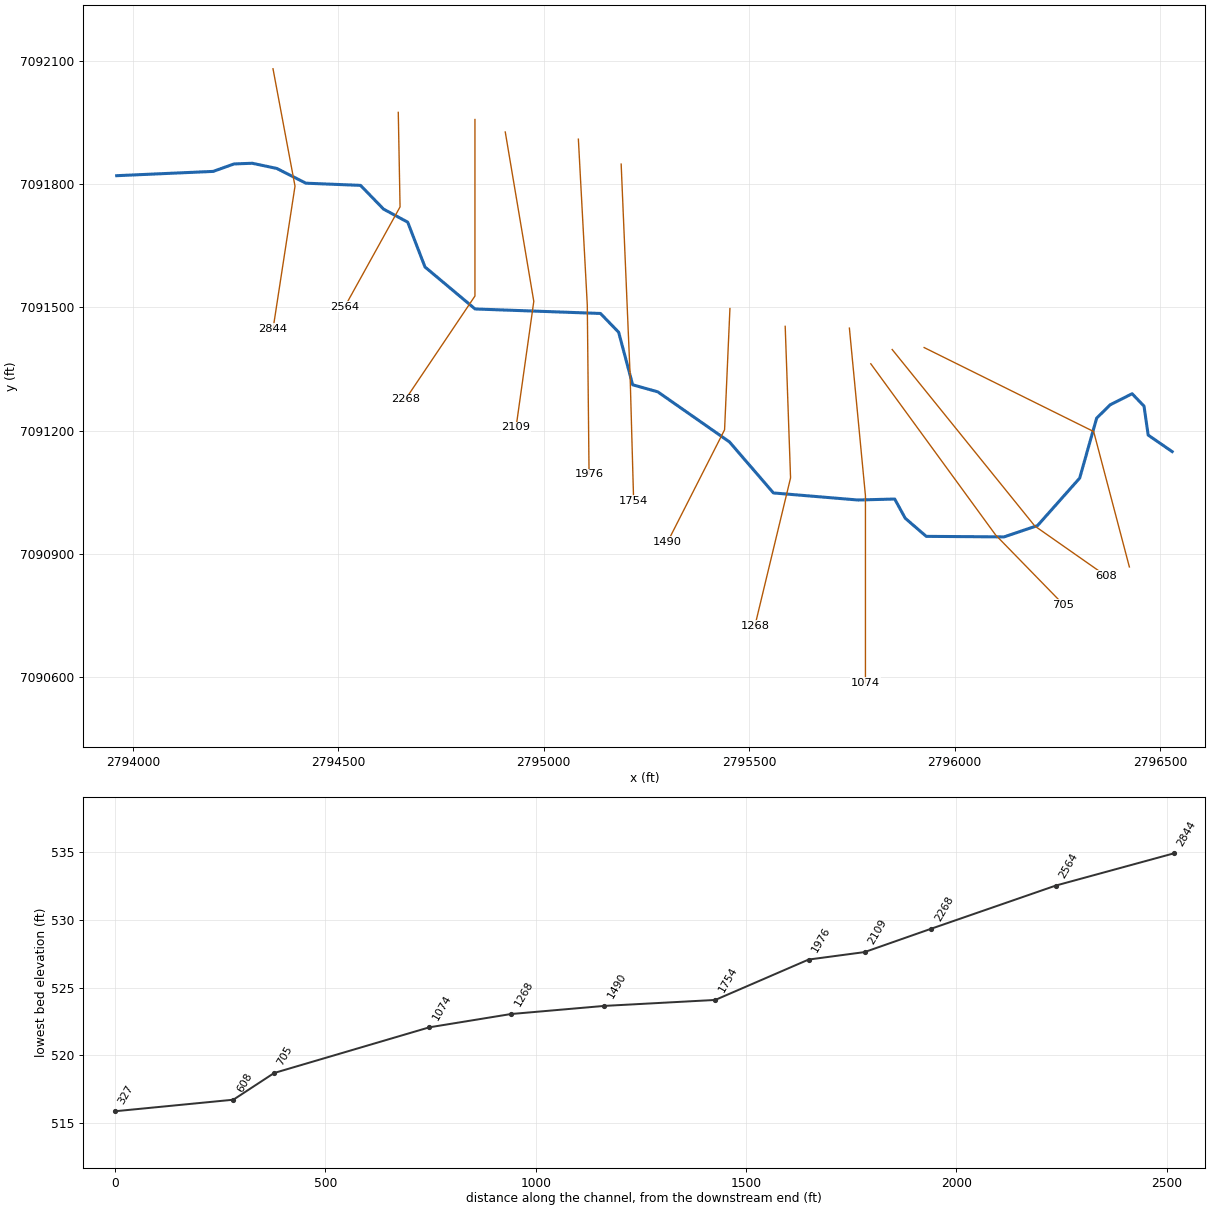
--- UNT 066 in LFCCL Watershed.prj (project) ---

Proj Title=UNT 066 in LFCCL Watershed Base Level Engineering
Current Plan=p01
Default Exp/Contr=0.3,0.1
English Units
Geom File=g01
Flow File=f01
Plan File=p01
BEGIN DESCRIPTION:
UNT 066 in LFCCL Watershed
END DESCRIPTION:

--- UNT 066 in LFCCL Watershed.p01 (plan) ---

Plan Title=Multiple Run
Short Identifier=Multiple
Geom File=g01
Flow File=f01
Subcritical Flow
K Sum by GR= 0
Std Step Tol= 0.01
Critical Tol= 0.01
Num of Std Step Trials= 20
Max Error Tol= 0.3
Flow Tol Ratio= 0.001
Split Flow NTrial= 30
Split Flow Tol= 0.02
Split Flow Ratio= 0.02
Log Output Level= 0
Friction Slope Method= 1
Unsteady Friction Slope Method= 2
Unsteady Bridges Friction Slope Method= 1
Parabolic Critical Depth
Global Vel Dist=  1 , 1 , 1
Global Log Level= 0
CheckData=True
Encroach Param= -1, 0, 0, 0
BEGIN DESCRIPTION:
Multiple Run
END DESCRIPTION:

--- UNT 066 in LFCCL Watershed.f01 (steady flow) ---

Flow Title=Multiple
Number of Profiles=7
Profile Names=10-year,25-year,50-year,1pct_min,100-year,1pct_plu,500-year
River Rch & RM= UNT 066 in LFCCL,Reach-1,2844
     476     621     734     432     861    1718    1179
Boundary for River Rch & Prof#=UNT 066 in LFCCL,Reach-1,1
Up Type=0
Dn Type=3
Dn Slope=0.005
Boundary for River Rch & Prof#=UNT 066 in LFCCL,Reach-1,2
Up Type=0
Dn Type=3
Dn Slope=0.005
Boundary for River Rch & Prof#=UNT 066 in LFCCL,Reach-1,3
Up Type=0
Dn Type=3
Dn Slope=0.005
Boundary for River Rch & Prof#=UNT 066 in LFCCL,Reach-1,4
Up Type=0
Dn Type=3
Dn Slope=0.005
Boundary for River Rch & Prof#=UNT 066 in LFCCL,Reach-1,5
Up Type=0
Dn Type=3
Dn Slope=0.005
Boundary for River Rch & Prof#=UNT 066 in LFCCL,Reach-1,6
Up Type=0
Dn Type=3
Dn Slope=0.005
Boundary for River Rch & Prof#=UNT 066 in LFCCL,Reach-1,7
Up Type=0
Dn Type=3
Dn Slope=0.005

--- UNT 066 in LFCCL Watershed.g01 (geometry) ---

Geom Title=Existing Conditions

River Reach=UNT 066 in LFCCL,Reach-1
Reach XY= 30
      2793960.59      7091820.71      2794195.42      7091831.14
      2794246.29      7091849.30      2794290.50      7091850.96
      2794350.29      7091838.32      2794421.13      7091802.44
      2794554.19      7091797.13      2794610.19      7091739.38
      2794669.01      7091707.54      2794711.09      7091598.48
      2794833.00      7091496.27      2795138.26      7091485.34
      2795182.48      7091439.62      2795216.55      7091311.74
      2795277.66      7091294.60      2795452.21      7091172.66
      2795559.23      7091048.45      2795764.95      7091031.25
      2795854.41      7091033.67      2795880.06      7090986.88
      2795931.25      7090942.78      2796120.63      7090941.46
      2796202.09      7090969.01      2796304.61      7091084.45
      2796346.09      7091230.65      2796379.00      7091263.02
      2796432.30      7091289.96      2796461.28      7091259.82
      2796471.48      7091189.23      2796529.79      7091149.07

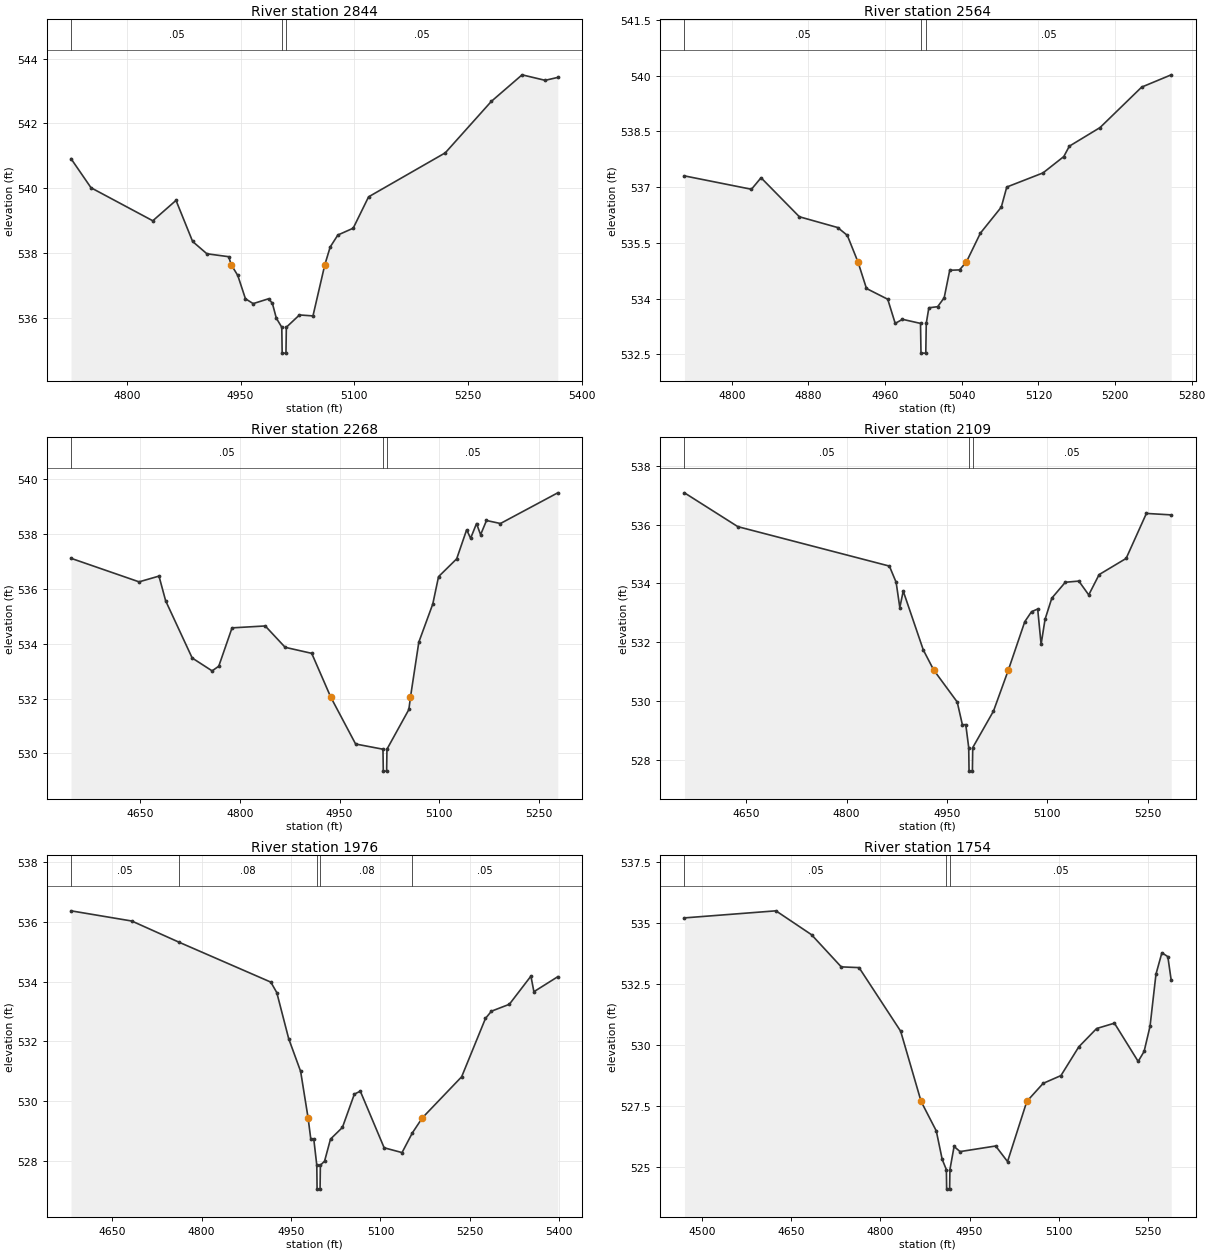
Type RM Length L Ch R = 1,2844,280,280,280
BEGIN DESCRIPTION:
UNT 066 in LFCCL Watershed 2.0
END DESCRIPTION:
XS GIS Cut Line= 3
      2794341.10      7092080.99      2794394.67      7091795.27
      2794341.33      7091448.55
#Sta/Elev= 30
  4726.6  540.91  4753.0  540.01  4834.4  538.99  4865.0  539.62  4886.9  538.35
  4905.7  537.97  4934.4  537.88  4937.8  537.63  4946.4  537.30  4956.5  536.58
  4966.7  536.43  4987.0  536.58  4992.0  536.44  4997.2  535.98  5004.4  535.70
  5004.9  534.90  5009.9  534.90  5010.4  535.70  5027.7  536.08  5045.5  536.05
  5061.1  537.63  5068.2  538.18  5078.3  538.55  5098.5  538.76  5118.8  539.73
  5219.9  541.09  5280.6  542.68  5321.1  543.50  5351.5  543.33  5368.1  543.42
#Mann=3,-1,0
  4726.6    0.05       0  5004.4    0.03       0  5010.4    0.05       0
Bank Sta=4937.8,5061.1
Exp/Cntr=0.3,0.1

Type RM Length L Ch R = 1,2564,296,296,296
BEGIN DESCRIPTION:
XS3466A
END DESCRIPTION:
XS GIS Cut Line= 3
      2794646.05      7091974.86      2794650.39      7091744.79
      2794515.85      7091501.75
#Sta/Elev= 30
  4750.7  537.30  4820.6  536.94  4830.6  537.25  4870.6  536.20  4910.6  535.91
  4920.6  535.70  4931.8  534.98  4940.6  534.27  4962.8  533.98  4970.6  533.33
  4978.2  533.44  4997.0  533.33  4997.5  532.53  5002.5  532.53  5003.0  533.33
  5005.7  533.75  5014.9  533.78  5021.7  534.02  5027.5  534.76  5037.7  534.77
  5044.8  534.98  5059.5  535.76  5081.3  536.46  5087.0  537.00  5124.8  537.38
  5146.5  537.82  5152.3  538.10  5184.3  538.60  5227.8  539.69  5258.6  540.02
#Mann=3,-1,0
  4750.7    0.05       0  4997.0    0.03       0  5003.0    0.05       0
Bank Sta=4931.8,5044.8
Exp/Cntr=0.3,0.1

Type RM Length L Ch R = 1,2268,159,159,159
BEGIN DESCRIPTION:
XS3474A
END DESCRIPTION:
XS GIS Cut Line= 3
      2794832.68      7091957.46      2794832.68      7091527.78
      2794663.44      7091276.08
#Sta/Elev= 30
  4545.5  537.12  4648.0  536.26  4678.0  536.47  4688.0  535.57  4728.0  533.48
  4758.0  533.01  4768.0  533.18  4788.0  534.58  4838.0  534.65  4868.0  533.87
  4908.0  533.65  4936.7  532.05  4974.1  530.34  5015.3  530.15  5015.8  529.35
  5020.8  529.35  5021.3  530.15  5054.3  531.60  5056.7  532.05  5069.3  534.06
  5090.3  535.45  5099.0  536.45  5126.3  537.10  5141.3  538.16  5147.3  537.85
  5156.2  538.39  5162.3  537.98  5171.2  538.50  5192.2  538.39  5278.5  539.51
#Mann=3,-1,0
  4545.5    0.05       0  5015.3    0.03       0  5021.3    0.05       0
Bank Sta=4936.7,5056.7
Exp/Cntr=0.3,0.1

Type RM Length L Ch R = 1,2109,133,133,133
BEGIN DESCRIPTION:
XS3467A
END DESCRIPTION:
XS GIS Cut Line= 3
      2794906.47      7091927.04      2794975.91      7091514.75
      2794932.74      7091208.27
#Sta/Elev= 30
  4557.6  537.08  4637.4  535.93  4863.9  534.59  4874.0  534.04  4879.5  533.18
  4884.6  533.74  4914.6  531.74  4930.1  531.06  4965.3  529.97  4973.0  529.20
  4978.1  529.20  4982.5  528.42  4983.0  527.62  4988.0  527.62  4988.5  528.42
  5019.5  529.66  5041.8  531.06  5066.3  532.70  5076.4  533.04  5085.6  533.13
  5090.7  531.93  5096.6  532.78  5106.7  533.50  5126.9  534.04  5147.1  534.08
  5161.9  533.61  5177.4  534.30  5217.8  534.85  5248.1  536.38  5285.2  536.33
#Mann=3,-1,0
  4557.6    0.05       0  4982.5    0.03       0  4988.5    0.05       0
Bank Sta=4930.1,5041.8
Exp/Cntr=0.3,0.1

Type RM Length L Ch R = 1,1976,222,222,222
BEGIN DESCRIPTION:
XS3468A
END DESCRIPTION:
XS GIS Cut Line= 3
      2795084.42      7091909.67      2795106.12      7091506.07
      2795110.46      7091093.78
#Sta/Elev= 30
  4580.9  536.36  4682.8  536.02  4762.4  535.31  4916.1  533.98  4926.1  533.63
  4946.1  532.09  4966.1  531.00  4978.6  529.45  4983.1  528.75  4988.1  528.75
  4993.2  527.87  4993.7  527.07  4998.7  527.07  4999.2  527.87  5006.2  528.00
  5016.2  528.74  5036.2  529.13  5056.2  530.24  5066.2  530.34  5106.2  528.45
  5136.2  528.29  5153.6  528.95  5170.3  529.45  5236.2  530.82  5276.2  532.77
  5286.2  533.01  5316.2  533.24  5352.4  534.18  5357.4  533.66  5397.4  534.16
#Mann=5,-1,0
  4580.9    0.05       0  4762.4    0.08       0  4993.2    0.07       0
  4999.2    0.08       0  5153.6    0.05       0
Bank Sta=4978.6,5170.3
Exp/Cntr=0.3,0.1

Type RM Length L Ch R = 1,1754,264,264,264
BEGIN DESCRIPTION:
XS3469A
END DESCRIPTION:
XS GIS Cut Line= 3
      2795188.59      7091848.94      2795210.29      7091336.80
      2795218.95      7091029.32
#Sta/Elev= 30
  4469.7  535.22  4623.8  535.51  4683.8  534.53  4733.9  533.21  4763.9  533.18
  4834.0  530.57  4868.4  527.69  4894.0  526.48  4904.0  525.31  4911.0  524.89
  4911.5  524.09  4916.5  524.09  4917.0  524.89  4924.0  525.84  4934.1  525.63
  4994.1  525.86  5014.1  525.22  5046.6  527.69  5074.1  528.43  5104.1  528.75
  5134.2  529.93  5164.2  530.68  5194.2  530.90  5234.2  529.33  5244.2  529.74
  5254.2  530.77  5264.2  532.91  5274.2  533.79  5284.2  533.63  5289.9  532.66
#Mann=3,-1,0
  4469.7    0.05       0  4911.0    0.03       0  4917.0    0.05       0
Bank Sta=4868.4,5046.6
Exp/Cntr=0.3,0.1

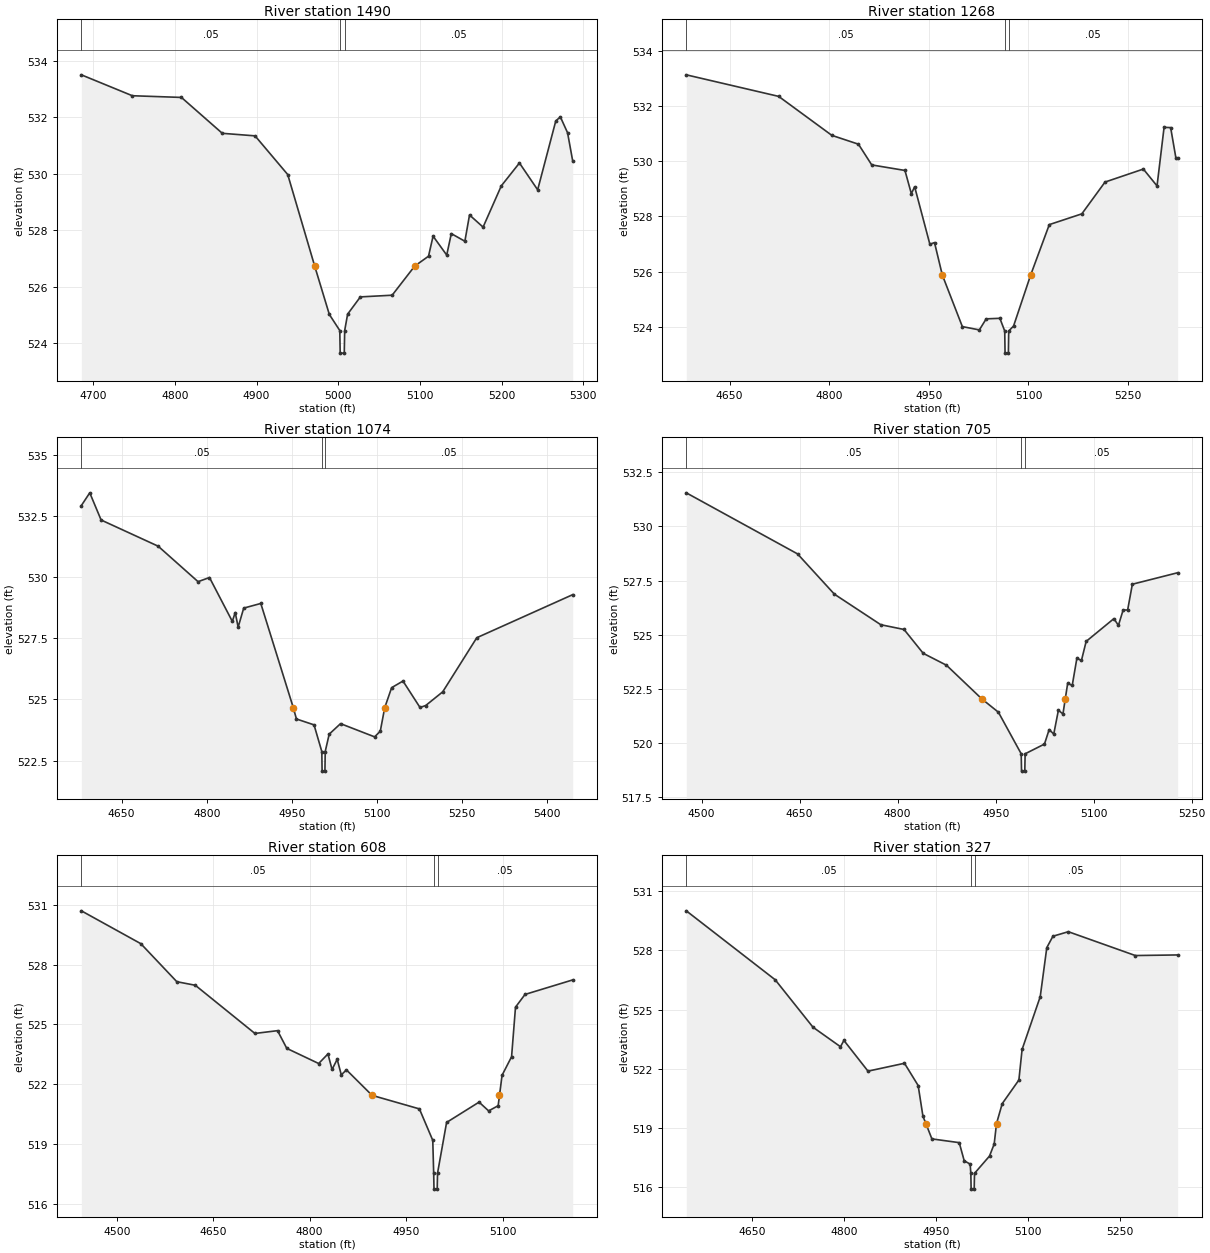
Type RM Length L Ch R = 1,1490,222,222,222
BEGIN DESCRIPTION:
XS3470A
END DESCRIPTION:
XS GIS Cut Line= 3
      2795453.34      7091497.35      2795440.32      7091202.25
      2795301.73      7090929.41
#Sta/Elev= 30
  4685.5  533.50  4747.9  532.76  4808.0  532.70  4858.0  531.43  4898.1  531.34
  4938.1  529.97  4971.1  526.73  4989.0  525.02  5001.8  524.45  5002.3  523.65
  5007.3  523.65  5007.8  524.45  5011.4  525.03  5027.0  525.64  5065.9  525.70
  5093.5  526.73  5110.4  527.08  5116.0  527.79  5132.7  527.12  5138.3  527.88
  5154.9  527.61  5160.6  528.54  5177.2  528.11  5199.5  529.57  5221.7  530.38
  5244.0  529.43  5266.2  531.87  5271.8  532.01  5280.6  531.45  5286.9  530.45
#Mann=3,-1,0
  4685.5    0.05       0  5001.8    0.03       0  5007.8    0.05       0
Bank Sta=4971.1,5093.5
Exp/Cntr=0.3,0.1

Type RM Length L Ch R = 1,1268,194,194,194
BEGIN DESCRIPTION:
XS3471A
END DESCRIPTION:
XS GIS Cut Line= 3
      2795587.89      7091454.00      2795600.91      7091085.07
      2795514.11      7090724.84
#Sta/Elev= 30
  4584.9  533.12  4724.0  532.34  4804.0  530.93  4844.1  530.61  4864.1  529.86
  4914.1  529.66  4923.7  528.82  4928.7  529.07  4951.6  526.99  4958.6  527.05
  4970.3  525.88  5000.5  524.01  5026.1  523.89  5036.4  524.29  5057.0  524.31
  5064.3  523.85  5064.8  523.05  5069.8  523.05  5070.3  523.85  5077.6  524.03
  5103.4  525.88  5131.4  527.70  5180.4  528.09  5215.3  529.24  5273.0  529.71
  5293.6  529.10  5304.2  531.22  5314.1  531.21  5322.0  530.11  5324.6  530.11
#Mann=3,-1,0
  4584.9    0.05       0  5064.3    0.03       0  5070.3    0.05       0
Bank Sta=4970.3,5103.4
Exp/Cntr=0.3,0.1

Type RM Length L Ch R = 1,1074,369,369,369
BEGIN DESCRIPTION:
XS3472A
END DESCRIPTION:
XS GIS Cut Line= 3
      2795744.14      7091449.69      2795783.20      7091041.66
      2795783.20      7090585.95
#Sta/Elev= 30
  4579.2  532.92  4594.0  533.44  4614.0  532.33  4714.5  531.26  4784.8  529.81
  4804.9  529.98  4845.1  528.19  4850.3  528.55  4855.4  527.95  4865.2  528.73
  4895.3  528.92  4952.6  524.66  4958.1  524.20  4989.1  523.96  5002.8  522.87
  5003.3  522.07  5008.3  522.07  5008.8  522.87  5015.8  523.58  5035.8  524.01
  5095.8  523.47  5105.8  523.70  5113.6  524.66  5125.8  525.48  5145.8  525.75
  5175.8  524.67  5185.8  524.75  5215.8  525.31  5275.8  527.52  5444.8  529.28
#Mann=3,-1,0
  4579.2    0.05       0  5002.8    0.03       0  5008.8    0.05       0
Bank Sta=4952.6,5113.6
Exp/Cntr=0.3,0.1

Type RM Length L Ch R = 1,705,97,97,97
BEGIN DESCRIPTION:
XS3475A
END DESCRIPTION:
XS GIS Cut Line= 3
      2795796.24      7091362.83      2796100.04      7090946.18
      2796264.98      7090776.90
#Sta/Elev= 30
  4476.5  531.55  4646.8  528.73  4703.2  526.87  4774.2  525.46  4809.8  525.24
  4839.1  524.14  4874.7  523.59  4929.0  522.03  4954.2  521.42  4989.1  519.50
  4989.6  518.70  4994.6  518.70  4995.1  519.50  5024.7  519.95  5031.9  520.62
  5038.9  520.41  5046.0  521.51  5053.0  521.34  5056.5  522.03  5060.2  522.75
  5067.2  522.66  5074.3  523.91  5081.3  523.81  5088.5  524.69  5130.9  525.74
  5137.9  525.43  5145.1  526.14  5152.0  526.14  5159.2  527.33  5228.5  527.86
#Mann=3,-1,0
  4476.5    0.05       0  4989.1    0.03       0  4995.1    0.05       0
Bank Sta=4929,5056.5
Exp/Cntr=0.3,0.1

Type RM Length L Ch R = 1,608,281,281,281
BEGIN DESCRIPTION:
XS3473A
END DESCRIPTION:
XS GIS Cut Line= 3
      2795848.29      7091397.59      2796195.53      7090967.88
      2796369.15      7090846.35
#Sta/Elev= 30
  4444.8  530.71  4537.3  529.06  4593.3  527.15  4622.1  526.97  4714.8  524.55
  4750.0  524.69  4764.4  523.80  4814.0  523.04  4828.4  523.52  4834.8  522.74
  4842.8  523.25  4849.2  522.47  4857.2  522.72  4897.1  521.44  4970.7  520.76
  4991.5  519.18  4992.9  517.53  4993.4  516.73  4998.4  516.73  4998.9  517.53
  5013.0  520.08  5063.5  521.10  5078.4  520.66  5093.2  520.92  5095.3  521.44
  5099.3  522.45  5114.1  523.38  5120.2  525.87  5135.0  526.51  5209.2  527.24
#Mann=3,-1,0
  4444.8    0.05       0  4992.9    0.03       0  4998.9    0.05       0
Bank Sta=4897.1,5095.3
Exp/Cntr=0.3,0.1

Type RM Length L Ch R = 1,327,0,0,0
BEGIN DESCRIPTION:
UNT 066 in LFCCL Watershed 1.0
END DESCRIPTION:
XS GIS Cut Line= 3
      2795926.08      7091402.37      2796338.76      7091197.91
      2796425.64      7090868.33
#Sta/Elev= 30
  4543.0  530.01  4688.0  526.51  4749.7  524.10  4794.5  523.11  4800.1  523.43
  4839.4  521.87  4898.9  522.27  4921.2  521.14  4929.0  519.58  4933.8  519.21
  4943.6  518.43  4988.2  518.24  4996.3  517.32  5006.0  517.15  5007.1  516.68
  5007.6  515.88  5012.6  515.88  5013.1  516.68  5037.6  517.56  5045.2  518.17
  5049.0  519.21  5058.3  520.22  5085.5  521.42  5090.7  522.97  5120.3  525.65
  5131.0  528.14  5141.0  528.72  5166.1  528.95  5275.4  527.74  5344.4  527.77
#Mann=3,-1,0
  4543.0    0.05       0  5007.1    0.03       0  5013.1    0.05       0
Bank Sta=4933.8,5049
Exp/Cntr=0.3,0.1

Chan Stop Cuts=-1