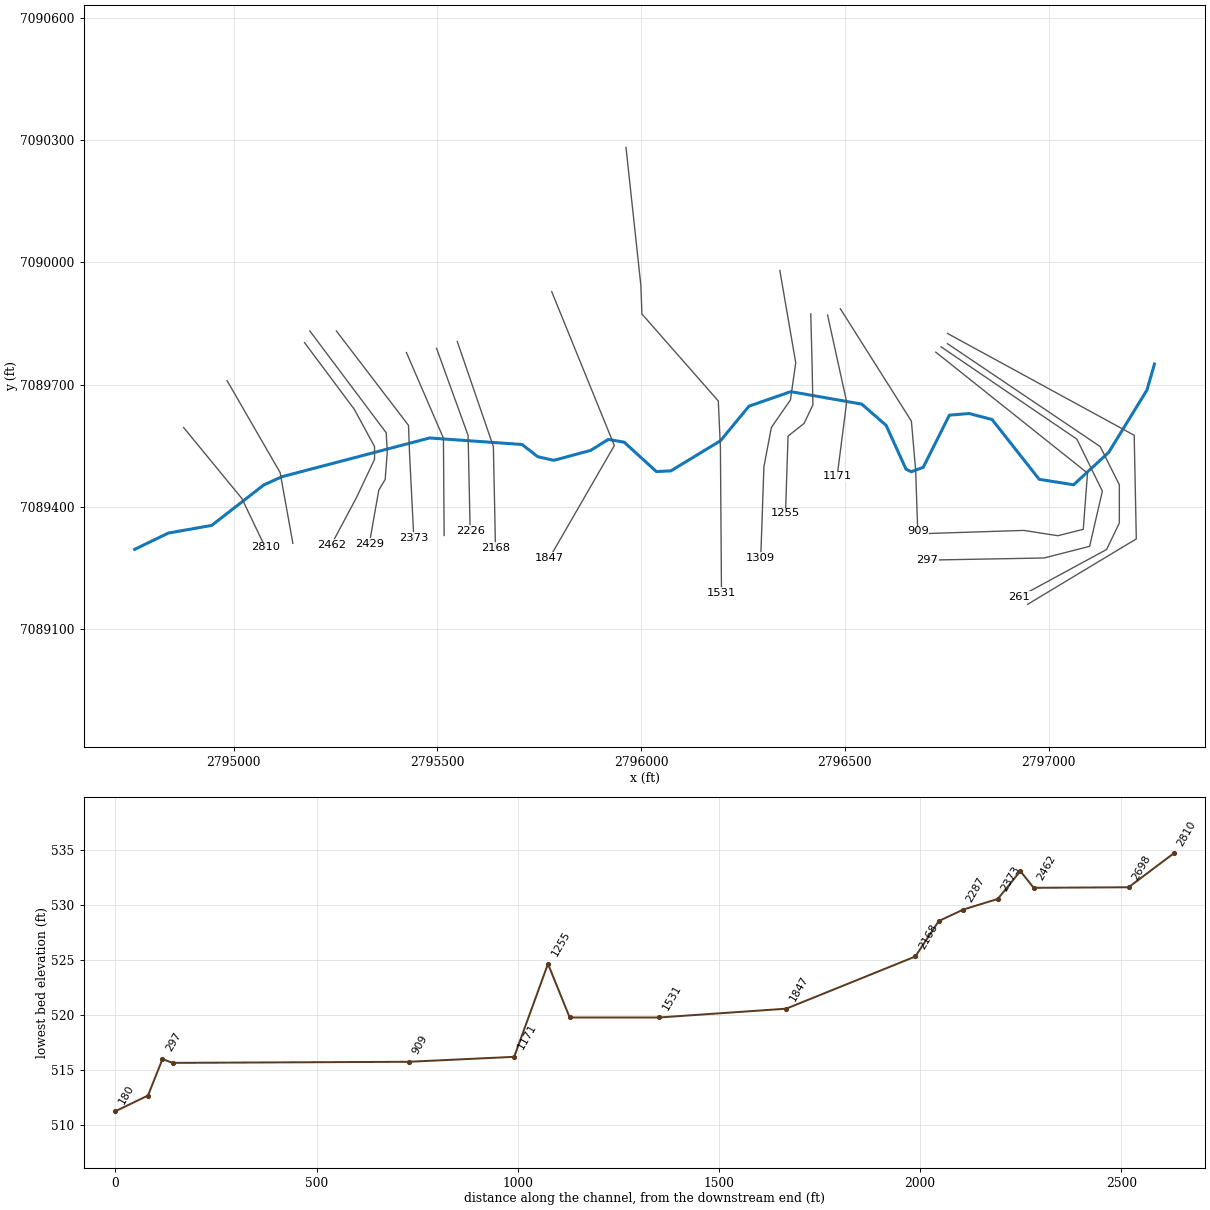
--- UNT 067 in LFCCL Watershed.prj (project) ---

Proj Title=UNT 067 in LFCCL Watershed Base Level Engineering
Current Plan=p01
Default Exp/Contr=0.3,0.1
English Units
Geom File=g01
Flow File=f01
Plan File=p01
BEGIN DESCRIPTION:
UNT 067 in LFCCL Watershed
END DESCRIPTION:

--- UNT 067 in LFCCL Watershed.p01 (plan) ---

Plan Title=Multiple Run
Short Identifier=Multiple
Geom File=g01
Flow File=f01
Subcritical Flow
K Sum by GR= 0
Std Step Tol= 0.01
Critical Tol= 0.01
Num of Std Step Trials= 20
Max Error Tol= 0.3
Flow Tol Ratio= 0.001
Split Flow NTrial= 30
Split Flow Tol= 0.02
Split Flow Ratio= 0.02
Log Output Level= 0
Friction Slope Method= 1
Unsteady Friction Slope Method= 2
Unsteady Bridges Friction Slope Method= 1
Parabolic Critical Depth
Global Vel Dist=  1 , 1 , 1
Global Log Level= 0
CheckData=True
Encroach Param= -1, 0, 0, 0
BEGIN DESCRIPTION:
Multiple Run
END DESCRIPTION:

--- UNT 067 in LFCCL Watershed.f01 (steady flow) ---

Flow Title=Multiple
Number of Profiles=7
Profile Names=10-year,25-year,50-year,1pct_min,100-year,1pct_plu,500-year
River Rch & RM= UNT 067 in LFCCL,Reach-1,2810
     205     252     286     162     323     645     411
Boundary for River Rch & Prof#=UNT 067 in LFCCL,Reach-1,1
Up Type=0
Dn Type=3
Dn Slope=0.005
Boundary for River Rch & Prof#=UNT 067 in LFCCL,Reach-1,2
Up Type=0
Dn Type=3
Dn Slope=0.005
Boundary for River Rch & Prof#=UNT 067 in LFCCL,Reach-1,3
Up Type=0
Dn Type=3
Dn Slope=0.005
Boundary for River Rch & Prof#=UNT 067 in LFCCL,Reach-1,4
Up Type=0
Dn Type=3
Dn Slope=0.005
Boundary for River Rch & Prof#=UNT 067 in LFCCL,Reach-1,5
Up Type=0
Dn Type=3
Dn Slope=0.005
Boundary for River Rch & Prof#=UNT 067 in LFCCL,Reach-1,6
Up Type=0
Dn Type=3
Dn Slope=0.005
Boundary for River Rch & Prof#=UNT 067 in LFCCL,Reach-1,7
Up Type=0
Dn Type=3
Dn Slope=0.005

--- UNT 067 in LFCCL Watershed.g01 (geometry) ---

Geom Title=Existing Conditions

River Reach=UNT 067 in LFCCL,Reach-1
Reach XY= 30
      2794756.69      7089295.92      2794839.59      7089335.94
      2794945.84      7089354.69      2795073.62      7089454.00
      2795118.06      7089474.14      2795480.56      7089569.27
      2795707.64      7089553.30      2795745.84      7089523.44
      2795785.42      7089514.41      2795875.70      7089538.72
      2795919.45      7089565.80      2795958.34      7089558.86
      2796037.33      7089486.81      2796072.92      7089488.55
      2796194.45      7089562.33      2796264.76      7089647.40
      2796367.19      7089682.99      2796541.46      7089652.39
      2796601.13      7089600.31      2796649.96      7089492.89
      2796662.98      7089486.38      2796692.28      7089497.23
      2796756.51      7089625.28      2796805.04      7089629.32
      2796861.36      7089614.50      2796976.97      7089467.77
      2797061.45      7089454.43      2797147.61      7089534.05
      2797241.53      7089687.12      2797259.79      7089750.64

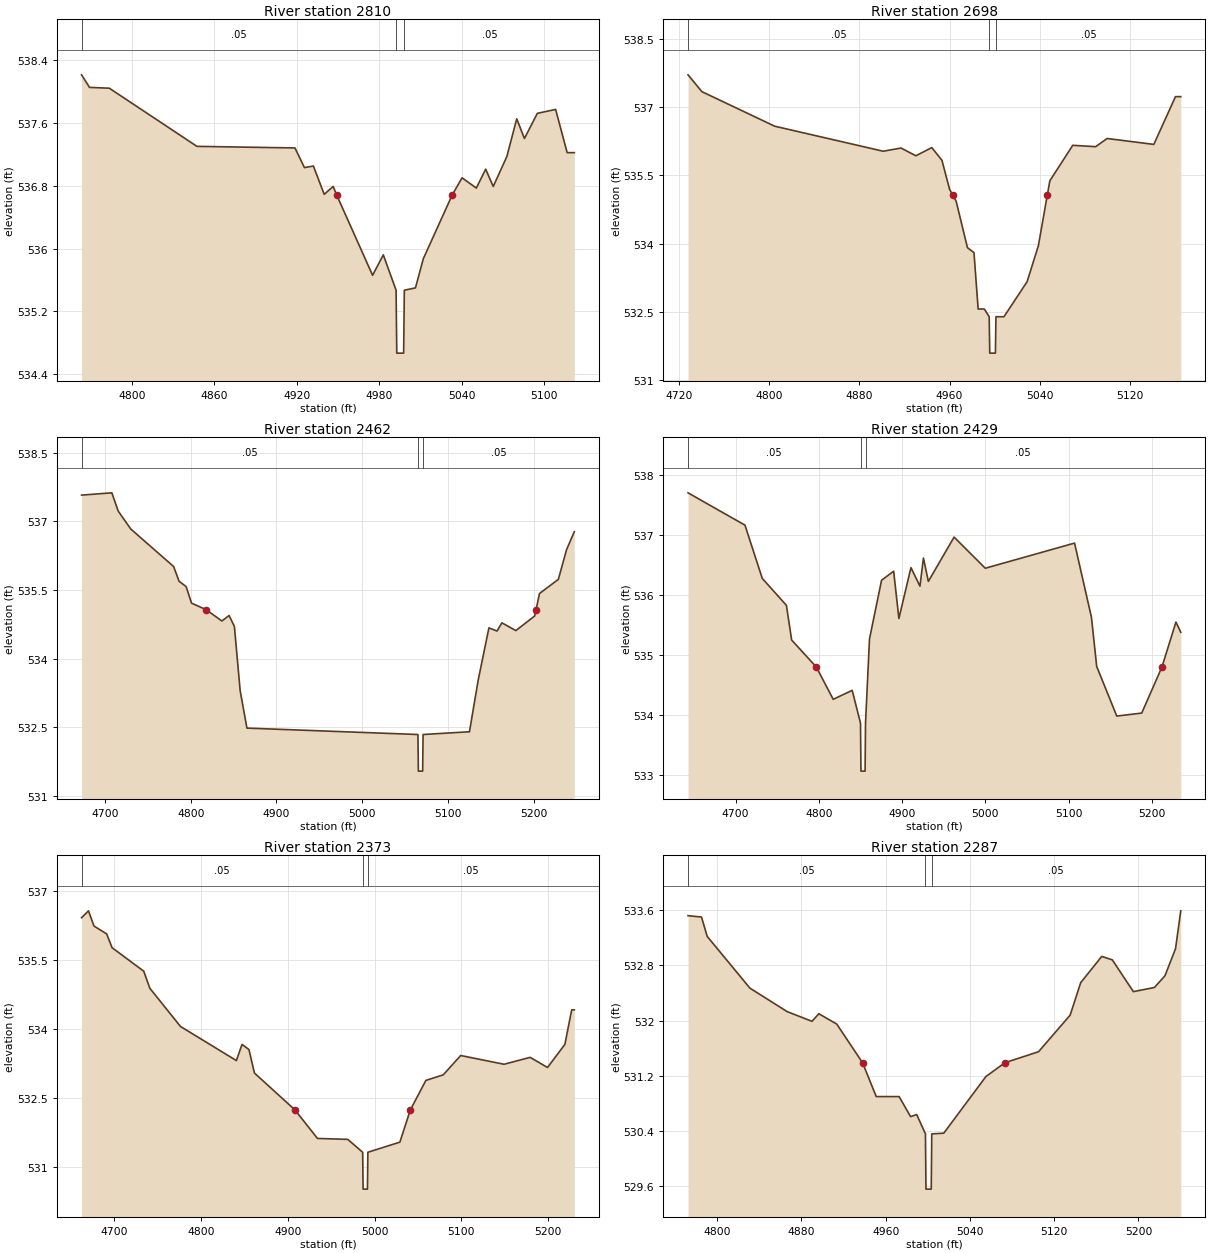
Type RM Length L Ch R = 1,2810,112,112,112
BEGIN DESCRIPTION:
UNT 067 in LFCCL Watershed 5.0
END DESCRIPTION:
XS GIS Cut Line= 3
      2794876.76      7089595.03      2795020.01      7089420.52
      2795077.32      7089300.69
#Sta/Elev= 30
  4763.3  538.21  4769.1  538.05  4783.5  538.04  4847.3  537.30  4918.6  537.28
  4925.5  537.03  4932.0  537.05  4939.9  536.69  4946.4  536.79  4949.0  536.68
  4975.1  535.66  4982.9  535.92  4992.2  535.47  4992.7  534.67  4997.7  534.67
  4998.2  535.47  5006.3  535.50  5012.0  535.87  5033.0  536.68  5040.2  536.90
  5050.6  536.77  5057.4  537.01  5062.9  536.79  5072.8  537.17  5080.0  537.65
  5085.6  537.40  5095.0  537.72  5108.3  537.77  5116.7  537.22  5121.9  537.22
#Mann=3,-1,0
  4763.3    0.05       0  4992.2    0.03       0  4998.2    0.05       0
Bank Sta=4949,5033
Exp/Cntr=0.3,0.1

Type RM Length L Ch R = 1,2698,236,236,236
BEGIN DESCRIPTION:
XS3487A
END DESCRIPTION:
XS GIS Cut Line= 3
      2794983.54      7089710.05      2795113.76      7089484.32
      2795145.01      7089310.71
#Sta/Elev= 30
  4728.0  537.71  4740.3  537.34  4804.9  536.58  4901.1  536.03  4916.9  536.10
  4930.1  535.93  4944.2  536.11  4953.2  535.83  4960.0  535.19  4962.9  535.06
  4965.8  534.93  4975.8  533.91  4981.6  533.80  4985.3  532.56  4990.8  532.56
  4995.1  532.39  4995.6  531.59  5000.6  531.59  5001.1  532.39  5008.2  532.39
  5028.7  533.16  5038.7  533.95  5046.6  535.06  5048.9  535.38  5069.2  536.16
  5089.5  536.13  5099.7  536.31  5141.1  536.18  5160.3  537.23  5165.0  537.23
#Mann=3,-1,0
  4728.0    0.05       0  4995.1    0.03       0  5001.1    0.05       0
Bank Sta=4962.9,5046.6
Exp/Cntr=0.3,0.1

Type RM Length L Ch R = 1,2462,33,33,33
BEGIN DESCRIPTION:
XS3485A
END DESCRIPTION:
XS GIS Cut Line= 6
      2795173.67      7089803.31      2795296.06      7089639.27
      2795345.53      7089548.12      2795345.53      7089516.87
      2795301.26      7089423.12      2795239.38      7089307.10
#Sta/Elev= 30
  4672.6  537.57  4707.9  537.62  4715.4  537.22  4730.0  536.83  4780.0  536.01
  4786.3  535.69  4794.6  535.57  4800.9  535.21  4817.7  535.07  4836.3  534.82
  4844.7  534.94  4850.9  534.70  4857.6  533.30  4865.5  532.48  5065.0  532.34
  5065.5  531.54  5070.5  531.54  5071.0  532.34  5125.1  532.40  5135.3  533.53
  5147.8  534.67  5157.3  534.60  5162.9  534.78  5179.2  534.61  5201.2  534.93
  5202.8  535.07  5206.8  535.42  5228.8  535.73  5238.4  536.38  5247.4  536.77
#Mann=3,-1,0
  4672.6    0.05       0  5065.0    0.03       0  5071.0    0.05       0
Bank Sta=4817.7,5202.8
Exp/Cntr=0.3,0.1

Type RM Length L Ch R = 1,2429,56,56,56
BEGIN DESCRIPTION:
XS3486A
END DESCRIPTION:
XS GIS Cut Line= 6
      2795186.69      7089831.97      2795374.18      7089581.98
      2795376.78      7089535.10      2795371.58      7089467.39
      2795355.95      7089441.35      2795332.65      7089309.32
#Sta/Elev= 30
  4642.8  537.71  4711.2  537.17  4732.0  536.28  4761.0  535.83  4767.3  535.25
  4796.9  534.80  4817.2  534.26  4840.0  534.41  4850.0  533.86  4850.5  533.06
  4855.5  533.06  4856.0  533.86  4860.8  535.27  4875.3  536.25  4889.8  536.40
  4896.1  535.61  4910.6  536.46  4921.4  536.15  4925.6  536.62  4931.5  536.23
  4962.4  536.97  4999.9  536.45  5107.1  536.87  5127.4  535.63  5133.7  534.81
  5157.8  533.98  5187.8  534.03  5212.1  534.80  5228.9  535.55  5234.7  535.38
#Mann=3,-1,0
  4642.8    0.05       0  4850.0    0.03       0  4856.0    0.05       0
Bank Sta=4796.9,5212.1
Exp/Cntr=0.3,0.1

Type RM Length L Ch R = 1,2373,86,86,86
BEGIN DESCRIPTION:
XS3484A
END DESCRIPTION:
XS GIS Cut Line= 4
      2795251.76      7089832.01      2795428.87      7089600.21
      2795431.47      7089529.89      2795441.89      7089324.14
#Sta/Elev= 30
  4662.1  536.42  4670.1  536.57  4676.4  536.24  4691.0  536.07  4697.3  535.77
  4733.8  535.26  4740.8  534.89  4776.2  534.06  4840.6  533.32  4847.1  533.67
  4855.1  533.56  4861.4  533.05  4908.1  532.25  4934.1  531.63  4969.0  531.61
  4986.2  531.33  4986.7  530.53  4991.7  530.53  4992.2  531.33  5029.1  531.55
  5041.2  532.25  5059.1  532.89  5079.1  533.01  5099.2  533.43  5149.2  533.24
  5179.3  533.39  5199.3  533.17  5219.3  533.67  5227.2  534.42  5230.2  534.42
#Mann=3,-1,0
  4662.1    0.05       0  4986.2    0.03       0  4992.2    0.05       0
Bank Sta=4908.1,5041.2
Exp/Cntr=0.3,0.1

Type RM Length L Ch R = 1,2287,61,61,61
BEGIN DESCRIPTION:
Mapping XS 5d522e54
END DESCRIPTION:
XS GIS Cut Line= 3
      2795423.78      7089779.01      2795514.61      7089568.74
      2795516.29      7089330.00
#Sta/Elev= 30
  4772.4  533.52  4785.2  533.50  4790.6  533.22  4831.2  532.47  4866.6  532.13
  4890.1  531.99  4896.6  532.10  4913.6  531.95  4938.1  531.39  4951.1  530.90
  4972.8  530.90  4983.7  530.61  4989.5  530.64  4997.8  530.36  4998.3  529.56
  5003.3  529.56  5003.8  530.36  5015.2  530.37  5055.2  531.19  5073.2  531.39
  5105.2  531.55  5135.2  532.08  5145.2  532.55  5165.2  532.93  5175.2  532.88
  5195.2  532.42  5215.2  532.48  5225.2  532.65  5235.2  533.04  5240.2  533.59
#Mann=3,-1,0
  4772.4    0.05       0  4997.8    0.03       0  5003.8    0.05       0
Bank Sta=4938.1,5073.2
Exp/Cntr=0.3,0.1

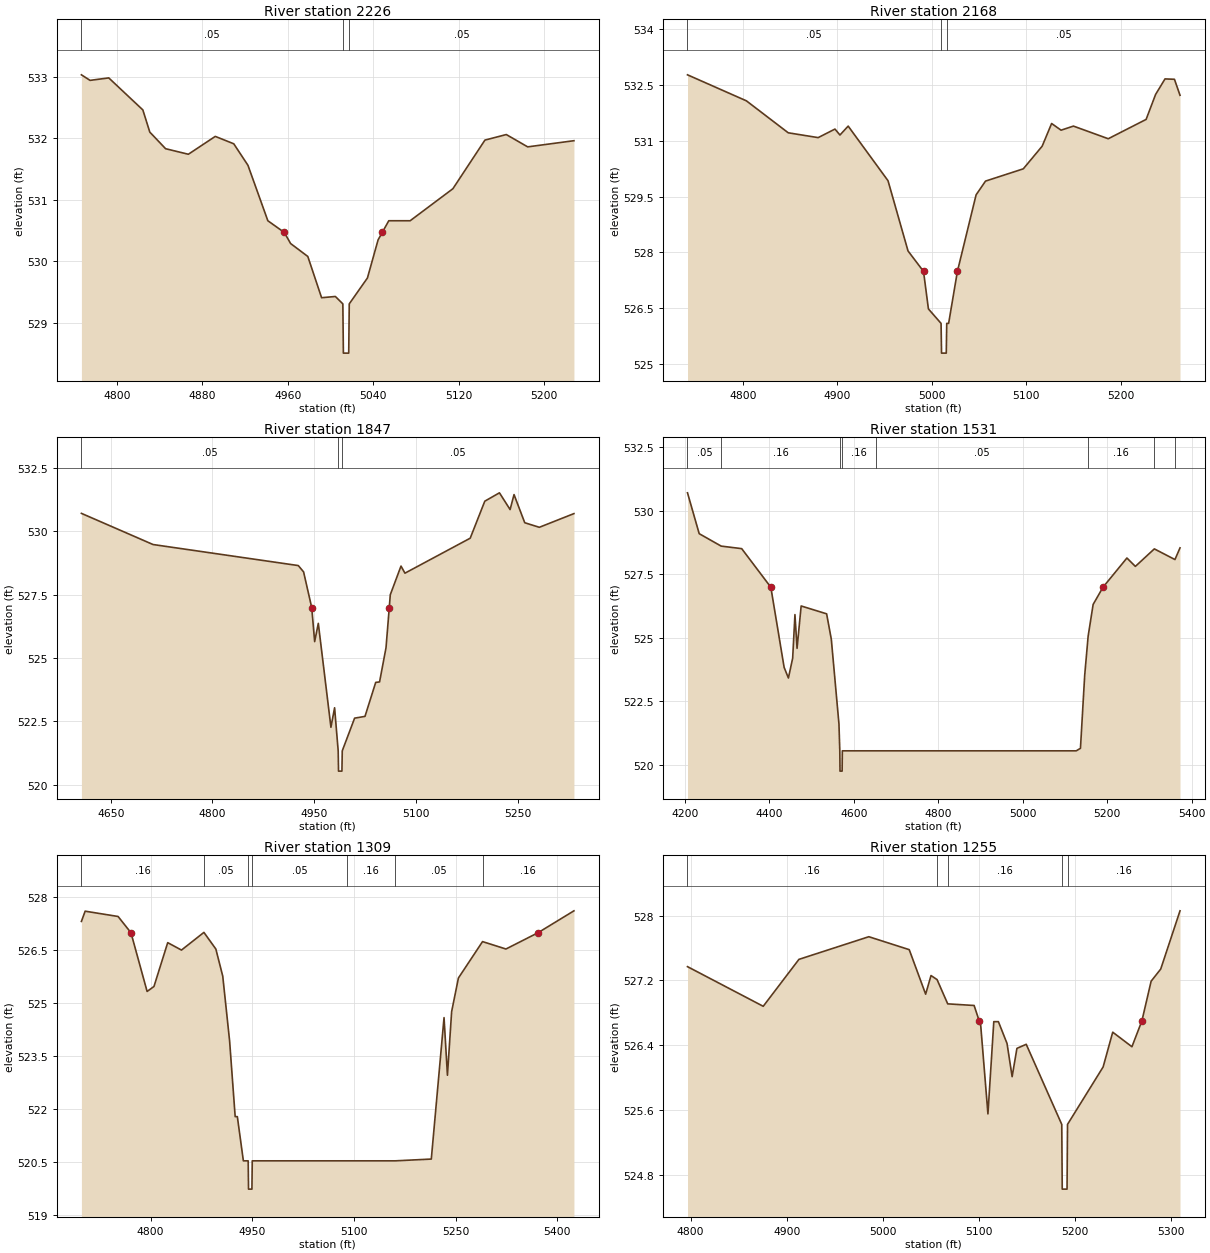
Type RM Length L Ch R = 1,2226,58,58,58
BEGIN DESCRIPTION:
Mapping XS be1b3d87
END DESCRIPTION:
XS GIS Cut Line= 3
      2795497.79      7089789.08      2795575.16      7089575.47
      2795580.21      7089341.72
#Sta/Elev= 30
  4766.7  533.03  4774.8  532.94  4792.3  532.98  4824.2  532.46  4830.7  532.10
  4845.5  531.83  4866.8  531.74  4892.0  532.03  4909.3  531.91  4922.6  531.56
  4941.2  530.66  4956.6  530.47  4962.5  530.29  4978.6  530.08  4991.5  529.41
  5004.4  529.43  5011.4  529.31  5011.9  528.51  5016.9  528.51  5017.4  529.31
  5034.4  529.73  5044.4  530.35  5048.3  530.47  5054.4  530.66  5074.4  530.66
  5114.4  531.18  5144.4  531.97  5164.4  532.06  5184.4  531.86  5227.7  531.96
#Mann=3,-1,0
  4766.7    0.05       0  5011.4    0.03       0  5017.4    0.05       0
Bank Sta=4956.6,5048.3
Exp/Cntr=0.3,0.1

Type RM Length L Ch R = 1,2168,321,321,321
BEGIN DESCRIPTION:
UNT 067 in LFCCL Watershed 3.0
END DESCRIPTION:
XS GIS Cut Line= 3
      2795548.66      7089805.93      2795637.20      7089548.12
      2795642.39      7089299.06
#Sta/Elev= 30
  4741.2  532.78  4803.6  532.08  4847.9  531.22  4879.6  531.09  4897.4  531.32
  4902.7  531.16  4911.4  531.40  4953.6  529.93  4974.8  528.04  4991.2  527.49
  4996.4  526.48  5009.8  526.09  5010.3  525.29  5015.3  525.29  5015.8  526.09
  5017.8  526.09  5027.1  527.49  5046.9  529.55  5056.9  529.92  5096.9  530.25
  5116.9  530.86  5126.9  531.47  5136.9  531.29  5150.0  531.40  5186.9  531.06
  5227.0  531.58  5237.0  532.25  5247.0  532.67  5257.0  532.66  5262.9  532.23
#Mann=3,-1,0
  4741.2    0.05       0  5009.8    0.03       0  5015.8    0.05       0
Bank Sta=4991.2,5027.1
Exp/Cntr=0.3,0.1

Type RM Length L Ch R = 1,1847,316,316,316
BEGIN DESCRIPTION:
UNT 067 in LFCCL Watershed 2.0
END DESCRIPTION:
XS GIS Cut Line= 3
      2795780.41      7089928.37      2795934.08      7089550.73
      2795775.02      7089275.03
#Sta/Elev= 30
  4606.8  530.71  4712.4  529.48  4926.5  528.65  4934.3  528.40  4946.3  526.99
  4950.6  525.65  4956.0  526.37  4974.6  522.27  4980.0  523.04  4985.3  521.34
  4985.8  520.54  4990.8  520.54  4991.3  521.34  5009.5  522.63  5024.8  522.70
  5040.6  524.04  5046.3  524.06  5055.8  525.41  5060.6  526.99  5062.1  527.50
  5077.9  528.63  5083.7  528.35  5179.9  529.73  5201.4  531.19  5223.0  531.52
  5238.7  530.86  5244.5  531.45  5260.3  530.34  5281.8  530.16  5332.8  530.70
#Mann=3,-1,0
  4606.8    0.05       0  4985.3    0.03       0  4991.3    0.05       0
Bank Sta=4946.3,5060.6
Exp/Cntr=0.3,0.1

Type RM Length L Ch R = 1,1531,222,222,222
BEGIN DESCRIPTION:
XS3483A
END DESCRIPTION:
XS GIS Cut Line= 6
      2795962.72      7090282.53      2795999.18      7089943.96
      2796001.78      7089873.64      2796189.28      7089660.10
      2796194.49      7089545.52      2796197.09      7089189.35
#Sta/Elev= 30
  4206.4  530.71  4234.1  529.10  4286.1  528.61  4334.7  528.51  4403.7  526.99
  4435.2  523.83  4445.3  523.41  4455.4  524.19  4460.8  525.91  4465.8  524.58
  4475.5  526.25  4535.8  525.94  4546.9  524.94  4565.0  521.60  4567.0  520.54
  4567.5  519.74  4572.5  519.74  4573.0  520.54  4652.9  520.54  5126.8  520.54
  5136.8  520.64  5146.8  523.51  5154.9  525.05  5166.8  526.31  5190.2  526.99
  5246.8  528.14  5266.8  527.81  5311.7  528.50  5360.5  528.08  5372.5  528.54
#Mann=8,-1,0
  4206.4    0.05       0  4286.1    0.16       0  4567.0   0.033       0
  4573.0    0.16       0  4652.9    0.05       0  5154.9    0.16       0
  5311.7    0.05       0  5360.5    0.12       0
Bank Sta=4403.7,5190.2
Exp/Cntr=0.3,0.1

Type RM Length L Ch R = 1,1309,54,54,54
BEGIN DESCRIPTION:
XS3482A
END DESCRIPTION:
XS GIS Cut Line= 6
      2796340.32      7089980.46      2796379.39      7089753.85
      2796366.37      7089662.71      2796319.49      7089595.00
      2796301.26      7089498.64      2796293.45      7089274.72
#Sta/Elev= 30
  4698.0  527.31  4703.5  527.60  4752.1  527.45  4771.1  526.99  4794.9  525.33
  4805.0  525.47  4825.3  526.71  4845.6  526.50  4878.7  527.00  4896.3  526.53
  4906.5  525.76  4916.6  523.93  4924.8  521.79  4928.0  521.79  4936.9  520.54
  4944.0  520.54  4944.5  519.74  4949.5  519.74  4950.0  520.54  5089.3  520.54
  5161.1  520.54  5214.1  520.59  5232.9  524.59  5237.9  522.96  5244.1  524.76
  5254.1  525.71  5289.7  526.74  5324.2  526.53  5371.5  526.99  5424.5  527.61
#Mann=7,-1,0
  4698.0    0.16       0  4878.7    0.05       0  4944.0   0.033       0
  4950.0    0.05       0  5089.3    0.16       0  5161.1    0.05       0
  5289.7    0.16       0
Bank Sta=4771.1,5371.5
Exp/Cntr=0.3,0.1

Type RM Length L Ch R = 1,1255,84,84,84
BEGIN DESCRIPTION:
Mapping XS d849a367
END DESCRIPTION:
XS GIS Cut Line= 6
      2796416.25      7089873.87      2796419.38      7089755.69
      2796421.46      7089650.48      2796399.77      7089604.91
      2796360.48      7089573.96      2796354.27      7089384.90
#Sta/Elev= 30
  4796.7  527.37  4875.6  526.88  4912.8  527.46  4985.6  527.74  5027.7  527.58
  5044.8  527.03  5050.4  527.26  5056.7  527.21  5067.8  526.91  5095.3  526.89
  5100.6  526.70  5102.2  526.64  5109.7  525.55  5115.8  526.69  5120.6  526.69
  5129.6  526.42  5134.9  526.01  5139.9  526.36  5149.6  526.41  5186.6  525.42
  5187.1  524.62  5192.1  524.62  5192.6  525.42  5229.7  526.13  5239.7  526.56
  5259.7  526.38  5270.1  526.70  5279.7  527.19  5289.7  527.34  5309.8  528.06
#Mann=5,-1,0
  4796.7    0.16       0  5056.7    0.05       0  5067.8    0.16       0
  5186.6    0.07       0  5192.6    0.16       0
Bank Sta=5100.6,5270.1
Exp/Cntr=0.3,0.1

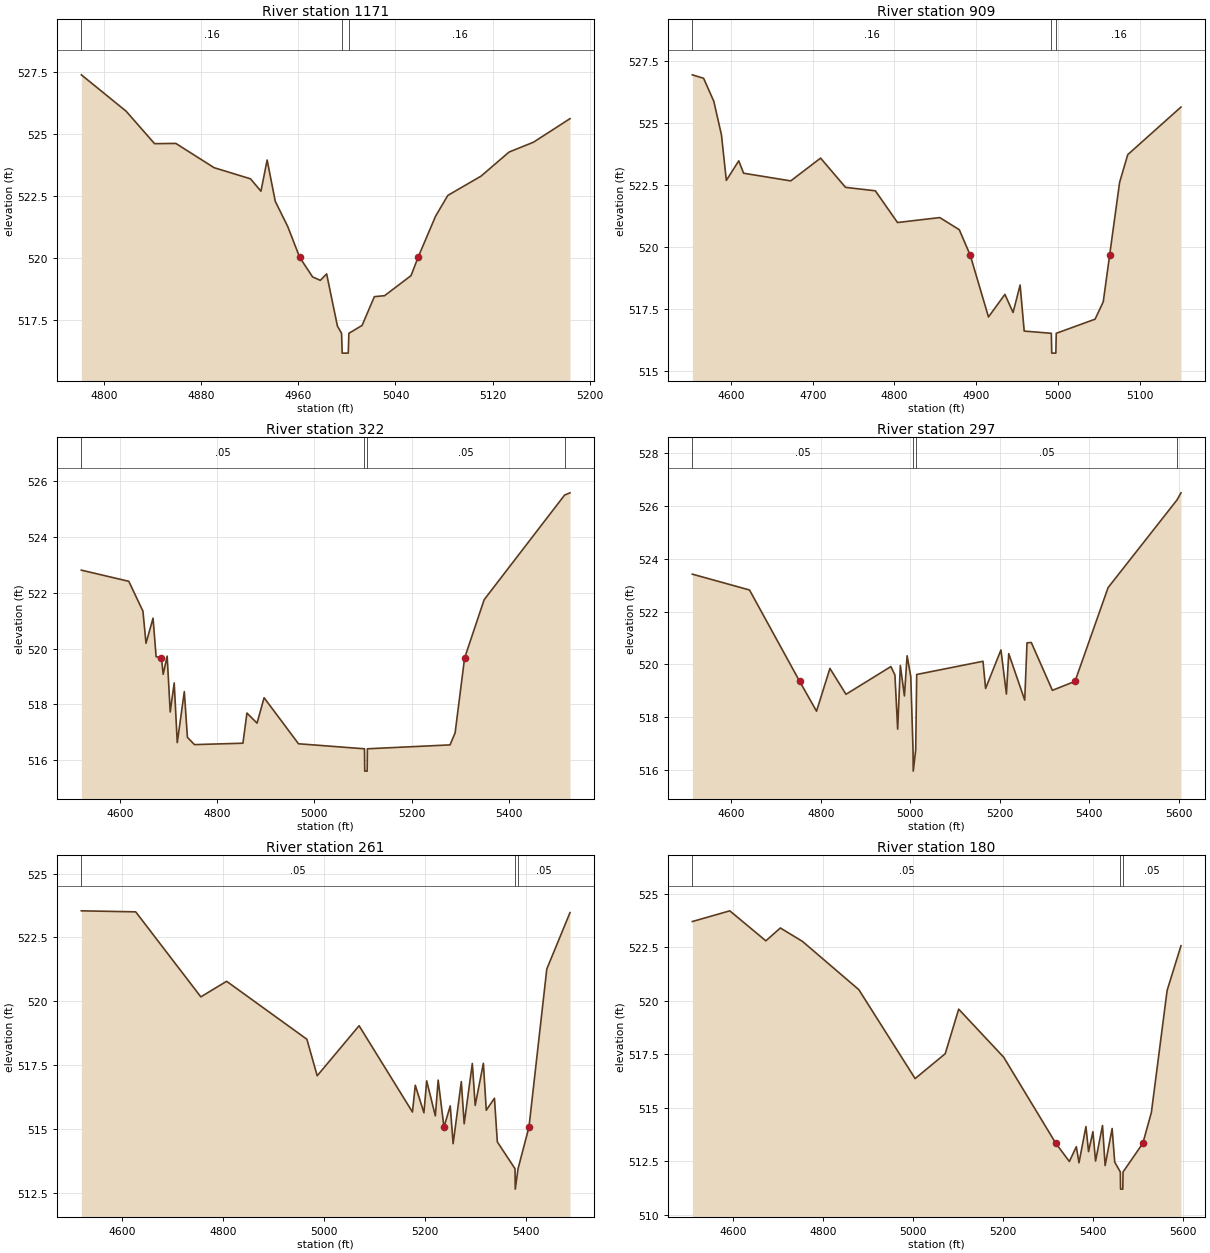
Type RM Length L Ch R = 1,1171,262,262,262
BEGIN DESCRIPTION:
XS3479A
END DESCRIPTION:
XS GIS Cut Line= 3
      2796457.52      7089871.01      2796504.39      7089657.50
      2796480.95      7089475.20
#Sta/Elev= 30
  4781.3  527.40  4818.2  525.93  4841.6  524.62  4859.1  524.63  4890.6  523.65
  4920.6  523.20  4929.2  522.70  4934.3  523.96  4941.0  522.29  4951.3  521.27
  4961.1  520.03  4971.7  519.24  4978.1  519.10  4983.3  519.36  4992.2  517.25
  4995.6  516.96  4996.1  516.16  5001.1  516.16  5001.6  516.96  5012.5  517.28
  5022.6  518.44  5031.0  518.48  5052.8  519.29  5058.6  520.03  5073.0  521.69
  5083.1  522.53  5110.5  523.31  5133.5  524.28  5153.7  524.68  5183.7  525.63
#Mann=3,-1,0
  4781.3    0.16       0  4995.6    0.07       0  5001.6    0.16       0
Bank Sta=4961.1,5058.6
Exp/Cntr=0.3,0.1

Type RM Length L Ch R = 1,909,587,587,587
BEGIN DESCRIPTION:
XS3480A
END DESCRIPTION:
XS GIS Cut Line= 4
      2796488.76      7089886.66      2796663.24      7089610.62
      2796673.66      7089490.83      2796678.86      7089339.93
#Sta/Elev= 30
  4552.7  526.94  4566.5  526.80  4579.0  525.87  4588.3  524.52  4594.3  522.68
  4609.5  523.47  4615.4  522.97  4673.1  522.66  4709.6  523.58  4740.1  522.40
  4776.6  522.26  4803.7  520.98  4855.4  521.18  4879.3  520.69  4892.7  519.66
  4915.0  517.17  4935.1  518.08  4945.1  517.35  4953.7  518.46  4958.7  516.60
  4991.9  516.51  4992.4  515.71  4997.4  515.71  4997.9  516.51  5045.4  517.08
  5055.4  517.78  5063.2  519.66  5075.4  522.60  5085.4  523.72  5150.5  525.64
#Mann=3,-1,0
  4552.7    0.16       0  4991.9    0.07       0  4997.9    0.16       0
Bank Sta=4892.7,5063.2
Exp/Cntr=0.3,0.1

Type RM Length L Ch R = 1,322,25,25,25
BEGIN DESCRIPTION:
XS3478A
END DESCRIPTION:
XS GIS Cut Line= 6
      2796723.12      7089779.91      2797095.53      7089483.02
      2797085.12      7089345.00      2797022.62      7089329.37
      2796939.28      7089342.39      2796698.51      7089334.63
#Sta/Elev= 30
  4520.9  522.81  4618.5  522.41  4647.6  521.34  4653.9  520.19  4668.4  521.09
  4674.7  519.71  4685.7  519.66  4689.2  519.08  4697.4  519.73  4703.7  517.73
  4711.9  518.77  4718.2  516.63  4732.7  518.46  4739.1  516.82  4753.6  516.56
  4853.3  516.61  4861.5  517.69  4882.3  517.33  4896.8  518.24  4967.6  516.59
  5103.3  516.41  5103.8  515.61  5108.8  515.61  5109.3  516.41  5279.3  516.55
  5289.7  516.98  5309.2  519.66  5349.4  521.75  5514.9  525.50  5526.0  525.58
#Mann=4,-1,0
  4520.9    0.05       0  5103.3    0.03       0  5109.3    0.05       0
  5514.9    0.16       0
Bank Sta=4685.7,5309.2
Exp/Cntr=0.3,0.1

Type RM Length L Ch R = 1,297,36,36,36
BEGIN DESCRIPTION:
XS3477A
END DESCRIPTION:
XS GIS Cut Line= 6
      2796736.13      7089792.94      2797069.49      7089566.35
      2797131.99      7089438.75      2797100.74      7089303.33
      2796988.76      7089274.69      2796702.28      7089269.48
#Sta/Elev= 30
  4513.3  523.42  4641.0  522.82  4753.0  519.36  4790.7  518.23  4820.6  519.85
  4856.5  518.87  4956.8  519.92  4965.8  519.60  4971.9  517.55  4977.9  519.96
  4987.0  518.81  4993.0  520.33  5001.2  519.54  5006.2  516.76  5006.7  515.96
  5012.2  516.76  5014.4  519.62  5162.5  520.12  5168.3  519.09  5202.6  520.55
  5214.8  518.88  5220.0  520.41  5255.7  518.65  5260.8  520.82  5270.4  520.83
  5317.5  519.02  5368.0  519.36  5441.9  522.91  5595.8  526.23  5604.7  526.50
#Mann=4,-1,0
  4513.3    0.05       0  5006.2    0.03       0  5012.2    0.05       0
  5595.8    0.16       0
Bank Sta=4753,5368
Exp/Cntr=0.3,0.1

Type RM Length L Ch R = 1,261,81,81,81
BEGIN DESCRIPTION:
XS3476A
END DESCRIPTION:
XS GIS Cut Line= 6
      2796751.76      7089800.74      2797126.78      7089548.12
      2797173.66      7089454.37      2797173.66      7089360.62
      2797142.41      7089295.52      2796927.78      7089179.15
#Sta/Elev= 30
  4519.9  523.54  4627.5  523.50  4756.4  520.17  4807.4  520.78  4966.3  518.51
  4986.7  517.08  5069.6  519.04  5175.2  515.66  5180.8  516.71  5197.9  515.63
  5203.4  516.88  5220.5  515.51  5226.1  516.91  5237.6  515.07  5250.0  515.90
  5255.7  514.42  5271.9  516.85  5277.6  515.20  5293.7  517.56  5299.4  515.92
  5315.6  517.57  5321.3  515.73  5337.5  516.20  5343.2  514.49  5378.2  513.44
  5378.7  512.64  5384.2  513.44  5405.8  515.07  5441.1  521.26  5487.0  523.47
#Mann=3,-1,0
  4519.9    0.05       0  5378.2    0.03       0  5384.2    0.05       0
Bank Sta=5237.6,5405.8
Exp/Cntr=0.3,0.1

Type RM Length L Ch R = 1,180,0,0,0
BEGIN DESCRIPTION:
UNT 067 in LFCCL Watershed 1.0
END DESCRIPTION:
XS GIS Cut Line= 4
      2796751.74      7089825.92      2797210.12      7089575.90
      2797215.33      7089321.56      2796948.55      7089160.98
#Sta/Elev= 30
  4508.5  523.70  4591.9  524.20  4672.2  522.80  4704.5  523.40  4753.9  522.77
  4879.2  520.52  5004.5  516.37  5071.5  517.53  5101.5  519.61  5201.6  517.37
  5317.7  513.35  5347.9  512.50  5363.4  513.19  5369.3  512.44  5384.8  514.13
  5390.6  512.96  5400.3  513.89  5406.2  512.52  5421.7  514.18  5427.5  512.31
  5443.1  514.04  5448.9  512.47  5461.4  512.01  5461.9  511.21  5466.9  511.21
  5467.4  512.01  5511.5  513.35  5530.5  514.79  5565.5  520.48  5596.4  522.57
#Mann=3,-1,0
  4508.5    0.05       0  5461.4    0.03       0  5467.4    0.05       0
Bank Sta=5317.7,5511.5
Exp/Cntr=0.3,0.1

Chan Stop Cuts=-1