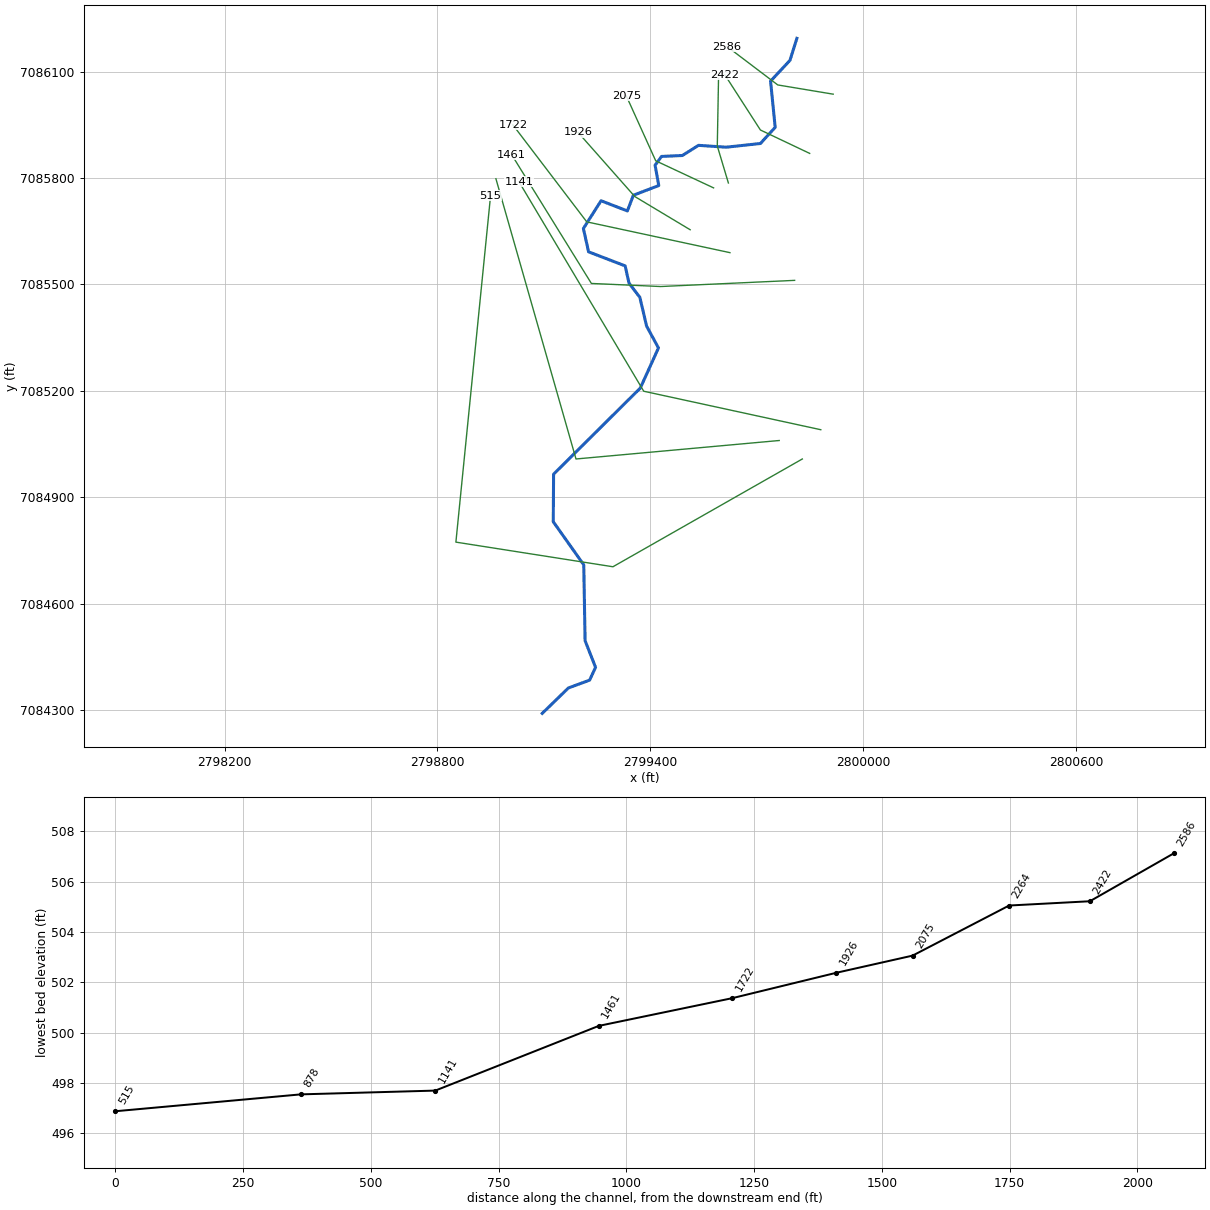
--- UNT 068 in LFCCL Watershed.prj (project) ---

Proj Title=UNT 068 in LFCCL Watershed Base Level Engineering
Current Plan=p01
Default Exp/Contr=0.3,0.1
English Units
Geom File=g01
Flow File=f01
Plan File=p01
BEGIN DESCRIPTION:
UNT 068 in LFCCL Watershed
END DESCRIPTION:

--- UNT 068 in LFCCL Watershed.p01 (plan) ---

Plan Title=Multiple Run
Short Identifier=Multiple
Geom File=g01
Flow File=f01
Subcritical Flow
K Sum by GR= 0
Std Step Tol= 0.01
Critical Tol= 0.01
Num of Std Step Trials= 20
Max Error Tol= 0.3
Flow Tol Ratio= 0.001
Split Flow NTrial= 30
Split Flow Tol= 0.02
Split Flow Ratio= 0.02
Log Output Level= 0
Friction Slope Method= 1
Unsteady Friction Slope Method= 2
Unsteady Bridges Friction Slope Method= 1
Parabolic Critical Depth
Global Vel Dist=  1 , 1 , 1
Global Log Level= 0
CheckData=True
Encroach Param= -1, 0, 0, 0
BEGIN DESCRIPTION:
Multiple Run
END DESCRIPTION:

--- UNT 068 in LFCCL Watershed.f01 (steady flow) ---

Flow Title=Multiple
Number of Profiles=7
Profile Names=10-year,25-year,50-year,1pct_min,100-year,1pct_plu,500-year
River Rch & RM= UNT 068 in LFCCL,Reach-1,2586
     222     274     312     177     353     705     450
Boundary for River Rch & Prof#=UNT 068 in LFCCL,Reach-1,1
Up Type=0
Dn Type=3
Dn Slope=0.005
Boundary for River Rch & Prof#=UNT 068 in LFCCL,Reach-1,2
Up Type=0
Dn Type=3
Dn Slope=0.005
Boundary for River Rch & Prof#=UNT 068 in LFCCL,Reach-1,3
Up Type=0
Dn Type=3
Dn Slope=0.005
Boundary for River Rch & Prof#=UNT 068 in LFCCL,Reach-1,4
Up Type=0
Dn Type=3
Dn Slope=0.005
Boundary for River Rch & Prof#=UNT 068 in LFCCL,Reach-1,5
Up Type=0
Dn Type=3
Dn Slope=0.005
Boundary for River Rch & Prof#=UNT 068 in LFCCL,Reach-1,6
Up Type=0
Dn Type=3
Dn Slope=0.005
Boundary for River Rch & Prof#=UNT 068 in LFCCL,Reach-1,7
Up Type=0
Dn Type=3
Dn Slope=0.005

--- UNT 068 in LFCCL Watershed.g01 (geometry) ---

Geom Title=Existing Conditions

River Reach=UNT 068 in LFCCL,Reach-1
Reach XY= 30
      2799813.49      7086193.56      2799793.96      7086131.49
      2799739.27      7086072.90      2799752.29      7085942.69
      2799710.63      7085897.11      2799614.27      7085886.70
      2799536.15      7085891.91      2799490.57      7085863.26
      2799431.98      7085860.66      2799413.75      7085835.92
      2799424.17      7085778.62      2799352.55      7085751.28
      2799335.63      7085707.01      2799261.43      7085735.77
      2799211.67      7085657.55      2799226.31      7085591.73
      2799329.41      7085552.10      2799340.26      7085503.41
      2799370.82      7085463.46      2799389.80      7085382.37
      2799423.30      7085320.83      2799371.93      7085207.48
      2799127.67      7084965.00      2799126.72      7084830.87
      2799212.68      7084709.51      2799216.44      7084495.68
      2799245.94      7084420.52      2799229.21      7084384.39
      2799169.36      7084362.28      2799095.59      7084290.71

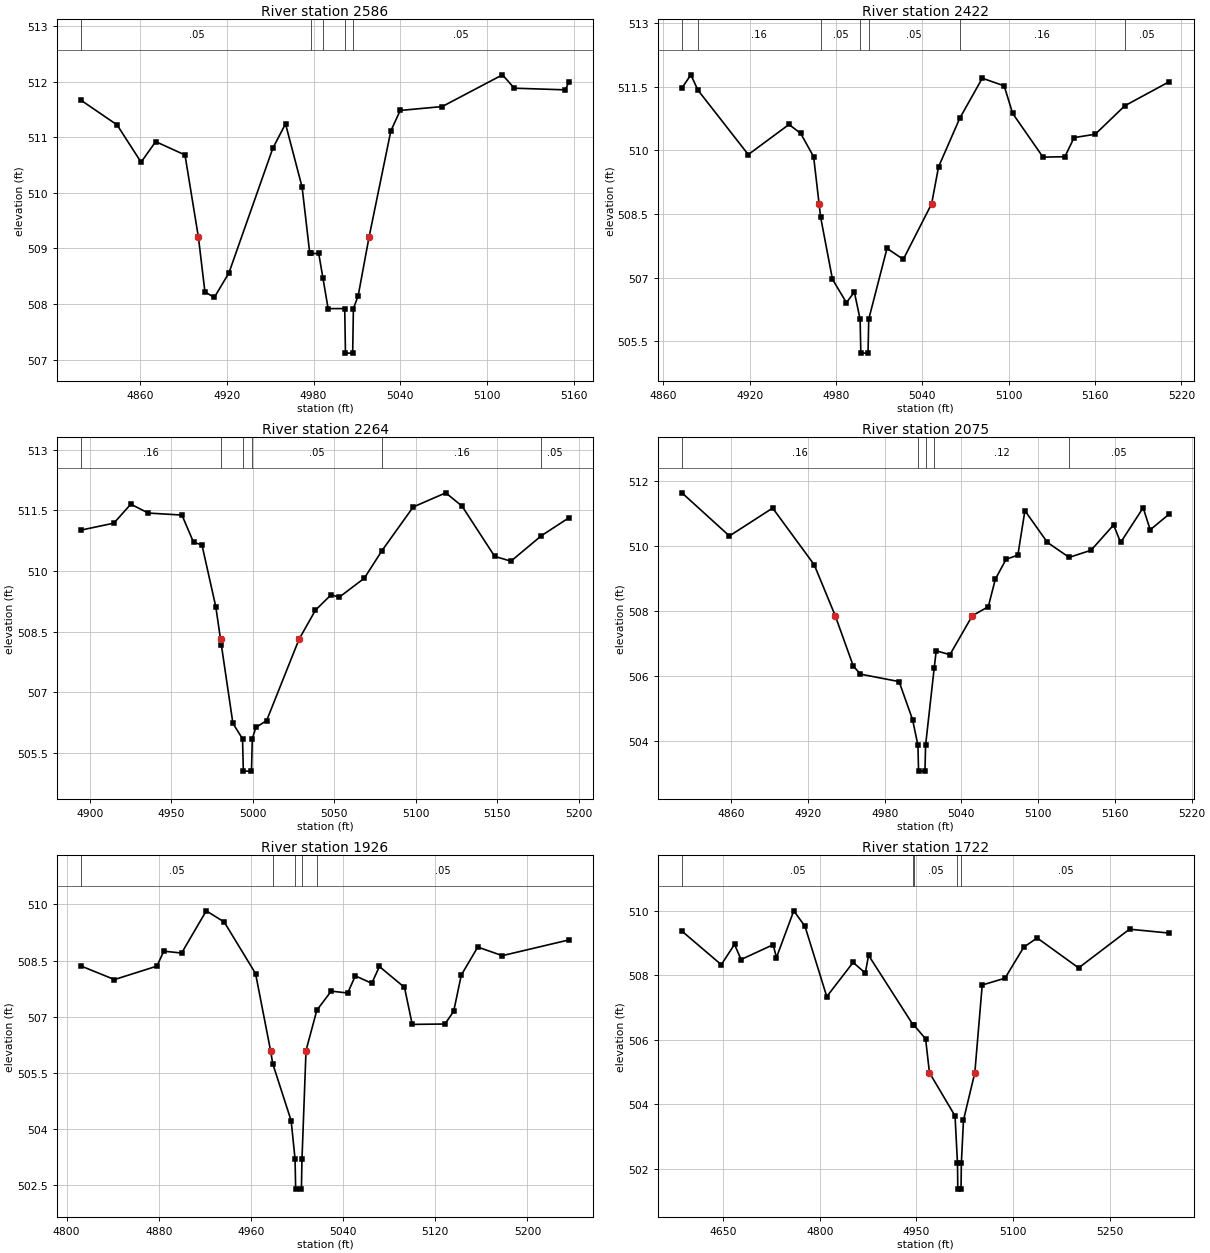
Type RM Length L Ch R = 1,2586,164,164,164
BEGIN DESCRIPTION:
UNT 068 in LFCCL Watershed 2.0
END DESCRIPTION:
XS GIS Cut Line= 3
      2799915.81      7086036.16      2799759.53      7086062.20
      2799616.80      7086170.33
#Sta/Elev= 30
  4819.2  511.66  4844.0  511.22  4860.6  510.55  4870.7  510.92  4891.0  510.68
  4900.3  509.20  4904.8  508.22  4911.3  508.12  4921.4  508.56  4951.8  510.80
  4960.6  511.24  4972.1  510.10  4977.4  508.91  4978.5  508.91  4983.6  508.91
  4986.5  508.47  4990.1  507.92  5001.6  507.92  5002.1  507.12  5007.1  507.12
  5007.6  507.92  5010.9  508.15  5018.4  509.20  5033.5  511.11  5040.0  511.48
  5069.1  511.55  5110.8  512.12  5119.0  511.88  5154.4  511.85  5156.7  511.99
#Mann=5,-1,0
  4819.2    0.05       0  4978.5    0.16       0  4986.5    0.05       0
  5001.6    0.03       0  5007.6    0.05       0
Bank Sta=4900.3,5018.4
Exp/Cntr=0.3,0.1

Type RM Length L Ch R = 1,2422,158,158,158
BEGIN DESCRIPTION:
XS3488A
END DESCRIPTION:
XS GIS Cut Line= 3
      2799849.51      7085869.21      2799710.63      7085935.18
      2799610.44      7086090.64
#Sta/Elev= 30
  4872.9  511.47  4879.1  511.78  4884.0  511.42  4919.0  509.90  4947.3  510.61
  4955.4  510.40  4964.4  509.85  4968.2  508.74  4969.3  508.42  4977.5  506.96
  4987.2  506.41  4992.7  506.66  4996.7  506.02  4997.2  505.22  5002.2  505.22
  5002.7  506.02  5015.4  507.69  5026.7  507.43  5046.4  508.74  5051.2  509.61
  5066.0  510.76  5081.6  511.70  5096.8  511.52  5102.7  510.87  5123.8  509.84
  5139.0  509.85  5145.4  510.30  5160.1  510.38  5180.6  511.05  5211.6  511.62
#Mann=7,-1,0
  4872.9    0.05       0  4884.0    0.16       0  4969.3    0.05       0
  4996.7    0.03       0  5002.7    0.05       0  5066.0    0.16       0
  5180.6    0.05       0
Bank Sta=4968.2,5046.4
Exp/Cntr=0.3,0.1

Type RM Length L Ch R = 1,2264,189,189,189
BEGIN DESCRIPTION:
XS3489A
END DESCRIPTION:
XS GIS Cut Line= 3
      2799620.36      7085785.84      2799589.10      7085890.04
      2799592.57      7086080.52
#Sta/Elev= 30
  4894.7  511.01  4914.7  511.18  4925.1  511.65  4935.8  511.43  4956.5  511.38
  4963.6  510.71  4968.8  510.64  4977.3  509.11  4980.2  508.31  4980.7  508.17
  4987.8  506.23  4993.7  505.85  4994.2  505.05  4999.2  505.05  4999.7  505.85
  5001.9  506.13  5008.5  506.30  5028.4  508.31  5038.5  509.03  5048.1  509.41
  5053.1  509.35  5068.5  509.82  5079.3  510.50  5098.5  511.58  5118.5  511.93
  5128.5  511.60  5148.5  510.36  5158.5  510.24  5177.2  510.87  5194.0  511.31
#Mann=6,-1,0
  4894.7    0.16       0  4980.7    0.05       0  4993.7    0.03       0
  4999.7    0.05       0  5079.3    0.16       0  5177.2    0.05       0
Bank Sta=4980.2,5028.4
Exp/Cntr=0.3,0.1

Type RM Length L Ch R = 1,2075,149,149,149
BEGIN DESCRIPTION:
XS3490A
END DESCRIPTION:
XS GIS Cut Line= 3
      2799578.67      7085771.99      2799415.49      7085848.37
      2799332.69      7086031.23
#Sta/Elev= 30
  4821.6  511.64  4858.7  510.31  4892.5  511.17  4925.0  509.42  4941.4  507.85
  4955.5  506.30  4961.1  506.05  4991.3  505.82  5001.8  504.65  5006.0  503.86
  5006.5  503.06  5011.5  503.06  5012.0  503.86  5018.7  506.23  5020.3  506.77
  5031.0  506.65  5048.5  507.85  5061.0  508.13  5066.5  508.98  5074.9  509.59
  5084.1  509.72  5089.6  511.09  5107.2  510.11  5124.2  509.65  5141.3  509.87
  5158.9  510.65  5164.4  510.11  5182.0  511.18  5187.5  510.50  5202.5  510.99
#Mann=5,-1,0
  4821.6    0.16       0  5006.0    0.07       0  5012.0    0.16       0
  5018.7    0.12       0  5124.2    0.05       0
Bank Sta=4941.4,5048.5
Exp/Cntr=0.3,0.1

Type RM Length L Ch R = 1,1926,204,204,204
BEGIN DESCRIPTION:
XS3491A
END DESCRIPTION:
XS GIS Cut Line= 3
      2799512.67      7085653.95      2799356.46      7085747.68
      2799196.76      7085928.21
#Sta/Elev= 30
  4812.7  508.35  4841.5  507.99  4878.4  508.35  4884.3  508.75  4899.8  508.70
  4921.2  509.83  4936.8  509.53  4964.0  508.15  4977.0  506.09  4978.9  505.74
  4994.9  504.21  4998.3  503.18  4998.8  502.38  5003.8  502.38  5004.3  503.18
  5007.8  506.09  5017.2  507.17  5029.7  507.68  5044.0  507.63  5050.6  508.09
  5064.9  507.89  5071.5  508.34  5093.3  507.78  5100.0  506.79  5128.4  506.80
  5136.0  507.14  5142.6  508.11  5156.9  508.86  5178.2  508.63  5235.9  509.05
#Mann=5,-1,0
  4812.7    0.05       0  4978.9    0.16       0  4998.3    0.07       0
  5004.3    0.16       0  5017.2    0.05       0
Bank Sta=4977,5007.8
Exp/Cntr=0.3,0.1

Type RM Length L Ch R = 1,1722,261,261,261
BEGIN DESCRIPTION:
Mapping XS 43f0efe0
END DESCRIPTION:
XS GIS Cut Line= 3
      2799624.76      7085589.43      2799221.16      7085676.23
      2799012.82      7085949.67
#Sta/Elev= 30
  4586.0  509.37  4647.1  508.33  4667.6  508.96  4677.8  508.49  4727.6  508.95
  4732.7  508.55  4759.6  510.00  4777.0  509.52  4810.8  507.34  4851.7  508.40
  4870.6  508.07  4875.7  508.62  4945.2  506.45  4945.9  506.46  4964.2  506.03
  4970.2  504.98  5009.9  503.64  5013.7  502.17  5014.2  501.37  5019.2  501.37
  5019.7  502.17  5023.0  503.51  5040.6  504.98  5052.1  507.70  5087.4  507.91
  5116.5  508.87  5137.3  509.16  5201.7  508.23  5280.7  509.43  5342.6  509.31
#Mann=5,-1,0
  4586.0    0.05       0  4945.2    0.16       0  4945.9    0.05       0
  5013.7    0.03       0  5019.7    0.05       0
Bank Sta=4970.2,5040.6
Exp/Cntr=0.3,0.1

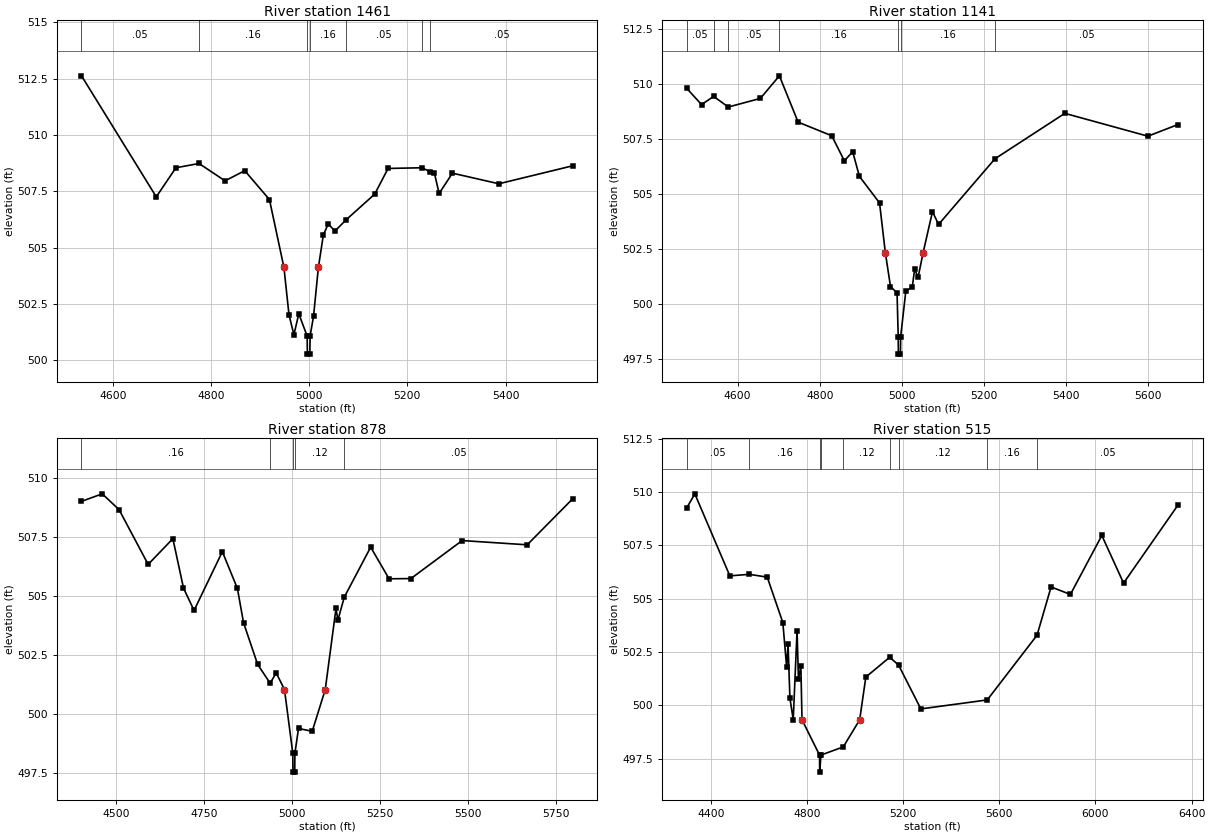
Type RM Length L Ch R = 1,1461,320,320,320
BEGIN DESCRIPTION:
Mapping XS 1917bf08
END DESCRIPTION:
XS GIS Cut Line= 4
      2799807.11      7085511.30      2799429.49      7085493.94
      2799234.18      7085502.62      2799009.23      7085866.00
#Sta/Elev= 30
  4536.3  512.62  4688.6  507.25  4728.6  508.54  4775.7  508.73  4828.7  507.96
  4868.8  508.41  4919.1  507.13  4948.6  504.12  4958.9  502.02  4968.9  501.13
  4978.9  502.06  4995.9  501.07  4996.4  500.27  5001.4  500.27  5001.9  501.07
  5008.9  501.95  5018.8  504.12  5028.9  505.56  5038.9  506.05  5052.4  505.73
  5075.7  506.24  5133.5  507.37  5160.7  508.51  5229.6  508.54  5246.9  508.36
  5255.2  508.29  5264.7  507.40  5291.8  508.30  5386.4  507.83  5537.2  508.63
#Mann=7,-1,0
  4536.3    0.05       0  4775.7    0.16       0  4995.9    0.07       0
  5001.9    0.16       0  5075.7    0.05       0  5229.6    0.16       0
  5246.9    0.05       0
Bank Sta=4948.6,5018.8
Exp/Cntr=0.3,0.1

Type RM Length L Ch R = 1,1141,263,263,263
BEGIN DESCRIPTION:
Mapping XS fedc5d28
END DESCRIPTION:
XS GIS Cut Line= 3
      2799880.89      7085090.29      2799381.75      7085198.80
      2799030.21      7085789.04
#Sta/Elev= 30
  4475.3  509.82  4512.0  509.07  4541.4  509.44  4577.3  508.96  4655.3  509.35
  4701.7  510.38  4747.4  508.27  4829.3  507.65  4860.0  506.51  4880.4  506.92
  4896.7  505.80  4945.8  504.59  4959.9  502.33  4972.5  500.78  4988.5  500.49
  4991.3  498.50  4991.8  497.70  4996.8  497.70  4997.3  498.50  5009.9  500.58
  5025.5  500.75  5031.3  501.56  5039.9  501.21  5052.1  502.33  5074.8  504.19
  5089.7  503.61  5227.1  506.60  5397.4  508.67  5599.9  507.63  5673.1  508.16
#Mann=7,-1,0
  4475.3    0.05       0  4541.4    0.16       0  4577.3    0.05       0
  4701.7    0.16       0  4991.3    0.07       0  4997.3    0.16       0
  5227.1    0.05       0
Bank Sta=4959.9,5052.1
Exp/Cntr=0.3,0.1

Type RM Length L Ch R = 1,878,363,363,363
BEGIN DESCRIPTION:
Mapping XS 51653008
END DESCRIPTION:
XS GIS Cut Line= 3
      2799763.73      7085059.91      2799190.78      7085007.82
      2798965.07      7085797.80
#Sta/Elev= 30
  4401.8  509.02  4460.8  509.34  4508.6  508.67  4591.3  506.35  4661.6  507.44
  4691.7  505.35  4721.8  504.40  4802.2  506.89  4845.0  505.33  4862.4  503.88
  4902.6  502.11  4937.9  501.32  4955.4  501.75  4978.8  501.05  5002.4  498.35
  5002.9  497.55  5007.9  497.55  5008.4  498.35  5018.7  499.40  5057.7  499.28
  5094.7  501.05  5125.3  504.49  5130.5  503.98  5148.7  504.96  5223.8  507.08
  5276.1  505.74  5338.2  505.75  5483.8  507.36  5668.7  507.18  5798.7  509.14
#Mann=5,-1,0
  4401.8    0.16       0  4937.9    0.12       0  5002.4    0.07       0
  5008.4    0.12       0  5148.7    0.05       0
Bank Sta=4978.8,5094.7
Exp/Cntr=0.3,0.1

Type RM Length L Ch R = 1,515,0,0,0
BEGIN DESCRIPTION:
XS3496A
END DESCRIPTION:
XS GIS Cut Line= 4
      2799828.83      7085007.84      2799294.94      7084704.00
      2798852.24      7084773.45      2798950.00      7085749.96
#Sta/Elev= 30
  4299.2  509.23  4333.8  509.91  4479.4  506.07  4560.5  506.14  4635.0  506.01
  4699.9  503.88  4715.7  501.79  4721.5  502.90  4729.3  500.34  4743.1  499.34
  4759.0  503.51  4764.7  501.23  4774.8  501.84  4779.6  499.33  4852.5  497.68
  4853.0  496.88  4858.5  497.68  4951.2  498.06  5019.4  499.33  5045.0  501.33
  5144.3  502.26  5181.3  501.89  5273.8  499.84  5549.9  500.26  5757.0  503.29
  5815.4  505.55  5895.8  505.20  6026.5  507.96  6116.9  505.73  6343.0  509.38
#Mann=9,-1,0
  4299.2    0.05       0  4560.5    0.16       0  4852.5    0.07       0
  4858.5    0.16       0  4951.2    0.12       0  5144.3    0.16       0
  5181.3    0.12       0  5549.9    0.16       0  5757.0    0.05       0
Bank Sta=4779.6,5019.4
Exp/Cntr=0.3,0.1

Chan Stop Cuts=-1