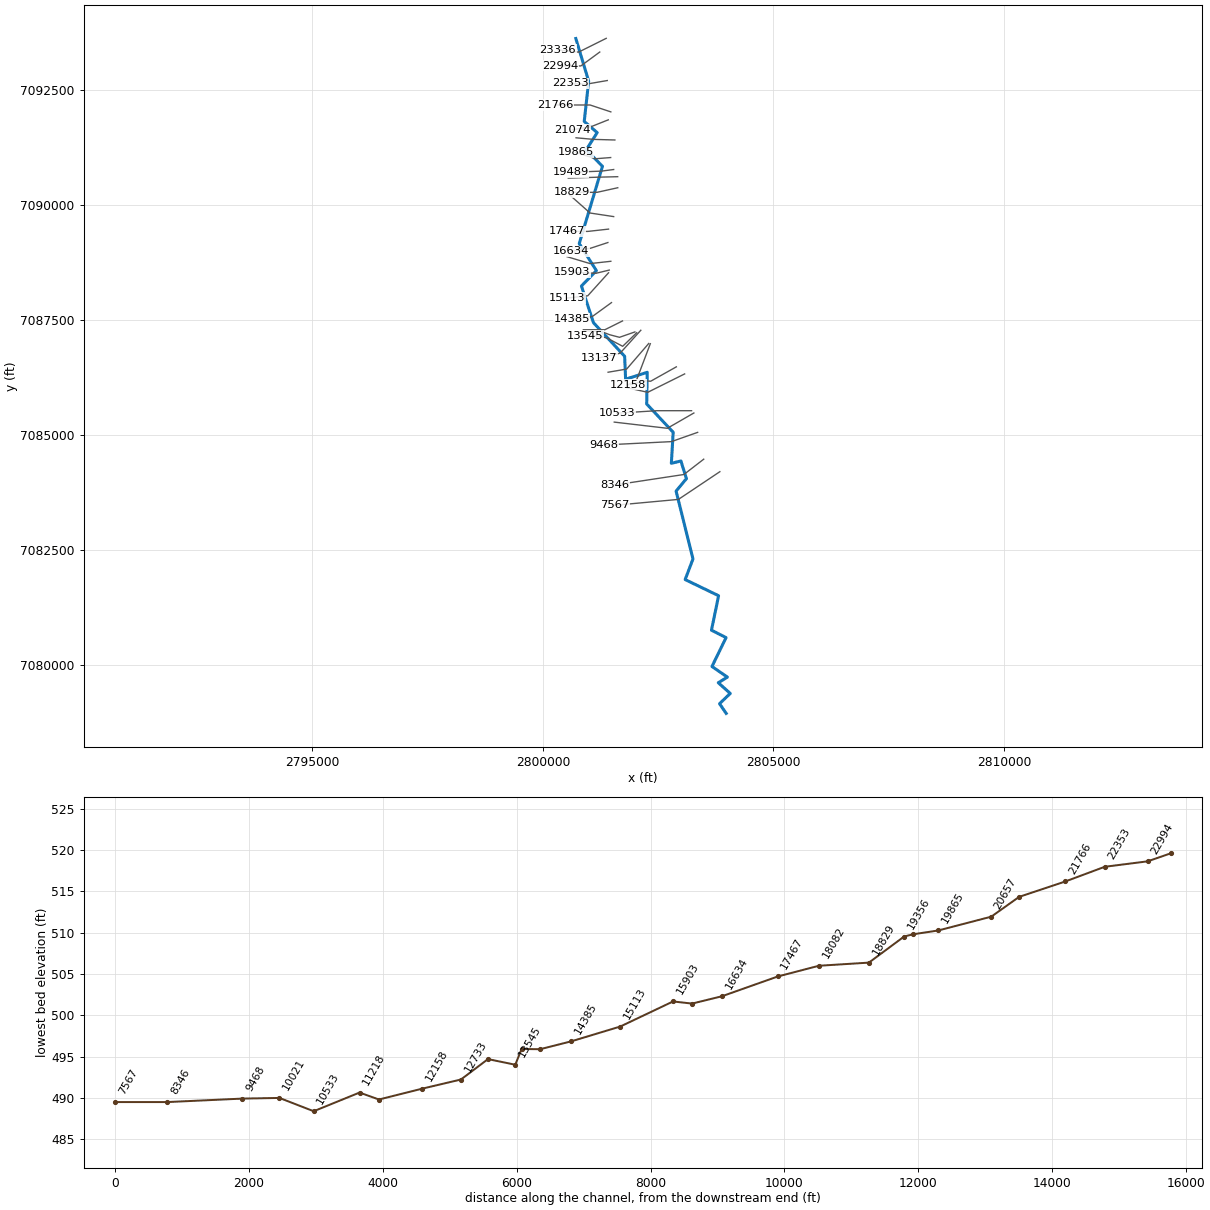
--- UNT 070 in LFCCL Watershed.prj (project) ---

Proj Title=UNT 070 in LFCCL Watershed Base Level Engineering
Current Plan=p01
Default Exp/Contr=0.3,0.1
English Units
Geom File=g01
Flow File=f01
Plan File=p01
BEGIN DESCRIPTION:
UNT 070 in LFCCL Watershed
END DESCRIPTION:

--- UNT 070 in LFCCL Watershed.p01 (plan) ---

Plan Title=Multiple Run
Short Identifier=Multiple
Geom File=g01
Flow File=f01
Subcritical Flow
K Sum by GR= 0
Std Step Tol= 0.01
Critical Tol= 0.01
Num of Std Step Trials= 20
Max Error Tol= 0.3
Flow Tol Ratio= 0.001
Split Flow NTrial= 30
Split Flow Tol= 0.02
Split Flow Ratio= 0.02
Log Output Level= 0
Friction Slope Method= 1
Unsteady Friction Slope Method= 2
Unsteady Bridges Friction Slope Method= 1
Parabolic Critical Depth
Global Vel Dist=  1 , 1 , 1
Global Log Level= 0
CheckData=True
Encroach Param= -1, 0, 0, 0
BEGIN DESCRIPTION:
Multiple Run
END DESCRIPTION:

--- UNT 070 in LFCCL Watershed.f01 (steady flow) ---

Flow Title=Multiple
Number of Profiles=7
Profile Names=10-year,25-year,50-year,1pct_min,100-year,1pct_plu,500-year
River Rch & RM= UNT 070 in LFCCL,Reach-1,23336
     732     976    1173     698    1393    2780    1961
River Rch & RM= UNT 070 in LFCCL,Reach-1,22353
     985    1328    1607     962    1920    3830    2734
River Rch & RM= UNT 070 in LFCCL,Reach-1,11508
    1230    1680    2048    1235    2464    4917    3562
River Rch & RM= UNT 070 in LFCCL,Reach-1,10533
    1353    1854    2267    1369    2732    5452    3965
River Rch & RM= UNT 070 in LFCCL,Reach-1,6848
    1476    2035    2499    1516    3025    6035    4427
River Rch & RM= UNT 070 in LFCCL,Reach-1,6093
    1568    2169    2668    1622    3236    6456    4753
River Rch & RM= UNT 070 in LFCCL,Reach-1,3641
    1651    2287    2816    1712    3417    6817    5026
Boundary for River Rch & Prof#=UNT 070 in LFCCL,Reach-1,1
Up Type=0
Dn Type=3
Dn Slope=0.005
Boundary for River Rch & Prof#=UNT 070 in LFCCL,Reach-1,2
Up Type=0
Dn Type=3
Dn Slope=0.005
Boundary for River Rch & Prof#=UNT 070 in LFCCL,Reach-1,3
Up Type=0
Dn Type=3
Dn Slope=0.005
Boundary for River Rch & Prof#=UNT 070 in LFCCL,Reach-1,4
Up Type=0
Dn Type=3
Dn Slope=0.005
Boundary for River Rch & Prof#=UNT 070 in LFCCL,Reach-1,5
Up Type=0
Dn Type=3
Dn Slope=0.005
Boundary for River Rch & Prof#=UNT 070 in LFCCL,Reach-1,6
Up Type=0
Dn Type=3
Dn Slope=0.005
Boundary for River Rch & Prof#=UNT 070 in LFCCL,Reach-1,7
Up Type=0
Dn Type=3
Dn Slope=0.005

--- UNT 070 in LFCCL Watershed.g01 (geometry) ---

Geom Title=Existing Conditions

River Reach=UNT 070 in LFCCL,Reach-1
Reach XY= 30
      2800715.59      7093620.71      2800994.12      7092694.34
      2800897.99      7091816.95      2801179.06      7091574.46
      2800941.82      7091200.58      2801293.27      7090841.15
      2800789.83      7089159.67      2801161.82      7088571.79
      2800837.18      7088236.58      2801097.55      7087440.04
      2801774.28      7086708.24      2801795.03      7086209.47
      2802264.27      7086360.30      2802252.30      7085670.80
      2802826.09      7085056.31      2802786.99      7084380.38
      2802993.68      7084431.45      2803114.18      7084047.60
      2802889.93      7083775.47      2803255.84      7082299.68
      2803086.02      7081851.22      2803810.96      7081500.22
      2803656.81      7080749.97      2803973.42      7080589.24
      2803667.46      7079960.63      2804002.25      7079729.36
      2803804.69      7079607.47      2804063.51      7079374.43
      2803831.74      7079150.87      2803975.59      7078940.71

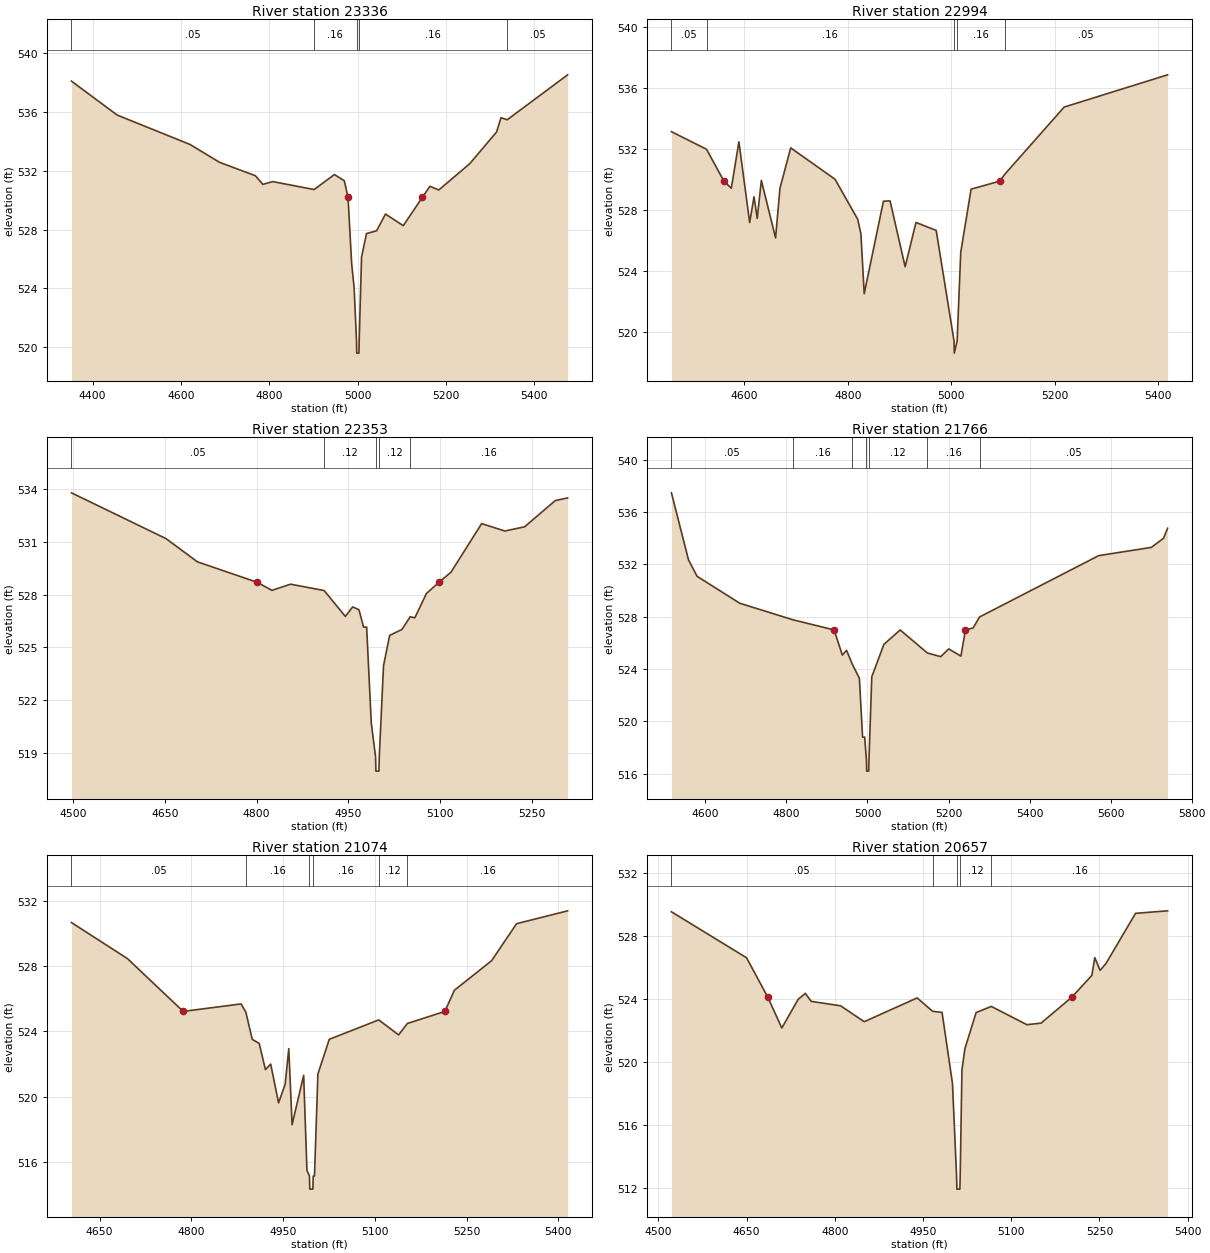
Type RM Length L Ch R = 1,23336,342,342,342
BEGIN DESCRIPTION:
UNT 070 in LFCCL Watershed 30.0
END DESCRIPTION:
XS GIS Cut Line= 3
      2801375.04      7093625.02      2800775.00      7093325.00
      2800325.04      7093375.00
#Sta/Elev= 30
  4352.1  538.11  4455.6  535.80  4620.5  533.80  4687.6  532.58  4768.6  531.67
  4785.4  531.08  4807.7  531.27  4901.6  530.73  4947.5  531.75  4969.9  531.33
  4978.4  530.20  4986.6  525.67  4992.2  524.05  4997.6  520.39  4998.1  519.59
  5003.1  519.59  5003.6  520.39  5009.0  526.13  5020.2  527.73  5043.1  527.92
  5063.2  529.06  5103.5  528.27  5146.8  530.20  5163.8  530.95  5184.0  530.70
  5254.4  532.50  5314.8  534.65  5324.8  535.62  5338.9  535.48  5475.7  538.54
#Mann=5,-1,0
  4352.1    0.05       0  4901.6    0.16       0  4997.6    0.07       0
  5003.6    0.16       0  5338.9    0.05       0
Bank Sta=4978.4,5146.8
Exp/Cntr=0.3,0.1

Type RM Length L Ch R = 1,22994,641,641,641
BEGIN DESCRIPTION:
UNT 070 in LFCCL Watershed 29.0
END DESCRIPTION:
XS GIS Cut Line= 3
      2801234.96      7093327.47      2800825.00      7093025.00
      2800374.97      7093025.00
#Sta/Elev= 30
  4458.9  533.12  4526.8  531.97  4560.4  529.88  4574.7  529.42  4589.4  532.46
  4610.2  527.17  4618.6  528.86  4624.8  527.45  4632.8  529.93  4660.3  526.17
  4668.8  529.42  4689.6  532.06  4775.2  530.01  4819.1  527.39  4825.3  526.44
  4831.7  522.52  4868.9  528.57  4881.7  528.59  4910.9  524.28  4931.8  527.18
  4970.9  526.66  5005.4  519.43  5005.9  518.63  5011.4  519.43  5018.4  525.23
  5038.4  529.36  5093.7  529.88  5104.0  530.35  5218.4  534.73  5418.4  536.84
#Mann=5,-1,0
  4458.9    0.05       0  4526.8    0.16       0  5005.4    0.07       0
  5011.4    0.16       0  5104.0    0.05       0
Bank Sta=4560.4,5093.7
Exp/Cntr=0.3,0.1

Type RM Length L Ch R = 1,22353,587,587,587
BEGIN DESCRIPTION:
UNT 070 in LFCCL Watershed 28.0
END DESCRIPTION:
XS GIS Cut Line= 3
      2801397.73      7092707.23      2800925.00      7092625.00
      2800594.82      7092646.46
#Sta/Elev= 30
  4497.5  533.78  4651.9  531.18  4703.3  529.86  4800.7  528.70  4825.1  528.24
  4855.5  528.59  4910.3  528.23  4945.0  526.76  4957.0  527.30  4967.2  527.14
  4974.8  526.15  4979.8  526.15  4987.3  520.74  4994.4  518.77  4994.9  517.97
  4999.9  517.97  5000.4  518.77  5007.4  523.96  5017.4  525.68  5037.5  526.02
  5051.0  526.74  5058.5  526.68  5077.5  528.06  5098.1  528.70  5117.6  529.27
  5167.7  532.03  5205.7  531.61  5237.9  531.85  5288.0  533.34  5308.2  533.49
#Mann=5,-1,0
  4497.5    0.05       0  4910.3    0.12       0  4994.4    0.07       0
  5000.4    0.12       0  5051.0    0.16       0
Bank Sta=4800.7,5098.1
Exp/Cntr=0.3,0.1

Type RM Length L Ch R = 1,21766,692,692,692
BEGIN DESCRIPTION:
UNT 070 in LFCCL Watershed 27.0
END DESCRIPTION:
XS GIS Cut Line= 3
      2801475.03      7092024.99      2801025.00      7092175.00
      2800274.97      7092175.00
#Sta/Elev= 30
  4516.2  537.47  4558.4  532.34  4579.5  531.09  4684.9  529.03  4815.8  527.77
  4917.7  526.99  4937.9  525.07  4948.4  525.43  4962.5  524.38  4980.0  523.30
  4987.9  518.80  4993.1  518.80  4997.5  517.00  4998.0  516.20  5003.1  516.20
  5003.6  517.00  5010.6  523.41  5040.6  525.89  5080.6  526.99  5147.8  525.23
  5180.6  524.95  5200.6  525.54  5230.6  524.99  5241.7  526.99  5260.6  527.14
  5276.5  527.98  5570.6  532.67  5700.6  533.30  5730.6  534.00  5740.6  534.76
#Mann=7,-1,0
  4516.2    0.05       0  4815.8    0.16       0  4962.5    0.12       0
  4997.5    0.07       0  5003.6    0.12       0  5147.8    0.16       0
  5276.5    0.05       0
Bank Sta=4917.7,5241.7
Exp/Cntr=0.3,0.1

Type RM Length L Ch R = 1,21074,417,417,417
BEGIN DESCRIPTION:
XS3498A
END DESCRIPTION:
XS GIS Cut Line= 3
      2801419.39      7091852.18      2801050.50      7091704.63
      2800642.48      7091635.17
#Sta/Elev= 30
  4604.0  530.68  4695.5  528.47  4786.7  525.23  4881.3  525.69  4889.2  525.17
  4899.5  523.52  4910.9  523.27  4921.1  521.66  4929.7  522.00  4942.6  519.62
  4953.4  520.77  4959.3  522.95  4964.7  518.28  4983.6  521.31  4989.0  515.48
  4993.1  515.13  4993.6  514.33  4998.7  514.33  4999.2  515.13  5001.3  515.13
  5006.9  521.39  5025.5  523.52  5106.4  524.71  5138.8  523.79  5153.2  524.49
  5214.5  525.23  5230.1  526.53  5290.9  528.34  5331.7  530.61  5415.2  531.40
#Mann=6,-1,0
  4604.0    0.05       0  4889.2    0.16       0  4993.1    0.07       0
  4999.2    0.16       0  5106.4    0.12       0  5153.2    0.16       0
Bank Sta=4786.7,5214.5
Exp/Cntr=0.3,0.1

Type RM Length L Ch R = 1,20657,792,792,792
BEGIN DESCRIPTION:
XS3499A
END DESCRIPTION:
XS GIS Cut Line= 3
      2801562.63      7091413.83      2801102.59      7091426.85
      2800720.69      7091461.57
#Sta/Elev= 30
  4522.2  529.54  4649.9  526.62  4686.3  524.10  4709.9  522.16  4737.7  523.98
  4749.9  524.36  4759.9  523.85  4809.9  523.57  4850.0  522.56  4940.0  524.07
  4966.4  523.22  4982.4  523.15  5000.1  518.64  5007.1  512.73  5007.6  511.93
  5012.7  511.93  5013.2  512.73  5016.2  519.49  5021.2  520.84  5040.3  523.14
  5066.1  523.53  5126.7  522.37  5150.7  522.47  5202.6  524.10  5237.1  525.50
  5242.1  526.63  5251.1  525.82  5261.2  526.26  5311.4  529.44  5365.9  529.60
#Mann=5,-1,0
  4522.2    0.05       0  4966.4    0.12       0  5007.1    0.07       0
  5013.2    0.12       0  5066.1    0.16       0
Bank Sta=4686.3,5202.6
Exp/Cntr=0.3,0.1

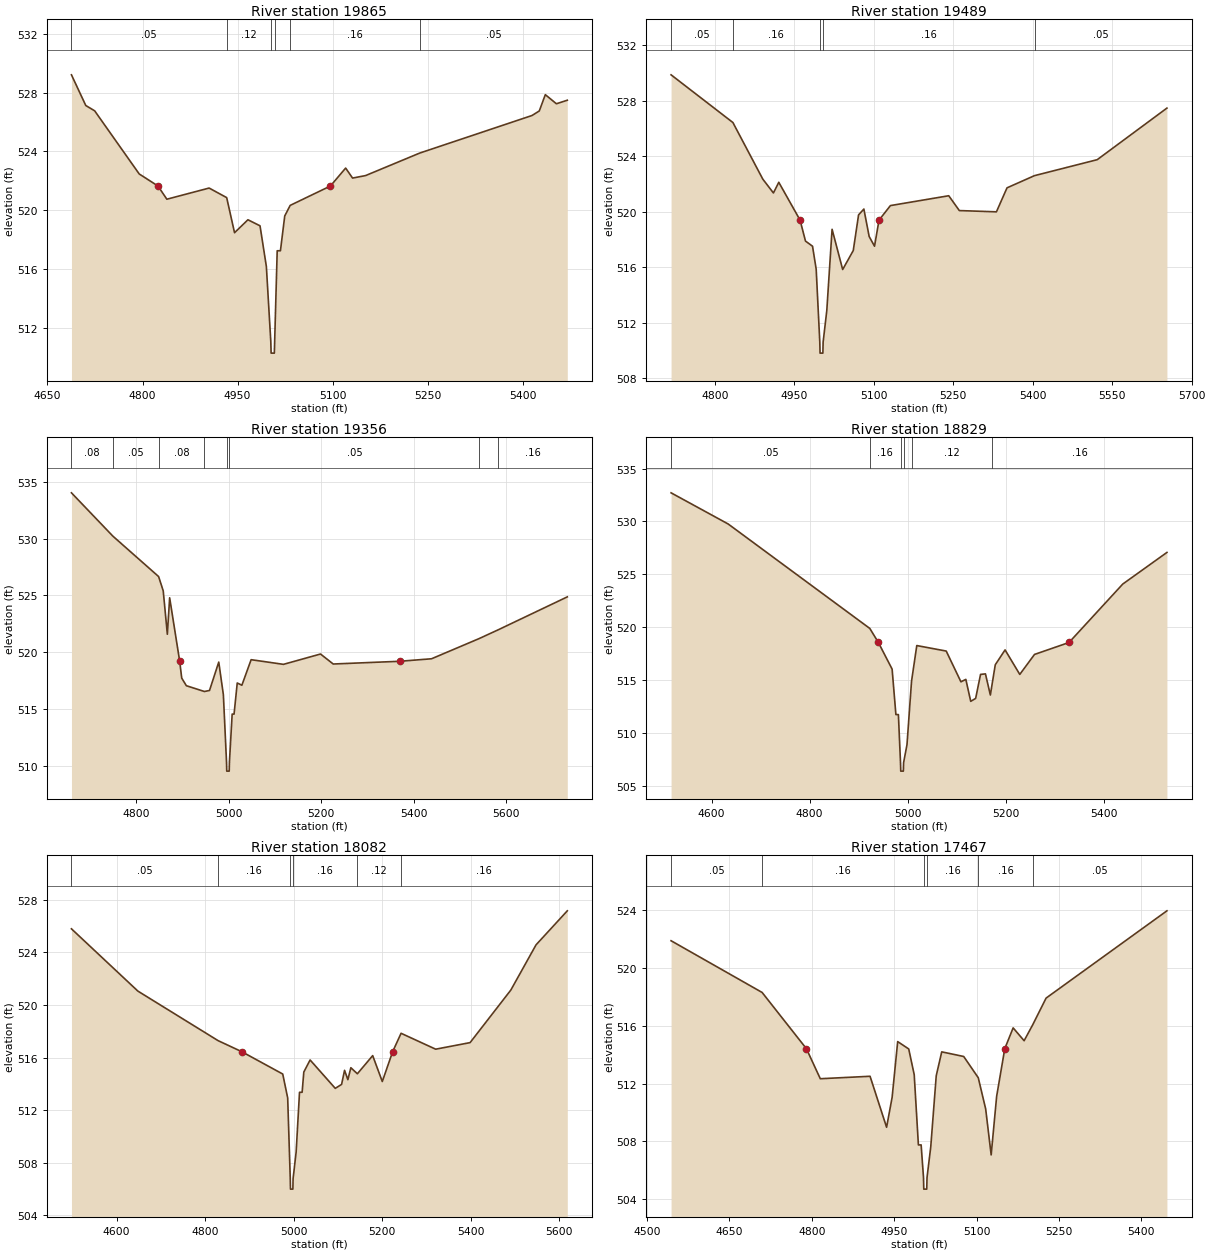
Type RM Length L Ch R = 1,19865,376,376,376
BEGIN DESCRIPTION:
XS3500A
END DESCRIPTION:
XS GIS Cut Line= 3
      2801471.52      7091031.88      2801145.99      7091005.84
      2800711.95      7091144.74
#Sta/Elev= 30
  4687.9  529.21  4710.5  527.12  4724.5  526.76  4794.8  522.46  4824.4  521.64
  4838.4  520.74  4905.1  521.50  4932.8  520.85  4945.2  518.46  4966.3  519.34
  4985.4  518.93  4995.4  516.16  5002.4  511.06  5002.9  510.26  5008.0  510.26
  5008.5  511.06  5012.5  517.23  5017.6  517.23  5024.4  519.60  5033.0  520.32
  5096.5  521.64  5120.5  522.86  5131.4  522.18  5152.0  522.35  5237.2  523.88
  5414.5  526.44  5426.0  526.75  5435.5  527.86  5453.0  527.24  5470.2  527.48
#Mann=6,-1,0
  4687.9    0.05       0  4932.8    0.12       0  5002.4    0.07       0
  5008.5    0.12       0  5033.0    0.16       0  5237.2    0.05       0
Bank Sta=4824.4,5096.5
Exp/Cntr=0.3,0.1

Type RM Length L Ch R = 1,19489,133,133,133
BEGIN DESCRIPTION:
XS3501A
END DESCRIPTION:
XS GIS Cut Line= 3
      2801536.59      7090771.46      2801271.86      7090736.74
      2800603.47      7090710.70
#Sta/Elev= 30
  4717.4  529.87  4834.1  526.43  4890.5  522.35  4910.6  521.35  4920.7  522.12
  4960.9  519.39  4971.1  517.88  4984.4  517.51  4991.3  515.85  4998.1  510.60
  4998.6  509.80  5003.9  509.80  5004.4  510.60  5011.3  512.86  5021.3  518.73
  5041.3  515.83  5061.3  517.20  5071.3  519.77  5081.3  520.19  5091.3  518.21
  5101.4  517.51  5109.9  519.39  5131.4  520.44  5241.5  521.15  5261.5  520.08
  5331.5  519.99  5351.5  521.72  5403.4  522.60  5521.7  523.75  5653.3  527.47
#Mann=5,-1,0
  4717.4    0.05       0  4834.1    0.16       0  4998.1    0.07       0
  5004.4    0.16       0  5403.4    0.05       0
Bank Sta=4960.9,5109.9
Exp/Cntr=0.3,0.1

Type RM Length L Ch R = 1,19356,527,527,527
BEGIN DESCRIPTION:
XS3502A
END DESCRIPTION:
XS GIS Cut Line= 3
      2801623.47      7090615.22      2801271.86      7090606.53
      2800551.40      7090584.83
#Sta/Elev= 30
  4659.8  534.03  4749.3  530.22  4848.3  526.66  4858.3  525.40  4867.2  521.58
  4872.2  524.79  4893.9  519.20  4898.3  517.72  4908.3  517.05  4947.4  516.54
  4958.4  516.63  4978.4  519.13  4988.4  516.25  4995.2  510.33  4995.7  509.53
  5001.0  509.53  5001.5  510.33  5007.4  514.55  5011.5  514.55  5018.4  517.29
  5028.4  517.09  5048.4  519.34  5118.4  518.93  5198.5  519.84  5226.0  518.96
  5369.6  519.20  5438.6  519.42  5541.7  521.20  5583.3  521.98  5732.3  524.87
#Mann=8,-1,0
  4659.8    0.08       0  4749.3    0.05       0  4848.3    0.08       0
  4947.4    0.05       0  4995.2    0.04       0  5001.5    0.05       0
  5541.7    0.08       0  5583.3    0.16       0
Bank Sta=4893.9,5369.6
Exp/Cntr=0.3,0.1

Type RM Length L Ch R = 1,18829,747,747,747
BEGIN DESCRIPTION:
UNT 070 in LFCCL Watershed 24.0
END DESCRIPTION:
XS GIS Cut Line= 3
      2801624.99      7090375.00      2801175.00      7090275.00
      2800624.97      7090275.00
#Sta/Elev= 30
  4517.5  532.70  4634.0  529.75  4922.7  519.87  4940.2  518.54  4968.2  516.02
  4975.9  511.72  4981.0  511.72  4985.3  507.17  4985.8  506.37  4991.1  506.37
  4991.6  507.17  4998.5  508.87  5007.8  514.88  5018.5  518.25  5078.5  517.73
  5108.5  514.82  5118.5  515.05  5128.5  512.97  5138.5  513.25  5148.5  515.52
  5158.5  515.57  5168.5  513.57  5171.6  514.46  5178.5  516.43  5198.5  517.84
  5228.5  515.52  5258.5  517.41  5328.9  518.54  5438.5  524.07  5528.5  527.06
#Mann=6,-1,0
  4517.5    0.05       0  4922.7    0.16       0  4985.3    0.07       0
  4991.6    0.16       0  5007.8    0.12       0  5171.6    0.16       0
Bank Sta=4940.2,5328.9
Exp/Cntr=0.3,0.1

Type RM Length L Ch R = 1,18082,615,615,615
BEGIN DESCRIPTION:
UNT 070 in LFCCL Watershed 23.0
END DESCRIPTION:
XS GIS Cut Line= 3
      2801536.57      7089747.17      2801025.00      7089825.00
      2800575.03      7090224.97
#Sta/Elev= 30
  4498.3  525.80  4648.3  521.06  4829.4  517.29  4882.8  516.45  4975.3  514.75
  4986.5  512.93  4992.3  506.79  4992.8  505.99  4998.2  505.99  4998.7  506.79
  5005.6  508.82  5013.2  513.36  5019.1  513.36  5022.9  514.90  5037.1  515.82
  5093.9  513.66  5108.2  513.96  5114.9  515.03  5122.4  514.32  5129.1  515.23
  5143.8  514.77  5178.4  516.15  5200.1  514.18  5223.5  516.45  5242.5  517.85
  5320.6  516.64  5398.3  517.14  5490.3  521.14  5547.2  524.58  5617.8  527.17
#Mann=6,-1,0
  4498.3    0.05       0  4829.4    0.16       0  4992.3    0.07       0
  4998.7    0.16       0  5143.8    0.12       0  5242.5    0.16       0
Bank Sta=4882.8,5223.5
Exp/Cntr=0.3,0.1

Type RM Length L Ch R = 1,17467,833,833,833
BEGIN DESCRIPTION:
UNT 070 in LFCCL Watershed 22.0
END DESCRIPTION:
XS GIS Cut Line= 3
      2801425.04      7089475.00      2800975.00      7089425.00
      2800525.01      7089425.00
#Sta/Elev= 30
  4543.9  521.88  4709.7  518.30  4790.3  514.41  4815.6  512.33  4906.2  512.50
  4936.3  508.97  4946.4  511.05  4956.5  514.90  4976.6  514.39  4986.6  512.61
  4994.2  507.75  4999.2  507.75  5003.5  505.49  5004.0  504.69  5009.4  504.69
  5009.9  505.49  5016.7  507.61  5026.7  512.54  5036.7  514.19  5076.7  513.87
  5103.2  512.40  5116.7  510.24  5126.7  507.06  5136.7  511.12  5151.5  514.41
  5166.7  515.85  5186.7  514.96  5202.3  516.06  5226.7  517.91  5446.7  523.95
#Mann=6,-1,0
  4543.9    0.05       0  4709.7    0.16       0  5003.5    0.07       0
  5009.9    0.16       0  5103.2    0.16       0  5202.3    0.05       0
Bank Sta=4790.3,5151.5
Exp/Cntr=0.3,0.1

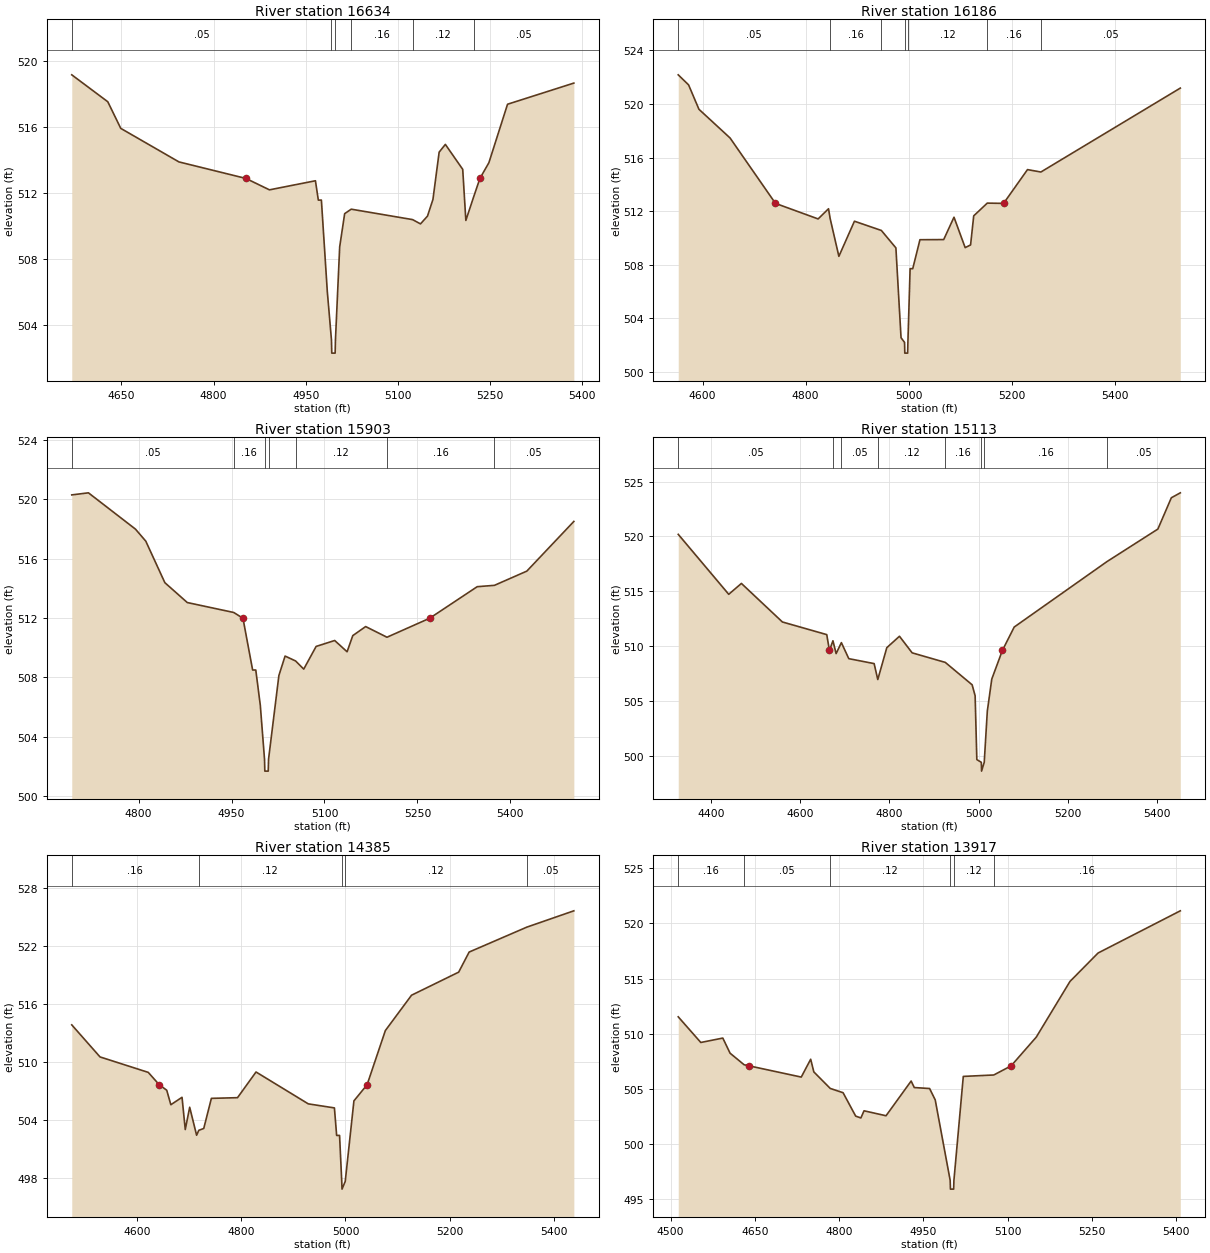
Type RM Length L Ch R = 1,16634,448,448,448
BEGIN DESCRIPTION:
XS3503A
END DESCRIPTION:
XS GIS Cut Line= 3
      2801410.78      7089182.94      2801028.80      7089057.06
      2800618.28      7088992.24
#Sta/Elev= 30
  4569.0  519.14  4627.7  517.51  4648.8  515.90  4743.6  513.87  4852.7  512.87
  4891.0  512.18  4965.9  512.73  4970.6  511.56  4975.6  511.56  4985.2  506.04
  4992.0  503.10  4992.5  502.30  4998.0  502.30  4998.5  503.10  5005.4  508.73
  5013.5  510.74  5024.2  511.01  5124.1  510.38  5137.0  510.12  5148.4  510.59
  5157.3  511.60  5167.4  514.46  5177.5  514.93  5205.8  513.42  5210.9  510.33
  5224.1  511.81  5233.8  512.87  5248.4  513.82  5278.8  517.36  5386.8  518.64
#Mann=6,-1,0
  4569.0    0.05       0  4992.0    0.03       0  4998.5    0.05       0
  5024.2    0.16       0  5124.1    0.12       0  5224.1    0.05       0
Bank Sta=4852.7,5233.8
Exp/Cntr=0.3,0.1

Type RM Length L Ch R = 1,16186,283,283,283
BEGIN DESCRIPTION:
UNT 070 in LFCCL Watershed 20.0
END DESCRIPTION:
XS GIS Cut Line= 3
      2801474.97      7088775.00      2801025.00      7088725.00
      2800524.96      7088875.01
#Sta/Elev= 30
  4552.8  522.17  4572.9  521.42  4593.0  519.60  4653.4  517.46  4741.6  512.58
  4824.4  511.42  4844.6  512.18  4847.8  511.44  4864.7  508.63  4894.9  511.25
  4947.2  510.56  4975.4  509.26  4985.4  502.56  4992.2  502.21  4992.7  501.41
  4998.2  501.41  4998.7  502.21  5003.0  507.71  5008.1  507.71  5022.1  509.87
  5068.2  509.88  5088.2  511.55  5109.9  509.28  5120.4  509.48  5126.5  511.65
  5152.8  512.60  5184.5  512.58  5230.9  515.10  5256.9  514.92  5527.6  521.18
#Mann=7,-1,0
  4552.8    0.05       0  4847.8    0.16       0  4947.2    0.12       0
  4992.2    0.07       0  4998.7    0.12       0  5152.8    0.16       0
  5256.9    0.05       0
Bank Sta=4741.6,5184.5
Exp/Cntr=0.3,0.1

Type RM Length L Ch R = 1,15903,790,790,790
BEGIN DESCRIPTION:
XS3504A
END DESCRIPTION:
XS GIS Cut Line= 3
      2801441.11      7088583.96      2801154.67      7088514.52
      2800639.10      7088531.85
#Sta/Elev= 30
  4692.0  520.30  4718.9  520.44  4794.9  517.99  4811.5  517.18  4842.3  514.38
  4878.5  513.04  4953.5  512.37  4968.4  511.98  4984.0  508.49  4989.1  508.49
  4996.4  506.11  5003.2  502.47  5003.7  501.67  5009.2  501.67  5009.7  502.47
  5026.4  508.12  5036.4  509.43  5053.4  509.10  5066.5  508.55  5086.5  510.08
  5116.5  510.48  5136.5  509.72  5145.7  510.81  5166.5  511.42  5200.9  510.70
  5269.8  511.98  5346.6  514.11  5374.4  514.20  5426.7  515.16  5502.6  518.51
#Mann=7,-1,0
  4692.0    0.05       0  4953.5    0.16       0  5003.2    0.07       0
  5009.7    0.16       0  5053.4    0.12       0  5200.9    0.16       0
  5374.4    0.05       0
Bank Sta=4968.4,5269.8
Exp/Cntr=0.3,0.1

Type RM Length L Ch R = 1,15113,728,728,728
BEGIN DESCRIPTION:
UNT 070 in LFCCL Watershed 18.0
END DESCRIPTION:
XS GIS Cut Line= 3
      2801424.97      7088524.96      2800975.00      7088025.00
      2800525.00      7087975.00
#Sta/Elev= 30
  4326.8  520.19  4440.0  514.73  4468.4  515.72  4560.3  512.21  4659.7  511.06
  4665.7  509.62  4673.6  510.50  4680.7  509.33  4692.5  510.33  4709.1  508.87
  4765.9  508.42  4774.1  506.97  4794.3  509.87  4822.7  510.91  4851.1  509.40
  4925.4  508.53  4985.6  506.49  4992.3  505.49  4996.1  499.68  5006.2  499.43
  5006.7  498.63  5012.7  499.43  5019.6  504.09  5029.6  507.01  5053.4  509.62
  5079.9  511.75  5287.9  517.71  5401.9  520.67  5432.1  523.52  5452.2  523.97
#Mann=8,-1,0
  4326.8    0.05       0  4673.6    0.16       0  4692.5    0.05       0
  4774.1    0.12       0  4925.4    0.16       0  5006.2    0.07       0
  5012.7    0.16       0  5287.9    0.05       0
Bank Sta=4665.7,5053.4
Exp/Cntr=0.3,0.1

Type RM Length L Ch R = 1,14385,468,468,468
BEGIN DESCRIPTION:
UNT 070 in LFCCL Watershed 17.0
END DESCRIPTION:
XS GIS Cut Line= 3
      2801488.89      7087876.51      2801075.00      7087575.00
      2800625.03      7087525.00
#Sta/Elev= 30
  4474.0  513.86  4528.3  510.54  4621.0  508.94  4642.1  507.66  4656.5  507.09
  4664.4  505.59  4685.9  506.36  4692.1  503.02  4700.6  505.33  4713.9  502.43
  4718.1  502.94  4727.6  503.13  4742.3  506.25  4792.5  506.32  4828.1  508.98
  4928.5  505.68  4978.7  505.26  4983.0  502.41  4988.6  502.41  4992.8  497.65
  4993.3  496.85  4999.5  497.65  5016.2  505.99  5041.5  507.66  5076.6  513.27
  5126.9  516.93  5217.5  519.32  5237.6  521.40  5348.4  523.98  5438.8  525.67
#Mann=5,-1,0
  4474.0    0.16       0  4718.1    0.12       0  4992.8    0.07       0
  4999.5    0.12       0  5348.4    0.05       0
Bank Sta=4642.1,5041.5
Exp/Cntr=0.3,0.1

Type RM Length L Ch R = 1,13917,277,277,277
BEGIN DESCRIPTION:
UNT 070 in LFCCL Watershed 16.0
END DESCRIPTION:
XS GIS Cut Line= 3
      2801727.60      7087477.20      2801345.64      7087286.22
      2800878.48      7087286.22
#Sta/Elev= 30
  4513.5  511.53  4553.7  509.20  4592.9  509.60  4605.8  508.23  4630.8  507.18
  4639.6  507.08  4732.6  506.06  4749.4  507.68  4755.0  506.53  4784.2  505.03
  4807.1  504.64  4829.5  502.52  4838.8  502.35  4844.4  503.00  4883.6  502.55
  4928.3  505.70  4933.9  505.11  4961.2  505.02  4971.2  503.99  4997.8  496.69
  4998.3  495.89  5004.0  495.89  5004.5  496.69  5021.2  506.12  5075.5  506.25
  5106.4  507.08  5151.2  509.69  5211.2  514.74  5261.2  517.32  5407.7  521.15
#Mann=6,-1,0
  4513.5    0.16       0  4630.8    0.05       0  4784.2    0.12       0
  4997.8    0.07       0  5004.5    0.12       0  5075.5    0.16       0
Bank Sta=4639.6,5106.4
Exp/Cntr=0.3,0.1

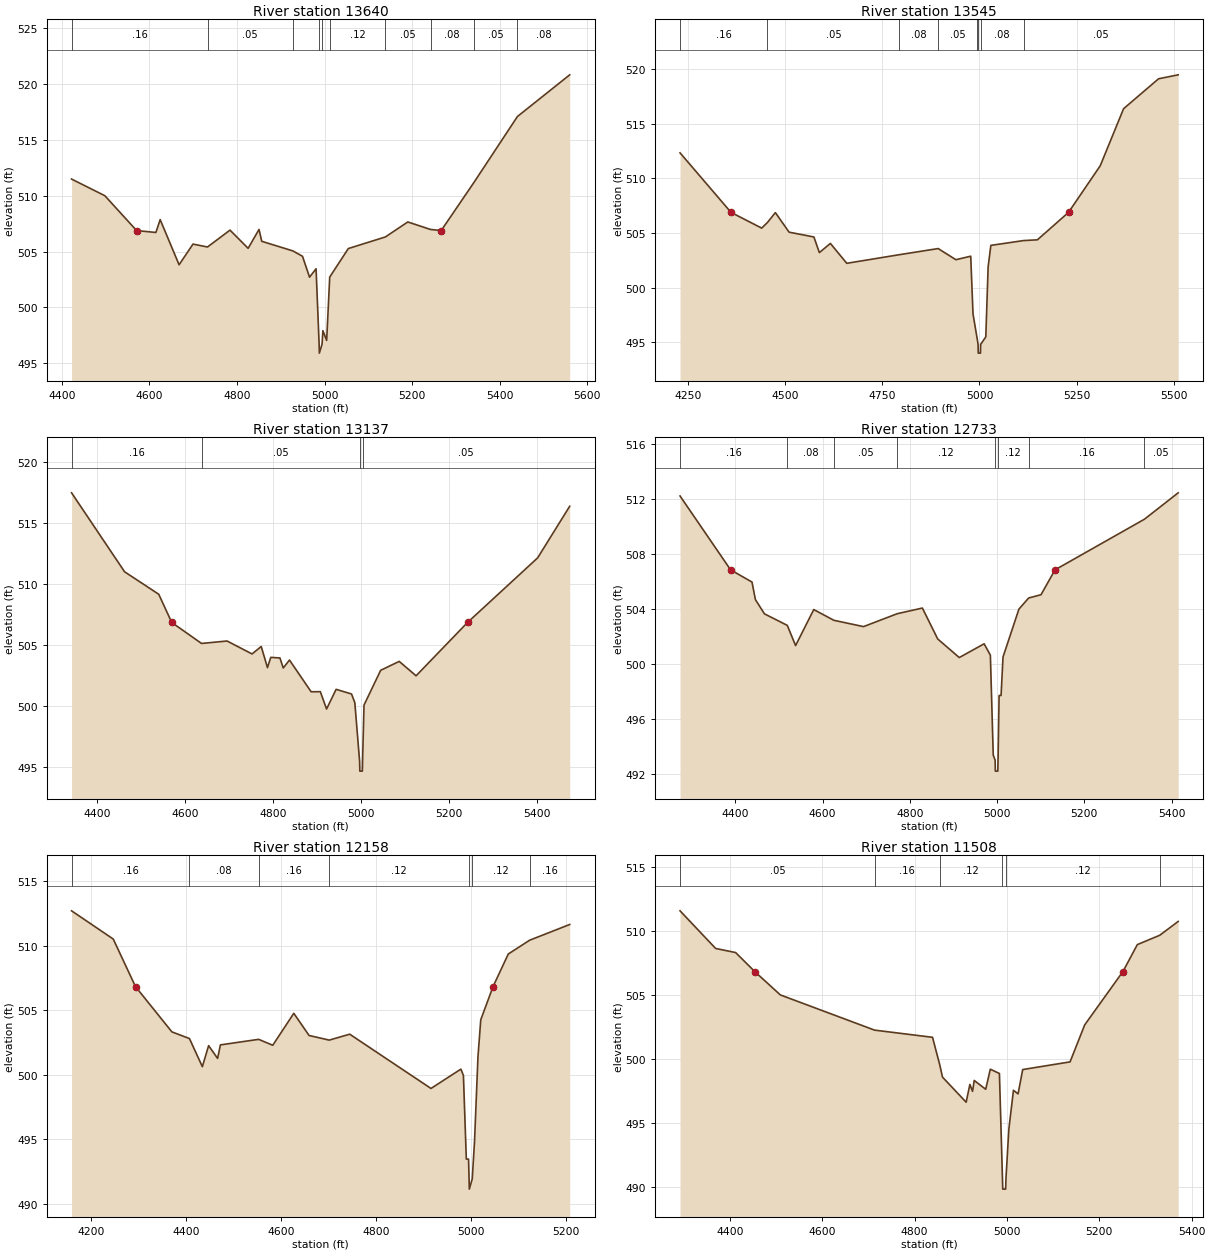
Type RM Length L Ch R = 1,13640,95,95,95
BEGIN DESCRIPTION:
XS3505A
END DESCRIPTION:
XS GIS Cut Line= 5
      2801996.73      7087238.49      2801662.48      7087121.29
      2801449.81      7087177.72      2801267.52      7087247.16
      2800899.32      7087264.49
#Sta/Elev= 30
  4422.2  511.49  4498.2  510.00  4570.8  506.88  4614.8  506.71  4624.6  507.86
  4667.8  503.82  4699.6  505.67  4732.7  505.41  4784.1  506.92  4825.5  505.29
  4850.4  506.98  4856.6  505.92  4927.7  505.06  4949.7  504.58  4965.8  502.71
  4980.7  503.46  4987.7  496.71  4988.2  495.91  4994.4  496.71  4996.3  497.92
  5004.9  497.05  5011.9  502.72  5054.4  505.27  5139.1  506.31  5190.2  507.65
  5242.1  506.98  5266.5  506.88  5341.4  511.19  5440.7  517.09  5560.1  520.82
#Mann=10,-1,0
  4422.2    0.16       0  4732.7    0.05       0  4927.7    0.08       0
  4987.7    0.07       0  4994.4    0.08       0  5011.9    0.12       0
  5139.1    0.05       0  5242.1    0.08       0  5341.4    0.05       0
  5440.7    0.08       0
Bank Sta=4570.8,5266.5
Exp/Cntr=0.3,0.1

Type RM Length L Ch R = 1,13545,408,408,408
BEGIN DESCRIPTION:
XS3506A
END DESCRIPTION:
XS GIS Cut Line= 5
      2802035.77      7087221.14      2801731.93      7086925.98
      2801410.75      7087095.25      2801258.84      7087147.33
      2800924.64      7087160.35
#Sta/Elev= 30
  4229.6  512.34  4360.8  506.89  4439.7  505.45  4454.6  505.97  4474.9  506.87
  4510.2  505.08  4574.0  504.64  4588.1  503.21  4616.4  504.05  4658.6  502.23
  4794.1  503.02  4893.8  503.58  4939.3  502.56  4977.5  502.88  4983.4  497.60
  4994.8  495.18  4996.4  494.81  4996.9  494.01  5002.6  494.01  5003.1  494.81
  5016.3  495.50  5022.3  501.90  5029.3  503.87  5113.4  504.31  5149.1  504.38
  5229.1  506.89  5310.8  511.16  5370.8  516.38  5460.9  519.12  5511.3  519.48
#Mann=8,-1,0
  4229.6    0.16       0  4454.6    0.05       0  4794.1    0.08       0
  4893.8    0.05       0  4994.8    0.08       0  4996.4    0.07       0
  5003.1    0.08       0  5113.4    0.05       0
Bank Sta=4360.8,5229.1
Exp/Cntr=0.3,0.1

Type RM Length L Ch R = 1,13137,404,404,404
BEGIN DESCRIPTION:
UNT 070 in LFCCL Watershed 15.0
END DESCRIPTION:
XS GIS Cut Line= 3
      2802124.98      7087274.97      2801675.00      7086775.00
      2801225.02      7086675.00
#Sta/Elev= 30
  4341.6  517.49  4462.3  511.02  4540.0  509.18  4569.5  506.87  4637.4  505.15
  4695.5  505.35  4752.3  504.29  4773.2  504.90  4787.4  503.17  4794.9  504.01
  4815.8  503.96  4823.3  503.14  4837.5  503.79  4886.8  501.19  4907.7  501.20
  4921.9  499.78  4943.6  501.39  4978.7  501.01  4986.2  500.30  4997.1  495.49
  4997.6  494.69  5003.3  494.69  5003.8  495.49  5007.1  500.10  5045.0  502.95
  5087.2  503.68  5125.6  502.50  5242.7  506.87  5402.2  512.16  5475.2  516.39
#Mann=4,-1,0
  4341.6    0.16       0  4637.4    0.05       0  4997.1    0.03       0
  5003.8    0.05       0
Bank Sta=4569.5,5242.7
Exp/Cntr=0.3,0.1

Type RM Length L Ch R = 1,12733,575,575,575
BEGIN DESCRIPTION:
XS3507A
END DESCRIPTION:
XS GIS Cut Line= 3
      2802296.17      7086986.75      2801818.73      7086431.19
      2801415.08      7086361.74
#Sta/Elev= 30
  4273.2  512.23  4389.1  506.86  4438.2  505.97  4445.9  504.70  4466.7  503.66
  4519.1  502.82  4538.1  501.35  4579.8  503.97  4625.8  503.19  4693.9  502.73
  4771.3  503.67  4828.8  504.08  4864.0  501.83  4913.4  500.48  4970.4  501.48
  4984.7  500.65  4991.3  493.38  4995.6  493.02  4996.1  492.22  5001.8  492.22
  5002.3  493.02  5004.7  497.72  5009.2  497.72  5013.7  500.52  5050.1  504.00
  5072.4  504.81  5100.8  505.05  5133.0  506.86  5337.9  510.54  5415.3  512.46
#Mann=8,-1,0
  4273.2    0.16       0  4519.1    0.08       0  4625.8    0.05       0
  4771.3    0.12       0  4995.6    0.07       0  5002.3    0.12       0
  5072.4    0.16       0  5337.9    0.05       0
Bank Sta=4389.1,5133
Exp/Cntr=0.3,0.1

Type RM Length L Ch R = 1,12158,650,650,650
BEGIN DESCRIPTION:
XS3508A
END DESCRIPTION:
XS GIS Cut Line= 3
      2802330.87      7086982.36      2802035.75      7086201.15
      2801854.80      7086089.14
#Sta/Elev= 30
  4159.9  512.71  4247.6  510.52  4294.4  506.83  4370.9  503.32  4407.9  502.80
  4435.0  500.62  4448.2  502.25  4467.1  501.26  4473.0  502.31  4553.5  502.74
  4583.1  502.28  4627.4  504.76  4659.5  503.04  4701.9  502.68  4745.0  503.14
  4916.0  498.93  4978.9  500.43  4984.2  499.94  4990.3  493.45  4995.0  493.45
  4996.1  491.92  4996.6  491.12  5002.8  491.92  5007.6  494.85  5014.8  501.39
  5020.7  504.26  5046.5  506.83  5078.6  509.36  5123.5  510.43  5207.8  511.65
#Mann=7,-1,0
  4159.9    0.16       0  4407.9    0.08       0  4553.5    0.16       0
  4701.9    0.12       0  4996.1    0.07       0  5002.8    0.12       0
  5123.5    0.16       0
Bank Sta=4294.4,5046.5
Exp/Cntr=0.3,0.1

Type RM Length L Ch R = 1,11508,290,290,290
BEGIN DESCRIPTION:
XS3509A
END DESCRIPTION:
XS GIS Cut Line= 4
      2802895.16      7086478.95      2802339.57      7086166.43
      2802196.34      7086175.11      2801909.92      7086092.66
#Sta/Elev= 30
  4291.9  511.54  4369.0  508.60  4412.3  508.28  4453.6  506.80  4509.2  504.97
  4713.3  502.22  4838.8  501.66  4854.3  499.53  4860.4  498.55  4911.6  496.59
  4919.7  497.98  4925.5  497.44  4929.1  498.29  4954.0  497.60  4964.0  499.17
  4983.7  498.83  4990.3  490.60  4990.9  489.80  4997.2  489.80  4997.8  490.60
  5004.1  494.48  5014.1  497.52  5024.1  497.24  5034.1  499.14  5136.7  499.74
  5168.4  502.63  5251.3  506.80  5282.4  508.90  5330.9  509.63  5370.9  510.71
#Mann=6,-1,0
  4291.9    0.05       0  4713.3    0.16       0  4854.3    0.12       0
  4990.3    0.07       0  4997.8    0.12       0  5330.9    0.16       0
Bank Sta=4453.6,5251.3
Exp/Cntr=0.3,0.1

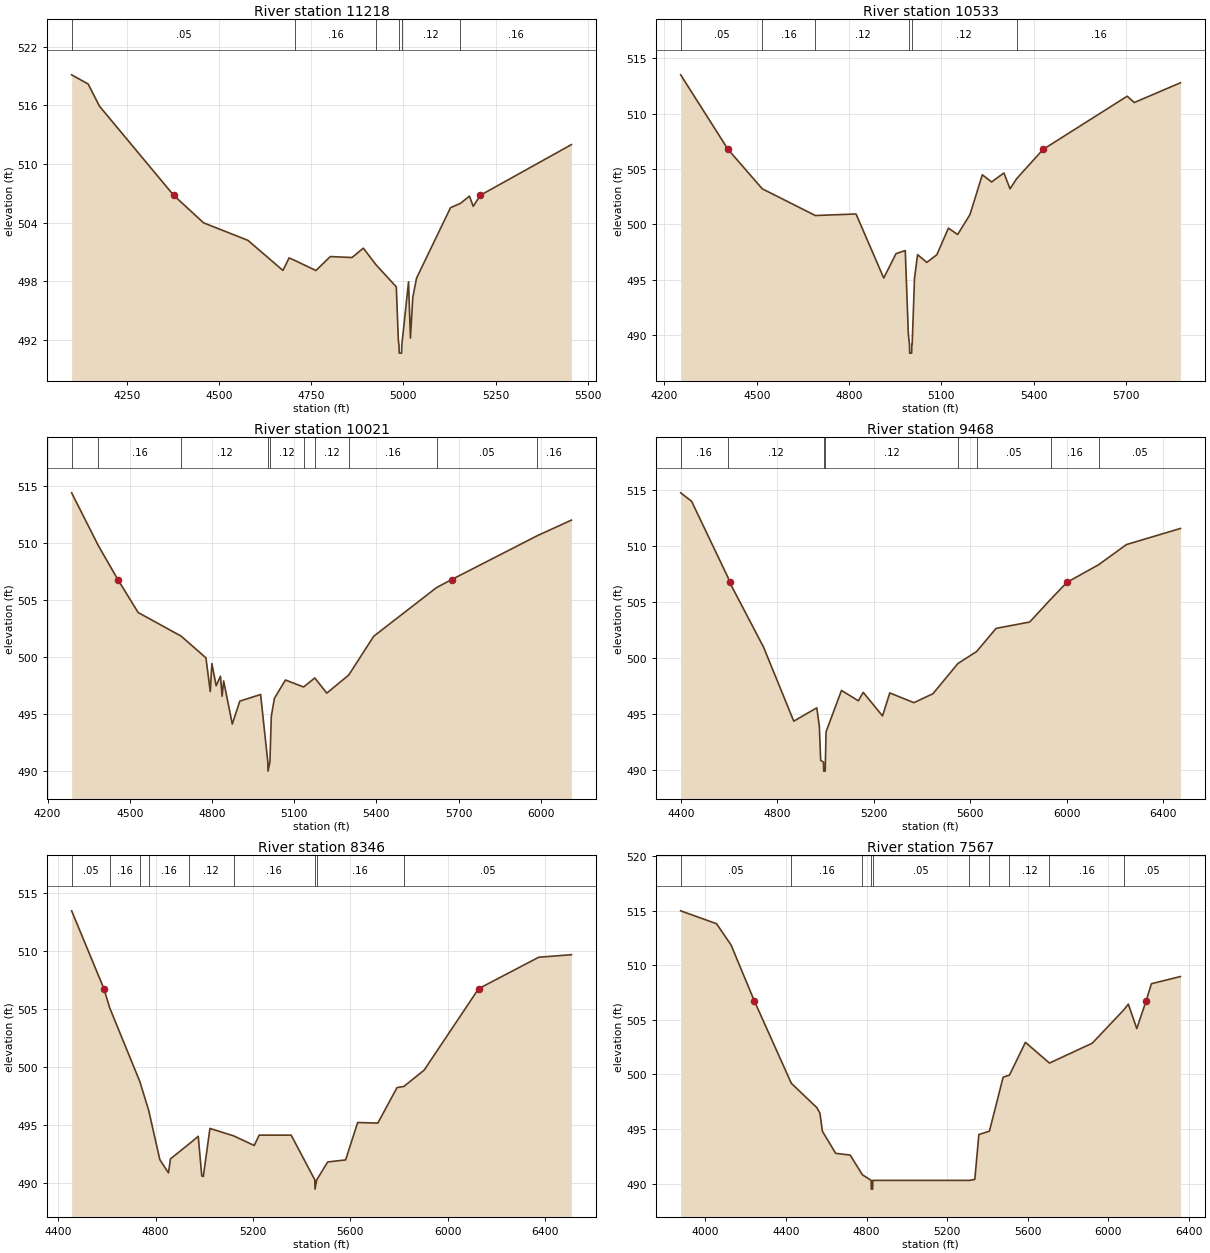
Type RM Length L Ch R = 1,11218,685,685,685
BEGIN DESCRIPTION:
UNT 070 in LFCCL Watershed 13.0
END DESCRIPTION:
XS GIS Cut Line= 3
      2803075.04      7086325.02      2802275.00      7085925.00
      2801825.04      7086024.99
#Sta/Elev= 30
  4100.3  519.11  4145.1  518.17  4175.8  515.90  4376.9  506.79  4458.1  503.97
  4578.3  502.18  4673.3  499.10  4690.1  500.38  4706.3  500.11  4762.8  499.09
  4801.9  500.52  4860.6  500.42  4891.4  501.38  4925.7  499.68  4980.8  497.42
  4986.4  491.92  4988.2  491.44  4988.8  490.64  4995.1  490.64  4995.7  491.44
  5014.0  497.94  5019.1  492.18  5025.5  496.33  5035.7  498.31  5127.9  505.52
  5154.7  505.96  5179.2  506.70  5189.4  505.66  5208.8  506.79  5455.7  511.97
#Mann=6,-1,0
  4100.3    0.05       0  4706.3    0.16       0  4925.7    0.12       0
  4988.2    0.07       0  4995.7    0.12       0  5154.7    0.16       0
Bank Sta=4376.9,5208.8
Exp/Cntr=0.3,0.1

Type RM Length L Ch R = 1,10533,512,512,512
BEGIN DESCRIPTION:
UNT 070 in LFCCL Watershed 12.0
END DESCRIPTION:
XS GIS Cut Line= 3
      2803225.01      7085525.00      2802475.00      7085525.00
      2801602.31      7085470.53
#Sta/Elev= 30
  4252.9  513.50  4406.8  506.77  4518.2  503.21  4690.7  500.80  4822.9  500.94
  4912.9  495.16  4952.9  497.36  4982.9  497.64  4992.9  490.11  4996.6  489.18
  4997.2  488.38  5003.7  488.38  5004.3  489.18  5005.4  489.18  5012.9  495.12
  5023.0  497.27  5053.0  496.57  5085.6  497.26  5123.1  499.66  5153.2  499.09
  5193.3  500.89  5233.4  504.48  5263.4  503.83  5303.5  504.64  5323.5  503.21
  5345.0  504.13  5431.0  506.77  5704.3  511.57  5727.3  511.00  5877.3  512.78
#Mann=6,-1,0
  4252.9    0.05       0  4518.2    0.16       0  4690.7    0.12       0
  4996.6    0.07       0  5004.3    0.12       0  5345.0    0.16       0
Bank Sta=4406.8,5431
Exp/Cntr=0.3,0.1

Type RM Length L Ch R = 1,10021,553,553,553
BEGIN DESCRIPTION:
UNT 070 in LFCCL Watershed 11.0
END DESCRIPTION:
XS GIS Cut Line= 3
      2803275.04      7085475.02      2802699.81      7085142.13
      2801548.47      7085276.76
#Sta/Elev= 30
  4288.1  514.36  4385.4  509.74  4456.9  506.76  4530.8  503.88  4687.8  501.81
  4778.2  499.91  4794.0  496.96  4799.8  499.41  4815.5  497.47  4831.2  498.30
  4837.1  496.55  4842.8  497.89  4874.4  494.11  4901.7  496.12  4977.7  496.70
  5004.0  490.79  5004.6  489.99  5011.7  490.79  5016.7  494.79  5028.0  496.36
  5068.3  497.97  5134.6  497.36  5175.5  498.15  5219.3  496.82  5299.5  498.41
  5390.5  501.80  5619.6  506.06  5674.5  506.76  5987.1  510.60  6111.9  511.97
#Mann=10,-1,0
  4288.1    0.05       0  4385.4    0.16       0  4687.8    0.12       0
  5004.0    0.07       0  5011.7    0.12       0  5134.6    0.16       0
  5175.5    0.12       0  5299.5    0.16       0  5619.6    0.05       0
  5987.1    0.16       0
Bank Sta=4456.9,5674.5
Exp/Cntr=0.3,0.1

Type RM Length L Ch R = 1,9468,1122,1122,1122
BEGIN DESCRIPTION:
XS3512A
END DESCRIPTION:
XS GIS Cut Line= 3
      2803356.89      7085053.57      2802787.48      7084852.19
      2801321.78      7084779.07
#Sta/Elev= 30
  4399.0  514.75  4444.2  514.00  4595.4  507.18  4601.9  506.76  4742.7  500.97
  4867.7  494.37  4963.2  495.56  4973.8  493.91  4979.3  490.87  4991.1  490.71
  4991.7  489.91  4998.2  489.91  4998.8  490.71  5001.6  493.42  5065.5  497.11
  5135.6  496.19  5155.6  496.94  5235.7  494.84  5265.8  496.89  5365.9  496.02
  5444.7  496.82  5548.4  499.52  5625.5  500.58  5706.3  502.65  5845.7  503.22
  5932.0  505.23  6000.0  506.76  6131.1  508.33  6246.6  510.13  6470.5  511.57
#Mann=8,-1,0
  4399.0    0.16       0  4595.4    0.12       0  4991.1    0.07       0
  4998.8    0.12       0  5548.4    0.16       0  5625.5    0.05       0
  5932.0    0.16       0  6131.1    0.05       0
Bank Sta=4601.9,6000
Exp/Cntr=0.3,0.1

Type RM Length L Ch R = 1,8346,779,779,779
BEGIN DESCRIPTION:
XS3515A
END DESCRIPTION:
XS GIS Cut Line= 3
      2803488.85      7084470.24      2803058.32      7084136.92
      2801566.79      7083909.82
#Sta/Elev= 30
  4455.4  513.47  4588.0  506.76  4611.9  505.10  4735.0  498.79  4771.8  496.28
  4817.9  492.02  4853.2  490.89  4861.4  492.10  4937.7  493.38  4975.5  494.04
  4990.0  490.63  4996.3  490.58  5023.5  494.72  5120.8  494.08  5205.5  493.25
  5225.8  494.14  5357.3  494.14  5454.5  490.29  5455.2  489.49  5462.3  490.29
  5507.4  491.83  5581.1  492.01  5630.4  495.23  5713.3  495.18  5792.2  498.24
  5820.5  498.34  5903.5  499.74  6127.4  506.76  6374.2  509.47  6508.6  509.69
#Mann=9,-1,0
  4455.4    0.05       0  4611.9    0.16       0  4735.0    0.12       0
  4771.8    0.16       0  4937.7    0.12       0  5120.8    0.16       0
  5454.5    0.07       0  5462.3    0.16       0  5820.5    0.05       0
Bank Sta=4588,6127.4
Exp/Cntr=0.3,0.1

Type RM Length L Ch R = 1,7567,719,719,719
BEGIN DESCRIPTION:
XS3514A
END DESCRIPTION:
XS GIS Cut Line= 3
      2803838.68      7084198.23      2802940.26      7083595.25
      2801549.42      7083466.49
#Sta/Elev= 30
  3878.3  514.99  4056.0  513.81  4128.0  511.87  4243.1  506.76  4427.1  499.19
  4554.1  496.95  4569.1  496.45  4581.3  494.79  4647.1  492.77  4719.1  492.61
  4779.5  490.81  4823.1  490.29  4823.8  489.49  4830.5  489.49  4831.2  490.29
  5310.4  490.29  5337.2  490.38  5357.3  494.49  5409.7  494.80  5477.8  499.75
  5509.0  499.93  5588.2  502.94  5707.5  501.04  5919.7  502.86  6076.0  505.91
  6098.7  506.44  6140.6  504.20  6187.2  506.76  6213.2  508.31  6357.1  508.97
#Mann=10,-1,0
  3878.3    0.05       0  4427.1    0.16       0  4779.5    0.05       0
  4823.1   0.033       0  4831.2    0.05       0  5310.4    0.16       0
  5409.7    0.05       0  5509.0    0.12       0  5707.5    0.16       0
  6076.0    0.05       0
Bank Sta=4243.1,6187.2
Exp/Cntr=0.3,0.1