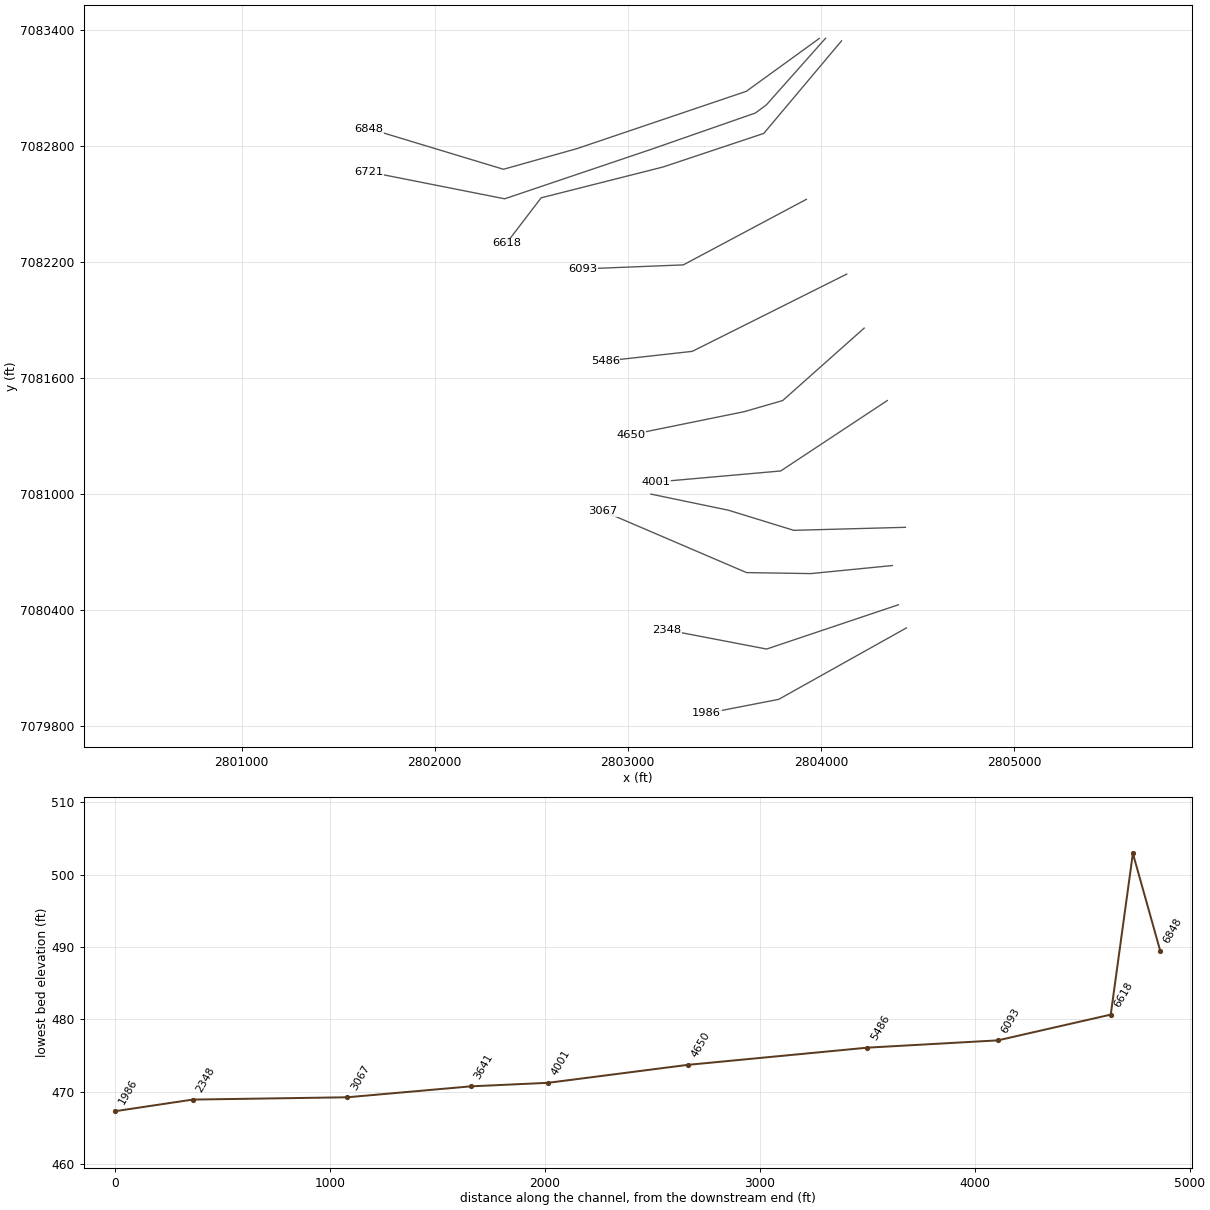
HEC-RAS study UNT 070 in LFCCL Watershed.prj: UNT 070 in LFCCL Watershed Base Level Engineering

--- UNT 070 in LFCCL Watershed.g01 (geometry) --- (continued)

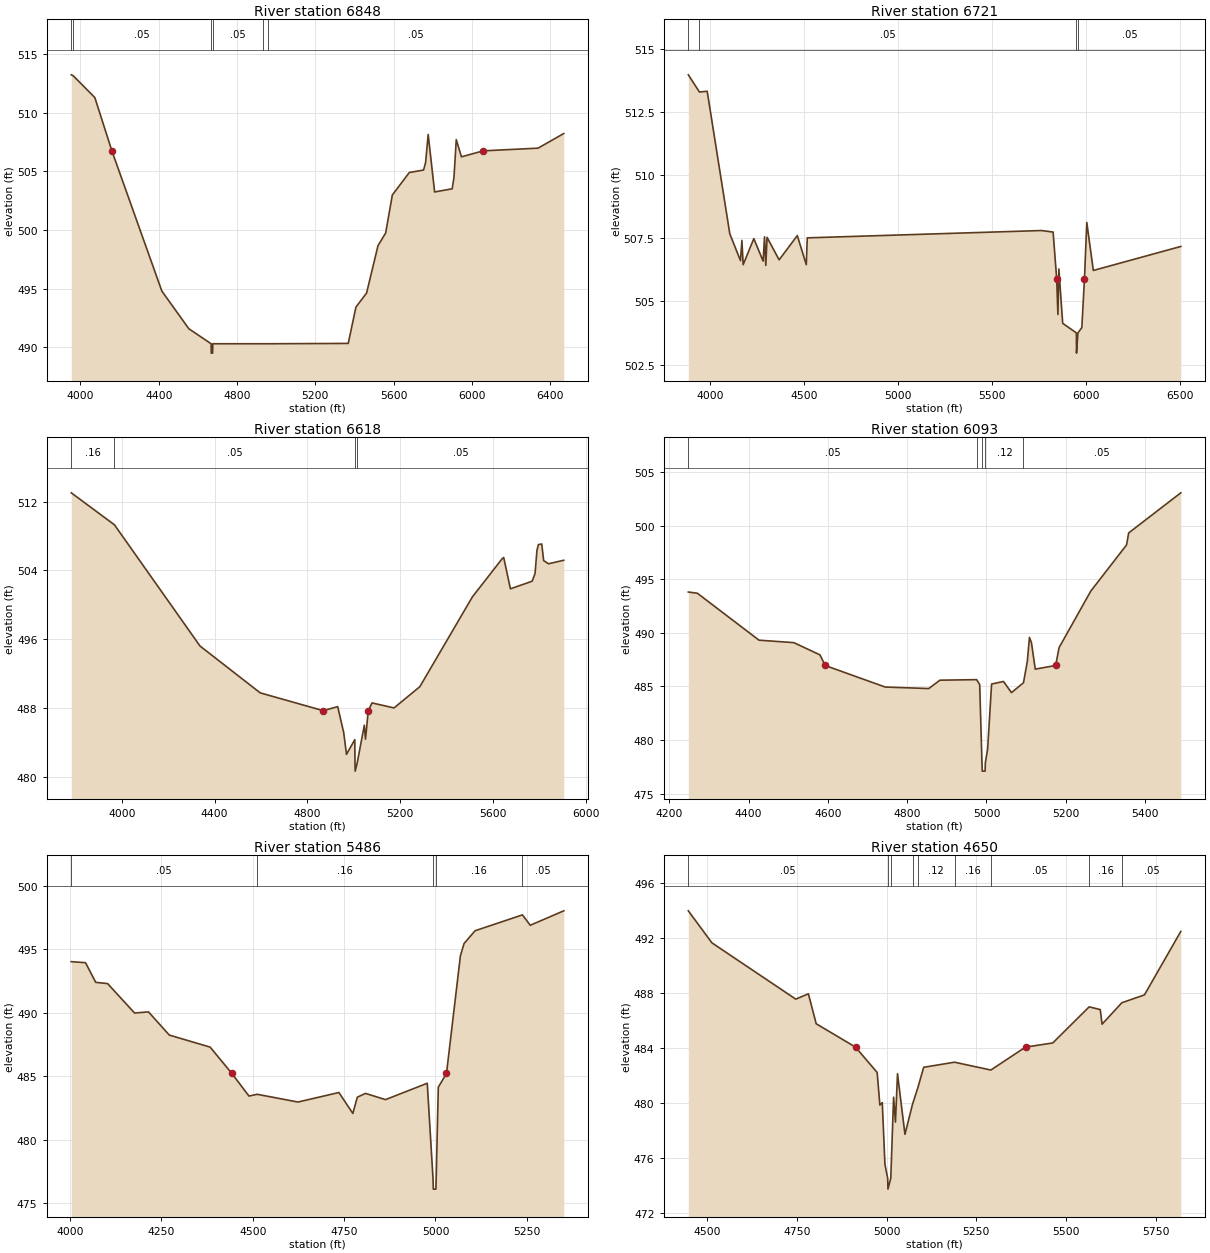
Type RM Length L Ch R = 1,6848,127,127,127
BEGIN DESCRIPTION:
Mapping XS 8d6a08b8
END DESCRIPTION:
XS GIS Cut Line= 5
      2803991.58      7083357.59      2803613.97      7083084.15
      2802736.37      7082787.28      2802356.16      7082680.50
      2801659.52      7082891.22
#Sta/Elev= 30
  3953.6  513.25  3963.5  513.17  4073.9  511.31  4160.9  506.76  4416.1  494.79
  4554.1  491.57  4667.9  490.29  4668.6  489.49  4675.5  489.49  4676.3  490.29
  4934.3  490.29  4959.9  490.29  5368.2  490.32  5407.5  493.42  5461.9  494.62
  5520.1  498.66  5559.4  499.75  5593.4  502.99  5680.1  504.91  5752.8  505.12
  5763.3  505.76  5776.5  508.16  5809.4  503.25  5899.1  503.52  5908.2  504.49
  5920.0  507.72  5946.4  506.25  6057.7  506.76  6337.9  506.99  6469.0  508.24
#Mann=6,-1,0
  3953.6    0.16       0  3963.5    0.05       0  4667.9   0.033       0
  4676.3    0.05       0  4934.3    0.07       0  4959.9    0.05       0
Bank Sta=4160.9,6057.7
Exp/Cntr=0.3,0.1

Type RM Length L Ch R = 1,6721,103,103,103
BEGIN DESCRIPTION:
Mapping XS d778bcac
END DESCRIPTION:
XS GIS Cut Line= 6
      2804023.85      7083358.34      2803717.27      7083013.49
      2803661.02      7082971.82      2803118.74      7082782.94
      2802362.41      7082527.62      2801658.23      7082667.05
#Sta/Elev= 30
  3882.0  513.96  3941.3  513.28  3982.5  513.31  4102.9  507.67  4159.7  506.61
  4167.3  507.41  4174.0  506.45  4230.8  507.48  4280.2  506.59  4287.7  507.55
  4294.4  506.42  4301.3  507.53  4365.5  506.64  4462.2  507.60  4510.0  506.45
  4515.3  507.51  5762.0  507.80  5824.1  507.74  5843.1  505.89  5849.6  504.48
  5854.7  506.28  5875.1  504.13  5947.9  503.75  5948.6  502.95  5956.3  503.75
  5977.0  503.96  5991.0  505.89  6003.3  508.12  6038.2  506.22  6503.8  507.17
#Mann=4,-1,0
  3882.0    0.16       0  3941.3    0.05       0  5947.9    0.03       0
  5956.3    0.05       0
Bank Sta=5843.1,5991
Exp/Cntr=0.3,0.1

Type RM Length L Ch R = 1,6618,525,525,525
BEGIN DESCRIPTION:
XS3516A
END DESCRIPTION:
XS GIS Cut Line= 5
      2804106.91      7083345.23      2803704.15      7082866.08
      2803183.32      7082692.47      2802551.37      7082532.75
      2802370.82      7082296.64
#Sta/Elev= 30
  3782.2  513.02  3968.4  509.30  4337.3  495.21  4597.0  489.76  4868.8  487.69
  4931.2  488.16  4957.1  485.14  4969.1  482.61  5004.9  484.32  5005.9  481.46
  5006.6  480.66  5014.3  481.46  5046.0  486.00  5051.1  484.38  5063.1  487.69
  5079.2  488.59  5174.2  488.01  5285.5  490.48  5512.4  500.93  5640.9  505.37
  5647.2  505.50  5676.2  501.86  5769.7  502.74  5782.4  503.64  5790.5  506.32
  5796.8  507.00  5811.3  507.07  5819.5  505.14  5840.4  504.77  5906.2  505.18
#Mann=4,-1,0
  3782.2    0.16       0  3968.4    0.05       0  5005.9    0.03       0
  5014.3    0.05       0
Bank Sta=4868.8,5063.1
Exp/Cntr=0.3,0.1

Type RM Length L Ch R = 1,6093,607,607,607
BEGIN DESCRIPTION:
UNT 070 in LFCCL Watershed 4.0
END DESCRIPTION:
XS GIS Cut Line= 3
      2803925.04      7082525.02      2803287.48      7082185.53
      2802768.31      7082164.76
#Sta/Elev= 30
  4248.2  493.80  4270.9  493.69  4426.5  489.31  4514.3  489.08  4580.2  487.94
  4593.3  486.95  4744.7  484.94  4854.5  484.80  4882.7  485.58  4975.3  485.63
  4983.0  485.17  4988.7  477.90  4989.5  477.10  4996.6  477.10  4997.3  477.90
  5003.0  479.15  5013.0  485.22  5043.0  485.46  5063.1  484.42  5093.4  485.34
  5103.1  487.34  5108.5  489.57  5113.5  489.08  5123.1  486.61  5174.5  486.95
  5183.2  488.62  5263.2  493.89  5353.3  498.19  5358.7  499.31  5490.1  503.05
#Mann=5,-1,0
  4248.2    0.05       0  4975.3    0.12       0  4988.7    0.07       0
  4997.3    0.12       0  5093.4    0.05       0
Bank Sta=4593.3,5174.5
Exp/Cntr=0.3,0.1

Type RM Length L Ch R = 1,5486,836,836,836
BEGIN DESCRIPTION:
UNT 070 in LFCCL Watershed 3.0
END DESCRIPTION:
XS GIS Cut Line= 3
      2804133.89      7082137.87      2803333.85      7081737.85
      2802883.89      7081687.85
#Sta/Elev= 30
  4003.7  494.03  4042.6  493.95  4070.6  492.40  4103.1  492.30  4176.8  489.98
  4214.9  490.07  4271.8  488.24  4383.6  487.29  4443.1  485.21  4489.8  483.43
  4512.2  483.57  4624.0  482.96  4735.8  483.71  4773.9  482.06  4786.1  483.34
  4808.5  483.64  4863.3  483.15  4977.5  484.44  4993.3  476.89  4994.1  476.09
  5001.2  476.09  5001.9  476.89  5007.7  484.13  5030.1  485.21  5068.1  494.48
  5078.1  495.46  5108.3  496.47  5237.9  497.72  5259.2  496.90  5350.9  498.04
#Mann=5,-1,0
  4003.7    0.05       0  4512.2    0.16       0  4993.3    0.07       0
  5001.9    0.16       0  5237.9    0.05       0
Bank Sta=4443.1,5030.1
Exp/Cntr=0.3,0.1

Type RM Length L Ch R = 1,4650,649,649,649
BEGIN DESCRIPTION:
XS3519A
END DESCRIPTION:
XS GIS Cut Line= 4
      2804224.12      7081858.28      2803802.24      7081483.27
      2803604.32      7081425.98      2803015.79      7081306.19
#Sta/Elev= 30
  4448.2  493.97  4513.9  491.64  4747.4  487.54  4782.5  487.93  4804.2  485.75
  4913.7  484.05  4974.0  482.20  4981.5  479.83  4988.2  480.01  4995.6  475.52
  5003.2  474.51  5004.0  473.71  5011.9  474.51  5019.7  480.40  5024.9  478.59
  5030.6  482.11  5051.4  477.70  5072.4  479.89  5087.0  481.07  5103.5  482.58
  5189.4  482.95  5290.5  482.38  5387.0  484.05  5462.9  484.35  5564.2  486.98
  5595.1  486.78  5600.2  485.72  5655.3  487.28  5718.1  487.85  5819.3  492.47
#Mann=9,-1,0
  4448.2    0.05       0  5003.2    0.03       0  5011.9    0.05       0
  5072.4    0.16       0  5087.0    0.12       0  5189.4    0.16       0
  5290.5    0.05       0  5564.2    0.16       0  5655.3    0.05       0
Bank Sta=4913.7,5387
Exp/Cntr=0.3,0.1

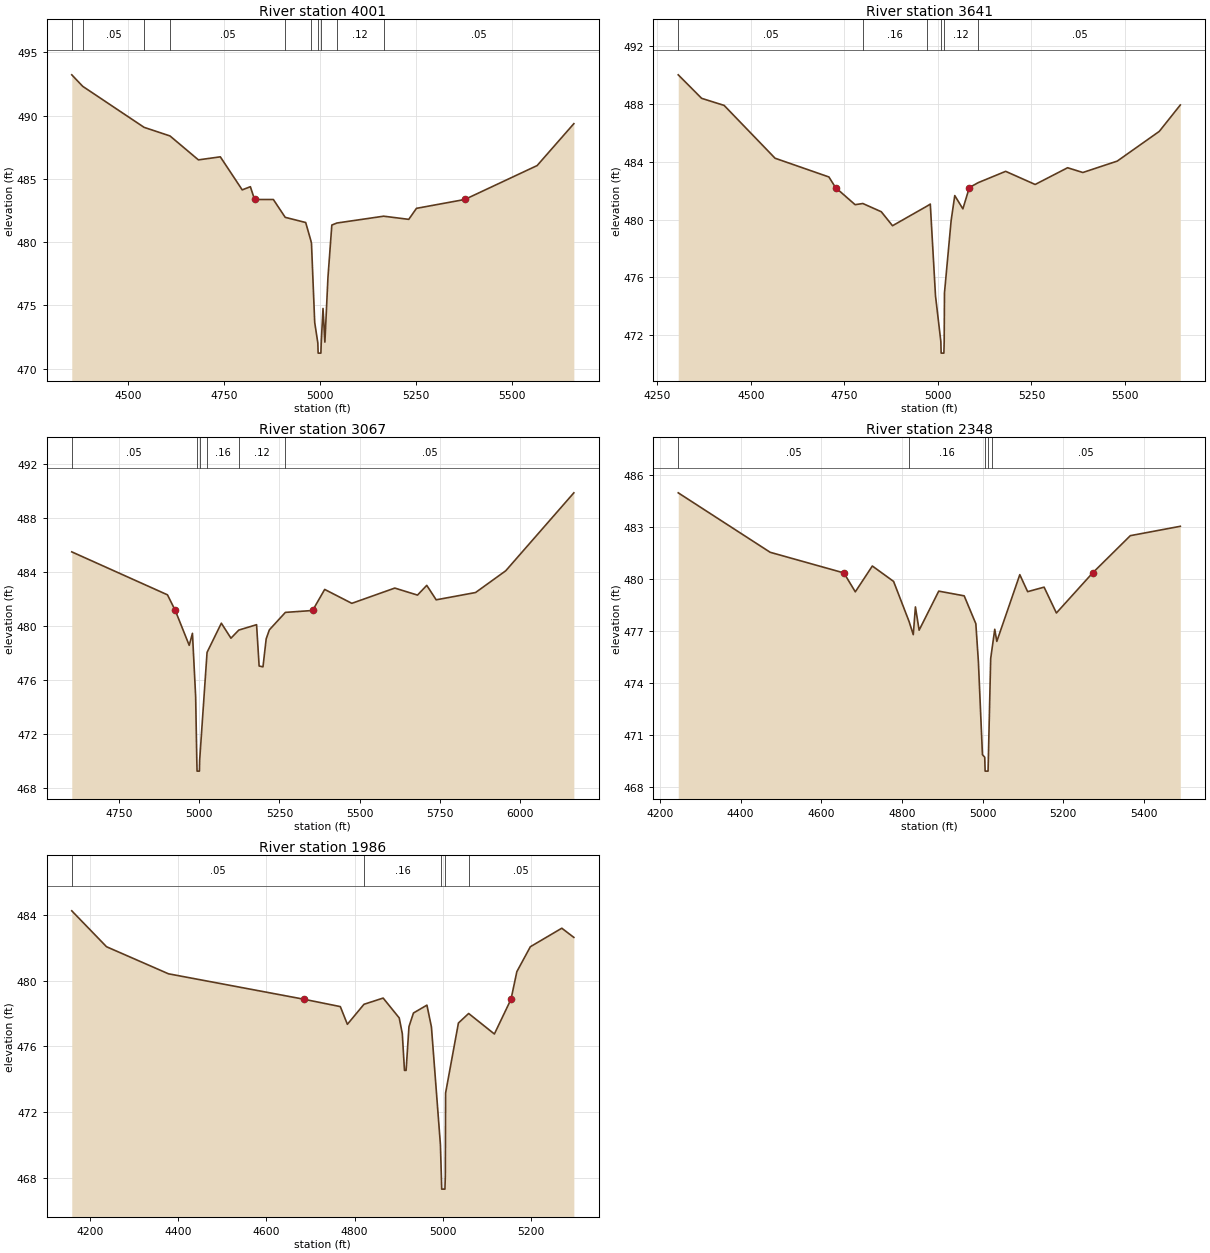
Type RM Length L Ch R = 1,4001,360,360,360
BEGIN DESCRIPTION:
XS3520A
END DESCRIPTION:
XS GIS Cut Line= 3
      2804343.88      7081483.25      2803791.82      7081118.69
      2803146.03      7081061.40
#Sta/Elev= 30
  4352.2  493.22  4380.8  492.31  4540.9  489.07  4608.5  488.39  4682.6  486.50
  4739.8  486.74  4796.9  484.13  4818.2  484.38  4829.1  483.37  4878.1  483.37
  4909.1  481.96  4962.5  481.55  4975.9  480.13  4977.6  479.91  4986.0  473.66
  4994.2  472.03  4995.0  471.23  5002.2  471.23  5003.0  472.03  5007.7  474.76
  5012.6  472.10  5020.6  477.22  5030.7  481.35  5043.8  481.51  5166.0  482.05
  5231.4  481.80  5251.5  482.67  5377.5  483.37  5566.3  486.05  5662.1  489.36
#Mann=10,-1,0
  4352.2    0.16       0  4380.8    0.05       0  4540.9    0.16       0
  4608.5    0.05       0  4909.1    0.12       0  4975.9    0.16       0
  4994.2    0.07       0  5003.0    0.16       0  5043.8    0.12       0
  5166.0    0.05       0
Bank Sta=4829.1,5377.5
Exp/Cntr=0.3,0.1

Type RM Length L Ch R = 1,3641,574,574,574
BEGIN DESCRIPTION:
XS3521A
END DESCRIPTION:
XS GIS Cut Line= 4
      2804437.62      7080827.02      2803859.53      7080811.40
      2803520.99      7080915.56      2803119.96      7080998.89
#Sta/Elev= 30
  4306.0  490.03  4368.6  488.40  4428.7  487.91  4564.8  484.25  4708.8  482.95
  4726.4  482.22  4778.8  481.03  4799.5  481.11  4848.8  480.54  4878.8  479.57
  4971.0  480.93  4979.8  481.07  4993.7  474.71  5008.0  471.54  5008.8  470.74
  5016.1  470.74  5016.9  471.54  5017.7  474.92  5035.5  479.93  5045.2  481.66
  5066.9  480.74  5084.2  482.22  5108.2  482.56  5181.2  483.34  5260.1  482.43
  5346.8  483.59  5387.6  483.26  5479.5  484.05  5591.9  486.11  5648.1  487.94
#Mann=6,-1,0
  4306.0    0.05       0  4799.5    0.16       0  4971.0    0.12       0
  5008.0    0.07       0  5016.9    0.12       0  5108.2    0.05       0
Bank Sta=4726.4,5084.2
Exp/Cntr=0.3,0.1

Type RM Length L Ch R = 1,3067,719,719,719
BEGIN DESCRIPTION:
XS3518A
END DESCRIPTION:
XS GIS Cut Line= 4
      2804369.97      7080629.11      2803948.07      7080587.44
      2803614.74      7080592.65      2802869.93      7080911.72
#Sta/Elev= 30
  4601.5  485.46  4900.3  482.28  4924.7  481.12  4968.2  478.54  4978.3  479.43
  4988.3  474.75  4991.9  470.03  4992.7  469.23  5000.0  469.23  5000.8  470.03
  5023.9  478.02  5068.5  480.18  5098.5  479.07  5123.0  479.67  5178.5  480.07
  5186.5  477.01  5198.5  476.95  5208.5  479.02  5218.5  479.69  5268.5  480.98
  5353.4  481.12  5391.2  482.68  5475.9  481.65  5610.1  482.78  5680.9  482.26
  5709.9  482.98  5739.3  481.91  5862.2  482.45  5956.5  484.06  6169.1  489.83
#Mann=6,-1,0
  4601.5    0.05       0  4991.9    0.03       0  5000.8    0.05       0
  5023.9    0.16       0  5123.0    0.12       0  5268.5    0.05       0
Bank Sta=4924.7,5353.4
Exp/Cntr=0.3,0.1

Type RM Length L Ch R = 1,2348,362,362,362
BEGIN DESCRIPTION:
XS3517A
END DESCRIPTION:
XS GIS Cut Line= 3
      2804401.16      7080425.97      2803718.91      7080196.81
      2803203.32      7080295.76
#Sta/Elev= 30
  4245.4  484.96  4473.4  481.53  4656.1  480.34  4684.4  479.25  4726.6  480.74
  4779.3  479.85  4817.7  477.54  4828.1  476.78  4833.4  478.38  4842.6  477.04
  4891.2  479.29  4954.3  479.02  4983.2  477.41  4989.5  475.24  4999.6  469.86
  5005.3  469.71  5006.2  468.91  5013.5  468.91  5014.3  469.71  5020.0  475.40
  5023.7  476.02  5030.1  477.09  5035.2  476.39  5092.2  480.24  5111.6  479.26
  5152.4  479.52  5182.9  478.03  5272.7  480.34  5366.2  482.49  5490.1  483.03
#Mann=5,-1,0
  4245.4    0.05       0  4817.7    0.16       0  5005.3    0.07       0
  5014.3    0.16       0  5023.7    0.05       0
Bank Sta=4656.1,5272.7
Exp/Cntr=0.3,0.1

Type RM Length L Ch R = 1,1986,0,0,0
BEGIN DESCRIPTION:
UNT 070 in LFCCL Watershed 2.0
END DESCRIPTION:
XS GIS Cut Line= 3
      2804442.83      7080306.17      2803781.41      7079936.40
      2803408.17      7079863.82
#Sta/Elev= 30
  4159.1  484.27  4237.9  482.08  4378.3  480.43  4685.1  478.88  4767.8  478.43
  4783.8  477.35  4821.4  478.57  4864.9  478.95  4901.3  477.74  4908.3  476.78
  4913.2  474.54  4916.9  474.54  4923.4  477.21  4933.6  478.04  4964.1  478.52
  4974.3  477.19  4994.7  470.01  4996.8  468.10  4997.6  467.30  5004.9  467.30
  5005.8  468.10  5006.4  473.16  5035.5  477.43  5058.7  478.01  5117.0  476.76
  5154.7  478.88  5167.9  480.56  5198.5  482.08  5269.8  483.21  5297.1  482.65
#Mann=5,-1,0
  4159.1    0.05       0  4821.4    0.16       0  4996.8    0.07       0
  5005.8    0.16       0  5058.7    0.05       0
Bank Sta=4685.1,5154.7
Exp/Cntr=0.3,0.1

Chan Stop Cuts=-1