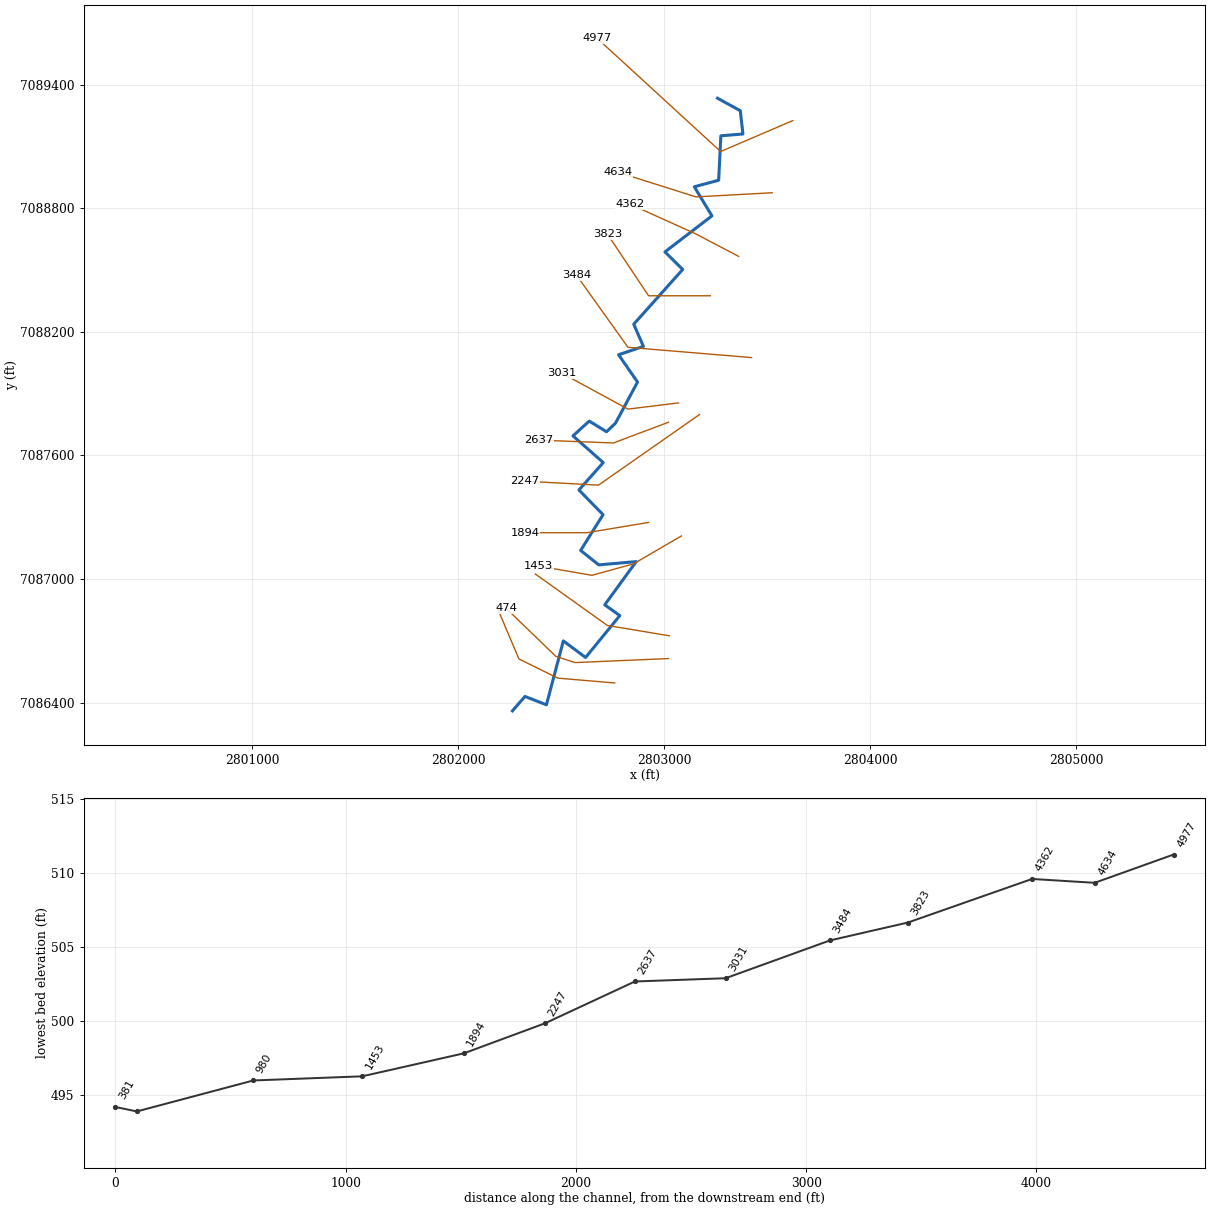
--- UNT 071 in LFCCL Watershed.prj (project) ---

Proj Title=UNT 071 in LFCCL Watershed Base Level Engineering
Current Plan=p01
Default Exp/Contr=0.3,0.1
English Units
Geom File=g01
Flow File=f01
Plan File=p01
BEGIN DESCRIPTION:
UNT 071 in LFCCL Watershed
END DESCRIPTION:

--- UNT 071 in LFCCL Watershed.p01 (plan) ---

Plan Title=Multiple Run
Short Identifier=Multiple
Geom File=g01
Flow File=f01
Subcritical Flow
K Sum by GR= 0
Std Step Tol= 0.01
Critical Tol= 0.01
Num of Std Step Trials= 20
Max Error Tol= 0.3
Flow Tol Ratio= 0.001
Split Flow NTrial= 30
Split Flow Tol= 0.02
Split Flow Ratio= 0.02
Log Output Level= 0
Friction Slope Method= 1
Unsteady Friction Slope Method= 2
Unsteady Bridges Friction Slope Method= 1
Parabolic Critical Depth
Global Vel Dist=  1 , 1 , 1
Global Log Level= 0
CheckData=True
Encroach Param= -1, 0, 0, 0
BEGIN DESCRIPTION:
Multiple Run
END DESCRIPTION:

--- UNT 071 in LFCCL Watershed.f01 (steady flow) ---

Flow Title=Multiple
Number of Profiles=7
Profile Names=10-year,25-year,50-year,1pct_min,100-year,1pct_plu,500-year
River Rch & RM= UNT 071 in LFCCL,Reach-1,4977
     477     620     732     429     855    1706    1165
Boundary for River Rch & Prof#=UNT 071 in LFCCL,Reach-1,1
Up Type=0
Dn Type=3
Dn Slope=0.005
Boundary for River Rch & Prof#=UNT 071 in LFCCL,Reach-1,2
Up Type=0
Dn Type=3
Dn Slope=0.005
Boundary for River Rch & Prof#=UNT 071 in LFCCL,Reach-1,3
Up Type=0
Dn Type=3
Dn Slope=0.005
Boundary for River Rch & Prof#=UNT 071 in LFCCL,Reach-1,4
Up Type=0
Dn Type=3
Dn Slope=0.005
Boundary for River Rch & Prof#=UNT 071 in LFCCL,Reach-1,5
Up Type=0
Dn Type=3
Dn Slope=0.005
Boundary for River Rch & Prof#=UNT 071 in LFCCL,Reach-1,6
Up Type=0
Dn Type=3
Dn Slope=0.005
Boundary for River Rch & Prof#=UNT 071 in LFCCL,Reach-1,7
Up Type=0
Dn Type=3
Dn Slope=0.005

--- UNT 071 in LFCCL Watershed.g01 (geometry) ---

Geom Title=Existing Conditions

River Reach=UNT 071 in LFCCL,Reach-1
Reach XY= 30
      2803259.74      7089333.72      2803370.14      7089273.25
      2803383.21      7089160.16      2803276.00      7089151.35
      2803265.26      7088935.75      2803147.17      7088904.08
      2803232.59      7088762.63      2803004.55      7088587.94
      2803090.73      7088502.64      2802852.97      7088237.04
      2802900.01      7088129.27      2802779.46      7088088.77
      2802871.53      7087956.28      2802764.68      7087757.03
      2802720.72      7087715.03      2802637.17      7087766.88
      2802558.07      7087695.07      2802705.12      7087565.46
      2802587.01      7087432.58      2802704.20      7087312.62
      2802595.31      7087139.14      2802682.97      7087069.01
      2802864.76      7087084.70      2802712.50      7086875.23
      2802785.40      7086822.63      2802619.30      7086619.63
      2802511.34      7086699.91      2802429.21      7086389.86
      2802324.94      7086430.46      2802264.27      7086360.30

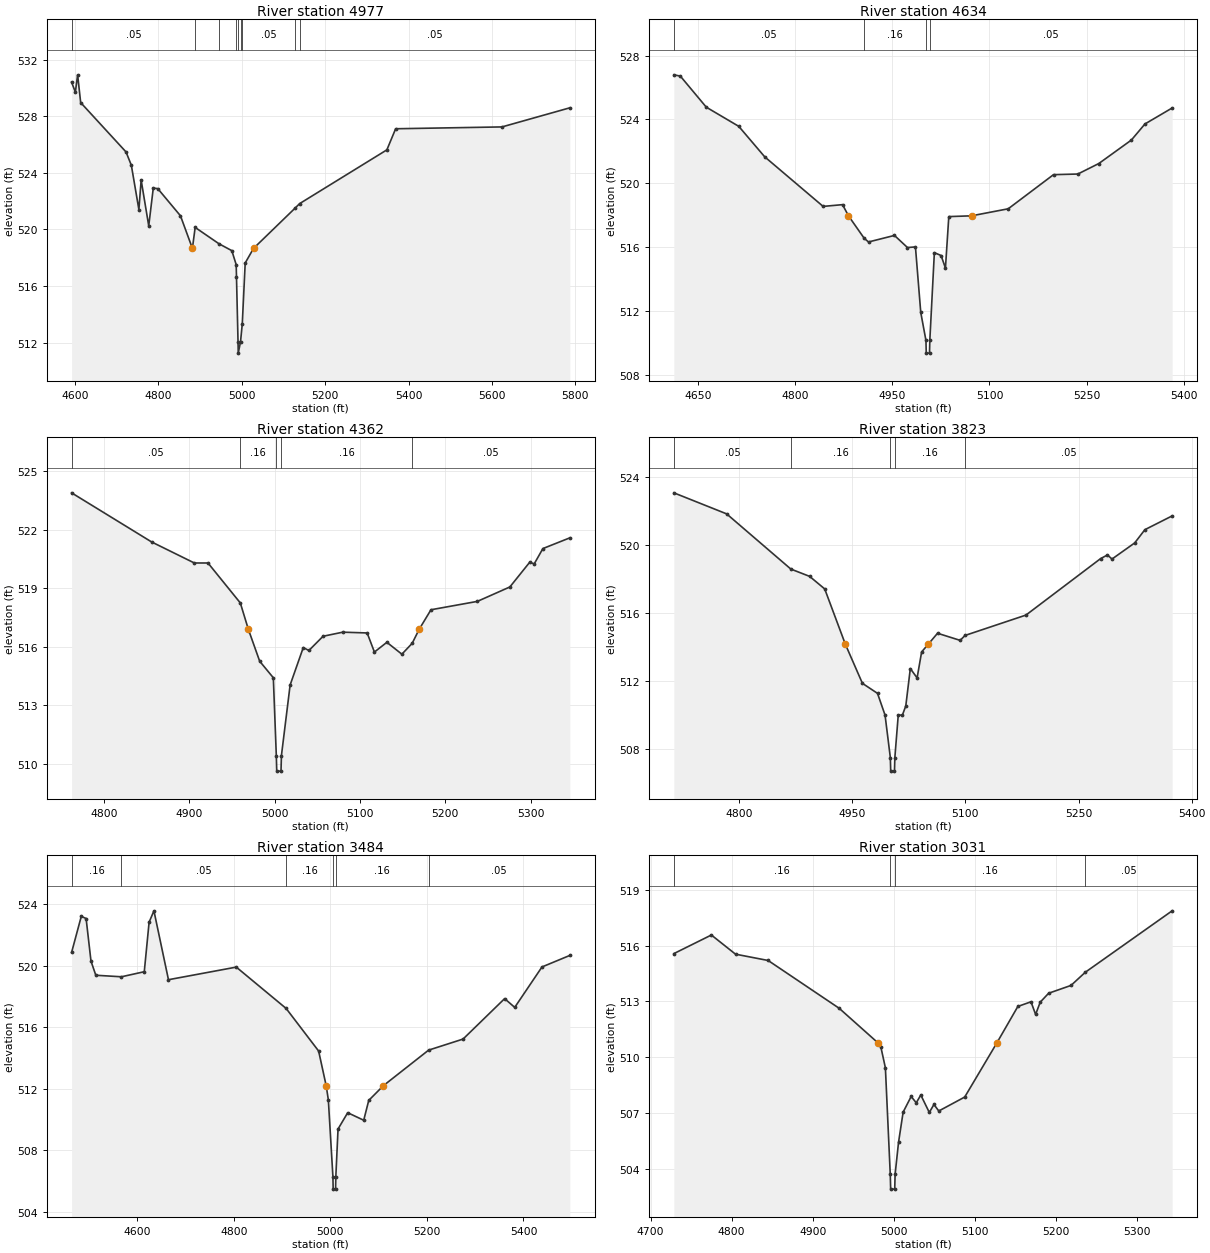
Type RM Length L Ch R = 1,4977,343,343,343
BEGIN DESCRIPTION:
UNT 071 in LFCCL Watershed 11.0
END DESCRIPTION:
XS GIS Cut Line= 3
      2803625.02      7089225.01      2803275.00      7089075.00
      2802675.03      7089624.97
#Sta/Elev= 30
  4592.0  530.40  4601.1  529.70  4606.5  530.92  4613.8  528.96  4722.6  525.47
  4735.3  524.53  4753.4  521.40  4758.8  523.49  4777.0  520.25  4787.9  522.92
  4798.7  522.88  4853.1  520.96  4881.7  518.66  4888.3  520.14  4945.7  518.98
  4976.2  518.50  4986.7  517.51  4987.4  516.64  4991.1  512.06  4991.6  511.26
  4997.1  512.06  5001.3  513.34  5008.3  517.63  5028.3  518.66  5128.5  521.52
  5138.7  521.82  5348.0  525.62  5369.0  527.11  5624.0  527.24  5786.7  528.59
#Mann=9,-1,0
  4592.0    0.05       0  4888.3    0.12       0  4945.7    0.05       0
  4987.4    0.12       0  4991.1    0.07       0  4997.1    0.12       0
  5001.3    0.05       0  5128.5    0.16       0  5138.7    0.05       0
Bank Sta=4881.7,5028.3
Exp/Cntr=0.3,0.1

Type RM Length L Ch R = 1,4634,272,272,272
BEGIN DESCRIPTION:
UNT 071 in LFCCL Watershed 10.0
END DESCRIPTION:
XS GIS Cut Line= 3
      2803525.01      7088875.00      2803155.52      7088854.79
      2802775.00      7088975.00
#Sta/Elev= 30
  4612.8  526.80  4622.8  526.72  4662.9  524.77  4713.0  523.57  4753.0  521.66
  4843.2  518.55  4873.2  518.66  4882.3  517.96  4906.6  516.55  4913.3  516.32
  4953.3  516.73  4973.4  515.97  4985.7  516.01  4993.9  511.90  5001.9  510.15
  5002.4  509.35  5007.4  509.35  5007.9  510.15  5014.9  515.65  5025.3  515.47
  5032.0  514.68  5037.2  517.91  5072.4  517.96  5128.9  518.40  5198.8  520.54
  5236.4  520.58  5268.8  521.24  5319.0  522.71  5340.0  523.72  5381.9  524.72
#Mann=4,-1,0
  4612.8    0.05       0  4906.6    0.16       0  5001.9    0.07       0
  5007.9    0.05       0
Bank Sta=4882.3,5072.4
Exp/Cntr=0.3,0.1

Type RM Length L Ch R = 1,4362,539,539,539
BEGIN DESCRIPTION:
XS3522A
END DESCRIPTION:
XS GIS Cut Line= 3
      2803362.44      7088566.14      2803152.97      7088675.99
      2802836.20      7088819.05
#Sta/Elev= 30
  4762.0  523.89  4855.8  521.37  4905.9  520.29  4921.9  520.29  4959.8  518.24
  4969.2  516.89  4982.5  515.25  4998.5  514.40  5002.0  510.41  5002.5  509.61
  5007.5  509.61  5008.0  510.41  5018.2  514.03  5033.6  515.95  5040.2  515.80
  5056.8  516.53  5079.9  516.74  5108.5  516.70  5117.0  515.72  5131.6  516.22
  5149.2  515.61  5161.3  516.17  5169.5  516.89  5183.3  517.89  5237.7  518.32
  5275.8  519.06  5298.9  520.32  5304.4  520.25  5314.5  521.03  5346.1  521.58
#Mann=5,-1,0
  4762.0    0.05       0  4959.8    0.16       0  5002.0    0.07       0
  5008.0    0.16       0  5161.3    0.05       0
Bank Sta=4969.2,5169.5
Exp/Cntr=0.3,0.1

Type RM Length L Ch R = 1,3823,339,339,339
BEGIN DESCRIPTION:
UNT 071 in LFCCL Watershed 8.0
END DESCRIPTION:
XS GIS Cut Line= 3
      2803225.00      7088375.00      2802925.00      7088375.00
      2802724.97      7088675.04
#Sta/Elev= 30
  4713.5  523.06  4783.5  521.82  4868.6  518.57  4893.5  518.14  4913.5  517.40
  4940.9  514.14  4963.5  511.84  4983.5  511.25  4993.5  509.97  5000.5  507.47
  5001.0  506.67  5006.0  506.67  5006.5  507.47  5011.0  509.97  5016.5  509.97
  5021.0  510.51  5027.0  512.71  5036.0  512.16  5042.0  513.69  5050.7  514.14
  5063.1  514.79  5093.1  514.37  5099.5  514.66  5180.3  515.86  5279.4  519.19
  5288.4  519.40  5294.4  519.16  5324.5  520.11  5338.0  520.89  5374.1  521.70
#Mann=5,-1,0
  4713.5    0.05       0  4868.6    0.16       0  5000.5    0.07       0
  5006.5    0.16       0  5099.5    0.05       0
Bank Sta=4940.9,5050.7
Exp/Cntr=0.3,0.1

Type RM Length L Ch R = 1,3484,453,453,453
BEGIN DESCRIPTION:
UNT 071 in LFCCL Watershed 7.0
END DESCRIPTION:
XS GIS Cut Line= 3
      2803425.05      7088075.00      2802825.00      7088125.00
      2802575.02      7088474.97
#Sta/Elev= 30
  4463.9  520.85  4484.0  523.20  4494.0  523.06  4504.1  520.29  4514.1  519.37
  4567.2  519.27  4614.5  519.60  4624.5  522.82  4634.5  523.56  4664.6  519.08
  4805.1  519.90  4908.4  517.21  4975.7  514.44  4991.3  512.19  4995.8  511.27
  5005.3  506.26  5005.8  505.46  5010.8  505.46  5011.3  506.26  5015.9  509.37
  5035.9  510.43  5069.1  509.94  5079.5  511.23  5109.9  512.19  5203.5  514.50
  5274.9  515.22  5361.0  517.85  5381.9  517.28  5438.4  519.91  5496.1  520.66
#Mann=6,-1,0
  4463.9    0.16       0  4567.2    0.05       0  4908.4    0.16       0
  5005.3    0.07       0  5011.3    0.16       0  5203.5    0.05       0
Bank Sta=4991.3,5109.9
Exp/Cntr=0.3,0.1

Type RM Length L Ch R = 1,3031,394,394,394
BEGIN DESCRIPTION:
UNT 071 in LFCCL Watershed 6.0
END DESCRIPTION:
XS GIS Cut Line= 3
      2803070.52      7087855.06      2802825.00      7087825.00
      2802501.91      7088000.43
#Sta/Elev= 30
  4728.7  515.57  4775.0  516.57  4804.8  515.54  4845.1  515.20  4932.8  512.63
  4981.2  510.75  4984.1  510.57  4989.8  509.43  4995.8  503.71  4996.3  502.91
  5001.3  502.91  5001.8  503.71  5006.0  505.42  5011.7  507.05  5021.6  507.89
  5027.9  507.55  5033.5  507.97  5044.0  507.03  5049.7  507.46  5055.7  507.11
  5087.7  507.86  5127.1  510.75  5153.3  512.73  5169.5  512.98  5175.2  512.30
  5180.9  512.96  5191.3  513.44  5218.9  513.86  5236.6  514.57  5343.7  517.87
#Mann=4,-1,0
  4728.7    0.16       0  4995.8    0.07       0  5001.8    0.16       0
  5236.6    0.05       0
Bank Sta=4981.2,5127.1
Exp/Cntr=0.3,0.1

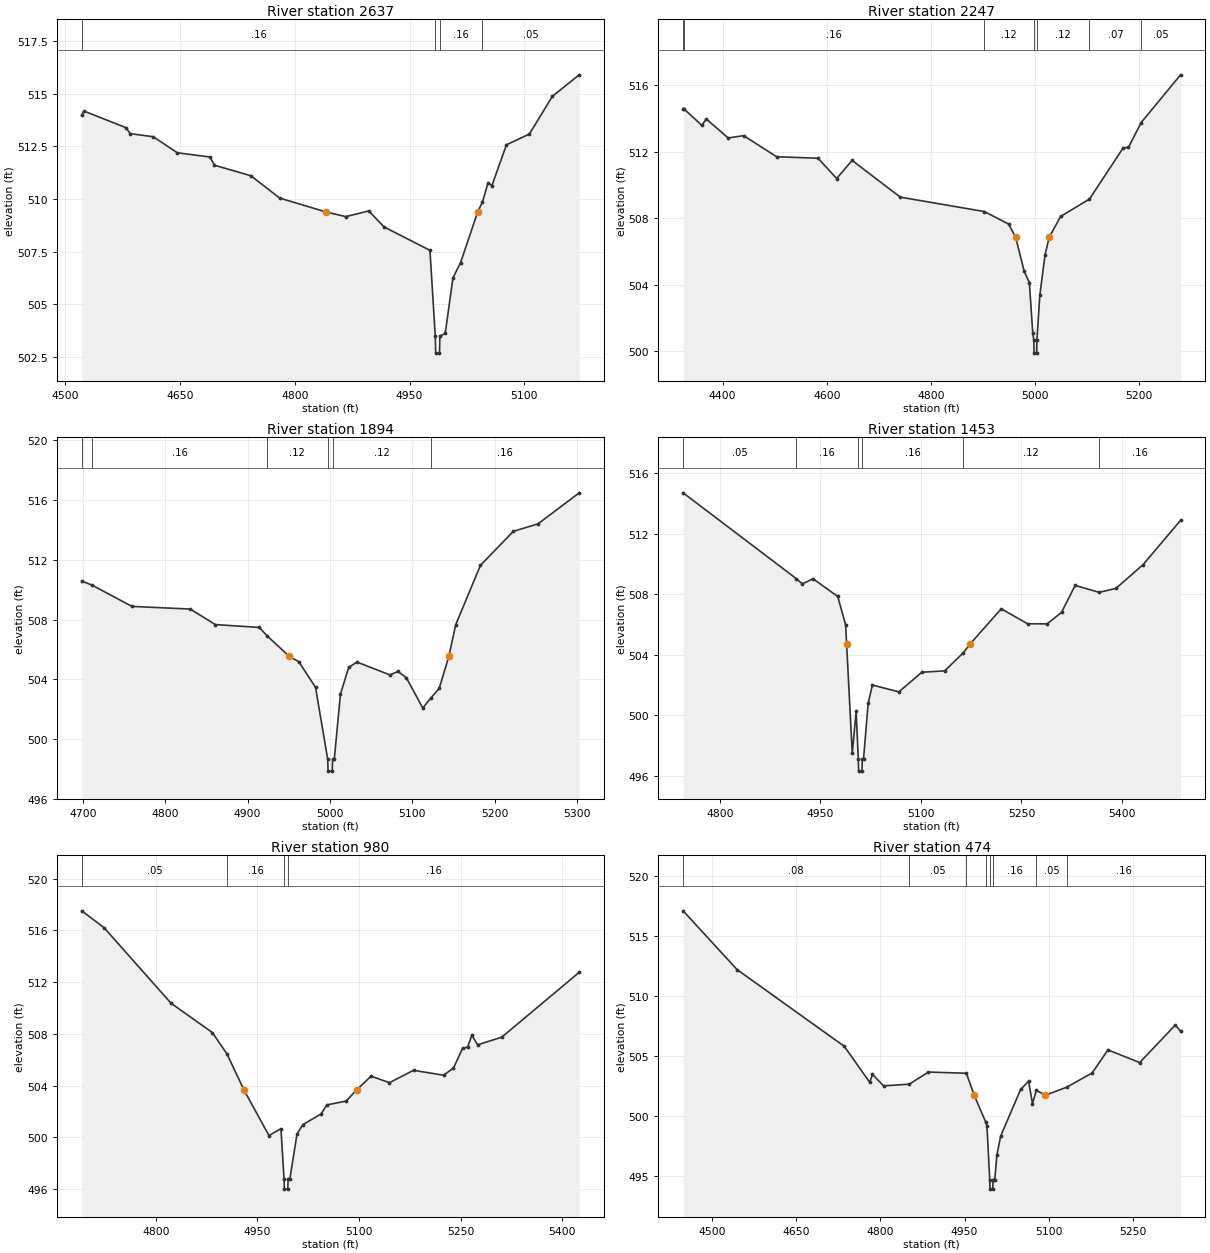
Type RM Length L Ch R = 1,2637,390,390,390
BEGIN DESCRIPTION:
XS3523A
END DESCRIPTION:
XS GIS Cut Line= 3
      2803021.88      7087761.30      2802754.54      7087660.61
      2802389.98      7087674.50
#Sta/Elev= 30
  4521.4  513.99  4524.2  514.18  4579.3  513.39  4584.7  513.11  4614.9  512.96
  4646.3  512.20  4689.0  512.00  4694.9  511.61  4742.5  511.11  4780.2  510.05
  4840.8  509.39  4866.7  509.17  4896.7  509.44  4916.7  508.68  4976.7  507.57
  4983.7  503.49  4984.2  502.69  4989.2  502.69  4989.7  503.49  4996.7  503.63
  5006.8  506.26  5016.8  506.99  5039.1  509.39  5045.4  509.86  5052.7  510.78
  5057.7  510.64  5076.8  512.58  5106.8  513.09  5136.8  514.88  5171.9  515.90
#Mann=4,-1,0
  4521.4    0.16       0  4983.7    0.07       0  4989.7    0.16       0
  5045.4    0.05       0
Bank Sta=4840.8,5039.1
Exp/Cntr=0.3,0.1

Type RM Length L Ch R = 1,2247,353,353,353
BEGIN DESCRIPTION:
UNT 071 in LFCCL Watershed 4.0
END DESCRIPTION:
XS GIS Cut Line= 3
      2803172.32      7087798.56      2802681.96      7087456.01
      2802325.02      7087475.00
#Sta/Elev= 30
  4324.2  514.59  4326.1  514.56  4360.1  513.58  4368.8  513.96  4410.7  512.82
  4440.4  512.96  4503.9  511.69  4583.4  511.60  4619.2  510.38  4648.8  511.47
  4741.3  509.26  4903.0  508.39  4949.4  507.64  4962.9  506.85  4979.4  504.80
  4989.4  504.11  4995.9  501.07  4997.9  500.67  4998.4  499.87  5003.4  499.87
  5003.9  500.67  5009.4  503.34  5019.5  505.80  5027.6  506.85  5049.5  508.10
  5104.8  509.14  5169.7  512.23  5179.7  512.25  5204.2  513.75  5279.8  516.62
#Mann=7,-1,0
  4324.2    0.05       0  4326.1    0.16       0  4903.0    0.12       0
  4997.9    0.07       0  5003.9    0.12       0  5104.8    0.07       0
  5204.2    0.05       0
Bank Sta=4962.9,5027.6
Exp/Cntr=0.3,0.1

Type RM Length L Ch R = 1,1894,441,441,441
BEGIN DESCRIPTION:
UNT 071 in LFCCL Watershed 3.0
END DESCRIPTION:
XS GIS Cut Line= 3
      2802925.05      7087275.01      2802625.00      7087225.00
      2802324.99      7087225.00
#Sta/Elev= 30
  4698.6  510.58  4711.2  510.30  4759.5  508.88  4830.4  508.70  4860.9  507.66
  4914.1  507.47  4923.5  506.92  4950.4  505.54  4962.2  505.17  4982.5  503.46
  4997.3  498.64  4997.8  497.84  5002.8  497.84  5003.3  498.64  5005.3  498.64
  5012.8  503.00  5022.8  504.79  5032.8  505.15  5072.8  504.29  5082.8  504.52
  5092.8  504.10  5112.8  502.07  5122.4  502.73  5132.8  503.39  5144.5  505.54
  5152.8  507.65  5182.8  511.63  5222.8  513.91  5252.8  514.41  5302.8  516.49
#Mann=6,-1,0
  4698.6    0.05       0  4711.2    0.16       0  4923.5    0.12       0
  4997.3    0.07       0  5003.3    0.12       0  5122.4    0.16       0
Bank Sta=4950.4,5144.5
Exp/Cntr=0.3,0.1

Type RM Length L Ch R = 1,1453,473,473,473
BEGIN DESCRIPTION:
XS3524A
END DESCRIPTION:
XS GIS Cut Line= 4
      2803084.38      7087209.21      2802851.76      7087073.81
      2802650.37      7087018.25      2802390.02      7087063.38
#Sta/Elev= 30
  4745.1  514.72  4913.9  509.04  4923.1  508.69  4938.8  509.03  4975.8  507.86
  4987.6  505.98  4989.1  504.68  4997.5  497.47  5003.3  500.25  5006.5  497.09
  5007.0  496.29  5012.0  496.29  5012.5  497.09  5014.3  497.09  5021.3  500.80
  5027.5  501.99  5067.1  501.54  5101.4  502.84  5135.4  502.93  5163.3  504.13
  5172.7  504.68  5219.9  507.04  5259.1  506.05  5288.2  506.04  5309.8  506.80
  5330.1  508.59  5365.9  508.13  5391.0  508.39  5431.6  509.97  5487.4  512.90
#Mann=6,-1,0
  4745.1    0.05       0  4913.9    0.16       0  5006.5    0.07       0
  5012.5    0.16       0  5163.3    0.12       0  5365.9    0.16       0
Bank Sta=4989.1,5172.7
Exp/Cntr=0.3,0.1

Type RM Length L Ch R = 1,980,506,506,506
BEGIN DESCRIPTION:
UNT 071 in LFCCL Watershed 2.0
END DESCRIPTION:
XS GIS Cut Line= 3
      2803025.03      7086724.99      2802725.00      7086775.00
      2802374.99      7087025.01
#Sta/Elev= 30
  4690.8  517.51  4723.8  516.20  4822.6  510.37  4883.5  508.11  4905.2  506.45
  4930.2  503.67  4967.1  500.15  4984.8  500.68  4989.4  496.81  4989.9  496.01
  4994.9  496.01  4995.4  496.81  4998.0  496.81  5008.5  500.26  5017.1  500.99
  5044.1  501.82  5052.7  502.52  5081.0  502.81  5096.5  503.67  5117.9  504.74
  5144.9  504.23  5180.5  505.19  5224.8  504.81  5239.5  505.36  5253.0  506.89
  5260.4  506.98  5266.6  507.90  5275.2  507.16  5310.8  507.75  5425.1  512.76
#Mann=4,-1,0
  4690.8    0.05       0  4905.2    0.16       0  4989.4    0.07       0
  4995.4    0.16       0
Bank Sta=4930.2,5096.5
Exp/Cntr=0.3,0.1

Type RM Length L Ch R = 1,474,93,93,93
BEGIN DESCRIPTION:
UNT 071 in LFCCL Watershed 1.0
END DESCRIPTION:
XS GIS Cut Line= 4
      2803022.04      7086614.32      2802568.49      7086594.79
      2802475.00      7086625.00      2802234.29      7086857.37
#Sta/Elev= 30
  4448.3  517.07  4544.5  512.18  4735.6  505.80  4780.9  502.81  4785.9  503.46
  4805.7  502.51  4851.4  502.65  4885.7  503.66  4953.3  503.56  4967.2  501.73
  4988.0  499.47  4990.0  499.15  4994.9  494.72  4995.4  493.92  5000.4  493.92
  5000.9  494.72  5004.0  494.72  5007.6  496.74  5014.5  498.34  5050.0  502.21
  5064.2  502.90  5071.1  501.04  5078.1  502.14  5094.0  501.73  5132.2  502.40
  5177.4  503.58  5205.7  505.50  5262.3  504.45  5325.8  507.57  5335.1  507.06
#Mann=8,-1,0
  4448.3    0.08       0  4851.4    0.05       0  4953.3    0.08       0
  4988.0    0.16       0  4994.9    0.07       0  5000.9    0.16       0
  5078.1    0.05       0  5132.2    0.16       0
Bank Sta=4967.2,5094
Exp/Cntr=0.3,0.1

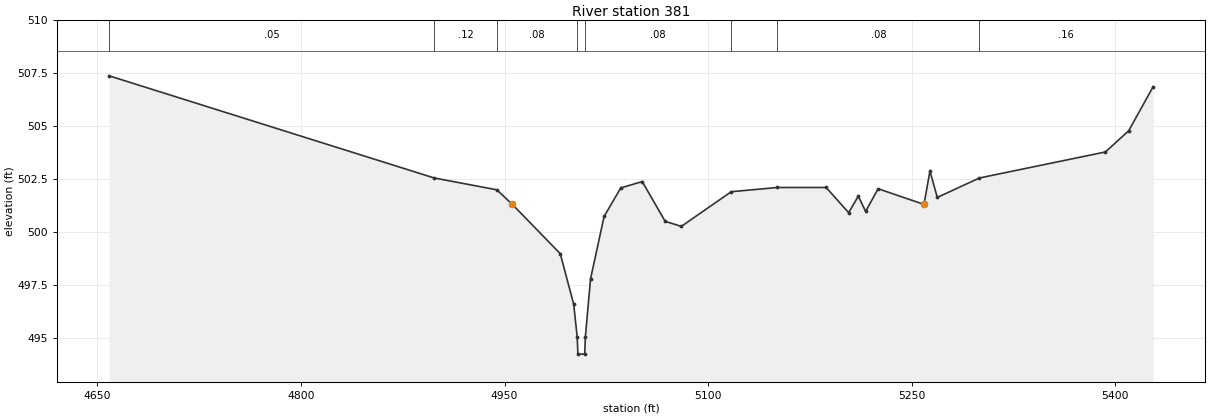
Type RM Length L Ch R = 1,381,0,0,0
BEGIN DESCRIPTION:
XS3525A
END DESCRIPTION:
XS GIS Cut Line= 4
      2802760.75      7086495.83      2802484.72      7086519.27
      2802295.62      7086612.45      2802185.98      7086871.68
#Sta/Elev= 30
  4658.6  507.38  4898.1  502.55  4944.3  501.99  4955.7  501.30  4991.0  498.97
  5000.9  496.58  5003.5  495.02  5004.0  494.22  5009.0  494.22  5009.5  495.02
  5013.3  497.77  5023.3  500.73  5035.6  502.08  5051.4  502.38  5068.3  500.50
  5080.2  500.26  5117.0  501.90  5150.9  502.10  5186.9  502.10  5203.5  500.91
  5210.6  501.69  5216.0  500.97  5225.2  502.04  5259.0  501.30  5263.4  502.88
  5268.8  501.63  5299.9  502.55  5392.7  503.78  5409.8  504.78  5427.9  506.87
#Mann=8,-1,0
  4658.6    0.05       0  4898.1    0.12       0  4944.3    0.08       0
  5003.5    0.07       0  5009.5    0.08       0  5117.0    0.16       0
  5150.9    0.08       0  5299.9    0.16       0
Bank Sta=4955.7,5259
Exp/Cntr=0.3,0.1

Chan Stop Cuts=-1