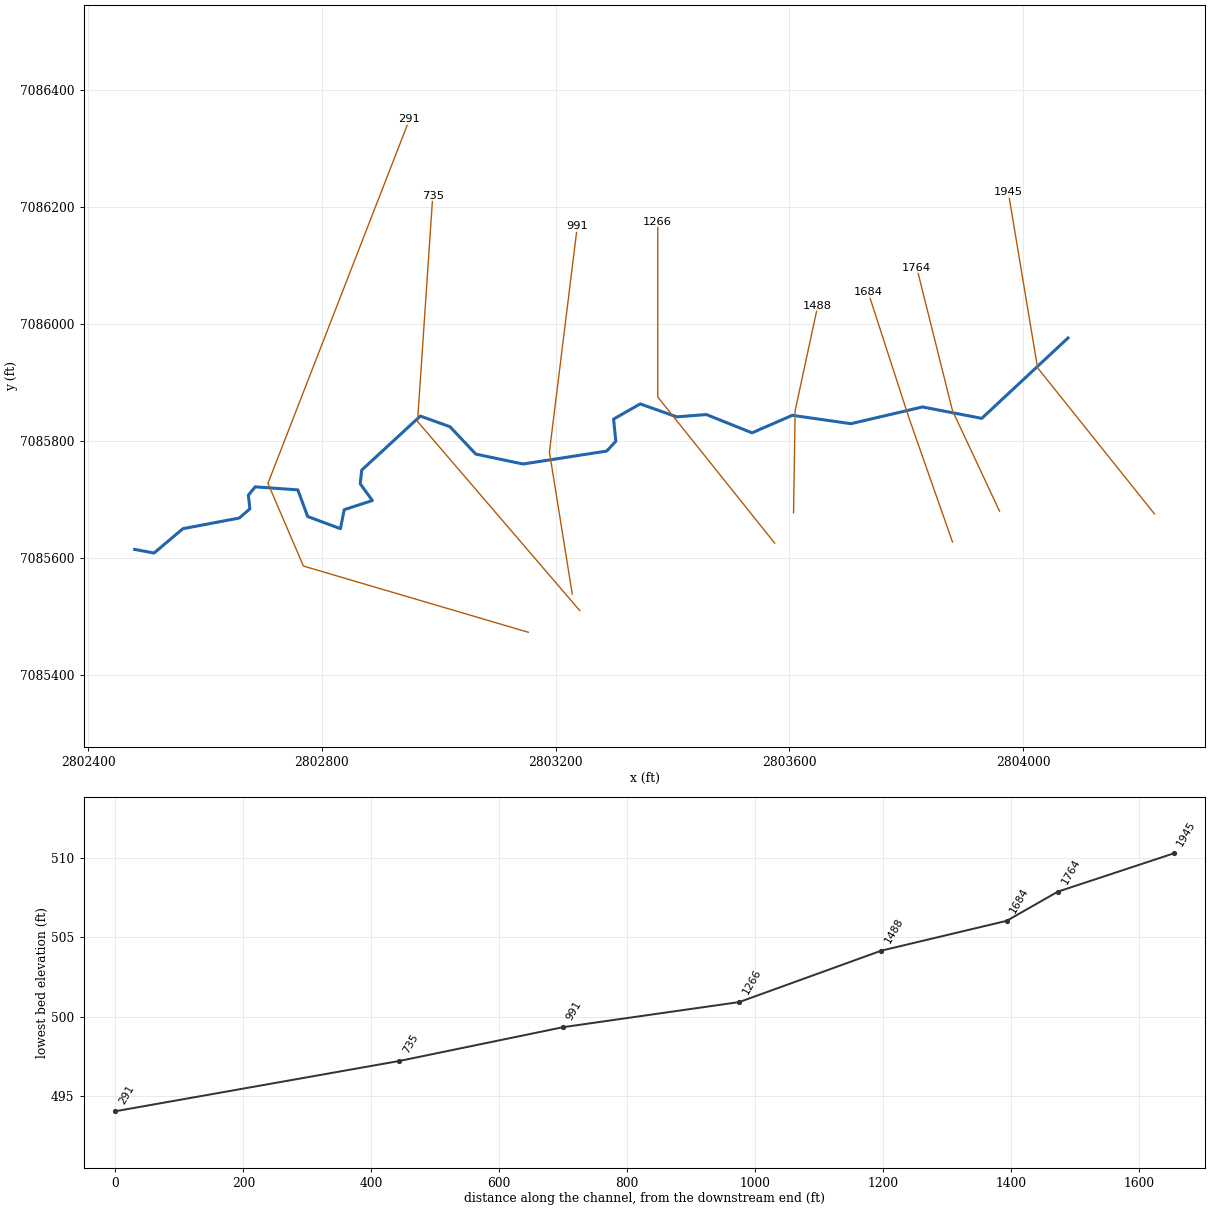
--- UNT 072 in LFCCL Watershed.prj (project) ---

Proj Title=UNT 072 in LFCCL Watershed Base Level Engineering
Current Plan=p01
Default Exp/Contr=0.3,0.1
English Units
Geom File=g01
Flow File=f01
Plan File=p01
BEGIN DESCRIPTION:
UNT 072 in LFCCL Watershed
END DESCRIPTION:

--- UNT 072 in LFCCL Watershed.p01 (plan) ---

Plan Title=Multiple Run
Short Identifier=Multiple
Geom File=g01
Flow File=f01
Subcritical Flow
K Sum by GR= 0
Std Step Tol= 0.01
Critical Tol= 0.01
Num of Std Step Trials= 20
Max Error Tol= 0.3
Flow Tol Ratio= 0.001
Split Flow NTrial= 30
Split Flow Tol= 0.02
Split Flow Ratio= 0.02
Log Output Level= 0
Friction Slope Method= 1
Unsteady Friction Slope Method= 2
Unsteady Bridges Friction Slope Method= 1
Parabolic Critical Depth
Global Vel Dist=  1 , 1 , 1
Global Log Level= 0
CheckData=True
Encroach Param= -1, 0, 0, 0
BEGIN DESCRIPTION:
Multiple Run
END DESCRIPTION:

--- UNT 072 in LFCCL Watershed.f01 (steady flow) ---

Flow Title=Multiple
Number of Profiles=7
Profile Names=10-year,25-year,50-year,1pct_min,100-year,1pct_plu,500-year
River Rch & RM= UNT 072 in LFCCL,Reach-1,1945
     178     217     246     139     278     555     352
Boundary for River Rch & Prof#=UNT 072 in LFCCL,Reach-1,1
Up Type=0
Dn Type=3
Dn Slope=0.005
Boundary for River Rch & Prof#=UNT 072 in LFCCL,Reach-1,2
Up Type=0
Dn Type=3
Dn Slope=0.005
Boundary for River Rch & Prof#=UNT 072 in LFCCL,Reach-1,3
Up Type=0
Dn Type=3
Dn Slope=0.005
Boundary for River Rch & Prof#=UNT 072 in LFCCL,Reach-1,4
Up Type=0
Dn Type=3
Dn Slope=0.005
Boundary for River Rch & Prof#=UNT 072 in LFCCL,Reach-1,5
Up Type=0
Dn Type=3
Dn Slope=0.005
Boundary for River Rch & Prof#=UNT 072 in LFCCL,Reach-1,6
Up Type=0
Dn Type=3
Dn Slope=0.005
Boundary for River Rch & Prof#=UNT 072 in LFCCL,Reach-1,7
Up Type=0
Dn Type=3
Dn Slope=0.005

--- UNT 072 in LFCCL Watershed.g01 (geometry) ---

Geom Title=Existing Conditions

River Reach=UNT 072 in LFCCL,Reach-1
Reach XY= 30
      2804077.12      7085976.03      2803929.55      7085838.44
      2803827.99      7085857.97      2803705.59      7085829.33
      2803605.33      7085843.65      2803536.32      7085813.70
      2803458.19      7085844.95      2803407.41      7085841.04
      2803344.91      7085863.18      2803299.34      7085837.14
      2803303.25      7085799.38      2803287.62      7085782.45
      2803144.39      7085760.31      2803063.66      7085777.24
      2803019.39      7085824.12      2802968.61      7085842.35
      2802868.35      7085749.90      2802865.75      7085726.46
      2802886.58      7085697.81      2802838.40      7085682.19
      2802831.89      7085649.64      2802775.90      7085670.47
      2802758.98      7085716.04      2802686.06      7085721.25
      2802674.34      7085706.93      2802676.94      7085683.49
      2802658.71      7085667.87      2802562.36      7085649.64
      2802512.88      7085607.97      2802479.74      7085614.14

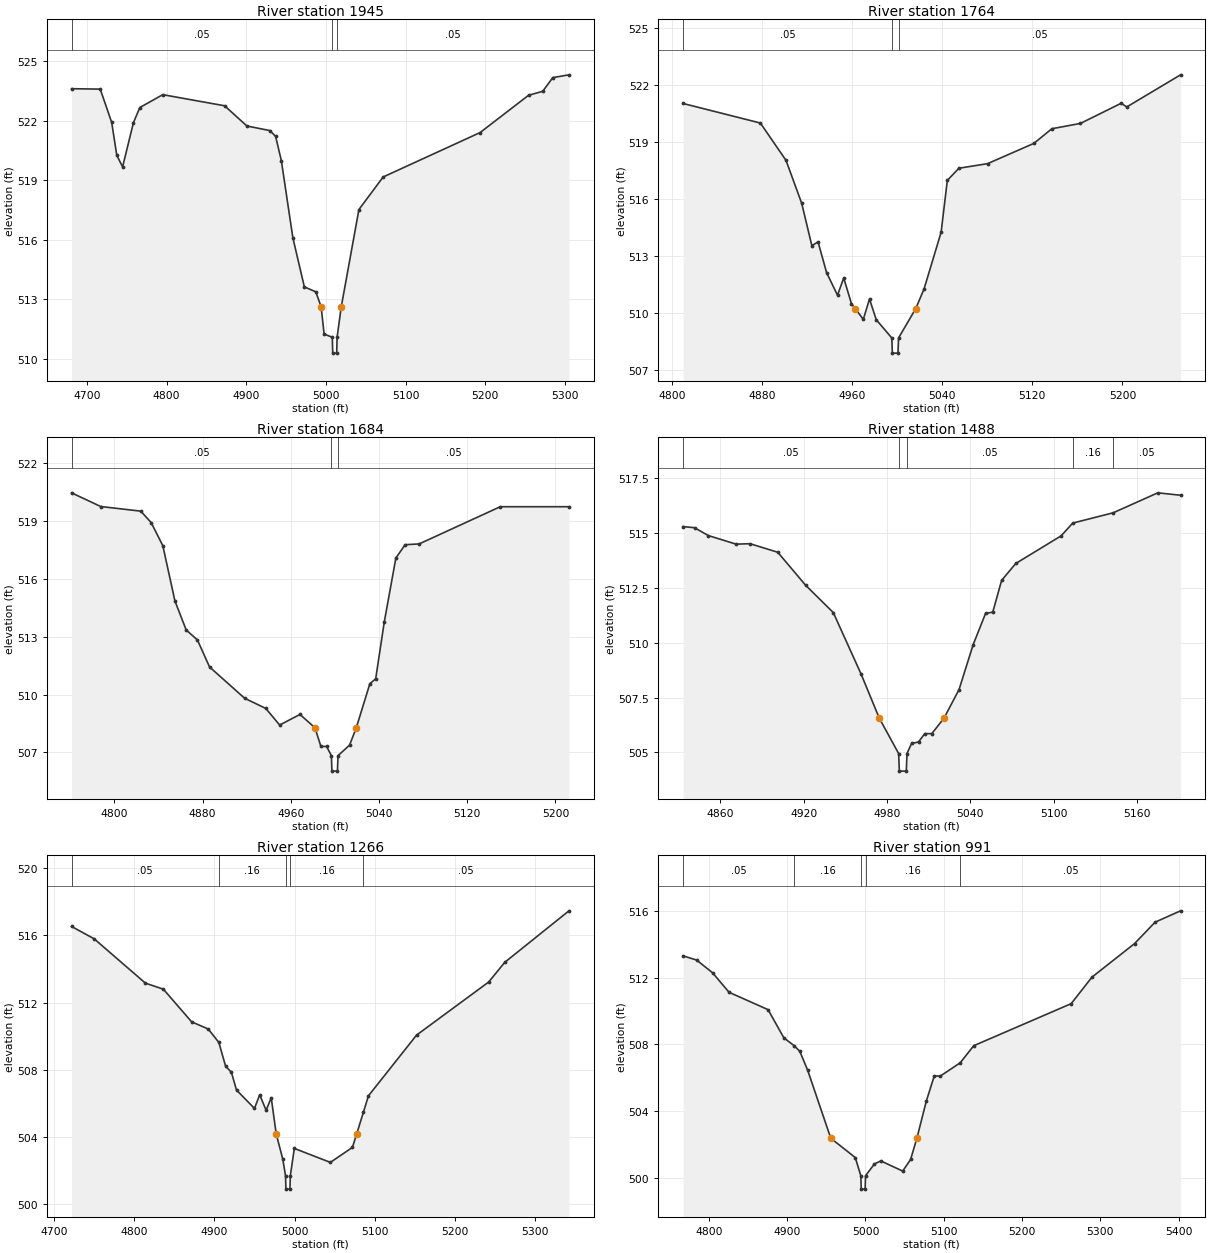
Type RM Length L Ch R = 1,1945,181,181,181
BEGIN DESCRIPTION:
UNT 072 in LFCCL Watershed 4.0
END DESCRIPTION:
XS GIS Cut Line= 3
      2804225.01      7085674.98      2804025.00      7085925.00
      2803975.00      7086224.99
#Sta/Elev= 30
  4680.6  523.61  4716.6  523.59  4731.0  521.91  4737.4  520.25  4744.7  519.67
  4758.3  521.90  4766.3  522.66  4795.1  523.31  4872.7  522.75  4900.7  521.73
  4929.5  521.50  4936.7  521.21  4943.9  519.99  4958.4  516.09  4972.8  513.62
  4987.2  513.37  4993.9  512.61  4997.6  511.24  5007.9  511.08  5008.4  510.28
  5013.4  510.28  5013.9  511.08  5019.1  512.61  5041.3  517.52  5071.7  519.16
  5193.4  521.40  5254.2  523.28  5272.0  523.48  5284.6  524.17  5304.9  524.31
#Mann=3,-1,0
  4680.6    0.05       0  5007.9    0.03       0  5013.9    0.05       0
Bank Sta=4993.9,5019.1
Exp/Cntr=0.3,0.1

Type RM Length L Ch R = 1,1764,80,80,80
BEGIN DESCRIPTION:
XS3526A
END DESCRIPTION:
XS GIS Cut Line= 3
      2803959.88      7085679.62      2803879.40      7085851.68
      2803818.34      7086095.91
#Sta/Elev= 30
  4809.9  521.02  4878.5  519.99  4901.3  518.02  4915.2  515.76  4924.2  513.53
  4929.7  513.73  4937.3  512.11  4947.0  510.92  4952.5  511.83  4959.4  510.47
  4962.6  510.22  4969.9  509.65  4975.4  510.72  4981.4  509.63  4995.2  508.67
  4995.7  507.87  5000.7  507.87  5001.2  508.67  5016.5  510.22  5023.9  511.26
  5039.0  514.24  5044.5  516.97  5054.8  517.61  5080.2  517.85  5121.4  518.92
  5137.3  519.69  5162.7  519.97  5198.8  521.03  5203.9  520.84  5251.6  522.53
#Mann=3,-1,0
  4809.9    0.05       0  4995.2    0.03       0  5001.2    0.05       0
Bank Sta=4962.6,5016.5
Exp/Cntr=0.3,0.1

Type RM Length L Ch R = 1,1684,196,196,196
BEGIN DESCRIPTION:
XS3527A
END DESCRIPTION:
XS GIS Cut Line= 3
      2803879.40      7085626.84      2803804.45      7085840.58
      2803735.06      7086054.30
#Sta/Elev= 30
  4761.1  520.46  4787.6  519.75  4823.9  519.51  4833.3  518.92  4843.9  517.72
  4854.9  514.85  4865.1  513.35  4875.3  512.83  4886.3  511.43  4918.1  509.81
  4937.3  509.28  4949.9  508.42  4968.3  508.97  4981.9  508.28  4987.3  507.31
  4992.5  507.31  4996.8  506.83  4997.3  506.03  5002.3  506.03  5002.8  506.83
  5013.3  507.38  5019.4  508.28  5031.7  510.56  5037.0  510.82  5044.8  513.77
  5055.3  517.08  5063.7  517.77  5076.4  517.81  5150.0  519.74  5212.3  519.74
#Mann=3,-1,0
  4761.1    0.05       0  4996.8    0.03       0  5002.8    0.05       0
Bank Sta=4981.9,5019.4
Exp/Cntr=0.3,0.1

Type RM Length L Ch R = 1,1488,222,222,222
BEGIN DESCRIPTION:
XS3528A
END DESCRIPTION:
XS GIS Cut Line= 3
      2803607.37      7085676.77      2803610.14      7085851.68
      2803648.77      7086031.03
#Sta/Elev= 30
  4833.1  515.30  4841.3  515.25  4851.3  514.89  4871.3  514.50  4881.3  514.52
  4901.3  514.13  4921.3  512.63  4941.3  511.38  4961.3  508.58  4974.4  506.57
  4988.4  504.95  4988.9  504.15  4993.9  504.15  4994.4  504.95  4997.7  505.41
  5002.7  505.48  5007.2  505.86  5012.3  505.86  5021.1  506.57  5031.9  507.87
  5042.1  509.92  5051.0  511.34  5056.2  511.40  5062.6  512.85  5072.8  513.62
  5105.5  514.88  5113.8  515.46  5143.0  515.93  5175.1  516.84  5191.5  516.73
#Mann=5,-1,0
  4833.1    0.05       0  4988.4    0.03       0  4994.4    0.05       0
  5113.8    0.16       0  5143.0    0.05       0
Bank Sta=4974.4,5021.1
Exp/Cntr=0.3,0.1

Type RM Length L Ch R = 1,1266,275,275,275
BEGIN DESCRIPTION:
UNT 072 in LFCCL Watershed 2.0
END DESCRIPTION:
XS GIS Cut Line= 3
      2803575.02      7085624.97      2803375.00      7085875.00
      2803375.00      7086175.01
#Sta/Elev= 30
  4722.0  516.53  4750.1  515.80  4814.1  513.16  4836.5  512.80  4871.7  510.86
  4892.5  510.43  4905.7  509.63  4914.1  508.22  4921.3  507.86  4927.7  506.80
  4950.1  505.71  4956.6  506.52  4964.6  505.60  4971.0  506.34  4977.2  504.19
  4985.4  502.69  4988.8  501.71  4989.3  500.91  4994.3  500.91  4994.8  501.71
  4999.8  503.33  5044.7  502.50  5072.2  503.39  5077.5  504.19  5085.9  505.48
  5092.2  506.46  5152.2  510.07  5242.2  513.23  5262.2  514.40  5342.2  517.46
#Mann=5,-1,0
  4722.0    0.05       0  4905.7    0.16       0  4988.8    0.07       0
  4994.8    0.16       0  5085.9    0.05       0
Bank Sta=4977.2,5077.5
Exp/Cntr=0.3,0.1

Type RM Length L Ch R = 1,991,256,256,256
BEGIN DESCRIPTION:
XS3530A
END DESCRIPTION:
XS GIS Cut Line= 3
      2803228.65      7085537.88      2803189.58      7085780.97
      2803237.32      7086167.23
#Sta/Elev= 30
  4767.1  513.30  4784.4  513.05  4804.7  512.29  4825.8  511.12  4875.6  510.08
  4895.8  508.39  4908.7  507.93  4916.1  507.59  4926.2  506.45  4955.7  502.38
  4987.0  501.22  4994.1  500.13  4994.6  499.33  4999.6  499.33  5000.1  500.13
  5011.5  500.84  5019.6  501.02  5047.6  500.41  5057.7  501.11  5065.7  502.38
  5077.8  504.61  5087.9  506.11  5095.6  506.10  5121.1  506.90  5138.3  507.92
  5262.8  510.44  5289.4  512.03  5343.8  514.04  5370.0  515.32  5402.5  516.00
#Mann=5,-1,0
  4767.1    0.05       0  4908.7    0.16       0  4994.1    0.07       0
  5000.1    0.16       0  5121.1    0.05       0
Bank Sta=4955.7,5065.7
Exp/Cntr=0.3,0.1

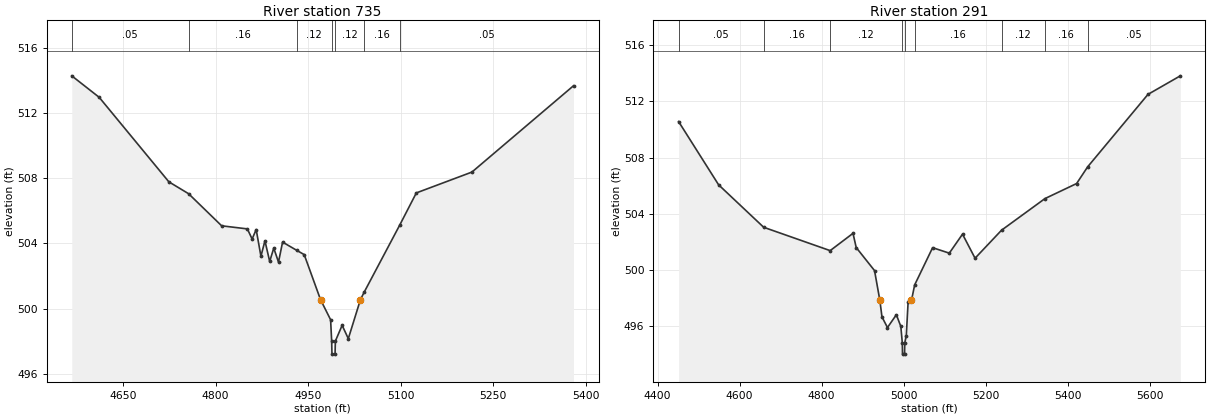
Type RM Length L Ch R = 1,735,444,444,444
BEGIN DESCRIPTION:
XS3529A
END DESCRIPTION:
XS GIS Cut Line= 3
      2803241.59      7085509.35      2802963.88      7085833.05
      2802989.93      7086219.37
#Sta/Elev= 30
  4566.8  514.29  4611.3  512.97  4724.3  507.78  4756.3  507.05  4809.9  505.08
  4851.6  504.89  4859.3  504.27  4865.9  504.85  4873.6  503.21  4880.1  504.16
  4887.8  502.89  4894.4  503.71  4902.1  502.85  4908.7  504.08  4931.8  503.57
  4943.8  503.31  4970.2  500.55  4986.6  499.31  4988.3  498.00  4988.8  497.20
  4993.8  497.20  4994.3  498.00  5005.3  498.97  5015.3  498.15  5035.0  500.55
  5041.1  501.01  5098.9  505.14  5125.6  507.10  5215.8  508.38  5380.5  513.68
#Mann=7,-1,0
  4566.8    0.05       0  4756.3    0.16       0  4931.8    0.12       0
  4988.3    0.07       0  4994.3    0.12       0  5041.1    0.16       0
  5098.9    0.05       0
Bank Sta=4970.2,5035
Exp/Cntr=0.3,0.1

Type RM Length L Ch R = 1,291,0,0,0
BEGIN DESCRIPTION:
UNT 072 in LFCCL Watershed 1.0
END DESCRIPTION:
XS GIS Cut Line= 4
      2803153.39      7085472.37      2802768.57      7085585.66
      2802707.83      7085727.19      2802950.00      7086350.00
#Sta/Elev= 30
  4451.3  510.57  4548.9  506.07  4658.8  503.05  4820.9  501.39  4876.6  502.62
  4884.4  501.61  4929.1  499.97  4942.1  497.85  4947.2  496.68  4960.6  495.92
  4982.3  496.83  4993.2  496.00  4996.8  494.83  4997.3  494.03  5002.3  494.03
  5002.8  494.83  5006.5  495.33  5011.0  497.76  5019.2  497.85  5026.9  498.95
  5070.7  501.60  5111.4  501.21  5143.6  502.56  5174.2  500.85  5238.7  502.84
  5344.6  505.09  5421.8  506.16  5448.8  507.35  5595.8  512.50  5674.7  513.82
#Mann=9,-1,0
  4451.3    0.05       0  4658.8    0.16       0  4820.9    0.12       0
  4996.8    0.07       0  5002.8    0.12       0  5026.9    0.16       0
  5238.7    0.12       0  5344.6    0.16       0  5448.8    0.05       0
Bank Sta=4942.1,5019.2
Exp/Cntr=0.3,0.1

Chan Stop Cuts=-1