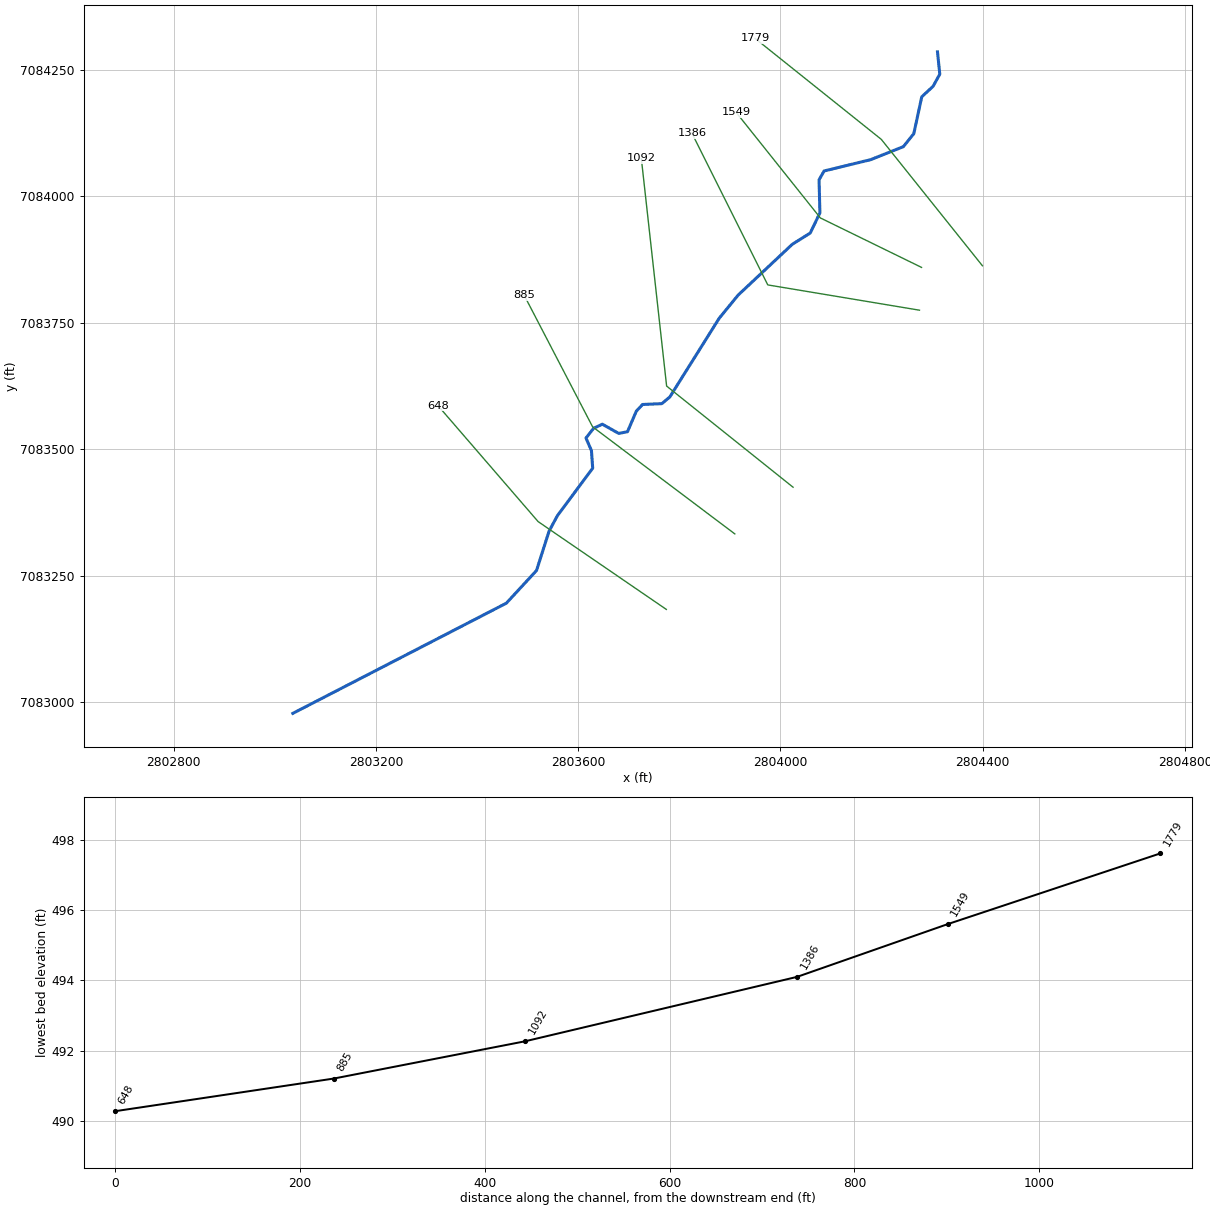
--- UNT 073 in LFCCL Watershed.prj (project) ---

Proj Title=UNT 073 in LFCCL Watershed Base Level Engineering
Current Plan=p01
Default Exp/Contr=0.3,0.1
English Units
Geom File=g01
Flow File=f01
Plan File=p01
BEGIN DESCRIPTION:
UNT 073 in LFCCL Watershed
END DESCRIPTION:

--- UNT 073 in LFCCL Watershed.p01 (plan) ---

Plan Title=Multiple Run
Short Identifier=Multiple
Geom File=g01
Flow File=f01
Subcritical Flow
K Sum by GR= 0
Std Step Tol= 0.01
Critical Tol= 0.01
Num of Std Step Trials= 20
Max Error Tol= 0.3
Flow Tol Ratio= 0.001
Split Flow NTrial= 30
Split Flow Tol= 0.02
Split Flow Ratio= 0.02
Log Output Level= 0
Friction Slope Method= 1
Unsteady Friction Slope Method= 2
Unsteady Bridges Friction Slope Method= 1
Parabolic Critical Depth
Global Vel Dist=  1 , 1 , 1
Global Log Level= 0
CheckData=True
Encroach Param= -1, 0, 0, 0
BEGIN DESCRIPTION:
Multiple Run
END DESCRIPTION:

--- UNT 073 in LFCCL Watershed.f01 (steady flow) ---

Flow Title=Multiple
Number of Profiles=7
Profile Names=10-year,25-year,50-year,1pct_min,100-year,1pct_plu,500-year
River Rch & RM= UNT 073 in LFCCL,Reach-1,1779
     229     284     326     186     372     742     481
Boundary for River Rch & Prof#=UNT 073 in LFCCL,Reach-1,1
Up Type=0
Dn Type=3
Dn Slope=0.005
Boundary for River Rch & Prof#=UNT 073 in LFCCL,Reach-1,2
Up Type=0
Dn Type=3
Dn Slope=0.005
Boundary for River Rch & Prof#=UNT 073 in LFCCL,Reach-1,3
Up Type=0
Dn Type=3
Dn Slope=0.005
Boundary for River Rch & Prof#=UNT 073 in LFCCL,Reach-1,4
Up Type=0
Dn Type=3
Dn Slope=0.005
Boundary for River Rch & Prof#=UNT 073 in LFCCL,Reach-1,5
Up Type=0
Dn Type=3
Dn Slope=0.005
Boundary for River Rch & Prof#=UNT 073 in LFCCL,Reach-1,6
Up Type=0
Dn Type=3
Dn Slope=0.005
Boundary for River Rch & Prof#=UNT 073 in LFCCL,Reach-1,7
Up Type=0
Dn Type=3
Dn Slope=0.005

--- UNT 073 in LFCCL Watershed.g01 (geometry) ---

Geom Title=Existing Conditions

River Reach=UNT 073 in LFCCL,Reach-1
Reach XY= 30
      2804310.59      7084285.71      2804315.12      7084241.71
      2804301.86      7084217.68      2804279.48      7084196.95
      2804263.73      7084124.01      2804243.01      7084098.32
      2804178.36      7084072.63      2804086.36      7084050.25
      2804076.41      7084032.84      2804078.07      7083967.36
      2804059.00      7083927.58      2804023.36      7083905.20
      2803916.44      7083804.90      2803879.14      7083759.32
      2803781.34      7083603.49      2803765.59      7083590.23
      2803727.46      7083588.57      2803715.03      7083575.31
      2803697.62      7083534.70      2803680.22      7083531.38
      2803647.89      7083549.62      2803630.48      7083541.33
      2803615.57      7083522.26      2803626.34      7083497.40
      2803628.83      7083462.59      2803559.20      7083368.92
      2803542.63      7083338.26      2803517.76      7083260.34
      2803458.08      7083195.69      2803035.90      7082977.81

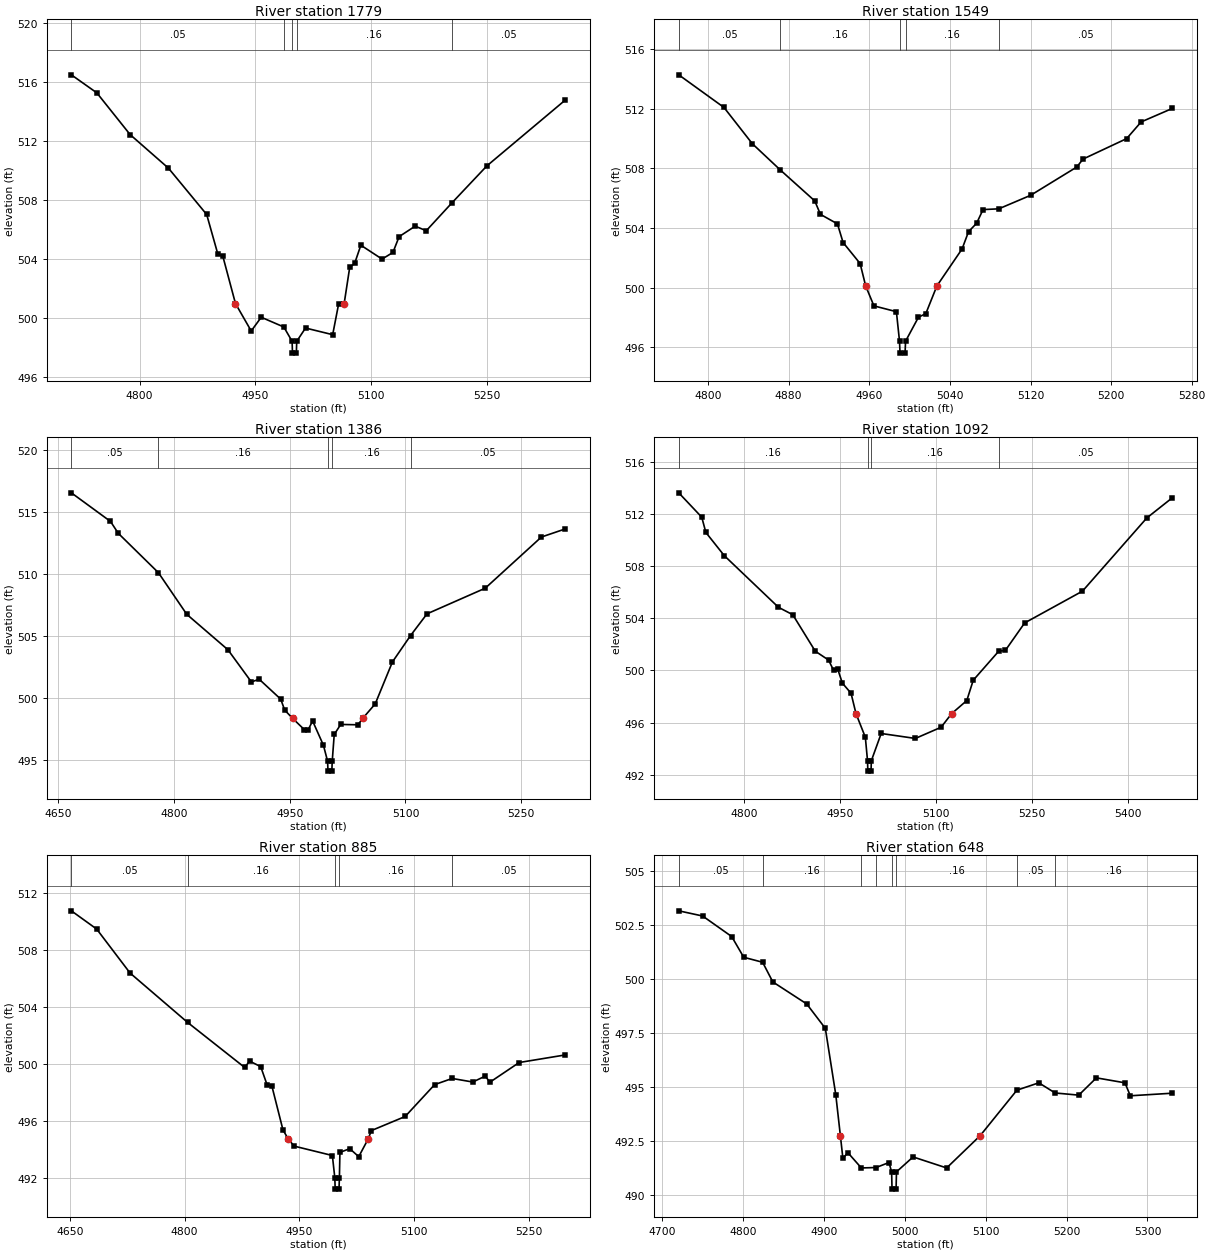
Type RM Length L Ch R = 1,1779,230,230,230
BEGIN DESCRIPTION:
UNT 073 in LFCCL Watershed 3.0
END DESCRIPTION:
XS GIS Cut Line= 3
      2804399.44      7083862.80      2804199.45      7084112.79
      2803949.76      7084312.54
#Sta/Elev= 30
  4711.6  516.46  4744.6  515.24  4787.8  512.41  4837.4  510.14  4887.0  507.00
  4901.5  504.31  4907.9  504.18  4924.3  500.97  4944.7  499.11  4957.7  500.04
  4987.0  499.38  4997.7  498.41  4998.2  497.61  5003.2  497.61  5003.7  498.41
  5015.1  499.31  5050.3  498.86  5058.0  500.94  5065.2  500.97  5072.4  503.43
  5078.8  503.69  5086.8  504.92  5114.3  503.98  5128.4  504.43  5136.4  505.50
  5157.2  506.21  5171.6  505.90  5204.9  507.79  5250.1  510.29  5351.5  514.74
#Mann=5,-1,0
  4711.6    0.05       0  4987.0    0.16       0  4997.7    0.07       0
  5003.7    0.16       0  5204.9    0.05       0
Bank Sta=4924.3,5065.2
Exp/Cntr=0.3,0.1

Type RM Length L Ch R = 1,1549,163,163,163
BEGIN DESCRIPTION:
XS3531A
END DESCRIPTION:
XS GIS Cut Line= 3
      2804279.05      7083859.61      2804078.98      7083957.43
      2803912.27      7084166.37
#Sta/Elev= 30
  4770.9  514.27  4815.8  512.08  4843.9  509.65  4871.8  507.88  4905.9  505.81
  4911.5  504.91  4928.4  504.27  4934.0  503.02  4950.9  501.61  4956.4  500.11
  4964.6  498.77  4986.9  498.38  4990.0  496.40  4990.5  495.60  4995.5  495.60
  4996.0  496.40  5008.8  498.01  5016.1  498.25  5027.1  500.11  5052.1  502.59
  5058.5  503.75  5066.5  504.31  5072.9  505.23  5088.5  505.28  5120.2  506.19
  5165.8  508.08  5172.2  508.62  5215.4  509.99  5229.8  511.11  5260.9  512.02
#Mann=5,-1,0
  4770.9    0.05       0  4871.8    0.16       0  4990.0    0.07       0
  4996.0    0.16       0  5088.5    0.05       0
Bank Sta=4956.4,5027.1
Exp/Cntr=0.3,0.1

Type RM Length L Ch R = 1,1386,294,294,294
BEGIN DESCRIPTION:
UNT 073 in LFCCL Watershed 2.0
END DESCRIPTION:
XS GIS Cut Line= 3
      2804274.99      7083775.00      2803975.00      7083825.00
      2803825.02      7084124.96
#Sta/Elev= 30
  4667.2  516.57  4717.9  514.26  4728.0  513.30  4780.0  510.12  4816.7  506.76
  4870.0  503.90  4900.4  501.30  4910.5  501.52  4938.4  499.91  4943.5  499.03
  4953.8  498.36  4968.8  497.46  4974.1  497.46  4979.7  498.15  4993.7  496.19
  4999.1  494.90  4999.6  494.10  5004.6  494.10  5005.1  494.90  5007.7  497.06
  5016.1  497.87  5038.4  497.84  5044.6  498.36  5060.8  499.53  5083.1  502.92
  5106.6  505.05  5127.9  506.80  5203.3  508.87  5276.0  513.00  5306.7  513.65
#Mann=5,-1,0
  4667.2    0.05       0  4780.0    0.16       0  4999.1    0.07       0
  5005.1    0.16       0  5106.6    0.05       0
Bank Sta=4953.8,5044.6
Exp/Cntr=0.3,0.1

Type RM Length L Ch R = 1,1092,207,207,207
BEGIN DESCRIPTION:
UNT 073 in LFCCL Watershed 1.0
END DESCRIPTION:
XS GIS Cut Line= 3
      2804024.99      7083425.01      2803775.00      7083625.00
      2803725.00      7084074.99
#Sta/Elev= 30
  4697.4  513.64  4733.4  511.77  4739.8  510.60  4768.6  508.82  4853.5  504.85
  4875.9  504.28  4911.1  501.48  4931.9  500.80  4939.9  500.00  4946.3  500.10
  4953.5  499.03  4967.1  498.25  4974.9  496.68  4989.5  494.87  4992.9  493.07
  4993.4  492.27  4998.4  492.27  4998.9  493.07  5014.3  495.16  5067.8  494.78
  5108.1  495.64  5124.5  496.68  5148.3  497.69  5158.4  499.25  5198.3  501.48
  5208.7  501.54  5238.9  503.65  5329.4  506.09  5430.1  511.71  5470.3  513.27
#Mann=4,-1,0
  4697.4    0.16       0  4992.9    0.07       0  4998.9    0.16       0
  5198.3    0.05       0
Bank Sta=4974.9,5124.5
Exp/Cntr=0.3,0.1

Type RM Length L Ch R = 1,885,237,237,237
BEGIN DESCRIPTION:
XS3533A
END DESCRIPTION:
XS GIS Cut Line= 3
      2803909.87      7083332.65      2803628.60      7083544.47
      2803493.20      7083804.86
#Sta/Elev= 30
  4652.0  510.75  4685.1  509.47  4728.8  506.38  4803.9  502.92  4878.7  499.75
  4885.0  500.20  4899.6  499.81  4907.9  498.54  4914.2  498.45  4928.7  495.37
  4935.6  494.73  4943.3  494.23  4993.3  493.57  4996.5  492.01  4997.0  491.21
  5002.0  491.21  5002.5  492.01  5003.2  493.79  5016.0  494.05  5027.8  493.49
  5040.1  494.73  5044.3  495.32  5088.5  496.31  5127.1  498.55  5150.0  498.98
  5176.9  498.73  5193.4  499.15  5199.1  498.71  5237.6  500.10  5297.6  500.63
#Mann=5,-1,0
  4652.0    0.05       0  4803.9    0.16       0  4996.5    0.07       0
  5002.5    0.16       0  5150.0    0.05       0
Bank Sta=4935.6,5040.1
Exp/Cntr=0.3,0.1

Type RM Length L Ch R = 1,648,0,0,0
BEGIN DESCRIPTION:
XS3532A
END DESCRIPTION:
XS GIS Cut Line= 3
      2803774.42      7083183.37      2803520.96      7083356.97
      2803323.05      7083586.13
#Sta/Elev= 30
  4720.9  503.16  4750.4  502.92  4786.3  501.97  4801.2  501.01  4824.5  500.78
  4837.1  499.87  4879.0  498.85  4902.0  497.72  4914.9  494.65  4920.6  492.75
  4923.7  491.70  4929.8  491.97  4946.5  491.26  4964.7  491.28  4980.6  491.51
  4983.9  491.08  4984.4  490.28  4989.4  490.28  4989.9  491.08  5010.4  491.77
  5051.9  491.26  5093.2  492.75  5138.7  494.86  5165.8  495.20  5185.9  494.73
  5215.1  494.63  5236.9  495.43  5272.2  495.20  5278.8  494.60  5330.9  494.72
#Mann=8,-1,0
  4720.9    0.05       0  4824.5    0.16       0  4946.5    0.05       0
  4964.7    0.16       0  4983.9    0.07       0  4989.9    0.16       0
  5138.7    0.05       0  5185.9    0.16       0
Bank Sta=4920.6,5093.2
Exp/Cntr=0.3,0.1

Chan Stop Cuts=-1