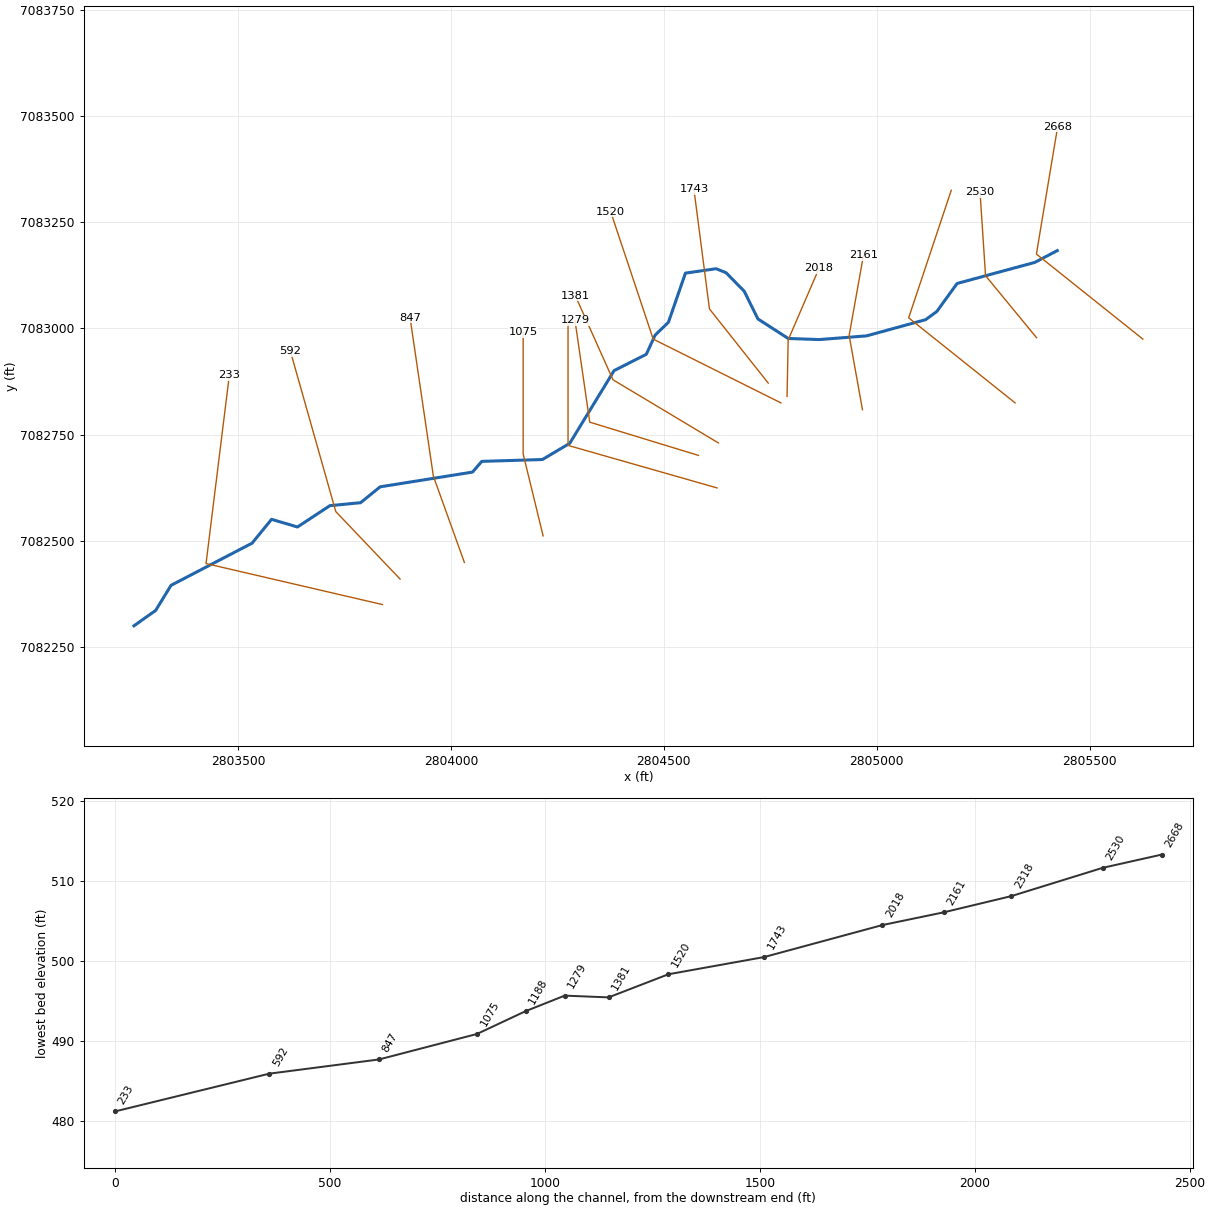
--- UNT 074 in LFCCL Watershed.prj (project) ---

Proj Title=UNT 074 in LFCCL Watershed Base Level Engineering
Current Plan=p01
Default Exp/Contr=0.3,0.1
English Units
Geom File=g01
Flow File=f01
Plan File=p01
BEGIN DESCRIPTION:
UNT 074 in LFCCL Watershed
END DESCRIPTION:

--- UNT 074 in LFCCL Watershed.p01 (plan) ---

Plan Title=Multiple Run
Short Identifier=Multiple
Geom File=g01
Flow File=f01
Subcritical Flow
K Sum by GR= 0
Std Step Tol= 0.01
Critical Tol= 0.01
Num of Std Step Trials= 20
Max Error Tol= 0.3
Flow Tol Ratio= 0.001
Split Flow NTrial= 30
Split Flow Tol= 0.02
Split Flow Ratio= 0.02
Log Output Level= 0
Friction Slope Method= 1
Unsteady Friction Slope Method= 2
Unsteady Bridges Friction Slope Method= 1
Parabolic Critical Depth
Global Vel Dist=  1 , 1 , 1
Global Log Level= 0
CheckData=True
Encroach Param= -1, 0, 0, 0
BEGIN DESCRIPTION:
Multiple Run
END DESCRIPTION:

--- UNT 074 in LFCCL Watershed.f01 (steady flow) ---

Flow Title=Multiple
Number of Profiles=7
Profile Names=10-year,25-year,50-year,1pct_min,100-year,1pct_plu,500-year
River Rch & RM= UNT 074 in LFCCL,Reach-1,2668
     174     212     239     135     269     536     337
Boundary for River Rch & Prof#=UNT 074 in LFCCL,Reach-1,1
Up Type=0
Dn Type=3
Dn Slope=0.005
Boundary for River Rch & Prof#=UNT 074 in LFCCL,Reach-1,2
Up Type=0
Dn Type=3
Dn Slope=0.005
Boundary for River Rch & Prof#=UNT 074 in LFCCL,Reach-1,3
Up Type=0
Dn Type=3
Dn Slope=0.005
Boundary for River Rch & Prof#=UNT 074 in LFCCL,Reach-1,4
Up Type=0
Dn Type=3
Dn Slope=0.005
Boundary for River Rch & Prof#=UNT 074 in LFCCL,Reach-1,5
Up Type=0
Dn Type=3
Dn Slope=0.005
Boundary for River Rch & Prof#=UNT 074 in LFCCL,Reach-1,6
Up Type=0
Dn Type=3
Dn Slope=0.005
Boundary for River Rch & Prof#=UNT 074 in LFCCL,Reach-1,7
Up Type=0
Dn Type=3
Dn Slope=0.005

--- UNT 074 in LFCCL Watershed.g01 (geometry) ---

Geom Title=Existing Conditions

River Reach=UNT 074 in LFCCL,Reach-1
Reach XY= 30
      2805424.01      7083183.09      2805371.06      7083155.32
      2805188.76      7083105.84      2805141.02      7083039.86
      2805114.98      7083020.77      2804976.09      7082982.57
      2804864.98      7082973.89      2804792.06      7082976.50
      2804720.88      7083022.50      2804688.76      7083087.61
      2804646.23      7083131.01      2804622.79      7083140.56
      2804550.74      7083130.14      2804510.81      7083014.69
      2804479.56      7082984.31      2804458.73      7082939.17
      2804383.21      7082900.98      2804279.04      7082729.97
      2804214.81      7082691.77      2804072.45      7082687.43
      2804050.74      7082662.26      2803833.73      7082627.54
      2803787.72      7082590.21      2803715.67      7082583.27
      2803639.54      7082533.11      2803578.67      7082551.14
      2803533.04      7082495.13      2803342.65      7082395.92
      2803306.49      7082336.82      2803255.59      7082300.71

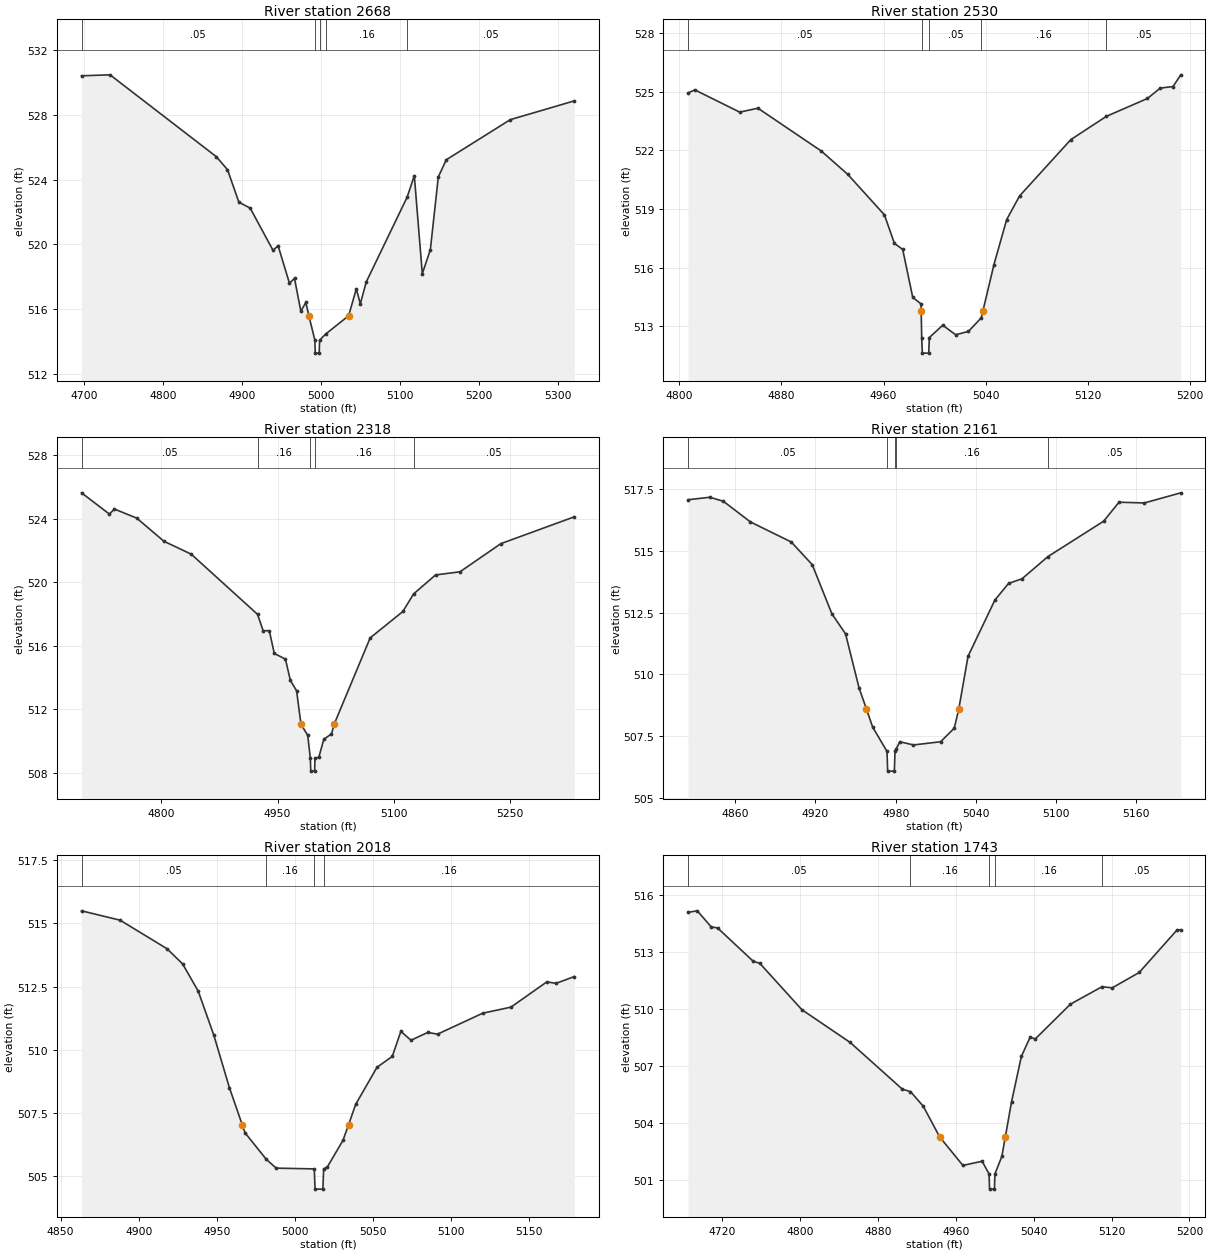
Type RM Length L Ch R = 1,2668,138,138,138
BEGIN DESCRIPTION:
UNT 074 in LFCCL Watershed 6.0
END DESCRIPTION:
XS GIS Cut Line= 3
      2805625.04      7082974.97      2805375.00      7083175.00
      2805424.99      7083474.96
#Sta/Elev= 30
  4696.3  530.42  4732.4  530.48  4866.8  525.43  4881.2  524.62  4895.6  522.61
  4910.0  522.24  4938.9  519.63  4945.3  519.92  4959.7  517.60  4966.1  517.90
  4974.1  515.87  4980.5  516.41  4984.3  515.59  4991.9  514.08  4992.4  513.28
  4997.4  513.28  4997.9  514.08  5005.6  514.46  5034.7  515.59  5044.4  517.25
  5049.5  516.33  5057.1  517.69  5108.9  522.93  5117.9  524.25  5128.0  518.19
  5138.2  519.67  5148.3  524.17  5158.4  525.23  5239.5  527.71  5320.6  528.87
#Mann=5,-1,0
  4696.3    0.05       0  4991.9    0.03       0  4997.9    0.05       0
  5005.6    0.16       0  5108.9    0.05       0
Bank Sta=4984.3,5034.7
Exp/Cntr=0.3,0.1

Type RM Length L Ch R = 1,2530,212,212,212
BEGIN DESCRIPTION:
XS3534A
END DESCRIPTION:
XS GIS Cut Line= 3
      2805375.36      7082978.29      2805255.54      7083124.15
      2805242.58      7083321.06
#Sta/Elev= 30
  4806.8  524.94  4812.1  525.10  4847.3  523.96  4861.6  524.16  4911.2  521.97
  4932.0  520.77  4960.7  518.70  4968.5  517.24  4975.0  516.93  4982.9  514.47
  4989.4  514.14  4989.5  513.79  4989.9  512.42  4990.4  511.62  4995.4  511.62
  4995.9  512.42  5006.4  513.05  5016.5  512.56  5026.5  512.73  5036.6  513.43
  5037.9  513.79  5046.5  516.15  5056.5  518.46  5066.6  519.67  5106.7  522.55
  5134.5  523.74  5166.8  524.66  5176.8  525.19  5186.8  525.27  5192.9  525.87
#Mann=5,-1,0
  4806.8    0.05       0  4989.9    0.03       0  4995.9    0.05       0
  5036.6    0.16       0  5134.5    0.05       0
Bank Sta=4989.5,5037.9
Exp/Cntr=0.3,0.1

Type RM Length L Ch R = 1,2318,157,157,157
BEGIN DESCRIPTION:
UNT 074 in LFCCL Watershed 5.0
END DESCRIPTION:
XS GIS Cut Line= 3
      2805324.97      7082825.02      2805075.00      7083025.00
      2805175.02      7083325.05
#Sta/Elev= 30
  4696.8  525.62  4732.8  524.28  4739.2  524.60  4768.0  524.03  4803.2  522.57
  4838.4  521.76  4924.1  517.97  4931.3  516.94  4939.3  516.94  4945.7  515.51
  4960.1  515.15  4966.5  513.81  4974.5  513.16  4980.2  511.05  4988.9  510.35
  4992.3  508.90  4992.8  508.10  4997.8  508.10  4998.3  508.90  5003.3  508.98
  5009.7  510.11  5019.6  510.44  5023.0  511.05  5069.6  516.49  5111.8  518.15
  5125.7  519.26  5154.0  520.45  5185.6  520.65  5238.3  522.42  5333.2  524.11
#Mann=5,-1,0
  4696.8    0.05       0  4924.1    0.16       0  4992.3    0.07       0
  4998.3    0.16       0  5125.7    0.05       0
Bank Sta=4980.2,5023
Exp/Cntr=0.3,0.1

Type RM Length L Ch R = 1,2161,143,143,143
BEGIN DESCRIPTION:
XS3535A
END DESCRIPTION:
XS GIS Cut Line= 3
      2804966.47      7082809.06      2804935.22      7082983.53
      2804968.76      7083171.82
#Sta/Elev= 30
  4824.7  517.07  4840.9  517.17  4851.1  517.01  4871.4  516.17  4901.9  515.36
  4917.6  514.44  4932.3  512.45  4942.5  511.64  4952.6  509.45  4958.1  508.60
  4962.8  507.86  4973.5  506.88  4974.0  506.08  4979.0  506.08  4979.5  506.88
  4980.2  506.96  4983.1  507.27  4993.3  507.14  5013.6  507.27  5023.8  507.82
  5027.2  508.60  5034.1  510.73  5054.2  513.01  5064.4  513.68  5074.5  513.87
  5093.9  514.77  5135.5  516.20  5147.0  516.97  5166.0  516.94  5193.2  517.35
#Mann=5,-1,0
  4824.7    0.05       0  4973.5    0.07       0  4979.5    0.05       0
  4980.2    0.16       0  5093.9    0.05       0
Bank Sta=4958.1,5027.2
Exp/Cntr=0.3,0.1

Type RM Length L Ch R = 1,2018,275,275,275
BEGIN DESCRIPTION:
XS3536A
END DESCRIPTION:
XS GIS Cut Line= 3
      2804789.39      7082840.26      2804792.00      7082973.11
      2804864.40      7083141.20
#Sta/Elev= 30
  4863.4  515.50  4888.1  515.13  4918.2  514.00  4928.2  513.40  4938.2  512.32
  4948.2  510.58  4958.2  508.50  4966.4  507.04  4968.2  506.72  4981.8  505.67
  4988.2  505.32  5012.6  505.29  5013.1  504.49  5018.1  504.49  5018.6  505.29
  5021.0  505.37  5031.0  506.42  5034.6  507.04  5039.1  507.84  5052.8  509.31
  5062.6  509.74  5068.1  510.73  5074.6  510.38  5085.4  510.69  5091.6  510.62
  5120.6  511.45  5138.7  511.69  5161.7  512.69  5167.6  512.63  5179.3  512.90
#Mann=4,-1,0
  4863.4    0.05       0  4981.8    0.16       0  5012.6    0.07       0
  5018.6    0.16       0
Bank Sta=4966.4,5034.6
Exp/Cntr=0.3,0.1

Type RM Length L Ch R = 1,1743,223,223,223
BEGIN DESCRIPTION:
XS3537A
END DESCRIPTION:
XS GIS Cut Line= 3
      2804745.12      7082871.56      2804607.10      7083046.03
      2804570.64      7083327.31
#Sta/Elev= 30
  4685.0  515.09  4694.5  515.17  4708.9  514.32  4715.3  514.27  4752.2  512.50
  4758.6  512.41  4801.9  509.96  4851.6  508.23  4905.1  505.77  4913.5  505.64
  4926.6  504.87  4943.5  503.25  4967.3  501.75  4987.1  501.97  4994.2  501.30
  4994.7  500.50  4999.7  500.50  5000.2  501.30  5007.3  502.22  5010.9  503.25
  5017.3  505.11  5027.4  507.50  5036.5  508.52  5041.5  508.41  5077.8  510.25
  5110.2  511.17  5120.7  511.11  5148.4  511.92  5187.4  514.17  5191.1  514.17
#Mann=5,-1,0
  4685.0    0.05       0  4913.5    0.16       0  4994.2    0.07       0
  5000.2    0.16       0  5110.2    0.05       0
Bank Sta=4943.5,5010.9
Exp/Cntr=0.3,0.1

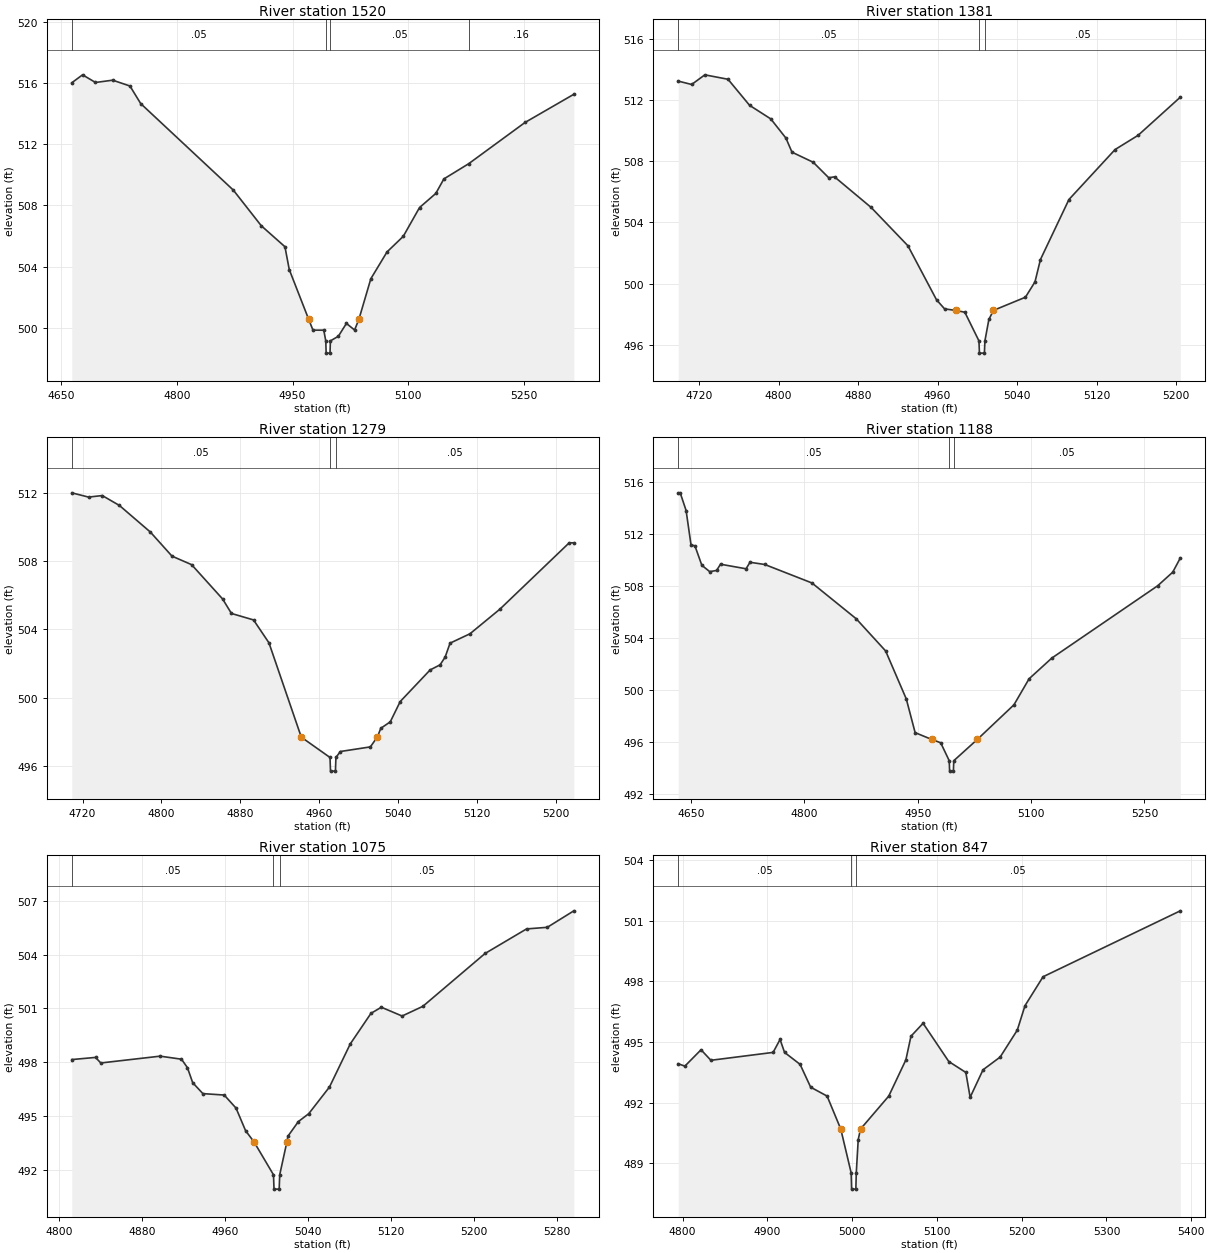
Type RM Length L Ch R = 1,1520,139,139,139
BEGIN DESCRIPTION:
UNT 074 in LFCCL Watershed 3.0
END DESCRIPTION:
XS GIS Cut Line= 3
      2804775.03      7082824.98      2804475.00      7082975.00
      2804374.99      7083275.03
#Sta/Elev= 30
  4663.4  516.01  4677.4  516.53  4694.2  516.03  4716.5  516.18  4738.9  515.80
  4752.9  514.65  4873.1  509.00  4909.4  506.67  4940.1  505.30  4945.7  503.81
  4970.9  500.56  4976.5  499.85  4990.5  499.85  4993.1  499.15  4993.6  498.35
  4998.6  498.35  4999.1  499.15  5009.4  499.45  5019.9  500.29  5030.5  499.86
  5036.1  500.56  5051.6  503.21  5072.6  504.96  5093.7  505.98  5114.8  507.86
  5135.9  508.78  5146.4  509.73  5178.5  510.72  5251.8  513.42  5315.1  515.26
#Mann=4,-1,0
  4663.4    0.05       0  4993.1    0.03       0  4999.1    0.05       0
  5178.5    0.16       0
Bank Sta=4970.9,5036.1
Exp/Cntr=0.3,0.1

Type RM Length L Ch R = 1,1381,102,102,102
BEGIN DESCRIPTION:
XS3538A
END DESCRIPTION:
XS GIS Cut Line= 3
      2804627.95      7082730.91      2804380.54      7082879.36
      2804291.98      7083077.32
#Sta/Elev= 30
  4698.9  513.23  4712.4  513.01  4725.7  513.64  4749.0  513.35  4770.7  511.65
  4792.1  510.76  4807.3  509.51  4813.4  508.59  4834.8  507.93  4850.4  506.92
  4856.2  506.98  4893.1  504.98  4930.1  502.48  4958.9  498.95  4967.0  498.36
  4978.0  498.26  4987.4  498.14  5001.6  496.27  5002.1  495.47  5007.1  495.47
  5007.6  496.27  5011.6  497.67  5016.2  498.26  5048.4  499.12  5058.0  500.12
  5063.5  501.58  5092.2  505.50  5138.6  508.76  5161.8  509.69  5204.3  512.18
#Mann=3,-1,0
  4698.9    0.05       0  5001.6    0.03       0  5007.6    0.05       0
Bank Sta=4978,5016.2
Exp/Cntr=0.3,0.1

Type RM Length L Ch R = 1,1279,91,91,91
BEGIN DESCRIPTION:
Mapping XS 1ba068d2
END DESCRIPTION:
XS GIS Cut Line= 3
      2804581.22      7082701.50      2804326.01      7082779.62
      2804291.28      7083019.21
#Sta/Elev= 30
  4709.1  512.00  4726.1  511.75  4740.0  511.84  4757.4  511.26  4788.8  509.70
  4810.7  508.29  4830.6  507.79  4862.0  505.78  4871.0  504.93  4893.4  504.55
  4909.0  503.21  4941.8  497.68  4970.9  496.49  4971.4  495.69  4976.4  495.69
  4976.9  496.49  4981.4  496.84  5011.8  497.11  5018.9  497.69  5022.4  498.20
  5032.0  498.58  5042.1  499.77  5072.4  501.62  5082.5  501.92  5087.6  502.37
  5092.6  503.19  5112.8  503.74  5143.1  505.18  5213.4  509.07  5218.1  509.07
#Mann=3,-1,0
  4709.1    0.05       0  4970.9    0.03       0  4976.9    0.05       0
Bank Sta=4941.8,5018.9
Exp/Cntr=0.3,0.1

Type RM Length L Ch R = 1,1188,113,113,113
BEGIN DESCRIPTION:
UNT 074 in LFCCL Watershed 2.0
END DESCRIPTION:
XS GIS Cut Line= 3
      2804624.98      7082625.00      2804275.00      7082725.00
      2804275.00      7083025.01
#Sta/Elev= 30
  4633.4  515.15  4636.0  515.15  4643.8  513.79  4650.3  511.15  4655.5  511.07
  4664.6  509.58  4675.0  509.09  4684.1  509.18  4689.3  509.66  4723.1  509.31
  4728.3  509.81  4747.8  509.64  4810.2  508.22  4868.7  505.47  4907.7  502.99
  4935.0  499.30  4946.7  496.71  4968.5  496.19  4980.5  495.93  4991.8  494.55
  4992.3  493.75  4997.3  493.75  4997.8  494.55  5029.0  496.19  5077.4  498.85
  5097.4  500.85  5127.4  502.44  5267.4  508.00  5287.4  509.05  5297.4  510.14
#Mann=3,-1,0
  4633.4    0.05       0  4991.8    0.03       0  4997.8    0.05       0
Bank Sta=4968.5,5029
Exp/Cntr=0.3,0.1

Type RM Length L Ch R = 1,1075,228,228,228
BEGIN DESCRIPTION:
XS3541A
END DESCRIPTION:
XS GIS Cut Line= 3
      2804216.48      7082512.17      2804169.60      7082704.88
      2804169.60      7082990.65
#Sta/Elev= 30
  4812.4  498.14  4835.3  498.26  4840.4  497.95  4897.6  498.33  4918.2  498.16
  4923.9  497.69  4929.0  496.85  4938.8  496.24  4959.4  496.16  4970.8  495.43
  4980.0  494.17  4988.2  493.54  5006.9  491.71  5007.4  490.91  5012.4  490.91
  5012.9  491.71  5019.8  493.54  5020.9  493.87  5030.9  494.68  5040.9  495.12
  5060.9  496.61  5080.9  499.01  5100.9  500.72  5110.9  501.06  5130.9  500.57
  5150.9  501.11  5210.9  504.06  5250.9  505.43  5270.9  505.52  5296.5  506.44
#Mann=3,-1,0
  4812.4    0.05       0  5006.9    0.03       0  5012.9    0.05       0
Bank Sta=4988.2,5019.8
Exp/Cntr=0.3,0.1

Type RM Length L Ch R = 1,847,255,255,255
BEGIN DESCRIPTION:
XS3540A
END DESCRIPTION:
XS GIS Cut Line= 3
      2804031.57      7082449.71      2803958.66      7082652.80
      2803903.97      7083025.23
#Sta/Elev= 30
  4794.9  493.93  4802.7  493.81  4821.8  494.62  4833.4  494.10  4906.8  494.49
  4915.0  495.13  4920.3  494.49  4938.6  493.90  4951.1  492.77  4970.5  492.33
  4986.6  490.70  4998.9  488.53  4999.4  487.73  5004.4  487.73  5004.9  488.53
  5007.2  490.18  5009.9  490.70  5043.2  492.33  5063.4  494.12  5069.4  495.29
  5083.7  495.93  5114.0  494.04  5134.1  493.50  5139.2  492.27  5154.4  493.63
  5174.6  494.26  5194.8  495.59  5203.9  496.80  5225.2  498.23  5387.1  501.49
#Mann=3,-1,0
  4794.9    0.05       0  4998.9    0.03       0  5004.9    0.05       0
Bank Sta=4986.6,5009.9
Exp/Cntr=0.3,0.1

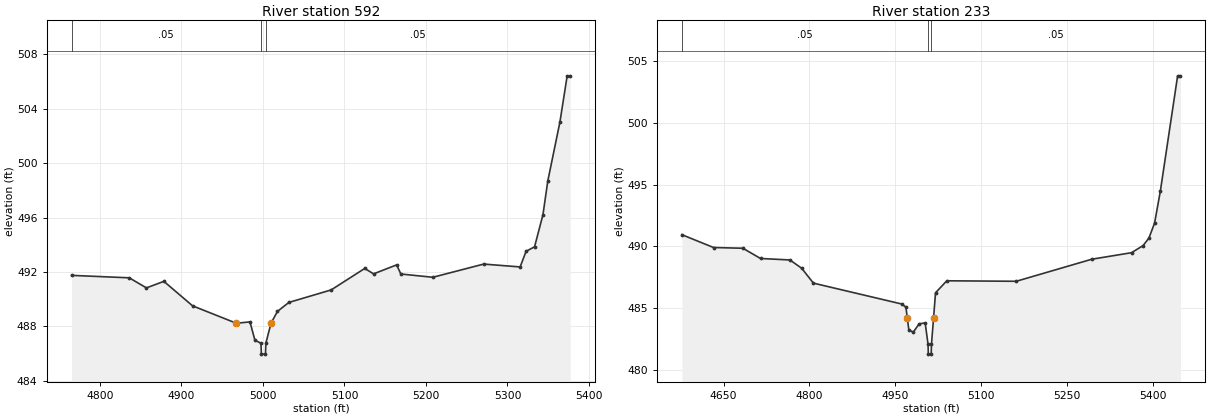
Type RM Length L Ch R = 1,592,359,359,359
BEGIN DESCRIPTION:
XS3539A
END DESCRIPTION:
XS GIS Cut Line= 3
      2803880.51      7082410.64      2803729.50      7082569.47
      2803622.72      7082947.10
#Sta/Elev= 30
  4765.3  491.75  4836.0  491.57  4857.1  490.83  4878.5  491.31  4913.7  489.51
  4967.4  488.23  4984.1  488.33  4990.2  486.98  4997.6  486.76  4998.1  485.96
  5003.1  485.96  5003.6  486.76  5009.9  488.23  5017.8  489.10  5031.8  489.76
  5083.7  490.68  5124.9  492.26  5135.7  491.86  5164.0  492.52  5169.2  491.85
  5208.4  491.61  5270.8  492.58  5315.5  492.37  5322.8  493.52  5333.2  493.85
  5343.5  496.21  5349.4  498.68  5364.3  503.02  5373.2  506.42  5376.9  506.42
#Mann=3,-1,0
  4765.3    0.05       0  4997.6    0.03       0  5003.6    0.05       0
Bank Sta=4967.4,5009.9
Exp/Cntr=0.3,0.1

Type RM Length L Ch R = 1,233,0,0,0
BEGIN DESCRIPTION:
UNT 074 in LFCCL Watershed 1.0
END DESCRIPTION:
XS GIS Cut Line= 3
      2803838.83      7082350.73      2803424.81      7082447.07
      2803479.50      7082889.82
#Sta/Elev= 30
  4577.2  490.94  4632.5  489.90  4683.8  489.84  4714.6  489.01  4765.9  488.89
  4786.5  488.22  4807.0  487.01  4961.0  485.32  4968.6  485.07  4971.0  484.21
  4973.8  483.19  4981.6  483.04  4991.8  483.71  5002.3  483.78  5007.3  482.05
  5007.8  481.25  5012.8  481.25  5013.3  482.05  5017.0  484.21  5020.4  486.23
  5040.1  487.20  5161.4  487.16  5293.4  488.95  5362.9  489.48  5383.1  490.06
  5393.2  490.66  5403.2  491.89  5413.3  494.50  5443.4  503.83  5448.4  503.83
#Mann=3,-1,0
  4577.2    0.05       0  5007.3    0.03       0  5013.3    0.05       0
Bank Sta=4971,5017
Exp/Cntr=0.3,0.1

Chan Stop Cuts=-1