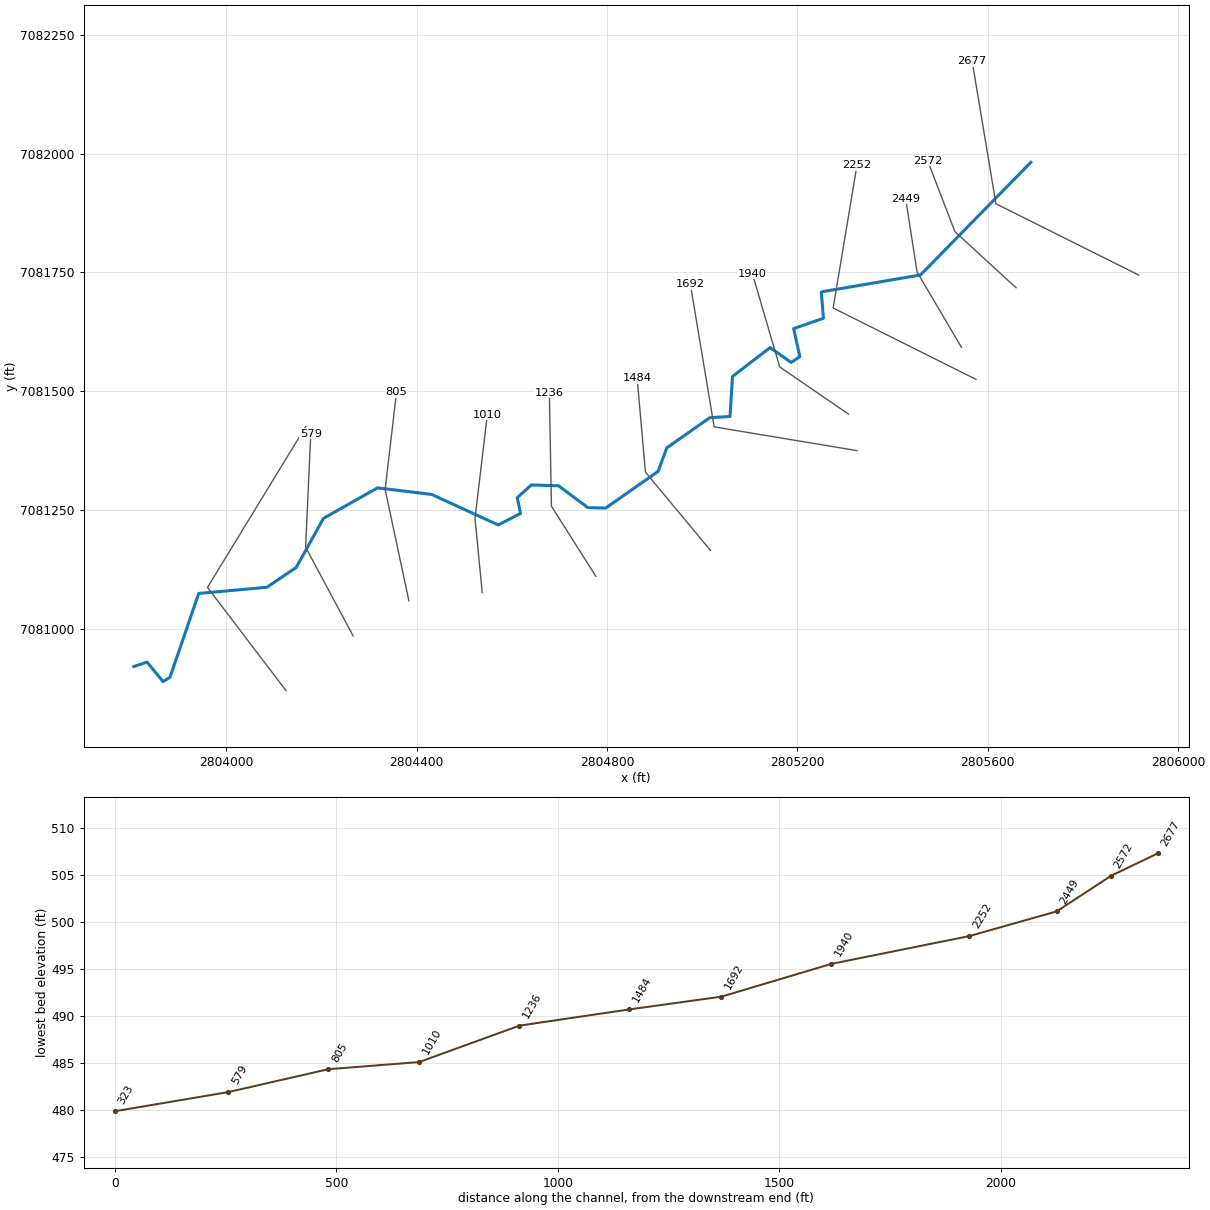
--- UNT 075 in LFCCL Watershed.prj (project) ---

Proj Title=UNT 075 in LFCCL Watershed Base Level Engineering
Current Plan=p01
Default Exp/Contr=0.3,0.1
English Units
Geom File=g01
Flow File=f01
Plan File=p01
BEGIN DESCRIPTION:
UNT 075 in LFCCL Watershed
END DESCRIPTION:

--- UNT 075 in LFCCL Watershed.p01 (plan) ---

Plan Title=Multiple Run
Short Identifier=Multiple
Geom File=g01
Flow File=f01
Subcritical Flow
K Sum by GR= 0
Std Step Tol= 0.01
Critical Tol= 0.01
Num of Std Step Trials= 20
Max Error Tol= 0.3
Flow Tol Ratio= 0.001
Split Flow NTrial= 30
Split Flow Tol= 0.02
Split Flow Ratio= 0.02
Log Output Level= 0
Friction Slope Method= 1
Unsteady Friction Slope Method= 2
Unsteady Bridges Friction Slope Method= 1
Parabolic Critical Depth
Global Vel Dist=  1 , 1 , 1
Global Log Level= 0
CheckData=True
Encroach Param= -1, 0, 0, 0
BEGIN DESCRIPTION:
Multiple Run
END DESCRIPTION:

--- UNT 075 in LFCCL Watershed.f01 (steady flow) ---

Flow Title=Multiple
Number of Profiles=7
Profile Names=10-year,25-year,50-year,1pct_min,100-year,1pct_plu,500-year
River Rch & RM= UNT 075 in LFCCL,Reach-1,2677
     134     160     179     100     199     397     244
Boundary for River Rch & Prof#=UNT 075 in LFCCL,Reach-1,1
Up Type=0
Dn Type=3
Dn Slope=0.005
Boundary for River Rch & Prof#=UNT 075 in LFCCL,Reach-1,2
Up Type=0
Dn Type=3
Dn Slope=0.005
Boundary for River Rch & Prof#=UNT 075 in LFCCL,Reach-1,3
Up Type=0
Dn Type=3
Dn Slope=0.005
Boundary for River Rch & Prof#=UNT 075 in LFCCL,Reach-1,4
Up Type=0
Dn Type=3
Dn Slope=0.005
Boundary for River Rch & Prof#=UNT 075 in LFCCL,Reach-1,5
Up Type=0
Dn Type=3
Dn Slope=0.005
Boundary for River Rch & Prof#=UNT 075 in LFCCL,Reach-1,6
Up Type=0
Dn Type=3
Dn Slope=0.005
Boundary for River Rch & Prof#=UNT 075 in LFCCL,Reach-1,7
Up Type=0
Dn Type=3
Dn Slope=0.005

--- UNT 075 in LFCCL Watershed.g01 (geometry) ---

Geom Title=Existing Conditions

River Reach=UNT 075 in LFCCL,Reach-1
Reach XY= 30
      2805690.25      7081981.56      2805458.48      7081744.58
      2805250.15      7081708.99      2805254.49      7081653.44
      2805191.99      7081631.74      2805205.01      7081572.71
      2805186.78      7081560.56      2805142.51      7081591.81
      2805063.52      7081531.04      2805058.31      7081446.84
      2805015.77      7081444.24      2804925.50      7081380.87
      2804907.27      7081331.39      2804797.02      7081254.13
      2804759.70      7081255.00      2804698.07      7081301.01
      2804640.77      7081302.74      2804611.26      7081275.83
      2804618.21      7081242.85      2804571.33      7081218.54
      2804431.57      7081282.78      2804317.86      7081296.67
      2804204.14      7081232.43      2804146.85      7081129.13
      2804085.22      7081087.47      2803941.99      7081074.44
      2803881.55      7080897.75      2803867.11      7080889.09
      2803833.42      7080930.02      2803805.59      7080920.71

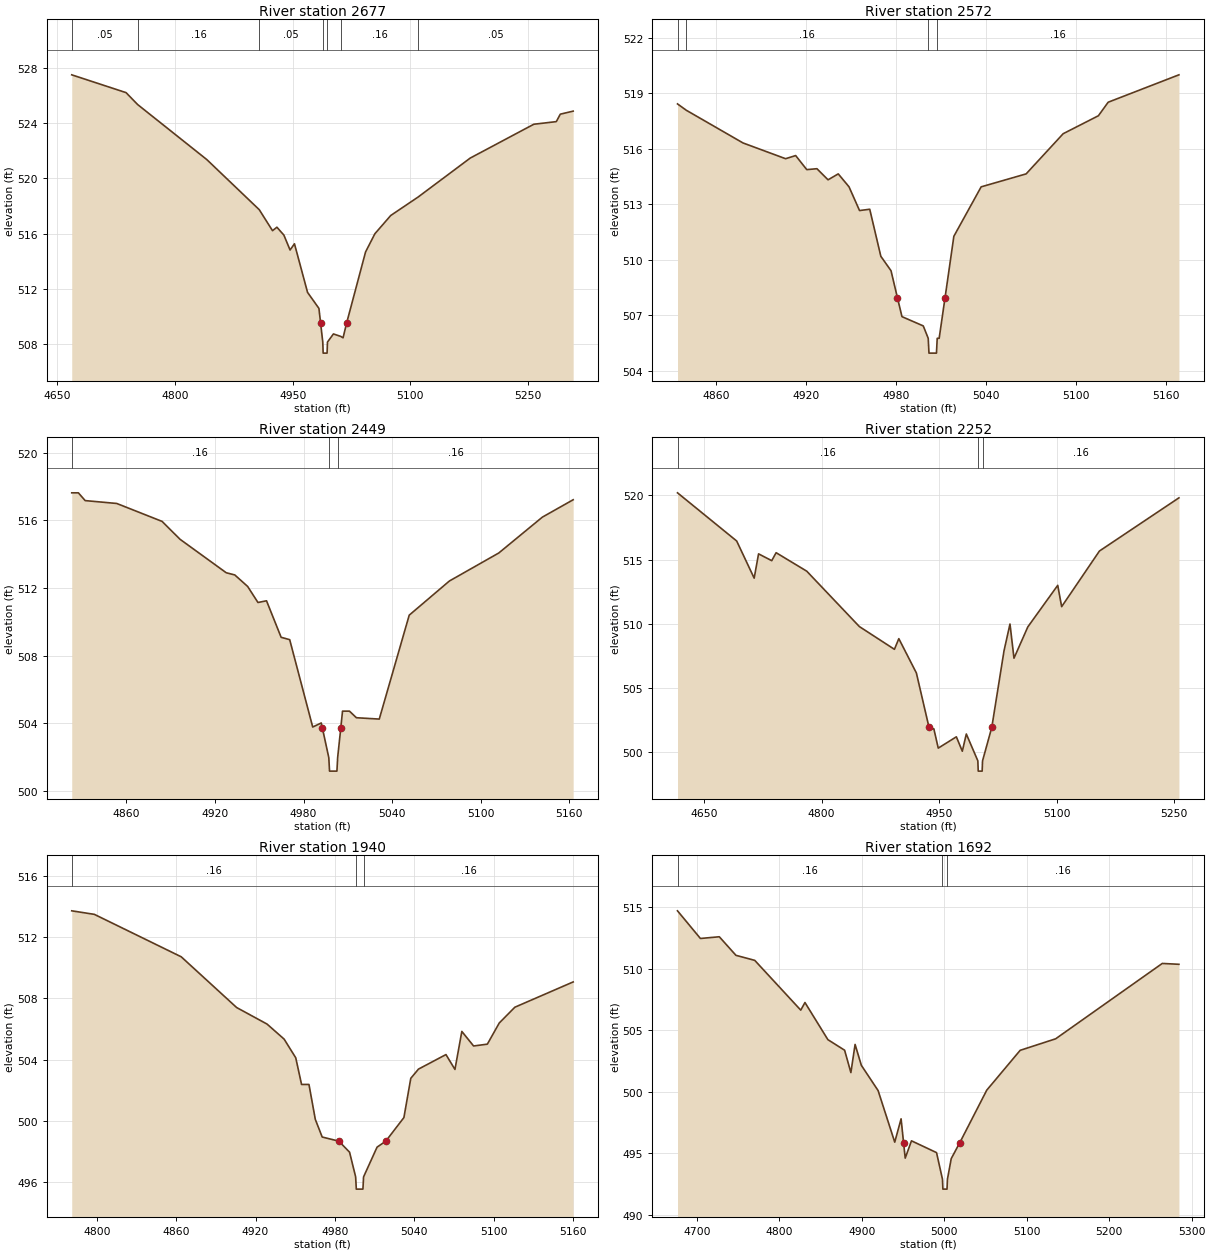
Type RM Length L Ch R = 1,2677,105,105,105
BEGIN DESCRIPTION:
UNT 075 in LFCCL Watershed 5.0
END DESCRIPTION:
XS GIS Cut Line= 3
      2805917.02      7081744.44      2805617.01      7081894.44
      2805567.01      7082194.49
#Sta/Elev= 30
  4668.2  527.50  4737.5  526.21  4752.2  525.35  4840.5  521.36  4907.4  517.73
  4924.3  516.21  4929.9  516.46  4938.8  515.89  4946.7  514.81  4952.3  515.26
  4969.0  511.74  4983.5  510.58  4985.7  509.49  4988.4  508.14  4988.9  507.34
  4993.9  507.34  4994.4  508.14  5002.0  508.73  5011.4  508.55  5014.3  508.45
  5018.7  509.49  5043.0  514.67  5054.9  515.99  5075.1  517.31  5110.1  518.65
  5176.5  521.47  5257.6  523.92  5286.3  524.11  5291.4  524.65  5307.8  524.87
#Mann=7,-1,0
  4668.2    0.05       0  4752.2    0.16       0  4907.4    0.05       0
  4988.4    0.03       0  4994.4    0.05       0  5011.4    0.16       0
  5110.1    0.05       0
Bank Sta=4985.7,5018.7
Exp/Cntr=0.3,0.1

Type RM Length L Ch R = 1,2572,123,123,123
BEGIN DESCRIPTION:
XS3542A
END DESCRIPTION:
XS GIS Cut Line= 3
      2805659.25      7081717.74      2805530.75      7081835.83
      2805473.47      7081985.10
#Sta/Elev= 30
  4834.0  518.42  4839.8  518.08  4877.7  516.31  4906.1  515.46  4912.8  515.63
  4920.2  514.87  4927.0  514.92  4934.4  514.32  4941.2  514.64  4948.4  513.94
  4955.4  512.66  4962.2  512.73  4969.6  510.19  4976.4  509.41  4980.7  507.94
  4983.7  506.93  4997.9  506.43  5001.2  505.76  5001.7  504.96  5006.7  504.96
  5007.2  505.76  5008.5  505.76  5012.4  507.94  5018.3  511.27  5036.5  513.94
  5066.5  514.64  5091.2  516.81  5114.7  517.78  5121.2  518.51  5168.4  519.99
#Mann=4,-1,0
  4834.0    0.05       0  4839.8    0.16       0  5001.2    0.07       0
  5007.2    0.16       0
Bank Sta=4980.7,5012.4
Exp/Cntr=0.3,0.1

Type RM Length L Ch R = 1,2449,197,197,197
BEGIN DESCRIPTION:
XS3544A
END DESCRIPTION:
XS GIS Cut Line= 3
      2805544.66      7081592.30      2805451.32      7081750.76
      2805427.45      7081904.81
#Sta/Elev= 30
  4822.9  517.63  4827.4  517.63  4832.0  517.17  4853.4  517.00  4884.1  515.94
  4896.3  514.88  4927.6  512.90  4933.4  512.77  4942.1  512.09  4949.1  511.14
  4954.9  511.24  4964.8  509.08  4970.6  508.94  4986.2  503.77  4992.0  504.01
  4992.8  503.69  4997.1  501.96  4997.6  501.16  5002.6  501.16  5003.1  501.96
  5005.2  503.69  5006.4  504.71  5011.1  504.71  5015.8  504.32  5031.3  504.24
  5051.6  510.39  5078.8  512.41  5112.3  514.07  5141.8  516.19  5162.7  517.22
#Mann=3,-1,0
  4822.9    0.16       0  4997.1    0.07       0  5003.1    0.16       0
Bank Sta=4992.8,5005.2
Exp/Cntr=0.3,0.1

Type RM Length L Ch R = 1,2252,312,312,312
BEGIN DESCRIPTION:
UNT 075 in LFCCL Watershed 4.0
END DESCRIPTION:
XS GIS Cut Line= 3
      2805575.02      7081524.99      2805275.00      7081675.00
      2805325.01      7081975.03
#Sta/Elev= 30
  4616.3  520.19  4691.8  516.44  4714.1  513.55  4719.7  515.44  4736.5  514.91
  4742.1  515.53  4781.2  514.09  4848.3  509.78  4893.0  508.01  4898.6  508.84
  4921.0  506.17  4937.1  501.94  4943.3  501.82  4948.9  500.32  4972.0  501.20
  4979.6  500.08  4984.7  501.42  4999.4  499.33  4999.9  498.53  5004.9  498.53
  5005.4  499.33  5017.2  501.94  5032.8  507.90  5040.4  509.98  5045.5  507.32
  5063.2  509.76  5101.3  512.99  5106.3  511.33  5154.5  515.66  5255.9  519.80
#Mann=3,-1,0
  4616.3    0.16       0  4999.4    0.07       0  5005.4    0.16       0
Bank Sta=4937.1,5017.2
Exp/Cntr=0.3,0.1

Type RM Length L Ch R = 1,1940,248,248,248
BEGIN DESCRIPTION:
XS3543A
END DESCRIPTION:
XS GIS Cut Line= 3
      2805306.78      7081452.15      2805162.69      7081551.11
      2805105.39      7081747.31
#Sta/Elev= 30
  4781.0  513.72  4798.1  513.49  4863.8  510.72  4905.7  507.41  4928.7  506.33
  4941.6  505.35  4950.4  504.13  4954.8  502.39  4960.4  502.39  4965.2  500.11
  4970.4  498.96  4983.0  498.69  4991.1  497.97  4995.7  496.36  4996.2  495.56
  5001.2  495.56  5001.7  496.36  5011.9  498.30  5018.5  498.69  5032.2  500.23
  5037.4  502.79  5043.2  503.39  5064.0  504.34  5070.8  503.37  5076.0  505.85
  5084.9  504.90  5095.3  505.02  5104.3  506.40  5116.1  507.43  5160.2  509.08
#Mann=3,-1,0
  4781.0    0.16       0  4995.7    0.07       0  5001.7    0.16       0
Bank Sta=4983,5018.5
Exp/Cntr=0.3,0.1

Type RM Length L Ch R = 1,1692,208,208,208
BEGIN DESCRIPTION:
UNT 075 in LFCCL Watershed 3.0
END DESCRIPTION:
XS GIS Cut Line= 3
      2805324.96      7081375.01      2805025.00      7081425.00
      2804975.01      7081724.96
#Sta/Elev= 30
  4676.4  514.71  4704.2  512.46  4727.1  512.60  4747.3  511.09  4770.1  510.68
  4825.9  506.63  4831.0  507.25  4858.8  504.23  4879.1  503.37  4886.7  501.55
  4891.8  503.84  4899.4  502.14  4919.7  500.09  4939.9  495.89  4947.6  497.79
  4950.6  495.85  4952.6  494.59  4960.2  496.00  4990.6  495.04  4997.8  492.87
  4998.3  492.07  5003.3  492.07  5003.8  492.87  5008.4  494.55  5018.8  495.85
  5051.5  500.12  5092.0  503.36  5135.1  504.30  5264.4  510.43  5284.6  510.36
#Mann=3,-1,0
  4676.4    0.16       0  4997.8    0.07       0  5003.8    0.16       0
Bank Sta=4950.6,5018.8
Exp/Cntr=0.3,0.1

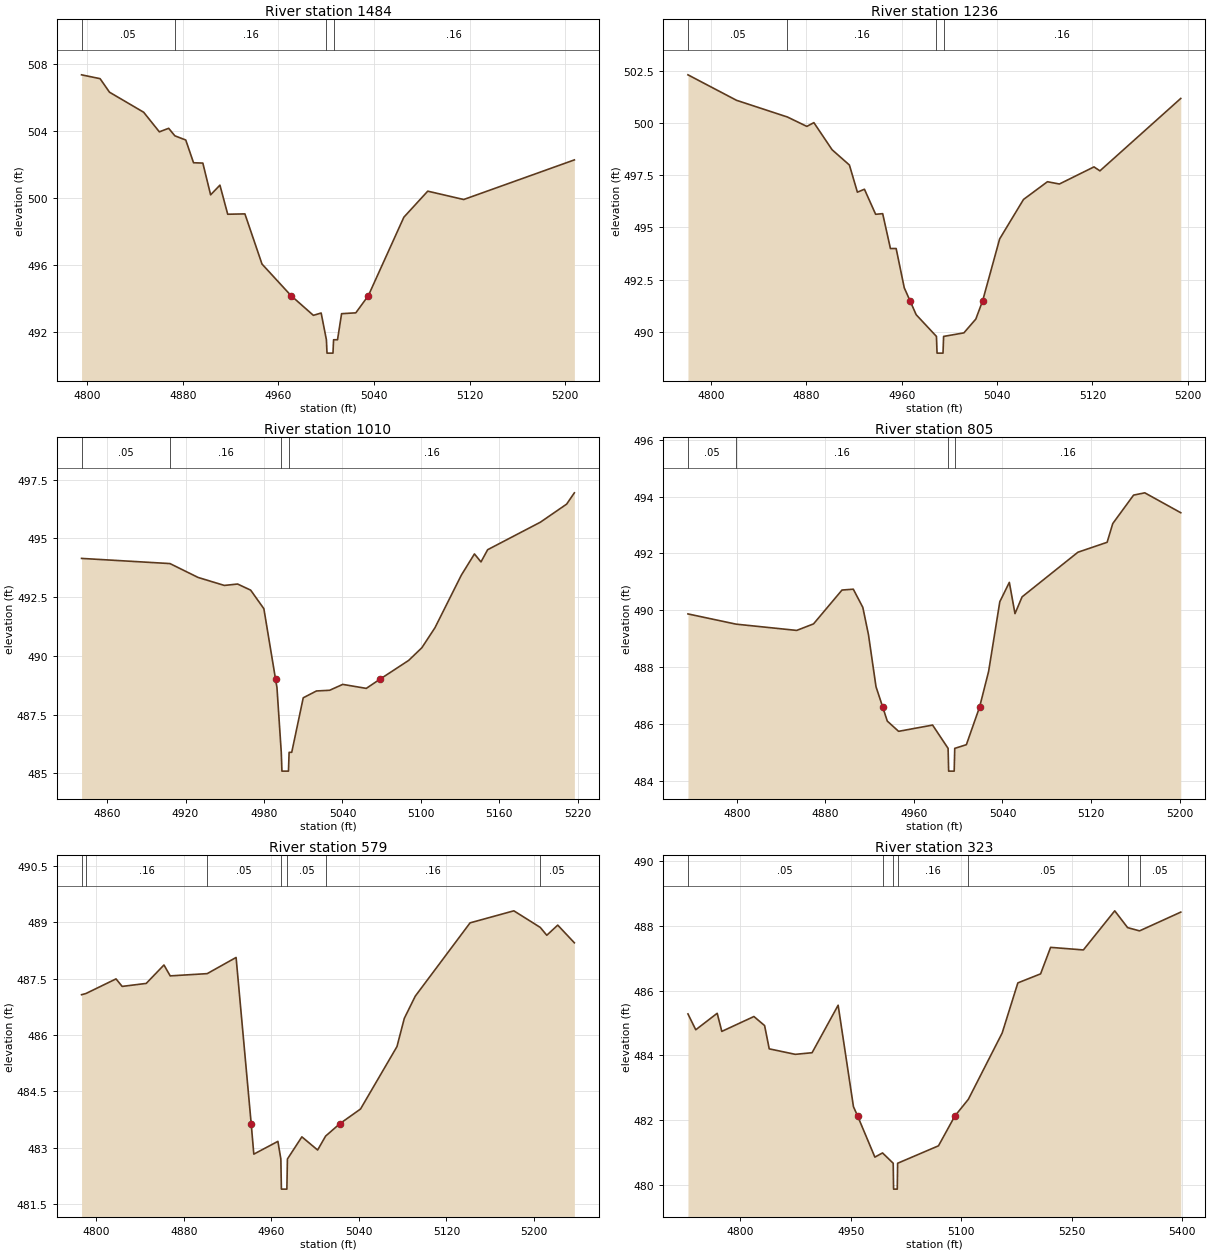
Type RM Length L Ch R = 1,1484,248,248,248
BEGIN DESCRIPTION:
XS3545A
END DESCRIPTION:
XS GIS Cut Line= 3
      2805017.27      7081164.85      2804880.57      7081329.75
      2804863.21      7081527.19
#Sta/Elev= 30
  4795.2  507.36  4810.7  507.13  4818.6  506.32  4847.2  505.12  4860.3  503.95
  4868.1  504.16  4873.3  503.71  4882.4  503.46  4888.9  502.10  4896.7  502.08
  4903.2  500.18  4911.0  500.76  4917.5  499.02  4931.9  499.04  4946.2  496.04
  4970.5  494.15  4989.2  492.97  4995.7  493.11  5000.1  491.51  5000.6  490.71
  5005.6  490.71  5006.1  491.51  5009.4  491.51  5012.8  493.07  5024.7  493.12
  5035.2  494.15  5064.9  498.84  5084.9  500.40  5115.0  499.90  5207.6  502.27
#Mann=4,-1,0
  4795.2    0.05       0  4873.3    0.16       0  5000.1    0.07       0
  5006.1    0.16       0
Bank Sta=4970.5,5035.2
Exp/Cntr=0.3,0.1

Type RM Length L Ch R = 1,1236,226,226,226
BEGIN DESCRIPTION:
XS3546A
END DESCRIPTION:
XS GIS Cut Line= 3
      2804776.39      7081110.59      2804683.09      7081258.14
      2804678.75      7081496.83
#Sta/Elev= 30
  4780.8  502.31  4821.5  501.09  4864.2  500.29  4880.5  499.84  4886.4  500.02
  4901.7  498.72  4916.2  497.99  4922.9  496.69  4928.8  496.83  4938.2  495.63
  4944.1  495.66  4950.6  493.99  4955.4  493.99  4962.2  492.11  4967.1  491.48
  4972.2  490.82  4989.2  489.78  4989.7  488.98  4994.7  488.98  4995.2  489.78
  5012.2  489.95  5022.2  490.61  5027.9  491.48  5042.2  494.45  5062.2  496.34
  5082.3  497.19  5092.3  497.08  5121.3  497.90  5126.3  497.71  5194.1  501.18
#Mann=4,-1,0
  4780.8    0.05       0  4864.2    0.16       0  4989.2    0.07       0
  4995.2    0.16       0
Bank Sta=4967.1,5027.9
Exp/Cntr=0.3,0.1

Type RM Length L Ch R = 1,1010,205,205,205
BEGIN DESCRIPTION:
XS3549A
END DESCRIPTION:
XS GIS Cut Line= 3
      2804537.69      7081076.29      2804522.50      7081232.53
      2804548.43      7081450.82
#Sta/Elev= 30
  4840.5  494.15  4908.1  493.93  4929.6  493.34  4949.7  493.00  4959.8  493.06
  4969.8  492.80  4979.9  492.01  4988.8  489.02  4989.9  488.66  4993.2  485.90
  4993.7  485.10  4998.7  485.10  4999.2  485.90  5001.2  485.90  5010.0  488.22
  5020.1  488.51  5030.2  488.54  5040.2  488.79  5058.2  488.62  5068.9  489.02
  5090.6  489.81  5100.7  490.35  5110.7  491.20  5130.9  493.44  5140.9  494.34
  5145.9  494.00  5151.0  494.52  5191.3  495.69  5211.4  496.46  5217.3  496.94
#Mann=4,-1,0
  4840.5    0.05       0  4908.1    0.16       0  4993.2    0.07       0
  4999.2    0.16       0
Bank Sta=4988.8,5068.9
Exp/Cntr=0.3,0.1

Type RM Length L Ch R = 1,805,226,226,226
BEGIN DESCRIPTION:
XS3548A
END DESCRIPTION:
XS GIS Cut Line= 3
      2804383.60      7081058.95      2804333.70      7081293.29
      2804357.57      7081497.31
#Sta/Elev= 30
  4756.0  489.87  4799.5  489.51  4854.2  489.29  4869.4  489.52  4895.1  490.71
  4905.3  490.74  4913.9  490.10  4919.0  489.14  4925.8  487.31  4931.9  486.59
  4936.0  486.10  4946.2  485.74  4976.9  485.96  4990.9  485.14  4991.4  484.34
  4996.4  484.34  4996.9  485.14  5007.4  485.27  5019.3  486.59  5027.5  487.85
  5037.6  490.30  5046.2  490.98  5051.3  489.88  5057.7  490.47  5108.1  492.04
  5134.5  492.39  5139.6  493.05  5158.4  494.05  5168.5  494.13  5201.0  493.43
#Mann=4,-1,0
  4756.0    0.05       0  4799.5    0.16       0  4990.9    0.07       0
  4996.9    0.16       0
Bank Sta=4931.9,5019.3
Exp/Cntr=0.3,0.1

Type RM Length L Ch R = 1,579,256,256,256
BEGIN DESCRIPTION:
XS3547A
END DESCRIPTION:
XS GIS Cut Line= 3
      2804266.40      7080985.18      2804166.60      7081171.77
      2804177.44      7081410.22
#Sta/Elev= 30
  4786.6  487.07  4790.5  487.10  4818.1  487.49  4823.7  487.29  4845.7  487.37
  4861.9  487.86  4867.6  487.57  4901.4  487.63  4927.8  488.06  4941.6  483.64
  4944.0  482.83  4966.0  483.17  4968.7  482.70  4969.2  481.90  4974.2  481.90
  4974.7  482.70  4987.9  483.29  5002.3  482.94  5009.6  483.31  5022.6  483.64
  5041.5  484.03  5074.8  485.69  5081.5  486.44  5091.5  487.03  5141.6  488.98
  5181.6  489.30  5205.7  488.86  5211.7  488.65  5221.7  488.92  5236.9  488.45
#Mann=7,-1,0
  4786.6    0.05       0  4790.5    0.16       0  4901.4    0.05       0
  4968.7    0.03       0  4974.7    0.05       0  5009.6    0.16       0
  5205.7    0.05       0
Bank Sta=4941.6,5022.6
Exp/Cntr=0.3,0.1

Type RM Length L Ch R = 1,323,0,0,0
BEGIN DESCRIPTION:
UNT 075 in LFCCL Watershed 1.0
END DESCRIPTION:
XS GIS Cut Line= 3
      2804125.34      7080870.14      2803960.43      7081087.13
      2804167.04      7081425.97
#Sta/Elev= 30
  4728.8  485.28  4739.4  484.79  4768.5  485.30  4774.8  484.74  4818.4  485.20
  4832.9  484.92  4839.2  484.20  4874.6  484.03  4897.4  484.08  4932.8  485.55
  4953.6  482.41  4959.3  482.12  4982.7  480.85  4993.1  480.98  5007.6  480.66
  5008.1  479.86  5013.1  479.86  5013.6  480.66  5069.1  481.20  5091.3  482.12
  5109.7  482.64  5155.6  484.69  5176.9  486.24  5207.8  486.52  5221.4  487.34
  5265.9  487.26  5308.5  488.47  5326.0  487.95  5342.2  487.85  5398.2  488.43
#Mann=7,-1,0
  4728.8    0.05       0  4993.1    0.16       0  5007.6    0.07       0
  5013.6    0.16       0  5109.7    0.05       0  5326.0    0.16       0
  5342.2    0.05       0
Bank Sta=4959.3,5091.3
Exp/Cntr=0.3,0.1

Chan Stop Cuts=-1