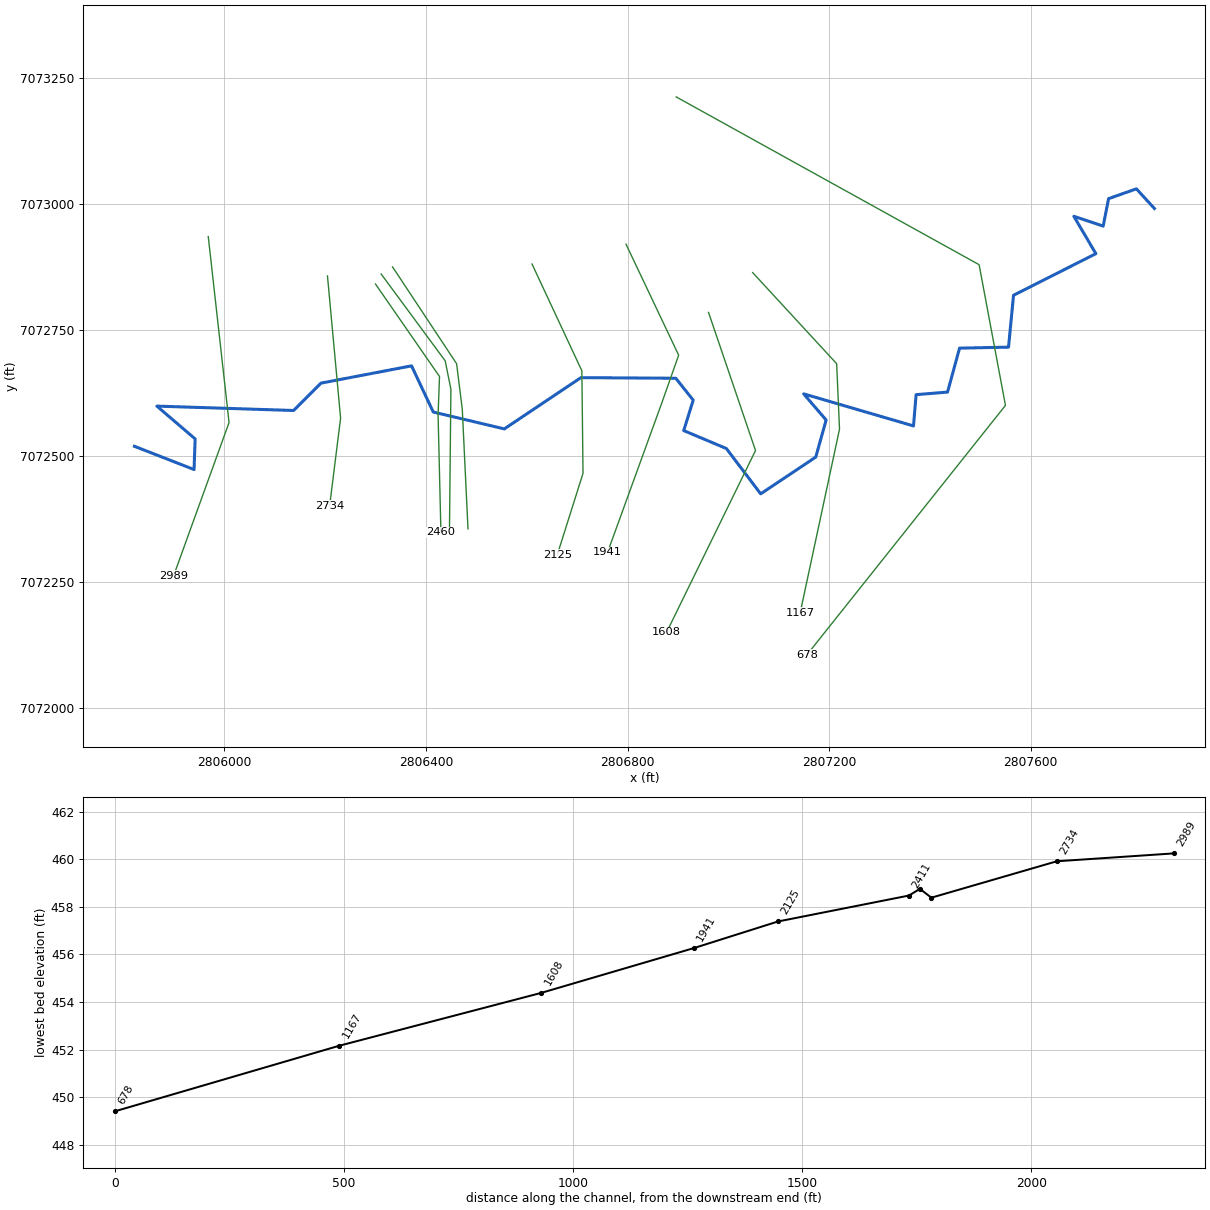
--- UNT 076 in LFCCL Watershed.prj (project) ---

Proj Title=UNT 076 in LFCCL Watershed Base Level Engineering
Current Plan=p01
Default Exp/Contr=0.3,0.1
English Units
Geom File=g01
Flow File=f01
Plan File=p01
BEGIN DESCRIPTION:
UNT 076 in LFCCL Watershed
END DESCRIPTION:

--- UNT 076 in LFCCL Watershed.p01 (plan) ---

Plan Title=Multiple Run
Short Identifier=Multiple
Geom File=g01
Flow File=f01
Subcritical Flow
K Sum by GR= 0
Std Step Tol= 0.01
Critical Tol= 0.01
Num of Std Step Trials= 20
Max Error Tol= 0.3
Flow Tol Ratio= 0.001
Split Flow NTrial= 30
Split Flow Tol= 0.02
Split Flow Ratio= 0.02
Log Output Level= 0
Friction Slope Method= 1
Unsteady Friction Slope Method= 2
Unsteady Bridges Friction Slope Method= 1
Parabolic Critical Depth
Global Vel Dist=  1 , 1 , 1
Global Log Level= 0
CheckData=True
Encroach Param= -1, 0, 0, 0
BEGIN DESCRIPTION:
Multiple Run
END DESCRIPTION:

--- UNT 076 in LFCCL Watershed.f01 (steady flow) ---

Flow Title=Multiple
Number of Profiles=7
Profile Names=10-year,25-year,50-year,1pct_min,100-year,1pct_plu,500-year
River Rch & RM= UNT 076 in LFCCL,Reach-1,2989
     579     763     910     538    1074    2142    1490
Boundary for River Rch & Prof#=UNT 076 in LFCCL,Reach-1,1
Up Type=0
Dn Type=3
Dn Slope=0.005
Boundary for River Rch & Prof#=UNT 076 in LFCCL,Reach-1,2
Up Type=0
Dn Type=3
Dn Slope=0.005
Boundary for River Rch & Prof#=UNT 076 in LFCCL,Reach-1,3
Up Type=0
Dn Type=3
Dn Slope=0.005
Boundary for River Rch & Prof#=UNT 076 in LFCCL,Reach-1,4
Up Type=0
Dn Type=3
Dn Slope=0.005
Boundary for River Rch & Prof#=UNT 076 in LFCCL,Reach-1,5
Up Type=0
Dn Type=3
Dn Slope=0.005
Boundary for River Rch & Prof#=UNT 076 in LFCCL,Reach-1,6
Up Type=0
Dn Type=3
Dn Slope=0.005
Boundary for River Rch & Prof#=UNT 076 in LFCCL,Reach-1,7
Up Type=0
Dn Type=3
Dn Slope=0.005

--- UNT 076 in LFCCL Watershed.g01 (geometry) ---

Geom Title=Existing Conditions

River Reach=UNT 076 in LFCCL,Reach-1
Reach XY= 30
      2805821.54      7072518.84      2805939.88      7072472.69
      2805942.05      7072533.46      2805866.10      7072598.56
      2806137.37      7072589.88      2806191.62      7072644.13
      2806371.46      7072678.45      2806414.57      7072586.82
      2806555.58      7072553.33      2806707.51      7072655.05
      2806895.81      7072653.87      2806930.39      7072610.42
      2806911.56      7072550.00      2806996.22      7072514.39
      2807064.23      7072424.48      2807173.58      7072497.44
      2807194.13      7072570.98      2807149.58      7072622.87
      2807367.51      7072559.25      2807372.69      7072621.30
      2807435.10      7072626.39      2807458.91      7072713.60
      2807556.08      7072715.57      2807566.02      7072818.51
      2807729.40      7072901.07      2807685.77      7072975.17
      2807743.92      7072955.77      2807754.65      7073010.27
      2807809.86      7073029.70      2807845.59      7072990.71

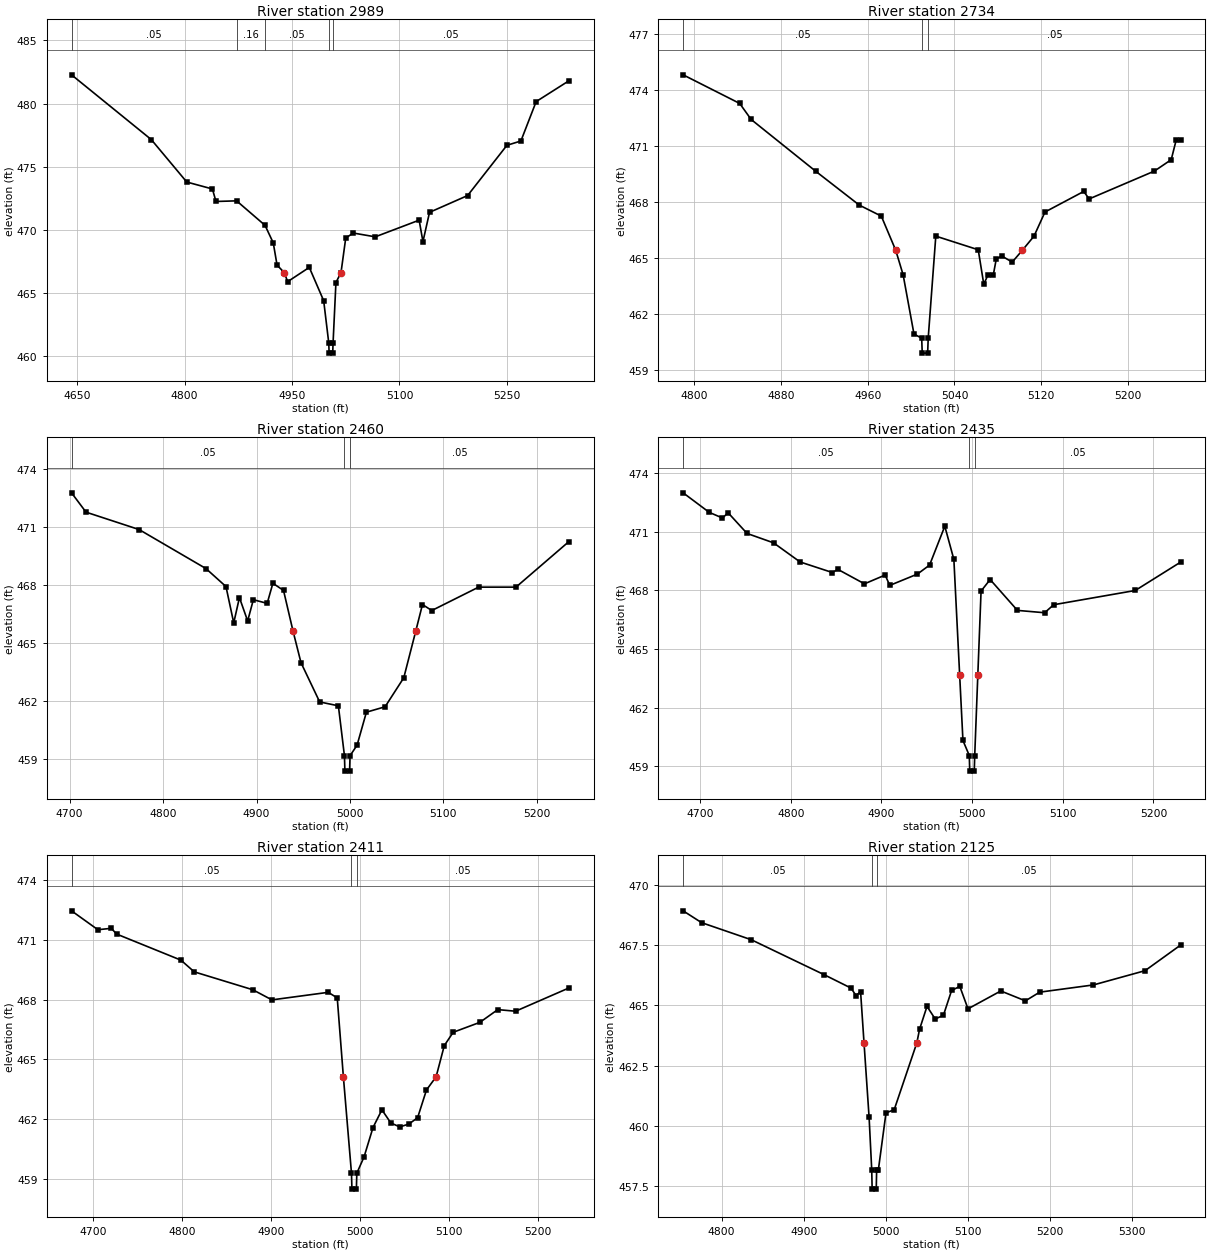
Type RM Length L Ch R = 1,2989,255,255,255
BEGIN DESCRIPTION:
UNT 076 in LFCCL Watershed 3.0
END DESCRIPTION:
XS GIS Cut Line= 3
      2805968.09      7072934.94      2806009.33      7072566.01
      2805899.34      7072261.92
#Sta/Elev= 30
  4642.1  482.28  4753.5  477.15  4803.0  473.79  4838.8  473.24  4843.8  472.25
  4872.6  472.30  4912.3  470.36  4923.8  468.97  4929.1  467.21  4939.1  466.62
  4943.9  465.90  4974.1  467.03  4994.2  464.39  5001.3  461.04  5001.8  460.24
  5006.8  460.24  5007.3  461.04  5011.3  465.83  5018.4  466.62  5025.0  469.36
  5035.6  469.75  5066.2  469.45  5127.5  470.77  5132.8  469.07  5142.0  471.39
  5195.2  472.72  5250.1  476.70  5269.6  477.04  5290.9  480.16  5336.7  481.81
#Mann=5,-1,0
  4642.1    0.05       0  4872.6    0.16       0  4912.3    0.05       0
  5001.3    0.03       0  5007.3    0.05       0
Bank Sta=4939.1,5018.4
Exp/Cntr=0.3,0.1

Type RM Length L Ch R = 1,2734,274,274,274
BEGIN DESCRIPTION:
Mapping XS 4edbb1a1
END DESCRIPTION:
XS GIS Cut Line= 3
      2806204.64      7072856.83      2806230.68      7072574.69
      2806208.98      7072401.09
#Sta/Elev= 30
  4790.0  474.80  4842.1  473.27  4852.7  472.41  4912.4  469.63  4952.3  467.83
  4972.6  467.24  4985.9  465.41  4992.7  464.10  5002.7  460.93  5009.8  460.71
  5010.3  459.91  5015.3  459.91  5015.8  460.71  5022.8  466.17  5061.9  465.44
  5067.0  463.60  5070.7  464.07  5075.7  464.07  5078.5  464.94  5083.5  465.11
  5093.2  464.78  5102.5  465.41  5113.3  466.17  5123.4  467.46  5159.1  468.56
  5164.1  468.16  5224.2  469.65  5239.7  470.26  5244.2  471.29  5248.3  471.29
#Mann=3,-1,0
  4790.0    0.05       0  5009.8    0.03       0  5015.8    0.05       0
Bank Sta=4985.9,5102.5
Exp/Cntr=0.3,0.1

Type RM Length L Ch R = 1,2460,25,25,25
BEGIN DESCRIPTION:
XS3550A
END DESCRIPTION:
XS GIS Cut Line= 4
      2806299.88      7072840.87      2806426.97      7072657.30
      2806424.14      7072581.04      2806429.75      7072348.29
#Sta/Elev= 30
  4702.0  472.78  4717.5  471.78  4774.3  470.88  4845.9  468.86  4867.3  467.93
  4875.6  466.05  4881.7  467.36  4890.5  466.15  4896.6  467.25  4911.4  467.06
  4917.5  468.10  4928.9  467.73  4939.1  465.62  4947.6  463.99  4967.6  461.96
  4987.6  461.76  4994.1  459.18  4994.6  458.38  4999.6  458.38  5000.1  459.18
  5007.6  459.72  5017.6  461.43  5037.6  461.71  5057.6  463.21  5070.4  465.62
  5077.6  467.00  5087.6  466.69  5137.7  467.90  5177.7  467.90  5234.4  470.26
#Mann=3,-1,0
  4702.0    0.05       0  4994.1    0.03       0  5000.1    0.05       0
Bank Sta=4939.1,5070.4
Exp/Cntr=0.3,0.1

Type RM Length L Ch R = 1,2435,24,24,24
BEGIN DESCRIPTION:
XS3551A
END DESCRIPTION:
XS GIS Cut Line= 4
      2806311.14      7072860.71      2806438.27      7072688.37
      2806449.57      7072631.88      2806446.74      7072355.06
#Sta/Elev= 30
  4681.3  473.00  4710.1  472.00  4724.7  471.71  4730.9  471.98  4751.8  470.92
  4781.0  470.44  4810.3  469.46  4845.8  468.92  4852.0  469.08  4881.3  468.34
  4904.1  468.79  4909.2  468.26  4939.7  468.84  4953.1  469.30  4969.9  471.29
  4979.9  469.59  4986.3  463.66  4989.9  460.32  4996.9  459.55  4997.4  458.75
  5002.4  458.75  5002.9  459.55  5006.3  463.66  5009.9  467.97  5019.9  468.56
  5050.0  466.98  5080.0  466.86  5090.0  467.27  5180.0  468.00  5229.9  469.45
#Mann=3,-1,0
  4681.3    0.05       0  4996.9    0.03       0  5002.9    0.05       0
Bank Sta=4986.3,5006.3
Exp/Cntr=0.3,0.1

Type RM Length L Ch R = 1,2411,286,286,286
BEGIN DESCRIPTION:
XS3552A
END DESCRIPTION:
XS GIS Cut Line= 4
      2806333.74      7072874.83      2806460.86      7072682.73
      2806472.16      7072592.34      2806483.46      7072355.06
#Sta/Elev= 30
  4676.2  472.47  4705.8  471.52  4720.9  471.59  4726.9  471.30  4799.1  469.99
  4814.1  469.40  4879.9  468.50  4901.4  467.99  4964.7  468.37  4974.8  468.09
  4981.7  464.12  4990.8  459.27  4991.3  458.47  4996.3  458.47  4996.8  459.27
  5005.0  460.10  5015.0  461.57  5025.0  462.46  5035.0  461.80  5045.0  461.60
  5055.1  461.74  5065.1  462.06  5075.1  463.46  5085.9  464.12  5095.1  465.69
  5105.1  466.36  5135.1  466.86  5155.2  467.50  5175.2  467.42  5235.2  468.59
#Mann=3,-1,0
  4676.2    0.05       0  4990.8    0.03       0  4996.8    0.05       0
Bank Sta=4981.7,5085.9
Exp/Cntr=0.3,0.1

Type RM Length L Ch R = 1,2125,184,184,184
BEGIN DESCRIPTION:
XS3553A
END DESCRIPTION:
XS GIS Cut Line= 4
      2806610.56      7072880.48      2806709.43      7072668.60
      2806711.72      7072465.19      2806660.72      7072303.69
#Sta/Elev= 30
  4753.0  468.91  4775.5  468.42  4836.3  467.71  4924.6  466.27  4957.7  465.71
  4963.8  465.40  4969.4  465.56  4973.6  463.44  4979.8  460.35  4983.0  458.18
  4983.5  457.38  4988.5  457.38  4989.0  458.18  4991.1  458.18  5000.4  460.54
  5010.4  460.67  5038.0  463.44  5041.3  464.00  5050.4  464.95  5060.4  464.43
  5070.4  464.58  5080.4  465.61  5090.4  465.78  5100.4  464.85  5140.4  465.59
  5170.4  465.18  5187.8  465.54  5253.4  465.84  5316.3  466.43  5359.6  467.49
#Mann=3,-1,0
  4753.0    0.05       0  4983.0    0.03       0  4989.0    0.05       0
Bank Sta=4973.6,5038
Exp/Cntr=0.3,0.1

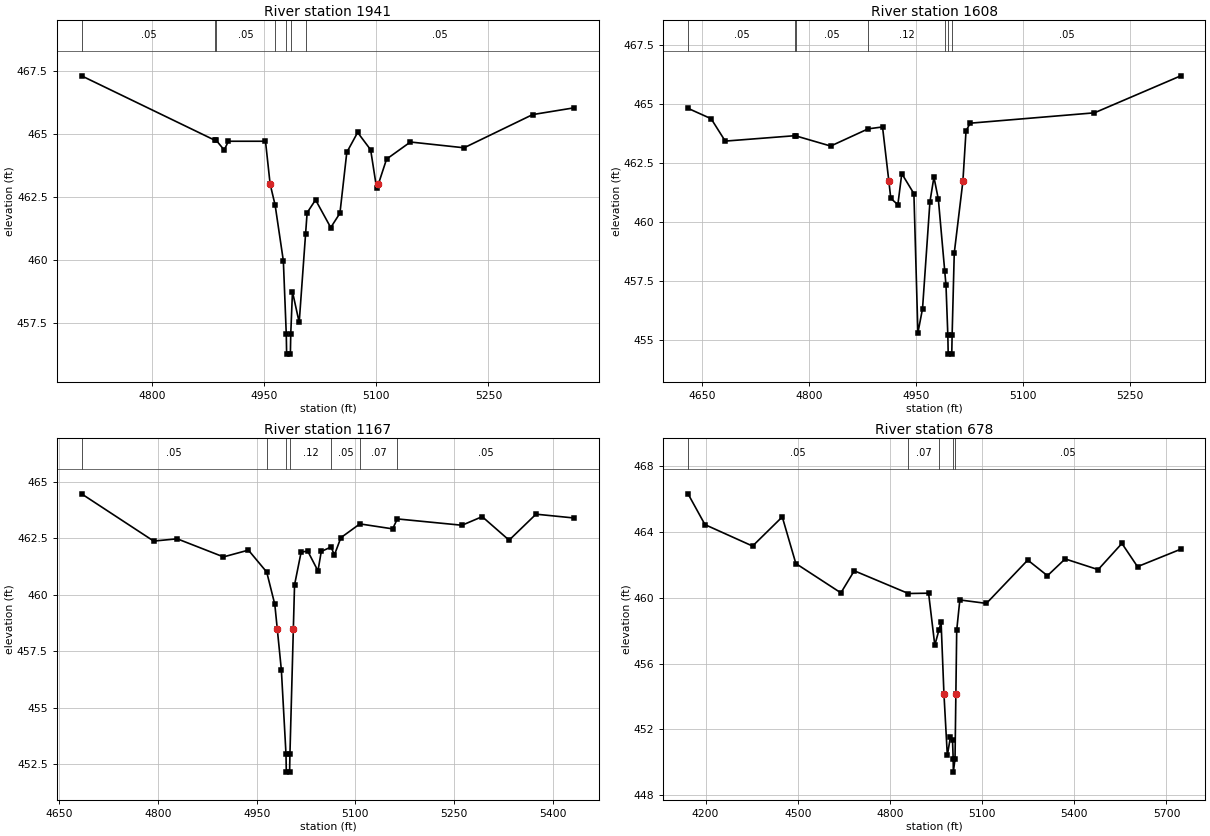
Type RM Length L Ch R = 1,1941,333,333,333
BEGIN DESCRIPTION:
XS3555A
END DESCRIPTION:
XS GIS Cut Line= 4
      2806797.01      7072919.97      2806901.51      7072699.67
      2806867.62      7072603.64      2806760.59      7072308.84
#Sta/Elev= 30
  4705.6  467.32  4884.6  464.75  4885.4  464.77  4896.5  464.37  4902.0  464.72
  4951.7  464.72  4957.9  463.02  4964.6  462.18  4975.6  459.97  4979.5  457.06
  4980.0  456.26  4985.0  456.26  4985.5  457.06  4987.8  458.74  4996.8  457.52
  5005.3  461.02  5007.4  461.88  5018.7  462.39  5039.0  461.29  5051.3  461.86
  5060.5  464.28  5075.0  465.07  5092.4  464.38  5100.3  462.87  5102.8  463.02
  5113.7  464.01  5145.6  464.69  5217.4  464.46  5309.2  465.78  5364.9  466.05
#Mann=7,-1,0
  4705.6    0.05       0  4884.6    0.12       0  4885.4    0.05       0
  4964.6    0.12       0  4979.5    0.07       0  4985.5    0.12       0
  5005.3    0.05       0
Bank Sta=4957.9,5102.8
Exp/Cntr=0.3,0.1

Type RM Length L Ch R = 1,1608,441,441,441
BEGIN DESCRIPTION:
XS3554A
END DESCRIPTION:
XS GIS Cut Line= 3
      2806960.82      7072784.44      2807054.04      7072510.42
      2806877.53      7072149.63
#Sta/Elev= 30
  4630.3  464.81  4662.7  464.37  4682.5  463.42  4780.4  463.65  4781.6  463.64
  4830.4  463.21  4882.9  463.94  4903.1  464.02  4912.0  461.71  4914.7  460.99
  4924.6  460.72  4930.1  462.04  4947.1  461.19  4952.7  455.28  4959.2  456.31
  4969.6  460.85  4975.2  461.89  4981.4  460.95  4990.3  457.92  4992.1  457.31
  4994.7  455.18  4995.2  454.38  5000.2  454.38  5000.7  455.18  5003.7  458.67
  5015.8  461.71  5020.2  463.85  5026.0  464.18  5200.3  464.62  5321.4  466.19
#Mann=7,-1,0
  4630.3    0.05       0  4780.4    0.07       0  4781.6    0.05       0
  4882.9    0.12       0  4990.3    0.05       0  4994.7    0.03       0
  5000.7    0.05       0
Bank Sta=4912,5015.8
Exp/Cntr=0.3,0.1

Type RM Length L Ch R = 1,1167,489,489,489
BEGIN DESCRIPTION:
XS3556A
END DESCRIPTION:
XS GIS Cut Line= 4
      2807048.38      7072863.52      2807215.05      7072682.73
      2807220.70      7072552.79      2807142.55      7072188.12
#Sta/Elev= 30
  4683.8  464.47  4793.4  462.38  4829.2  462.48  4899.5  461.68  4937.4  461.98
  4965.2  461.01  4977.5  459.58  4981.2  458.51  4987.5  456.67  4994.5  452.96
  4995.0  452.16  5000.0  452.16  5000.5  452.96  5005.7  458.51  5007.5  460.44
  5017.5  461.89  5027.5  461.94  5043.1  461.06  5048.1  461.92  5063.1  462.12
  5068.0  461.76  5077.9  462.53  5106.8  463.14  5156.6  462.92  5163.7  463.36
  5262.0  463.08  5292.7  463.46  5333.6  462.42  5374.5  463.57  5432.7  463.40
#Mann=7,-1,0
  4683.8    0.05       0  4965.2    0.12       0  4994.5    0.07       0
  5000.5    0.12       0  5063.1    0.05       0  5106.8    0.07       0
  5163.7    0.05       0
Bank Sta=4981.2,5005.7
Exp/Cntr=0.3,0.1

Type RM Length L Ch R = 1,678,0,0,0
BEGIN DESCRIPTION:
UNT 076 in LFCCL Watershed 2.0
END DESCRIPTION:
XS GIS Cut Line= 4
      2806896.71      7073212.10      2807497.72      7072879.17
      2807550.00      7072600.00      2807156.08      7072105.11
#Sta/Elev= 30
  4143.0  466.30  4198.2  464.43  4353.1  463.13  4449.7  464.90  4493.9  462.07
  4640.5  460.29  4684.0  461.63  4860.1  460.25  4925.9  460.27  4946.1  457.11
  4959.2  458.01  4966.6  458.51  4975.8  454.18  4986.9  450.42  4997.1  451.56
  5003.8  451.35  5005.9  450.21  5006.4  449.41  5011.9  450.21  5014.7  454.18
  5017.4  458.02  5027.6  459.86  5114.1  459.65  5248.6  462.28  5312.7  461.33
  5370.3  462.35  5477.7  461.70  5555.0  463.29  5605.8  461.88  5746.6  462.94
#Mann=5,-1,0
  4143.0    0.05       0  4860.1    0.07       0  4959.2    0.05       0
  5005.9    0.03       0  5011.9    0.05       0
Bank Sta=4975.8,5014.7
Exp/Cntr=0.3,0.1

Chan Stop Cuts=-1