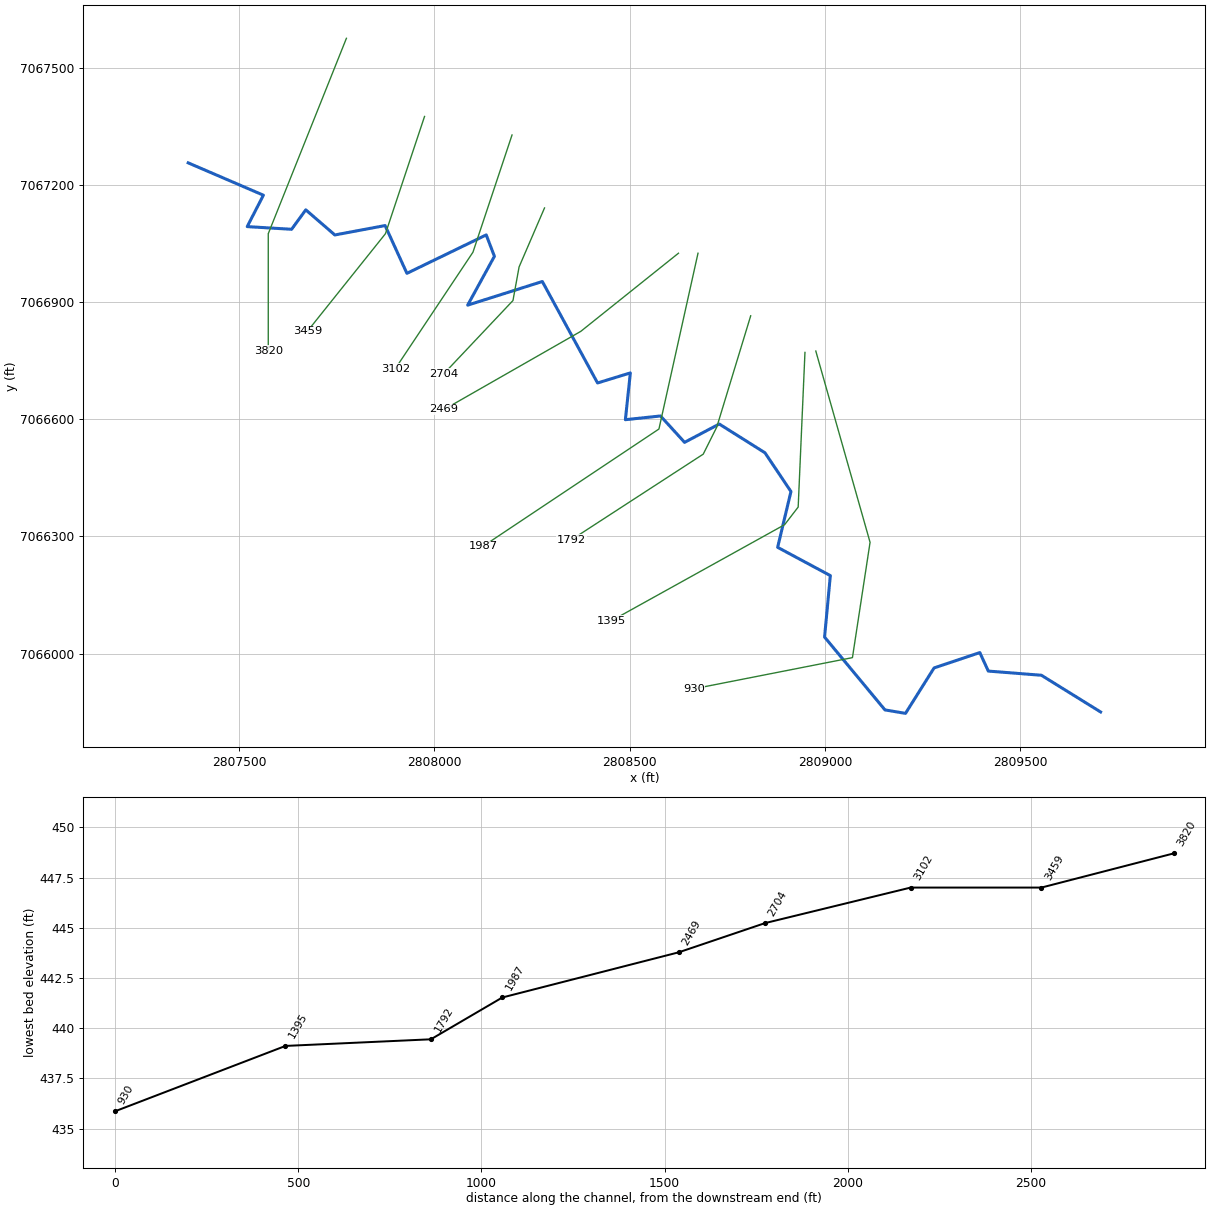
--- UNT 077 in LFCCL Watershed.prj (project) ---

Proj Title=UNT 077 in LFCCL Watershed Base Level Engineering
Current Plan=p01
Default Exp/Contr=0.3,0.1
English Units
Geom File=g01
Flow File=f01
Plan File=p01
BEGIN DESCRIPTION:
UNT 077 in LFCCL Watershed
END DESCRIPTION:

--- UNT 077 in LFCCL Watershed.p01 (plan) ---

Plan Title=Multiple Run
Short Identifier=Multiple
Geom File=g01
Flow File=f01
Subcritical Flow
K Sum by GR= 0
Std Step Tol= 0.01
Critical Tol= 0.01
Num of Std Step Trials= 20
Max Error Tol= 0.3
Flow Tol Ratio= 0.001
Split Flow NTrial= 30
Split Flow Tol= 0.02
Split Flow Ratio= 0.02
Log Output Level= 0
Friction Slope Method= 1
Unsteady Friction Slope Method= 2
Unsteady Bridges Friction Slope Method= 1
Parabolic Critical Depth
Global Vel Dist=  1 , 1 , 1
Global Log Level= 0
CheckData=True
Encroach Param= -1, 0, 0, 0
BEGIN DESCRIPTION:
Multiple Run
END DESCRIPTION:

--- UNT 077 in LFCCL Watershed.f01 (steady flow) ---

Flow Title=Multiple
Number of Profiles=7
Profile Names=10-year,25-year,50-year,1pct_min,100-year,1pct_plu,500-year
River Rch & RM= UNT 077 in LFCCL,Reach-1,3820
     471     609     717     418     835    1666    1129
Boundary for River Rch & Prof#=UNT 077 in LFCCL,Reach-1,1
Up Type=0
Dn Type=3
Dn Slope=0.005
Boundary for River Rch & Prof#=UNT 077 in LFCCL,Reach-1,2
Up Type=0
Dn Type=3
Dn Slope=0.005
Boundary for River Rch & Prof#=UNT 077 in LFCCL,Reach-1,3
Up Type=0
Dn Type=3
Dn Slope=0.005
Boundary for River Rch & Prof#=UNT 077 in LFCCL,Reach-1,4
Up Type=0
Dn Type=3
Dn Slope=0.005
Boundary for River Rch & Prof#=UNT 077 in LFCCL,Reach-1,5
Up Type=0
Dn Type=3
Dn Slope=0.005
Boundary for River Rch & Prof#=UNT 077 in LFCCL,Reach-1,6
Up Type=0
Dn Type=3
Dn Slope=0.005
Boundary for River Rch & Prof#=UNT 077 in LFCCL,Reach-1,7
Up Type=0
Dn Type=3
Dn Slope=0.005

--- UNT 077 in LFCCL Watershed.g01 (geometry) ---

Geom Title=Existing Conditions

River Reach=UNT 077 in LFCCL,Reach-1
Reach XY= 30
      2807370.09      7067256.26      2807562.51      7067173.52
      2807521.12      7067093.09      2807634.72      7067086.26
      2807671.05      7067136.04      2807745.42      7067071.73
      2807874.08      7067095.80      2807929.90      7066973.48
      2808132.93      7067071.85      2808153.88      7067017.07
      2808085.42      7066892.07      2808276.54      7066952.56
      2808417.88      7066692.86      2808501.85      7066718.65
      2808489.10      7066598.88      2808579.08      7066608.39
      2808640.65      7066540.92      2808729.39      7066587.80
      2808846.32      7066514.24      2808912.94      7066415.04
      2808878.86      7066272.13      2809013.71      7066199.80
      2808998.96      7066042.45      2809153.57      7065855.98
      2809206.15      7065847.13      2809279.26      7065963.42
      2809396.38      7066002.76      2809418.06      7065955.40
      2809554.00      7065944.69      2809705.59      7065850.71

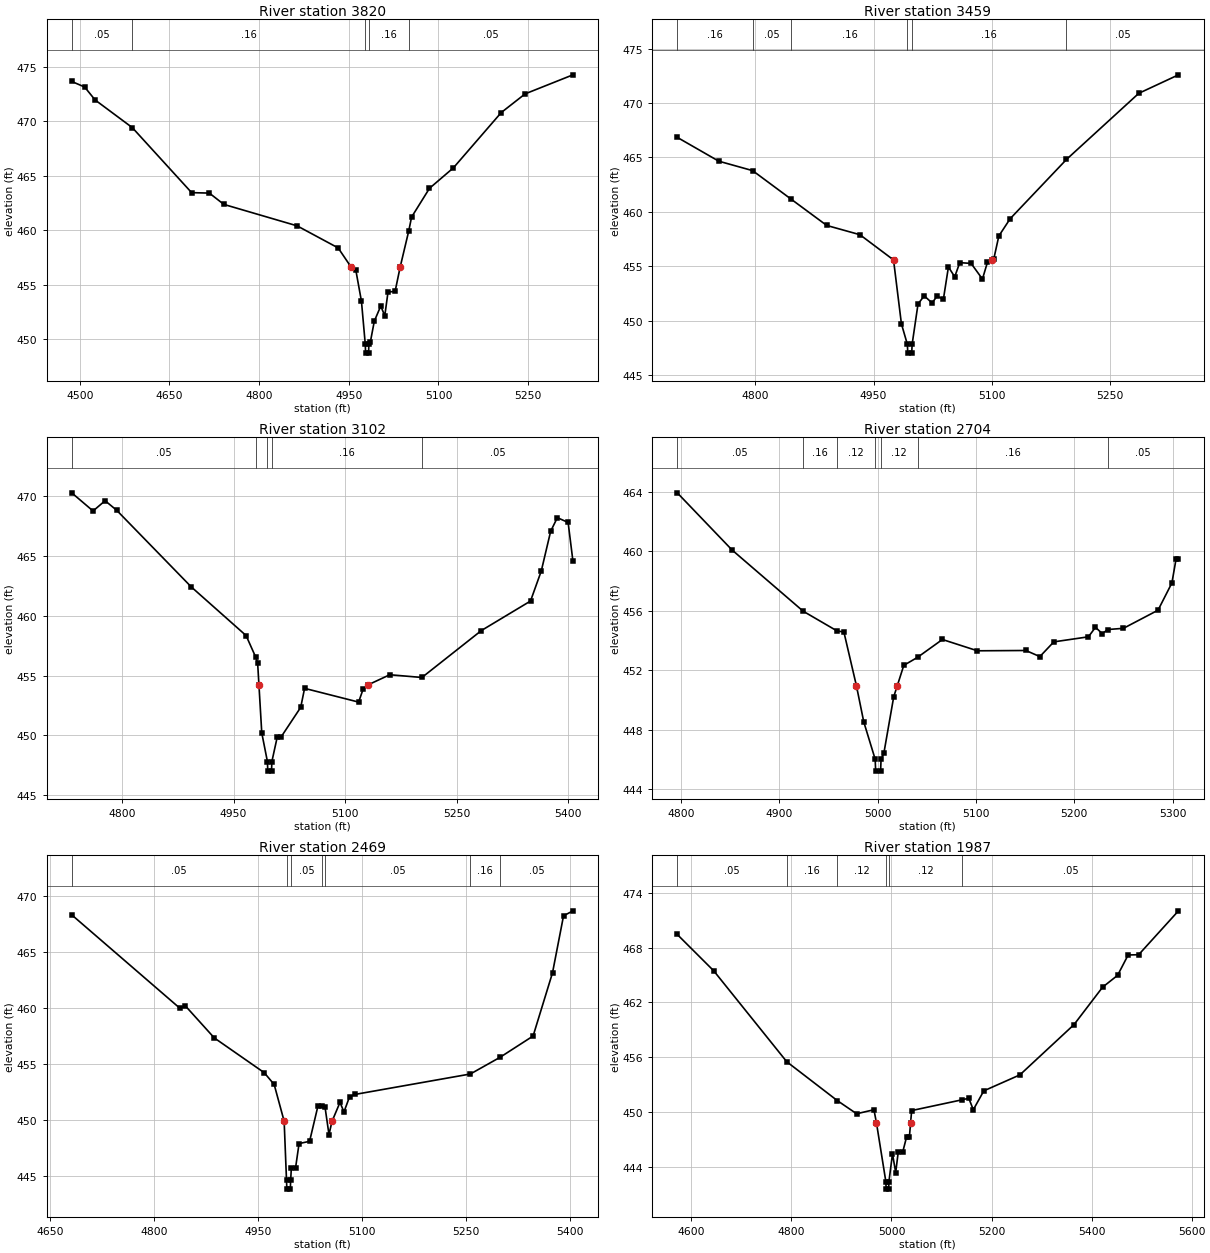
Type RM Length L Ch R = 1,3820,361,361,361
BEGIN DESCRIPTION:
UNT 077 in LFCCL Watershed 6.0
END DESCRIPTION:
XS GIS Cut Line= 3
      2807775.01      7067575.03      2807575.00      7067075.00
      2807575.00      7066775.05
#Sta/Elev= 30
  4486.5  473.67  4508.1  473.16  4525.6  471.97  4587.8  469.43  4687.1  463.45
  4716.7  463.41  4741.0  462.37  4863.5  460.40  4932.2  458.37  4954.0  456.60
  4961.8  456.32  4971.2  453.46  4977.6  449.50  4978.1  448.70  4983.1  448.70
  4983.6  449.50  4986.0  449.70  4992.7  451.64  5003.5  453.03  5010.2  452.13
  5015.6  454.31  5027.5  454.38  5035.9  456.60  5050.3  459.93  5055.0  461.20
  5085.0  463.85  5125.0  465.73  5205.0  470.81  5245.0  472.53  5325.0  474.28
#Mann=5,-1,0
  4486.5    0.05       0  4587.8    0.16       0  4977.6    0.07       0
  4983.6    0.16       0  5050.3    0.05       0
Bank Sta=4954,5035.9
Exp/Cntr=0.3,0.1

Type RM Length L Ch R = 1,3459,357,357,357
BEGIN DESCRIPTION:
UNT 077 in LFCCL Watershed 5.0
END DESCRIPTION:
XS GIS Cut Line= 3
      2807975.01      7067375.03      2807875.00      7067075.00
      2807675.01      7066825.01
#Sta/Elev= 30
  4700.8  466.84  4753.5  464.65  4796.5  463.78  4845.7  461.14  4890.6  458.74
  4932.7  457.89  4975.4  455.57  4985.4  449.70  4993.0  447.80  4993.5  447.00
  4998.5  447.00  4999.0  447.80  5006.5  451.52  5014.4  452.27  5024.3  451.61
  5030.7  452.24  5038.7  451.95  5045.1  454.92  5053.1  454.02  5059.5  455.32
  5073.9  455.25  5088.3  453.81  5094.7  455.37  5100.1  455.56  5102.7  455.66
  5109.1  457.77  5123.5  459.36  5195.0  464.81  5286.8  470.89  5337.2  472.59
#Mann=6,-1,0
  4700.8    0.16       0  4796.5    0.05       0  4845.7    0.16       0
  4993.0    0.07       0  4999.0    0.16       0  5195.0    0.05       0
Bank Sta=4975.4,5100.1
Exp/Cntr=0.3,0.1

Type RM Length L Ch R = 1,3102,398,398,398
BEGIN DESCRIPTION:
UNT 077 in LFCCL Watershed 4.0
END DESCRIPTION:
XS GIS Cut Line= 3
      2808198.96      7067327.61      2808098.96      7067027.60
      2807900.28      7066729.59
#Sta/Elev= 30
  4732.2  470.30  4760.9  468.78  4777.1  469.64  4792.5  468.85  4893.1  462.42
  4966.8  458.35  4979.7  456.55  4982.3  456.09  4984.1  454.22  4987.9  450.20
  4995.5  447.80  4996.0  447.00  5001.0  447.00  5001.5  447.80  5008.6  449.82
  5013.9  449.86  5040.3  452.34  5045.5  453.93  5118.2  452.78  5124.2  453.85
  5130.8  454.22  5160.2  455.07  5203.4  454.84  5283.4  458.77  5349.5  461.24
  5364.0  463.76  5376.6  467.08  5385.6  468.22  5400.1  467.82  5406.6  464.57
#Mann=5,-1,0
  4732.2    0.05       0  4979.7    0.16       0  4995.5    0.07       0
  5001.5    0.16       0  5203.4    0.05       0
Bank Sta=4984.1,5130.8
Exp/Cntr=0.3,0.1

Type RM Length L Ch R = 1,2704,235,235,235
BEGIN DESCRIPTION:
XS3557A
END DESCRIPTION:
XS GIS Cut Line= 4
      2808282.12      7067140.89      2808217.01      7066989.82
      2808201.38      7066903.88      2808024.27      7066716.35
#Sta/Elev= 30
  4796.1  463.94  4851.8  460.10  4924.2  455.98  4958.5  454.66  4965.6  454.58
  4978.4  450.95  4985.8  448.54  4997.4  446.03  4997.9  445.23  5002.9  445.23
  5003.4  446.03  5006.2  446.42  5016.3  450.24  5019.8  450.95  5026.5  452.34
  5040.5  452.88  5065.8  454.08  5101.4  453.32  5150.7  453.34  5164.9  452.93
  5179.1  453.92  5214.3  454.26  5221.5  454.90  5228.4  454.47  5233.9  454.75
  5249.9  454.83  5285.1  456.05  5299.2  457.88  5303.4  459.47  5305.9  459.47
#Mann=7,-1,0
  4796.1    0.05       0  4924.2    0.16       0  4958.5    0.12       0
  4997.4    0.07       0  5003.4    0.12       0  5040.5    0.16       0
  5233.9    0.05       0
Bank Sta=4978.4,5019.8
Exp/Cntr=0.3,0.1

Type RM Length L Ch R = 1,2469,482,482,482
BEGIN DESCRIPTION:
UNT 077 in LFCCL Watershed 3.0
END DESCRIPTION:
XS GIS Cut Line= 3
      2808624.98      7067024.98      2808375.00      7066825.00
      2808025.04      7066625.02
#Sta/Elev= 30
  4681.0  468.34  4837.0  459.98  4845.1  460.18  4886.7  457.32  4958.7  454.21
  4973.1  453.15  4987.5  449.86  4990.9  444.58  4991.4  443.78  4996.4  443.78
  4996.9  444.58  4997.9  445.70  5004.0  445.70  5009.0  447.86  5024.2  448.06
  5036.4  451.26  5042.5  451.20  5046.4  451.16  5052.2  448.66  5056.5  449.84
  5068.1  451.55  5073.8  450.69  5081.8  452.04  5089.7  452.26  5256.2  454.09
  5298.9  455.58  5346.7  457.49  5374.7  463.15  5390.6  468.25  5404.2  468.70
#Mann=7,-1,0
  4681.0    0.05       0  4990.9    0.03       0  4996.9    0.05       0
  5042.5    0.12       0  5046.4    0.05       0  5256.2    0.16       0
  5298.9    0.05       0
Bank Sta=4987.5,5056.5
Exp/Cntr=0.3,0.1

Type RM Length L Ch R = 1,1987,195,195,195
BEGIN DESCRIPTION:
UNT 077 in LFCCL Watershed 2.0
END DESCRIPTION:
XS GIS Cut Line= 3
      2808675.00      7067025.00      2808575.00      7066575.00
      2808125.01      7066275.01
#Sta/Elev= 30
  4571.9  469.44  4644.9  465.45  4790.8  455.49  4891.6  451.24  4930.4  449.79
  4965.0  450.23  4970.0  448.81  4988.9  442.33  4989.4  441.53  4994.4  441.53
  4994.9  442.33  5002.1  445.40  5008.5  443.35  5013.7  445.65  5022.6  445.61
  5030.3  447.26  5035.9  447.26  5038.3  448.81  5040.4  450.14  5142.0  451.33
  5154.6  451.49  5163.6  450.23  5184.6  452.30  5256.7  454.05  5364.9  459.56
  5422.0  463.66  5452.0  464.96  5473.1  467.19  5494.1  467.22  5573.7  472.03
#Mann=6,-1,0
  4571.9    0.05       0  4790.8    0.16       0  4891.6    0.12       0
  4988.9    0.07       0  4994.9    0.12       0  5142.0    0.05       0
Bank Sta=4970,5038.3
Exp/Cntr=0.3,0.1

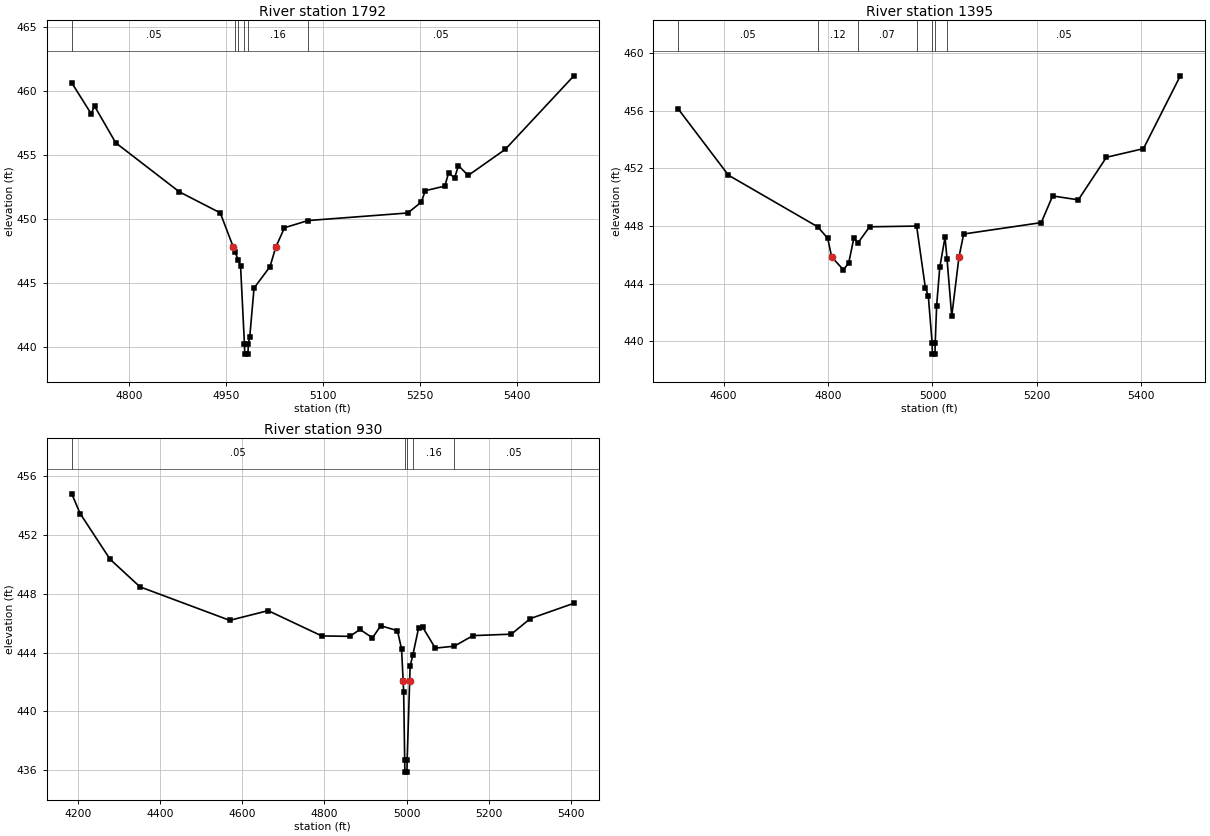
Type RM Length L Ch R = 1,1792,397,397,397
BEGIN DESCRIPTION:
XS3559A
END DESCRIPTION:
XS GIS Cut Line= 4
      2808809.90      7066864.86      2808723.08      7066580.10
      2808688.36      7066510.65      2808351.51      7066291.87
#Sta/Elev= 30
  4710.8  460.63  4740.8  458.22  4746.0  458.82  4778.8  455.95  4877.3  452.12
  4940.6  450.48  4960.9  447.79  4963.7  447.40  4968.7  446.77  4972.0  446.35
  4978.0  440.25  4978.5  439.45  4983.5  439.45  4984.0  440.25  4986.2  440.79
  4992.9  444.61  5017.6  446.28  5026.4  447.79  5040.0  449.32  5076.4  449.88
  5230.7  450.47  5251.8  451.32  5257.8  452.21  5288.1  452.57  5294.1  453.62
  5303.2  453.19  5309.2  454.17  5324.3  453.40  5381.7  455.44  5487.8  461.18
#Mann=6,-1,0
  4710.8    0.05       0  4963.7    0.12       0  4968.7    0.16       0
  4978.0    0.07       0  4984.0    0.16       0  5076.4    0.05       0
Bank Sta=4960.9,5026.4
Exp/Cntr=0.3,0.1

Type RM Length L Ch R = 1,1395,465,465,465
BEGIN DESCRIPTION:
XS3558A
END DESCRIPTION:
XS GIS Cut Line= 4
      2808948.78      7066771.04      2808931.42      7066375.23
      2808896.69      7066330.10      2808452.23      7066083.56
#Sta/Elev= 30
  4513.2  456.12  4609.3  451.53  4780.2  447.95  4799.5  447.15  4806.9  445.86
  4829.5  444.97  4839.6  445.44  4849.6  447.18  4857.3  446.83  4879.6  447.95
  4969.7  448.00  4986.3  443.74  4992.0  443.17  4999.3  439.92  4999.8  439.12
  5004.8  439.12  5005.3  439.92  5008.0  442.48  5014.0  445.14  5024.1  447.23
  5027.9  445.72  5036.9  441.75  5050.8  445.86  5059.8  447.45  5208.3  448.24
  5230.1  450.09  5279.3  449.82  5333.1  452.77  5404.0  453.37  5474.6  458.42
#Mann=7,-1,0
  4513.2    0.05       0  4780.2    0.12       0  4857.3    0.07       0
  4969.7    0.12       0  4999.3    0.07       0  5005.3    0.12       0
  5027.9    0.05       0
Bank Sta=4806.9,5050.8
Exp/Cntr=0.3,0.1

Type RM Length L Ch R = 1,930,0,0,0
BEGIN DESCRIPTION:
UNT 077 in LFCCL Watershed 1.0
END DESCRIPTION:
XS GIS Cut Line= 4
      2808976.55      7066774.57      2809115.44      7066284.96
      2809070.31      7065989.82      2808664.19      7065909.98
#Sta/Elev= 30
  4185.2  454.81  4205.5  453.47  4278.3  450.36  4351.1  448.48  4569.4  446.20
  4662.9  446.86  4793.2  445.14  4861.7  445.11  4886.3  445.58  4916.7  445.01
  4936.9  445.83  4977.4  445.50  4987.5  444.25  4991.3  442.09  4992.6  441.34
  4995.1  436.67  4995.6  435.87  5000.6  435.87  5001.1  436.67  5007.2  442.09
  5008.3  443.06  5015.1  443.87  5028.7  445.65  5038.7  445.74  5069.5  444.31
  5115.6  444.44  5161.2  445.16  5254.5  445.26  5300.8  446.32  5406.6  447.36
#Mann=5,-1,0
  4185.2    0.05       0  4995.1    0.03       0  5001.1    0.05       0
  5015.1    0.16       0  5115.6    0.05       0
Bank Sta=4991.3,5007.2
Exp/Cntr=0.3,0.1

Chan Stop Cuts=-1