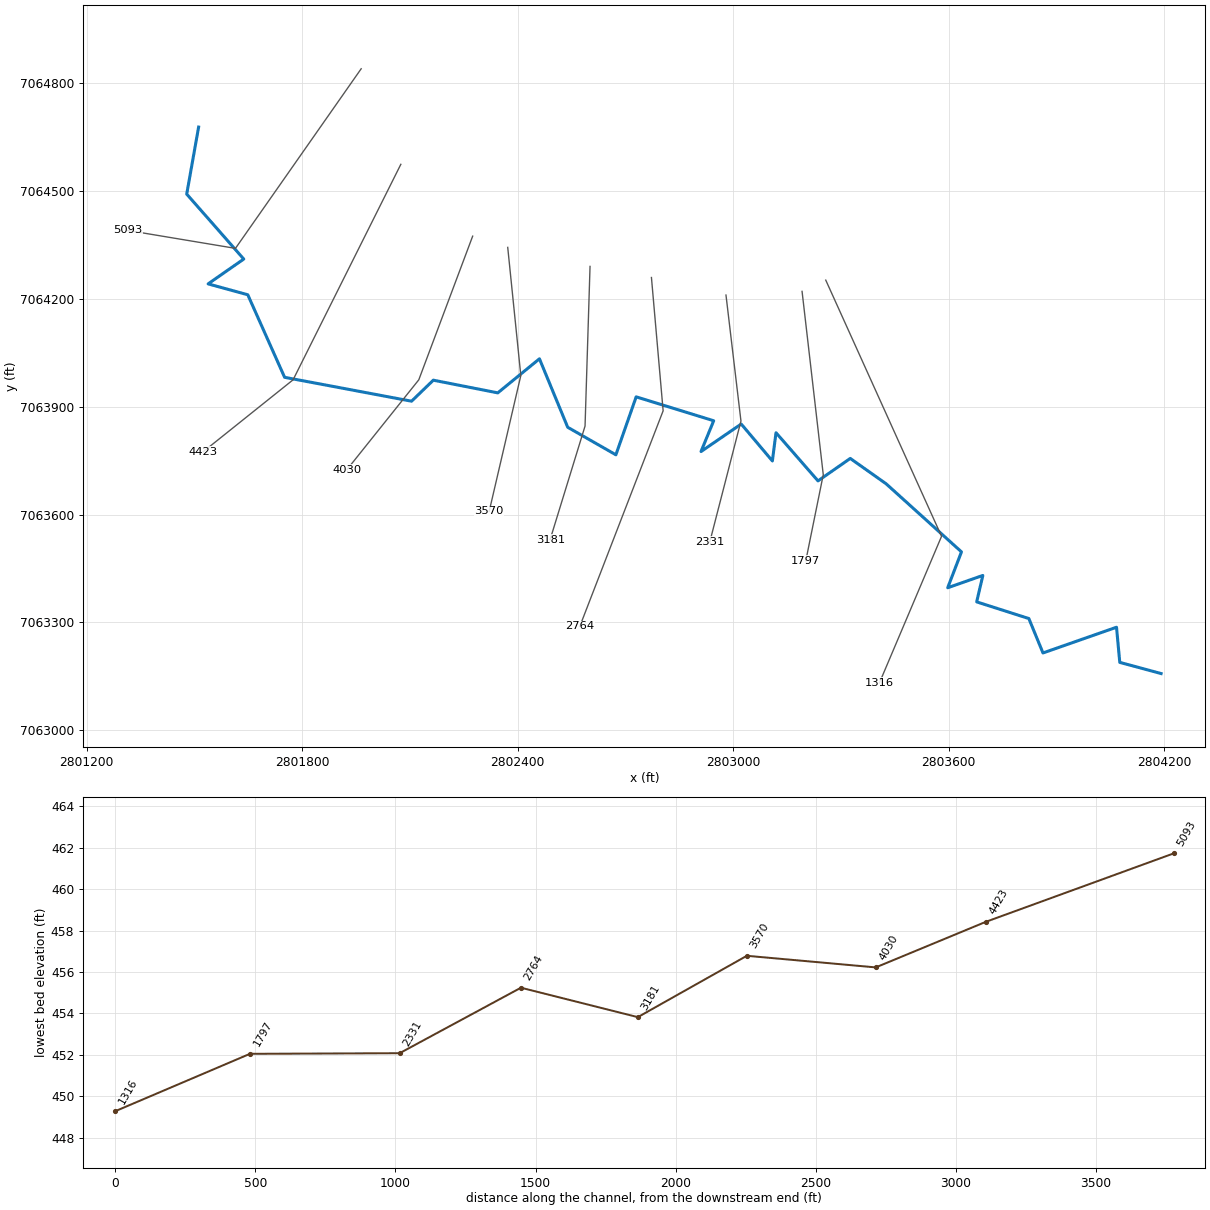
--- UNT 080 in LFCCL Watershed.prj (project) ---

Proj Title=UNT 080 in LFCCL Watershed Base Level Engineering
Current Plan=p01
Default Exp/Contr=0.3,0.1
English Units
Geom File=g01
Flow File=f01
Plan File=p01
BEGIN DESCRIPTION:
UNT 080 in LFCCL Watershed
END DESCRIPTION:

--- UNT 080 in LFCCL Watershed.p01 (plan) ---

Plan Title=Multiple Run
Short Identifier=Multiple
Geom File=g01
Flow File=f01
Subcritical Flow
K Sum by GR= 0
Std Step Tol= 0.01
Critical Tol= 0.01
Num of Std Step Trials= 20
Max Error Tol= 0.3
Flow Tol Ratio= 0.001
Split Flow NTrial= 30
Split Flow Tol= 0.02
Split Flow Ratio= 0.02
Log Output Level= 0
Friction Slope Method= 1
Unsteady Friction Slope Method= 2
Unsteady Bridges Friction Slope Method= 1
Parabolic Critical Depth
Global Vel Dist=  1 , 1 , 1
Global Log Level= 0
CheckData=True
Encroach Param= -1, 0, 0, 0
BEGIN DESCRIPTION:
Multiple Run
END DESCRIPTION:

--- UNT 080 in LFCCL Watershed.f01 (steady flow) ---

Flow Title=Multiple
Number of Profiles=7
Profile Names=10-year,25-year,50-year,1pct_min,100-year,1pct_plu,500-year
River Rch & RM= UNT 080 in LFCCL,Reach-1,5093
     713     949    1138     676    1350    2693    1894
River Rch & RM= UNT 080 in LFCCL,Reach-1,3181
     732     974    1167     693    1383    2760    1938
Boundary for River Rch & Prof#=UNT 080 in LFCCL,Reach-1,1
Up Type=0
Dn Type=3
Dn Slope=0.005
Boundary for River Rch & Prof#=UNT 080 in LFCCL,Reach-1,2
Up Type=0
Dn Type=3
Dn Slope=0.005
Boundary for River Rch & Prof#=UNT 080 in LFCCL,Reach-1,3
Up Type=0
Dn Type=3
Dn Slope=0.005
Boundary for River Rch & Prof#=UNT 080 in LFCCL,Reach-1,4
Up Type=0
Dn Type=3
Dn Slope=0.005
Boundary for River Rch & Prof#=UNT 080 in LFCCL,Reach-1,5
Up Type=0
Dn Type=3
Dn Slope=0.005
Boundary for River Rch & Prof#=UNT 080 in LFCCL,Reach-1,6
Up Type=0
Dn Type=3
Dn Slope=0.005
Boundary for River Rch & Prof#=UNT 080 in LFCCL,Reach-1,7
Up Type=0
Dn Type=3
Dn Slope=0.005

--- UNT 080 in LFCCL Watershed.g01 (geometry) ---

Geom Title=Existing Conditions

River Reach=UNT 080 in LFCCL,Reach-1
Reach XY= 30
      2801512.00      7064678.56      2801478.89      7064492.03
      2801637.69      7064311.19      2801538.43      7064242.10
      2801648.90      7064211.81      2801751.42      7063981.97
      2802104.91      7063915.49      2802165.42      7063973.98
      2802344.93      7063938.69      2802460.91      7064033.49
      2802539.58      7063842.88      2802673.71      7063766.23
      2802730.19      7063927.59      2802946.01      7063861.03
      2802910.71      7063775.31      2803022.65      7063851.95
      2803109.39      7063749.09      2803119.47      7063827.75
      2803236.46      7063693.62      2803326.22      7063756.15
      2803426.06      7063685.55      2803635.83      7063495.95
      2803597.51      7063396.11      2803695.33      7063430.40
      2803678.19      7063356.77      2803823.41      7063310.38
      2803862.75      7063214.57      2804067.47      7063286.18
      2804076.55      7063188.35      2804191.70      7063157.24

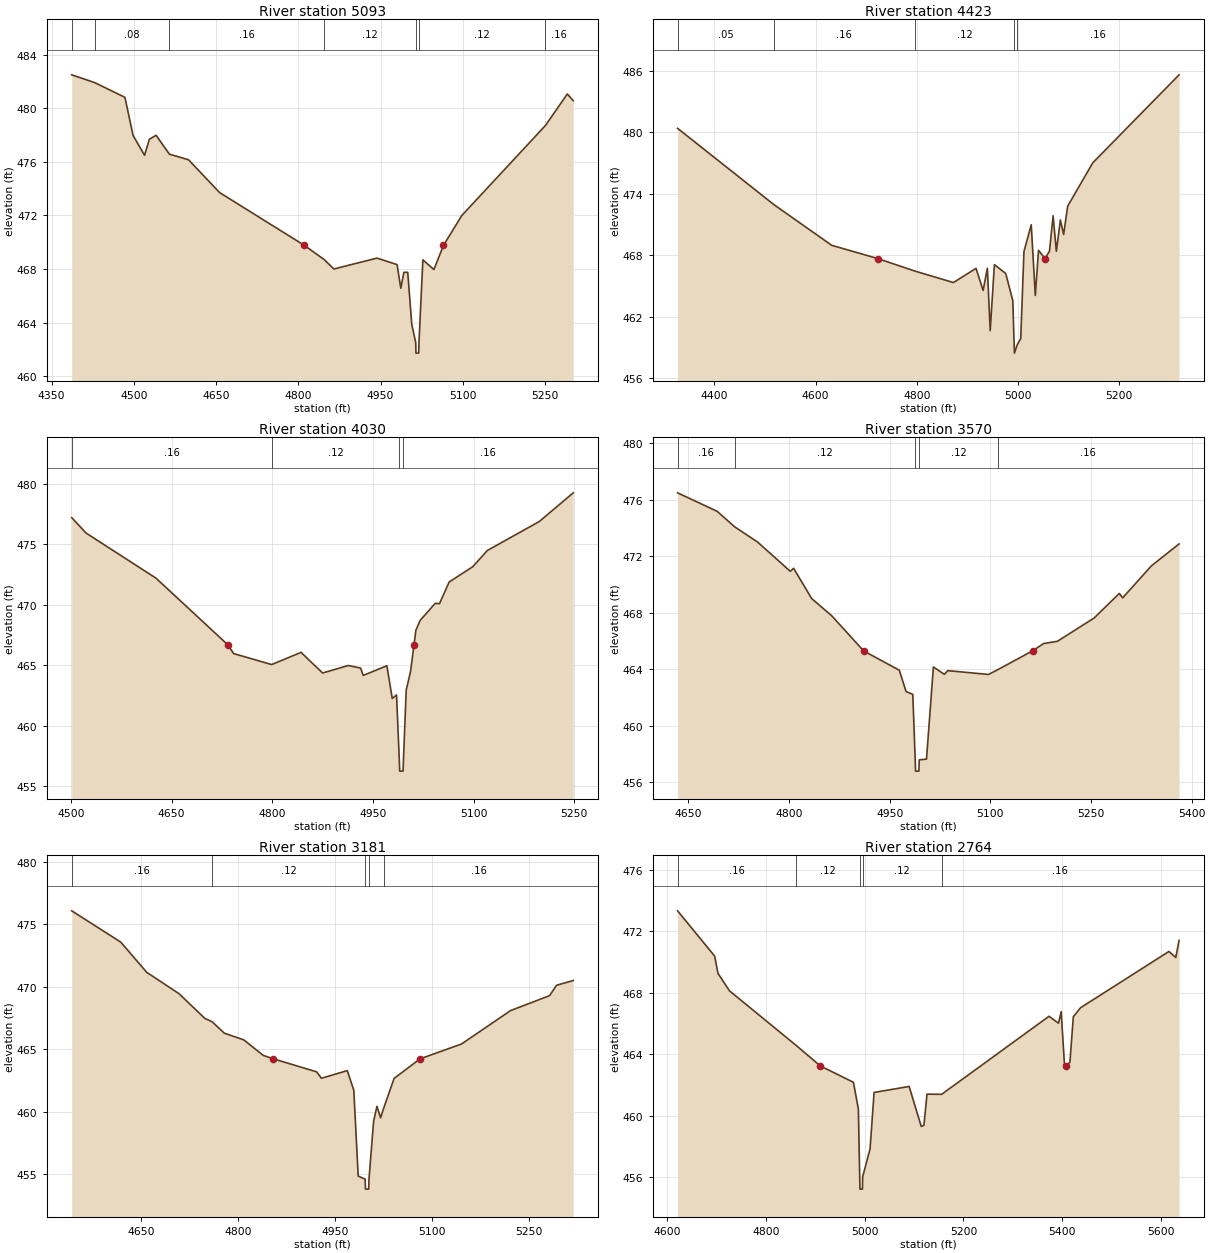
Type RM Length L Ch R = 1,5093,670,670,670
BEGIN DESCRIPTION:
UNT 080 in LFCCL Watershed 6.0
END DESCRIPTION:
XS GIS Cut Line= 3
      2801964.60      7064841.00      2801614.58      7064340.97
      2801314.58      7064390.97
#Sta/Elev= 30
  4386.9  482.49  4428.7  481.91  4483.9  480.81  4498.8  477.96  4519.7  476.48
  4528.4  477.68  4540.7  477.98  4564.9  476.57  4599.9  476.15  4656.6  473.70
  4811.2  469.76  4846.9  468.71  4865.0  468.00  4943.5  468.81  4980.1  468.33
  4987.0  466.56  4992.5  467.75  4999.6  467.75  5007.0  463.85  5014.1  462.52
  5014.6  461.72  5019.6  461.72  5020.1  462.52  5027.2  468.68  5047.3  467.96
  5064.8  469.76  5098.2  471.99  5250.7  478.71  5290.6  481.06  5301.4  480.56
#Mann=7,-1,0
  4386.9    0.05       0  4428.7    0.08       0  4564.9    0.16       0
  4846.9    0.12       0  5014.1    0.07       0  5020.1    0.12       0
  5250.7    0.16       0
Bank Sta=4811.2,5064.8
Exp/Cntr=0.3,0.1

Type RM Length L Ch R = 1,4423,393,393,393
BEGIN DESCRIPTION:
UNT 080 in LFCCL Watershed 5.0
END DESCRIPTION:
XS GIS Cut Line= 3
      2802074.98      7064574.96      2801775.00      7063975.00
      2801525.02      7063775.02
#Sta/Elev= 30
  4327.4  480.40  4517.7  472.94  4632.0  468.96  4722.7  467.67  4795.8  466.45
  4872.4  465.32  4917.1  466.71  4931.1  464.55  4939.5  466.72  4945.1  460.62
  4953.4  467.07  4975.8  466.21  4989.8  463.54  4992.4  459.22  4992.9  458.42
  4998.4  459.22  5005.4  459.83  5011.8  468.36  5026.2  470.97  5034.2  464.06
  5040.6  468.47  5053.2  467.67  5062.2  468.38  5069.4  471.85  5075.8  468.38
  5083.8  471.44  5090.2  470.02  5098.2  472.79  5147.8  477.03  5318.3  485.63
#Mann=5,-1,0
  4327.4    0.05       0  4517.7    0.16       0  4795.8    0.12       0
  4992.4    0.07       0  4998.4    0.16       0
Bank Sta=4722.7,5053.2
Exp/Cntr=0.3,0.1

Type RM Length L Ch R = 1,4030,460,460,460
BEGIN DESCRIPTION:
UNT 080 in LFCCL Watershed 4.0
END DESCRIPTION:
XS GIS Cut Line= 3
      2802274.99      7064374.96      2802125.00      7063975.00
      2801925.01      7063725.01
#Sta/Elev= 30
  4501.3  477.22  4522.6  475.95  4626.8  472.21  4734.2  466.67  4742.5  465.96
  4799.2  465.05  4843.0  466.06  4875.1  464.35  4913.3  464.97  4931.7  464.76
  4935.7  464.15  4970.9  464.95  4978.9  462.24  4985.3  462.53  4989.5  457.02
  4990.0  456.22  4995.0  456.22  4995.5  457.02  4999.7  462.94  5006.1  464.45
  5011.3  466.67  5014.1  467.89  5020.5  468.71  5042.9  470.12  5049.3  470.10
  5063.7  471.89  5098.9  473.16  5120.6  474.50  5198.2  476.91  5248.6  479.28
#Mann=4,-1,0
  4501.3    0.16       0  4799.2    0.12       0  4989.5    0.07       0
  4995.5    0.16       0
Bank Sta=4734.2,5011.3
Exp/Cntr=0.3,0.1

Type RM Length L Ch R = 1,3570,389,389,389
BEGIN DESCRIPTION:
XS3564A
END DESCRIPTION:
XS GIS Cut Line= 3
      2802372.59      7064343.72      2802409.05      7063986.93
      2802320.90      7063608.40
#Sta/Elev= 30
  4634.0  476.50  4693.0  475.19  4719.1  474.09  4753.3  473.01  4801.9  470.94
  4806.9  471.15  4833.8  469.01  4863.9  467.78  4911.2  465.30  4964.4  463.93
  4974.5  462.42  4984.5  462.22  4988.1  457.58  4988.6  456.78  4993.6  456.78
  4994.1  457.58  5004.9  457.63  5015.2  464.16  5031.5  463.64  5036.7  463.90
  5097.3  463.63  5110.8  463.96  5162.9  465.30  5179.4  465.82  5200.0  465.98
  5254.7  467.63  5292.2  469.37  5297.3  469.06  5339.9  471.32  5381.3  472.88
#Mann=5,-1,0
  4634.0    0.16       0  4719.1    0.12       0  4988.1    0.07       0
  4994.1    0.12       0  5110.8    0.16       0
Bank Sta=4911.2,5162.9
Exp/Cntr=0.3,0.1

Type RM Length L Ch R = 1,3181,417,417,417
BEGIN DESCRIPTION:
XS3562A
END DESCRIPTION:
XS GIS Cut Line= 3
      2802601.76      7064290.74      2802587.87      7063846.31
      2802490.66      7063530.38
#Sta/Elev= 30
  4542.8  476.06  4618.6  473.56  4658.6  471.15  4708.6  469.44  4748.6  467.46
  4759.7  467.20  4778.7  466.28  4808.7  465.75  4838.7  464.51  4854.6  464.23
  4921.4  463.19  4928.7  462.68  4968.7  463.29  4978.8  461.72  4985.6  454.86
  4996.3  454.62  4996.8  453.82  5001.8  453.82  5002.3  454.62  5009.4  459.24
  5014.6  460.44  5020.2  459.52  5025.2  460.32  5041.1  462.67  5081.2  464.23
  5145.4  465.42  5221.2  468.09  5281.4  469.28  5292.2  470.11  5318.0  470.49
#Mann=5,-1,0
  4542.8    0.16       0  4759.7    0.12       0  4996.3    0.07       0
  5002.3    0.12       0  5025.2    0.16       0
Bank Sta=4854.6,5081.2
Exp/Cntr=0.3,0.1

Type RM Length L Ch R = 1,2764,433,433,433
BEGIN DESCRIPTION:
Mapping XS 706cdb62
END DESCRIPTION:
XS GIS Cut Line= 3
      2802772.71      7064259.84      2802805.26      7063888.71
      2802573.34      7063288.73
#Sta/Elev= 30
  4620.9  473.32  4696.0  470.38  4702.7  469.26  4726.1  468.12  4861.0  464.58
  4909.7  463.25  4977.1  462.18  4987.1  460.44  4989.8  456.04  4990.3  455.24
  4995.3  455.24  4995.8  456.04  5010.8  457.86  5018.9  461.52  5089.9  461.91
  5114.5  459.31  5119.9  459.39  5126.1  461.41  5155.8  461.40  5373.3  466.47
  5392.5  466.02  5397.9  466.77  5404.8  463.20  5406.7  463.25  5415.6  463.48
  5422.5  466.44  5437.0  467.02  5616.1  470.68  5630.0  470.29  5636.7  471.40
#Mann=5,-1,0
  4620.9    0.16       0  4861.0    0.12       0  4989.8    0.07       0
  4995.8    0.12       0  5155.8    0.16       0
Bank Sta=4909.7,5406.7
Exp/Cntr=0.3,0.1

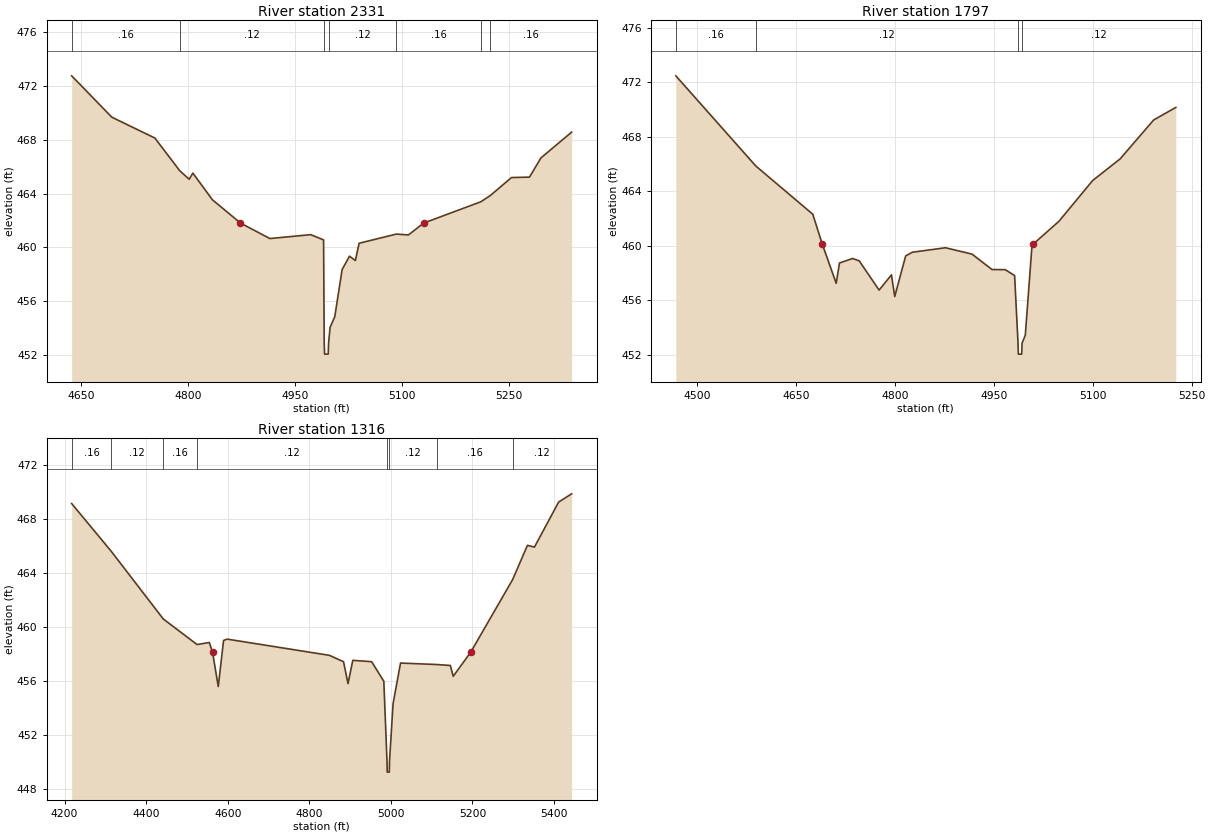
Type RM Length L Ch R = 1,2331,534,534,534
BEGIN DESCRIPTION:
XS3561A
END DESCRIPTION:
XS GIS Cut Line= 3
      2802980.22      7064210.93      2803021.90      7063860.20
      2802935.09      7063523.40
#Sta/Elev= 30
  4637.2  472.74  4693.5  469.67  4753.9  468.12  4788.8  465.69  4802.0  465.06
  4807.1  465.52  4834.5  463.54  4873.9  461.81  4915.1  460.66  4972.4  460.95
  4990.4  460.56  4991.3  452.88  4991.8  452.08  4996.9  452.08  4997.4  452.88
  4999.5  454.06  5006.1  454.86  5016.4  458.36  5026.7  459.35  5035.0  459.03
  5040.2  460.31  5092.3  460.99  5109.4  460.93  5130.8  461.81  5210.9  463.39
  5224.1  463.85  5253.9  465.19  5279.1  465.22  5295.2  466.65  5338.2  468.56
#Mann=7,-1,0
  4637.2    0.16       0  4788.8    0.12       0  4991.3    0.07       0
  4997.4    0.12       0  5092.3    0.16       0  5210.9    0.12       0
  5224.1    0.16       0
Bank Sta=4873.9,5130.8
Exp/Cntr=0.3,0.1

Type RM Length L Ch R = 1,1797,481,481,481
BEGIN DESCRIPTION:
XS3560A
END DESCRIPTION:
XS GIS Cut Line= 3
      2803192.04      7064221.30      2803251.06      7063710.89
      2803202.45      7063471.28
#Sta/Elev= 30
  4467.6  472.48  4588.9  465.86  4675.3  462.32  4689.6  460.14  4710.8  457.25
  4715.8  458.74  4735.7  459.07  4745.7  458.90  4775.9  456.75  4794.6  457.87
  4799.6  456.28  4816.2  459.26  4826.3  459.53  4876.6  459.86  4916.9  459.39
  4947.1  458.26  4967.2  458.25  4981.4  457.82  4986.6  452.85  4987.1  452.05
  4992.2  452.05  4992.7  452.85  4997.6  453.44  5007.8  460.04  5009.9  460.14
  5048.6  461.80  5099.7  464.79  5141.6  466.39  5192.3  469.24  5225.9  470.16
#Mann=4,-1,0
  4467.6    0.16       0  4588.9    0.12       0  4986.6    0.07       0
  4992.7    0.12       0
Bank Sta=4689.6,5009.9
Exp/Cntr=0.3,0.1

Type RM Length L Ch R = 1,1316,0,0,0
BEGIN DESCRIPTION:
UNT 080 in LFCCL Watershed 3.0
END DESCRIPTION:
XS GIS Cut Line= 3
      2803258.01      7064252.55      2803580.36      7063539.32
      2803407.33      7063131.07
#Sta/Elev= 30
  4217.3  469.15  4314.3  465.62  4442.0  460.61  4524.8  458.72  4554.8  458.87
  4562.8  458.15  4576.8  455.61  4589.8  459.02  4598.7  459.12  4849.5  457.92
  4884.0  457.45  4895.0  455.83  4906.7  457.55  4953.0  457.45  4982.8  456.00
  4990.6  450.08  4991.1  449.28  4996.2  449.28  4996.7  450.08  5005.5  454.35
  5023.8  457.35  5113.6  457.24  5145.9  457.17  5153.0  456.37  5195.8  458.15
  5298.6  463.52  5335.0  466.06  5352.2  465.93  5411.5  469.26  5443.4  469.87
#Mann=8,-1,0
  4217.3    0.16       0  4314.3    0.12       0  4442.0    0.16       0
  4524.8    0.12       0  4990.6    0.07       0  4996.7    0.12       0
  5113.6    0.16       0  5298.6    0.12       0
Bank Sta=4562.8,5195.8
Exp/Cntr=0.3,0.1

Chan Stop Cuts=-1