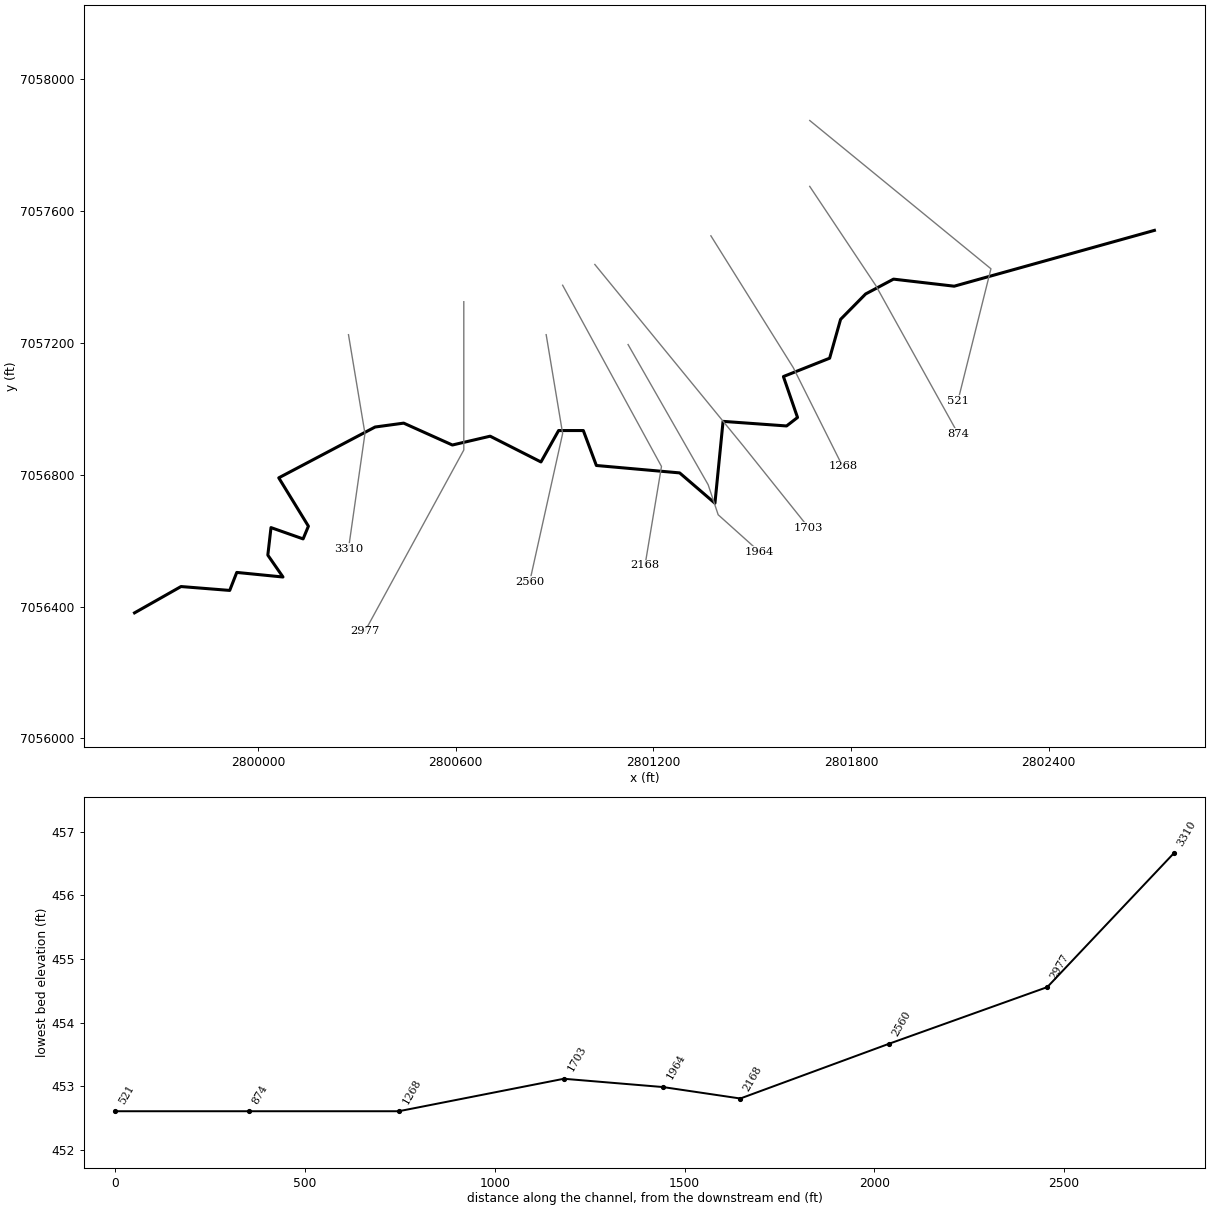
--- UNT 082 in LFCCL Watershed.prj (project) ---

Proj Title=UNT 082 in LFCCL Watershed Base Level Engineering
Current Plan=p01
Default Exp/Contr=0.3,0.1
English Units
Geom File=g01
Flow File=f01
Plan File=p01
BEGIN DESCRIPTION:
UNT 082 in LFCCL Watershed
END DESCRIPTION:

--- UNT 082 in LFCCL Watershed.p01 (plan) ---

Plan Title=Multiple Run
Short Identifier=Multiple
Geom File=g01
Flow File=f01
Subcritical Flow
K Sum by GR= 0
Std Step Tol= 0.01
Critical Tol= 0.01
Num of Std Step Trials= 20
Max Error Tol= 0.3
Flow Tol Ratio= 0.001
Split Flow NTrial= 30
Split Flow Tol= 0.02
Split Flow Ratio= 0.02
Log Output Level= 0
Friction Slope Method= 1
Unsteady Friction Slope Method= 2
Unsteady Bridges Friction Slope Method= 1
Parabolic Critical Depth
Global Vel Dist=  1 , 1 , 1
Global Log Level= 0
CheckData=True
Encroach Param= -1, 0, 0, 0
BEGIN DESCRIPTION:
Multiple Run
END DESCRIPTION:

--- UNT 082 in LFCCL Watershed.f01 (steady flow) ---

Flow Title=Multiple
Number of Profiles=7
Profile Names=10-year,25-year,50-year,1pct_min,100-year,1pct_plu,500-year
River Rch & RM= UNT 082 in LFCCL,Reach-1,3310
     433     566     673     397     793    1582    1101
Boundary for River Rch & Prof#=UNT 082 in LFCCL,Reach-1,1
Up Type=0
Dn Type=3
Dn Slope=0.005
Boundary for River Rch & Prof#=UNT 082 in LFCCL,Reach-1,2
Up Type=0
Dn Type=3
Dn Slope=0.005
Boundary for River Rch & Prof#=UNT 082 in LFCCL,Reach-1,3
Up Type=0
Dn Type=3
Dn Slope=0.005
Boundary for River Rch & Prof#=UNT 082 in LFCCL,Reach-1,4
Up Type=0
Dn Type=3
Dn Slope=0.005
Boundary for River Rch & Prof#=UNT 082 in LFCCL,Reach-1,5
Up Type=0
Dn Type=3
Dn Slope=0.005
Boundary for River Rch & Prof#=UNT 082 in LFCCL,Reach-1,6
Up Type=0
Dn Type=3
Dn Slope=0.005
Boundary for River Rch & Prof#=UNT 082 in LFCCL,Reach-1,7
Up Type=0
Dn Type=3
Dn Slope=0.005

--- UNT 082 in LFCCL Watershed.g01 (geometry) ---

Geom Title=Existing Conditions

River Reach=UNT 082 in LFCCL,Reach-1
Reach XY= 30
      2799625.59      7056380.71      2799766.65      7056460.59
      2799914.47      7056448.81      2799935.89      7056503.44
      2800076.21      7056489.51      2800030.15      7056555.92
      2800039.79      7056639.47      2800137.27      7056605.19
      2800153.33      7056643.76      2800063.36      7056790.50
      2800355.78      7056944.74      2800442.54      7056956.53
      2800590.36      7056890.12      2800704.97      7056916.90
      2800859.21      7056838.70      2800912.77      7056934.03
      2800987.75      7056934.03      2801027.38      7056827.99
      2801280.17      7056805.50      2801387.28      7056713.38
      2801411.92      7056961.88      2801604.72      7056947.96
      2801637.93      7056973.67      2801595.08      7057097.92
      2801735.40      7057153.62      2801768.61      7057271.44
      2801844.66      7057348.56      2801929.28      7057393.55
      2802113.51      7057372.13      2802721.22      7057541.54

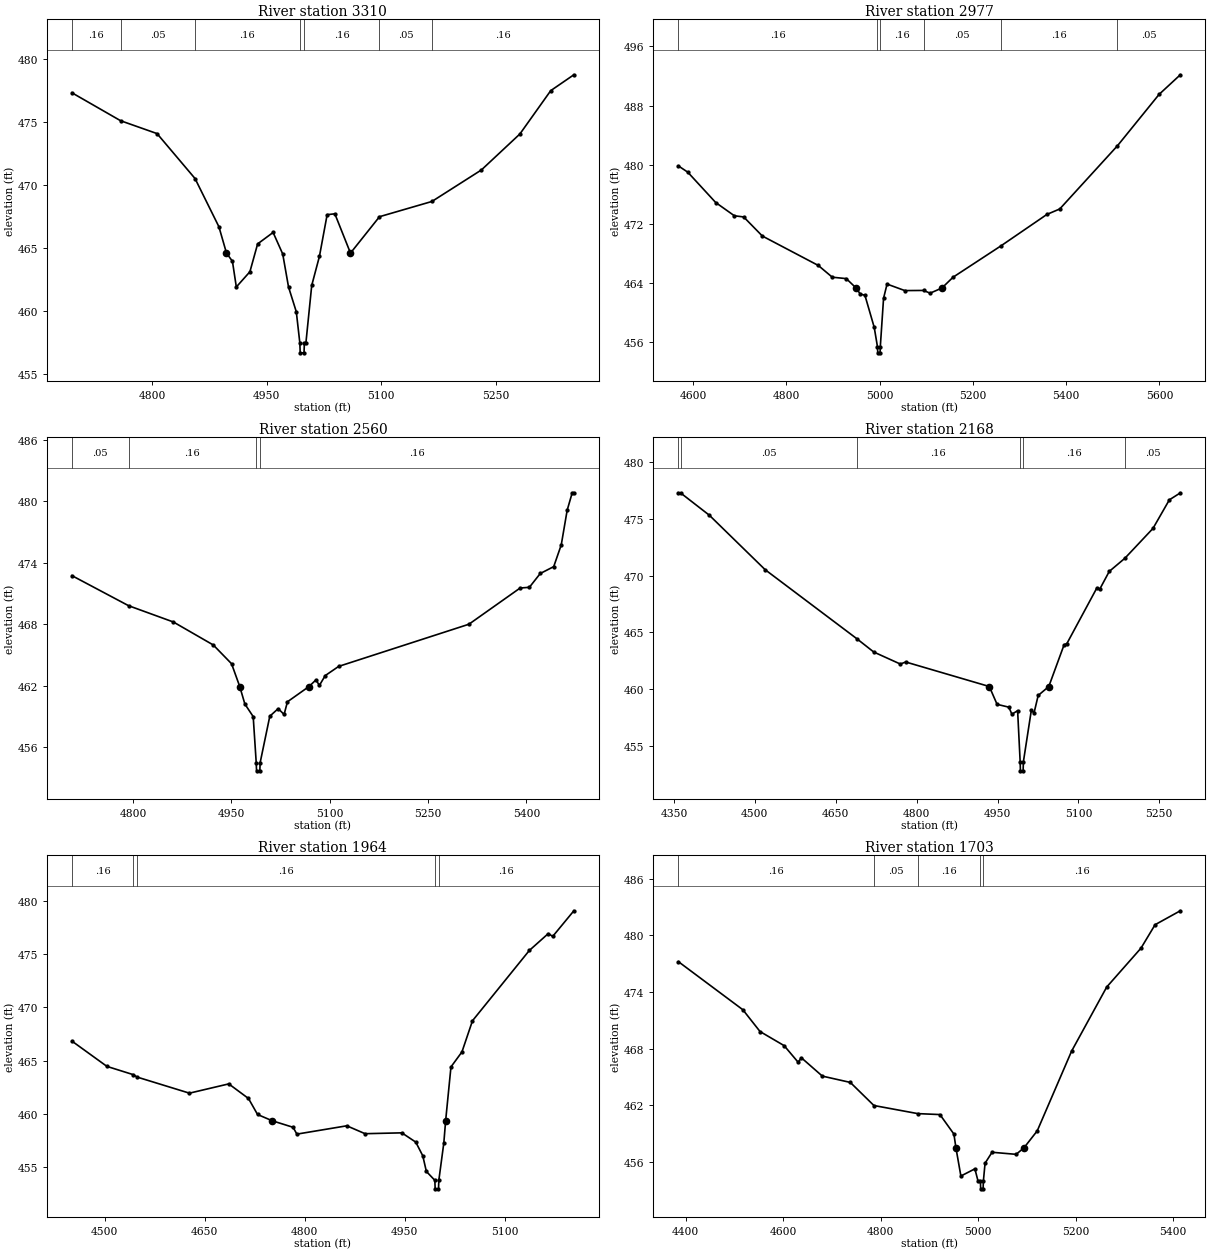
Type RM Length L Ch R = 1,3310,333,333,333
BEGIN DESCRIPTION:
UNT 082 in LFCCL Watershed 8.0
END DESCRIPTION:
XS GIS Cut Line= 3
      2800275.00      7057224.98      2800325.00      7056925.00
      2800275.00      7056574.97
#Sta/Elev= 30
  4694.8  477.31  4758.6  475.09  4806.3  474.07  4856.1  470.50  4887.4  466.67
  4897.3  464.58  4905.1  463.93  4910.2  461.89  4928.0  463.10  4938.1  465.31
  4958.4  466.22  4971.0  464.51  4978.6  461.89  4988.8  459.92  4993.4  457.46
  4993.9  456.66  4998.9  456.66  4999.4  457.46  5001.4  457.46  5009.0  462.01
  5019.1  464.32  5029.2  467.63  5039.3  467.70  5059.8  464.58  5097.8  467.47
  5166.5  468.68  5231.3  471.18  5281.8  474.04  5322.2  477.48  5352.5  478.74
#Mann=7,-1,0
  4694.8    0.16       0  4758.6    0.05       0  4856.1    0.16       0
  4993.4    0.07       0  4999.4    0.16       0  5097.8    0.05       0
  5166.5    0.16       0
Bank Sta=4897.3,5059.8
Exp/Cntr=0.3,0.1

Type RM Length L Ch R = 1,2977,417,417,417
BEGIN DESCRIPTION:
UNT 082 in LFCCL Watershed 7.0
END DESCRIPTION:
XS GIS Cut Line= 3
      2800625.00      7057325.05      2800625.00      7056875.00
      2800325.02      7056325.04
#Sta/Elev= 30
  4568.3  479.84  4588.3  479.00  4648.3  474.89  4688.3  473.10  4708.3  472.94
  4748.3  470.36  4868.3  466.38  4898.3  464.79  4928.3  464.60  4949.6  463.32
  4958.3  462.51  4968.3  462.35  4988.3  458.00  4995.3  455.36  4995.8  454.56
  5000.8  454.56  5001.3  455.36  5008.3  461.94  5015.8  463.86  5053.9  462.98
  5094.0  463.00  5108.1  462.63  5133.3  463.32  5157.4  464.79  5260.6  469.05
  5358.6  473.28  5386.2  474.02  5510.0  482.57  5599.3  489.52  5644.8  492.17
#Mann=6,-1,0
  4568.3    0.16       0  4995.3    0.07       0  5001.3    0.16       0
  5094.0    0.05       0  5260.6    0.16       0  5510.0    0.05       0
Bank Sta=4949.6,5133.3
Exp/Cntr=0.3,0.1

Type RM Length L Ch R = 1,2560,392,392,392
BEGIN DESCRIPTION:
UNT 082 in LFCCL Watershed 6.0
END DESCRIPTION:
XS GIS Cut Line= 3
      2800875.00      7057225.02      2800925.00      7056925.00
      2800825.01      7056475.04
#Sta/Elev= 30
  4707.1  472.75  4793.5  469.81  4861.7  468.22  4922.6  465.97  4950.4  464.14
  4962.9  461.91  4970.7  460.20  4983.4  458.97  4988.0  454.47  4988.5  453.67
  4993.5  453.67  4994.0  454.47  5008.7  459.01  5021.5  459.75  5030.5  459.18
  5035.6  460.42  5068.4  461.91  5079.1  462.56  5084.3  462.02  5093.2  462.98
  5113.7  463.88  5312.2  468.00  5390.3  471.54  5404.4  471.61  5421.0  472.96
  5441.5  473.63  5453.0  475.76  5462.0  479.14  5469.7  480.85  5472.2  480.85
#Mann=4,-1,0
  4707.1    0.05       0  4793.5    0.16       0  4988.0    0.07       0
  4994.0    0.16       0
Bank Sta=4962.9,5068.4
Exp/Cntr=0.3,0.1

Type RM Length L Ch R = 1,2168,204,204,204
BEGIN DESCRIPTION:
UNT 082 in LFCCL Watershed 5.0
END DESCRIPTION:
XS GIS Cut Line= 3
      2800924.99      7057375.01      2801225.00      7056825.00
      2801174.99      7056524.95
#Sta/Elev= 30
  4358.3  477.31  4362.8  477.28  4415.7  475.33  4519.2  470.53  4688.9  464.46
  4720.5  463.28  4769.8  462.22  4779.8  462.40  4934.8  460.24  4949.2  458.67
  4971.0  458.42  4976.7  457.80  4987.3  458.11  4992.0  453.61  4992.5  452.81
  4997.5  452.81  4998.0  453.61  5012.7  458.14  5017.8  457.92  5025.4  459.45
  5045.1  460.24  5073.5  463.92  5078.6  464.02  5134.3  468.93  5139.4  468.80
  5157.2  470.38  5186.2  471.54  5238.3  474.17  5268.7  476.69  5289.0  477.30
#Mann=6,-1,0
  4358.3    0.16       0  4362.8    0.05       0  4688.9    0.16       0
  4992.0    0.07       0  4998.0    0.16       0  5186.2    0.05       0
Bank Sta=4934.8,5045.1
Exp/Cntr=0.3,0.1

Type RM Length L Ch R = 1,1964,261,261,261
BEGIN DESCRIPTION:
XS3565A
END DESCRIPTION:
XS GIS Cut Line= 4
      2801123.63      7057194.99      2801366.70      7056769.60
      2801397.09      7056678.46      2801521.50      7056566.92
#Sta/Elev= 30
  4450.8  466.84  4503.3  464.47  4543.1  463.69  4548.5  463.47  4627.1  461.96
  4686.1  462.83  4715.7  461.46  4729.3  459.96  4751.4  459.37  4782.6  458.76
  4788.3  458.12  4863.2  458.90  4890.6  458.16  4945.8  458.24  4966.7  457.37
  4977.2  456.09  4982.6  454.62  4995.3  453.79  4995.8  452.99  5000.8  452.99
  5001.3  453.79  5008.8  457.30  5011.5  459.37  5019.5  464.42  5036.0  465.83
  5051.8  468.75  5137.1  475.34  5165.5  476.92  5172.2  476.66  5203.9  479.06
#Mann=5,-1,0
  4450.8    0.16       0  4543.1    0.05       0  4548.5    0.16       0
  4995.3    0.07       0  5001.3    0.16       0
Bank Sta=4751.4,5011.5
Exp/Cntr=0.3,0.1

Type RM Length L Ch R = 1,1703,435,435,435
BEGIN DESCRIPTION:
UNT 082 in LFCCL Watershed 4.0
END DESCRIPTION:
XS GIS Cut Line= 3
      2801022.74      7057438.03      2801472.74      7056888.02
      2801671.93      7056639.03
#Sta/Elev= 30
  4385.0  477.22  4517.2  472.12  4552.4  469.81  4601.9  468.31  4630.6  466.55
  4637.1  467.03  4680.2  465.08  4737.6  464.41  4786.0  461.96  4876.0  461.10
  4921.4  461.00  4950.1  458.93  4954.2  457.48  4964.4  454.48  4993.1  455.24
  4999.6  453.94  5004.5  453.92  5005.0  453.12  5010.0  453.12  5010.5  453.92
  5014.0  455.84  5028.3  457.00  5077.8  456.78  5093.9  457.48  5121.0  459.27
  5191.4  467.72  5263.5  474.53  5333.9  478.66  5362.7  481.14  5414.5  482.62
#Mann=5,-1,0
  4385.0    0.16       0  4786.0    0.05       0  4876.0    0.16       0
  5004.5    0.07       0  5010.5    0.16       0
Bank Sta=4954.2,5093.9
Exp/Cntr=0.3,0.1

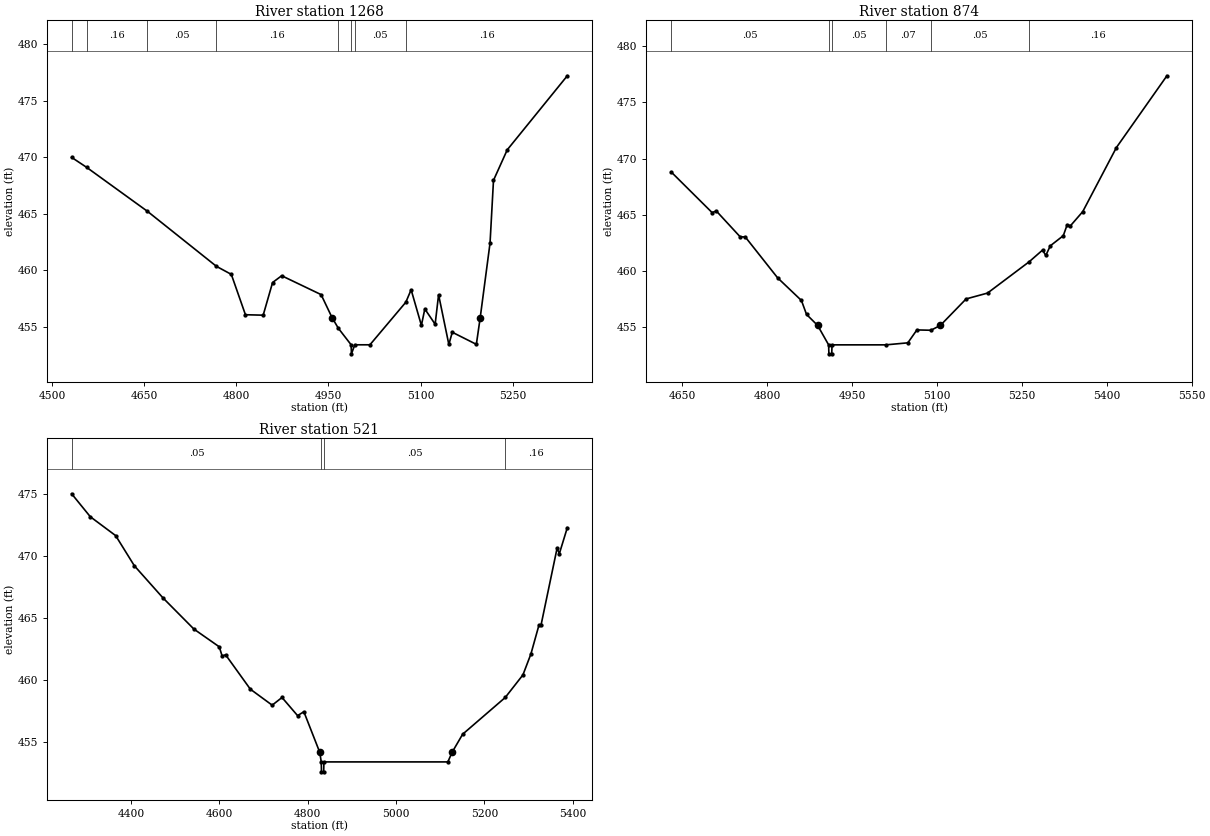
Type RM Length L Ch R = 1,1268,394,394,394
BEGIN DESCRIPTION:
UNT 082 in LFCCL Watershed 3.0
END DESCRIPTION:
XS GIS Cut Line= 3
      2801375.00      7057525.00      2801625.00      7057125.00
      2801775.00      7056825.01
#Sta/Elev= 30
  4531.9  469.99  4556.3  469.11  4655.3  465.22  4767.7  460.35  4791.9  459.64
  4814.9  456.07  4843.8  456.03  4859.1  458.92  4873.9  459.52  4938.1  457.85
  4955.9  455.82  4966.2  454.87  4987.0  453.41  4987.5  452.61  4993.0  453.41
  5017.6  453.41  5076.1  457.18  5084.7  458.28  5101.4  455.13  5107.0  456.58
  5123.8  455.23  5129.4  457.84  5146.1  453.44  5151.7  454.52  5190.9  453.45
  5197.2  455.82  5213.2  462.42  5218.8  467.96  5241.2  470.66  5339.0  477.21
#Mann=8,-1,0
  4531.9    0.05       0  4556.3    0.16       0  4655.3    0.05       0
  4767.7    0.16       0  4966.2    0.05       0  4987.0   0.035       0
  4993.0    0.05       0  5076.1    0.16       0
Bank Sta=4955.9,5197.2
Exp/Cntr=0.3,0.1

Type RM Length L Ch R = 1,874,353,353,353
BEGIN DESCRIPTION:
UNT 082 in LFCCL Watershed 2.0
END DESCRIPTION:
XS GIS Cut Line= 3
      2801674.99      7057675.01      2801875.00      7057375.00
      2802124.98      7056925.04
#Sta/Elev= 30
  4631.0  468.80  4703.1  465.19  4710.6  465.33  4752.7  463.03  4761.7  463.02
  4818.8  459.38  4860.9  457.36  4869.9  456.12  4889.5  455.14  4908.9  453.41
  4909.4  452.61  4914.4  452.61  4914.9  453.41  5009.9  453.41  5048.8  453.59
  5064.8  454.74  5089.5  454.71  5106.2  455.14  5151.7  457.50  5189.5  458.02
  5263.1  460.81  5286.7  461.85  5292.4  461.37  5300.4  462.23  5323.3  463.13
  5330.2  464.11  5335.9  464.01  5357.6  465.27  5417.1  470.98  5506.3  477.37
#Mann=6,-1,0
  4631.0    0.05       0  4908.9   0.033       0  4914.9    0.05       0
  5009.9    0.07       0  5089.5    0.05       0  5263.1    0.16       0
Bank Sta=4889.5,5106.2
Exp/Cntr=0.3,0.1

Type RM Length L Ch R = 1,521,0,0,0
BEGIN DESCRIPTION:
UNT 082 in LFCCL Watershed 1.0
END DESCRIPTION:
XS GIS Cut Line= 3
      2801675.02      7057874.98      2802225.00      7057425.00
      2802125.00      7057025.02
#Sta/Elev= 30
  4265.1  475.01  4307.4  473.16  4364.8  471.64  4407.2  469.21  4471.8  466.63
  4542.1  464.11  4599.6  462.68  4606.0  461.94  4613.9  462.04  4669.9  459.27
  4719.4  457.98  4741.7  458.60  4776.9  457.14  4791.2  457.45  4827.1  454.19
  4830.6  453.41  4831.1  452.61  4836.1  452.61  4836.6  453.41  5117.4  453.41
  5127.1  454.19  5150.9  455.64  5247.4  458.60  5287.5  460.42  5305.6  462.11
  5323.6  464.41  5328.7  464.47  5364.8  470.62  5370.0  470.19  5388.0  472.28
#Mann=4,-1,0
  4265.1    0.05       0  4830.6   0.033       0  4836.6    0.05       0
  5247.4    0.16       0
Bank Sta=4827.1,5127.1
Exp/Cntr=0.3,0.1

Chan Stop Cuts=-1