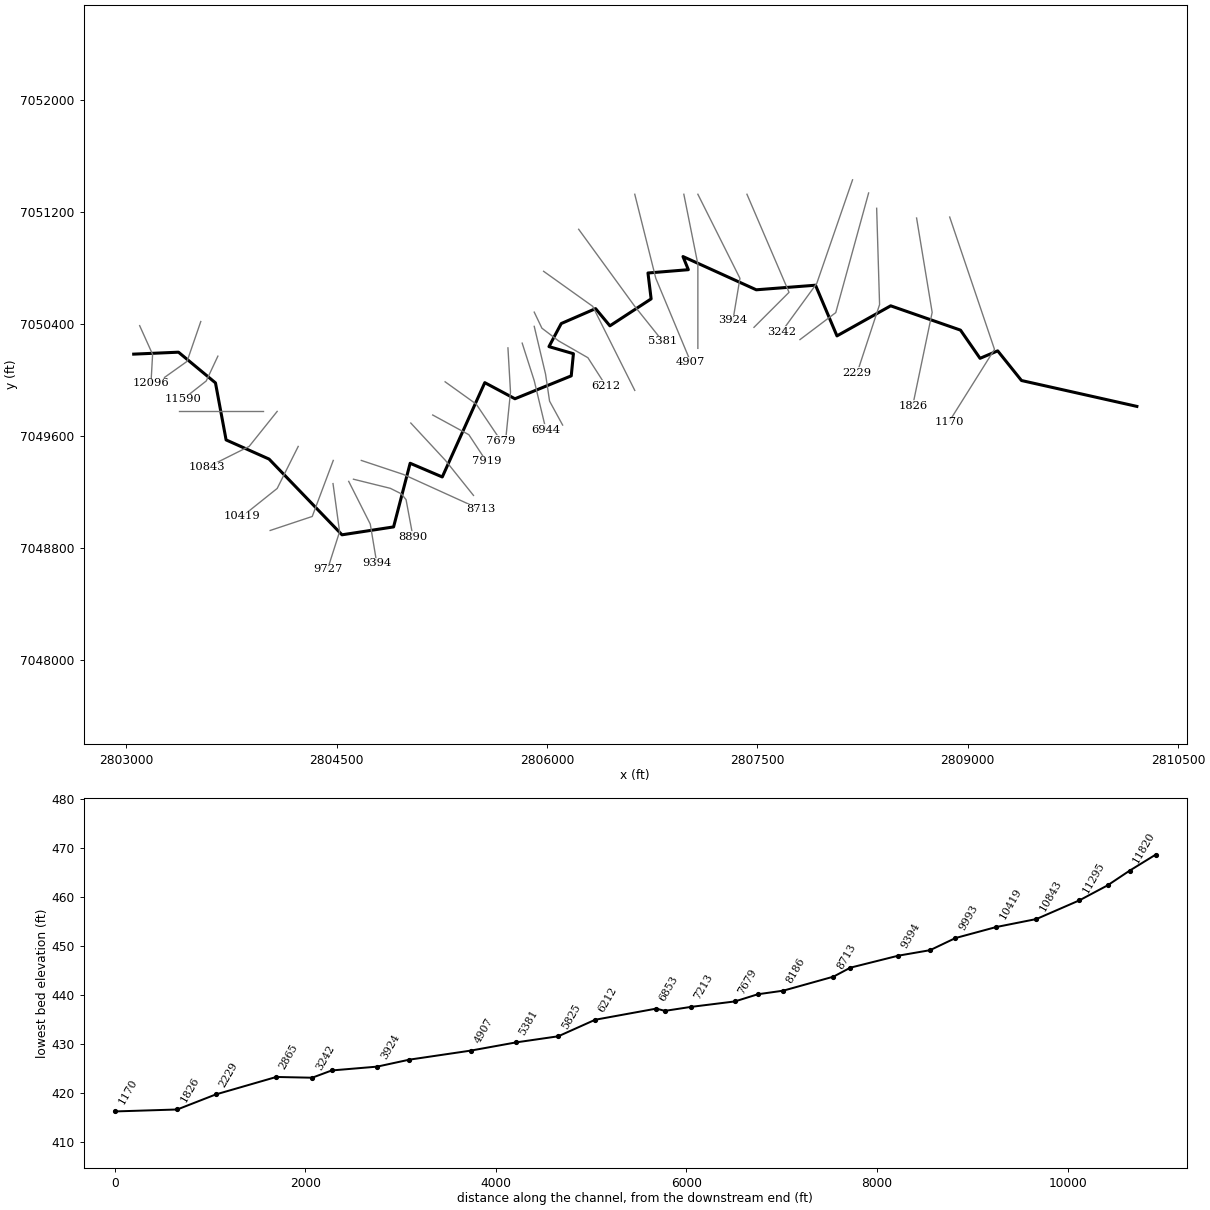
--- UNT 083 in LFCCL Watershed.prj (project) ---

Proj Title=UNT 083 in LFCCL Watershed Base Level Engineering
Current Plan=p01
Default Exp/Contr=0.3,0.1
English Units
Geom File=g01
Flow File=f01
Plan File=p01
BEGIN DESCRIPTION:
UNT 083 in LFCCL Watershed
END DESCRIPTION:

--- UNT 083 in LFCCL Watershed.p01 (plan) ---

Plan Title=Multiple Run
Short Identifier=Multiple
Geom File=g01
Flow File=f01
Subcritical Flow
K Sum by GR= 0
Std Step Tol= 0.01
Critical Tol= 0.01
Num of Std Step Trials= 20
Max Error Tol= 0.3
Flow Tol Ratio= 0.001
Split Flow NTrial= 30
Split Flow Tol= 0.02
Split Flow Ratio= 0.02
Log Output Level= 0
Friction Slope Method= 1
Unsteady Friction Slope Method= 2
Unsteady Bridges Friction Slope Method= 1
Parabolic Critical Depth
Global Vel Dist=  1 , 1 , 1
Global Log Level= 0
CheckData=True
Encroach Param= -1, 0, 0, 0
BEGIN DESCRIPTION:
Multiple Run
END DESCRIPTION:

--- UNT 083 in LFCCL Watershed.f01 (steady flow) ---

Flow Title=Multiple
Number of Profiles=7
Profile Names=10-year,25-year,50-year,1pct_min,100-year,1pct_plu,500-year
River Rch & RM= UNT 083 in LFCCL,Reach-1,12096
     204     256     295     170     340     678     449
River Rch & RM= UNT 083 in LFCCL,Reach-1,9727
     473     624     744     442     882    1760    1240
River Rch & RM= UNT 083 in LFCCL,Reach-1,2229
     598     799     963     577    1150    2295    1644
Boundary for River Rch & Prof#=UNT 083 in LFCCL,Reach-1,1
Up Type=0
Dn Type=3
Dn Slope=0.005
Boundary for River Rch & Prof#=UNT 083 in LFCCL,Reach-1,2
Up Type=0
Dn Type=3
Dn Slope=0.005
Boundary for River Rch & Prof#=UNT 083 in LFCCL,Reach-1,3
Up Type=0
Dn Type=3
Dn Slope=0.005
Boundary for River Rch & Prof#=UNT 083 in LFCCL,Reach-1,4
Up Type=0
Dn Type=3
Dn Slope=0.005
Boundary for River Rch & Prof#=UNT 083 in LFCCL,Reach-1,5
Up Type=0
Dn Type=3
Dn Slope=0.005
Boundary for River Rch & Prof#=UNT 083 in LFCCL,Reach-1,6
Up Type=0
Dn Type=3
Dn Slope=0.005
Boundary for River Rch & Prof#=UNT 083 in LFCCL,Reach-1,7
Up Type=0
Dn Type=3
Dn Slope=0.005

--- UNT 083 in LFCCL Watershed.g01 (geometry) ---

Geom Title=Existing Conditions

River Reach=UNT 083 in LFCCL,Reach-1
Reach XY= 30
      2803051.84      7050183.79      2803371.30      7050197.65
      2803634.96      7049978.61      2803710.75      7049571.42
      2804017.39      7049434.54      2804537.25      7048894.10
      2804905.17      7048950.45      2805023.25      7049404.78
      2805252.38      7049306.98      2805555.54      7049980.21
      2805770.44      7049865.21      2806172.05      7050028.65
      2806187.56      7050186.85      2806013.17      7050237.49
      2806100.79      7050402.22      2806345.62      7050508.64
      2806447.69      7050385.77      2806741.66      7050578.19
      2806719.22      7050762.93      2807007.01      7050786.58
      2806968.90      7050880.37      2807491.45      7050643.03
      2807913.92      7050675.78      2808066.94      7050314.05
      2808450.00      7050528.65      2808947.94      7050355.09
      2809087.18      7050153.86      2809213.13      7050207.13
      2809382.81      7049995.42      2810205.59      7049810.71

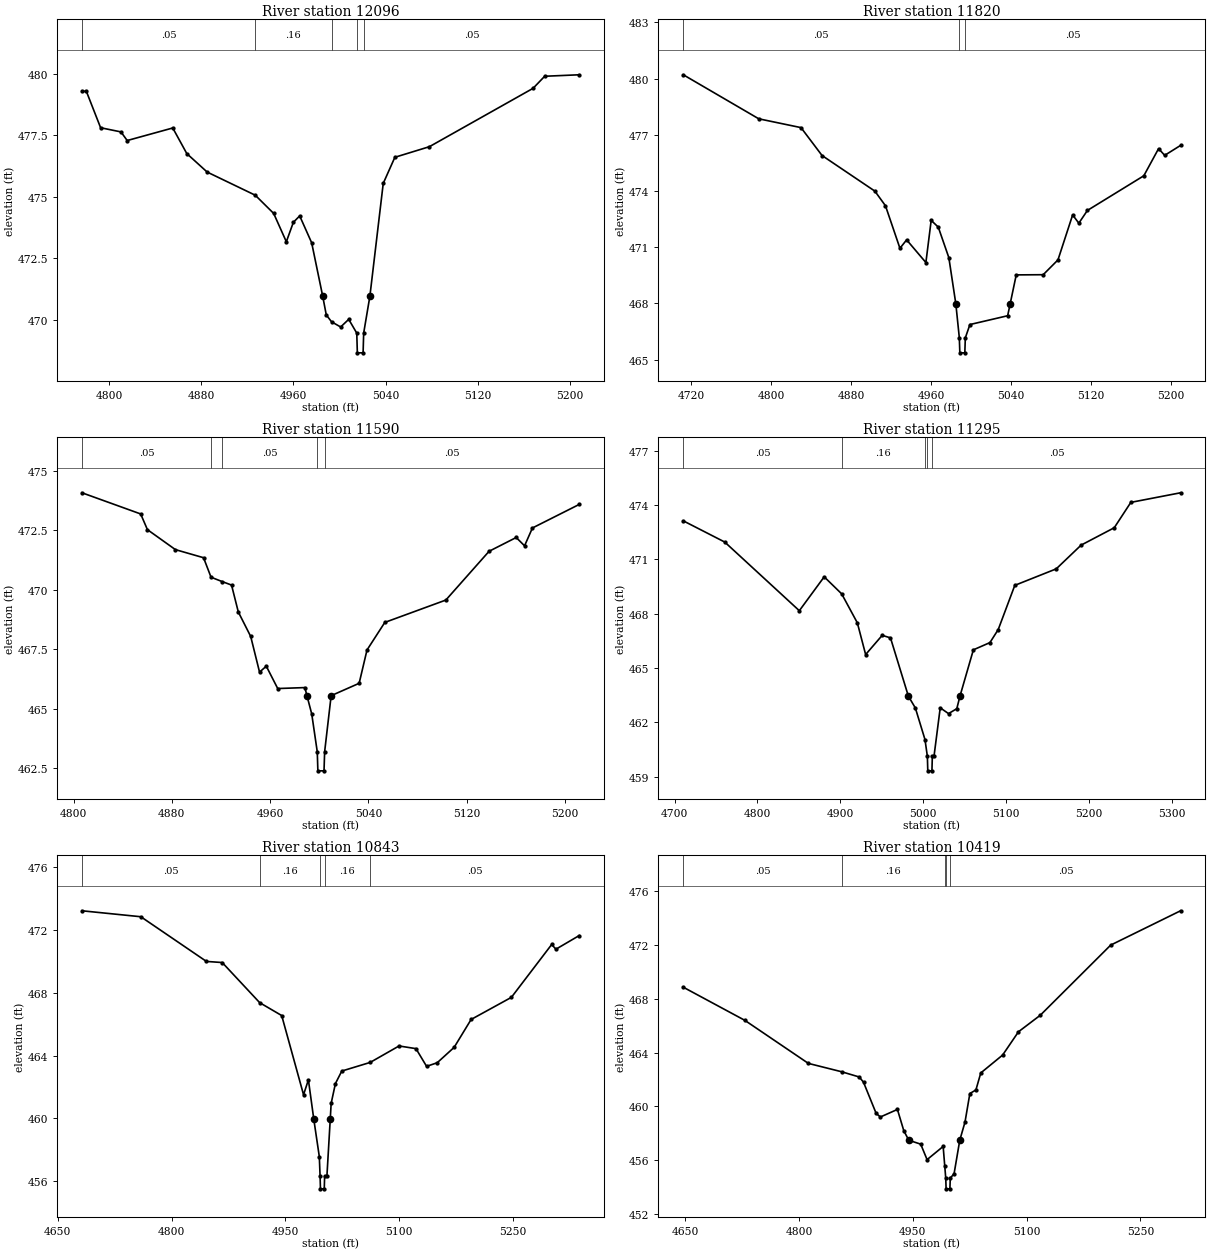
Type RM Length L Ch R = 1,12096,276,276,276
BEGIN DESCRIPTION:
UNT 083 in LFCCL Watershed 20.0
END DESCRIPTION:
XS GIS Cut Line= 3
      2803094.33      7050386.95      2803186.67      7050181.94
      2803175.00      7049975.01
#Sta/Elev= 30
  4776.2  479.28  4780.0  479.28  4792.4  477.80  4810.1  477.63  4815.5  477.28
  4855.1  477.79  4867.3  476.75  4885.0  476.00  4926.8  475.06  4942.8  474.32
  4953.8  473.17  4959.9  473.96  4965.4  474.22  4975.8  473.13  4985.4  470.96
  4988.5  470.20  4993.1  469.92  5001.0  469.71  5008.0  470.02  5015.0  469.46
  5015.5  468.66  5020.5  468.66  5021.0  469.46  5026.4  470.96  5038.0  475.54
  5048.1  476.60  5078.1  477.03  5168.2  479.40  5178.3  479.89  5208.3  479.95
#Mann=5,-1,0
  4776.2    0.05       0  4926.8    0.16       0  4993.1    0.05       0
  5015.0    0.03       0  5021.0    0.05       0
Bank Sta=4985.4,5026.4
Exp/Cntr=0.3,0.1

Type RM Length L Ch R = 1,11820,230,230,230
BEGIN DESCRIPTION:
XS3566A
END DESCRIPTION:
XS GIS Cut Line= 3
      2803530.19      7050416.48      2803432.31      7050132.08
      2803271.62      7050017.56
#Sta/Elev= 30
  4711.9  480.20  4787.5  477.85  4829.8  477.38  4850.9  475.89  4903.8  473.99
  4914.4  473.21  4928.9  470.94  4935.6  471.39  4954.9  470.18  4960.2  472.43
  4967.3  472.07  4977.9  470.44  4984.9  467.97  4988.4  466.16  4988.9  465.36
  4993.9  465.36  4994.4  466.16  4999.0  466.87  5036.8  467.34  5039.3  467.97
  5045.4  469.52  5072.4  469.53  5087.2  470.32  5101.9  472.72  5108.1  472.28
  5116.7  472.96  5173.2  474.81  5188.0  476.26  5194.1  475.90  5210.0  476.43
#Mann=3,-1,0
  4711.9    0.05       0  4988.4    0.03       0  4994.4    0.05       0
Bank Sta=4984.9,5039.3
Exp/Cntr=0.3,0.1

Type RM Length L Ch R = 1,11590,295,295,295
BEGIN DESCRIPTION:
XS3567A
END DESCRIPTION:
XS GIS Cut Line= 3
      2803652.11      7050169.37      2803569.00      7049992.08
      2803404.65      7049862.82
#Sta/Elev= 30
  4806.8  474.07  4854.6  473.18  4860.1  472.52  4882.9  471.68  4905.8  471.34
  4911.9  470.52  4920.8  470.34  4928.6  470.19  4934.1  469.06  4944.2  468.03
  4951.4  466.53  4956.9  466.78  4966.2  465.84  4988.3  465.88  4990.0  465.54
  4993.9  464.77  4998.4  463.18  4998.9  462.38  5003.9  462.38  5004.4  463.18
  5009.7  465.54  5032.5  466.06  5038.9  467.46  5053.4  468.62  5103.1  469.56
  5138.3  471.61  5160.4  472.19  5167.2  471.84  5173.6  472.59  5211.7  473.58
#Mann=5,-1,0
  4806.8    0.05       0  4911.9    0.16       0  4920.8    0.05       0
  4998.4    0.03       0  5004.4    0.05       0
Bank Sta=4990,5009.7
Exp/Cntr=0.3,0.1

Type RM Length L Ch R = 1,11295,452,452,452
BEGIN DESCRIPTION:
UNT 083 in LFCCL Watershed 19.0
END DESCRIPTION:
XS GIS Cut Line= 3
      2803975.04      7049775.00      2803675.00      7049775.00
      2803375.04      7049775.00
#Sta/Elev= 30
  4710.6  473.13  4760.6  471.96  4850.6  468.17  4880.6  470.04  4901.7  469.10
  4920.6  467.50  4930.6  465.75  4950.6  466.81  4960.6  466.67  4982.2  463.45
  4990.6  462.80  5002.2  461.06  5005.1  460.13  5005.6  459.33  5010.6  459.33
  5011.1  460.13  5013.1  460.13  5020.6  462.81  5030.6  462.49  5040.6  462.76
  5044.4  463.45  5060.6  466.01  5080.6  466.41  5090.6  467.13  5110.6  469.57
  5160.6  470.48  5190.6  471.79  5230.6  472.75  5250.6  474.15  5310.6  474.68
#Mann=5,-1,0
  4710.6    0.05       0  4901.7    0.16       0  5002.2    0.05       0
  5005.1    0.07       0  5011.1    0.05       0
Bank Sta=4982.2,5044.4
Exp/Cntr=0.3,0.1

Type RM Length L Ch R = 1,10843,424,424,424
BEGIN DESCRIPTION:
UNT 083 in LFCCL Watershed 18.0
END DESCRIPTION:
XS GIS Cut Line= 3
      2804074.99      7049774.99      2803875.00      7049525.00
      2803575.04      7049375.02
#Sta/Elev= 30
  4681.8  473.24  4759.4  472.86  4845.9  470.01  4866.7  469.94  4916.1  467.38
  4945.1  466.56  4973.9  461.51  4980.3  462.46  4987.4  459.95  4994.7  457.56
  4995.7  456.31  4996.2  455.51  5001.2  455.51  5001.7  456.31  5004.7  456.31
  5009.1  459.95  5010.3  460.96  5015.9  462.22  5024.3  463.02  5061.7  463.57
  5099.8  464.62  5122.1  464.45  5136.1  463.32  5150.1  463.55  5172.4  464.53
  5194.8  466.31  5247.9  467.72  5301.0  471.09  5306.6  470.79  5337.3  471.66
#Mann=5,-1,0
  4681.8    0.05       0  4916.1    0.16       0  4995.7    0.07       0
  5001.7    0.16       0  5061.7    0.05       0
Bank Sta=4987.4,5009.1
Exp/Cntr=0.3,0.1

Type RM Length L Ch R = 1,10419,426,426,426
BEGIN DESCRIPTION:
UNT 083 in LFCCL Watershed 17.0
END DESCRIPTION:
XS GIS Cut Line= 3
      2804225.00      7049524.99      2804075.00      7049225.00
      2803824.97      7049024.98
#Sta/Elev= 30
  4647.4  468.85  4728.5  466.39  4812.3  463.19  4856.1  462.57  4879.4  462.18
  4885.0  461.79  4901.7  459.47  4907.3  459.21  4929.7  459.77  4938.1  458.19
  4944.7  457.48  4960.4  457.19  4968.8  456.04  4990.0  457.02  4992.1  455.57
  4993.4  454.67  4993.9  453.87  4998.9  453.87  4999.4  454.67  5004.4  454.99
  5011.9  457.48  5018.8  458.83  5025.2  460.95  5033.2  461.22  5039.6  462.48
  5068.4  463.81  5089.3  465.54  5118.1  466.77  5210.9  471.98  5303.0  474.53
#Mann=5,-1,0
  4647.4    0.05       0  4856.1    0.16       0  4992.1    0.05       0
  4993.4    0.03       0  4999.4    0.05       0
Bank Sta=4944.7,5011.9
Exp/Cntr=0.3,0.1

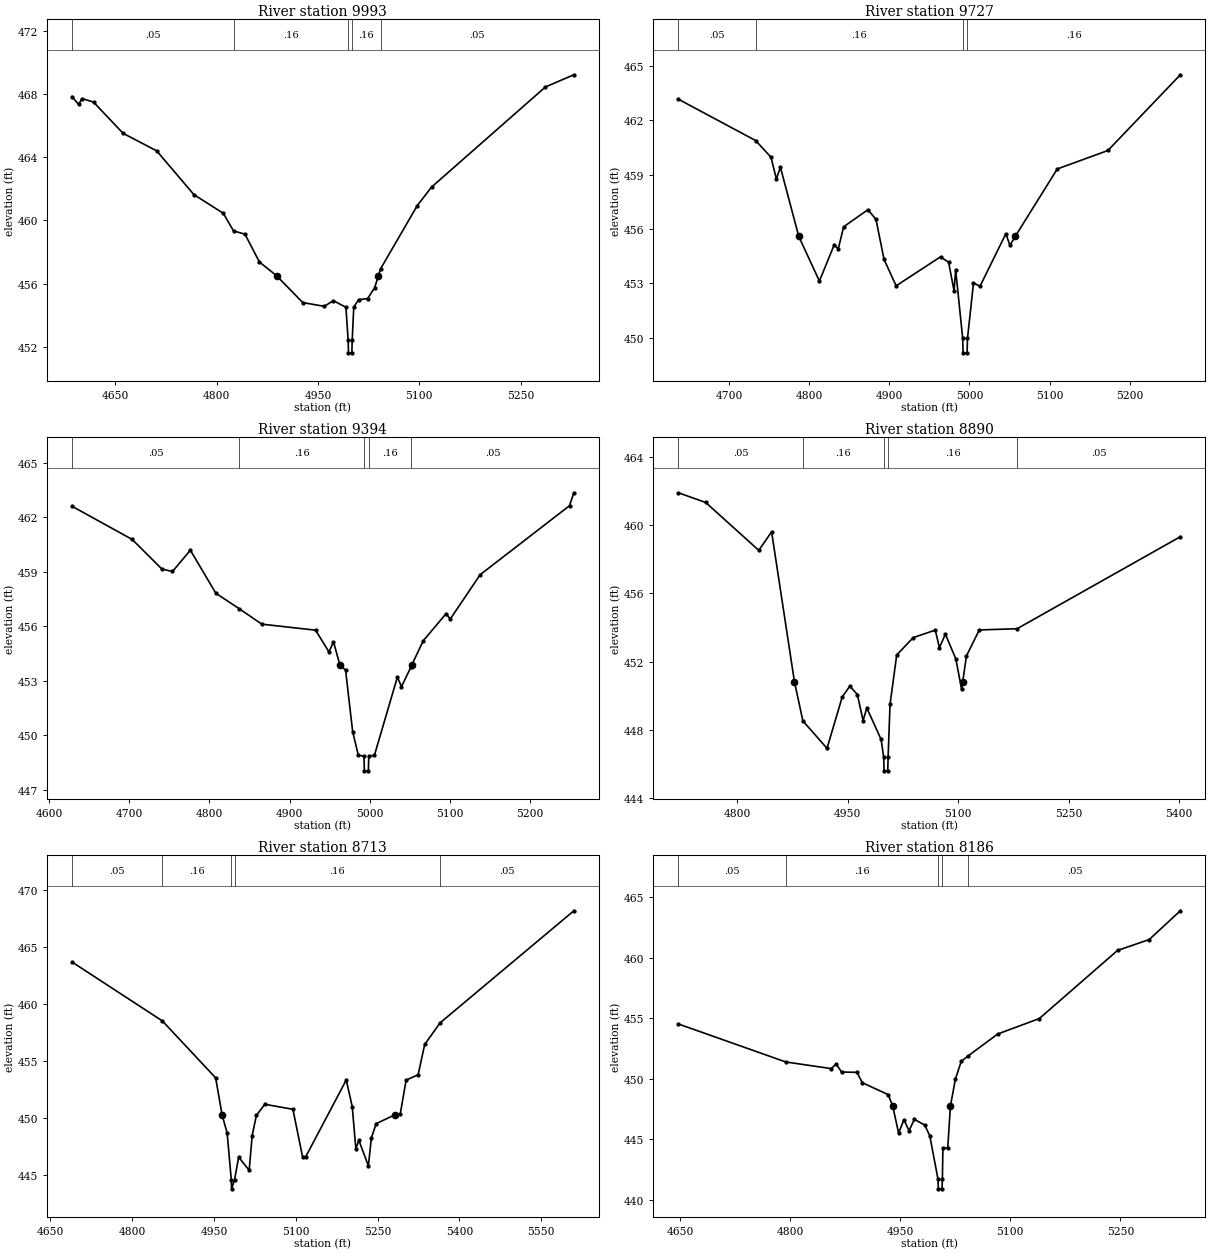
Type RM Length L Ch R = 1,9993,266,266,266
BEGIN DESCRIPTION:
UNT 083 in LFCCL Watershed 16.0
END DESCRIPTION:
XS GIS Cut Line= 3
      2804475.00      7049425.01      2804325.00      7049025.00
      2804025.04      7048925.01
#Sta/Elev= 30
  4585.5  467.83  4595.3  467.34  4600.6  467.71  4617.5  467.48  4661.2  465.51
  4711.0  464.40  4766.2  461.63  4809.8  460.45  4824.8  459.34  4841.8  459.13
  4863.2  457.37  4888.5  456.51  4927.3  454.81  4959.3  454.57  4972.7  454.93
  4991.3  454.51  4994.6  452.43  4995.1  451.63  5000.1  451.63  5000.6  452.43
  5002.9  454.52  5010.0  454.99  5023.3  455.06  5033.8  455.74  5039.4  456.50
  5042.6  456.94  5097.0  460.94  5118.1  462.11  5286.8  468.44  5328.9  469.21
#Mann=5,-1,0
  4585.5    0.05       0  4824.8    0.16       0  4994.6    0.07       0
  5000.6    0.16       0  5042.6    0.05       0
Bank Sta=4888.5,5039.4
Exp/Cntr=0.3,0.1

Type RM Length L Ch R = 1,9727,333,333,333
BEGIN DESCRIPTION:
XS3568A
END DESCRIPTION:
XS GIS Cut Line= 3
      2804473.23      7049259.61      2804520.10      7048915.89
      2804434.54      7048648.86
#Sta/Elev= 30
  4636.2  463.16  4732.7  460.88  4751.9  459.96  4758.6  458.76  4763.7  459.40
  4786.6  455.59  4812.4  453.12  4831.0  455.13  4836.0  454.90  4842.7  456.12
  4873.0  457.06  4883.1  456.53  4893.2  454.32  4908.3  452.86  4963.8  454.46
  4973.9  454.16  4980.7  452.59  4982.7  453.75  4991.5  449.96  4992.0  449.16
  4997.0  449.16  4997.5  449.96  5005.0  453.01  5013.2  452.84  5045.4  455.73
  5050.6  455.09  5057.2  455.59  5109.7  459.31  5173.0  460.33  5263.5  464.51
#Mann=4,-1,0
  4636.2    0.05       0  4732.7    0.16       0  4991.5    0.07       0
  4997.5    0.16       0
Bank Sta=4786.6,5057.2
Exp/Cntr=0.3,0.1

Type RM Length L Ch R = 1,9394,504,504,504
BEGIN DESCRIPTION:
XS3569A
END DESCRIPTION:
XS GIS Cut Line= 3
      2804585.19      7049275.29      2804738.85      7048970.58
      2804785.66      7048689.71
#Sta/Elev= 30
  4628.6  462.60  4703.8  460.77  4740.9  459.14  4754.0  459.01  4776.3  460.18
  4808.1  457.81  4836.9  456.97  4865.5  456.11  4932.5  455.78  4949.2  454.58
  4954.8  455.14  4962.7  453.88  4969.9  453.58  4978.7  450.20  4985.7  448.91
  4992.8  448.84  4993.3  448.04  4998.3  448.04  4998.8  448.84  5005.9  448.90
  5034.5  453.20  5039.6  452.67  5051.7  453.78  5052.6  453.88  5066.8  455.20
  5095.3  456.69  5100.4  456.39  5137.7  458.83  5249.2  462.63  5254.6  463.34
#Mann=5,-1,0
  4628.6    0.05       0  4836.9    0.16       0  4992.8    0.07       0
  4998.8    0.16       0  5051.7    0.05       0
Bank Sta=4962.7,5052.6
Exp/Cntr=0.3,0.1

Type RM Length L Ch R = 1,8890,177,177,177
BEGIN DESCRIPTION:
XS3570A
END DESCRIPTION:
XS GIS Cut Line= 5
      2804619.02      7049290.90      2804882.08      7049225.79
      2804960.20      7049186.73      2804994.05      7049145.06
      2805043.48      7048879.75
#Sta/Elev= 30
  4719.9  461.91  4757.0  461.34  4829.1  458.53  4846.5  459.62  4877.5  450.83
  4889.0  448.52  4921.8  446.91  4942.4  449.92  4952.7  450.56  4963.0  450.07
  4970.8  448.54  4975.9  449.28  4995.3  447.43  4998.8  446.39  4999.3  445.59
  5004.3  445.59  5004.8  446.39  5007.4  449.49  5016.5  452.39  5038.9  453.41
  5068.9  453.85  5074.5  452.82  5082.6  453.61  5096.8  452.16  5104.7  450.37
  5106.2  450.83  5111.2  452.33  5128.7  453.86  5180.0  453.93  5401.8  459.33
#Mann=5,-1,0
  4719.9    0.05       0  4889.0    0.16       0  4998.8    0.07       0
  5004.8    0.16       0  5180.0    0.05       0
Bank Sta=4877.5,5106.2
Exp/Cntr=0.3,0.1

Type RM Length L Ch R = 1,8713,527,527,527
BEGIN DESCRIPTION:
UNT 083 in LFCCL Watershed 13.0
END DESCRIPTION:
XS GIS Cut Line= 3
      2804674.98      7049425.01      2804975.00      7049325.00
      2805525.00      7049075.00
#Sta/Elev= 30
  4689.5  463.67  4855.4  458.49  4953.0  453.50  4964.9  450.24  4974.1  448.66
  4981.7  444.56  4982.2  443.76  4987.7  444.56  4995.2  446.54  5014.5  445.39
  5020.0  448.43  5027.7  450.20  5043.1  451.18  5094.7  450.74  5112.3  446.59
  5117.8  446.54  5192.5  453.31  5203.5  450.98  5210.1  447.27  5215.6  448.02
  5233.1  445.78  5238.6  448.23  5247.4  449.48  5281.0  450.24  5291.4  450.29
  5302.3  453.30  5324.3  453.77  5336.4  456.43  5364.5  458.32  5609.9  468.16
#Mann=5,-1,0
  4689.5    0.05       0  4855.4    0.16       0  4981.7    0.07       0
  4987.7    0.16       0  5364.5    0.05       0
Bank Sta=4964.9,5281
Exp/Cntr=0.3,0.1

Type RM Length L Ch R = 1,8186,267,267,267
BEGIN DESCRIPTION:
UNT 083 in LFCCL Watershed 12.0
END DESCRIPTION:
XS GIS Cut Line= 3
      2805027.88      7049691.96      2805275.00      7049425.00
      2805474.98      7049175.03
#Sta/Elev= 30
  4647.8  454.53  4794.1  451.39  4855.9  450.84  4862.8  451.22  4870.1  450.56
  4891.1  450.53  4898.5  449.67  4933.6  448.69  4939.9  447.73  4947.8  445.52
  4955.2  446.62  4962.0  445.70  4969.3  446.65  4983.5  446.17  4990.3  445.29
  5001.5  441.70  5002.0  440.90  5007.0  440.90  5007.5  441.70  5008.2  444.28
  5014.8  444.28  5018.4  447.73  5025.2  449.97  5033.2  451.44  5043.0  451.91
  5082.8  453.70  5139.6  454.98  5246.1  460.61  5289.3  461.51  5331.7  463.89
#Mann=5,-1,0
  4647.8    0.05       0  4794.1    0.16       0  5001.5    0.07       0
  5007.5    0.16       0  5043.0    0.05       0
Bank Sta=4939.9,5018.4
Exp/Cntr=0.3,0.1

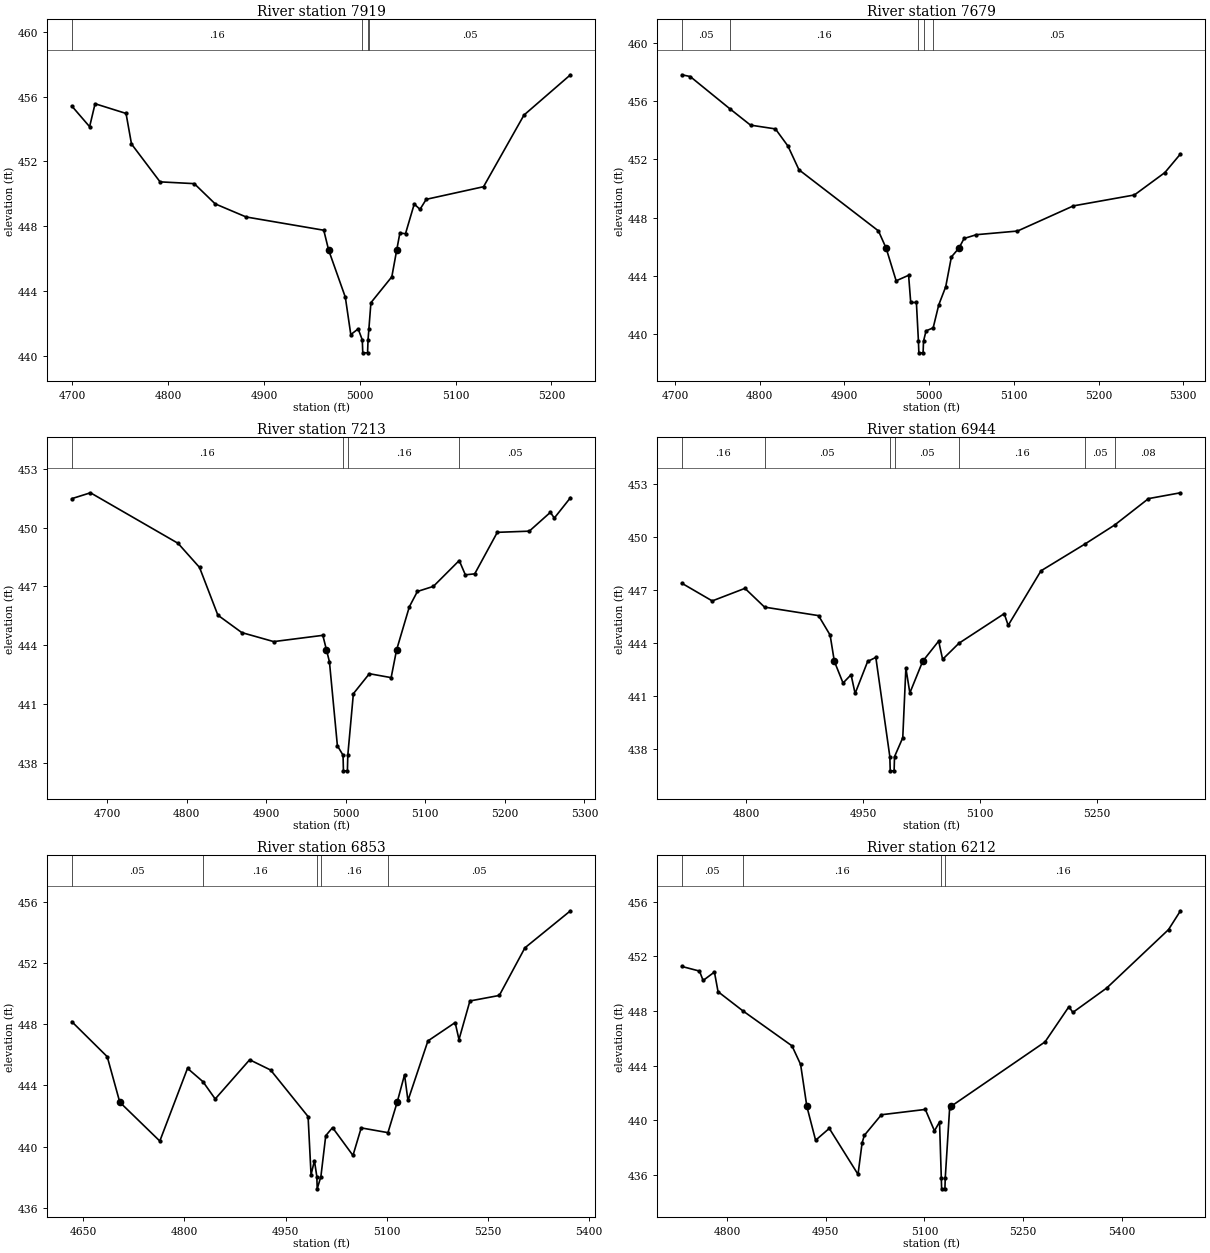
Type RM Length L Ch R = 1,7919,240,240,240
BEGIN DESCRIPTION:
XS3571A
END DESCRIPTION:
XS GIS Cut Line= 3
      2805184.18      7049749.22      2805441.97      7049608.60
      2805566.49      7049419.22
#Sta/Elev= 30
  4699.5  455.43  4718.1  454.15  4723.8  455.57  4756.1  454.97  4761.8  453.08
  4791.6  450.74  4827.3  450.63  4849.1  449.38  4881.4  448.57  4962.4  447.75
  4967.5  446.52  4984.9  443.61  4990.6  441.30  4998.3  441.65  5002.6  440.97
  5003.1  440.17  5008.1  440.17  5008.6  440.97  5009.5  441.66  5011.6  443.27
  5033.4  444.87  5038.5  446.52  5041.8  447.57  5047.7  447.54  5056.8  449.37
  5062.8  449.04  5069.3  449.66  5129.1  450.44  5171.3  454.87  5219.8  457.36
#Mann=4,-1,0
  4699.5    0.16       0  5002.6    0.07       0  5008.6    0.16       0
  5009.5    0.05       0
Bank Sta=4967.5,5038.5
Exp/Cntr=0.3,0.1

Type RM Length L Ch R = 1,7679,466,466,466
BEGIN DESCRIPTION:
XS3572A
END DESCRIPTION:
XS GIS Cut Line= 3
      2805272.66      7049986.23      2805494.05      7049827.35
      2805670.59      7049565.14
#Sta/Elev= 30
  4708.1  457.82  4718.0  457.70  4765.1  455.47  4789.2  454.36  4818.6  454.10
  4833.4  452.92  4846.4  451.29  4940.2  447.09  4949.3  445.90  4961.1  443.66
  4975.8  444.04  4978.3  442.17  4985.0  442.17  4987.4  439.51  4987.9  438.71
  4992.9  438.71  4993.4  439.51  4996.4  440.22  5004.8  440.43  5011.4  442.01
  5019.6  443.25  5026.3  445.30  5035.1  445.90  5041.3  446.57  5055.8  446.83
  5104.3  447.08  5170.3  448.81  5242.3  449.56  5278.3  451.10  5296.7  452.38
#Mann=5,-1,0
  4708.1    0.05       0  4765.1    0.16       0  4987.4    0.07       0
  4993.4    0.16       0  5004.8    0.05       0
Bank Sta=4949.3,5035.1
Exp/Cntr=0.3,0.1

Type RM Length L Ch R = 1,7213,269,269,269
BEGIN DESCRIPTION:
XS3575A
END DESCRIPTION:
XS GIS Cut Line= 3
      2805720.62      7050228.43      2805738.85      7049913.29
      2805707.60      7049603.43
#Sta/Elev= 30
  4655.4  451.48  4678.9  451.78  4789.0  449.20  4816.0  447.97  4839.1  445.53
  4869.2  444.64  4909.3  444.18  4971.1  444.50  4975.7  443.75  4979.4  443.15
  4989.4  438.86  4996.5  438.38  4997.0  437.58  5002.0  437.58  5002.5  438.38
  5009.5  441.52  5029.6  442.54  5057.0  442.34  5063.8  443.75  5079.9  445.96
  5090.0  446.74  5110.1  447.00  5142.6  448.32  5150.3  447.59  5162.1  447.64
  5190.5  449.76  5230.7  449.82  5257.2  450.78  5262.2  450.49  5282.5  451.53
#Mann=4,-1,0
  4655.4    0.16       0  4996.5    0.07       0  5002.5    0.16       0
  5142.6    0.05       0
Bank Sta=4975.7,5063.8
Exp/Cntr=0.3,0.1

Type RM Length L Ch R = 1,6944,91,91,91
BEGIN DESCRIPTION:
XS3573A
END DESCRIPTION:
XS GIS Cut Line= 3
      2805822.17      7050262.27      2805908.12      7049994.02
      2805991.46      7049645.02
#Sta/Elev= 30
  4717.2  447.38  4756.3  446.38  4798.3  447.09  4823.5  446.03  4892.8  445.55
  4907.7  444.45  4913.1  442.97  4924.3  441.74  4934.6  442.21  4939.8  441.15
  4955.9  442.96  4966.4  443.19  4984.4  437.58  4984.9  436.78  4989.9  436.78
  4990.4  437.58  5001.0  438.65  5005.0  442.59  5010.1  441.18  5026.6  442.97
  5047.1  444.11  5052.2  443.08  5073.2  443.99  5131.3  445.66  5136.4  445.00
  5178.5  448.08  5235.2  449.60  5273.2  450.67  5316.6  452.16  5357.7  452.49
#Mann=7,-1,0
  4717.2    0.16       0  4823.5    0.05       0  4984.4    0.04       0
  4990.4    0.05       0  5073.2    0.16       0  5235.2    0.05       0
  5273.2    0.08       0
Bank Sta=4913.1,5026.6
Exp/Cntr=0.3,0.1

Type RM Length L Ch R = 1,6853,641,641,641
BEGIN DESCRIPTION:
XS3574A
END DESCRIPTION:
XS GIS Cut Line= 4
      2805908.11      7050382.05      2805988.85      7050040.89
      2806017.49      7049848.18      2806110.63      7049677.44
#Sta/Elev= 30
  4632.9  448.16  4685.5  445.87  4704.1  442.90  4763.5  440.36  4804.6  445.11
  4827.5  444.24  4845.7  443.11  4896.8  445.67  4927.9  445.00  4983.5  441.96
  4987.9  438.16  4992.9  439.08  4996.5  438.04  4997.0  437.24  5002.5  438.04
  5009.7  440.71  5019.8  441.24  5050.1  439.42  5062.3  441.22  5102.0  440.91
  5115.7  442.90  5126.6  444.69  5131.7  443.01  5161.3  446.90  5201.7  448.10
  5207.4  446.99  5223.6  449.51  5267.2  449.87  5305.2  452.98  5372.8  455.40
#Mann=5,-1,0
  4632.9    0.05       0  4827.5    0.16       0  4996.5    0.07       0
  5002.5    0.16       0  5102.0    0.05       0
Bank Sta=4704.1,5115.7
Exp/Cntr=0.3,0.1

Type RM Length L Ch R = 1,6212,387,387,387
BEGIN DESCRIPTION:
XS3576A
END DESCRIPTION:
XS GIS Cut Line= 5
      2805908.10      7050483.63      2805962.80      7050369.02
      2806082.60      7050277.87      2806290.93      7050158.08
      2806420.59      7049955.81
#Sta/Elev= 30
  4731.2  451.27  4758.1  450.93  4763.6  450.24  4780.8  450.86  4786.3  449.42
  4823.9  448.02  4898.7  445.45  4911.8  444.09  4921.3  441.01  4934.6  438.53
  4955.4  439.40  4999.1  436.03  5005.3  438.34  5008.7  438.89  5034.6  440.40
  5101.4  440.79  5115.3  439.22  5123.0  439.87  5125.7  435.77  5126.2  434.97
  5131.2  434.97  5131.7  435.77  5138.4  440.91  5140.3  441.01  5283.4  445.74
  5319.7  448.32  5325.7  447.90  5377.2  449.69  5471.1  453.97  5489.3  455.35
#Mann=4,-1,0
  4731.2    0.05       0  4823.9    0.16       0  5125.7    0.07       0
  5131.7    0.16       0
Bank Sta=4921.3,5140.3
Exp/Cntr=0.3,0.1

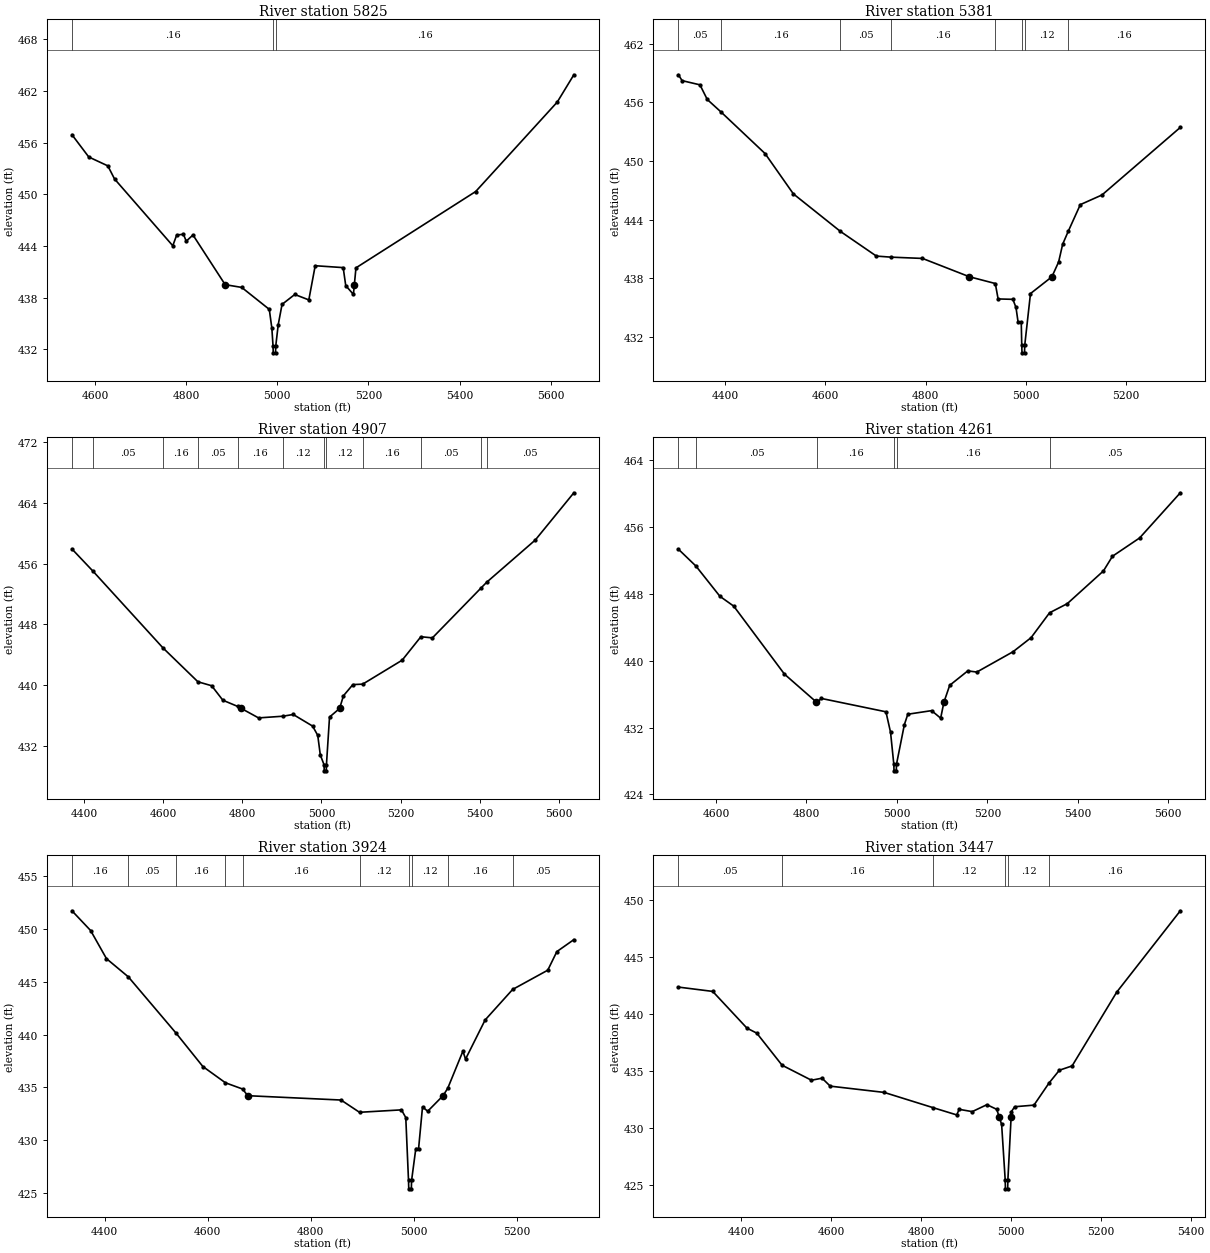
Type RM Length L Ch R = 1,5825,444,444,444
BEGIN DESCRIPTION:
UNT 083 in LFCCL Watershed 7.0
END DESCRIPTION:
XS GIS Cut Line= 3
      2805974.99      7050775.01      2806325.00      7050525.00
      2806625.02      7049924.96
#Sta/Elev= 30
  4549.6  456.94  4586.5  454.35  4628.3  453.32  4643.0  451.80  4770.8  444.04
  4779.4  445.29  4794.2  445.37  4800.3  444.57  4815.1  445.29  4885.7  439.52
  4922.0  439.20  4982.5  436.65  4988.1  434.47  4990.7  432.40  4991.2  431.60
  4996.2  431.60  4996.7  432.40  5002.1  434.87  5010.5  437.23  5038.4  438.38
  5069.2  437.75  5083.2  441.72  5144.6  441.50  5150.2  439.41  5167.0  438.39
  5169.1  439.52  5172.6  441.47  5435.3  450.34  5614.2  460.73  5650.6  463.90
#Mann=3,-1,0
  4549.6    0.16       0  4990.7    0.07       0  4996.7    0.16       0
Bank Sta=4885.7,5169.1
Exp/Cntr=0.3,0.1

Type RM Length L Ch R = 1,5381,474,474,474
BEGIN DESCRIPTION:
UNT 083 in LFCCL Watershed 6.0
END DESCRIPTION:
XS GIS Cut Line= 3
      2806225.02      7051074.97      2806625.00      7050525.00
      2806825.01      7050274.99
#Sta/Elev= 30
  4307.5  458.83  4314.8  458.23  4350.4  457.80  4365.0  456.30  4392.6  455.01
  4480.2  450.76  4536.6  446.63  4630.5  442.78  4702.0  440.26  4731.4  440.15
  4793.9  440.02  4887.5  438.14  4939.0  437.45  4944.6  435.87  4974.0  435.83
  4980.2  435.00  4984.4  433.50  4990.7  433.50  4991.7  431.15  4992.2  430.35
  4997.2  430.35  4997.7  431.15  5009.1  436.42  5051.8  438.14  5065.2  439.66
  5073.2  441.47  5084.2  442.78  5108.4  445.53  5151.6  446.52  5307.7  453.44
#Mann=8,-1,0
  4307.5    0.05       0  4392.6    0.16       0  4630.5    0.05       0
  4731.4    0.16       0  4939.0    0.12       0  4991.7    0.07       0
  4997.7    0.12       0  5084.2    0.16       0
Bank Sta=4887.5,5051.8
Exp/Cntr=0.3,0.1

Type RM Length L Ch R = 1,4907,646,646,646
BEGIN DESCRIPTION:
UNT 083 in LFCCL Watershed 5.0
END DESCRIPTION:
XS GIS Cut Line= 3
      2806624.99      7051325.04      2806775.00      7050725.00
      2807025.00      7050125.00
#Sta/Elev= 30
  4369.4  457.93  4422.8  454.99  4599.4  444.89  4687.8  440.42  4722.5  439.90
  4750.8  437.99  4788.0  437.18  4797.6  436.90  4841.0  435.66  4902.3  435.88
  4928.6  436.11  4977.6  434.58  4990.6  433.36  4997.1  430.77  5006.6  429.48
  5007.1  428.68  5012.1  428.68  5012.6  429.48  5020.4  435.77  5045.8  436.90
  5055.6  438.58  5079.4  440.05  5104.2  440.11  5204.0  443.27  5251.3  446.36
  5280.4  446.21  5402.8  452.76  5417.7  453.55  5540.4  459.11  5637.9  465.34
#Mann=12,-1,0
  4369.4    0.16       0  4422.8    0.05       0  4599.4    0.16       0
  4687.8    0.05       0  4788.0    0.16       0  4902.3    0.12       0
  5006.6    0.07       0  5012.6    0.12       0  5104.2    0.16       0
  5251.3    0.05       0  5402.8    0.16       0  5417.7    0.05       0
Bank Sta=4797.6,5045.8
Exp/Cntr=0.3,0.1

Type RM Length L Ch R = 1,4261,337,337,337
BEGIN DESCRIPTION:
UNT 083 in LFCCL Watershed 4.0
END DESCRIPTION:
XS GIS Cut Line= 3
      2806975.00      7051324.99      2807075.00      7050825.00
      2807075.00      7050224.99
#Sta/Elev= 30
  4516.8  453.37  4555.6  451.35  4608.6  447.73  4639.2  446.55  4751.3  438.41
  4822.0  435.06  4823.7  435.06  4832.9  435.50  4975.7  433.90  4985.9  431.45
  4993.1  427.63  4993.6  426.83  4998.6  426.83  4999.1  427.63  5016.5  432.37
  5024.1  433.61  5076.7  434.04  5096.7  433.14  5104.0  435.06  5116.7  437.07
  5156.7  438.80  5176.7  438.66  5256.7  441.09  5296.7  442.78  5337.6  445.76
  5376.7  446.85  5456.7  450.77  5476.7  452.53  5536.7  454.72  5626.7  460.13
#Mann=6,-1,0
  4516.8    0.16       0  4555.6    0.05       0  4823.7    0.16       0
  4993.1    0.07       0  4999.1    0.16       0  5337.6    0.05       0
Bank Sta=4822,5104
Exp/Cntr=0.3,0.1

Type RM Length L Ch R = 1,3924,477,477,477
BEGIN DESCRIPTION:
UNT 083 in LFCCL Watershed 3.0
END DESCRIPTION:
XS GIS Cut Line= 3
      2807075.00      7051325.00      2807375.00      7050725.00
      2807324.99      7050424.96
#Sta/Elev= 30
  4336.4  451.71  4372.7  449.84  4403.5  447.18  4445.9  445.46  4538.6  440.14
  4590.7  436.98  4634.6  435.44  4667.9  434.85  4677.9  434.22  4859.1  433.81
  4895.0  432.65  4976.5  432.88  4984.9  432.15  4990.2  426.21  4990.7  425.41
  4995.7  425.41  4996.2  426.21  5004.4  429.22  5009.8  429.22  5017.4  433.16
  5027.5  432.75  5057.3  434.22  5066.4  434.92  5095.9  438.43  5101.0  437.68
  5139.0  441.38  5192.5  444.27  5260.7  446.09  5278.4  447.85  5311.4  448.98
#Mann=10,-1,0
  4336.4    0.16       0  4445.9    0.05       0  4538.6    0.16       0
  4634.6    0.05       0  4667.9    0.16       0  4895.0    0.12       0
  4990.2    0.07       0  4996.2    0.12       0  5066.4    0.16       0
  5192.5    0.05       0
Bank Sta=4677.9,5057.3
Exp/Cntr=0.3,0.1

Type RM Length L Ch R = 1,3447,205,205,205
BEGIN DESCRIPTION:
UNT 083 in LFCCL Watershed 2.0
END DESCRIPTION:
XS GIS Cut Line= 3
      2807425.00      7051325.01      2807725.00      7050625.00
      2807475.03      7050375.03
#Sta/Elev= 30
  4261.0  442.37  4337.2  441.99  4413.3  438.76  4435.1  438.32  4491.3  435.50
  4556.6  434.18  4580.1  434.36  4598.3  433.66  4718.0  433.11  4825.8  431.78
  4879.3  431.13  4884.8  431.62  4913.8  431.42  4946.4  432.03  4968.2  431.62
  4973.6  430.97  4979.1  430.29  4987.0  425.43  4987.5  424.63  4992.5  424.63
  4993.0  425.43  5000.2  430.97  5000.8  431.42  5008.1  431.85  5050.9  431.99
  5084.5  433.94  5107.4  435.06  5135.7  435.44  5234.7  441.92  5376.1  449.08
#Mann=6,-1,0
  4261.0    0.05       0  4491.3    0.16       0  4825.8    0.12       0
  4987.0    0.07       0  4993.0    0.12       0  5084.5    0.16       0
Bank Sta=4973.6,5000.2
Exp/Cntr=0.3,0.1

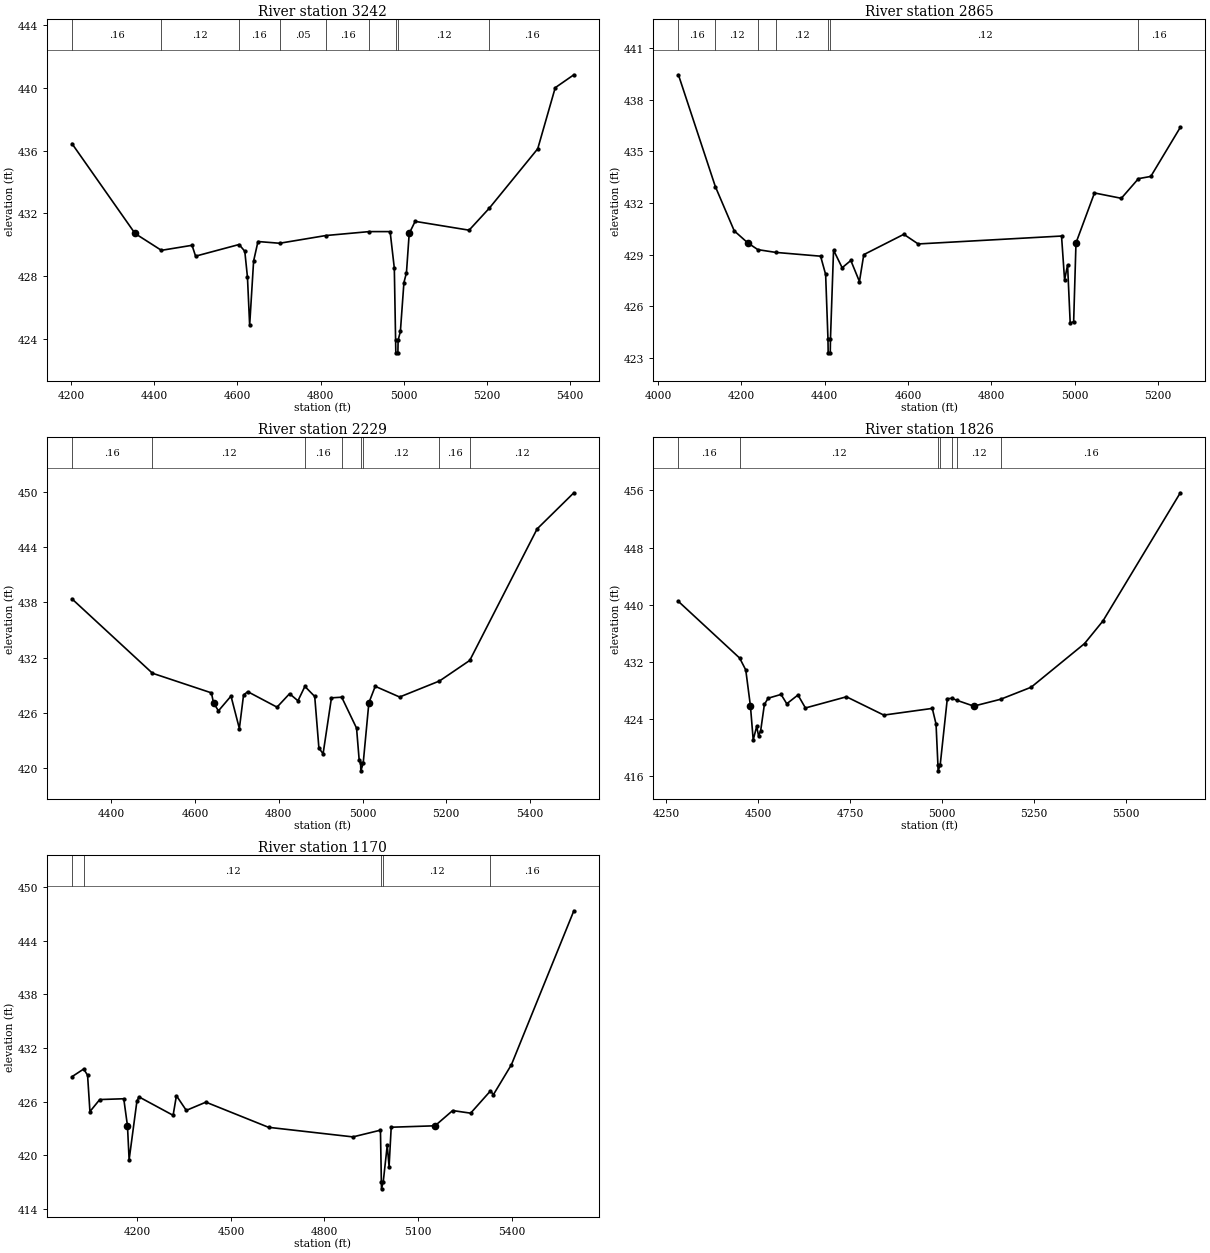
Type RM Length L Ch R = 1,3242,377,377,377
BEGIN DESCRIPTION:
XS3579A
END DESCRIPTION:
XS GIS Cut Line= 3
      2808178.09      7051428.05      2807922.87      7050688.46
      2807672.89      7050344.74
#Sta/Elev= 30
  4202.0  436.44  4353.8  430.73  4417.2  429.66  4490.9  429.98  4499.4  429.29
  4604.1  430.03  4617.8  429.60  4624.2  427.96  4629.5  424.90  4639.0  428.98
  4649.5  430.22  4701.5  430.11  4812.8  430.60  4917.1  430.85  4967.4  430.85
  4977.5  428.53  4980.6  423.95  4981.1  423.15  4986.1  423.15  4986.6  423.95
  4992.1  424.51  5000.6  427.61  5006.7  428.24  5013.3  430.73  5027.6  431.50
  5157.4  430.94  5206.1  432.34  5322.5  436.11  5364.6  439.99  5409.4  440.81
#Mann=9,-1,0
  4202.0    0.16       0  4417.2    0.12       0  4604.1    0.16       0
  4701.5    0.05       0  4812.8    0.16       0  4917.1    0.12       0
  4980.6    0.07       0  4986.6    0.12       0  5206.1    0.16       0
Bank Sta=4353.8,5013.3
Exp/Cntr=0.3,0.1

Type RM Length L Ch R = 1,2865,636,636,636
BEGIN DESCRIPTION:
XS3580A
END DESCRIPTION:
XS GIS Cut Line= 3
      2808292.67      7051334.31      2808058.29      7050480.13
      2807803.12      7050287.45
#Sta/Elev= 30
  4048.6  439.44  4137.3  432.95  4182.7  430.38  4215.3  429.68  4239.4  429.29
  4282.4  429.13  4390.1  428.91  4402.2  427.85  4407.8  424.10  4408.3  423.30
  4413.3  423.30  4413.8  424.10  4421.2  429.26  4441.9  428.24  4462.7  428.66
  4483.4  427.44  4493.8  429.00  4590.0  430.18  4624.5  429.62  4968.8  430.08
  4976.1  427.53  4983.3  428.40  4989.6  425.03  4997.9  425.11  5003.5  429.68
  5047.9  432.58  5112.4  432.27  5153.5  433.41  5183.2  433.54  5254.1  436.39
#Mann=7,-1,0
  4048.6    0.16       0  4137.3    0.12       0  4239.4    0.16       0
  4282.4    0.12       0  4407.8    0.07       0  4413.8    0.12       0
  5153.5    0.16       0
Bank Sta=4215.3,5003.5
Exp/Cntr=0.3,0.1

Type RM Length L Ch R = 1,2229,403,403,403
BEGIN DESCRIPTION:
XS3578A
END DESCRIPTION:
XS GIS Cut Line= 3
      2808349.96      7051224.90      2808370.79      7050537.42
      2808211.06      7050051.28
#Sta/Elev= 30
  4305.5  438.39  4497.9  430.32  4638.8  428.19  4643.8  427.11  4655.6  426.24
  4685.6  427.84  4705.6  424.32  4715.6  427.96  4725.6  428.32  4795.6  426.64
  4825.6  428.10  4845.6  427.33  4862.2  428.89  4885.7  427.80  4895.7  422.20
  4905.7  421.58  4925.7  427.65  4950.2  427.72  4985.7  424.36  4992.0  420.87
  4995.4  420.53  4995.9  419.73  5001.5  420.53  5015.1  427.11  5030.3  428.90
  5088.6  427.74  5183.9  429.48  5256.2  431.71  5417.2  445.98  5505.0  449.90
#Mann=8,-1,0
  4305.5    0.16       0  4497.9    0.12       0  4862.2    0.16       0
  4950.2    0.12       0  4995.4    0.07       0  5001.5    0.12       0
  5183.9    0.16       0  5256.2    0.12       0
Bank Sta=4643.8,5015.1
Exp/Cntr=0.3,0.1

Type RM Length L Ch R = 1,1826,656,656,656
BEGIN DESCRIPTION:
XS3577A
END DESCRIPTION:
XS GIS Cut Line= 3
      2808634.67      7051155.51      2808745.79      7050481.86
      2808606.91      7049815.23
#Sta/Elev= 30
  4284.1  440.44  4450.5  432.49  4467.1  430.82  4479.8  425.75  4487.3  421.01
  4496.8  422.91  4501.8  421.59  4507.6  422.30  4517.7  425.99  4527.9  426.86
  4563.0  427.39  4578.5  426.08  4608.9  427.31  4629.2  425.49  4740.7  427.06
  4842.1  424.49  4973.9  425.43  4984.1  423.23  4989.2  417.47  4989.7  416.67
  4995.3  417.47  5014.7  426.80  5027.8  426.84  5041.0  426.56  5086.5  425.75
  5159.4  426.71  5242.5  428.40  5387.5  434.52  5437.6  437.70  5647.8  455.68
#Mann=7,-1,0
  4284.1    0.16       0  4450.5    0.12       0  4989.2    0.07       0
  4995.3    0.12       0  5027.8    0.16       0  5041.0    0.12       0
  5159.4    0.16       0
Bank Sta=4479.8,5086.5
Exp/Cntr=0.3,0.1

Type RM Length L Ch R = 1,1170,0,0,0
BEGIN DESCRIPTION:
UNT 083 in LFCCL Watershed 1.0
END DESCRIPTION:
XS GIS Cut Line= 3
      2808870.79      7051162.43      2809190.24      7050217.98
      2808864.73      7049698.56
#Sta/Elev= 30
  3989.9  428.79  4027.5  429.65  4040.0  428.96  4047.6  424.90  4079.0  426.24
  4156.1  426.33  4168.0  423.31  4173.3  419.52  4198.3  426.06  4204.8  426.54
  4314.4  424.48  4325.0  426.67  4356.7  425.03  4419.6  425.95  4620.6  423.14
  4891.2  422.07  4979.5  422.82  4982.4  417.07  4982.9  416.27  4988.5  417.07
  5001.3  421.13  5007.2  418.76  5014.0  423.15  5154.6  423.31  5211.1  425.01
  5268.8  424.72  5332.3  427.20  5341.9  426.79  5399.6  430.13  5599.9  447.32
#Mann=5,-1,0
  3989.9    0.16       0  4027.5    0.12       0  4982.4    0.07       0
  4988.5    0.12       0  5332.3    0.16       0
Bank Sta=4168,5154.6
Exp/Cntr=0.3,0.1

Chan Stop Cuts=-1