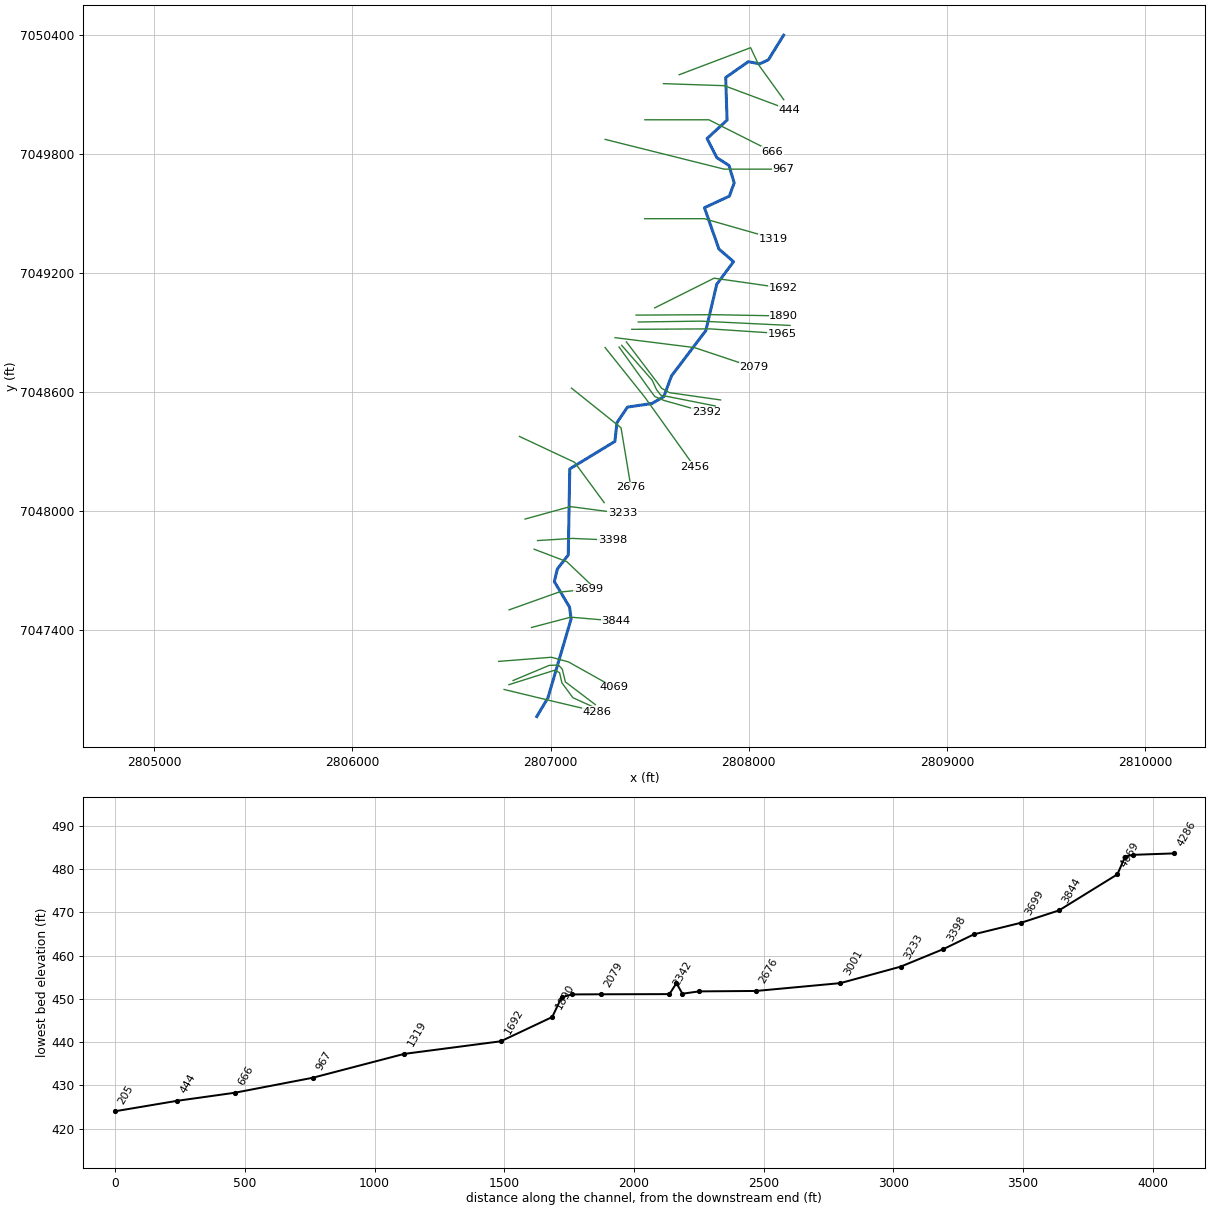
--- UNT 084 in LFCCL Watershed.prj (project) ---

Proj Title=UNT 084 in LFCCL Watershed Base Level Engineering
Current Plan=p01
Default Exp/Contr=0.3,0.1
English Units
Geom File=g01
Flow File=f01
Plan File=p01
BEGIN DESCRIPTION:
UNT 084 in LFCCL Watershed
END DESCRIPTION:

--- UNT 084 in LFCCL Watershed.p01 (plan) ---

Plan Title=Multiple Run
Short Identifier=Multiple
Geom File=g01
Flow File=f01
Subcritical Flow
K Sum by GR= 0
Std Step Tol= 0.01
Critical Tol= 0.01
Num of Std Step Trials= 20
Max Error Tol= 0.3
Flow Tol Ratio= 0.001
Split Flow NTrial= 30
Split Flow Tol= 0.02
Split Flow Ratio= 0.02
Log Output Level= 0
Friction Slope Method= 1
Unsteady Friction Slope Method= 2
Unsteady Bridges Friction Slope Method= 1
Parabolic Critical Depth
Global Vel Dist=  1 , 1 , 1
Global Log Level= 0
CheckData=True
Encroach Param= -1, 0, 0, 0
BEGIN DESCRIPTION:
Multiple Run
END DESCRIPTION:

--- UNT 084 in LFCCL Watershed.f01 (steady flow) ---

Flow Title=Multiple
Program Version=5.07
Number of Profiles= 7
Profile Names=10-year,25-year,50-year,1pct_min,100-year,1pct_plu,500-year
River Rch & RM=UNT 084 in LFCCL,Reach-1         ,4286
     224     284     329     191     381     761     510
Boundary for River Rch & Prof#=UNT 084 in LFCCL,Reach-1         , 1
Up Type= 0
Dn Type= 3
Dn Slope=0.01026
Boundary for River Rch & Prof#=UNT 084 in LFCCL,Reach-1         , 2
Up Type= 0
Dn Type= 3
Dn Slope=0.01026
Boundary for River Rch & Prof#=UNT 084 in LFCCL,Reach-1         , 3
Up Type= 0
Dn Type= 3
Dn Slope=0.01026
Boundary for River Rch & Prof#=UNT 084 in LFCCL,Reach-1         , 4
Up Type= 0
Dn Type= 3
Dn Slope=0.01026
Boundary for River Rch & Prof#=UNT 084 in LFCCL,Reach-1         , 5
Up Type= 0
Dn Type= 3
Dn Slope=0.01026
Boundary for River Rch & Prof#=UNT 084 in LFCCL,Reach-1         , 6
Up Type= 0
Dn Type= 3
Dn Slope=0.01026
Boundary for River Rch & Prof#=UNT 084 in LFCCL,Reach-1         , 7
Up Type= 0
Dn Type= 3
Dn Slope=0.01026
DSS Import GetInterval= 0
DSS Import GetPeak= 0
DSS Import FillOption= 0

--- UNT 084 in LFCCL Watershed.g01 (geometry) ---

Geom Title=Existing Conditions

River Reach=UNT 084 in LFCCL,Reach-1
Reach XY= 30
      2806930.35      7046963.92      2806986.34      7047057.67
      2807103.53      7047456.11      2807095.71      7047516.00
      2807018.89      7047644.91      2807034.52      7047708.71
      2807089.20      7047779.03      2807096.79      7048212.98
      2807324.38      7048351.70      2807334.86      7048446.56
      2807387.82      7048524.69      2807511.08      7048542.91
      2807570.97      7048577.64      2807609.86      7048681.90
      2807783.08      7048910.57      2807838.13      7049144.46
      2807922.95      7049258.27      2807848.95      7049322.05
      2807776.17      7049530.56      2807901.64      7049588.70
      2807926.06      7049655.68      2807899.97      7049743.27
      2807838.67      7049782.87      2807789.34      7049879.08
      2807890.14      7049972.24      2807883.28      7050187.01
      2807997.22      7050266.93      2808054.82      7050255.97
      2808098.06      7050275.94      2808175.59      7050400.71

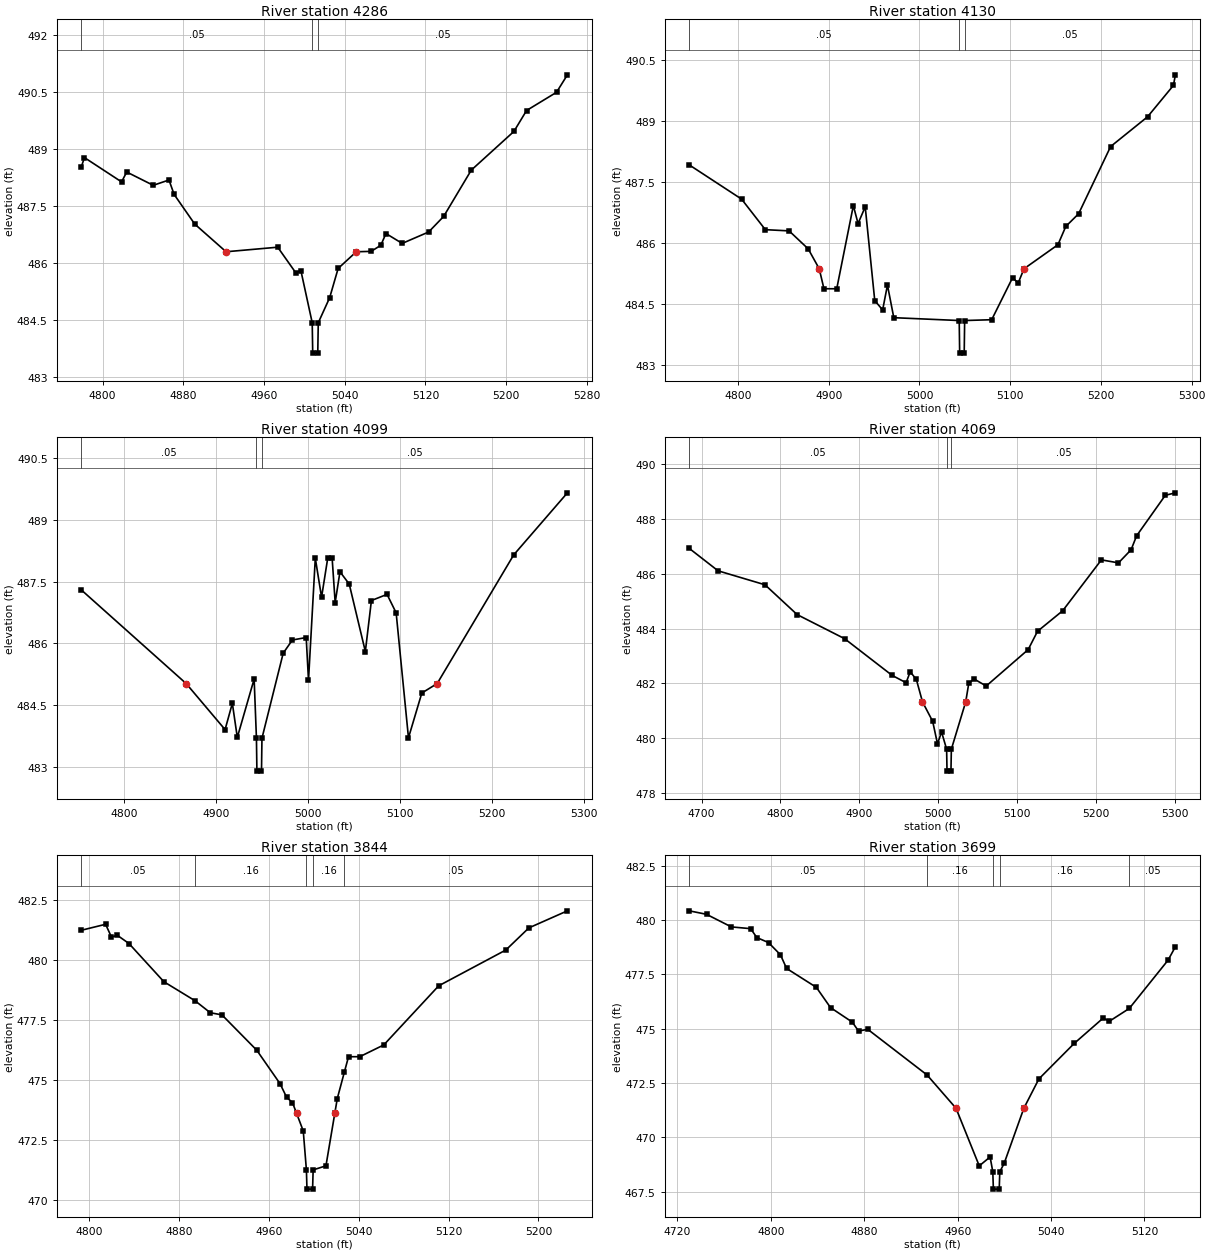
Type RM Length L Ch R = 1,4286,156,156,156
BEGIN DESCRIPTION:
UNT 084 in LFCCL Watershed 11.0
END DESCRIPTION:
XS GIS Cut Line= 3
      2806765.61      7047100.45      2806992.19      7047045.76
      2807234.42      7046988.45
#Sta/Elev= 30
  4778.8  488.53  4782.0  488.78  4818.8  488.14  4823.9  488.40  4850.2  488.05
  4865.8  488.19  4870.9  487.81  4891.3  487.03  4922.4  486.30  4973.6  486.42
  4991.4  485.75  4996.6  485.80  5007.8  484.43  5008.3  483.63  5013.3  483.63
  5013.8  484.43  5025.1  485.09  5033.5  485.86  5051.5  486.30  5066.2  486.31
  5075.8  486.47  5080.9  486.78  5097.0  486.52  5123.2  486.82  5138.1  487.23
  5165.5  488.45  5207.8  489.47  5220.3  490.02  5250.0  490.50  5260.8  490.96
#Mann=3,-1,0
  4778.8    0.05       0  5007.8    0.03       0  5013.8    0.05       0
Bank Sta=4922.4,5051.5
Exp/Cntr=0.3,0.1

Type RM Length L Ch R = 1,4130,31,31,31
BEGIN DESCRIPTION:
XS3582A
END DESCRIPTION:
XS GIS Cut Line= 6
      2806789.96      7047124.76      2807020.84      7047197.66
      2807045.15      7047185.51      2807057.30      7047133.43
      2807112.85      7047058.78      2807222.22      7047009.22
#Sta/Elev= 30
  4746.2  487.92  4803.9  487.08  4830.1  486.33  4856.3  486.30  4877.3  485.86
  4889.5  485.37  4894.7  484.88  4908.8  484.88  4927.1  486.92  4932.3  486.48
  4940.2  486.89  4950.7  484.59  4959.4  484.36  4964.7  484.97  4971.7  484.17
  5043.8  484.10  5044.3  483.30  5049.3  483.30  5049.8  484.10  5079.6  484.12
  5102.6  485.15  5108.8  485.02  5115.2  485.37  5152.6  485.96  5161.3  486.41
  5175.4  486.72  5210.7  488.37  5251.4  489.10  5279.9  489.87  5282.1  490.13
#Mann=3,-1,0
  4746.2    0.05       0  5043.8    0.03       0  5049.8    0.05       0
Bank Sta=4889.5,5115.2
Exp/Cntr=0.3,0.1

Type RM Length L Ch R = 1,4099,30,30,30
BEGIN DESCRIPTION:
XS3581A
END DESCRIPTION:
XS GIS Cut Line= 6
      2806810.75      7047145.57      2806993.06      7047221.97
      2807039.94      7047223.71      2807059.03      7047202.87
      2807074.66      7047138.64      2807225.70      7047024.05
#Sta/Elev= 30
  4753.0  487.30  4867.1  485.02  4909.4  483.90  4917.3  484.54  4922.7  483.71
  4941.0  485.13  4943.5  483.69  4944.0  482.89  4949.0  482.89  4949.5  483.69
  4972.6  485.76  4982.6  486.08  4997.6  486.14  5000.1  485.10  5007.5  488.07
  5014.3  487.12  5021.0  488.07  5025.8  488.07  5029.1  486.99  5034.3  487.74
  5044.4  487.44  5061.9  485.80  5068.5  487.04  5085.5  487.19  5095.4  486.74
  5108.8  483.70  5123.3  484.79  5140.0  485.02  5223.2  488.15  5281.6  489.66
#Mann=3,-1,0
  4753.0    0.05       0  4943.5    0.03       0  4949.5    0.05       0
Bank Sta=4867.1,5140
Exp/Cntr=0.3,0.1

Type RM Length L Ch R = 1,4069,225,225,225
BEGIN DESCRIPTION:
XS3583A
END DESCRIPTION:
XS GIS Cut Line= 4
      2806738.51      7047242.15      2807004.13      7047262.99
      2807090.07      7047239.55      2807317.96      7047111.93
#Sta/Elev= 30
  4684.3  486.93  4720.9  486.11  4780.4  485.60  4821.2  484.51  4881.4  483.63
  4941.6  482.29  4959.4  482.02  4964.6  482.42  4972.4  482.14  4980.2  481.32
  4993.1  480.61  4999.2  479.79  5004.4  480.22  5010.8  479.59  5011.3  478.79
  5016.3  478.79  5016.8  479.59  5035.0  481.32  5038.9  482.00  5045.5  482.16
  5061.0  481.90  5114.2  483.23  5126.1  483.90  5158.0  484.65  5207.1  486.51
  5228.8  486.40  5244.8  486.88  5251.8  487.39  5288.2  488.87  5301.0  488.96
#Mann=3,-1,0
  4684.3    0.05       0  5010.8    0.03       0  5016.8    0.05       0
Bank Sta=4980.2,5035
Exp/Cntr=0.3,0.1

Type RM Length L Ch R = 1,3844,145,145,145
BEGIN DESCRIPTION:
XS3584A
END DESCRIPTION:
XS GIS Cut Line= 3
      2806903.87      7047413.16      2807101.35      7047465.24
      2807329.19      7047445.71
#Sta/Elev= 30
  4792.9  481.23  4814.6  481.48  4819.8  480.95  4825.1  481.02  4835.4  480.68
  4866.5  479.09  4894.2  478.30  4907.8  477.80  4918.2  477.71  4949.2  476.24
  4969.9  474.85  4975.8  474.28  4981.0  474.06  4984.6  473.62  4990.6  472.88
  4993.4  471.26  4993.9  470.46  4998.9  470.46  4999.4  471.26  5010.8  471.43
  5018.7  473.62  5020.9  474.23  5027.2  475.33  5030.9  475.97  5040.9  475.97
  5062.3  476.46  5111.2  478.92  5171.0  480.41  5191.5  481.33  5225.8  482.04
#Mann=5,-1,0
  4792.9    0.05       0  4894.2    0.16       0  4993.4    0.07       0
  4999.4    0.16       0  5027.2    0.05       0
Bank Sta=4984.6,5018.7
Exp/Cntr=0.3,0.1

Type RM Length L Ch R = 1,3699,183,183,183
BEGIN DESCRIPTION:
XS3585A
END DESCRIPTION:
XS GIS Cut Line= 3
      2806791.01      7047502.13      2807040.59      7047591.11
      2807191.28      7047606.18
#Sta/Elev= 30
  4730.1  480.42  4744.9  480.26  4766.2  479.68  4782.7  479.60  4788.0  479.19
  4798.0  478.96  4808.2  478.40  4813.5  477.77  4839.0  476.90  4851.1  475.97
  4869.8  475.30  4875.1  474.89  4883.0  474.97  4933.8  472.87  4958.6  471.34
  4978.5  468.69  4987.8  469.10  4990.1  468.42  4990.6  467.62  4995.6  467.62
  4996.1  468.42  4999.8  468.80  5016.7  471.34  5029.6  472.69  5059.8  474.32
  5084.7  475.49  5089.9  475.34  5107.0  475.93  5140.2  478.15  5146.5  478.77
#Mann=5,-1,0
  4730.1    0.05       0  4933.8    0.16       0  4990.1    0.07       0
  4996.1    0.16       0  5107.0    0.05       0
Bank Sta=4958.6,5016.7
Exp/Cntr=0.3,0.1

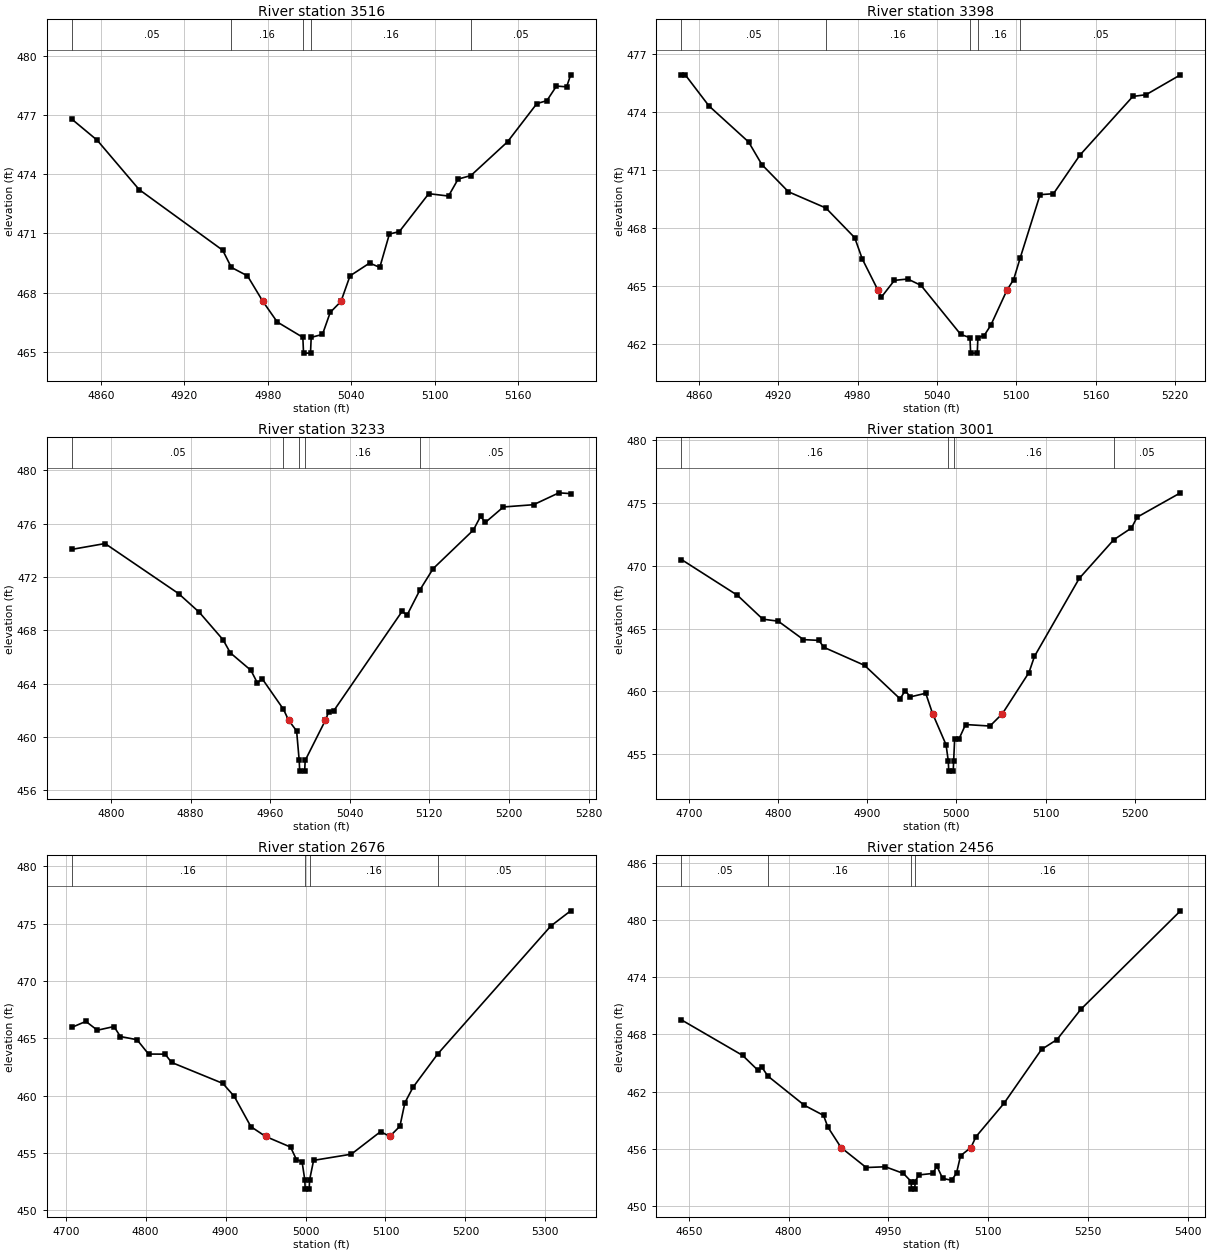
Type RM Length L Ch R = 1,3516,118,118,118
BEGIN DESCRIPTION:
XS3586A
END DESCRIPTION:
XS GIS Cut Line= 3
      2806916.91      7047808.12      2807081.82      7047745.19
      2807213.85      7047619.65
#Sta/Elev= 30
  4839.1  476.81  4857.5  475.73  4887.6  473.23  4947.7  470.15  4953.9  469.28
  4965.5  468.85  4976.6  467.55  4986.9  466.51  5005.3  465.73  5005.8  464.93
  5010.8  464.93  5011.3  465.73  5019.4  465.88  5025.0  467.00  5032.7  467.55
  5039.2  468.85  5053.3  469.50  5060.6  469.28  5067.5  470.97  5074.7  471.10
  5095.8  473.02  5110.0  472.90  5116.9  473.76  5126.1  473.94  5152.4  475.65
  5173.5  477.59  5180.7  477.74  5187.6  478.48  5194.9  478.44  5197.8  479.05
#Mann=5,-1,0
  4839.1    0.05       0  4953.9    0.16       0  5005.3    0.07       0
  5011.3    0.16       0  5126.1    0.05       0
Bank Sta=4976.6,5032.7
Exp/Cntr=0.3,0.1

Type RM Length L Ch R = 1,3398,165,165,165
BEGIN DESCRIPTION:
XS3587A
END DESCRIPTION:
XS GIS Cut Line= 3
      2806934.27      7047851.53      2807110.03      7047862.38
      2807310.95      7047853.74
#Sta/Elev= 30
  4846.9  475.93  4849.8  475.93  4867.7  474.32  4897.7  472.45  4907.7  471.28
  4927.8  469.87  4956.1  469.03  4977.9  467.49  4983.6  466.39  4995.4  464.78
  4997.9  464.40  5007.9  465.28  5018.0  465.35  5028.0  465.02  5058.0  462.48
  5065.0  462.31  5065.5  461.51  5070.5  461.51  5071.0  462.31  5075.7  462.42
  5080.7  462.95  5093.0  464.78  5098.0  465.32  5103.0  466.45  5118.0  469.72
  5128.1  469.77  5148.1  471.77  5188.1  474.81  5198.1  474.90  5224.1  475.93
#Mann=5,-1,0
  4846.9    0.05       0  4956.1    0.16       0  5065.0    0.07       0
  5071.0    0.16       0  5103.0    0.05       0
Bank Sta=4995.4,5093
Exp/Cntr=0.3,0.1

Type RM Length L Ch R = 1,3233,232,232,232
BEGIN DESCRIPTION:
XS3588A
END DESCRIPTION:
XS GIS Cut Line= 3
      2806871.28      7047960.03      2807099.18      7048022.97
      2807362.00      7047988.50
#Sta/Elev= 30
  4760.5  474.06  4794.1  474.50  4868.0  470.75  4888.8  469.35  4912.7  467.29
  4920.0  466.31  4940.7  465.00  4947.1  464.07  4952.2  464.35  4973.4  462.08
  4978.5  461.27  4986.6  460.46  4989.2  458.25  4989.7  457.45  4994.7  457.45
  4995.2  458.25  5015.6  461.27  5018.8  461.89  5023.9  461.97  5092.6  469.42
  5097.6  469.14  5110.7  471.05  5123.8  472.62  5164.2  475.51  5171.4  476.53
  5176.4  476.09  5194.4  477.24  5224.7  477.41  5250.2  478.30  5262.0  478.24
#Mann=5,-1,0
  4760.5    0.05       0  4973.4    0.16       0  4989.2    0.07       0
  4995.2    0.16       0  5110.7    0.05       0
Bank Sta=4978.5,5015.6
Exp/Cntr=0.3,0.1

Type RM Length L Ch R = 1,3001,325,325,325
BEGIN DESCRIPTION:
XS3589A
END DESCRIPTION:
XS GIS Cut Line= 3
      2806843.15      7048376.68      2807120.88      7048246.49
      2807270.33      7048042.89
#Sta/Elev= 30
  4691.8  470.50  4754.6  467.65  4783.0  465.75  4800.3  465.59  4828.6  464.12
  4845.9  464.06  4851.4  463.51  4897.1  462.07  4936.8  459.41  4942.7  460.06
  4948.3  459.56  4965.6  459.85  4973.3  458.23  4988.4  455.75  4990.9  454.45
  4991.4  453.65  4996.4  453.65  4996.9  454.45  4998.0  456.17  5002.6  456.17
  5010.3  457.36  5037.6  457.24  5051.6  458.23  5081.3  461.50  5087.5  462.79
  5137.6  468.99  5176.3  472.07  5196.2  473.01  5202.5  473.87  5251.1  475.81
#Mann=4,-1,0
  4691.8    0.16       0  4990.9    0.07       0  4996.9    0.16       0
  5176.3    0.05       0
Bank Sta=4973.3,5051.6
Exp/Cntr=0.3,0.1

Type RM Length L Ch R = 1,2676,220,220,220
BEGIN DESCRIPTION:
UNT 084 in LFCCL Watershed 7.0
END DESCRIPTION:
XS GIS Cut Line= 3
      2807105.32      7048620.47      2807355.30      7048420.49
      2807405.30      7048120.45
#Sta/Elev= 30
  4707.4  465.95  4725.2  466.48  4739.6  465.71  4760.4  466.03  4768.4  465.16
  4789.2  464.88  4803.6  463.63  4824.4  463.62  4832.4  462.90  4896.5  461.07
  4910.9  459.93  4931.7  457.29  4950.0  456.44  4981.3  455.51  4988.7  454.41
  4995.7  454.23  4999.1  452.64  4999.6  451.84  5004.6  451.84  5005.1  452.64
  5010.1  454.35  5057.3  454.89  5093.9  456.86  5105.4  456.44  5118.1  457.33
  5124.3  459.38  5134.5  460.73  5165.4  463.64  5306.8  474.80  5331.7  476.13
#Mann=4,-1,0
  4707.4    0.16       0  4999.1    0.07       0  5005.1    0.16       0
  5165.4    0.05       0
Bank Sta=4950,5105.4
Exp/Cntr=0.3,0.1

Type RM Length L Ch R = 1,2456,64,64,64
BEGIN DESCRIPTION:
UNT 084 in LFCCL Watershed 6.0
END DESCRIPTION:
XS GIS Cut Line= 3
      2807274.99      7048825.01      2807475.00      7048575.00
      2807725.01      7048224.99
#Sta/Elev= 30
  4638.8  469.53  4730.9  465.79  4753.3  464.27  4759.7  464.56  4768.8  463.62
  4823.7  460.55  4852.5  459.49  4858.9  458.27  4878.8  456.11  4916.6  454.01
  4945.4  454.09  4972.5  453.39  4984.2  452.54  4984.7  451.74  4989.7  451.74
  4990.2  452.54  4995.8  453.23  5016.7  453.39  5022.9  454.16  5031.5  452.87
  5045.0  452.67  5052.4  453.42  5058.5  455.25  5074.0  456.11  5081.9  457.27
  5123.6  460.74  5180.2  466.42  5203.5  467.46  5239.2  470.63  5389.1  480.99
#Mann=4,-1,0
  4638.8    0.05       0  4768.8    0.16       0  4984.2    0.07       0
  4990.2    0.16       0
Bank Sta=4878.8,5074
Exp/Cntr=0.3,0.1

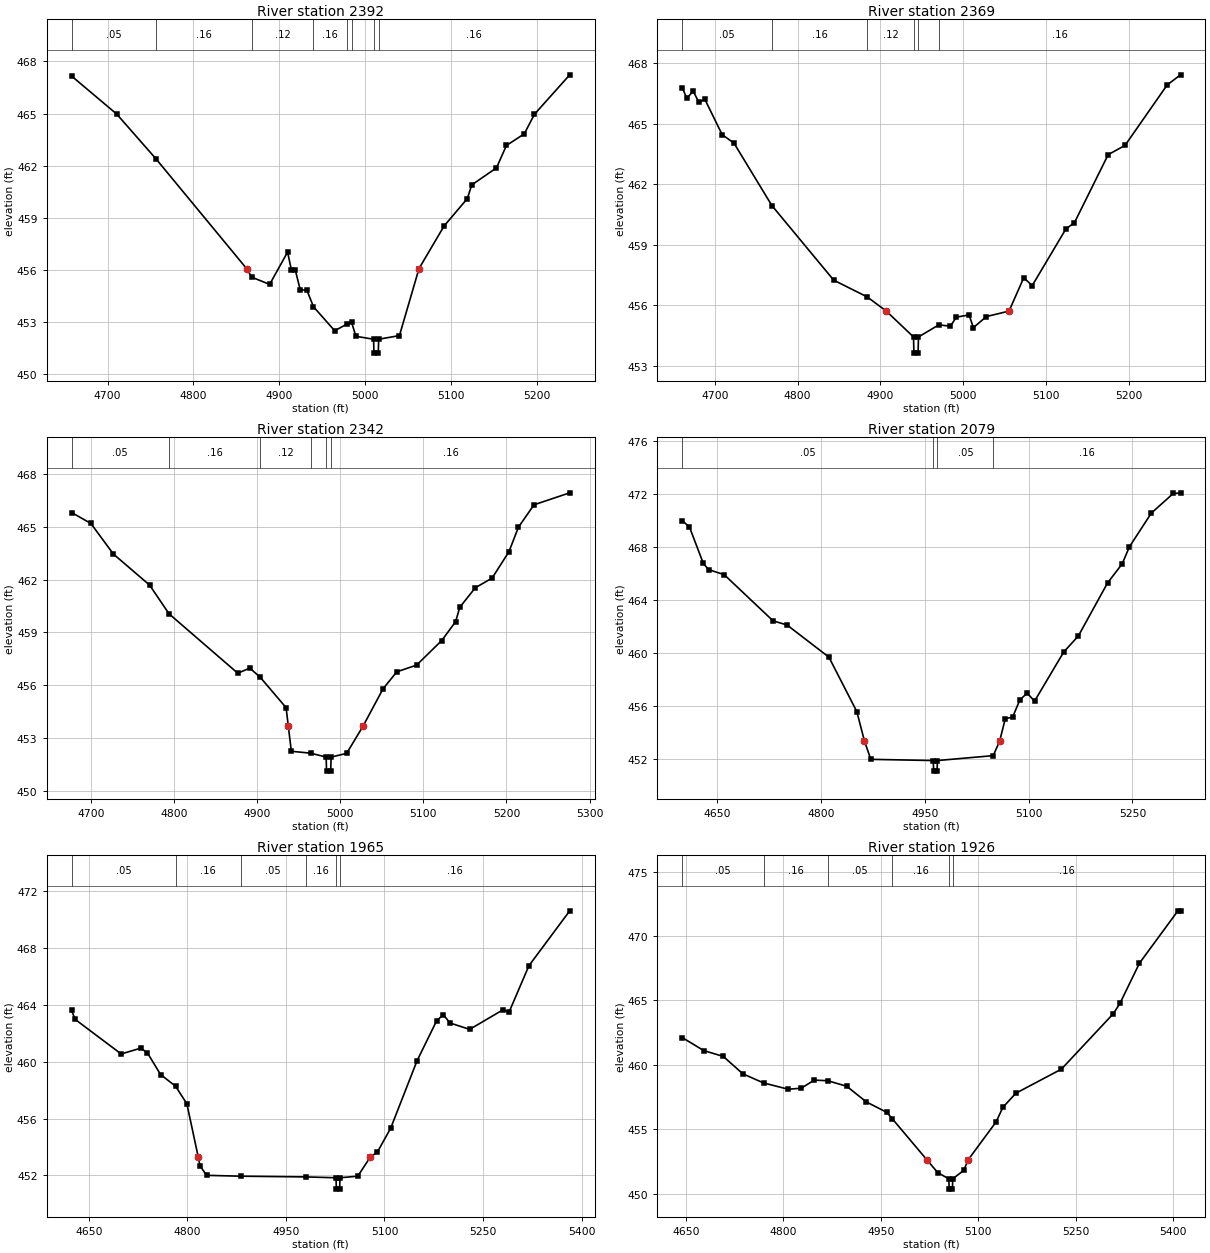
Type RM Length L Ch R = 1,2392,23,23,23
BEGIN DESCRIPTION:
Mapping XS 89f410b4
END DESCRIPTION:
XS GIS Cut Line= 5
      2807345.40      7048827.72      2807495.16      7048619.37
      2807525.54      7048578.14      2807571.11      7048558.60
      2807785.99      7048497.83
#Sta/Elev= 30
  4658.0  467.16  4710.6  464.97  4756.4  462.39  4862.0  456.07  4868.2  455.57
  4888.9  455.16  4909.8  457.02  4914.2  456.00  4918.7  456.00  4924.5  454.86
  4932.4  454.81  4940.0  453.87  4964.7  452.49  4979.3  452.88  4984.4  452.98
  4989.4  452.17  5010.0  452.00  5010.5  451.20  5015.5  451.20  5016.0  452.00
  5040.2  452.21  5063.0  456.07  5092.2  458.52  5119.3  460.10  5124.5  460.89
  5153.3  461.87  5164.9  463.16  5185.7  463.83  5197.6  464.96  5238.7  467.23
#Mann=8,-1,0
  4658.0    0.05       0  4756.4    0.16       0  4868.2    0.12       0
  4940.0    0.16       0  4979.3    0.12       0  4984.4    0.16       0
  5010.0    0.07       0  5016.0    0.16       0
Bank Sta=4862,5063
Exp/Cntr=0.3,0.1

Type RM Length L Ch R = 1,2369,27,27,27
BEGIN DESCRIPTION:
Mapping XS ae96c3b1
END DESCRIPTION:
XS GIS Cut Line= 6
      2807358.43      7048836.39      2807512.52      7048660.60
      2807534.22      7048612.86      2807555.92      7048584.65
      2807601.50      7048575.97      2807830.75      7048530.55
#Sta/Elev= 30
  4660.8  466.77  4666.2  466.24  4673.8  466.61  4680.5  466.07  4688.1  466.19
  4708.9  464.45  4723.2  464.03  4769.0  460.94  4843.7  457.25  4884.2  456.42
  4907.2  455.72  4940.1  454.44  4940.6  453.64  4945.6  453.64  4946.1  454.44
  4970.7  455.04  4984.7  454.97  4991.8  455.42  5007.3  455.53  5012.4  454.90
  5028.2  455.45  5055.5  455.72  5073.3  457.37  5083.5  456.98  5124.3  459.79
  5134.5  460.09  5175.3  463.46  5195.7  463.92  5246.6  466.91  5262.7  467.41
#Mann=6,-1,0
  4660.8    0.05       0  4769.0    0.16       0  4884.2    0.12       0
  4940.1    0.07       0  4946.1    0.12       0  4970.7    0.16       0
Bank Sta=4907.2,5055.5
Exp/Cntr=0.3,0.1

Type RM Length L Ch R = 1,2342,263,263,263
BEGIN DESCRIPTION:
Mapping XS 16b499bc
END DESCRIPTION:
XS GIS Cut Line= 4
      2807382.32      7048853.73      2807560.26      7048619.37
      2807599.33      7048597.67      2807857.56      7048560.78
#Sta/Elev= 30
  4676.4  465.82  4699.6  465.20  4726.7  463.46  4770.4  461.69  4793.7  460.06
  4876.5  456.68  4891.0  456.97  4903.7  456.44  4934.7  454.72  4937.4  453.65
  4941.0  452.24  4964.4  452.13  4982.9  451.91  4983.4  451.11  4988.4  451.11
  4988.9  451.91  5007.6  452.12  5027.1  453.65  5051.4  455.79  5068.0  456.76
  5091.8  457.14  5122.1  458.54  5138.8  459.61  5143.8  460.43  5162.5  461.54
  5182.7  462.09  5202.9  463.58  5214.5  464.99  5233.2  466.26  5276.2  466.94
#Mann=6,-1,0
  4676.4    0.05       0  4793.7    0.16       0  4903.7    0.12       0
  4964.4    0.16       0  4982.9    0.07       0  4988.9    0.16       0
Bank Sta=4937.4,5027.1
Exp/Cntr=0.3,0.1

Type RM Length L Ch R = 1,2079,114,114,114
BEGIN DESCRIPTION:
UNT 084 in LFCCL Watershed 5.0
END DESCRIPTION:
XS GIS Cut Line= 3
      2807325.02      7048875.00      2807725.00      7048825.00
      2808024.98      7048725.01
#Sta/Elev= 30
  4600.1  469.97  4610.2  469.53  4630.3  466.77  4637.9  466.29  4660.5  465.91
  4731.1  462.42  4751.2  462.11  4811.7  459.68  4852.0  455.57  4863.0  453.35
  4872.2  451.96  4962.4  451.87  4962.9  451.07  4967.9  451.07  4968.4  451.87
  5049.0  452.24  5058.3  453.35  5066.4  455.03  5077.0  455.15  5087.5  456.46
  5098.1  456.96  5108.6  456.35  5150.8  460.07  5171.8  461.27  5214.0  465.28
  5235.1  466.72  5245.6  468.01  5277.3  470.56  5308.9  472.04  5319.4  472.09
#Mann=4,-1,0
  4600.1    0.05       0  4962.4   0.033       0  4968.4    0.05       0
  5049.0    0.16       0
Bank Sta=4863,5058.3
Exp/Cntr=0.3,0.1

Type RM Length L Ch R = 1,1965,39,39,39
BEGIN DESCRIPTION:
XS3591A
END DESCRIPTION:
XS GIS Cut Line= 3
      2807409.52      7048917.07      2807804.48      7048919.24
      2808166.93      7048895.36
#Sta/Elev= 30
  4623.8  463.61  4629.3  462.98  4699.3  460.55  4729.3  460.96  4739.3  460.62
  4759.3  459.10  4782.1  458.28  4799.3  457.04  4816.7  453.27  4819.3  452.68
  4829.3  452.01  4881.1  451.95  4980.2  451.90  5026.3  451.84  5026.8  451.04
  5031.8  451.04  5032.3  451.84  5059.4  451.95  5078.1  453.27  5089.4  453.66
  5109.5  455.33  5149.6  460.07  5179.6  462.90  5189.7  463.31  5199.7  462.73
  5229.7  462.28  5279.8  463.64  5289.9  463.52  5319.9  466.76  5382.0  470.62
#Mann=6,-1,0
  4623.8    0.05       0  4782.1    0.16       0  4881.1    0.05       0
  4980.2    0.16       0  5026.3    0.07       0  5032.3    0.16       0
Bank Sta=4816.7,5078.1
Exp/Cntr=0.3,0.1

Type RM Length L Ch R = 1,1926,36,36,36
BEGIN DESCRIPTION:
XS3590A
END DESCRIPTION:
XS GIS Cut Line= 3
      2807442.05      7048953.96      2807756.73      7048958.30
      2808208.09      7048936.60
#Sta/Elev= 30
  4644.8  462.11  4677.8  461.10  4707.8  460.65  4737.8  459.30  4769.7  458.59
  4807.8  458.10  4827.8  458.18  4847.8  458.81  4868.7  458.76  4897.8  458.33
  4927.8  457.12  4959.5  456.30  4967.8  455.81  5021.2  452.61  5037.9  451.62
  5054.9  451.14  5055.4  450.34  5060.4  450.34  5060.9  451.14  5077.9  451.80
  5084.5  452.61  5127.6  455.56  5138.0  456.69  5158.0  457.79  5228.1  459.66
  5308.2  463.98  5318.2  464.77  5348.2  467.89  5407.4  471.96  5411.4  471.96
#Mann=6,-1,0
  4644.8    0.05       0  4769.7    0.16       0  4868.7    0.05       0
  4967.8    0.16       0  5054.9    0.07       0  5060.9    0.16       0
Bank Sta=5021.2,5084.5
Exp/Cntr=0.3,0.1

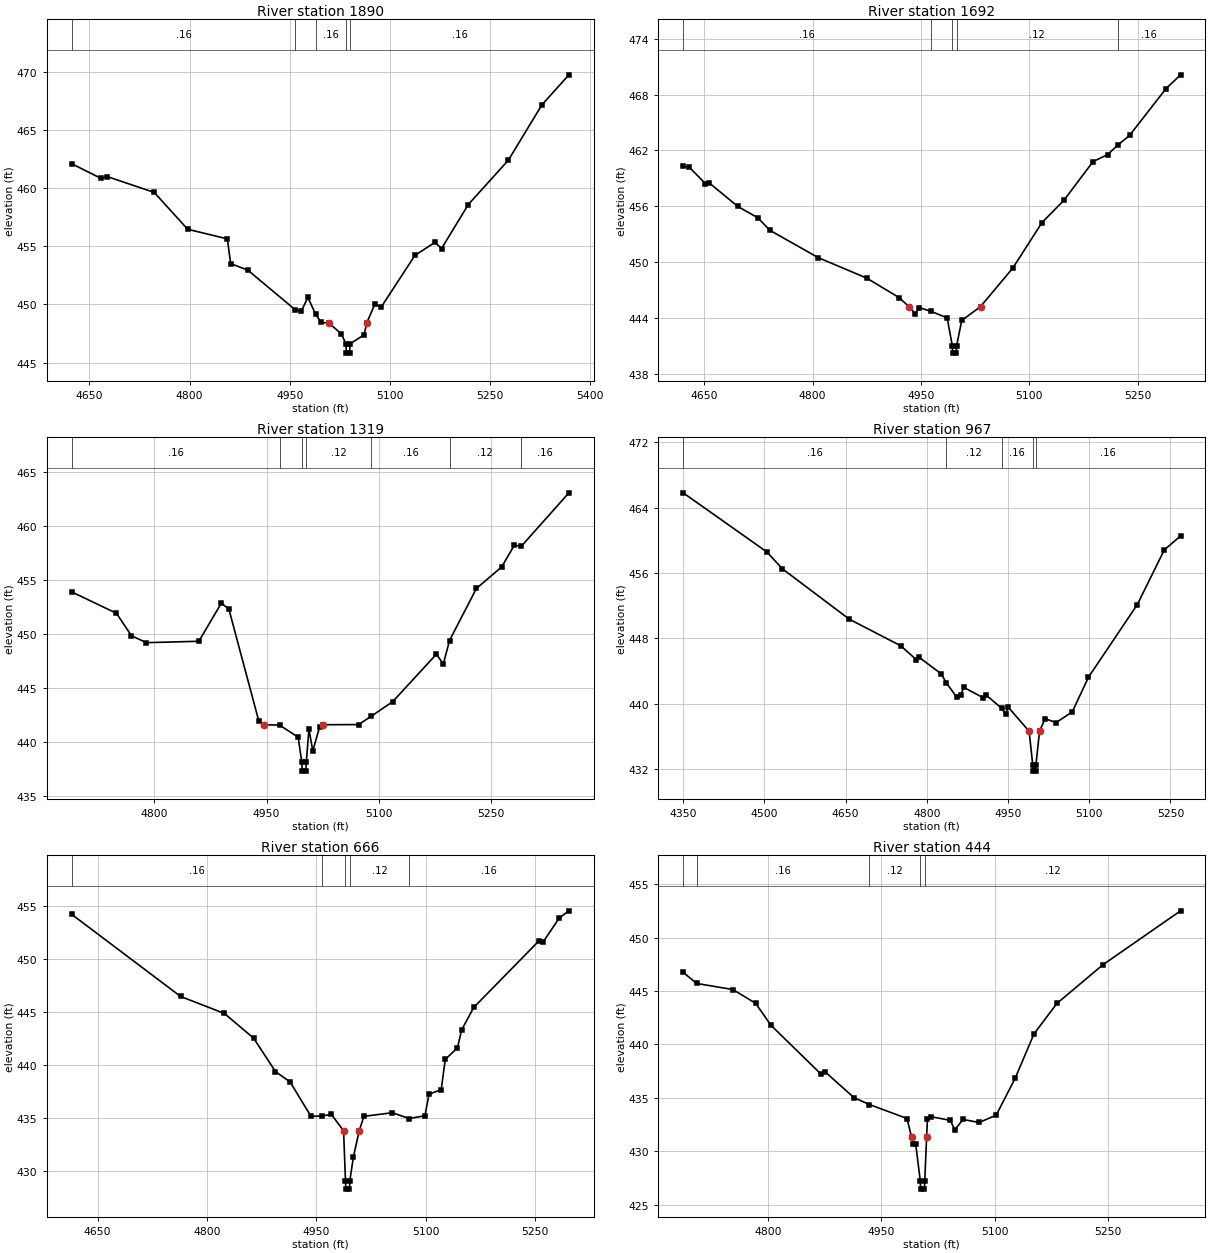
Type RM Length L Ch R = 1,1890,198,198,198
BEGIN DESCRIPTION:
XS3592A
END DESCRIPTION:
XS GIS Cut Line= 3
      2807431.16      7048988.68      2807821.84      7048990.85
      2808175.60      7048984.34
#Sta/Elev= 30
  4623.4  462.13  4667.2  460.87  4677.2  461.01  4747.2  459.65  4797.2  456.48
  4856.6  455.65  4861.6  453.52  4887.2  452.96  4958.3  449.54  4967.2  449.41
  4977.2  450.61  4988.6  449.17  4997.2  448.45  5008.5  448.41  5027.2  447.47
  5034.2  446.61  5034.7  445.81  5039.7  445.81  5040.2  446.61  5061.3  447.38
  5065.3  448.41  5077.3  450.01  5087.3  449.81  5137.3  454.22  5167.3  455.35
  5177.3  454.82  5217.3  458.61  5277.3  462.43  5327.3  467.18  5367.9  469.78
#Mann=5,-1,0
  4623.4    0.16       0  4958.3    0.12       0  4988.6    0.16       0
  5034.2    0.07       0  5040.2    0.16       0
Bank Sta=5008.5,5065.3
Exp/Cntr=0.3,0.1

Type RM Length L Ch R = 1,1692,373,373,373
BEGIN DESCRIPTION:
UNT 084 in LFCCL Watershed 4.0
END DESCRIPTION:
XS GIS Cut Line= 3
      2807524.97      7049024.99      2807825.00      7049175.00
      2808175.01      7049125.00
#Sta/Elev= 30
  4620.6  460.30  4629.0  460.20  4651.4  458.44  4657.0  458.49  4696.1  455.99
  4724.0  454.76  4740.8  453.41  4807.9  450.47  4875.0  448.27  4919.7  446.18
  4933.4  445.21  4942.1  444.45  4947.7  445.10  4963.8  444.71  4986.3  444.00
  4993.4  441.01  4993.9  440.21  4998.9  440.21  4999.4  441.01  5006.5  443.72
  5032.5  445.21  5077.3  449.36  5117.7  454.25  5148.0  456.64  5188.4  460.80
  5208.6  461.56  5222.4  462.56  5238.9  463.61  5289.4  468.64  5309.6  470.13
#Mann=5,-1,0
  4620.6    0.16       0  4963.8    0.12       0  4993.4    0.07       0
  4999.4    0.12       0  5222.4    0.16       0
Bank Sta=4933.4,5032.5
Exp/Cntr=0.3,0.1

Type RM Length L Ch R = 1,1319,352,352,352
BEGIN DESCRIPTION:
UNT 084 in LFCCL Watershed 3.0
END DESCRIPTION:
XS GIS Cut Line= 3
      2807474.99      7049475.00      2807775.00      7049475.00
      2808124.98      7049375.01
#Sta/Elev= 30
  4689.7  453.90  4749.7  451.91  4769.7  449.83  4789.7  449.19  4859.7  449.32
  4889.7  452.85  4899.7  452.31  4939.7  441.93  4946.9  441.59  4967.5  441.55
  4992.3  440.43  4997.1  438.09  4997.6  437.29  5002.6  437.29  5003.1  438.09
  5006.6  441.18  5011.8  439.16  5020.9  441.39  5025.9  441.59  5072.9  441.60
  5090.1  442.39  5118.4  443.72  5176.9  448.13  5186.0  447.20  5194.3  449.39
  5230.2  454.21  5264.0  456.21  5280.9  458.23  5289.9  458.10  5353.7  463.07
#Mann=7,-1,0
  4689.7    0.16       0  4967.5    0.12       0  4997.1    0.07       0
  5003.1    0.12       0  5090.1    0.16       0  5194.3    0.12       0
  5289.9    0.16       0
Bank Sta=4946.9,5025.9
Exp/Cntr=0.3,0.1

Type RM Length L Ch R = 1,967,301,301,301
BEGIN DESCRIPTION:
UNT 084 in LFCCL Watershed 2.0
END DESCRIPTION:
XS GIS Cut Line= 3
      2807275.00      7049875.00      2807875.00      7049725.00
      2808175.04      7049725.00
#Sta/Elev= 30
  4350.1  465.81  4504.7  458.58  4533.1  456.53  4656.8  450.36  4752.1  447.10
  4780.4  445.42  4785.6  445.71  4826.8  443.67  4835.8  442.60  4855.2  440.83
  4862.9  441.09  4868.1  442.03  4904.1  440.75  4909.3  441.10  4938.5  439.45
  4945.4  438.78  4950.5  439.60  4989.0  436.65  4995.6  432.58  4996.1  431.78
  5001.1  431.78  5001.6  432.58  5008.2  436.65  5018.6  438.20  5038.6  437.71
  5068.6  439.02  5098.6  443.27  5188.6  452.13  5238.6  458.83  5268.6  460.54
#Mann=5,-1,0
  4350.1    0.16       0  4835.8    0.12       0  4938.5    0.16       0
  4995.6    0.07       0  5001.6    0.16       0
Bank Sta=4989,5008.2
Exp/Cntr=0.3,0.1

Type RM Length L Ch R = 1,666,222,222,222
BEGIN DESCRIPTION:
XS3594A
END DESCRIPTION:
XS GIS Cut Line= 3
      2807475.49      7049973.92      2807798.40      7049973.92
      2808118.70      7049812.47
#Sta/Elev= 30
  4614.4  454.18  4763.9  446.44  4823.9  444.84  4863.9  442.52  4893.9  439.37
  4913.9  438.40  4942.6  435.15  4957.5  435.20  4970.5  435.34  4987.2  433.80
  4989.8  429.11  4990.3  428.31  4995.3  428.31  4995.8  429.11  5000.7  431.35
  5008.6  433.79  5015.1  435.16  5054.1  435.50  5077.0  434.95  5098.7  435.22
  5104.3  437.24  5121.0  437.68  5126.6  440.52  5143.3  441.61  5148.9  443.28
  5165.6  445.41  5254.9  451.67  5260.5  451.55  5282.8  453.83  5296.0  454.50
#Mann=5,-1,0
  4614.4    0.16       0  4957.5    0.12       0  4989.8    0.07       0
  4995.8    0.12       0  5077.0    0.16       0
Bank Sta=4987.2,5008.6
Exp/Cntr=0.3,0.1

Type RM Length L Ch R = 1,444,239,239,239
BEGIN DESCRIPTION:
XS3593A
END DESCRIPTION:
XS GIS Cut Line= 3
      2807569.20      7050156.22      2807876.53      7050145.80
      2808204.64      7050023.41
#Sta/Elev= 30
  4688.0  446.74  4706.0  445.70  4753.8  445.13  4783.9  443.84  4803.9  441.80
  4870.2  437.22  4875.2  437.46  4913.9  435.01  4934.3  434.37  4984.0  433.06
  4990.1  431.29  4992.2  430.68  4995.5  430.68  5001.5  427.25  5002.0  426.45
  5007.0  426.45  5007.5  427.25  5009.9  431.29  5011.0  433.03  5016.3  433.22
  5041.3  432.89  5047.2  431.99  5057.9  432.97  5079.3  432.69  5101.9  433.37
  5126.9  436.81  5151.9  440.98  5182.2  443.83  5242.8  447.44  5345.7  452.50
#Mann=5,-1,0
  4688.0    0.05       0  4706.0    0.16       0  4934.3    0.12       0
  5001.5    0.07       0  5007.5    0.12       0
Bank Sta=4990.1,5009.9
Exp/Cntr=0.3,0.1

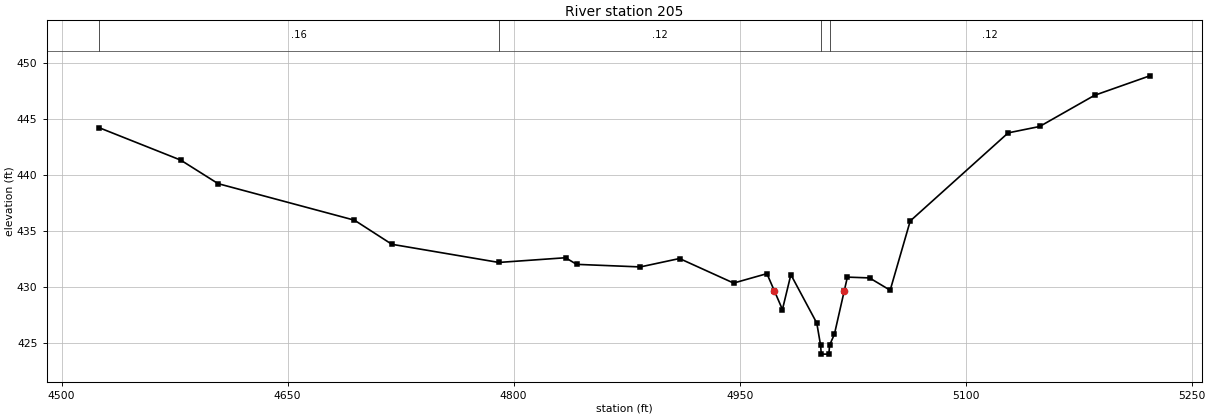
Type RM Length L Ch R = 1,205,0,0,0
BEGIN DESCRIPTION:
UNT 084 in LFCCL Watershed 1.0
END DESCRIPTION:
XS GIS Cut Line= 4
      2807648.72      7050201.10      2808008.84      7050337.47
      2808050.00      7050250.00      2808176.03      7050075.25
#Sta/Elev= 30
  4525.0  444.24  4579.1  441.35  4603.9  439.25  4694.4  435.99  4719.2  433.84
  4790.2  432.22  4834.5  432.64  4841.8  432.05  4884.1  431.82  4910.1  432.57
  4946.0  430.38  4968.1  431.22  4973.1  429.67  4978.4  428.02  4984.0  431.13
  5001.2  426.81  5003.7  424.84  5004.2  424.04  5009.2  424.04  5009.7  424.84
  5012.9  425.82  5019.4  429.67  5021.5  430.91  5036.2  430.84  5049.9  429.74
  5063.2  435.92  5128.2  443.78  5149.1  444.35  5185.5  447.13  5222.2  448.87
#Mann=4,-1,0
  4525.0    0.16       0  4790.2    0.12       0  5003.7    0.07       0
  5009.7    0.12       0
Bank Sta=4973.1,5019.4
Exp/Cntr=0.3,0.1

Chan Stop Cuts=-1