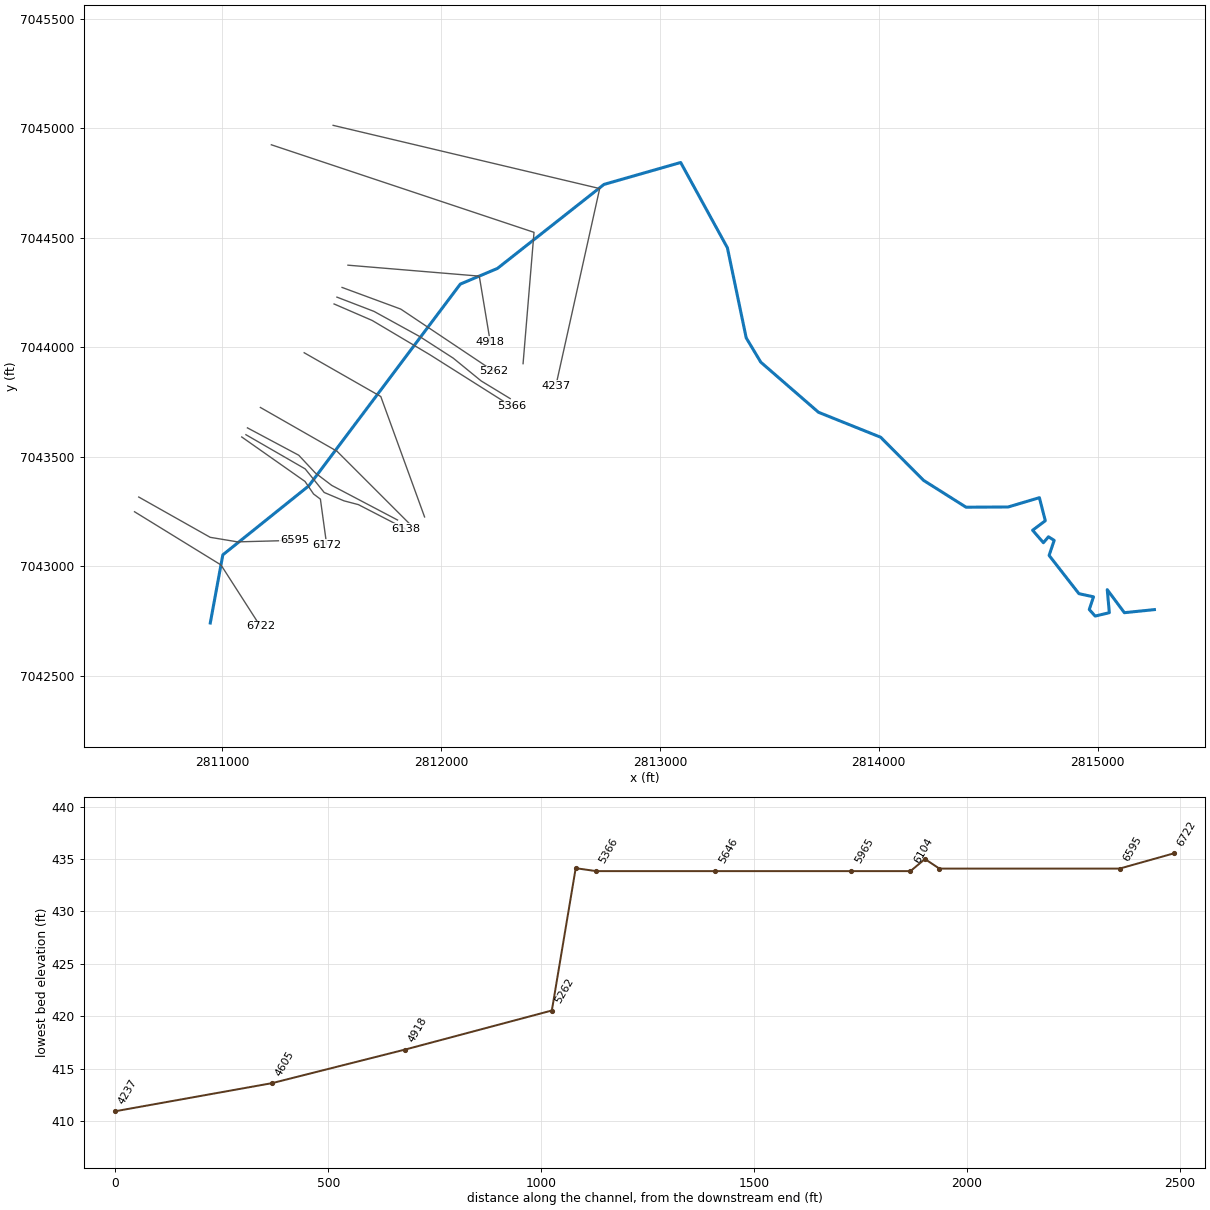
--- UNT 085 in LFCCL Watershed.prj (project) ---

Proj Title=UNT 085 in LFCCL Watershed Base Level Engineering
Current Plan=p01
Default Exp/Contr=0.3,0.1
English Units
Geom File=g01
Flow File=f01
Plan File=p01
BEGIN DESCRIPTION:
UNT 085 in LFCCL Watershed
END DESCRIPTION:

--- UNT 085 in LFCCL Watershed.p01 (plan) ---

Plan Title=Multiple Run
Short Identifier=Multiple
Geom File=g01
Flow File=f01
Subcritical Flow
K Sum by GR= 0
Std Step Tol= 0.01
Critical Tol= 0.01
Num of Std Step Trials= 20
Max Error Tol= 0.3
Flow Tol Ratio= 0.001
Split Flow NTrial= 30
Split Flow Tol= 0.02
Split Flow Ratio= 0.02
Log Output Level= 0
Friction Slope Method= 1
Unsteady Friction Slope Method= 2
Unsteady Bridges Friction Slope Method= 1
Parabolic Critical Depth
Global Vel Dist=  1 , 1 , 1
Global Log Level= 0
CheckData=True
Encroach Param= -1, 0, 0, 0
BEGIN DESCRIPTION:
Multiple Run
END DESCRIPTION:

--- UNT 085 in LFCCL Watershed.f01 (steady flow) ---

Flow Title=Multiple
Number of Profiles=7
Profile Names=10-year,25-year,50-year,1pct_min,100-year,1pct_plu,500-year
River Rch & RM= UNT 085 in LFCCL,Reach-1,6722
     209     263     304     176     351     700     466
Boundary for River Rch & Prof#=UNT 085 in LFCCL,Reach-1,1
Up Type=0
Dn Type=3
Dn Slope=0.005
Boundary for River Rch & Prof#=UNT 085 in LFCCL,Reach-1,2
Up Type=0
Dn Type=3
Dn Slope=0.005
Boundary for River Rch & Prof#=UNT 085 in LFCCL,Reach-1,3
Up Type=0
Dn Type=3
Dn Slope=0.005
Boundary for River Rch & Prof#=UNT 085 in LFCCL,Reach-1,4
Up Type=0
Dn Type=3
Dn Slope=0.005
Boundary for River Rch & Prof#=UNT 085 in LFCCL,Reach-1,5
Up Type=0
Dn Type=3
Dn Slope=0.005
Boundary for River Rch & Prof#=UNT 085 in LFCCL,Reach-1,6
Up Type=0
Dn Type=3
Dn Slope=0.005
Boundary for River Rch & Prof#=UNT 085 in LFCCL,Reach-1,7
Up Type=0
Dn Type=3
Dn Slope=0.005

--- UNT 085 in LFCCL Watershed.g01 (geometry) ---

Geom Title=Existing Conditions

River Reach=UNT 085 in LFCCL,Reach-1
Reach XY= 30
      2810946.01      7042740.54      2811003.30      7043051.74
      2811396.07      7043366.91      2812088.12      7044288.47
      2812257.92      7044360.15      2812744.64      7044743.89
      2813095.11      7044844.05      2813308.55      7044454.28
      2813394.50      7044042.91      2813461.13      7043931.86
      2813724.76      7043702.99      2814008.66      7043589.05
      2814204.69      7043392.05      2814398.79      7043269.41
      2814590.96      7043270.38      2814733.88      7043312.87
      2814760.92      7043207.61      2814702.98      7043164.15
      2814752.22      7043107.18      2814775.40      7043134.22
      2814801.47      7043117.80      2814778.30      7043049.24
      2814914.46      7042874.45      2814981.09      7042859.97
      2814961.77      7042802.03      2814988.81      7042772.09
      2815053.51      7042787.54      2815043.86      7042892.80
      2815122.07      7042787.54      2815259.44      7042801.57

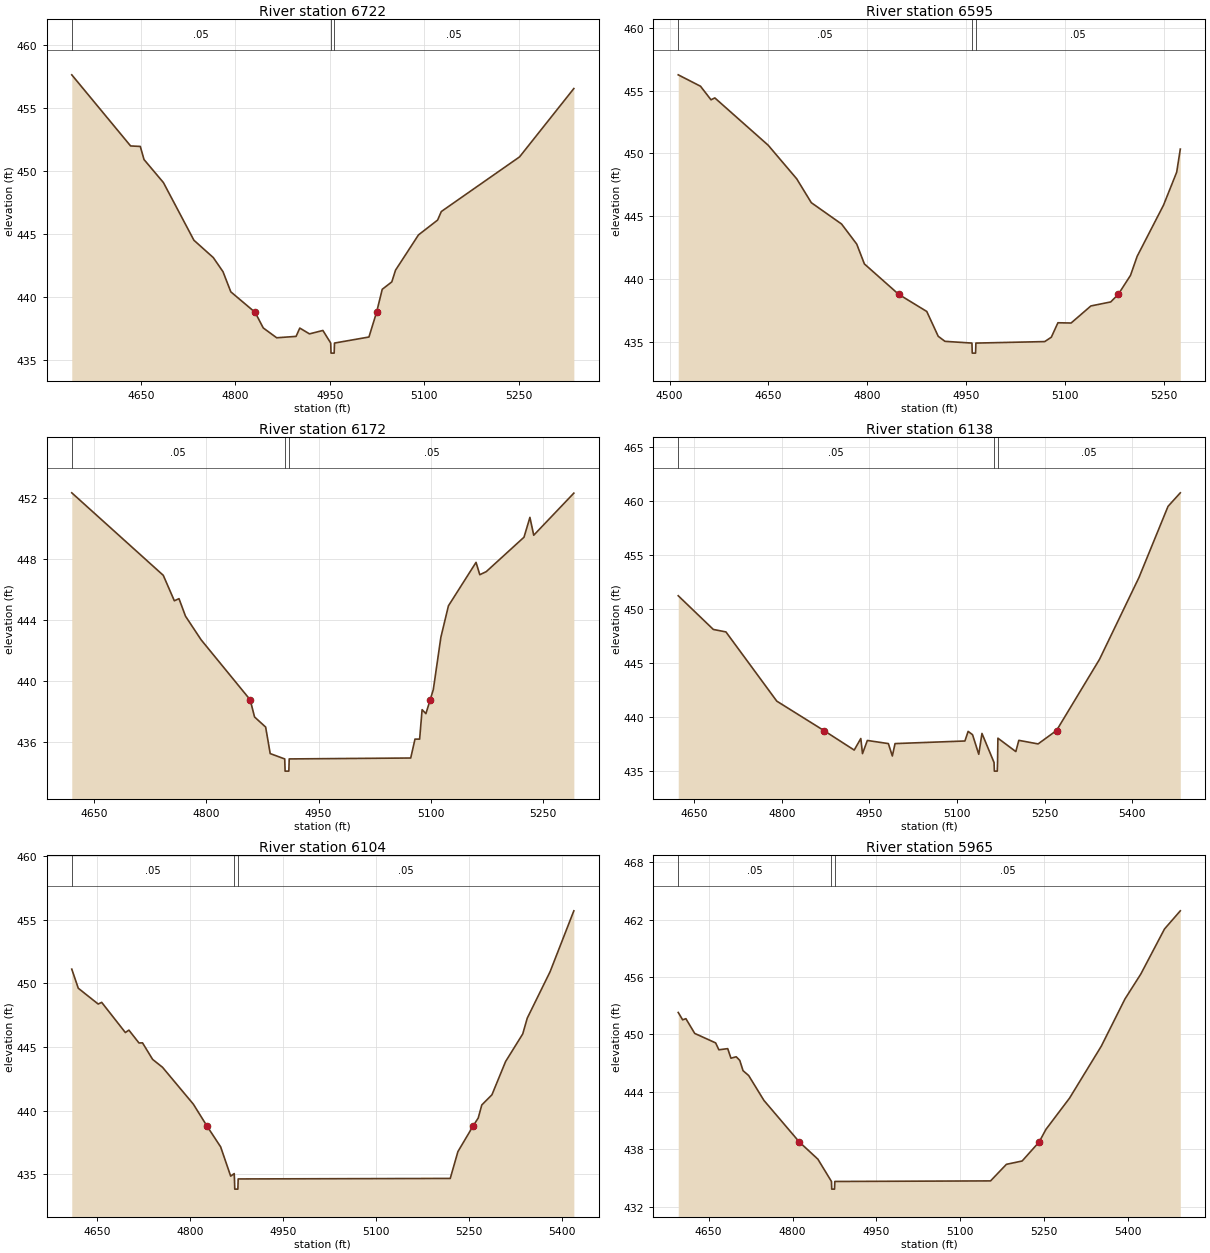
Type RM Length L Ch R = 1,6722,127,127,127
BEGIN DESCRIPTION:
UNT 085 in LFCCL Watershed 8.0
END DESCRIPTION:
XS GIS Cut Line= 3
      2810599.95      7043248.62      2810994.96      7043005.54
      2811174.97      7042725.04
#Sta/Elev= 30
  4540.3  457.64  4633.7  451.99  4649.1  451.95  4655.0  450.91  4685.8  449.08
  4734.2  444.50  4765.0  443.12  4780.4  442.00  4792.8  440.40  4831.4  438.77
  4844.3  437.53  4865.6  436.75  4896.4  436.86  4902.3  437.52  4917.7  437.06
  4939.0  437.33  4951.4  436.33  4951.9  435.53  4956.9  435.53  4957.4  436.33
  5012.1  436.81  5024.2  438.77  5033.2  440.60  5048.4  441.19  5054.3  442.12
  5090.7  444.92  5121.1  446.10  5127.0  446.78  5251.2  451.12  5337.4  456.55
#Mann=3,-1,0
  4540.3    0.05       0  4951.4    0.03       0  4957.4    0.05       0
Bank Sta=4831.4,5024.2
Exp/Cntr=0.3,0.1

Type RM Length L Ch R = 1,6595,423,423,423
BEGIN DESCRIPTION:
XS3595A
END DESCRIPTION:
XS GIS Cut Line= 4
      2810619.23      7043315.87      2810945.62      7043131.84
      2811070.62      7043111.01      2811330.51      7043117.94
#Sta/Elev= 30
  4513.2  456.26  4547.0  455.35  4562.9  454.27  4568.7  454.42  4649.6  450.65
  4692.9  447.97  4715.0  446.07  4760.9  444.37  4783.9  442.77  4795.5  441.19
  4847.4  438.77  4890.1  437.40  4907.5  435.42  4917.7  435.02  4958.6  434.88
  4959.1  434.08  4964.1  434.08  4964.6  434.88  5069.0  435.00  5079.0  435.35
  5089.0  436.50  5109.0  436.48  5139.0  437.84  5169.1  438.16  5180.6  438.77
  5199.1  440.28  5209.1  441.79  5249.1  445.87  5269.1  448.50  5274.6  450.34
#Mann=3,-1,0
  4513.2    0.05       0  4958.6    0.03       0  4964.6    0.05       0
Bank Sta=4847.4,5180.6
Exp/Cntr=0.3,0.1

Type RM Length L Ch R = 1,6172,34,34,34
BEGIN DESCRIPTION:
XS3597A
END DESCRIPTION:
XS GIS Cut Line= 5
      2811089.70      7043590.19      2811378.78      7043387.05
      2811417.84      7043329.76      2811449.09      7043306.32
      2811477.60      7043099.00
#Sta/Elev= 30
  4620.2  452.33  4742.5  446.92  4757.3  445.25  4763.5  445.39  4772.2  444.24
  4793.1  442.69  4858.6  438.76  4864.5  437.63  4879.3  436.97  4885.4  435.23
  4904.8  434.88  4905.3  434.08  4910.3  434.08  4910.8  434.88  5073.2  434.94
  5078.9  436.18  5085.1  436.18  5088.4  438.11  5093.5  437.85  5099.2  438.76
  5103.4  439.43  5113.5  442.86  5123.6  444.92  5160.5  447.77  5165.5  446.96
  5174.1  447.16  5224.6  449.42  5232.5  450.72  5237.6  449.55  5291.2  452.31
#Mann=3,-1,0
  4620.2    0.05       0  4904.8    0.03       0  4910.8    0.05       0
Bank Sta=4858.6,5099.2
Exp/Cntr=0.3,0.1

Type RM Length L Ch R = 1,6138,34,34,34
BEGIN DESCRIPTION:
XS3596A
END DESCRIPTION:
XS GIS Cut Line= 6
      2811108.83      7043600.58      2811379.65      7043444.34
      2811466.45      7043336.70      2811556.73      7043298.51
      2811622.70      7043281.15      2811837.97      7043170.04
#Sta/Elev= 30
  4622.7  451.23  4682.8  448.11  4704.4  447.88  4791.5  441.47  4872.1  438.75
  4924.1  436.94  4935.4  438.01  4938.3  436.61  4946.6  437.83  4982.6  437.54
  4989.4  436.39  4994.0  437.54  5113.7  437.78  5119.2  438.67  5126.8  438.36
  5137.4  436.55  5142.9  438.48  5163.6  435.79  5164.1  434.99  5169.1  434.99
  5169.6  435.79  5170.2  438.04  5200.9  436.80  5206.0  437.84  5239.0  437.51
  5270.6  438.75  5344.2  445.34  5411.7  452.91  5461.6  459.51  5482.6  460.76
#Mann=3,-1,0
  4622.7    0.05       0  5163.6   0.033       0  5169.6    0.05       0
Bank Sta=4872.1,5270.6
Exp/Cntr=0.3,0.1

Type RM Length L Ch R = 1,6104,139,139,139
BEGIN DESCRIPTION:
XS3598A
END DESCRIPTION:
XS GIS Cut Line= 5
      2811115.74      7043631.85      2811350.14      7043506.84
      2811425.66      7043426.11      2811501.18      7043368.82
      2811801.58      7043210.85
#Sta/Elev= 30
  4608.9  451.12  4619.4  449.62  4651.5  448.38  4657.2  448.51  4695.4  446.14
  4701.1  446.33  4717.4  445.32  4723.1  445.33  4739.4  444.03  4755.4  443.41
  4805.2  440.51  4827.6  438.76  4849.2  437.16  4865.4  434.86  4871.1  435.06
  4871.5  434.64  4872.0  433.84  4877.0  433.84  4877.5  434.64  5219.8  434.68
  5232.2  436.79  5256.2  438.76  5265.0  439.43  5270.7  440.45  5287.1  441.25
  5309.1  443.86  5336.8  446.03  5344.1  447.27  5380.9  450.91  5419.3  455.70
#Mann=3,-1,0
  4608.9    0.05       0  4871.5   0.033       0  4877.5    0.05       0
Bank Sta=4827.6,5256.2
Exp/Cntr=0.3,0.1

Type RM Length L Ch R = 1,5965,319,319,319
BEGIN DESCRIPTION:
UNT 085 in LFCCL Watershed 6.0
END DESCRIPTION:
XS GIS Cut Line= 3
      2811175.00      7043725.00      2811525.00      7043525.00
      2811875.01      7043174.99
#Sta/Elev= 30
  4595.6  452.30  4603.5  451.53  4609.3  451.65  4625.1  450.11  4662.5  449.12
  4668.3  448.40  4684.1  448.52  4689.9  447.52  4699.3  447.67  4705.7  447.29
  4711.5  446.22  4721.6  445.71  4748.9  443.11  4812.3  438.76  4845.4  436.97
  4869.7  434.64  4870.2  433.84  4875.2  433.84  4875.7  434.64  5154.3  434.70
  5182.6  436.43  5210.8  436.78  5241.1  438.76  5253.3  440.08  5295.7  443.36
  5352.3  448.77  5394.7  453.71  5423.0  456.31  5465.4  461.02  5493.7  462.92
#Mann=3,-1,0
  4595.6    0.05       0  4869.7   0.033       0  4875.7    0.05       0
Bank Sta=4812.3,5241.1
Exp/Cntr=0.3,0.1

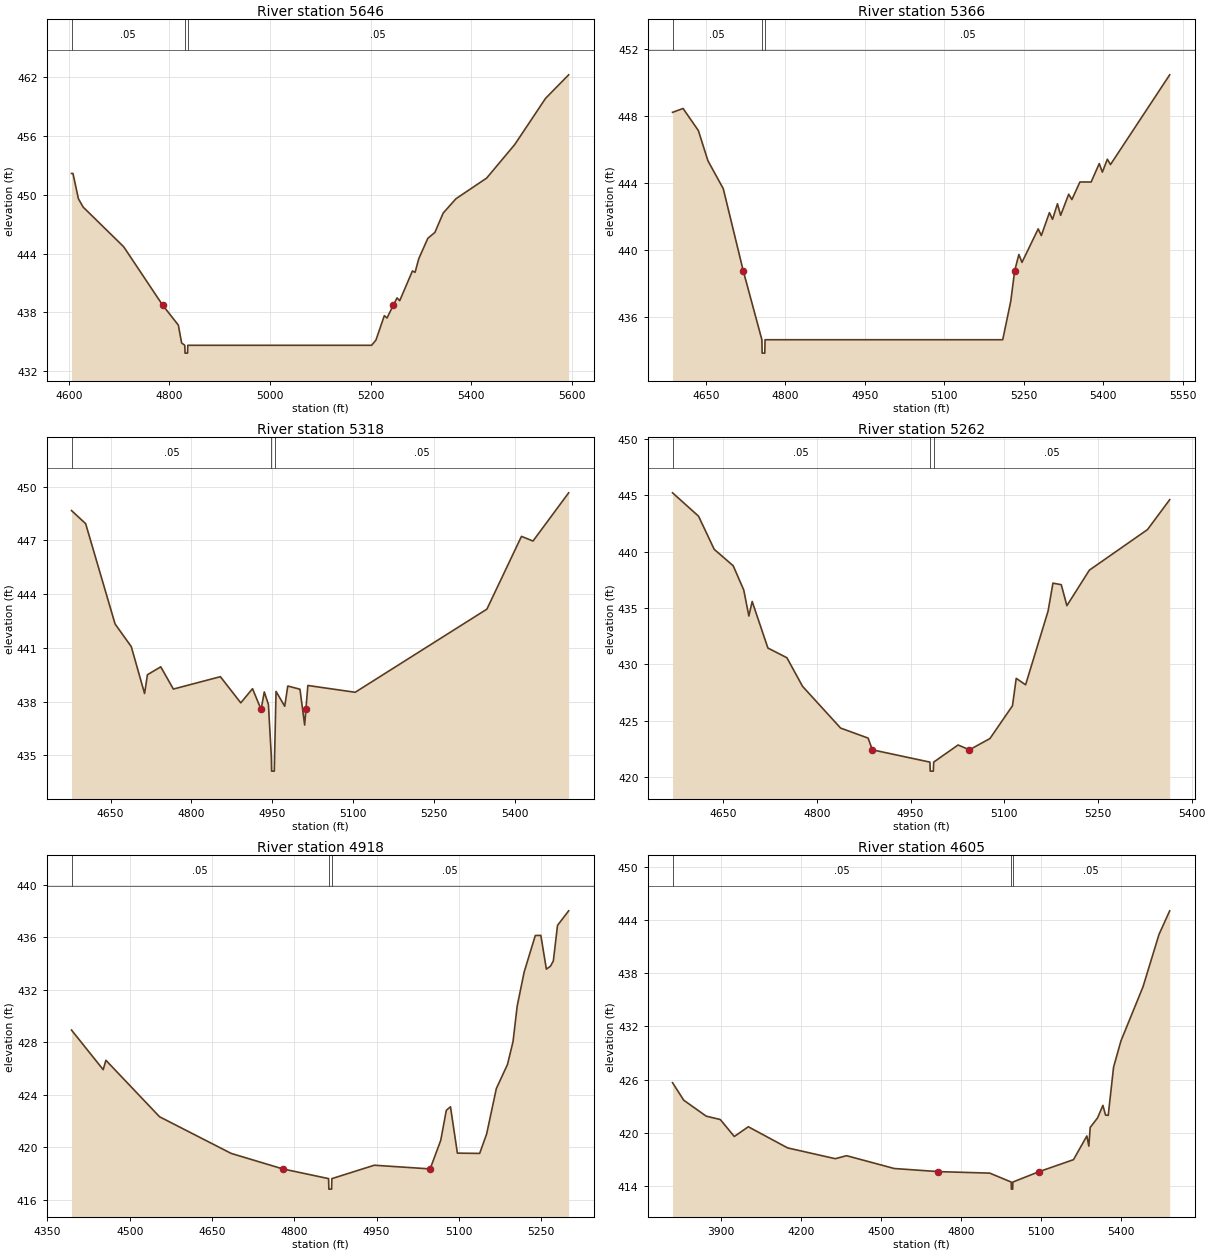
Type RM Length L Ch R = 1,5646,280,280,280
BEGIN DESCRIPTION:
UNT 085 in LFCCL Watershed 5.0
END DESCRIPTION:
XS GIS Cut Line= 3
      2811374.97      7043975.02      2811725.00      7043775.00
      2811925.01      7043224.98
#Sta/Elev= 30
  4605.4  452.18  4608.3  452.18  4619.1  449.60  4628.5  448.75  4709.1  444.70
  4786.3  438.76  4817.8  436.70  4824.3  434.88  4830.6  434.64  4831.1  433.84
  4836.1  433.84  4836.6  434.64  5202.1  434.64  5210.7  435.18  5227.3  437.66
  5232.7  437.43  5245.4  438.76  5252.6  439.48  5257.9  439.19  5283.2  442.23
  5288.5  442.09  5295.8  443.48  5313.8  445.56  5327.8  446.16  5344.4  448.14
  5369.7  449.60  5430.8  451.71  5486.7  455.14  5547.9  459.85  5593.8  462.25
#Mann=3,-1,0
  4605.4    0.05       0  4830.6   0.033       0  4836.6    0.05       0
Bank Sta=4786.3,5245.4
Exp/Cntr=0.3,0.1

Type RM Length L Ch R = 1,5366,48,48,48
BEGIN DESCRIPTION:
XS3599A
END DESCRIPTION:
XS GIS Cut Line= 4
      2811511.58      7044197.82      2811686.07      7044122.29
      2811949.09      7043966.04      2812323.36      7043729.52
#Sta/Elev= 30
  4586.8  448.22  4606.7  448.45  4635.6  447.13  4653.6  445.33  4682.6  443.66
  4720.3  438.76  4755.5  434.64  4756.0  433.84  4761.0  433.84  4761.5  434.64
  5210.3  434.64  5225.5  436.94  5232.9  438.76  5240.8  439.73  5246.7  439.26
  5277.3  441.26  5283.2  440.86  5298.5  442.23  5304.4  441.83  5313.7  442.76
  5319.7  442.07  5334.9  443.33  5340.9  443.01  5356.1  444.06  5377.3  444.06
  5392.6  445.16  5398.5  444.65  5407.9  445.42  5413.8  445.10  5525.6  450.46
#Mann=3,-1,0
  4586.8    0.05       0  4755.5    0.03       0  4761.5    0.05       0
Bank Sta=4720.3,5232.9
Exp/Cntr=0.3,0.1

Type RM Length L Ch R = 1,5318,56,56,56
BEGIN DESCRIPTION:
XS3600A
END DESCRIPTION:
XS GIS Cut Line= 6
      2811524.65      7044229.05      2811693.89      7044163.96
      2811902.22      7044049.37      2812055.86      7043950.42
      2812183.47      7043846.25      2812316.29      7043765.51
#Sta/Elev= 30
  4577.5  448.66  4603.7  447.93  4658.3  442.33  4688.3  441.07  4713.0  438.45
  4718.3  439.50  4743.0  439.94  4766.4  438.70  4853.6  439.39  4891.4  437.93
  4913.2  438.72  4929.1  437.56  4935.0  438.54  4942.7  437.84  4948.1  434.92
  4948.6  434.12  4953.6  434.12  4954.1  434.92  4956.8  438.57  4972.9  437.74
  4978.6  438.87  5001.2  438.69  5009.9  436.69  5012.2  437.56  5015.8  438.90
  5103.6  438.52  5347.9  443.16  5412.0  447.22  5433.4  446.96  5499.5  449.65
#Mann=3,-1,0
  4577.5    0.05       0  4948.1    0.03       0  4954.1    0.05       0
Bank Sta=4929.1,5012.2
Exp/Cntr=0.3,0.1

Type RM Length L Ch R = 1,5262,344,344,344
BEGIN DESCRIPTION:
XS3601A
END DESCRIPTION:
XS GIS Cut Line= 3
      2811548.09      7044273.32      2811816.28      7044174.37
      2812240.34      7043890.80
#Sta/Elev= 30
  4568.8  445.23  4610.4  443.16  4635.5  440.22  4665.9  438.76  4682.8  436.61
  4691.0  434.30  4696.3  435.59  4721.5  431.46  4751.9  430.60  4777.0  428.06
  4837.9  424.36  4881.9  423.47  4888.8  422.43  4980.9  421.34  4981.4  420.54
  4986.4  420.54  4986.9  421.34  5026.0  422.86  5044.1  422.43  5077.0  423.43
  5113.1  426.34  5119.1  428.77  5134.1  428.20  5170.1  434.74  5177.9  437.22
  5191.2  437.08  5200.2  435.22  5236.2  438.37  5329.3  441.97  5364.8  444.62
#Mann=3,-1,0
  4568.8    0.05       0  4980.9    0.03       0  4986.9    0.05       0
Bank Sta=4888.8,5044.1
Exp/Cntr=0.3,0.1

Type RM Length L Ch R = 1,4918,313,313,313
BEGIN DESCRIPTION:
UNT 085 in LFCCL Watershed 3.0
END DESCRIPTION:
XS GIS Cut Line= 3
      2811575.03      7044375.00      2812175.00      7044325.00
      2812225.00      7044024.99
#Sta/Elev= 30
  4393.9  428.93  4451.6  425.92  4456.6  426.63  4554.4  422.33  4684.9  419.54
  4779.0  418.36  4862.5  417.62  4863.0  416.82  4868.0  416.82  4868.5  417.62
  4945.8  418.64  5047.6  418.36  5066.9  420.53  5077.1  422.82  5084.7  423.09
  5097.3  419.56  5137.9  419.54  5150.6  421.02  5168.3  424.48  5188.6  426.31
  5198.7  428.05  5206.3  430.76  5219.0  433.35  5239.3  436.13  5249.4  436.14
  5259.5  433.57  5267.1  433.80  5272.2  434.20  5279.8  436.90  5300.1  438.01
#Mann=3,-1,0
  4393.9    0.05       0  4862.5    0.03       0  4868.5    0.05       0
Bank Sta=4779,5047.6
Exp/Cntr=0.3,0.1

Type RM Length L Ch R = 1,4605,368,368,368
BEGIN DESCRIPTION:
UNT 085 in LFCCL Watershed 2.0
END DESCRIPTION:
XS GIS Cut Line= 3
      2811225.04      7044924.99      2812425.00      7044525.00
      2812375.00      7043925.05
#Sta/Elev= 30
  3717.0  425.64  3759.1  423.66  3843.4  421.86  3896.2  421.48  3948.9  419.56
  4001.6  420.66  4149.1  418.27  4328.3  417.05  4370.5  417.39  4549.7  415.94
  4715.1  415.59  4908.1  415.42  4988.9  414.41  4989.4  413.61  4994.4  413.61
  4994.9  414.41  5093.9  415.59  5222.7  416.94  5272.9  419.62  5280.4  418.47
  5285.4  420.58  5313.0  421.66  5333.1  423.08  5343.1  421.98  5353.1  421.95
  5373.2  427.40  5400.8  430.36  5483.6  436.47  5543.8  442.40  5583.9  445.07
#Mann=3,-1,0
  3717.0    0.05       0  4988.9    0.03       0  4994.9    0.05       0
Bank Sta=4715.1,5093.9
Exp/Cntr=0.3,0.1

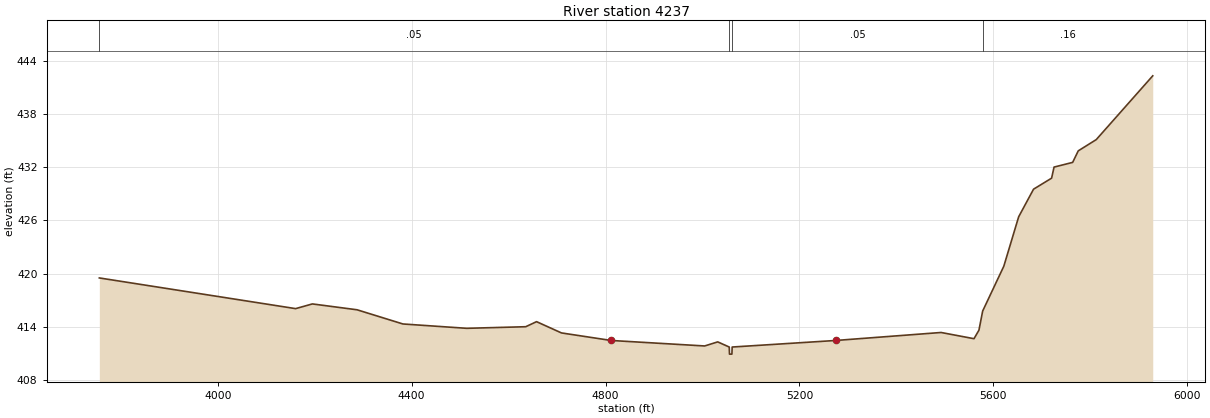
Type RM Length L Ch R = 1,4237,0,0,0
BEGIN DESCRIPTION:
UNT 085 in LFCCL Watershed 1.0
END DESCRIPTION:
XS GIS Cut Line= 3
      2811507.25      7045013.79      2812725.00      7044725.00
      2812525.00      7043824.98
#Sta/Elev= 30
  3755.6  419.52  4160.6  416.06  4195.2  416.59  4287.3  415.93  4382.0  414.33
  4513.8  413.84  4635.4  414.02  4657.7  414.59  4709.1  413.32  4811.6  412.47
  5004.6  411.85  5031.5  412.31  5055.3  411.73  5055.8  410.93  5060.8  410.93
  5061.3  411.73  5275.1  412.47  5492.4  413.37  5560.3  412.67  5570.5  413.63
  5578.2  415.79  5621.8  420.84  5652.5  426.42  5683.2  429.53  5720.4  430.77
  5725.5  432.02  5763.9  432.55  5775.4  433.85  5812.6  435.12  5929.1  442.31
#Mann=4,-1,0
  3755.6    0.05       0  5055.3    0.03       0  5061.3    0.05       0
  5578.2    0.16       0
Bank Sta=4811.6,5275.1
Exp/Cntr=0.3,0.1

Chan Stop Cuts=-1