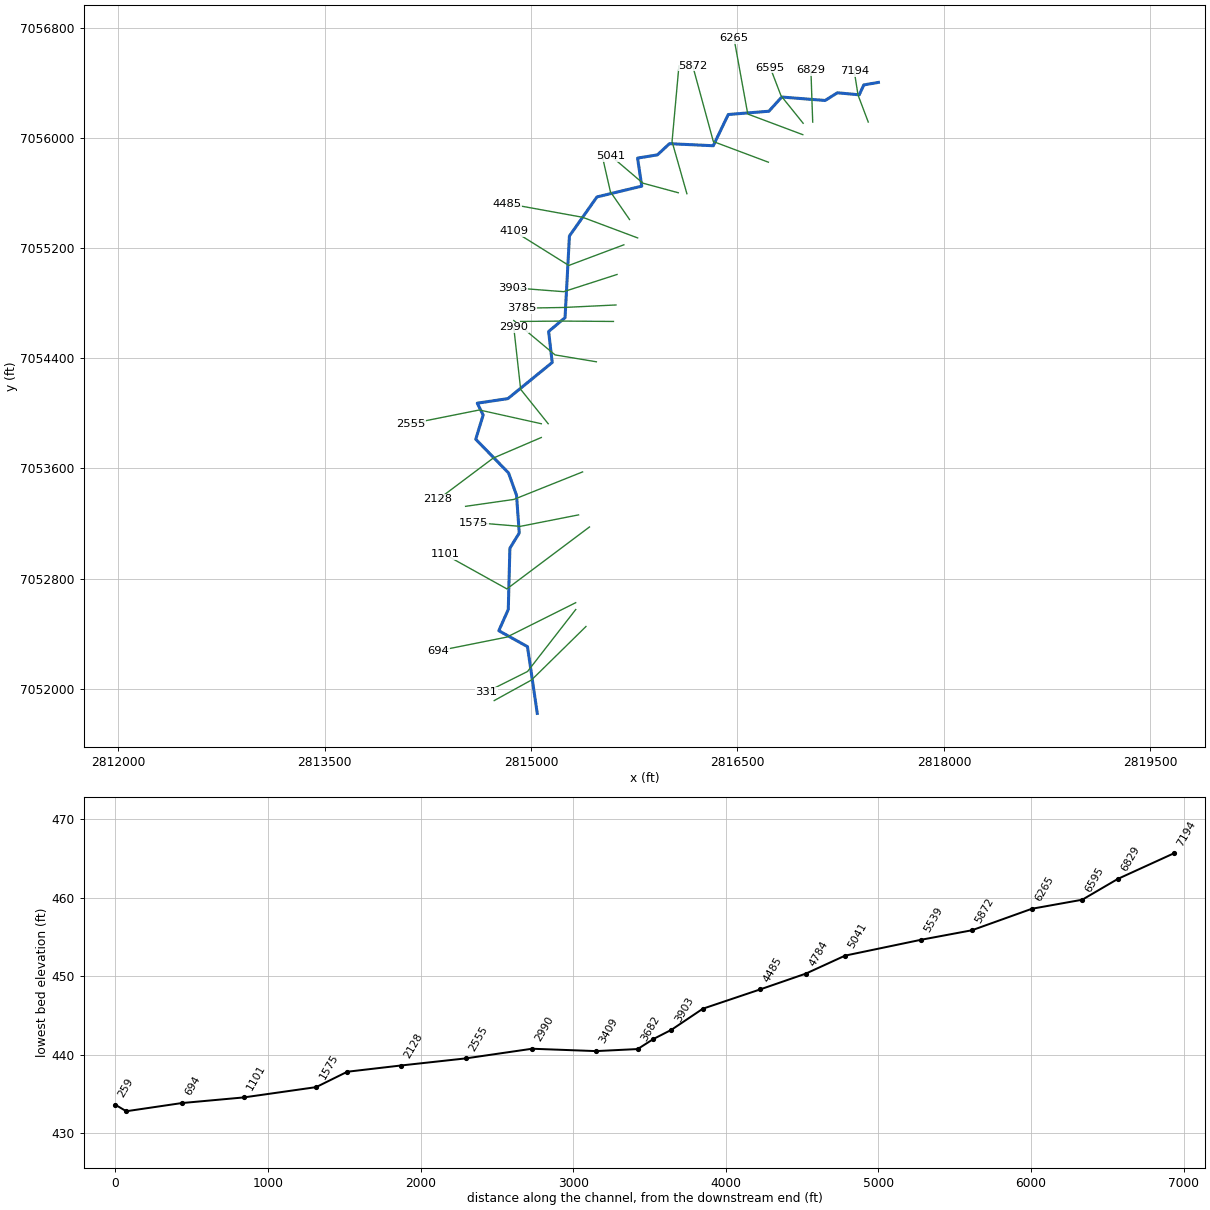
--- UNT 087 in LFCCL Watershed.prj (project) ---

Proj Title=UNT 087 in LFCCL Watershed Base Level Engineering
Current Plan=p01
Default Exp/Contr=0.3,0.1
English Units
Geom File=g01
Flow File=f01
Plan File=p01
BEGIN DESCRIPTION:
UNT 087 in LFCCL Watershed
END DESCRIPTION:

--- UNT 087 in LFCCL Watershed.p01 (plan) ---

Plan Title=Multiple Run
Short Identifier=Multiple
Geom File=g01
Flow File=f01
Subcritical Flow
K Sum by GR= 0
Std Step Tol= 0.01
Critical Tol= 0.01
Num of Std Step Trials= 20
Max Error Tol= 0.3
Flow Tol Ratio= 0.001
Split Flow NTrial= 30
Split Flow Tol= 0.02
Split Flow Ratio= 0.02
Log Output Level= 0
Friction Slope Method= 1
Unsteady Friction Slope Method= 2
Unsteady Bridges Friction Slope Method= 1
Parabolic Critical Depth
Global Vel Dist=  1 , 1 , 1
Global Log Level= 0
CheckData=True
Encroach Param= -1, 0, 0, 0
BEGIN DESCRIPTION:
Multiple Run
END DESCRIPTION:

--- UNT 087 in LFCCL Watershed.f01 (steady flow) ---

Flow Title=Multiple
Number of Profiles=7
Profile Names=10-year,25-year,50-year,1pct_min,100-year,1pct_plu,500-year
River Rch & RM= UNT 087 in LFCCL,Reach-1,7194
     350     452     533     313     625    1246     857
River Rch & RM= UNT 087 in LFCCL,Reach-1,2555
     413     539     639     377     751    1499    1040
Boundary for River Rch & Prof#=UNT 087 in LFCCL,Reach-1,1
Up Type=0
Dn Type=3
Dn Slope=0.005
Boundary for River Rch & Prof#=UNT 087 in LFCCL,Reach-1,2
Up Type=0
Dn Type=3
Dn Slope=0.005
Boundary for River Rch & Prof#=UNT 087 in LFCCL,Reach-1,3
Up Type=0
Dn Type=3
Dn Slope=0.005
Boundary for River Rch & Prof#=UNT 087 in LFCCL,Reach-1,4
Up Type=0
Dn Type=3
Dn Slope=0.005
Boundary for River Rch & Prof#=UNT 087 in LFCCL,Reach-1,5
Up Type=0
Dn Type=3
Dn Slope=0.005
Boundary for River Rch & Prof#=UNT 087 in LFCCL,Reach-1,6
Up Type=0
Dn Type=3
Dn Slope=0.005
Boundary for River Rch & Prof#=UNT 087 in LFCCL,Reach-1,7
Up Type=0
Dn Type=3
Dn Slope=0.005

--- UNT 087 in LFCCL Watershed.g01 (geometry) ---

Geom Title=Existing Conditions

River Reach=UNT 087 in LFCCL,Reach-1
Reach XY= 30
      2817524.23      7056404.86      2817418.03      7056386.51
      2817384.77      7056314.64      2817226.03      7056329.44
      2817137.02      7056273.47      2816821.78      7056298.60
      2816728.57      7056195.47      2816433.26      7056171.49
      2816324.30      7055944.66      2816005.95      7055959.63
      2815918.86      7055878.42      2815774.22      7055854.97
      2815805.07      7055651.20      2815479.31      7055572.70
      2815279.39      7055289.13      2815247.59      7054695.59
      2815128.26      7054595.37      2815154.25      7054370.06
      2814832.70      7054107.61      2814609.81      7054074.28
      2814652.67      7053988.55      2814598.78      7053812.32
      2814837.18      7053567.18      2814895.01      7053405.47
      2814914.81      7053131.11      2814846.81      7053020.64
      2814835.13      7052575.90      2814766.34      7052421.27
      2814974.64      7052305.45      2815045.59      7051820.71

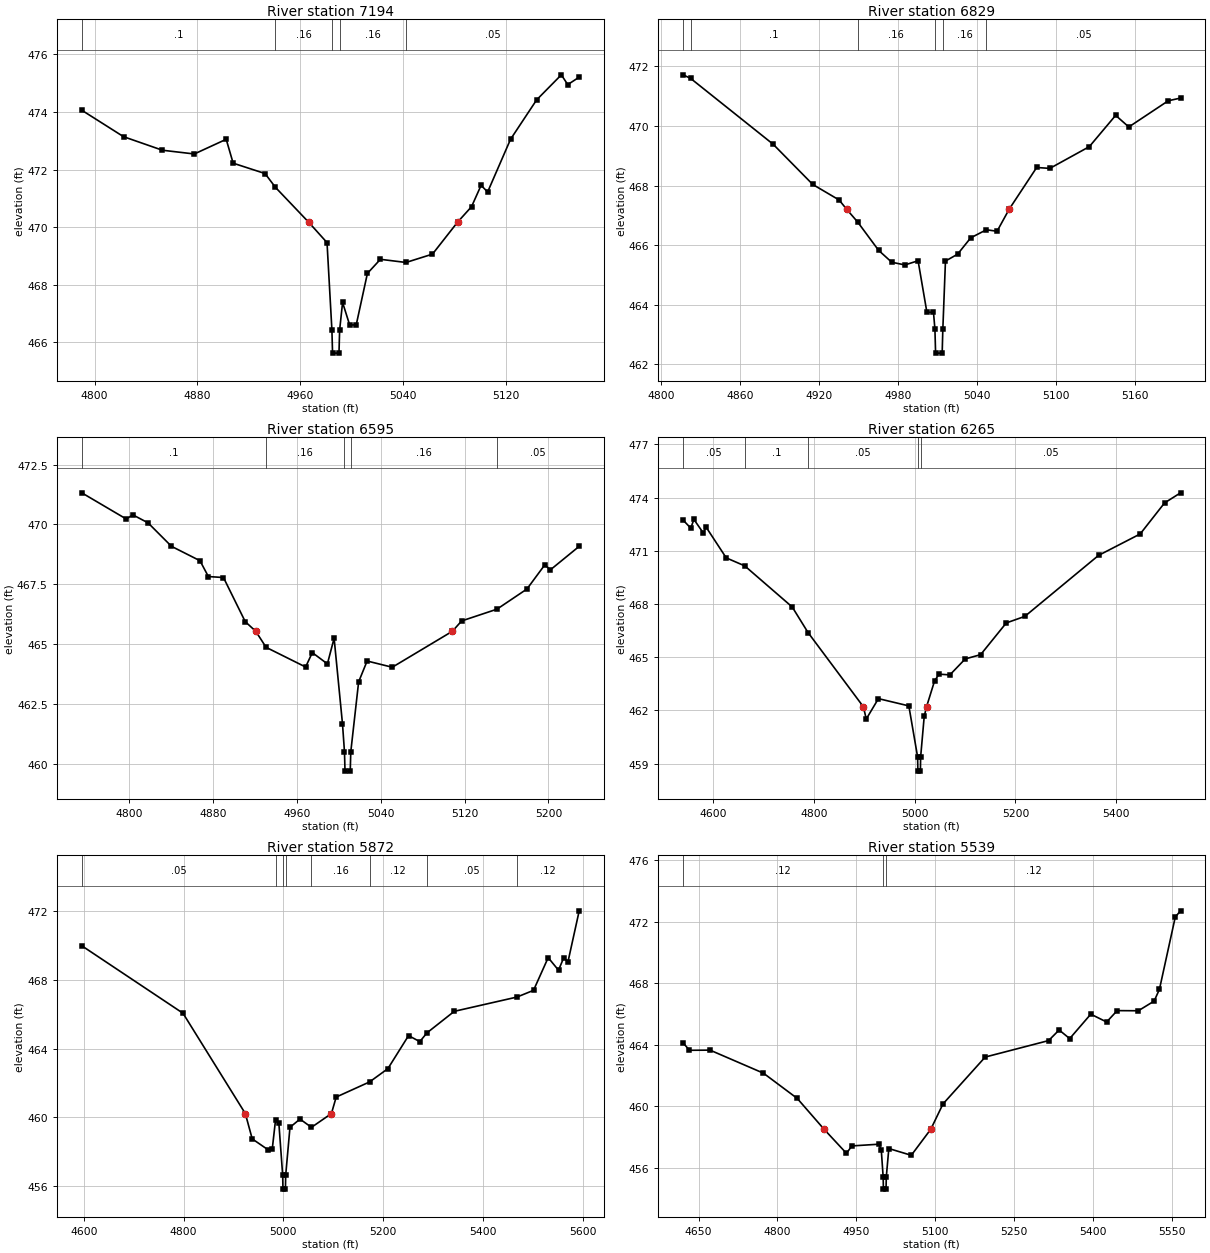
Type RM Length L Ch R = 1,7194,365,365,365
BEGIN DESCRIPTION:
UNT 087 in LFCCL Watershed 18.0
END DESCRIPTION:
XS GIS Cut Line= 3
      2817450.42      7056116.68      2817376.12      7056312.99
      2817348.45      7056487.71
#Sta/Elev= 30
  4790.1  474.06  4822.6  473.14  4852.8  472.67  4877.6  472.54  4902.4  473.05
  4907.8  472.22  4932.6  471.86  4940.7  471.38  4966.5  470.17  4980.8  469.46
  4984.6  466.42  4985.1  465.62  4990.1  465.62  4990.6  466.42  4992.9  467.38
  4998.4  466.60  5003.5  466.60  5012.2  468.39  5022.3  468.88  5042.2  468.77
  5062.8  469.06  5082.3  470.17  5093.2  470.71  5100.6  471.45  5105.7  471.22
  5123.5  473.05  5143.8  474.42  5163.0  475.29  5168.0  474.95  5176.9  475.21
#Mann=5,-1,0
  4790.1     0.1       0  4940.7    0.16       0  4984.6    0.07       0
  4990.6    0.16       0  5042.2    0.05       0
Bank Sta=4966.5,5082.3
Exp/Cntr=0.3,0.1

Type RM Length L Ch R = 1,6829,234,234,234
BEGIN DESCRIPTION:
XS3602A
END DESCRIPTION:
XS GIS Cut Line= 3
      2817046.80      7056116.60      2817040.28      7056303.27
      2817033.77      7056494.27
#Sta/Elev= 30
  4816.5  471.72  4822.2  471.60  4884.9  469.39  4915.0  468.04  4935.0  467.52
  4940.7  467.21  4949.1  466.78  4965.0  465.83  4975.0  465.43  4985.0  465.34
  4995.0  465.48  5001.7  463.75  5006.7  463.75  5007.8  463.18  5008.3  462.38
  5013.3  462.38  5013.8  463.18  5015.8  465.47  5025.0  465.70  5035.0  466.25
  5046.9  466.52  5055.0  466.47  5064.2  467.21  5085.1  468.61  5095.1  468.58
  5125.1  469.31  5145.1  470.36  5155.1  469.97  5185.1  470.85  5194.4  470.94
#Mann=6,-1,0
  4816.5    0.05       0  4822.2     0.1       0  4949.1    0.16       0
  5007.8    0.07       0  5013.8    0.16       0  5046.9    0.05       0
Bank Sta=4940.7,5064.2
Exp/Cntr=0.3,0.1

Type RM Length L Ch R = 1,6595,330,330,330
BEGIN DESCRIPTION:
XS3603A
END DESCRIPTION:
XS GIS Cut Line= 3
      2816977.37      7056107.93      2816816.76      7056307.61
      2816738.64      7056511.61
#Sta/Elev= 30
  4754.7  471.32  4797.1  470.23  4803.5  470.40  4817.9  470.07  4840.3  469.09
  4867.5  468.49  4875.5  467.83  4889.9  467.79  4910.7  465.95  4920.7  465.55
  4930.6  464.88  4968.3  464.06  4974.7  464.66  4989.1  464.19  4995.5  465.26
  5003.5  461.69  5005.4  460.52  5005.9  459.72  5010.9  459.72  5011.4  460.52
  5018.9  463.44  5027.0  464.31  5051.0  464.05  5108.4  465.55  5117.2  465.98
  5150.9  466.47  5179.5  467.31  5196.6  468.32  5201.9  468.11  5229.4  469.09
#Mann=5,-1,0
  4754.7     0.1       0  4930.6    0.16       0  5005.4    0.07       0
  5011.4    0.16       0  5150.9    0.05       0
Bank Sta=4920.7,5108.4
Exp/Cntr=0.3,0.1

Type RM Length L Ch R = 1,6265,393,393,393
BEGIN DESCRIPTION:
UNT 087 in LFCCL Watershed 16.0
END DESCRIPTION:
XS GIS Cut Line= 3
      2816975.02      7056024.99      2816575.00      7056175.00
      2816475.01      7056724.97
#Sta/Elev= 30
  4541.1  472.73  4556.2  472.28  4562.5  472.77  4581.2  472.00  4586.5  472.34
  4626.6  470.60  4663.2  470.15  4757.4  467.83  4788.7  466.39  4898.5  462.20
  4904.2  461.51  4928.3  462.66  4988.6  462.25  5006.0  459.37  5006.5  458.57
  5011.5  458.57  5012.0  459.37  5019.1  461.66  5023.7  462.20  5039.5  463.65
  5048.4  464.04  5070.0  464.00  5100.4  464.90  5130.9  465.14  5181.8  466.93
  5218.6  467.30  5364.7  470.74  5447.3  471.95  5495.6  473.70  5527.3  474.27
#Mann=5,-1,0
  4541.1    0.05       0  4663.2     0.1       0  4788.7    0.05       0
  5006.0   0.035       0  5012.0    0.05       0
Bank Sta=4898.5,5023.7
Exp/Cntr=0.3,0.1

Type RM Length L Ch R = 1,5872,333,333,333
BEGIN DESCRIPTION:
UNT 087 in LFCCL Watershed 15.0
END DESCRIPTION:
XS GIS Cut Line= 3
      2816724.97      7055825.01      2816325.00      7055975.00
      2816174.99      7056525.04
#Sta/Elev= 30
  4595.8  469.97  4798.7  466.05  4923.7  460.22  4937.5  458.75  4969.6  458.11
  4977.6  458.14  4984.2  459.83  4990.9  459.67  4998.6  456.63  4999.1  455.83
  5004.1  455.83  5004.6  456.63  5013.2  459.42  5033.3  459.90  5056.3  459.42
  5096.3  460.22  5105.9  461.18  5172.9  462.06  5209.5  462.83  5251.0  464.75
  5273.5  464.40  5287.9  464.91  5342.6  466.16  5468.3  466.99  5501.5  467.38
  5530.9  469.28  5551.6  468.55  5562.0  469.27  5570.6  469.04  5593.1  472.00
#Mann=8,-1,0
  4595.8    0.05       0  4984.2    0.12       0  4998.6    0.07       0
  5004.6    0.12       0  5056.3    0.16       0  5172.9    0.12       0
  5287.9    0.05       0  5468.3    0.12       0
Bank Sta=4923.7,5096.3
Exp/Cntr=0.3,0.1

Type RM Length L Ch R = 1,5539,498,498,498
BEGIN DESCRIPTION:
UNT 087 in LFCCL Watershed 14.0
END DESCRIPTION:
XS GIS Cut Line= 3
      2816132.72      7055596.27      2816025.00      7055975.00
      2816075.00      7056524.98
#Sta/Elev= 30
  4620.7  464.13  4632.8  463.65  4671.9  463.66  4773.5  462.16  4837.7  460.52
  4888.6  458.52  4931.3  456.95  4941.7  457.43  4992.3  457.54  4997.5  457.19
  5001.1  455.42  5001.6  454.62  5006.6  454.62  5007.1  455.42  5011.9  457.26
  5054.6  456.82  5091.8  458.52  5114.9  460.16  5195.2  463.21  5315.7  464.28
  5335.8  464.97  5355.9  464.41  5396.0  466.00  5426.1  465.49  5446.2  466.23
  5486.4  466.22  5516.5  466.85  5526.6  467.62  5556.7  472.32  5566.7  472.72
#Mann=3,-1,0
  4620.7    0.12       0  5001.1    0.07       0  5007.1    0.12       0
Bank Sta=4888.6,5091.8
Exp/Cntr=0.3,0.1

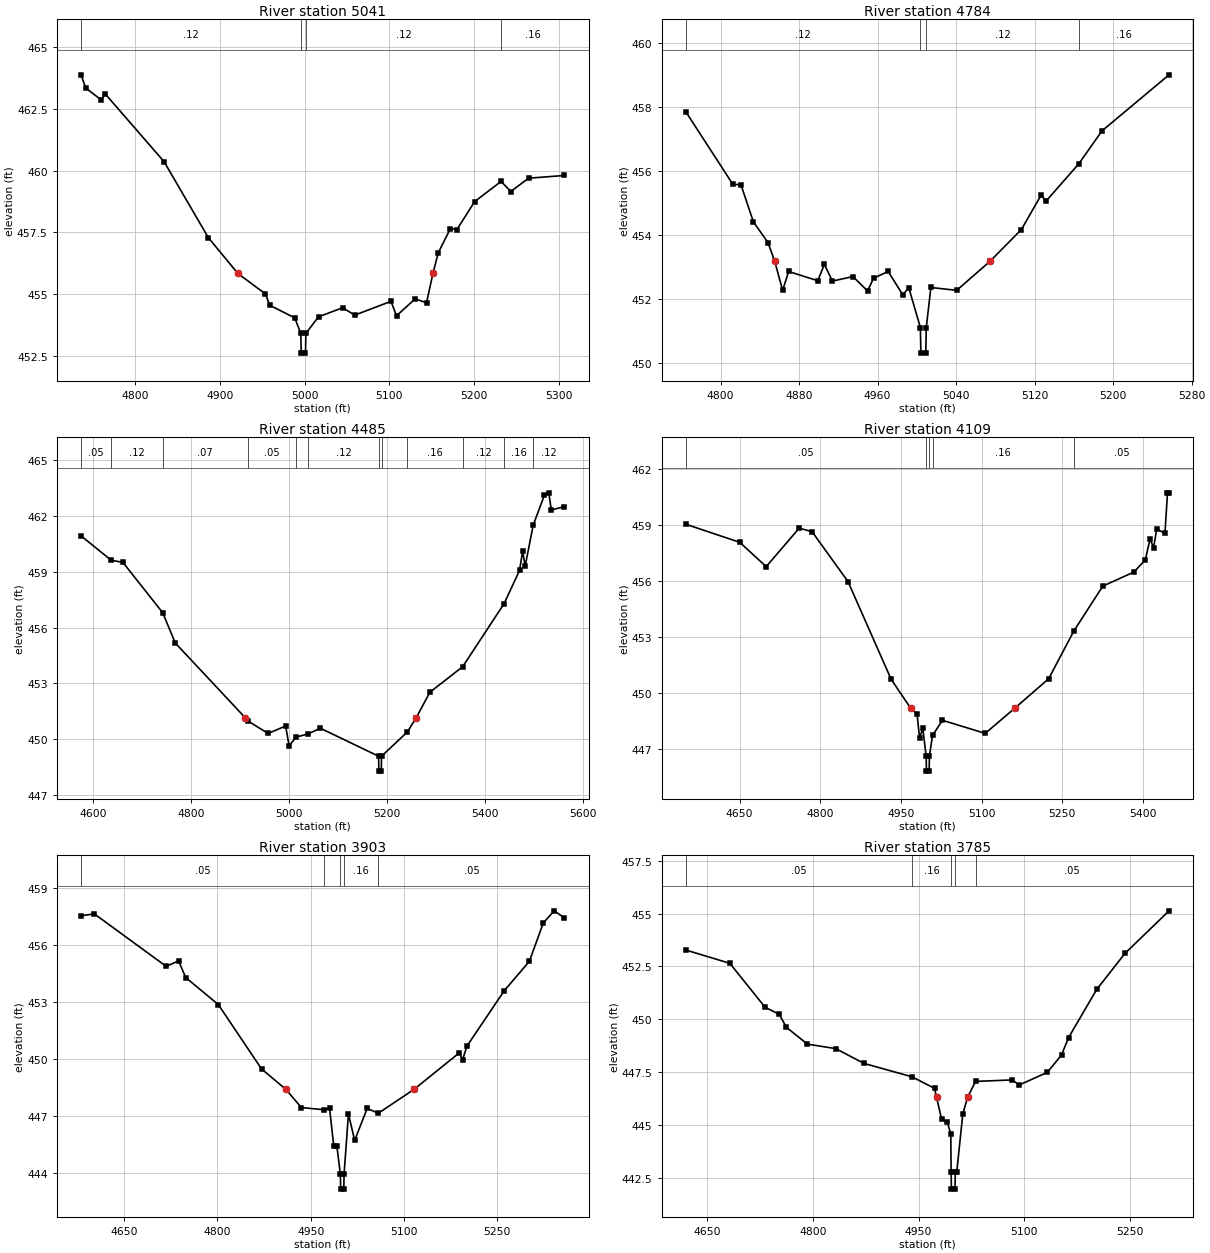
Type RM Length L Ch R = 1,5041,257,257,257
BEGIN DESCRIPTION:
XS3604A
END DESCRIPTION:
XS GIS Cut Line= 3
      2816070.24      7055603.18      2815813.29      7055672.63
      2815580.96      7055870.28
#Sta/Elev= 30
  4735.7  463.88  4741.1  463.35  4759.2  462.87  4764.4  463.10  4833.8  460.36
  4886.1  457.28  4921.0  455.83  4953.5  455.00  4958.7  454.54  4988.2  454.03
  4995.4  453.40  4995.9  452.60  5000.9  452.60  5001.4  453.40  5016.3  454.07
  5044.8  454.44  5059.1  454.14  5102.0  454.70  5108.5  454.11  5130.5  454.80
  5144.0  454.64  5151.5  455.83  5157.9  456.67  5172.2  457.65  5179.9  457.61
  5200.8  458.74  5232.1  459.56  5243.6  459.15  5264.5  459.69  5306.9  459.80
#Mann=4,-1,0
  4735.7    0.12       0  4995.4    0.07       0  5001.4    0.12       0
  5232.1    0.16       0
Bank Sta=4921,5151.5
Exp/Cntr=0.3,0.1

Type RM Length L Ch R = 1,4784,299,299,299
BEGIN DESCRIPTION:
XS3605A
END DESCRIPTION:
XS GIS Cut Line= 3
      2815716.05      7055408.77      2815577.18      7055610.13
      2815521.98      7055851.60
#Sta/Elev= 30
  4764.6  457.85  4812.6  455.58  4820.8  455.57  4833.5  454.41  4848.4  453.76
  4855.2  453.18  4863.3  452.27  4869.4  452.86  4899.1  452.57  4905.8  453.08
  4914.0  452.56  4935.0  452.70  4949.8  452.25  4955.9  452.65  4970.8  452.86
  4985.7  452.13  4991.8  452.35  5003.6  451.11  5004.1  450.31  5009.1  450.31
  5009.6  451.11  5014.3  452.36  5040.6  452.27  5074.6  453.18  5106.5  454.17
  5126.5  455.24  5131.7  455.06  5164.9  456.22  5188.6  457.25  5256.9  459.00
#Mann=4,-1,0
  4764.6    0.12       0  5003.6    0.07       0  5009.6    0.12       0
  5164.9    0.16       0
Bank Sta=4855.2,5074.6
Exp/Cntr=0.3,0.1

Type RM Length L Ch R = 1,4485,376,376,376
BEGIN DESCRIPTION:
UNT 087 in LFCCL Watershed 11.0
END DESCRIPTION:
XS GIS Cut Line= 3
      2815774.97      7055275.01      2815375.00      7055425.00
      2814824.99      7055525.00
#Sta/Elev= 30
  4575.0  460.91  4636.3  459.61  4660.4  459.49  4741.6  456.79  4767.2  455.17
  4910.4  451.15  4914.6  451.00  4956.8  450.32  4992.4  450.72  4999.5  449.65
  5013.4  450.12  5038.6  450.30  5063.2  450.60  5182.1  449.10  5182.6  448.30
  5187.6  448.30  5188.1  449.10  5240.8  450.40  5258.6  451.15  5286.8  452.53
  5353.7  453.90  5438.2  457.28  5469.7  459.06  5476.1  460.10  5481.1  459.28
  5497.5  461.48  5520.5  463.10  5529.4  463.22  5534.5  462.30  5561.2  462.48
#Mann=12,-1,0
  4575.0    0.05       0  4636.3    0.12       0  4741.6    0.07       0
  4914.6    0.05       0  5013.4    0.16       0  5038.6    0.12       0
  5182.1    0.03       0  5188.1    0.12       0  5240.8    0.16       0
  5353.7    0.12       0  5438.2    0.16       0  5497.5    0.12       0
Bank Sta=4910.4,5258.6
Exp/Cntr=0.3,0.1

Type RM Length L Ch R = 1,4109,206,206,206
BEGIN DESCRIPTION:
UNT 087 in LFCCL Watershed 10.0
END DESCRIPTION:
XS GIS Cut Line= 3
      2815675.04      7055225.02      2815275.00      7055075.00
      2814875.04      7055324.98
#Sta/Elev= 30
  4549.7  459.05  4650.3  458.08  4699.3  456.78  4760.7  458.84  4784.7  458.65
  4851.5  455.98  4931.6  450.76  4968.2  449.20  4979.9  448.90  4984.6  447.60
  4990.5  448.14  4996.9  446.64  4997.4  445.84  5002.4  445.84  5002.9  446.64
  5008.7  447.75  5027.1  448.56  5106.7  447.86  5161.4  449.20  5224.6  450.78
  5271.6  453.34  5325.4  455.74  5383.2  456.49  5404.4  457.14  5413.3  458.26
  5419.8  457.80  5425.7  458.79  5441.0  458.56  5445.7  460.73  5448.6  460.73
#Mann=5,-1,0
  4549.7    0.05       0  4996.9    0.03       0  5002.9    0.05       0
  5008.7    0.16       0  5271.6    0.05       0
Bank Sta=4968.2,5161.4
Exp/Cntr=0.3,0.1

Type RM Length L Ch R = 1,3903,118,118,118
BEGIN DESCRIPTION:
XS3606A
END DESCRIPTION:
XS GIS Cut Line= 3
      2815625.31      7055009.28      2815237.25      7054884.26
      2814868.75      7054912.81
#Sta/Elev= 30
  4580.6  457.52  4601.9  457.62  4717.5  454.86  4737.3  455.15  4749.0  454.27
  4801.4  452.85  4870.8  449.47  4909.8  448.40  4934.9  447.44  4971.9  447.32
  4980.2  447.41  4986.9  445.43  4991.9  445.43  4997.6  443.95  4998.1  443.15
  5003.1  443.15  5003.6  443.95  5010.6  447.11  5020.6  445.71  5040.7  447.39
  5058.7  447.14  5116.3  448.40  5189.1  450.32  5194.1  449.94  5201.2  450.67
  5261.4  453.59  5301.5  455.12  5324.1  457.15  5341.6  457.78  5357.9  457.41
#Mann=5,-1,0
  4580.6    0.05       0  4971.9    0.16       0  4997.6    0.07       0
  5003.6    0.16       0  5058.7    0.05       0
Bank Sta=4909.8,5116.3
Exp/Cntr=0.3,0.1

Type RM Length L Ch R = 1,3785,103,103,103
BEGIN DESCRIPTION:
XS3608A
END DESCRIPTION:
XS GIS Cut Line= 3
      2815617.45      7054787.91      2815237.25      7054769.68
      2814932.53      7054764.47
#Sta/Elev= 30
  4619.8  453.28  4682.3  452.65  4732.4  450.57  4752.4  450.24  4762.4  449.63
  4792.4  448.83  4832.5  448.62  4872.5  447.92  4940.5  447.29  4972.7  446.74
  4975.6  446.31  4982.7  445.27  4990.7  445.15  4995.7  444.58  4996.1  442.78
  4996.6  441.98  5001.6  441.98  5002.1  442.78  5004.1  442.78  5012.7  445.53
  5019.4  446.31  5030.8  447.07  5082.7  447.14  5092.7  446.90  5132.7  447.50
  5152.7  448.32  5162.7  449.14  5202.7  451.42  5242.7  453.12  5305.2  455.13
#Mann=5,-1,0
  4619.8    0.05       0  4940.5    0.16       0  4996.1    0.07       0
  5002.1    0.16       0  5030.8    0.05       0
Bank Sta=4975.6,5019.4
Exp/Cntr=0.3,0.1

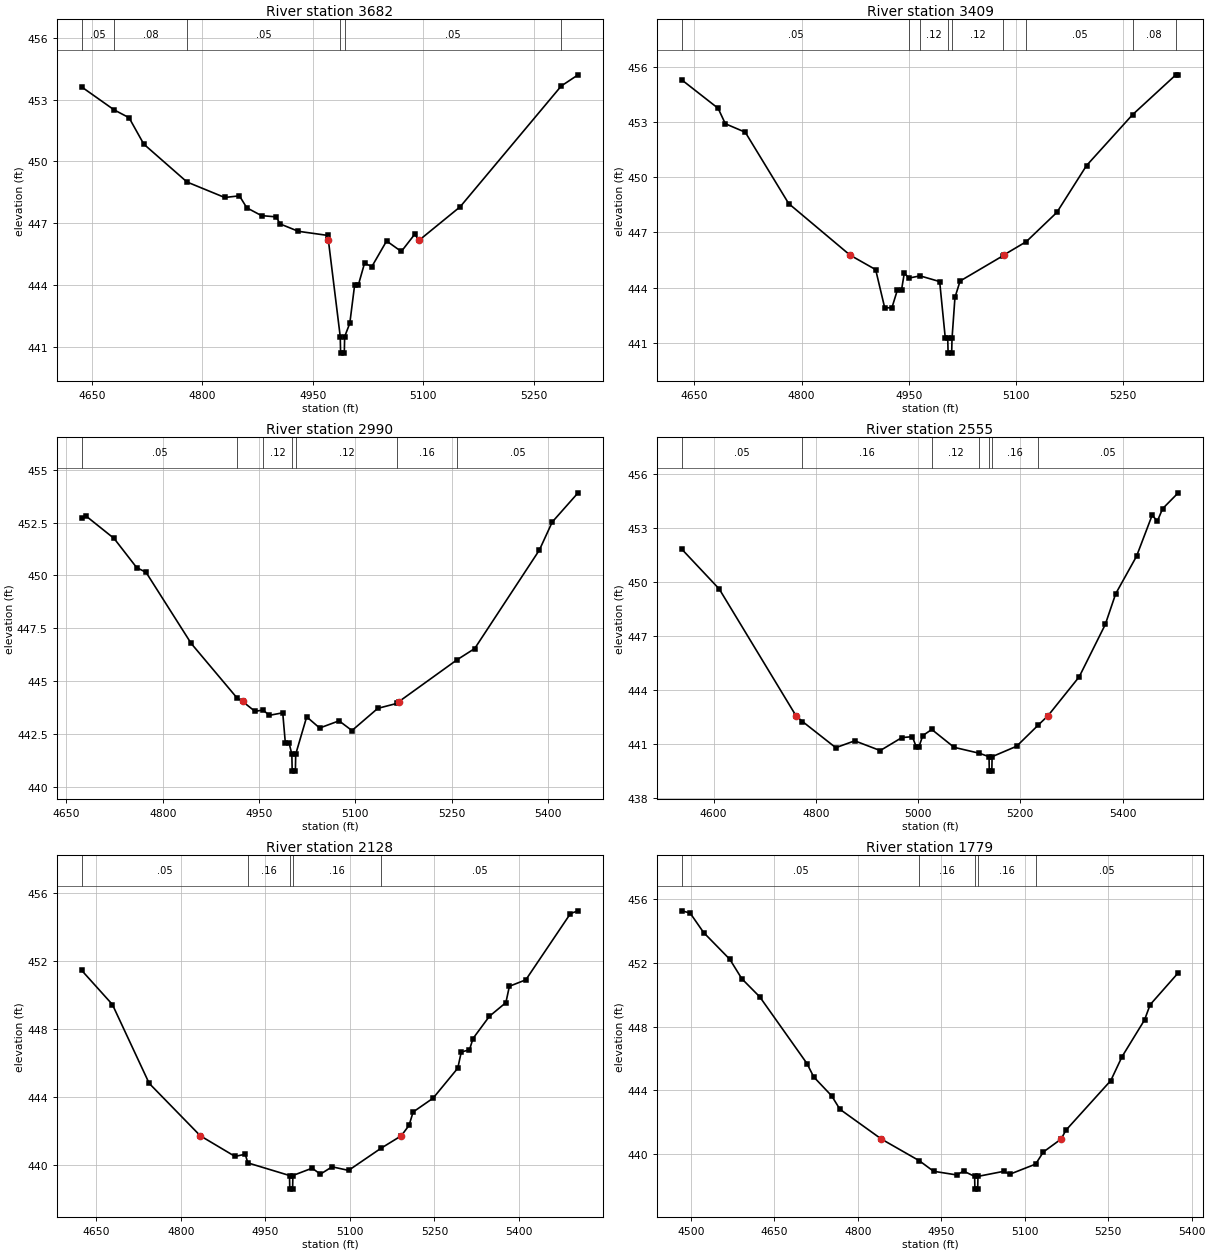
Type RM Length L Ch R = 1,3682,273,273,273
BEGIN DESCRIPTION:
XS3607A
END DESCRIPTION:
XS GIS Cut Line= 3
      2815599.25      7054668.12      2815226.83      7054670.72
      2814924.77      7054668.12
#Sta/Elev= 30
  4636.0  453.61  4680.0  452.50  4700.3  452.12  4720.3  450.84  4779.1  449.00
  4830.3  448.25  4850.3  448.33  4860.3  447.75  4880.3  447.37  4900.3  447.31
  4905.4  446.97  4930.3  446.61  4970.3  446.41  4971.2  446.17  4987.3  441.50
  4987.8  440.70  4992.8  440.70  4993.3  441.50  5000.3  442.15  5006.8  443.99
  5011.8  443.99  5020.3  445.06  5030.3  444.90  5050.3  446.14  5070.3  445.63
  5088.6  446.47  5094.3  446.17  5150.3  447.80  5287.7  453.66  5310.5  454.20
#Mann=6,-1,0
  4636.0    0.05       0  4680.0    0.08       0  4779.1    0.05       0
  4987.3    0.04       0  4993.3    0.05       0  5287.7    0.08       0
Bank Sta=4971.2,5094.3
Exp/Cntr=0.3,0.1

Type RM Length L Ch R = 1,3409,419,419,419
BEGIN DESCRIPTION:
UNT 087 in LFCCL Watershed 8.0
END DESCRIPTION:
XS GIS Cut Line= 3
      2815475.00      7054375.00      2815175.00      7054425.00
      2814874.96      7054675.03
#Sta/Elev= 30
  4632.5  455.29  4683.2  453.75  4693.3  452.91  4721.2  452.45  4782.0  448.57
  4867.8  445.77  4903.7  444.98  4916.4  442.90  4926.5  442.91  4934.1  443.87
  4939.9  443.87  4943.8  444.79  4950.3  444.52  4965.9  444.64  4993.3  444.33
  5001.1  441.28  5004.6  441.24  5005.1  440.44  5010.1  440.44  5010.6  441.24
  5014.7  443.47  5021.9  444.36  5081.8  445.73  5082.8  445.77  5114.5  446.50
  5157.3  448.09  5198.9  450.64  5263.2  453.40  5323.9  455.57  5327.2  455.57
#Mann=9,-1,0
  4632.5    0.05       0  4950.3    0.16       0  4965.9    0.12       0
  5004.6    0.07       0  5010.6    0.12       0  5081.8    0.16       0
  5114.5    0.05       0  5263.2    0.08       0  5323.9    0.05       0
Bank Sta=4867.8,5082.8
Exp/Cntr=0.3,0.1

Type RM Length L Ch R = 1,2990,435,435,435
BEGIN DESCRIPTION:
UNT 087 in LFCCL Watershed 7.0
END DESCRIPTION:
XS GIS Cut Line= 3
      2815125.00      7053925.00      2814925.00      7054175.00
      2814875.00      7054624.97
#Sta/Elev= 30
  4673.9  452.74  4681.1  452.80  4724.3  451.75  4759.5  450.37  4774.0  450.15
  4844.4  446.78  4915.8  444.20  4924.3  444.04  4943.6  443.57  4956.3  443.63
  4966.0  443.38  4986.9  443.50  4990.9  442.09  4996.6  442.09  5001.1  441.54
  5001.6  440.74  5006.6  440.74  5007.1  441.54  5024.2  443.31  5044.4  442.78
  5074.6  443.12  5094.7  442.66  5134.9  443.71  5165.3  443.95  5167.9  444.03
  5258.4  446.01  5285.8  446.54  5386.5  451.20  5406.6  452.53  5446.8  453.91
#Mann=7,-1,0
  4673.9    0.05       0  4915.8    0.16       0  4956.3    0.12       0
  5001.1    0.07       0  5007.1    0.12       0  5165.3    0.16       0
  5258.4    0.05       0
Bank Sta=4924.3,5167.9
Exp/Cntr=0.3,0.1

Type RM Length L Ch R = 1,2555,427,427,427
BEGIN DESCRIPTION:
UNT 087 in LFCCL Watershed 6.0
END DESCRIPTION:
XS GIS Cut Line= 3
      2815075.04      7053924.99      2814625.00      7054025.00
      2814125.02      7053925.00
#Sta/Elev= 30
  4538.0  451.81  4611.0  449.61  4761.2  442.58  4773.9  442.26  4839.0  440.81
  4876.1  441.19  4926.0  440.65  4968.3  441.37  4988.8  441.42  4996.5  440.85
  5001.6  440.85  5009.2  441.48  5026.8  441.82  5070.4  440.83  5120.0  440.50
  5138.8  440.31  5139.3  439.51  5144.3  439.51  5144.8  440.31  5192.8  440.89
  5235.3  442.07  5254.1  442.58  5315.2  444.74  5366.2  447.64  5386.5  449.34
  5427.3  451.42  5457.9  453.70  5468.1  453.37  5478.3  454.06  5508.9  454.94
#Mann=7,-1,0
  4538.0    0.05       0  4773.9    0.16       0  5026.8    0.12       0
  5120.0    0.16       0  5138.8    0.07       0  5144.8    0.16       0
  5235.3    0.05       0
Bank Sta=4761.2,5254.1
Exp/Cntr=0.3,0.1

Type RM Length L Ch R = 1,2128,349,349,349
BEGIN DESCRIPTION:
UNT 087 in LFCCL Watershed 5.0
END DESCRIPTION:
XS GIS Cut Line= 3
      2815075.01      7053825.00      2814725.00      7053675.00
      2814325.00      7053375.00
#Sta/Elev= 30
  4624.0  451.44  4678.4  449.44  4743.7  444.81  4834.5  441.73  4896.0  440.52
  4914.1  440.65  4918.8  440.14  4992.7  439.40  4993.2  438.60  4998.2  438.60
  4998.7  439.40  5032.9  439.83  5047.5  439.48  5068.3  439.91  5097.5  439.70
  5155.1  441.00  5191.0  441.73  5204.8  442.34  5212.1  443.13  5247.5  443.94
  5291.3  445.70  5297.5  446.65  5312.1  446.78  5318.3  447.44  5347.5  448.75
  5376.7  449.55  5382.9  450.51  5412.1  450.89  5491.3  454.78  5504.8  454.94
#Mann=5,-1,0
  4624.0    0.05       0  4918.8    0.16       0  4992.7    0.07       0
  4998.7    0.16       0  5155.1    0.05       0
Bank Sta=4834.5,5191
Exp/Cntr=0.3,0.1

Type RM Length L Ch R = 1,1779,204,204,204
BEGIN DESCRIPTION:
UNT 087 in LFCCL Watershed 4.0
END DESCRIPTION:
XS GIS Cut Line= 3
      2815374.96      7053574.98      2814875.00      7053375.00
      2814525.03      7053325.00
#Sta/Elev= 30
  4483.9  455.27  4498.7  455.13  4522.9  453.91  4570.0  452.23  4591.6  451.01
  4623.9  449.87  4708.7  445.69  4720.8  444.85  4753.1  443.66  4767.9  442.82
  4842.5  440.95  4910.6  439.59  4936.2  438.93  4977.9  438.70  4990.1  438.94
  5010.0  438.61  5010.5  437.81  5015.5  437.81  5016.0  438.61  5062.8  438.93
  5072.9  438.74  5119.6  439.38  5133.5  440.14  5165.4  440.95  5173.9  441.50
  5254.7  444.62  5274.9  446.12  5315.3  448.42  5325.4  449.38  5375.9  451.38
#Mann=5,-1,0
  4483.9    0.05       0  4910.6    0.16       0  5010.0    0.07       0
  5016.0    0.16       0  5119.6    0.05       0
Bank Sta=4842.5,5165.4
Exp/Cntr=0.3,0.1

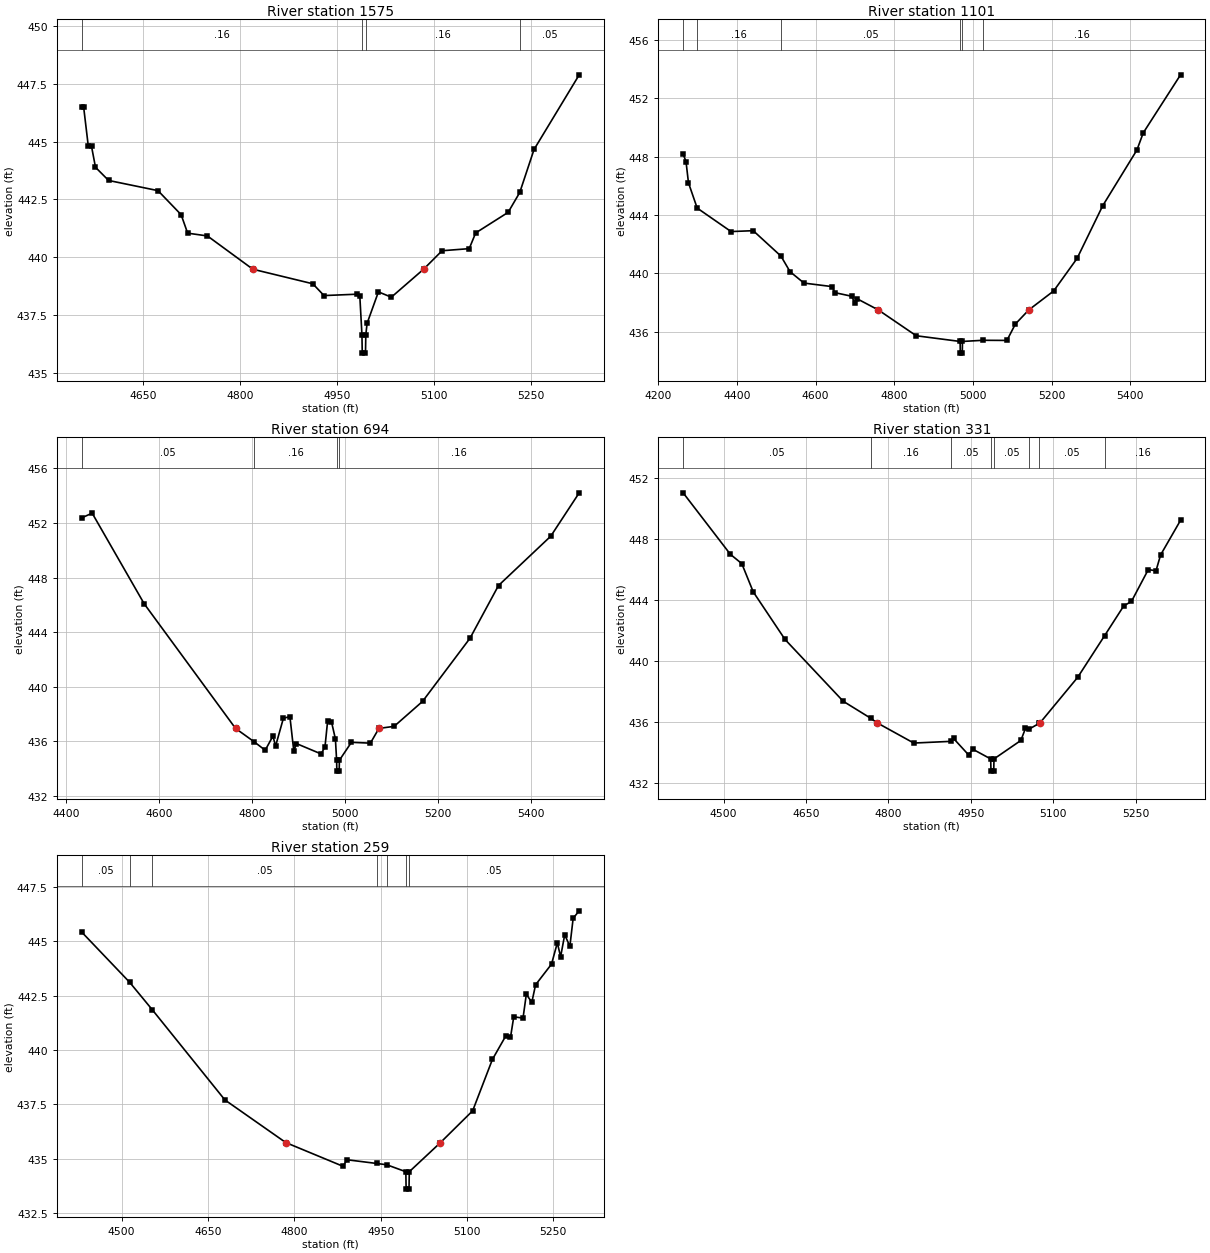
Type RM Length L Ch R = 1,1575,474,474,474
BEGIN DESCRIPTION:
XS3609A
END DESCRIPTION:
XS GIS Cut Line= 3
      2815345.77      7053262.74      2814922.14      7053179.40
      2814585.33      7053207.18
#Sta/Elev= 30
  4555.5  446.49  4558.4  446.49  4565.5  444.82  4570.6  444.79  4576.7  443.89
  4597.0  443.32  4673.4  442.88  4709.2  441.84  4719.3  441.04  4749.9  440.92
  4820.2  439.48  4913.0  438.85  4930.3  438.34  4981.7  438.40  4985.7  438.33
  4989.0  436.65  4989.5  435.85  4994.5  435.85  4995.0  436.65  4997.0  437.14
  5014.5  438.50  5034.5  438.27  5084.4  439.48  5113.0  440.28  5155.0  440.37
  5165.0  441.05  5215.2  441.94  5233.2  442.80  5255.3  444.66  5325.2  447.89
#Mann=4,-1,0
  4555.5    0.16       0  4989.0    0.07       0  4995.0    0.16       0
  5233.2    0.05       0
Bank Sta=4820.2,5084.4
Exp/Cntr=0.3,0.1

Type RM Length L Ch R = 1,1101,407,407,407
BEGIN DESCRIPTION:
UNT 087 in LFCCL Watershed 3.0
END DESCRIPTION:
XS GIS Cut Line= 3
      2815425.03      7053175.03      2814825.00      7052725.00
      2814375.02      7052974.99
#Sta/Elev= 30
  4263.2  448.18  4270.5  447.67  4276.8  446.21  4298.9  444.48  4385.1  442.87
  4441.4  442.93  4511.9  441.19  4535.1  440.12  4570.5  439.34  4641.4  439.10
  4649.7  438.68  4691.4  438.44  4699.7  437.99  4706.0  438.26  4759.5  437.50
  4856.0  435.73  4967.5  435.34  4968.0  434.54  4973.0  434.54  4973.5  435.34
  5025.8  435.42  5086.5  435.41  5108.2  436.54  5142.1  437.50  5205.4  438.80
  5264.9  441.03  5330.1  444.64  5417.1  448.46  5433.1  449.63  5528.0  453.61
#Mann=6,-1,0
  4263.2    0.05       0  4298.9    0.16       0  4511.9    0.05       0
  4967.5    0.03       0  4973.5    0.05       0  5025.8    0.16       0
Bank Sta=4759.5,5142.1
Exp/Cntr=0.3,0.1

Type RM Length L Ch R = 1,694,363,363,363
BEGIN DESCRIPTION:
UNT 087 in LFCCL Watershed 2.0
END DESCRIPTION:
XS GIS Cut Line= 3
      2815324.97      7052624.98      2814825.00      7052375.00
      2814324.98      7052275.00
#Sta/Elev= 30
  4433.9  452.38  4456.2  452.72  4568.0  446.08  4764.3  436.95  4804.3  435.97
  4828.0  435.35  4844.7  436.39  4850.3  435.65  4867.1  437.69  4881.1  437.82
  4889.5  435.29  4895.1  435.84  4948.2  435.08  4956.5  435.60  4962.1  437.47
  4970.5  437.43  4978.9  436.18  4981.5  434.62  4982.0  433.82  4987.0  433.82
  4987.5  434.62  5013.3  435.93  5054.1  435.87  5072.4  436.95  5105.1  437.10
  5166.2  438.93  5268.2  443.56  5329.4  447.42  5441.6  451.03  5502.8  454.21
#Mann=4,-1,0
  4433.9    0.05       0  4804.3    0.16       0  4981.5    0.07       0
  4987.5    0.16       0
Bank Sta=4764.3,5072.4
Exp/Cntr=0.3,0.1

Type RM Length L Ch R = 1,331,72,72,72
BEGIN DESCRIPTION:
UNT 087 in LFCCL Watershed 1.0
END DESCRIPTION:
XS GIS Cut Line= 3
      2815325.02      7052575.03      2814975.00      7052125.00
      2814675.03      7051975.02
#Sta/Elev= 30
  4426.4  451.02  4512.4  446.99  4533.2  446.38  4554.0  444.53  4611.9  441.41
  4717.8  437.36  4767.7  436.25  4778.8  435.96  4846.3  434.62  4913.2  434.73
  4918.7  434.92  4945.9  433.85  4954.0  434.21  4986.3  433.58  4986.8  432.78
  4991.8  432.78  4992.3  433.58  5041.2  434.79  5049.6  435.58  5055.5  435.52
  5074.6  435.91  5076.5  435.96  5144.7  438.93  5193.7  441.66  5228.5  443.61
  5242.5  443.90  5273.2  445.99  5287.2  445.91  5295.6  446.95  5331.9  449.22
#Mann=8,-1,0
  4426.4    0.05       0  4767.7    0.16       0  4913.2    0.05       0
  4986.3    0.04       0  4992.3    0.05       0  5055.5    0.16       0
  5074.6    0.05       0  5193.7    0.16       0
Bank Sta=4778.8,5076.5
Exp/Cntr=0.3,0.1

Type RM Length L Ch R = 1,259,0,0,0
BEGIN DESCRIPTION:
XS3610A
END DESCRIPTION:
XS GIS Cut Line= 3
      2815399.61      7052452.00      2815003.74      7052063.08
      2814732.92      7051913.78
#Sta/Elev= 30
  4430.7  445.42  4513.7  443.12  4553.3  441.85  4679.3  437.71  4785.1  435.75
  4884.5  434.66  4891.5  434.96  4942.8  434.79  4960.5  434.73  4993.7  434.41
  4994.2  433.61  4999.2  433.61  4999.7  434.41  5053.9  435.75  5109.8  437.21
  5144.1  439.57  5166.9  440.63  5175.5  440.58  5181.2  441.53  5197.3  441.47
  5203.0  442.56  5212.6  442.20  5219.1  443.00  5246.8  443.95  5256.9  444.93
  5262.6  444.29  5269.7  445.30  5278.7  444.77  5284.4  446.06  5294.9  446.40
#Mann=7,-1,0
  4430.7    0.05       0  4513.7    0.12       0  4553.3    0.05       0
  4942.8    0.12       0  4960.5    0.05       0  4993.7    0.04       0
  4999.7    0.05       0
Bank Sta=4785.1,5053.9
Exp/Cntr=0.3,0.1

Chan Stop Cuts=-1