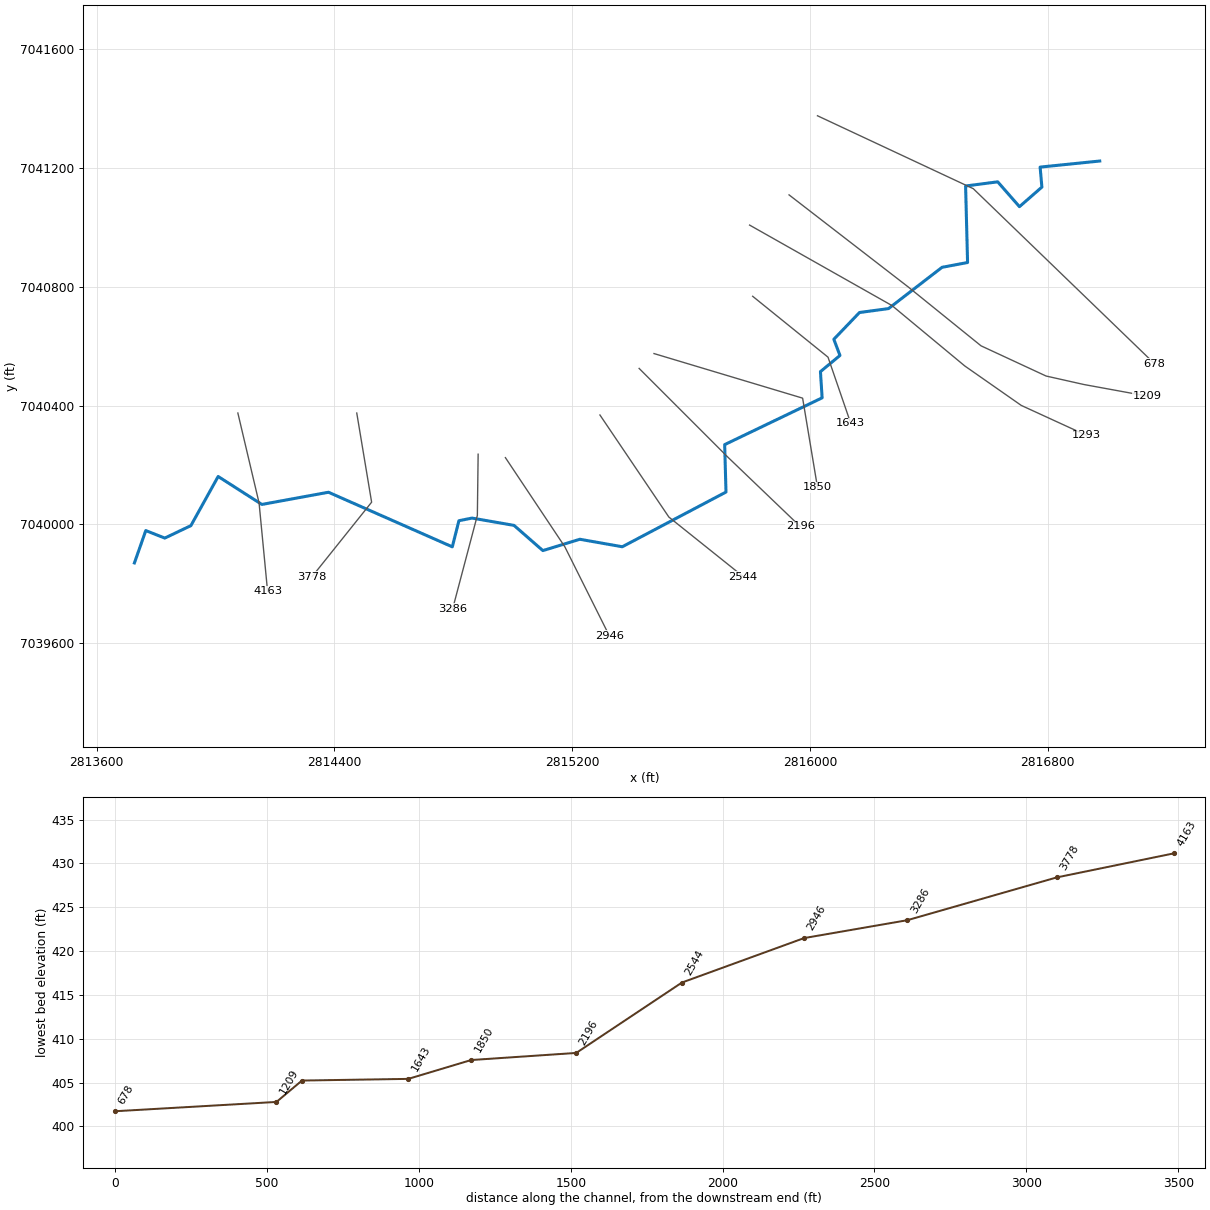
--- UNT 088 in LFCCL Watershed.prj (project) ---

Proj Title=UNT 088 in LFCCL Watershed Base Level Engineering
Current Plan=p01
Default Exp/Contr=0.3,0.1
English Units
Geom File=g01
Flow File=f01
Plan File=p01
BEGIN DESCRIPTION:
UNT 088 in LFCCL Watershed
END DESCRIPTION:

--- UNT 088 in LFCCL Watershed.p01 (plan) ---

Plan Title=Multiple Run
Short Identifier=Multiple
Geom File=g01
Flow File=f01
Subcritical Flow
K Sum by GR= 0
Std Step Tol= 0.01
Critical Tol= 0.01
Num of Std Step Trials= 20
Max Error Tol= 0.3
Flow Tol Ratio= 0.001
Split Flow NTrial= 30
Split Flow Tol= 0.02
Split Flow Ratio= 0.02
Log Output Level= 0
Friction Slope Method= 1
Unsteady Friction Slope Method= 2
Unsteady Bridges Friction Slope Method= 1
Parabolic Critical Depth
Global Vel Dist=  1 , 1 , 1
Global Log Level= 0
CheckData=True
Encroach Param= -1, 0, 0, 0
BEGIN DESCRIPTION:
Multiple Run
END DESCRIPTION:

--- UNT 088 in LFCCL Watershed.f01 (steady flow) ---

Flow Title=Multiple
Number of Profiles=7
Profile Names=10-year,25-year,50-year,1pct_min,100-year,1pct_plu,500-year
River Rch & RM= UNT 088 in LFCCL,Reach-1,4163
     311     400     470     275     548    1094     747
Boundary for River Rch & Prof#=UNT 088 in LFCCL,Reach-1,1
Up Type=0
Dn Type=3
Dn Slope=0.005
Boundary for River Rch & Prof#=UNT 088 in LFCCL,Reach-1,2
Up Type=0
Dn Type=3
Dn Slope=0.005
Boundary for River Rch & Prof#=UNT 088 in LFCCL,Reach-1,3
Up Type=0
Dn Type=3
Dn Slope=0.005
Boundary for River Rch & Prof#=UNT 088 in LFCCL,Reach-1,4
Up Type=0
Dn Type=3
Dn Slope=0.005
Boundary for River Rch & Prof#=UNT 088 in LFCCL,Reach-1,5
Up Type=0
Dn Type=3
Dn Slope=0.005
Boundary for River Rch & Prof#=UNT 088 in LFCCL,Reach-1,6
Up Type=0
Dn Type=3
Dn Slope=0.005
Boundary for River Rch & Prof#=UNT 088 in LFCCL,Reach-1,7
Up Type=0
Dn Type=3
Dn Slope=0.005

--- UNT 088 in LFCCL Watershed.g01 (geometry) ---

Geom Title=Existing Conditions

River Reach=UNT 088 in LFCCL,Reach-1
Reach XY= 30
      2813726.99      7039870.63      2813765.23      7039979.53
      2813829.19      7039954.25      2813917.00      7039996.13
      2814008.74      7040161.48      2814155.75      7040067.43
      2814379.87      7040108.47      2814796.46      7039924.78
      2814818.66      7040012.65      2814862.86      7040021.53
      2815004.09      7039996.94      2815101.05      7039912.19
      2815225.57      7039950.27      2815368.36      7039925.08
      2815717.19      7040109.09      2815712.74      7040268.68
      2816040.58      7040426.03      2816034.95      7040514.23
      2816100.63      7040568.65      2816079.99      7040623.07
      2816166.31      7040713.14      2816263.89      7040726.27
      2816444.03      7040865.14      2816529.92      7040881.32
      2816523.26      7041138.72      2816631.25      7041152.77
      2816704.48      7041069.19      2816779.93      7041135.02
      2816774.01      7041202.33      2816974.49      7041222.74

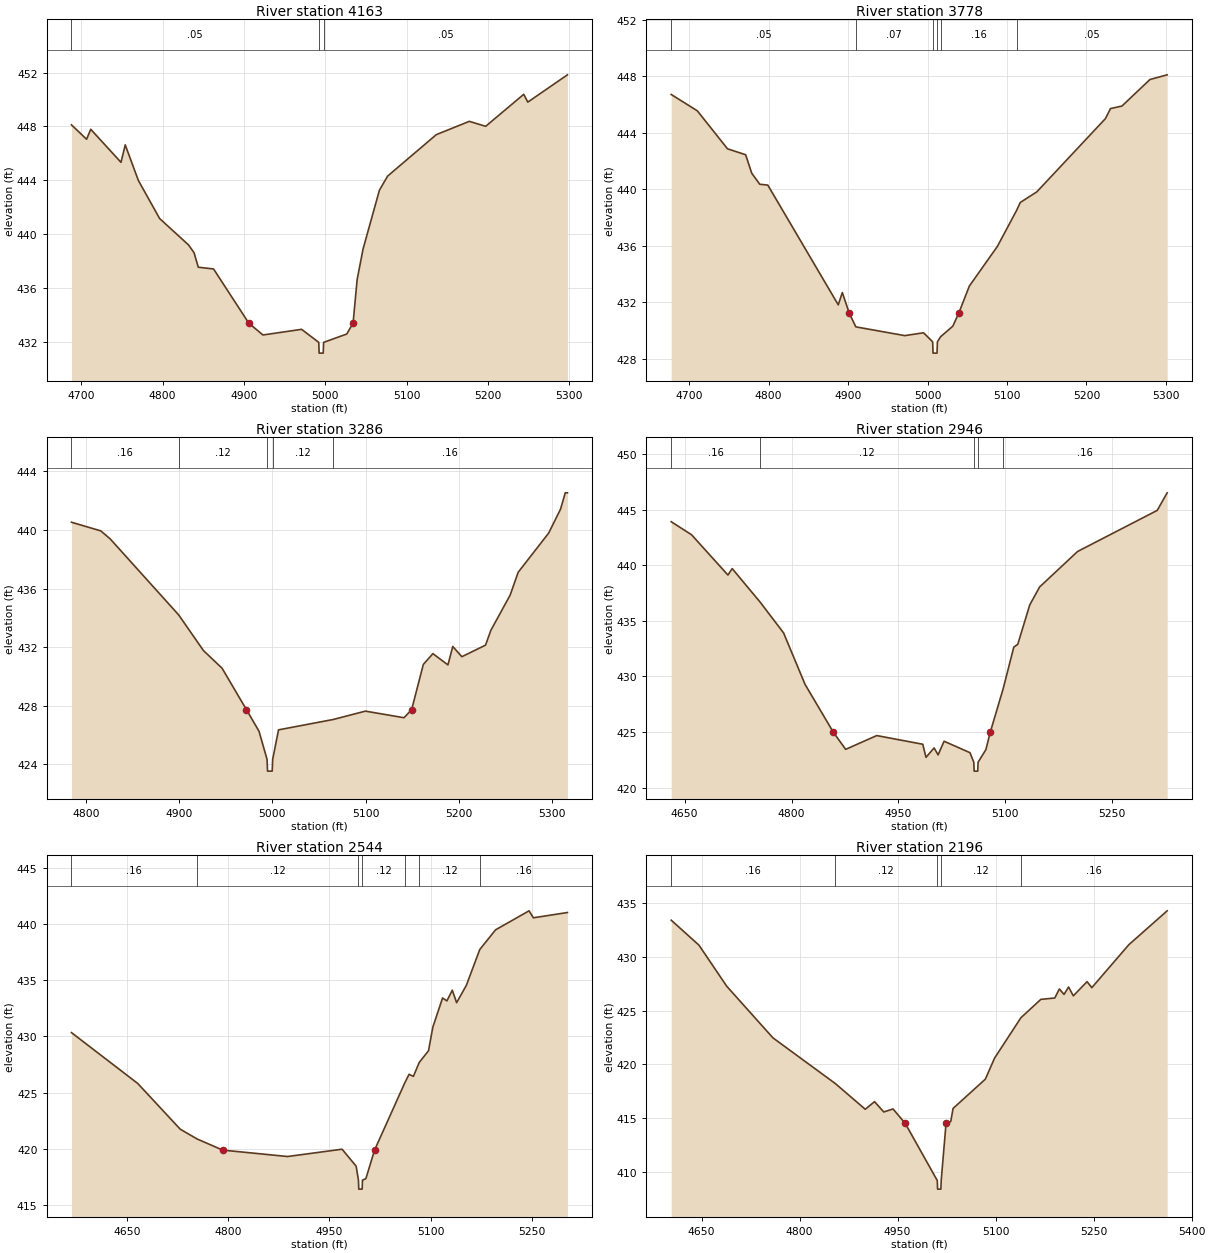
Type RM Length L Ch R = 1,4163,385,385,385
BEGIN DESCRIPTION:
UNT 088 in LFCCL Watershed 10.0
END DESCRIPTION:
XS GIS Cut Line= 3
      2814075.00      7040375.01      2814146.37      7040072.39
      2814175.00      7039774.99
#Sta/Elev= 30
  4688.0  448.12  4706.6  447.05  4711.7  447.79  4748.9  445.33  4754.1  446.63
  4770.2  443.99  4796.4  441.15  4831.9  439.19  4838.7  438.61  4843.9  437.53
  4862.7  437.40  4906.0  433.37  4923.4  432.49  4970.9  432.91  4992.0  431.94
  4992.5  431.14  4997.5  431.14  4998.0  431.94  5026.4  432.56  5034.2  433.37
  5039.2  436.61  5046.5  438.89  5066.6  443.26  5076.7  444.31  5136.5  447.39
  5177.1  448.38  5197.2  448.01  5244.0  450.39  5249.0  449.81  5297.7  451.84
#Mann=3,-1,0
  4688.0    0.05       0  4992.0    0.03       0  4998.0    0.05       0
Bank Sta=4906,5034.2
Exp/Cntr=0.3,0.1

Type RM Length L Ch R = 1,3778,492,492,492
BEGIN DESCRIPTION:
UNT 088 in LFCCL Watershed 9.0
END DESCRIPTION:
XS GIS Cut Line= 3
      2814475.00      7040374.97      2814525.00      7040075.00
      2814324.98      7039824.97
#Sta/Elev= 30
  4677.3  446.72  4710.2  445.56  4748.2  442.87  4771.0  442.45  4778.7  441.14
  4788.8  440.36  4798.9  440.30  4887.6  431.82  4892.7  432.69  4901.5  431.22
  4909.7  430.26  4971.3  429.64  4995.0  429.84  5006.4  429.20  5006.9  428.40
  5011.9  428.40  5012.4  429.20  5016.4  429.56  5031.8  430.31  5039.2  431.22
  5052.6  433.15  5087.9  435.96  5112.1  438.51  5116.7  439.07  5137.5  439.82
  5223.9  445.01  5230.3  445.72  5244.7  445.90  5280.0  447.78  5301.6  448.11
#Mann=6,-1,0
  4677.3    0.05       0  4909.7    0.07       0  5006.4    0.07       0
  5012.4    0.07       0  5016.4    0.16       0  5112.1    0.05       0
Bank Sta=4901.5,5039.2
Exp/Cntr=0.3,0.1

Type RM Length L Ch R = 1,3286,340,340,340
BEGIN DESCRIPTION:
XS3611A
END DESCRIPTION:
XS GIS Cut Line= 3
      2814883.35      7040236.44      2814880.74      7040030.73
      2814797.40      7039715.59
#Sta/Elev= 30
  4784.6  440.53  4816.0  439.94  4826.0  439.40  4899.5  434.20  4926.1  431.76
  4946.1  430.55  4972.2  427.72  4985.7  426.24  4994.3  424.32  4994.8  423.52
  4999.8  423.52  5000.3  424.32  5006.6  426.34  5065.3  427.05  5099.7  427.62
  5141.1  427.17  5149.3  427.72  5161.8  430.81  5172.1  431.55  5188.2  430.78
  5193.4  432.04  5203.1  431.34  5228.5  432.13  5234.2  433.14  5254.9  435.55
  5263.5  437.11  5296.2  439.79  5308.9  441.42  5314.0  442.54  5316.3  442.54
#Mann=5,-1,0
  4784.6    0.16       0  4899.5    0.12       0  4994.3    0.07       0
  5000.3    0.12       0  5065.3    0.16       0
Bank Sta=4972.2,5149.3
Exp/Cntr=0.3,0.1

Type RM Length L Ch R = 1,2946,402,402,402
BEGIN DESCRIPTION:
UNT 088 in LFCCL Watershed 7.0
END DESCRIPTION:
XS GIS Cut Line= 3
      2814975.02      7040224.98      2815175.00      7039925.00
      2815324.98      7039625.03
#Sta/Elev= 30
  4631.1  443.93  4659.6  442.76  4710.7  439.13  4716.7  439.71  4755.8  436.70
  4788.8  433.92  4818.9  429.29  4858.8  424.96  4875.9  423.44  4919.5  424.68
  4984.1  423.90  4988.6  422.72  5000.0  423.57  5005.6  422.94  5014.0  424.17
  5050.3  423.14  5055.7  422.28  5056.2  421.48  5061.2  421.48  5061.7  422.28
  5072.7  423.42  5078.7  424.96  5097.0  428.92  5111.8  432.64  5117.4  432.90
  5134.2  436.44  5148.1  438.06  5201.3  441.25  5313.1  444.95  5327.0  446.53
#Mann=5,-1,0
  4631.1    0.16       0  4755.8    0.12       0  5055.7    0.07       0
  5061.7    0.12       0  5097.0    0.16       0
Bank Sta=4858.8,5078.7
Exp/Cntr=0.3,0.1

Type RM Length L Ch R = 1,2544,348,348,348
BEGIN DESCRIPTION:
UNT 088 in LFCCL Watershed 6.0
END DESCRIPTION:
XS GIS Cut Line= 3
      2815293.09      7040368.37      2815525.00      7040025.00
      2815775.00      7039825.00
#Sta/Elev= 30
  4568.1  430.33  4666.2  425.81  4729.2  421.74  4754.2  420.87  4792.1  419.88
  4888.1  419.31  4968.9  419.96  4989.7  418.45  4993.1  417.21  4993.6  416.41
  4998.6  416.41  4999.1  417.21  5004.1  417.34  5017.0  419.88  5061.9  425.88
  5068.1  426.62  5074.5  426.44  5083.2  427.68  5096.9  428.72  5103.3  430.82
  5117.7  433.41  5124.1  433.15  5132.1  434.10  5138.5  432.99  5152.9  434.53
  5172.8  437.72  5196.2  439.47  5245.8  441.16  5252.2  440.54  5302.6  441.01
#Mann=7,-1,0
  4568.1    0.16       0  4754.2    0.12       0  4993.1    0.07       0
  4999.1    0.12       0  5061.9    0.16       0  5083.2    0.12       0
  5172.8    0.16       0
Bank Sta=4792.1,5017
Exp/Cntr=0.3,0.1

Type RM Length L Ch R = 1,2196,346,346,346
BEGIN DESCRIPTION:
UNT 088 in LFCCL Watershed 5.0
END DESCRIPTION:
XS GIS Cut Line= 3
      2815424.97      7040525.03      2815725.00      7040225.00
      2815966.65      7039993.43
#Sta/Elev= 30
  4603.5  433.44  4646.0  431.11  4688.4  427.29  4759.1  422.48  4854.6  418.22
  4900.5  415.82  4914.7  416.53  4928.8  415.57  4943.0  415.85  4961.7  414.50
  5010.7  409.18  5011.2  408.38  5016.2  408.38  5016.7  409.18  5024.1  414.50
  5031.3  414.68  5034.9  415.90  5084.3  418.63  5098.4  420.59  5138.7  424.35
  5169.2  426.06  5190.6  426.19  5197.5  427.03  5204.7  426.52  5211.6  427.21
  5218.9  426.39  5239.9  427.71  5247.2  427.15  5303.8  431.15  5362.5  434.31
#Mann=5,-1,0
  4603.5    0.16       0  4854.6    0.12       0  5010.7    0.07       0
  5016.7    0.12       0  5138.7    0.16       0
Bank Sta=4961.7,5024.1
Exp/Cntr=0.3,0.1

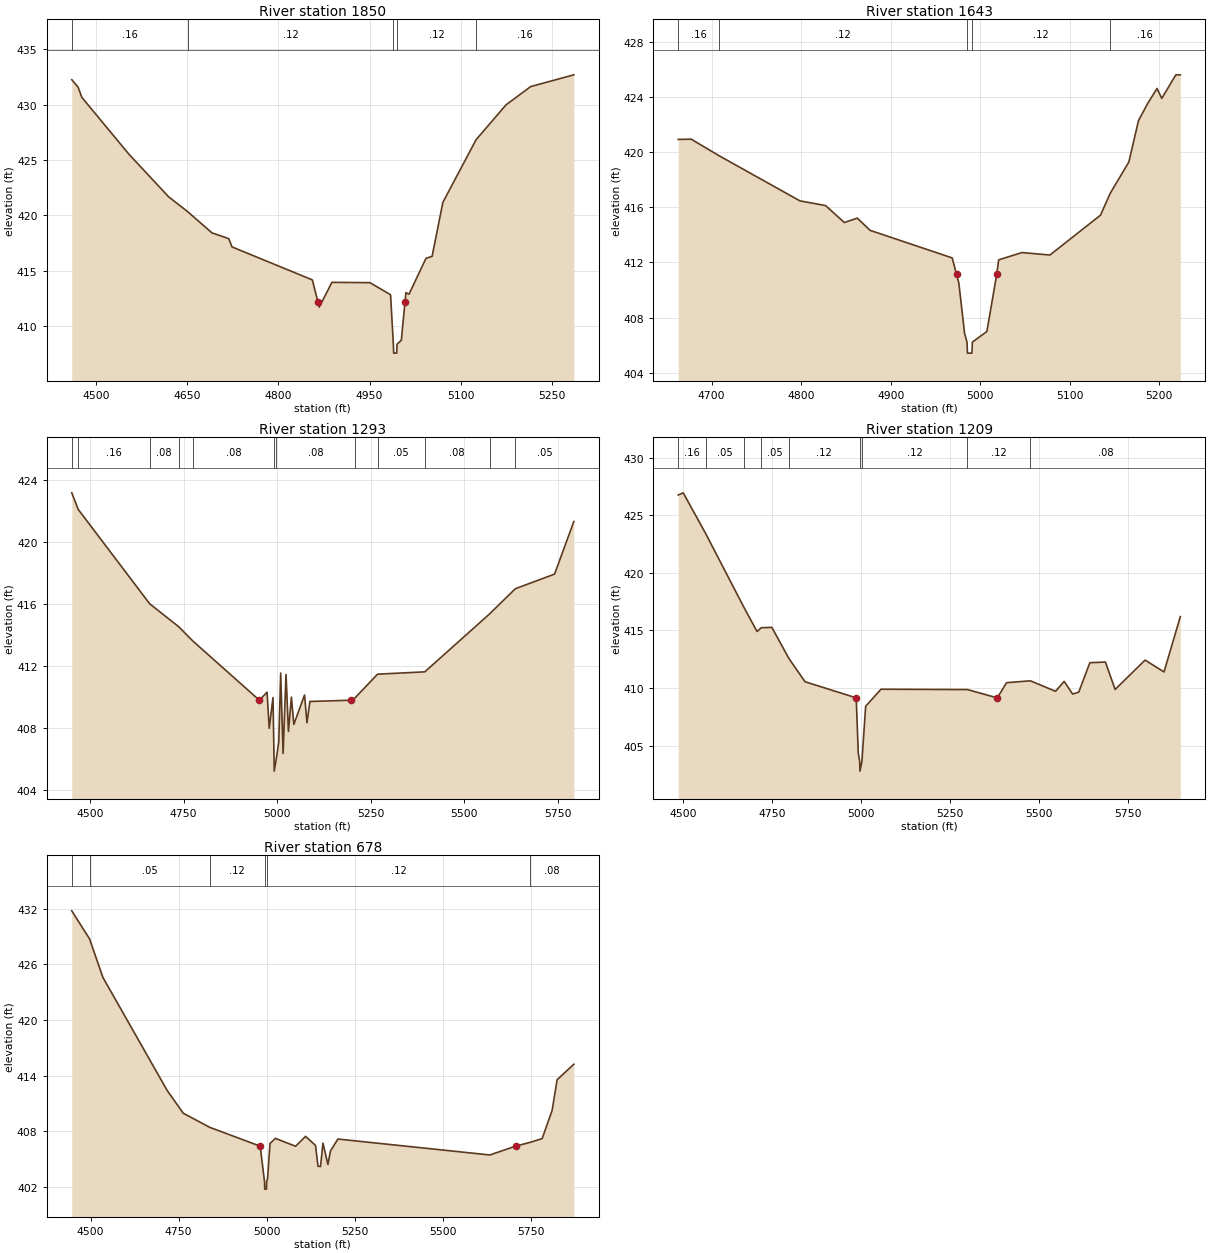
Type RM Length L Ch R = 1,1850,207,207,207
BEGIN DESCRIPTION:
UNT 088 in LFCCL Watershed 4.0
END DESCRIPTION:
XS GIS Cut Line= 3
      2815475.00      7040575.00      2815975.00      7040425.00
      2816025.01      7040124.96
#Sta/Elev= 30
  4460.0  432.25  4470.4  431.58  4476.5  430.66  4554.0  425.53  4619.2  421.69
  4650.7  420.34  4690.6  418.43  4718.4  417.90  4723.6  417.16  4855.9  414.18
  4865.3  412.14  4867.2  411.72  4888.1  413.96  4950.7  413.93  4984.6  412.84
  4989.2  408.37  4989.7  407.57  4994.7  407.57  4995.2  408.37  5002.3  408.73
  5008.3  412.14  5009.9  413.03  5015.0  412.89  5042.8  416.12  5053.0  416.31
  5070.7  421.18  5125.3  426.83  5174.6  429.98  5215.2  431.63  5286.2  432.69
#Mann=5,-1,0
  4460.0    0.16       0  4650.7    0.12       0  4989.2    0.07       0
  4995.2    0.12       0  5125.3    0.16       0
Bank Sta=4865.3,5008.3
Exp/Cntr=0.3,0.1

Type RM Length L Ch R = 1,1643,350,350,350
BEGIN DESCRIPTION:
XS3612A
END DESCRIPTION:
XS GIS Cut Line= 3
      2815806.95      7040767.71      2816060.43      7040562.84
      2816136.82      7040340.62
#Sta/Elev= 30
  4662.7  420.93  4677.2  420.95  4708.0  419.76  4798.7  416.47  4827.3  416.13
  4848.3  414.90  4862.7  415.22  4877.1  414.33  4968.8  412.33  4973.6  411.13
  4976.2  410.50  4982.6  406.85  4985.3  406.22  4985.8  405.42  4990.8  405.42
  4991.3  406.22  5007.5  406.99  5018.5  411.13  5020.7  412.19  5046.7  412.72
  5077.9  412.54  5134.4  415.43  5145.3  417.02  5166.1  419.29  5176.9  422.30
  5187.3  423.56  5197.6  424.63  5202.9  423.91  5218.6  425.62  5223.6  425.62
#Mann=5,-1,0
  4662.7    0.16       0  4708.0    0.12       0  4985.3    0.07       0
  4991.3    0.12       0  5145.3    0.16       0
Bank Sta=4973.6,5018.5
Exp/Cntr=0.3,0.1

Type RM Length L Ch R = 1,1293,84,84,84
BEGIN DESCRIPTION:
XS3614A
END DESCRIPTION:
XS GIS Cut Line= 5
      2815796.58      7041007.27      2816275.71      7040736.46
      2816520.50      7040533.33      2816710.60      7040400.52
      2816929.86      7040299.92
#Sta/Elev= 30
  4451.1  423.17  4468.4  422.10  4659.2  416.02  4736.8  414.54  4774.5  413.62
  4952.5  409.80  4972.9  410.32  4978.7  407.99  4988.8  409.97  4991.6  406.03
  4992.1  405.23  4997.6  406.03  5004.3  407.11  5009.3  411.55  5015.8  406.37
  5023.6  411.46  5030.1  407.79  5038.0  410.00  5044.5  408.24  5073.1  410.14
  5079.6  408.35  5087.4  409.72  5195.9  409.80  5207.2  409.93  5268.2  411.48
  5394.4  411.63  5568.2  415.38  5636.5  416.99  5741.2  417.93  5792.7  421.32
#Mann=12,-1,0
  4451.1    0.08       0  4468.4    0.16       0  4659.2    0.08       0
  4736.8    0.16       0  4774.5    0.08       0  4991.6    0.07       0
  4997.6    0.08       0  5207.2    0.16       0  5268.2    0.05       0
  5394.4    0.08       0  5568.2    0.16       0  5636.5    0.05       0
Bank Sta=4952.5,5195.9
Exp/Cntr=0.3,0.1

Type RM Length L Ch R = 1,1209,531,531,531
BEGIN DESCRIPTION:
XS3613A
END DESCRIPTION:
XS GIS Cut Line= 6
      2815929.33      7041108.87      2816330.40      7040798.96
      2816575.19      7040601.04      2816793.94      7040499.48
      2816921.54      7040470.83      2817135.09      7040431.77
#Sta/Elev= 30
  4486.6  426.76  4500.6  426.95  4564.8  423.35  4670.3  417.06  4708.0  414.91
  4720.1  415.24  4749.6  415.27  4797.8  412.56  4842.9  410.55  4986.7  409.15
  4992.4  404.38  4996.6  403.59  4997.1  402.79  5002.6  403.59  5013.2  408.42
  5056.3  409.90  5299.3  409.87  5383.0  409.15  5409.2  410.47  5476.2  410.63
  5546.6  409.72  5571.0  410.58  5594.7  409.48  5612.0  409.65  5643.1  412.20
  5686.8  412.26  5714.2  409.88  5798.3  412.43  5851.5  411.40  5897.3  416.20
#Mann=9,-1,0
  4486.6    0.16       0  4564.8    0.05       0  4670.3    0.16       0
  4720.1    0.05       0  4797.8    0.12       0  4996.6    0.07       0
  5002.6    0.12       0  5299.3    0.12       0  5476.2    0.08       0
Bank Sta=4986.7,5383
Exp/Cntr=0.3,0.1

Type RM Length L Ch R = 1,678,0,0,0
BEGIN DESCRIPTION:
UNT 088 in LFCCL Watershed 1.0
END DESCRIPTION:
XS GIS Cut Line= 3
      2816024.97      7041375.01      2816549.15      7041129.69
      2817158.50      7040541.16
#Sta/Elev= 30
  4446.6  431.79  4497.1  428.76  4535.0  424.60  4717.5  412.39  4763.2  409.93
  4838.7  408.40  4981.7  406.37  4994.1  402.53  4994.6  401.73  4999.6  401.73
  5000.1  402.53  5002.6  402.85  5009.7  406.66  5025.0  407.21  5082.3  406.36
  5110.6  407.43  5138.9  406.45  5145.9  404.21  5153.0  404.17  5160.0  406.70
  5174.1  404.39  5181.3  405.85  5202.4  407.14  5633.9  405.42  5707.0  406.37
  5749.2  406.79  5782.5  407.19  5810.8  410.23  5825.0  413.55  5872.5  415.22
#Mann=6,-1,0
  4446.6    0.16       0  4497.1    0.05       0  4838.7    0.12       0
  4994.1    0.07       0  5000.1    0.12       0  5749.2    0.08       0
Bank Sta=4981.7,5707
Exp/Cntr=0.3,0.1

Chan Stop Cuts=-1