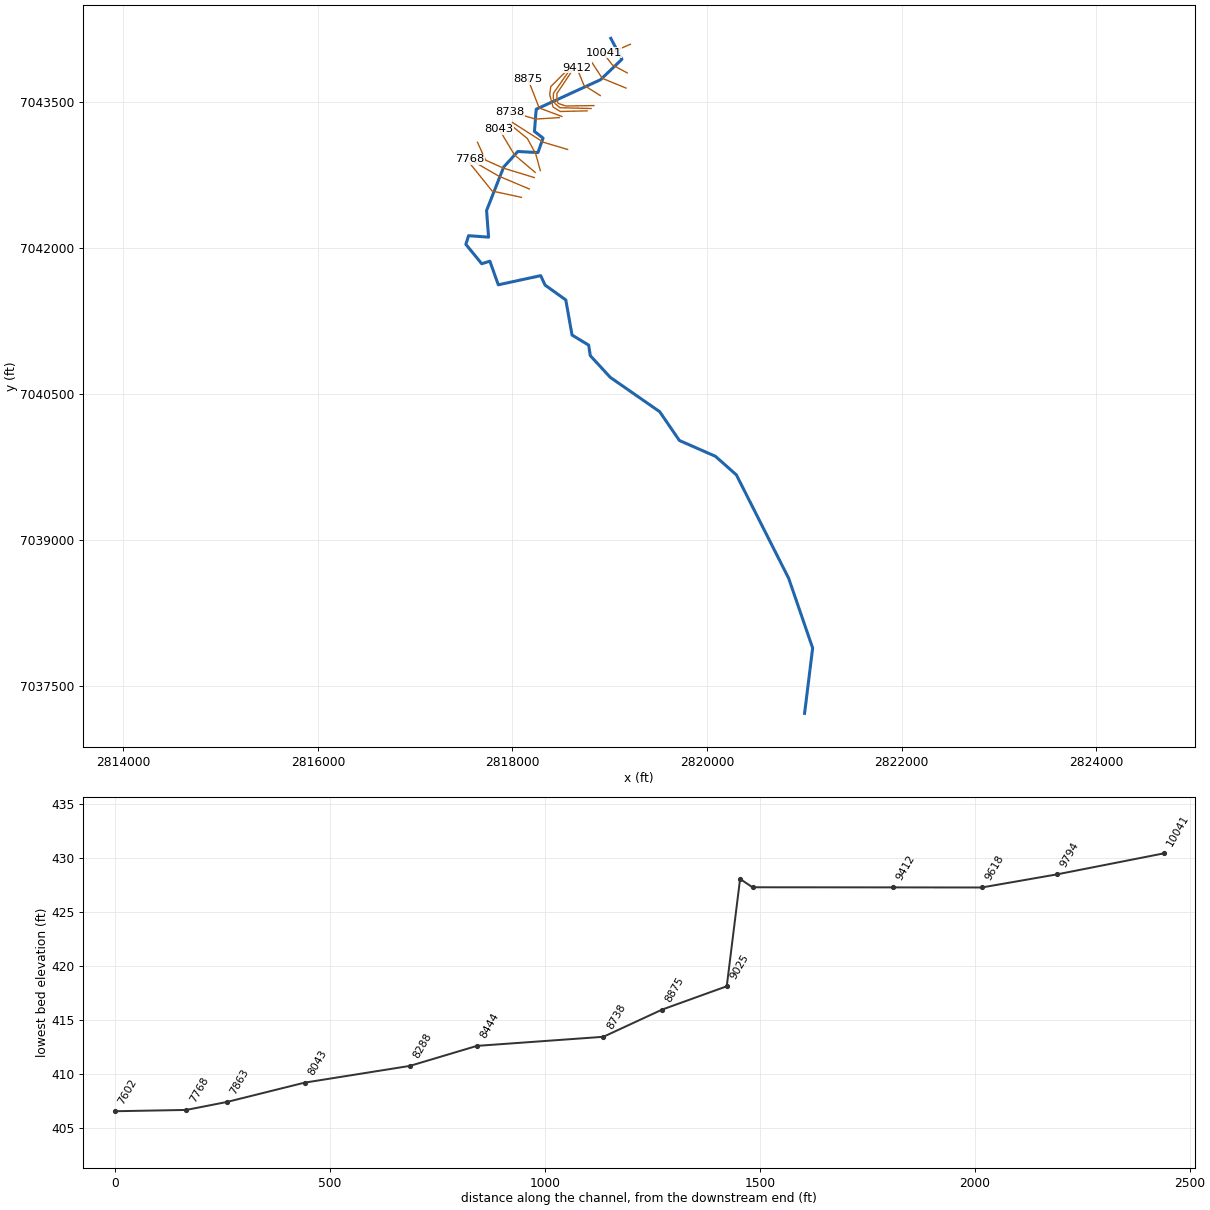
--- UNT 089 in LFCCL Watershed.prj (project) ---

Proj Title=UNT 089 in LFCCL Watershed Base Level Engineering
Current Plan=p01
Default Exp/Contr=0.3,0.1
English Units
Geom File=g01
Flow File=f01
Plan File=p01
BEGIN DESCRIPTION:
UNT 089 in LFCCL Watershed
END DESCRIPTION:

--- UNT 089 in LFCCL Watershed.p01 (plan) ---

Plan Title=Multiple Run
Short Identifier=Multiple
Geom File=g01
Flow File=f01
Subcritical Flow
K Sum by GR= 0
Std Step Tol= 0.01
Critical Tol= 0.01
Num of Std Step Trials= 20
Max Error Tol= 0.3
Flow Tol Ratio= 0.001
Split Flow NTrial= 30
Split Flow Tol= 0.02
Split Flow Ratio= 0.02
Log Output Level= 0
Friction Slope Method= 1
Unsteady Friction Slope Method= 2
Unsteady Bridges Friction Slope Method= 1
Parabolic Critical Depth
Global Vel Dist=  1 , 1 , 1
Global Log Level= 0
CheckData=True
Encroach Param= -1, 0, 0, 0
BEGIN DESCRIPTION:
Multiple Run
END DESCRIPTION:

--- UNT 089 in LFCCL Watershed.f01 (steady flow) ---

Flow Title=Multiple
Number of Profiles=7
Profile Names=10-year,25-year,50-year,1pct_min,100-year,1pct_plu,500-year
River Rch & RM= UNT 089 in LFCCL,Reach-1,10041
     201     250     288     166     331     660     434
Boundary for River Rch & Prof#=UNT 089 in LFCCL,Reach-1,1
Up Type=0
Dn Type=3
Dn Slope=0.005
Boundary for River Rch & Prof#=UNT 089 in LFCCL,Reach-1,2
Up Type=0
Dn Type=3
Dn Slope=0.005
Boundary for River Rch & Prof#=UNT 089 in LFCCL,Reach-1,3
Up Type=0
Dn Type=3
Dn Slope=0.005
Boundary for River Rch & Prof#=UNT 089 in LFCCL,Reach-1,4
Up Type=0
Dn Type=3
Dn Slope=0.005
Boundary for River Rch & Prof#=UNT 089 in LFCCL,Reach-1,5
Up Type=0
Dn Type=3
Dn Slope=0.005
Boundary for River Rch & Prof#=UNT 089 in LFCCL,Reach-1,6
Up Type=0
Dn Type=3
Dn Slope=0.005
Boundary for River Rch & Prof#=UNT 089 in LFCCL,Reach-1,7
Up Type=0
Dn Type=3
Dn Slope=0.005

--- UNT 089 in LFCCL Watershed.g01 (geometry) ---

Geom Title=Existing Conditions

River Reach=UNT 089 in LFCCL,Reach-1
Reach XY= 30
      2819010.59      7044155.71      2819125.05      7043940.36
      2818904.28      7043729.77      2818244.09      7043426.67
      2818225.89      7043198.55      2818314.48      7043129.76
      2818261.70      7042980.86      2818055.33      7042992.17
      2817910.20      7042832.91      2817733.98      7042385.29
      2817754.71      7042111.07      2817549.28      7042126.14
      2817521.01      7042037.56      2817684.04      7041837.78
      2817767.91      7041864.17      2817854.60      7041621.04
      2818289.97      7041715.28      2818335.21      7041618.21
      2818548.18      7041465.55      2818612.26      7041104.63
      2818782.83      7041000.97      2818799.79      7040892.60
      2819005.22      7040669.26      2819512.21      7040316.81
      2819715.76      7040019.97      2820085.17      7039857.88
      2820300.97      7039666.59      2820838.27      7038603.18
      2821084.81      7037885.48      2821001.74      7037213.93

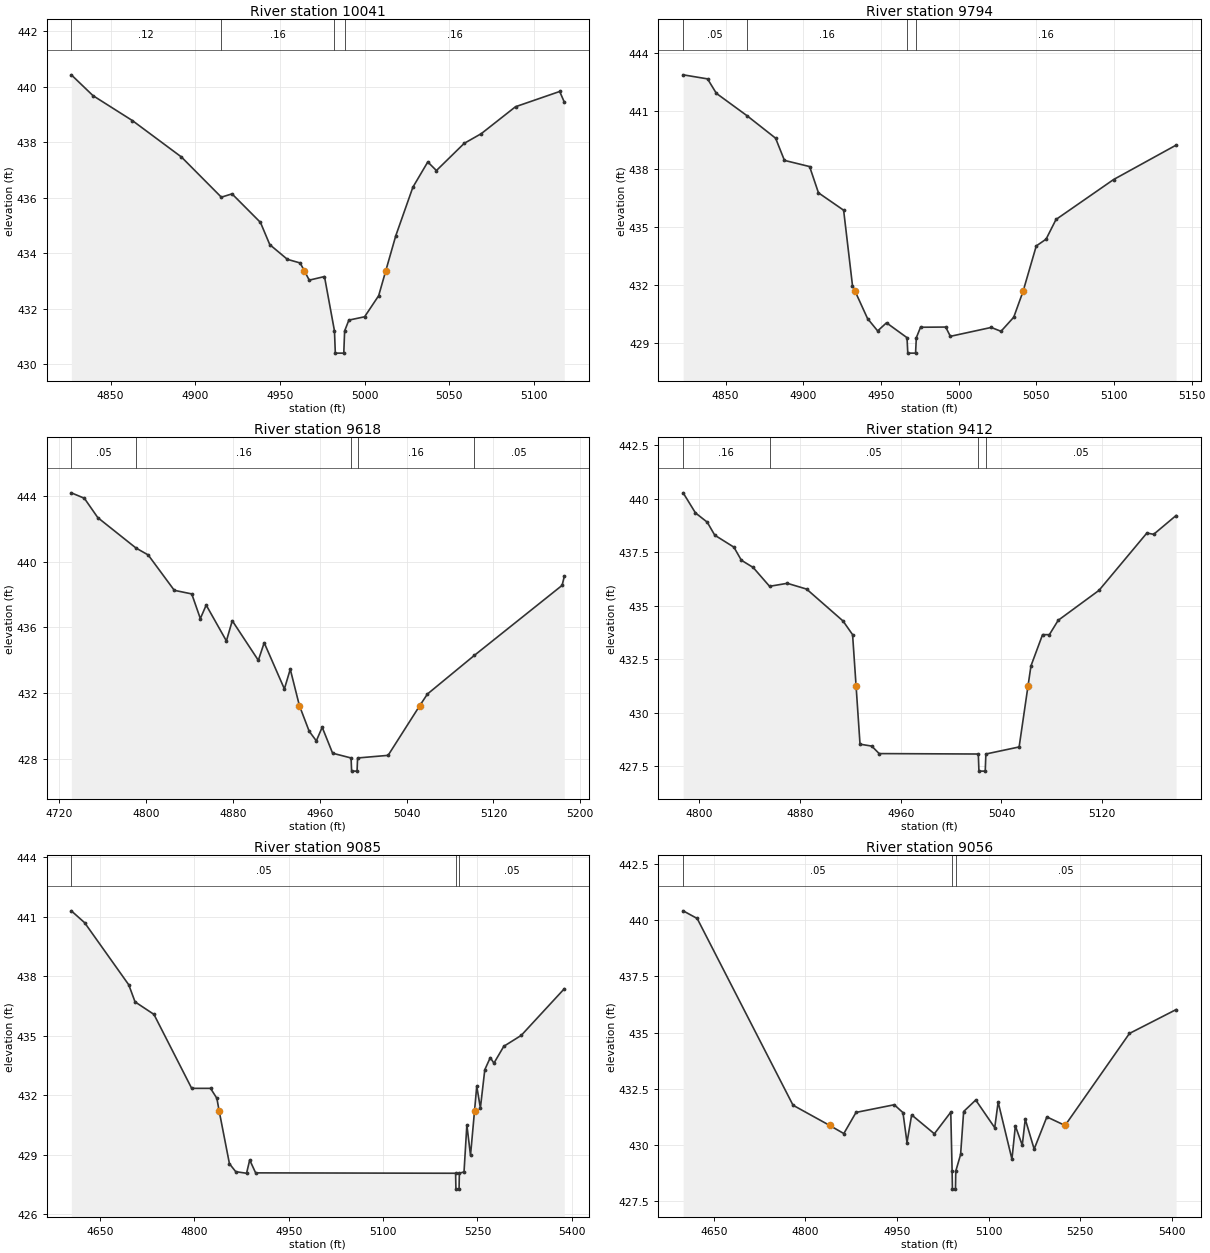
Type RM Length L Ch R = 1,10041,247,247,247
BEGIN DESCRIPTION:
UNT 089 in LFCCL Watershed 4.0
END DESCRIPTION:
XS GIS Cut Line= 3
      2819211.89      7044095.04      2819053.27      7044025.48
      2818936.42      7044009.77
#Sta/Elev= 30
  4826.8  440.43  4839.6  439.68  4862.9  438.78  4891.8  437.47  4915.4  436.02
  4921.7  436.14  4938.5  435.11  4944.0  434.31  4954.4  433.78  4961.9  433.65
  4964.4  433.37  4967.3  433.03  4976.3  433.16  4982.2  431.20  4982.7  430.40
  4987.7  430.40  4988.2  431.20  4990.7  431.59  5000.0  431.71  5008.3  432.47
  5012.5  433.37  5018.4  434.63  5028.5  436.38  5037.3  437.29  5042.4  436.98
  5058.8  437.96  5068.9  438.31  5089.1  439.28  5115.2  439.83  5117.9  439.45
#Mann=4,-1,0
  4826.8    0.12       0  4915.4    0.16       0  4982.2    0.07       0
  4988.2    0.16       0
Bank Sta=4964.4,5012.5
Exp/Cntr=0.3,0.1

Type RM Length L Ch R = 1,9794,176,176,176
BEGIN DESCRIPTION:
XS3616A
END DESCRIPTION:
XS GIS Cut Line= 3
      2819179.48      7043800.21      2819026.15      7043882.77
      2818938.86      7043996.24
#Sta/Elev= 30
  4822.7  442.88  4838.4  442.67  4844.1  441.92  4863.7  440.77  4882.2  439.60
  4887.9  438.45  4904.1  438.13  4909.8  436.77  4926.0  435.87  4931.7  431.97
  4933.4  431.67  4941.4  430.26  4947.9  429.62  4953.6  430.04  4966.8  429.27
  4967.3  428.47  4972.3  428.47  4972.8  429.27  4975.5  429.81  4991.7  429.82
  4994.7  429.34  5021.0  429.80  5027.3  429.60  5035.5  430.33  5041.5  431.67
  5050.0  434.02  5056.3  434.37  5062.7  435.39  5099.8  437.46  5140.0  439.24
#Mann=4,-1,0
  4822.7    0.05       0  4863.7    0.16       0  4966.8    0.07       0
  4972.8    0.16       0
Bank Sta=4933.4,5041.5
Exp/Cntr=0.3,0.1

Type RM Length L Ch R = 1,9618,206,206,206
BEGIN DESCRIPTION:
XS3617A
END DESCRIPTION:
XS GIS Cut Line= 3
      2819167.61      7043643.99      2818922.96      7043744.21
      2818819.88      7043903.24
#Sta/Elev= 30
  4731.3  444.18  4743.3  443.85  4755.7  442.67  4790.9  440.82  4802.1  440.40
  4826.1  438.25  4842.2  438.03  4850.1  436.53  4855.5  437.35  4874.1  435.17
  4879.5  436.40  4903.5  433.99  4908.9  435.06  4927.5  432.25  4932.9  433.45
  4941.3  431.24  4950.3  429.68  4956.9  429.09  4962.3  429.92  4971.9  428.34
  4988.9  428.05  4989.4  427.25  4994.4  427.25  4994.9  428.05  5023.0  428.21
  5052.2  431.24  5059.2  431.94  5102.4  434.29  5183.2  438.55  5185.2  439.09
#Mann=5,-1,0
  4731.3    0.05       0  4790.9    0.16       0  4988.9    0.07       0
  4994.9    0.16       0  5102.4    0.05       0
Bank Sta=4941.3,5052.2
Exp/Cntr=0.3,0.1

Type RM Length L Ch R = 1,9412,327,327,327
BEGIN DESCRIPTION:
XS3618A
END DESCRIPTION:
XS GIS Cut Line= 3
      2818902.30      7043567.33      2818734.28      7043673.45
      2818661.25      7043851.64
#Sta/Elev= 30
  4787.3  440.27  4797.1  439.33  4806.4  438.90  4812.4  438.29  4827.6  437.73
  4833.5  437.12  4842.9  436.78  4855.9  435.90  4870.0  436.04  4885.3  435.77
  4914.2  434.28  4921.8  433.64  4924.6  431.22  4927.7  428.52  4937.0  428.43
  4942.9  428.08  5021.6  428.06  5022.1  427.26  5027.1  427.26  5027.6  428.06
  5054.0  428.39  5061.0  431.22  5063.4  432.18  5072.6  433.64  5078.0  433.64
  5085.0  434.31  5117.4  435.71  5155.4  438.39  5160.8  438.33  5178.6  439.21
#Mann=4,-1,0
  4787.3    0.16       0  4855.9    0.05       0  5021.6   0.033       0
  5027.6    0.05       0
Bank Sta=4924.6,5061
Exp/Cntr=0.3,0.1

Type RM Length L Ch R = 1,9085,29,29,29
BEGIN DESCRIPTION:
XS3628A
END DESCRIPTION:
XS GIS Cut Line= 6
      2818836.24      7043464.22      2818547.61      7043459.88
      2818471.65      7043485.92      2818456.46      7043516.30
      2818456.46      7043587.92      2818627.92      7043844.03
#Sta/Elev= 30
  4604.6  441.30  4625.8  440.70  4695.9  437.57  4705.9  436.71  4735.9  436.08
  4795.9  432.35  4825.9  432.35  4835.9  431.85  4839.5  431.22  4855.9  428.55
  4865.9  428.15  4883.1  428.07  4888.1  428.74  4897.5  428.09  5215.3  428.07
  5215.8  427.27  5220.8  427.27  5221.3  428.07  5228.7  428.14  5233.2  430.51
  5239.0  428.97  5245.4  431.22  5248.9  432.46  5254.7  431.36  5261.7  433.29
  5270.4  433.90  5276.2  433.62  5291.9  434.47  5319.6  435.02  5388.0  437.37
#Mann=3,-1,0
  4604.6    0.05       0  5215.3    0.03       0  5221.3    0.05       0
Bank Sta=4839.5,5245.4
Exp/Cntr=0.3,0.1

Type RM Length L Ch R = 1,9056,31,31,31
BEGIN DESCRIPTION:
XS3627A
END DESCRIPTION:
XS GIS Cut Line= 6
      2818808.02      7043433.84      2818486.84      7043442.52
      2818436.93      7043485.92      2818419.57      7043540.17
      2818421.74      7043592.26      2818599.67      7043846.14
#Sta/Elev= 30
  4599.6  440.41  4622.6  440.07  4779.6  431.77  4839.7  430.87  4862.8  430.51
  4882.8  431.45  4945.4  431.79  4959.7  431.44  4966.3  430.11  4973.9  431.34
  5011.1  430.50  5038.0  431.46  5040.2  428.84  5040.7  428.04  5045.7  428.04
  5046.2  428.84  5054.1  429.58  5059.1  431.49  5078.9  432.00  5110.0  430.77
  5115.6  431.91  5138.2  429.37  5143.8  430.85  5155.1  429.99  5160.0  431.15
  5174.6  429.82  5195.4  431.25  5225.2  430.87  5330.7  434.96  5407.1  436.02
#Mann=3,-1,0
  4599.6    0.05       0  5040.2    0.03       0  5046.2    0.05       0
Bank Sta=4839.7,5225.2
Exp/Cntr=0.3,0.1

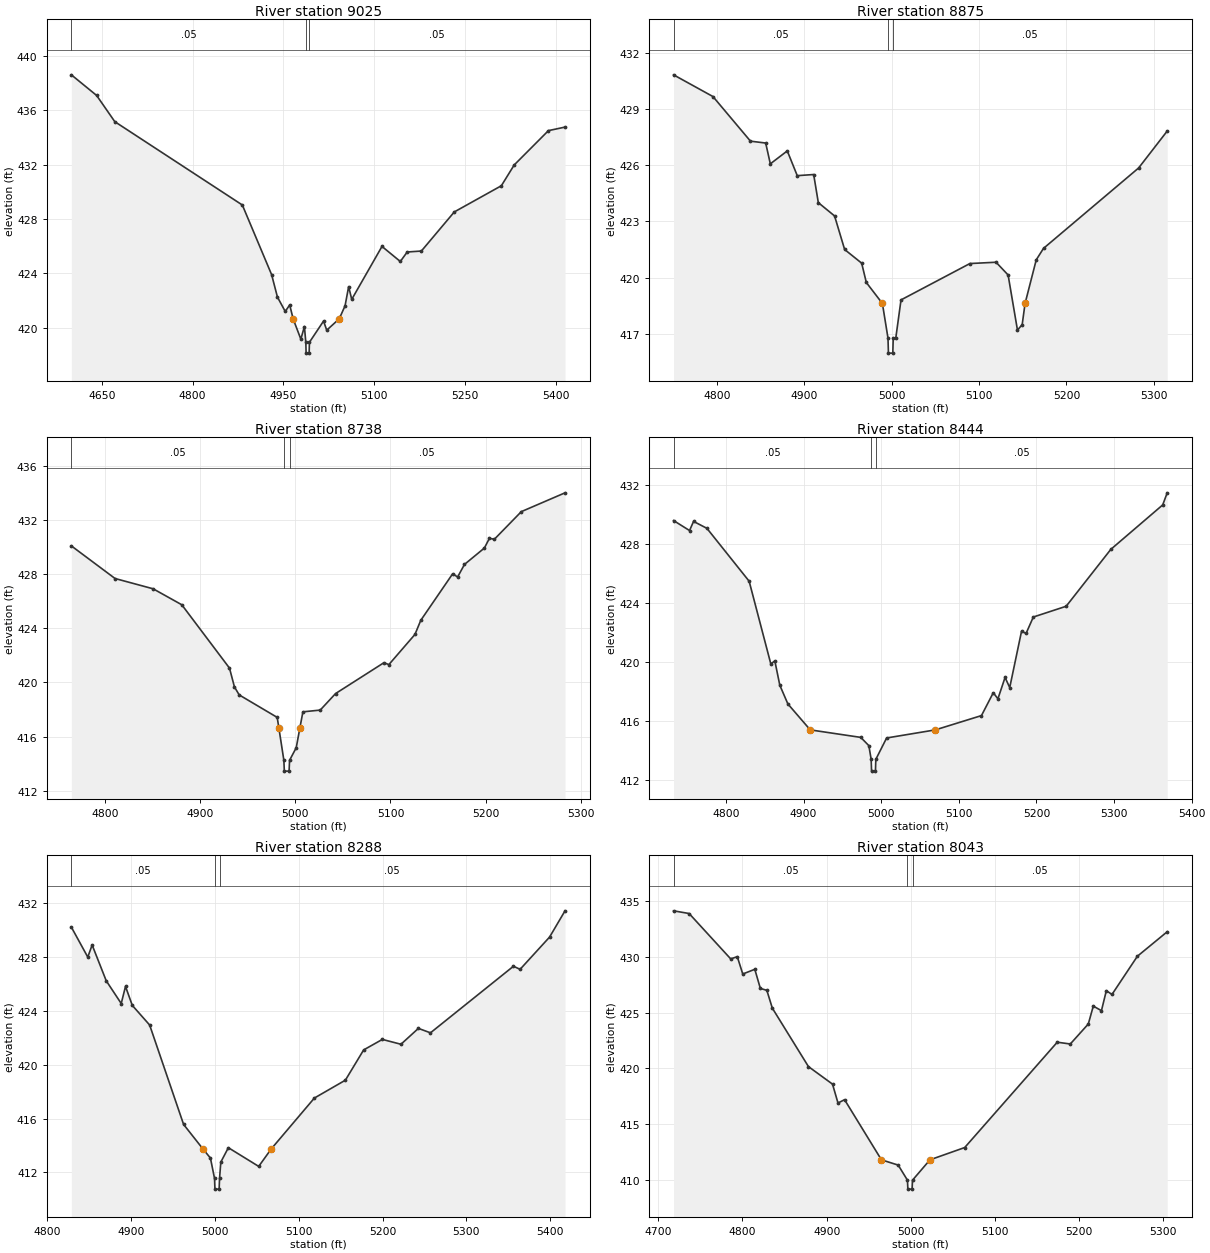
Type RM Length L Ch R = 1,9025,150,150,150
BEGIN DESCRIPTION:
XS3626A
END DESCRIPTION:
XS GIS Cut Line= 6
      2818766.82      7043409.97      2818491.18      7043403.46
      2818417.40      7043449.03      2818382.68      7043577.07
      2818393.53      7043659.53      2818561.39      7043827.40
#Sta/Elev= 30
  4599.6  438.62  4641.4  437.10  4671.4  435.17  4882.2  429.03  4930.6  423.90
  4940.2  422.25  4953.1  421.19  4960.5  421.67  4966.1  420.65  4978.9  419.15
  4984.8  420.08  4987.1  418.92  4987.6  418.12  4992.6  418.12  4993.1  418.92
  5016.4  420.48  5021.7  419.81  5042.4  420.65  5052.0  421.61  5057.9  423.02
  5063.0  422.08  5113.0  425.98  5143.3  424.87  5154.7  425.57  5178.1  425.64
  5232.5  428.52  5310.3  430.45  5331.5  431.98  5388.1  434.51  5415.5  434.77
#Mann=3,-1,0
  4599.6    0.05       0  4987.1    0.03       0  4993.1    0.05       0
Bank Sta=4966.1,5042.4
Exp/Cntr=0.3,0.1

Type RM Length L Ch R = 1,8875,137,137,137
BEGIN DESCRIPTION:
XS3625A
END DESCRIPTION:
XS GIS Cut Line= 3
      2818507.24      7043352.12      2818274.37      7043440.55
      2818159.70      7043734.59
#Sta/Elev= 30
  4750.6  430.82  4795.7  429.66  4838.6  427.28  4856.0  427.18  4861.3  426.07
  4880.7  426.76  4892.1  425.44  4910.9  425.50  4916.2  424.00  4934.8  423.29
  4946.3  421.50  4965.8  420.77  4971.1  419.74  4989.5  418.62  4995.9  416.77
  4996.4  415.97  5001.4  415.97  5001.9  416.77  5004.8  416.77  5010.8  418.81
  5089.6  420.75  5119.5  420.82  5133.3  420.14  5144.0  417.20  5149.4  417.49
  5152.7  418.62  5165.5  420.95  5173.8  421.56  5282.6  425.85  5315.3  427.82
#Mann=3,-1,0
  4750.6    0.05       0  4995.9    0.03       0  5001.9    0.05       0
Bank Sta=4989.5,5152.7
Exp/Cntr=0.3,0.1

Type RM Length L Ch R = 1,8738,294,294,294
BEGIN DESCRIPTION:
XS3624A
END DESCRIPTION:
XS GIS Cut Line= 3
      2818480.77      7043340.32      2818236.05      7043325.57
      2817973.68      7043402.22
#Sta/Elev= 30
  4764.8  430.09  4810.7  427.68  4850.7  426.92  4880.8  425.74  4930.9  421.06
  4936.1  419.67  4941.1  419.08  4981.0  417.42  4982.7  416.67  4988.0  414.25
  4988.5  413.45  4993.5  413.45  4994.0  414.25  5001.0  415.18  5004.9  416.67
  5008.0  417.83  5026.2  417.96  5042.3  419.18  5093.1  421.46  5098.3  421.32
  5125.7  423.55  5131.8  424.59  5165.3  428.03  5170.5  427.79  5177.7  428.72
  5198.6  429.93  5203.9  430.65  5209.1  430.58  5237.4  432.62  5283.3  434.01
#Mann=3,-1,0
  4764.8    0.05       0  4988.0    0.03       0  4994.0    0.05       0
Bank Sta=4982.7,5004.9
Exp/Cntr=0.3,0.1

Type RM Length L Ch R = 1,8444,156,156,156
BEGIN DESCRIPTION:
XS3623A
END DESCRIPTION:
XS GIS Cut Line= 3
      2818566.19      7043013.09      2818318.59      7043086.78
      2818000.33      7043290.11
#Sta/Elev= 30
  4732.5  429.62  4753.1  428.94  4758.3  429.56  4775.5  429.09  4829.9  425.50
  4857.8  419.89  4863.0  420.09  4869.4  418.44  4879.8  417.17  4908.6  415.41
  4973.7  414.90  4984.1  414.34  4987.1  413.41  4987.6  412.61  4992.6  412.61
  4993.1  413.41  5007.0  414.86  5069.8  415.41  5129.2  416.38  5144.4  417.93
  5150.4  417.52  5159.6  418.97  5165.6  418.28  5180.8  422.10  5186.7  421.96
  5196.0  423.07  5238.3  423.80  5295.8  427.66  5362.7  430.68  5368.5  431.50
#Mann=3,-1,0
  4732.5    0.05       0  4987.1    0.03       0  4993.1    0.05       0
Bank Sta=4908.6,5069.8
Exp/Cntr=0.3,0.1

Type RM Length L Ch R = 1,8288,245,245,245
BEGIN DESCRIPTION:
XS3622A
END DESCRIPTION:
XS GIS Cut Line= 4
      2818286.18      7042794.87      2818239.00      7042968.85
      2818153.50      7043125.10      2817975.22      7043271.23
#Sta/Elev= 30
  4828.8  430.24  4848.4  428.01  4853.6  428.91  4870.4  426.25  4888.3  424.56
  4893.4  425.83  4901.5  424.42  4922.2  422.96  4962.7  415.57  4985.6  413.76
  4994.7  413.07  4999.6  411.56  5000.1  410.76  5005.1  410.76  5005.6  411.56
  5007.1  412.77  5016.1  413.84  5052.3  412.45  5067.4  413.76  5118.7  417.53
  5155.7  418.86  5177.5  421.11  5199.8  421.89  5222.0  421.53  5242.8  422.71
  5257.2  422.38  5356.2  427.33  5364.1  427.10  5399.3  429.50  5417.7  431.45
#Mann=3,-1,0
  4828.8    0.05       0  4999.6    0.03       0  5005.6    0.05       0
Bank Sta=4985.6,5067.4
Exp/Cntr=0.3,0.1

Type RM Length L Ch R = 1,8043,180,180,180
BEGIN DESCRIPTION:
XS3621A
END DESCRIPTION:
XS GIS Cut Line= 3
      2818233.13      7042777.20      2818020.83      7042957.06
      2817862.34      7043221.22
#Sta/Elev= 30
  4718.2  434.10  4736.7  433.86  4786.1  429.80  4793.9  430.00  4800.4  428.45
  4814.7  428.87  4821.3  427.16  4829.0  426.99  4835.5  425.40  4878.4  420.17
  4907.0  418.60  4913.5  416.91  4921.3  417.21  4965.1  411.83  4985.0  411.36
  4996.0  410.01  4996.5  409.21  5001.5  409.21  5002.0  410.01  5022.7  411.83
  5064.0  412.93  5173.9  422.35  5189.4  422.19  5210.8  423.98  5216.7  425.58
  5226.4  425.17  5232.2  426.96  5238.9  426.62  5269.1  430.04  5304.5  432.23
#Mann=3,-1,0
  4718.2    0.05       0  4996.0    0.03       0  5002.0    0.05       0
Bank Sta=4965.1,5022.7
Exp/Cntr=0.3,0.1

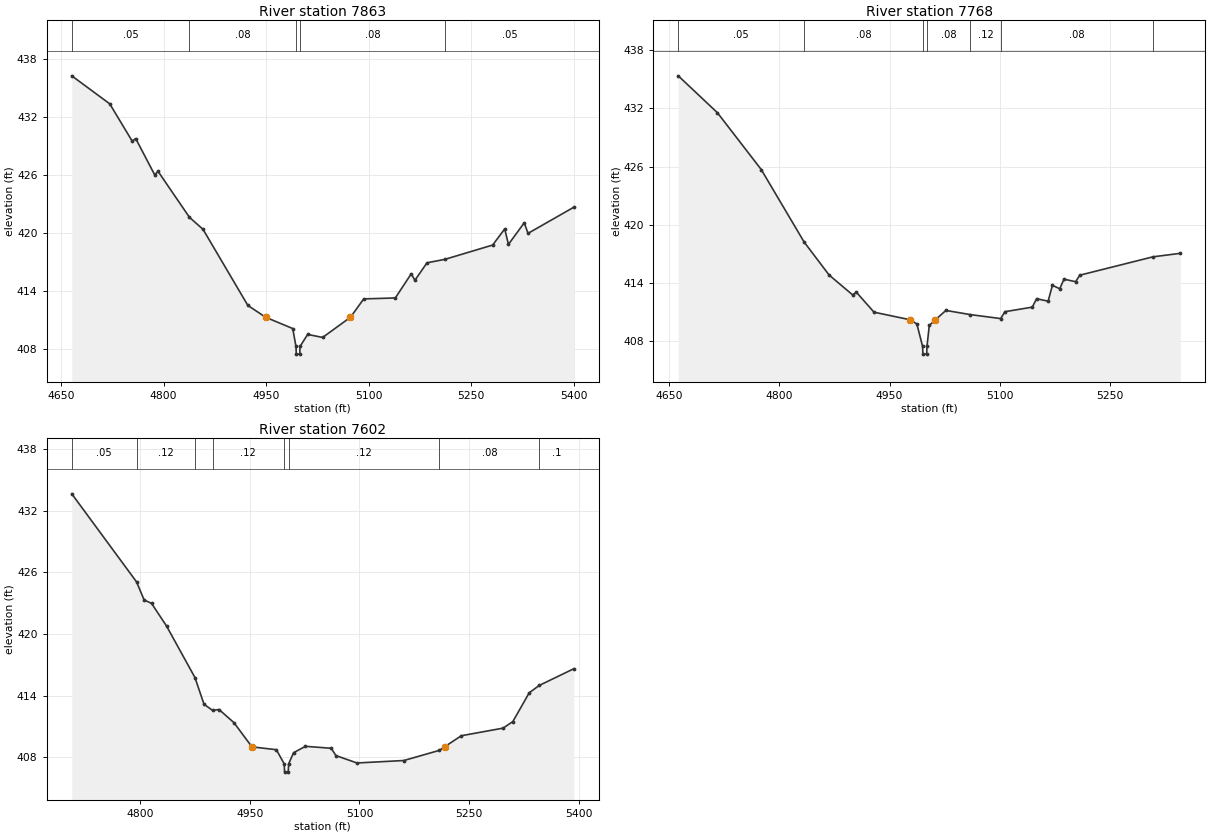
Type RM Length L Ch R = 1,7863,95,95,95
BEGIN DESCRIPTION:
XS3620A
END DESCRIPTION:
XS GIS Cut Line= 4
      2818224.28      7042724.15      2817905.86      7042821.44
      2817723.07      7042903.99      2817640.52      7043086.80
#Sta/Elev= 30
  4665.8  436.26  4721.3  433.36  4754.1  429.50  4759.3  429.76  4786.9  426.02
  4792.1  426.35  4837.9  421.60  4857.7  420.36  4923.3  412.47  4949.3  411.25
  4988.9  410.08  4993.6  408.23  4994.1  407.43  4999.1  407.43  4999.6  408.23
  5010.7  409.47  5032.6  409.16  5073.3  411.25  5092.7  413.15  5138.9  413.25
  5162.1  415.75  5167.5  415.08  5185.2  416.89  5211.4  417.25  5281.2  418.73
  5298.8  420.40  5304.3  418.80  5327.4  421.04  5332.9  419.94  5399.9  422.65
#Mann=5,-1,0
  4665.8    0.05       0  4837.9    0.08       0  4993.6    0.07       0
  4999.6    0.08       0  5211.4    0.05       0
Bank Sta=4949.3,5073.3
Exp/Cntr=0.3,0.1

Type RM Length L Ch R = 1,7768,166,166,166
BEGIN DESCRIPTION:
XS3619A
END DESCRIPTION:
XS GIS Cut Line= 3
      2818174.15      7042606.23      2817858.69      7042738.90
      2817563.90      7042909.87
#Sta/Elev= 30
  4662.5  435.35  4715.8  431.55  4775.4  425.70  4833.7  418.24  4867.7  414.84
  4899.6  412.80  4905.0  413.05  4928.8  411.01  4977.9  410.23  4987.1  409.80
  4994.9  407.49  4995.4  406.69  5000.4  406.69  5000.9  407.49  5004.0  409.64
  5012.4  410.23  5026.6  411.19  5059.9  410.76  5101.2  410.35  5106.9  411.06
  5144.2  411.53  5150.0  412.40  5165.7  412.14  5171.5  413.78  5181.5  413.42
  5187.2  414.41  5203.0  414.15  5208.8  414.82  5308.3  416.71  5345.5  417.07
#Mann=7,-1,0
  4662.5    0.05       0  4833.7    0.08       0  4994.9    0.07       0
  5000.9    0.08       0  5059.9    0.12       0  5101.2    0.08       0
  5308.3     0.1       0
Bank Sta=4977.9,5012.4
Exp/Cntr=0.3,0.1

Type RM Length L Ch R = 1,7602,0,0,0
BEGIN DESCRIPTION:
UNT 089 in LFCCL Watershed 1.0
END DESCRIPTION:
XS GIS Cut Line= 3
      2818091.56      7042520.74      2817790.88      7042585.59
      2817554.12      7042880.27
#Sta/Elev= 30
  4707.1  433.64  4795.6  425.07  4805.9  423.32  4816.1  422.98  4836.6  420.77
  4875.3  415.77  4887.7  413.17  4899.3  412.58  4908.2  412.66  4928.6  411.38
  4953.1  409.03  4986.5  408.75  4997.2  407.37  4997.7  406.57  5002.7  406.57
  5003.2  407.37  5010.0  408.46  5026.2  409.08  5061.4  408.89  5067.8  408.18
  5096.6  407.46  5160.6  407.70  5209.2  408.69  5216.2  409.03  5239.0  410.11
  5296.1  410.85  5309.4  411.49  5331.8  414.29  5345.4  415.00  5392.7  416.63
#Mann=8,-1,0
  4707.1    0.05       0  4795.6    0.12       0  4875.3    0.05       0
  4899.3    0.12       0  4997.2    0.07       0  5003.2    0.12       0
  5209.2    0.08       0  5345.4     0.1       0
Bank Sta=4953.1,5216.2
Exp/Cntr=0.3,0.1

Chan Stop Cuts=-1