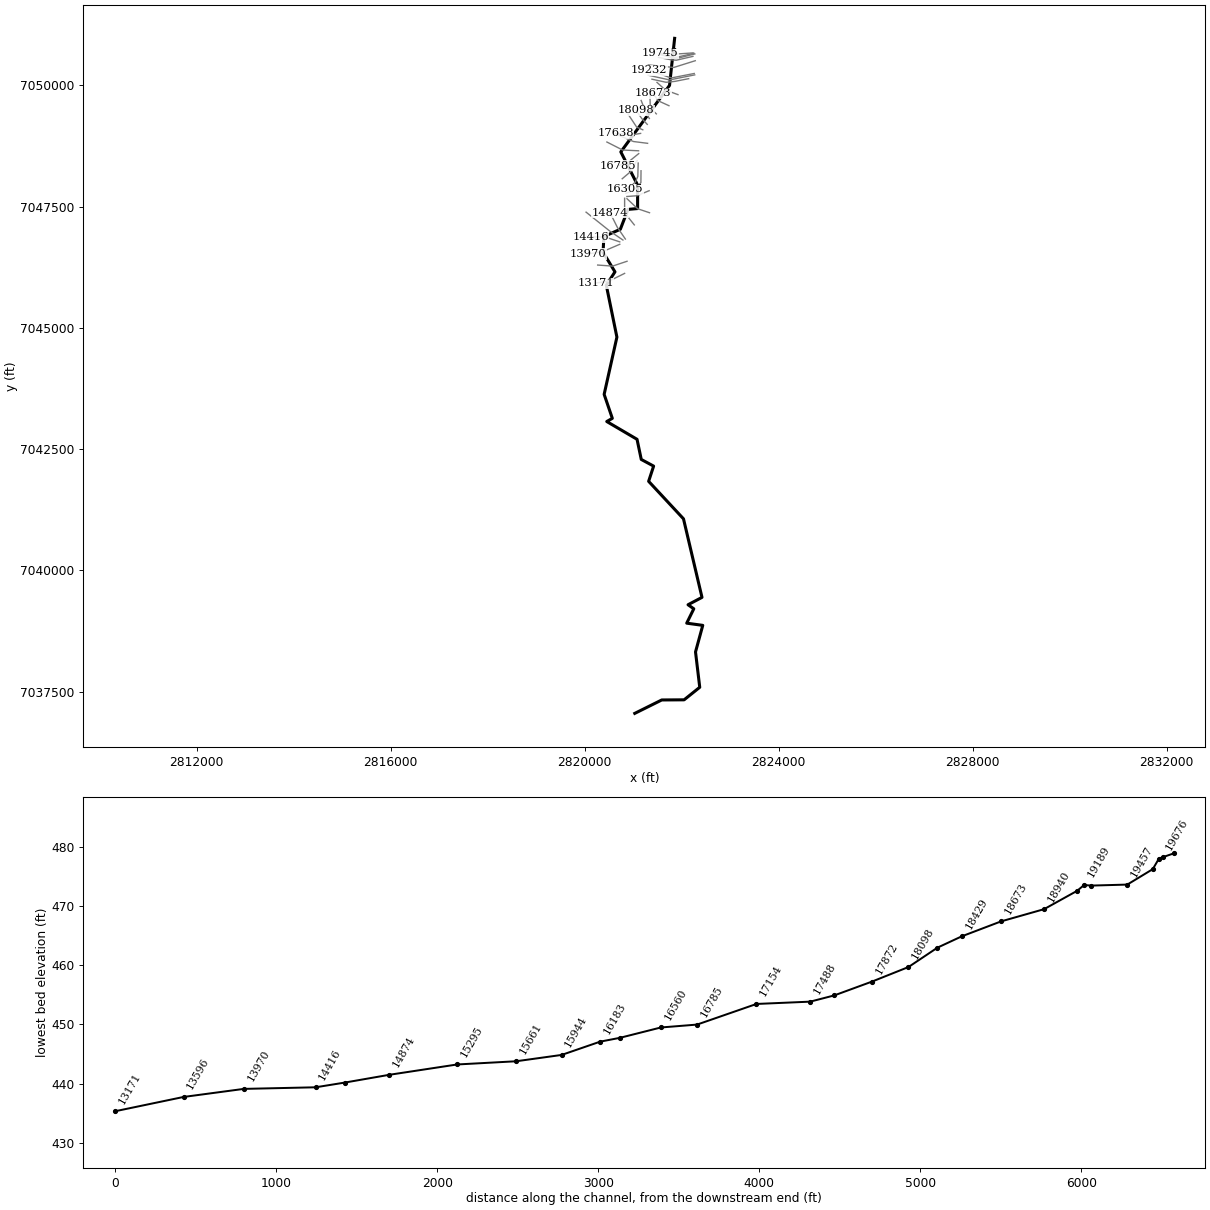
--- UNT 090 in LFCCL Watershed.prj (project) ---

Proj Title=UNT 090 in LFCCL Watershed Base Level Engineering
Current Plan=p01
Default Exp/Contr=0.3,0.1
English Units
Geom File=g01
Flow File=f01
Plan File=p01
BEGIN DESCRIPTION:
UNT 090 in LFCCL Watershed
END DESCRIPTION:

--- UNT 090 in LFCCL Watershed.p01 (plan) ---

Plan Title=Multiple Run
Short Identifier=Multiple
Geom File=g01
Flow File=f01
Subcritical Flow
K Sum by GR= 0
Std Step Tol= 0.01
Critical Tol= 0.01
Num of Std Step Trials= 20
Max Error Tol= 0.3
Flow Tol Ratio= 0.001
Split Flow NTrial= 30
Split Flow Tol= 0.02
Split Flow Ratio= 0.02
Log Output Level= 0
Friction Slope Method= 1
Unsteady Friction Slope Method= 2
Unsteady Bridges Friction Slope Method= 1
Parabolic Critical Depth
Global Vel Dist=  1 , 1 , 1
Global Log Level= 0
CheckData=True
Encroach Param= -1, 0, 0, 0
BEGIN DESCRIPTION:
Multiple Run
END DESCRIPTION:

--- UNT 090 in LFCCL Watershed.f01 (steady flow) ---

Flow Title=Multiple
Number of Profiles=7
Profile Names=10-year,25-year,50-year,1pct_min,100-year,1pct_plu,500-year
River Rch & RM= UNT 090 in LFCCL,Reach-1,19745
     302     387     453     264     527    1052     713
River Rch & RM= UNT 090 in LFCCL,Reach-1,14416
     651     871    1049     627    1252    2497    1786
River Rch & RM= UNT 090 in LFCCL,Reach-1,5196
     944    1286    1568     948    1891    3773    2758
Boundary for River Rch & Prof#=UNT 090 in LFCCL,Reach-1,1
Up Type=0
Dn Type=3
Dn Slope=0.005
Boundary for River Rch & Prof#=UNT 090 in LFCCL,Reach-1,2
Up Type=0
Dn Type=3
Dn Slope=0.005
Boundary for River Rch & Prof#=UNT 090 in LFCCL,Reach-1,3
Up Type=0
Dn Type=3
Dn Slope=0.005
Boundary for River Rch & Prof#=UNT 090 in LFCCL,Reach-1,4
Up Type=0
Dn Type=3
Dn Slope=0.005
Boundary for River Rch & Prof#=UNT 090 in LFCCL,Reach-1,5
Up Type=0
Dn Type=3
Dn Slope=0.005
Boundary for River Rch & Prof#=UNT 090 in LFCCL,Reach-1,6
Up Type=0
Dn Type=3
Dn Slope=0.005
Boundary for River Rch & Prof#=UNT 090 in LFCCL,Reach-1,7
Up Type=0
Dn Type=3
Dn Slope=0.005

--- UNT 090 in LFCCL Watershed.g01 (geometry) ---

Geom Title=Existing Conditions

River Reach=UNT 090 in LFCCL,Reach-1
Reach XY= 30
      2821856.14      7050971.97      2821751.10      7050001.92
      2820746.55      7048630.39      2821092.68      7047945.89
      2821092.94      7047461.93      2820894.92      7047444.76
      2820736.95      7047035.45      2820397.33      7046884.49
      2820380.62      7046561.75      2820625.79      7046156.57
      2820447.25      7045881.16      2820665.85      7044810.81
      2820402.72      7043630.86      2820571.68      7043135.75
      2820456.34      7043070.84      2821080.94      7042703.91
      2821168.14      7042288.44      2821423.02      7042151.19
      2821320.09      7041837.50      2822038.83      7041064.10
      2822420.47      7039444.35      2822132.51      7039292.41
      2822251.37      7039209.08      2822105.55      7038912.54
      2822436.40      7038867.20      2822286.90      7038319.46
      2822373.90      7037590.37      2822051.63      7037331.82
      2821590.99      7037329.13      2821034.21      7037052.42

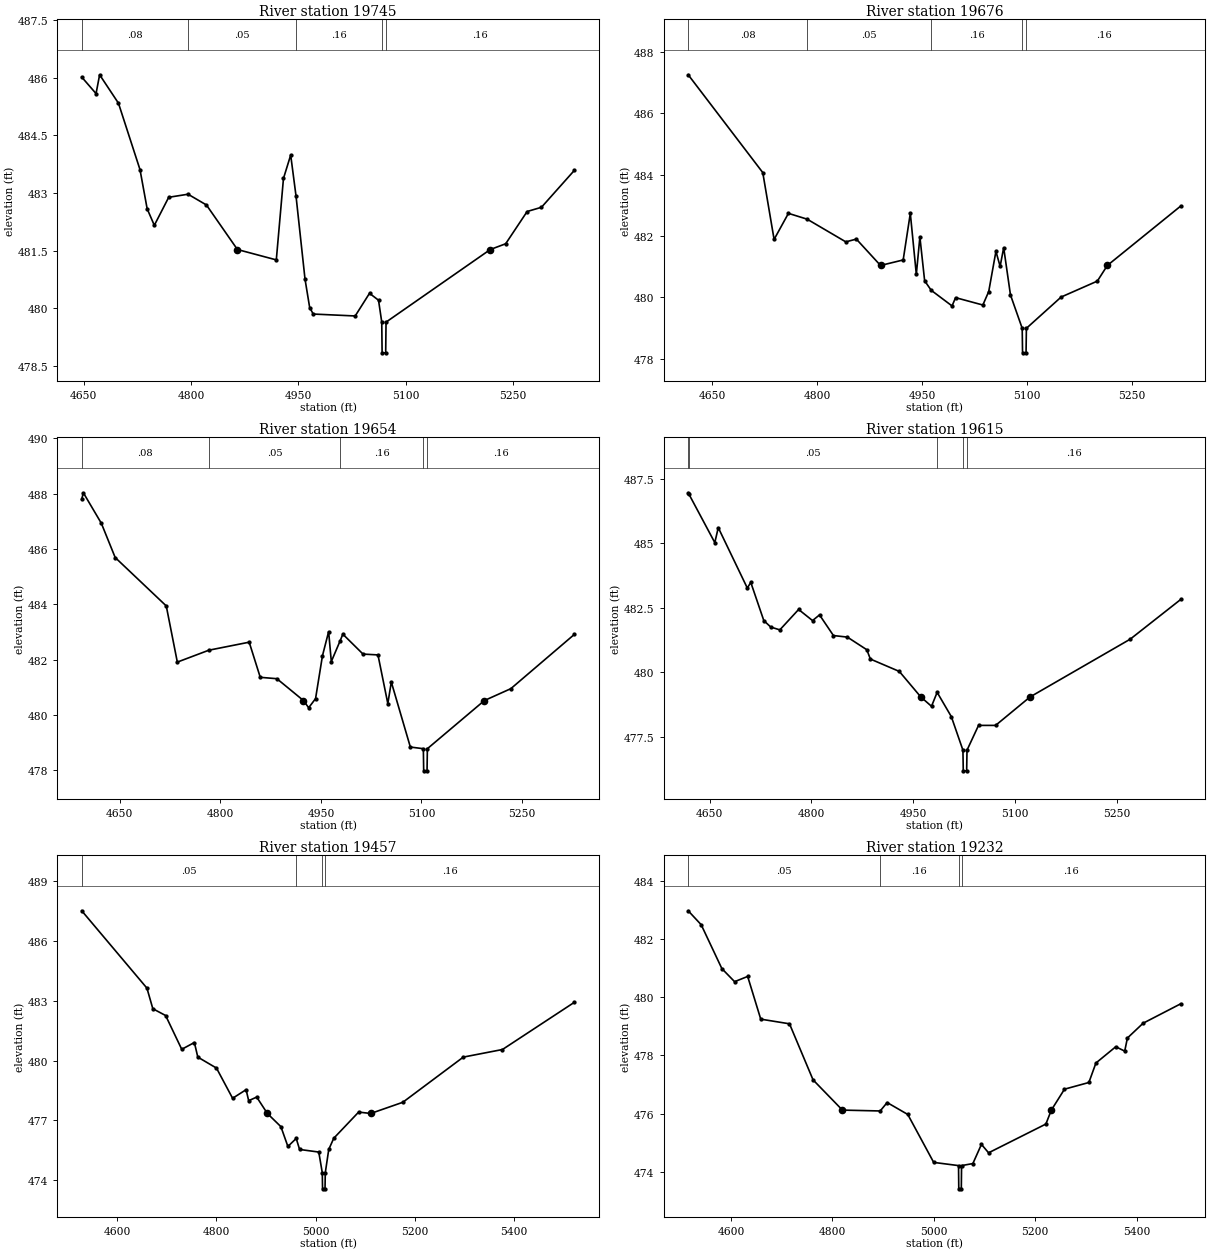
Type RM Length L Ch R = 1,19745,69,69,69
BEGIN DESCRIPTION:
XS3629A
END DESCRIPTION:
XS GIS Cut Line= 3
      2822236.20      7050671.60      2821882.98      7050647.70
      2821549.17      7050660.94
#Sta/Elev= 30
  4647.5  486.02  4667.5  485.59  4672.5  486.08  4698.8  485.34  4728.9  483.61
  4738.9  482.59  4748.9  482.16  4769.0  482.89  4796.0  482.97  4821.7  482.69
  4865.0  481.53  4919.3  481.26  4929.3  483.38  4939.4  483.99  4946.8  482.93
  4959.4  480.76  4965.9  480.02  4970.9  479.85  5029.5  479.80  5049.5  480.39
  5062.1  480.21  5066.6  479.64  5067.1  478.84  5072.1  478.84  5072.6  479.64
  5218.2  481.53  5239.7  481.68  5269.7  482.52  5289.7  482.63  5335.6  483.59
#Mann=5,-1,0
  4647.5    0.08       0  4796.0    0.05       0  4946.8    0.16       0
  5066.6    0.07       0  5072.6    0.16       0
Bank Sta=4865,5218.2
Exp/Cntr=0.3,0.1

Type RM Length L Ch R = 1,19676,22,22,22
BEGIN DESCRIPTION:
XS3631A
END DESCRIPTION:
XS GIS Cut Line= 4
      2822254.81      7050663.63      2821906.88      7050583.95
      2821843.14      7050573.33      2821569.81      7050647.63
#Sta/Elev= 30
  4615.3  487.26  4722.0  484.07  4738.2  481.89  4758.7  482.74  4785.5  482.55
  4840.8  481.81  4855.9  481.90  4890.5  481.04  4922.9  481.22  4933.1  482.74
  4941.7  480.75  4946.8  481.97  4953.6  480.54  4963.0  480.23  4992.8  479.72
  4997.9  479.99  5036.9  479.75  5045.3  480.19  5055.6  481.50  5061.6  481.01
  5066.7  481.62  5076.4  480.08  5093.2  478.99  5093.7  478.19  5098.7  478.19
  5099.2  478.99  5148.9  480.01  5200.7  480.53  5215.0  481.04  5320.1  482.98
#Mann=5,-1,0
  4615.3    0.08       0  4785.5    0.05       0  4963.0    0.16       0
  5093.2    0.07       0  5099.2    0.16       0
Bank Sta=4890.5,5215
Exp/Cntr=0.3,0.1

Type RM Length L Ch R = 1,19654,39,39,39
BEGIN DESCRIPTION:
XS3630A
END DESCRIPTION:
XS GIS Cut Line= 4
      2822273.37      7050650.34      2821912.19      7050560.05
      2821845.80      7050554.74      2821561.58      7050637.08
#Sta/Elev= 30
  4593.2  487.80  4595.6  488.03  4622.4  486.93  4643.1  485.69  4719.3  483.94
  4735.8  481.91  4782.8  482.34  4843.0  482.63  4859.5  481.36  4884.3  481.31
  4924.0  480.52  4931.7  480.26  4942.0  480.59  4952.3  482.14  4961.5  483.01
  4965.5  481.93  4978.5  482.67  4982.7  482.92  5012.8  482.20  5035.1  482.17
  5049.8  480.41  5055.0  481.19  5083.4  478.84  5102.8  478.78  5103.3  477.98
  5108.3  477.98  5108.8  478.78  5193.8  480.52  5233.3  480.95  5328.0  482.91
#Mann=5,-1,0
  4593.2    0.08       0  4782.8    0.05       0  4978.5    0.16       0
  5102.8    0.07       0  5108.8    0.16       0
Bank Sta=4924,5193.8
Exp/Cntr=0.3,0.1

Type RM Length L Ch R = 1,19615,158,158,158
BEGIN DESCRIPTION:
XS3632A
END DESCRIPTION:
XS GIS Cut Line= 4
      2822233.51      7050599.88      2821888.29      7050520.21
      2821790.02      7050528.18      2821521.81      7050578.64
#Sta/Elev= 30
  4618.5  486.95  4619.3  486.91  4657.7  485.02  4662.8  485.60  4705.6  483.26
  4710.7  483.48  4729.9  482.00  4740.1  481.75  4753.5  481.64  4781.2  482.43
  4801.7  482.00  4812.0  482.22  4832.5  481.42  4853.0  481.36  4881.7  480.87
  4886.9  480.51  4929.6  480.03  4961.3  479.04  4977.0  478.68  4985.3  479.22
  5006.2  478.28  5023.3  476.98  5023.8  476.18  5028.8  476.18  5029.3  476.98
  5046.3  477.94  5071.4  477.94  5122.1  479.04  5269.8  481.28  5344.3  482.82
#Mann=5,-1,0
  4618.5    0.08       0  4619.3    0.05       0  4985.3    0.16       0
  5023.3    0.07       0  5029.3    0.16       0
Bank Sta=4961.3,5122.1
Exp/Cntr=0.3,0.1

Type RM Length L Ch R = 1,19457,225,225,225
BEGIN DESCRIPTION:
XS3633A
END DESCRIPTION:
XS GIS Cut Line= 3
      2822281.83      7050510.44      2821837.83      7050371.48
      2821312.19      7050424.07
#Sta/Elev= 30
  4528.3  487.49  4659.8  483.62  4671.7  482.59  4697.5  482.25  4730.0  480.56
  4755.5  480.90  4762.4  480.17  4800.1  479.62  4832.6  478.11  4859.8  478.54
  4865.0  477.99  4881.2  478.17  4902.7  477.35  4930.0  476.69  4944.1  475.70
  4960.9  476.10  4967.7  475.55  5006.4  475.42  5013.5  474.38  5014.0  473.58
  5019.0  473.58  5019.5  474.38  5026.5  475.55  5036.6  476.11  5086.8  477.42
  5111.1  477.35  5175.9  477.91  5297.9  480.17  5376.9  480.55  5521.8  482.91
#Mann=4,-1,0
  4528.3    0.05       0  4960.9    0.16       0  5013.5    0.07       0
  5019.5    0.16       0
Bank Sta=4902.7,5111.1
Exp/Cntr=0.3,0.1

Type RM Length L Ch R = 1,19232,43,43,43
BEGIN DESCRIPTION:
XS3634A
END DESCRIPTION:
XS GIS Cut Line= 4
      2822260.14      7050247.42      2821792.68      7050156.35
      2821726.28      7050174.94      2821323.90      7050316.00
#Sta/Elev= 30
  4515.4  482.98  4541.0  482.50  4581.8  480.99  4606.9  480.54  4632.7  480.72
  4658.5  479.25  4715.2  479.09  4761.7  477.16  4819.6  476.12  4894.1  476.09
  4907.8  476.38  4948.5  475.97  4999.6  474.32  5048.6  474.21  5049.1  473.41
  5054.1  473.41  5054.6  474.21  5076.9  474.28  5093.8  474.94  5107.9  474.65
  5220.9  475.64  5231.7  476.12  5257.6  476.84  5305.7  477.07  5319.6  477.74
  5358.7  478.30  5376.4  478.15  5381.7  478.60  5412.7  479.11  5487.0  479.78
#Mann=4,-1,0
  4515.4    0.05       0  4894.1    0.16       0  5048.6    0.07       0
  5054.6    0.16       0
Bank Sta=4819.6,5231.7
Exp/Cntr=0.3,0.1

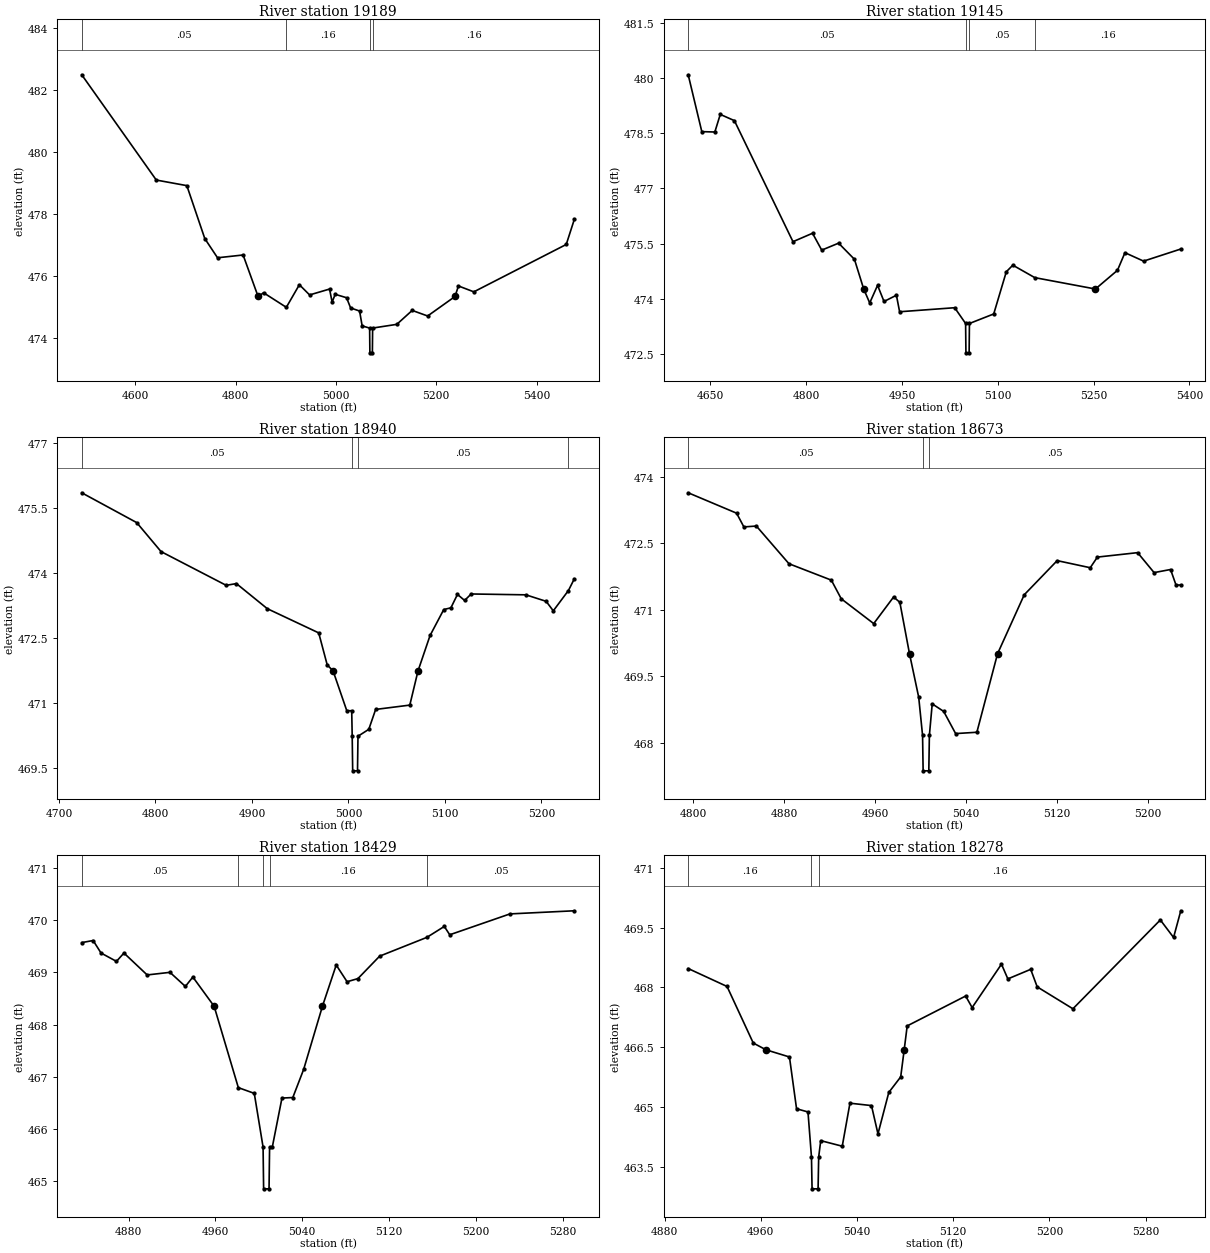
Type RM Length L Ch R = 1,19189,44,44,44
BEGIN DESCRIPTION:
XS3635A
END DESCRIPTION:
XS GIS Cut Line= 4
      2822270.52      7050218.33      2821803.30      7050124.48
      2821752.84      7050113.86      2821309.33      7050211.70
#Sta/Elev= 30
  4493.1  482.49  4641.8  479.09  4702.7  478.91  4738.5  477.20  4763.9  476.58
  4814.9  476.67  4844.8  475.33  4855.7  475.45  4901.1  474.98  4927.1  475.71
  4947.5  475.38  4987.3  475.57  4992.4  475.15  4998.6  475.40  5021.2  475.29
  5029.3  474.96  5047.2  474.86  5052.3  474.38  5067.2  474.31  5067.7  473.51
  5072.7  473.51  5073.2  474.31  5121.4  474.43  5152.1  474.88  5182.9  474.70
  5237.5  475.33  5244.3  475.67  5275.0  475.48  5459.3  477.01  5475.4  477.82
#Mann=4,-1,0
  4493.1    0.05       0  4901.1    0.16       0  5067.2    0.07       0
  5073.2    0.16       0
Bank Sta=4844.8,5237.5
Exp/Cntr=0.3,0.1

Type RM Length L Ch R = 1,19145,205,205,205
BEGIN DESCRIPTION:
XS3636A
END DESCRIPTION:
XS GIS Cut Line= 5
      2822145.92      7050140.42      2821864.39      7050084.64
      2821766.12      7050074.02      2821678.47      7050066.05
      2821388.16      7050129.39
#Sta/Elev= 30
  4615.5  480.10  4636.8  478.55  4657.2  478.54  4665.7  479.02  4687.8  478.85
  4779.5  475.55  4810.1  475.78  4824.5  475.32  4850.9  475.51  4875.7  475.07
  4890.2  474.26  4899.6  473.88  4911.9  474.36  4922.0  473.92  4941.4  474.09
  4946.4  473.64  5032.6  473.75  5049.7  473.32  5050.2  472.52  5055.2  472.52
  5055.7  473.32  5093.7  473.58  5113.4  474.73  5123.6  474.91  5158.0  474.57
  5252.9  474.26  5287.4  474.77  5299.1  475.25  5328.3  475.02  5386.5  475.35
#Mann=4,-1,0
  4615.5    0.05       0  5049.7    0.03       0  5055.7    0.05       0
  5158.0    0.16       0
Bank Sta=4890.2,5252.9
Exp/Cntr=0.3,0.1

Type RM Length L Ch R = 1,18940,267,267,267
BEGIN DESCRIPTION:
XS3637A
END DESCRIPTION:
XS GIS Cut Line= 3
      2821925.50      7049811.08      2821665.20      7049906.70
      2821492.53      7050063.43
#Sta/Elev= 30
  4723.6  475.86  4780.6  475.17  4805.8  474.50  4873.3  473.72  4883.9  473.76
  4915.9  473.18  4969.2  472.62  4978.0  471.88  4984.1  471.74  4998.3  470.82
  5003.4  470.82  5003.9  470.23  5004.4  469.43  5009.4  469.43  5009.9  470.23
  5021.1  470.39  5028.2  470.85  5063.6  470.95  5072.1  471.74  5084.6  472.56
  5098.8  473.16  5106.2  473.20  5113.0  473.51  5120.4  473.37  5127.2  473.52
  5183.9  473.50  5204.9  473.35  5212.3  473.13  5228.0  473.60  5234.1  473.87
#Mann=4,-1,0
  4723.6    0.05       0  5003.9    0.03       0  5009.9    0.05       0
  5228.0    0.16       0
Bank Sta=4984.1,5072.1
Exp/Cntr=0.3,0.1

Type RM Length L Ch R = 1,18673,244,244,244
BEGIN DESCRIPTION:
XS3638A
END DESCRIPTION:
XS GIS Cut Line= 3
      2821739.59      7049582.66      2821524.43      7049680.94
      2821404.92      7049837.63
#Sta/Elev= 30
  4795.5  473.64  4838.1  473.18  4844.5  472.87  4855.5  472.89  4884.2  472.04
  4921.5  471.67  4930.2  471.25  4958.8  470.69  4976.3  471.29  4981.8  471.17
  4990.3  470.01  4998.4  469.03  5001.8  468.17  5002.3  467.37  5007.3  467.37
  5007.8  468.17  5010.3  468.88  5020.4  468.71  5030.9  468.21  5049.6  468.24
  5067.8  470.01  5091.3  471.34  5120.3  472.11  5149.4  471.95  5155.7  472.19
  5191.1  472.29  5205.6  471.84  5220.1  471.91  5224.9  471.56  5229.1  471.56
#Mann=3,-1,0
  4795.5    0.05       0  5001.8    0.03       0  5007.8    0.05       0
Bank Sta=4990.3,5067.8
Exp/Cntr=0.3,0.1

Type RM Length L Ch R = 1,18429,151,151,151
BEGIN DESCRIPTION:
XS3639A
END DESCRIPTION:
XS GIS Cut Line= 3
      2821479.19      7049414.20      2821354.45      7049532.21
      2821346.93      7049814.30
#Sta/Elev= 30
  4836.9  469.57  4847.4  469.61  4854.7  469.37  4868.9  469.21  4875.8  469.37
  4897.2  468.95  4918.2  469.00  4932.4  468.73  4939.3  468.91  4958.9  468.35
  4981.2  466.79  4995.9  466.68  5004.0  465.65  5004.5  464.85  5009.5  464.85
  5010.0  465.65  5012.5  465.65  5021.4  466.59  5031.4  466.60  5041.4  467.14
  5058.7  468.35  5071.4  469.14  5081.4  468.82  5091.4  468.88  5111.4  469.31
  5154.9  469.67  5171.0  469.88  5176.0  469.72  5231.5  470.12  5290.8  470.18
#Mann=5,-1,0
  4836.9    0.05       0  4981.2    0.16       0  5004.0    0.07       0
  5010.0    0.16       0  5154.9    0.05       0
Bank Sta=4958.9,5058.7
Exp/Cntr=0.3,0.1

Type RM Length L Ch R = 1,18278,180,180,180
BEGIN DESCRIPTION:
Mapping XS 2b70d634
END DESCRIPTION:
XS GIS Cut Line= 3
      2821334.80      7049319.05      2821275.00      7049415.43
      2821165.90      7049690.77
#Sta/Elev= 30
  4899.7  468.47  4932.0  468.02  4953.8  466.60  4964.4  466.43  4983.9  466.25
  4989.8  464.95  4999.3  464.87  5002.2  463.74  5002.7  462.94  5007.7  462.94
  5008.2  463.74  5009.9  464.15  5027.8  464.01  5034.2  465.09  5052.1  465.03
  5057.5  464.32  5066.5  465.36  5076.4  465.75  5079.3  466.43  5081.8  467.03
  5130.4  467.78  5135.8  467.49  5160.2  468.58  5165.5  468.21  5184.5  468.45
  5189.9  468.01  5219.6  467.46  5292.3  469.69  5303.3  469.25  5309.3  469.92
#Mann=3,-1,0
  4899.7    0.16       0  5002.2    0.07       0  5008.2    0.16       0
Bank Sta=4964.4,5079.3
Exp/Cntr=0.3,0.1

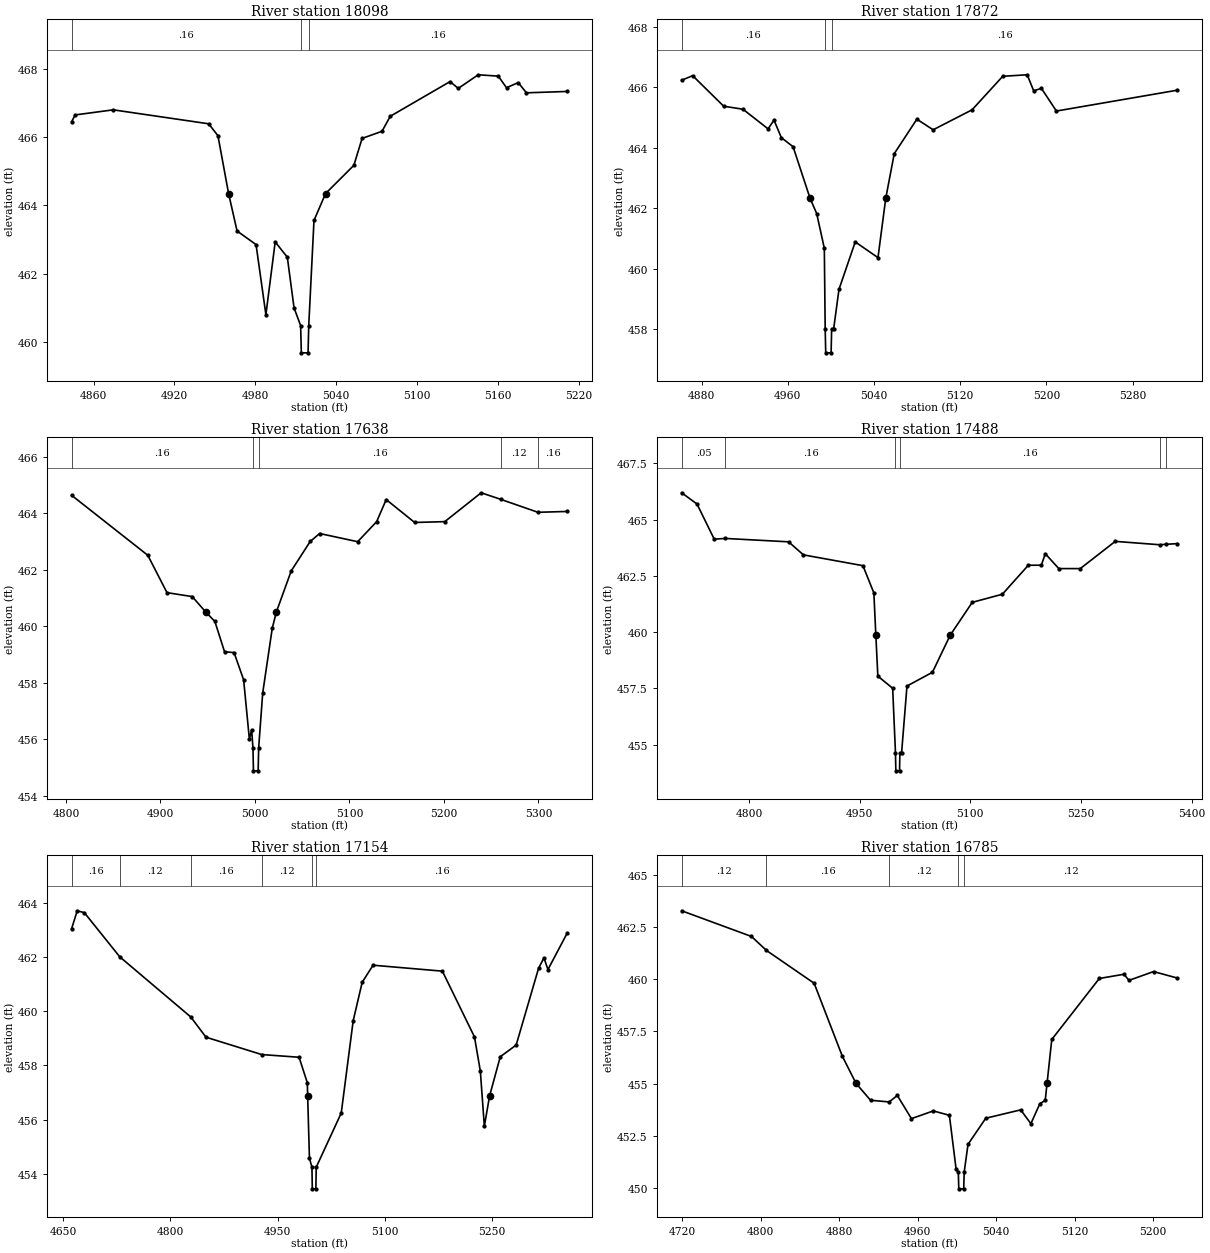
Type RM Length L Ch R = 1,18098,226,226,226
BEGIN DESCRIPTION:
XS3641A
END DESCRIPTION:
XS GIS Cut Line= 3
      2821291.83      7049198.13      2821181.82      7049314.43
      2821062.29      7049484.43
#Sta/Elev= 30
  4843.7  466.46  4846.3  466.66  4874.6  466.81  4945.4  466.40  4952.3  466.05
  4960.2  464.35  4966.5  463.25  4980.6  462.85  4987.9  460.79  4994.8  462.93
  5003.8  462.48  5008.8  460.99  5013.7  460.47  5014.2  459.67  5019.2  459.67
  5019.7  460.47  5023.6  463.56  5032.2  464.35  5053.2  465.18  5059.3  465.97
  5074.1  466.18  5080.2  466.62  5124.6  467.64  5130.7  467.44  5145.5  467.84
  5160.4  467.80  5166.5  467.46  5175.2  467.61  5181.3  467.31  5211.6  467.35
#Mann=3,-1,0
  4843.7    0.16       0  5013.7    0.07       0  5019.7    0.16       0
Bank Sta=4960.2,5032.2
Exp/Cntr=0.3,0.1

Type RM Length L Ch R = 1,17872,234,234,234
BEGIN DESCRIPTION:
XS3642A
END DESCRIPTION:
XS GIS Cut Line= 3
      2821199.69      7049086.06      2821072.93      7049141.79
      2820895.99      7049410.25
#Sta/Elev= 30
  4861.5  466.24  4871.7  466.39  4900.5  465.38  4918.4  465.28  4941.7  464.63
  4947.2  464.92  4954.0  464.34  4964.9  464.04  4980.7  462.33  4986.8  461.83
  4993.9  460.68  4994.7  458.02  4995.2  457.22  5000.2  457.22  5000.7  458.02
  5002.6  458.02  5007.5  459.32  5022.6  460.89  5043.7  460.37  5050.9  462.33
  5058.8  463.81  5079.8  464.95  5094.9  464.60  5131.0  465.26  5159.5  466.37
  5182.2  466.42  5188.2  465.89  5195.4  465.97  5209.3  465.22  5321.5  465.91
#Mann=3,-1,0
  4861.5    0.16       0  4994.7    0.07       0  5000.7    0.16       0
Bank Sta=4980.7,5050.9
Exp/Cntr=0.3,0.1

Type RM Length L Ch R = 1,17638,150,150,150
BEGIN DESCRIPTION:
XS3643A
END DESCRIPTION:
XS GIS Cut Line= 3
      2821154.51      7049011.40      2820966.69      7048979.78
      2820634.35      7049013.34
#Sta/Elev= 30
  4806.0  464.63  4886.6  462.51  4906.9  461.19  4933.6  461.05  4947.8  460.51
  4957.6  460.17  4967.8  459.10  4977.9  459.07  4988.0  458.11  4994.1  456.01
  4996.5  456.34  4997.9  455.69  4998.4  454.89  5003.4  454.89  5003.9  455.69
  5008.2  457.64  5018.3  459.93  5022.7  460.51  5038.4  461.96  5058.5  463.00
  5068.5  463.28  5108.7  462.99  5128.8  463.70  5138.9  464.48  5169.0  463.67
  5200.9  463.70  5239.4  464.72  5259.9  464.49  5299.5  464.03  5330.5  464.06
#Mann=5,-1,0
  4806.0    0.16       0  4997.9    0.07       0  5003.9    0.16       0
  5259.9    0.12       0  5299.5    0.16       0
Bank Sta=4947.8,5022.7
Exp/Cntr=0.3,0.1

Type RM Length L Ch R = 1,17488,334,334,334
BEGIN DESCRIPTION:
XS3644A
END DESCRIPTION:
XS GIS Cut Line= 3
      2821298.73      7048807.14      2821006.53      7048844.33
      2820659.08      7048991.27
#Sta/Elev= 30
  4708.7  466.19  4729.5  465.69  4752.8  464.13  4768.0  464.16  4853.6  464.01
  4873.7  463.43  4954.4  462.95  4969.2  461.74  4971.9  459.86  4974.6  458.04
  4994.7  457.50  4998.5  454.63  4999.0  453.83  5004.0  453.83  5004.5  454.63
  5006.8  454.63  5014.1  457.60  5048.6  458.21  5072.7  459.86  5102.6  461.32
  5143.4  461.68  5178.6  462.97  5196.2  462.97  5201.6  463.48  5219.9  462.82
  5249.0  462.82  5296.4  464.03  5356.6  463.88  5365.5  463.90  5380.5  463.93
#Mann=6,-1,0
  4708.7    0.05       0  4768.0    0.16       0  4998.5    0.07       0
  5004.5    0.16       0  5356.6    0.12       0  5365.5    0.16       0
Bank Sta=4971.9,5072.7
Exp/Cntr=0.3,0.1

Type RM Length L Ch R = 1,17154,369,369,369
BEGIN DESCRIPTION:
XS3645A
END DESCRIPTION:
XS GIS Cut Line= 3
      2821112.78      7048653.11      2820783.43      7048669.04
      2820459.30      7048833.93
#Sta/Elev= 30
  4661.8  463.05  4669.6  463.71  4679.6  463.64  4729.1  462.01  4828.4  459.79
  4849.8  459.04  4927.7  458.40  4980.0  458.30  4991.5  457.36  4992.0  456.87
  4994.5  454.57  4998.0  454.24  4998.5  453.44  5003.5  453.44  5004.0  454.24
  5039.0  456.24  5055.7  459.65  5068.3  461.07  5083.5  461.70  5180.5  461.48
  5225.4  459.05  5233.6  457.79  5239.2  455.75  5246.5  456.87  5261.5  458.32
  5283.7  458.75  5315.1  461.59  5322.6  461.97  5328.2  461.54  5355.2  462.89
#Mann=6,-1,0
  4661.8    0.16       0  4729.1    0.12       0  4828.4    0.16       0
  4927.7    0.12       0  4998.0    0.07       0  5004.0    0.16       0
Bank Sta=4992,5246.5
Exp/Cntr=0.3,0.1

Type RM Length L Ch R = 1,16785,225,225,225
BEGIN DESCRIPTION:
XS3646A
END DESCRIPTION:
XS GIS Cut Line= 3
      2821115.44      7048594.69      2820905.60      7048424.70
      2820685.13      7048342.35
#Sta/Elev= 30
  4719.4  463.27  4790.6  462.04  4805.9  461.37  4854.5  459.80  4883.3  456.30
  4897.2  455.01  4912.0  454.20  4931.0  454.12  4939.3  454.43  4953.7  453.32
  4976.0  453.69  4992.4  453.48  4999.2  450.92  5001.5  450.76  5002.0  449.96
  5007.0  449.96  5007.5  450.76  5011.4  452.09  5029.5  453.34  5065.1  453.74
  5075.5  453.08  5084.7  454.04  5090.1  454.19  5092.0  455.01  5096.8  457.11
  5145.3  460.03  5170.3  460.23  5175.6  459.94  5200.6  460.36  5224.8  460.05
#Mann=5,-1,0
  4719.4    0.12       0  4805.9    0.16       0  4931.0    0.12       0
  5001.5    0.07       0  5007.5    0.12       0
Bank Sta=4897.2,5092
Exp/Cntr=0.3,0.1

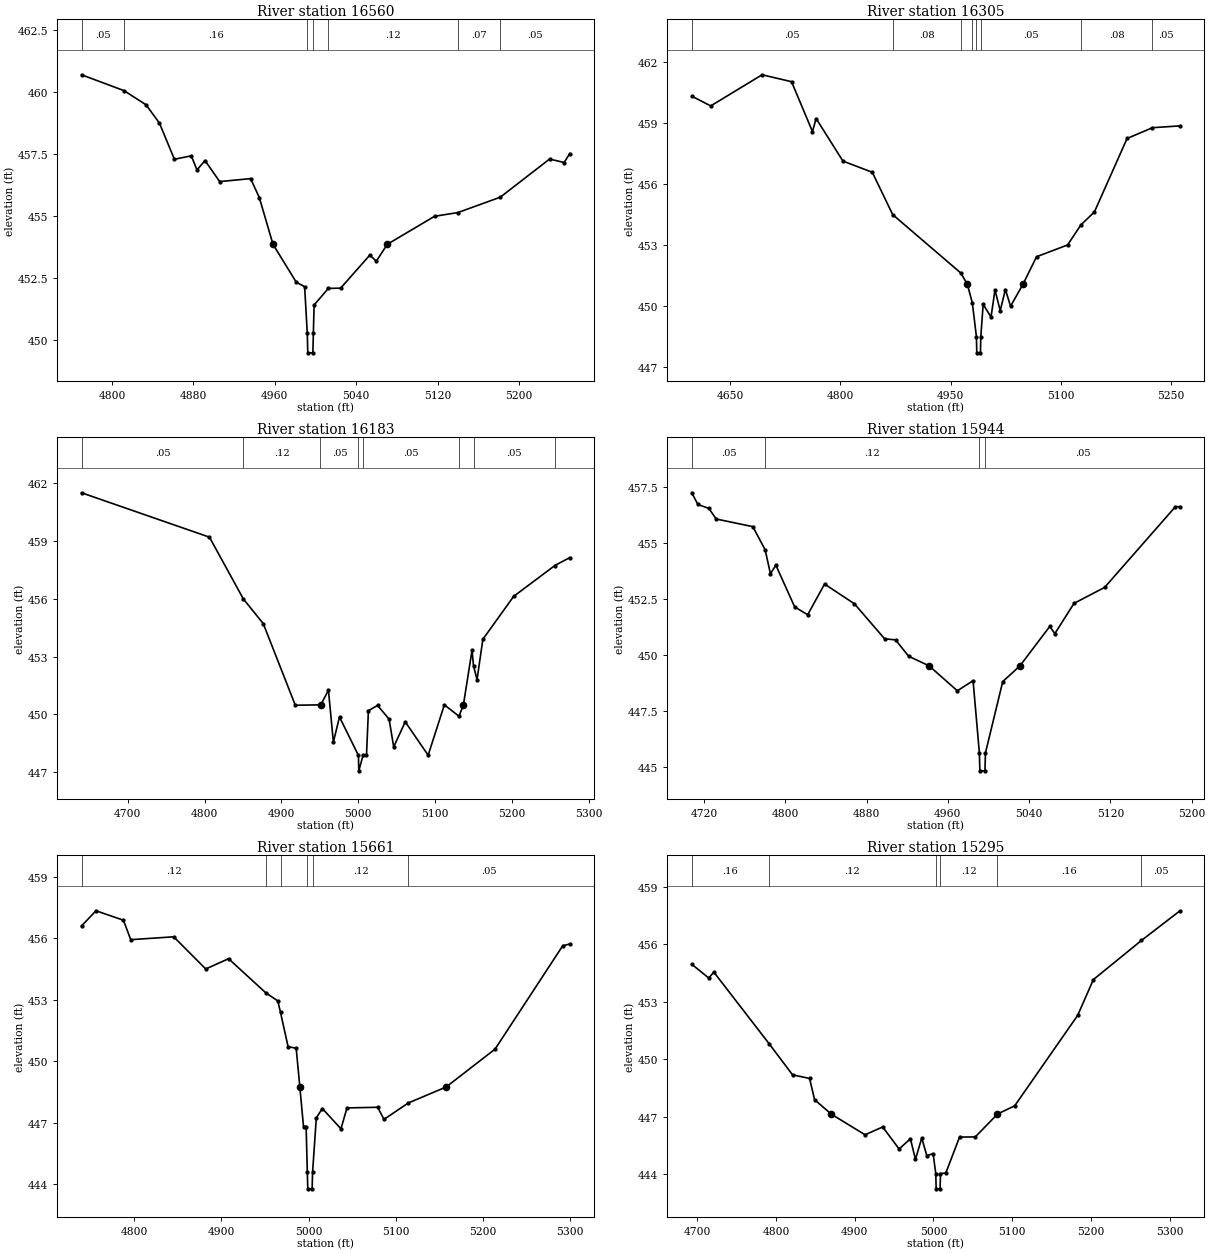
Type RM Length L Ch R = 1,16560,255,255,255
BEGIN DESCRIPTION:
XS3648A
END DESCRIPTION:
XS GIS Cut Line= 3
      2821070.28      7048443.30      2820966.69      7048238.78
      2820775.45      7048076.76
#Sta/Elev= 30
  4770.0  460.69  4811.8  460.05  4833.4  459.48  4846.6  458.74  4861.3  457.28
  4877.9  457.42  4883.5  456.85  4891.4  457.23  4905.8  456.38  4936.2  456.50
  4944.8  455.73  4958.2  453.85  4981.1  452.32  4989.3  452.14  4991.9  450.27
  4992.4  449.47  4997.4  449.47  4997.9  450.27  4998.6  451.40  5012.6  452.07
  5024.7  452.08  5053.3  453.41  5059.8  453.17  5070.6  453.85  5117.0  454.98
  5139.9  455.13  5181.6  455.75  5230.1  457.29  5244.4  457.15  5249.9  457.51
#Mann=7,-1,0
  4770.0    0.05       0  4811.8    0.16       0  4991.9    0.07       0
  4997.9    0.16       0  5012.6    0.12       0  5139.9    0.07       0
  5181.6    0.05       0
Bank Sta=4958.2,5070.6
Exp/Cntr=0.3,0.1

Type RM Length L Ch R = 1,16305,122,122,122
BEGIN DESCRIPTION:
XS3647A
END DESCRIPTION:
XS GIS Cut Line= 5
      2821104.80      7048400.80      2821096.83      7048121.92
      2821043.71      7048007.72      2820990.59      7047954.60
      2820833.92      7047856.35
#Sta/Elev= 30
  4597.5  460.33  4623.3  459.85  4693.3  461.38  4733.4  461.04  4761.9  458.59
  4766.9  459.23  4803.4  457.14  4843.4  456.59  4871.2  454.51  4964.0  451.64
  4972.9  451.08  4979.6  450.18  4985.2  448.52  4985.7  447.72  4990.7  447.72
  4991.2  448.52  4994.4  450.10  5005.1  449.48  5010.5  450.81  5017.6  449.79
  5024.7  450.83  5031.7  450.01  5048.5  451.08  5067.1  452.44  5109.4  453.02
  5127.4  454.00  5145.9  454.64  5190.4  458.25  5225.0  458.78  5262.5  458.87
#Mann=8,-1,0
  4597.5    0.05       0  4871.2    0.08       0  4964.0    0.16       0
  4979.6    0.05       0  4985.2    0.04       0  4991.2    0.05       0
  5127.4    0.08       0  5225.0    0.05       0
Bank Sta=4972.9,5048.5
Exp/Cntr=0.3,0.1

Type RM Length L Ch R = 1,16183,239,239,239
BEGIN DESCRIPTION:
XS3649A
END DESCRIPTION:
XS GIS Cut Line= 5
      2821163.23      7048241.43      2821160.57      7047997.10
      2821078.24      7047896.17      2820964.03      7047819.15
      2820849.88      7047774.02
#Sta/Elev= 30
  4639.9  461.49  4806.3  459.19  4850.4  455.99  4876.3  454.71  4918.0  450.48
  4950.7  450.50  4950.9  450.48  4961.1  451.26  4967.5  448.57  4975.5  449.87
  5000.1  447.88  5000.6  447.08  5006.1  447.88  5010.6  447.89  5013.1  450.20
  5025.0  450.47  5040.0  449.76  5046.0  448.32  5061.0  449.62  5090.8  447.89
  5111.9  450.50  5130.9  449.91  5136.6  450.48  5147.9  453.33  5149.8  452.53
  5154.4  451.81  5162.0  453.90  5202.0  456.12  5255.6  457.72  5275.0  458.13
#Mann=8,-1,0
  4639.9    0.05       0  4850.4    0.12       0  4950.7    0.05       0
  5000.1    0.04       0  5006.1    0.05       0  5130.9    0.16       0
  5149.8    0.05       0  5255.6    0.08       0
Bank Sta=4950.9,5136.6
Exp/Cntr=0.3,0.1

Type RM Length L Ch R = 1,15944,283,283,283
BEGIN DESCRIPTION:
XS3650A
END DESCRIPTION:
XS GIS Cut Line= 3
      2821330.59      7047829.79      2821078.24      7047726.19
      2820871.04      7047710.25
#Sta/Elev= 30
  4707.9  457.24  4713.9  456.72  4724.8  456.54  4731.9  456.07  4768.0  455.73
  4780.2  454.69  4785.3  453.63  4790.7  454.01  4809.2  452.15  4822.0  451.80
  4838.6  453.17  4868.0  452.29  4897.7  450.73  4908.5  450.68  4921.4  449.95
  4941.6  449.52  4969.3  448.41  4984.8  448.86  4991.0  445.64  4991.5  444.84
  4996.5  444.84  4997.0  445.64  5014.0  448.82  5030.9  449.52  5060.3  451.28
  5065.3  450.96  5084.2  452.31  5114.3  453.02  5184.0  456.62  5188.5  456.62
#Mann=4,-1,0
  4707.9    0.05       0  4780.2    0.12       0  4991.0    0.03       0
  4997.0    0.05       0
Bank Sta=4941.6,5030.9
Exp/Cntr=0.3,0.1

Type RM Length L Ch R = 1,15661,366,366,366
BEGIN DESCRIPTION:
XS3651A
END DESCRIPTION:
XS GIS Cut Line= 3
      2821338.52      7047375.61      2821094.17      7047457.95
      2820873.70      7047665.14
#Sta/Elev= 30
  4739.4  456.60  4756.0  457.34  4787.5  456.88  4795.9  455.93  4845.2  456.07
  4882.0  454.50  4908.2  455.00  4950.8  453.34  4964.7  452.94  4967.8  452.38
  4976.5  450.71  4985.8  450.63  4990.0  448.74  4994.2  446.81  4997.2  446.81
  4998.6  444.57  4999.1  443.77  5004.1  443.77  5004.6  444.57  5008.9  447.23
  5015.8  447.69  5037.2  446.70  5044.1  447.72  5079.3  447.75  5086.6  447.16
  5114.5  447.96  5157.9  448.74  5214.1  450.59  5291.7  455.63  5299.8  455.72
#Mann=6,-1,0
  4739.4    0.12       0  4950.8    0.16       0  4967.8    0.12       0
  4998.6    0.07       0  5004.6    0.12       0  5114.5    0.05       0
Bank Sta=4990,5157.9
Exp/Cntr=0.3,0.1

Type RM Length L Ch R = 1,15295,421,421,421
BEGIN DESCRIPTION:
UNT 090 in LFCCL Watershed 21.0
END DESCRIPTION:
XS GIS Cut Line= 3
      2821024.98      7047125.03      2820825.00      7047375.00
      2820825.00      7047674.98
#Sta/Elev= 30
  4693.0  454.95  4714.6  454.23  4721.0  454.54  4791.1  450.81  4821.0  449.18
  4842.6  448.99  4849.0  447.88  4870.2  447.13  4913.1  446.05  4935.5  446.46
  4956.3  445.31  4970.7  445.84  4977.1  444.77  4985.1  445.88  4991.5  444.96
  4999.5  445.07  5002.9  444.03  5003.4  443.23  5008.4  443.23  5008.9  444.03
  5015.6  444.05  5033.1  445.93  5053.1  445.94  5080.3  447.09  5081.1  447.13
  5103.1  447.56  5183.1  452.28  5203.1  454.15  5264.1  456.19  5313.1  457.74
#Mann=6,-1,0
  4693.0    0.16       0  4791.1    0.12       0  5002.9    0.07       0
  5008.9    0.12       0  5080.3    0.16       0  5264.1    0.05       0
Bank Sta=4870.2,5081.1
Exp/Cntr=0.3,0.1

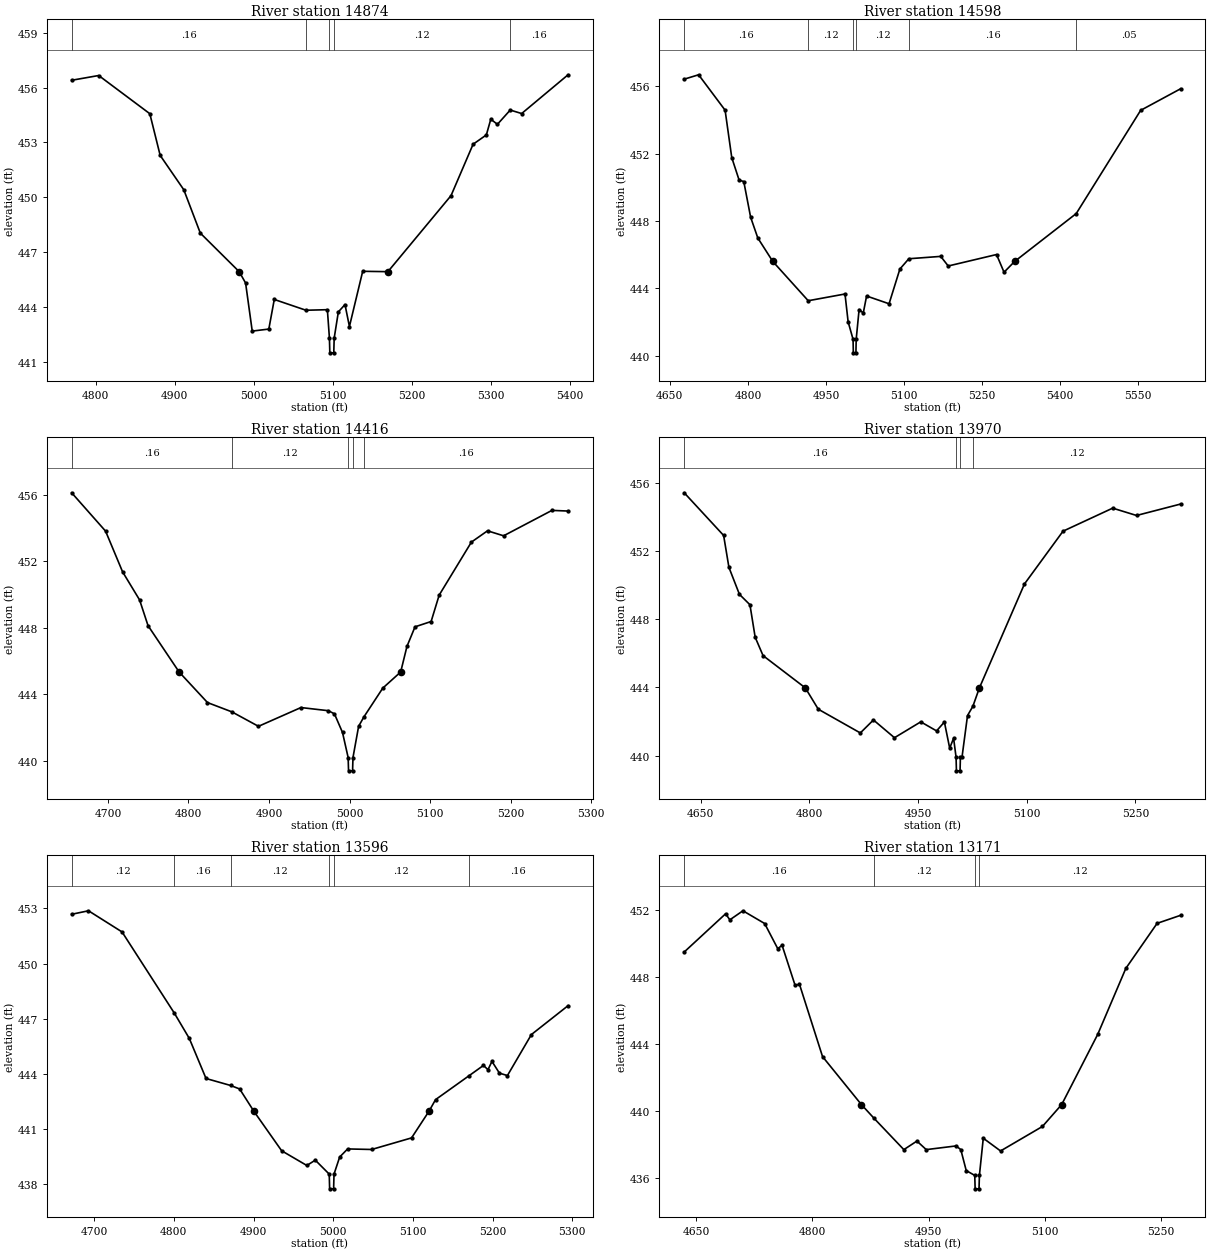
Type RM Length L Ch R = 1,14874,276,276,276
BEGIN DESCRIPTION:
UNT 090 in LFCCL Watershed 20.0
END DESCRIPTION:
XS GIS Cut Line= 3
      2820840.50      7046833.44      2820675.00      7047075.00
      2820525.01      7047374.98
#Sta/Elev= 30
  4769.4  456.40  4803.6  456.66  4868.3  454.57  4881.4  452.29  4911.3  450.41
  4932.2  448.04  4981.4  445.93  4989.5  445.31  4997.9  442.68  5018.9  442.79
  5025.8  444.41  5065.9  443.82  5093.0  443.85  5095.6  442.29  5096.1  441.49
  5101.1  441.49  5101.6  442.29  5106.9  443.73  5115.3  444.13  5120.9  442.93
  5137.7  445.95  5169.6  445.93  5249.5  450.09  5277.4  452.90  5294.2  453.41
  5299.8  454.27  5308.2  453.99  5324.4  454.77  5338.9  454.58  5397.6  456.70
#Mann=5,-1,0
  4769.4    0.16       0  5065.9    0.12       0  5095.6    0.07       0
  5101.6    0.12       0  5324.4    0.16       0
Bank Sta=4981.4,5169.6
Exp/Cntr=0.3,0.1

Type RM Length L Ch R = 1,14598,182,182,182
BEGIN DESCRIPTION:
Mapping XS 6bf81ab6
END DESCRIPTION:
XS GIS Cut Line= 3
      2820790.58      7046812.83      2820519.32      7046997.29
      2820029.94      7047387.92
#Sta/Elev= 30
  4677.6  456.41  4705.3  456.67  4756.2  454.57  4769.0  451.76  4783.2  450.42
  4792.1  450.34  4805.3  448.22  4819.1  446.99  4847.9  445.60  4916.0  443.27
  4986.7  443.67  4992.7  442.02  5002.2  440.98  5002.7  440.18  5007.7  440.18
  5008.2  440.98  5013.8  442.75  5021.8  442.54  5028.2  443.55  5071.4  443.09
  5092.2  445.15  5109.4  445.76  5170.7  445.90  5185.1  445.33  5278.0  446.01
  5292.4  444.96  5312.8  445.60  5431.2  448.44  5555.0  454.56  5631.8  455.84
#Mann=6,-1,0
  4677.6    0.16       0  4916.0    0.12       0  5002.2    0.07       0
  5008.2    0.12       0  5109.4    0.16       0  5431.2    0.05       0
Bank Sta=4847.9,5312.8
Exp/Cntr=0.3,0.1

Type RM Length L Ch R = 1,14416,446,446,446
BEGIN DESCRIPTION:
UNT 090 in LFCCL Watershed 19.0
END DESCRIPTION:
XS GIS Cut Line= 3
      2820724.96      7046775.01      2820425.00      7046875.00
      2820124.98      7046875.00
#Sta/Elev= 30
  4655.0  456.12  4697.1  453.81  4718.2  451.36  4739.3  449.67  4749.8  448.12
  4788.4  445.33  4823.6  443.49  4853.9  442.93  4886.9  442.06  4939.6  443.19
  4973.7  443.00  4981.2  442.81  4991.2  441.69  4998.2  440.18  4998.7  439.38
  5003.7  439.38  5004.2  440.18  5011.2  442.06  5017.8  442.63  5041.2  444.36
  5063.4  445.33  5071.2  446.87  5081.2  448.05  5101.2  448.37  5111.2  449.96
  5151.2  453.15  5171.2  453.83  5191.2  453.53  5251.2  455.06  5271.2  455.02
#Mann=5,-1,0
  4655.0    0.16       0  4853.9    0.12       0  4998.2    0.07       0
  5004.2    0.12       0  5017.8    0.16       0
Bank Sta=4788.4,5063.4
Exp/Cntr=0.3,0.1

Type RM Length L Ch R = 1,13970,374,374,374
BEGIN DESCRIPTION:
UNT 090 in LFCCL Watershed 18.0
END DESCRIPTION:
XS GIS Cut Line= 3
      2820725.02      7046725.01      2820375.00      7046575.00
      2820075.05      7046525.01
#Sta/Elev= 30
  4627.4  455.40  4681.8  452.90  4689.1  451.03  4703.6  449.45  4718.1  448.84
  4725.3  446.94  4736.2  445.86  4794.5  443.97  4812.4  442.72  4870.4  441.33
  4888.5  442.09  4917.5  441.05  4953.8  441.98  4975.6  441.45  4986.4  441.97
  4993.7  440.44  4999.1  441.02  5002.5  439.91  5003.0  439.11  5008.0  439.11
  5008.5  439.91  5010.7  439.91  5018.3  442.35  5025.7  442.89  5034.7  443.97
  5096.9  450.06  5150.1  453.15  5218.6  454.50  5251.5  454.07  5312.3  454.74
#Mann=4,-1,0
  4627.4    0.16       0  5002.5    0.07       0  5008.5    0.16       0
  5025.7    0.12       0
Bank Sta=4794.5,5034.7
Exp/Cntr=0.3,0.1

Type RM Length L Ch R = 1,13596,425,425,425
BEGIN DESCRIPTION:
UNT 090 in LFCCL Watershed 17.0
END DESCRIPTION:
XS GIS Cut Line= 3
      2820874.99      7046375.00      2820575.00      7046275.00
      2820269.13      7046297.24
#Sta/Elev= 30
  4671.8  452.68  4692.9  452.87  4735.0  451.72  4800.7  447.30  4819.4  445.93
  4840.4  443.75  4871.3  443.37  4882.6  443.18  4900.4  441.97  4935.3  439.82
  4966.9  439.02  4977.5  439.31  4995.0  438.55  4995.5  437.75  5000.5  437.75
  5001.0  438.55  5008.1  439.48  5018.1  439.92  5048.2  439.89  5098.3  440.52
  5120.2  441.97  5128.4  442.60  5170.1  443.89  5188.5  444.46  5194.2  444.23
  5199.2  444.68  5208.6  444.04  5218.6  443.91  5248.7  446.14  5294.7  447.71
#Mann=6,-1,0
  4671.8    0.12       0  4800.7    0.16       0  4871.3    0.12       0
  4995.0    0.07       0  5001.0    0.12       0  5170.1    0.16       0
Bank Sta=4900.4,5120.2
Exp/Cntr=0.3,0.1

Type RM Length L Ch R = 1,13171,306,306,306
BEGIN DESCRIPTION:
UNT 090 in LFCCL Watershed 16.0
END DESCRIPTION:
XS GIS Cut Line= 3
      2820825.03      7046125.01      2820497.38      7045963.26
      2820224.95      7045924.99
#Sta/Elev= 30
  4634.6  449.47  4688.0  451.75  4693.5  451.39  4710.4  451.93  4738.4  451.17
  4755.3  449.67  4760.9  449.87  4777.7  447.48  4783.3  447.55  4813.1  443.23
  4863.2  440.37  4879.1  439.57  4918.0  437.68  4934.9  438.19  4946.9  437.68
  4985.4  437.90  4991.5  437.68  4998.5  436.43  5009.5  436.14  5010.0  435.34
  5015.0  435.34  5015.5  436.14  5020.5  438.36  5042.8  437.60  5096.8  439.06
  5121.7  440.37  5168.1  444.55  5204.4  448.49  5244.8  451.18  5275.1  451.66
#Mann=4,-1,0
  4634.6    0.16       0  4879.1    0.12       0  5009.5    0.07       0
  5015.5    0.12       0
Bank Sta=4863.2,5121.7
Exp/Cntr=0.3,0.1