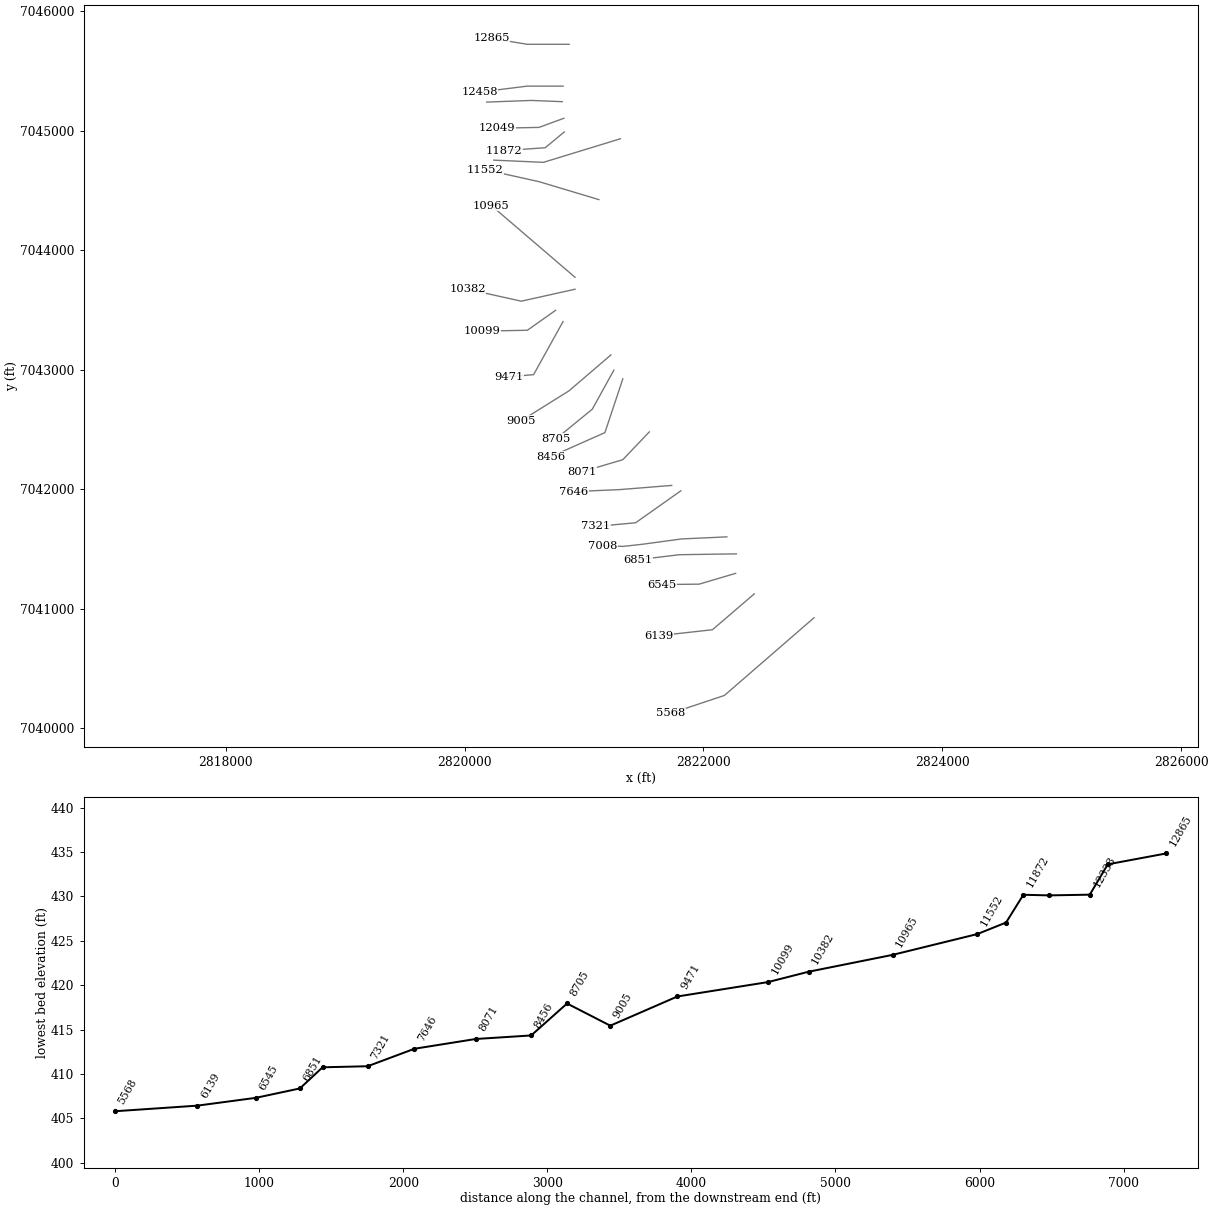
HEC-RAS study UNT 090 in LFCCL Watershed.prj: UNT 090 in LFCCL Watershed Base Level Engineering

--- UNT 090 in LFCCL Watershed.g01 (geometry) --- (continued)

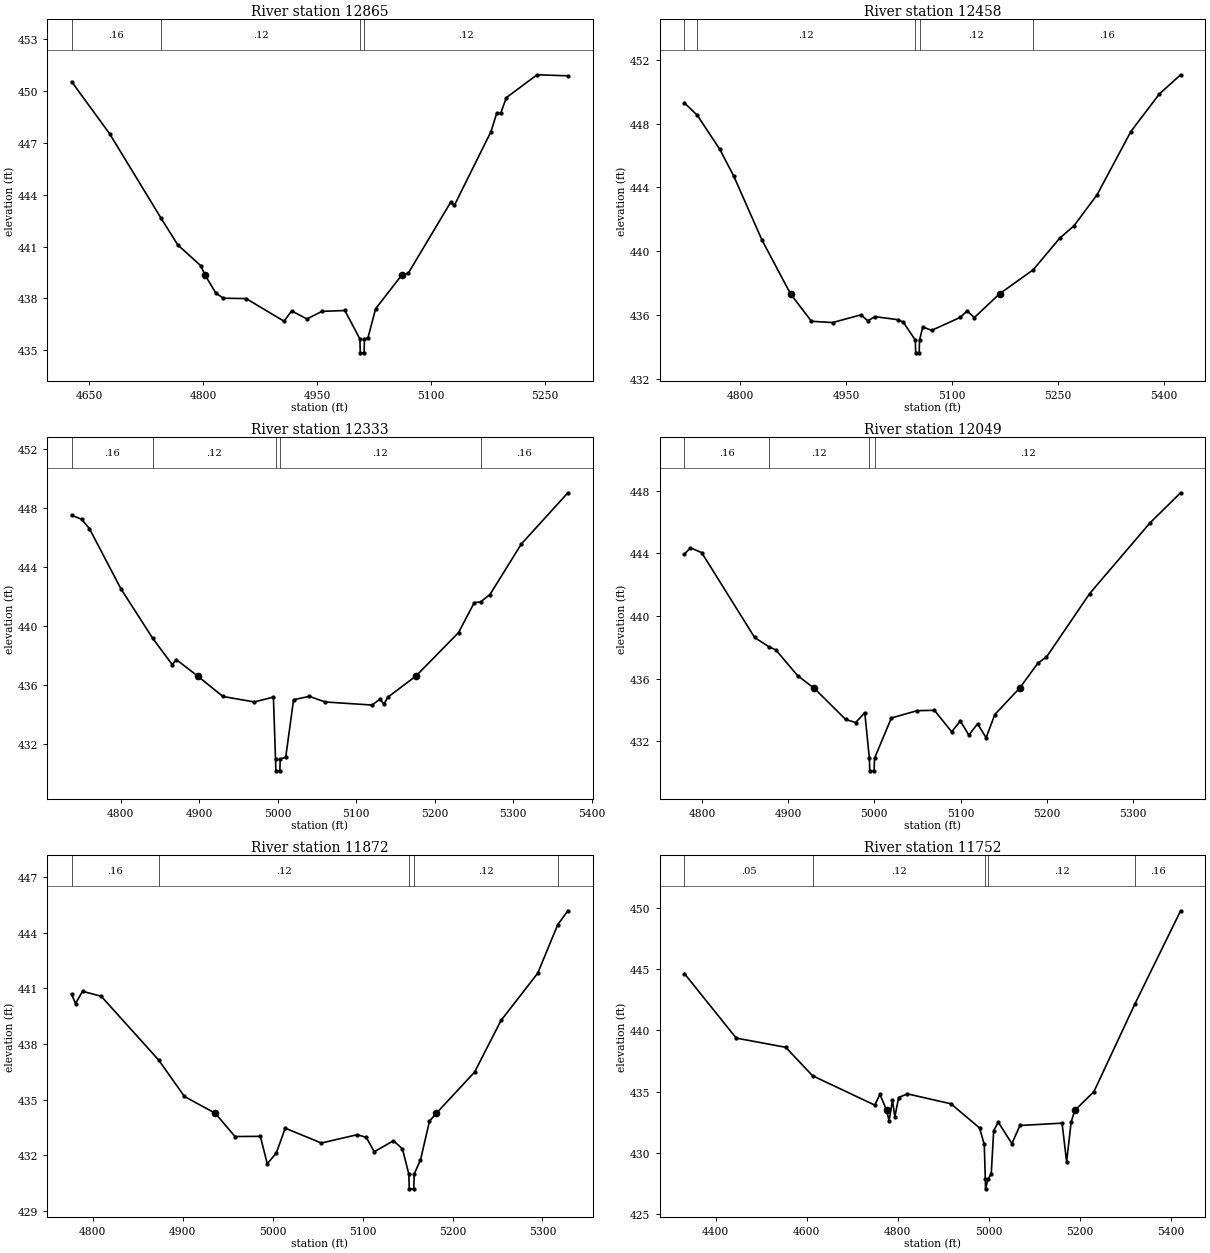
Type RM Length L Ch R = 1,12865,407,407,407
BEGIN DESCRIPTION:
UNT 090 in LFCCL Watershed 15.0
END DESCRIPTION:
XS GIS Cut Line= 3
      2820875.03      7045725.00      2820525.00      7045725.00
      2820224.97      7045775.01
#Sta/Elev= 30
  4626.6  450.54  4676.6  447.53  4744.6  442.63  4766.6  441.09  4796.6  439.90
  4802.5  439.35  4816.6  438.31  4826.6  438.01  4856.6  437.99  4906.6  436.68
  4916.6  437.28  4936.6  436.81  4956.6  437.25  4986.8  437.30  5006.6  435.65
  5007.1  434.85  5012.1  434.85  5012.6  435.65  5017.2  435.71  5027.3  437.40
  5061.8  439.35  5070.4  439.46  5126.2  443.56  5131.2  443.39  5179.4  447.65
  5187.0  448.72  5192.1  448.70  5199.7  449.62  5240.2  450.94  5280.8  450.88
#Mann=4,-1,0
  4626.6    0.16       0  4744.6    0.12       0  5006.6    0.07       0
  5012.6    0.12       0
Bank Sta=4802.5,5061.8
Exp/Cntr=0.3,0.1

Type RM Length L Ch R = 1,12458,125,125,125
BEGIN DESCRIPTION:
UNT 090 in LFCCL Watershed 14.0
END DESCRIPTION:
XS GIS Cut Line= 3
      2820824.99      7045375.00      2820525.00      7045375.00
      2820125.00      7045325.00
#Sta/Elev= 30
  4720.6  449.30  4738.7  448.53  4770.6  446.40  4790.6  444.70  4830.6  440.69
  4871.0  437.32  4900.6  435.60  4930.6  435.52  4970.6  436.00  4980.6  435.63
  4990.6  435.89  5023.1  435.70  5030.7  435.55  5047.8  434.42  5048.3  433.62
  5053.3  433.62  5053.8  434.42  5058.4  435.24  5071.0  435.03  5111.3  435.84
  5121.4  436.25  5131.4  435.83  5167.1  437.32  5214.9  438.83  5252.4  440.81
  5272.5  441.58  5305.3  443.53  5353.2  447.50  5393.5  449.85  5423.7  451.06
#Mann=5,-1,0
  4720.6    0.16       0  4738.7    0.12       0  5047.8    0.07       0
  5053.8    0.12       0  5214.9    0.16       0
Bank Sta=4871,5167.1
Exp/Cntr=0.3,0.1

Type RM Length L Ch R = 1,12333,284,284,284
BEGIN DESCRIPTION:
XS3652A
END DESCRIPTION:
XS GIS Cut Line= 3
      2820817.62      7045244.79      2820560.68      7045255.21
      2820185.69      7045241.32
#Sta/Elev= 30
  4737.5  447.49  4750.1  447.22  4760.1  446.59  4800.2  442.52  4840.6  439.18
  4865.7  437.38  4870.7  437.73  4898.1  436.61  4930.3  435.23  4970.3  434.86
  4994.6  435.19  4997.3  431.00  4997.8  430.20  5002.8  430.20  5003.3  431.00
  5010.3  431.12  5020.3  435.01  5040.4  435.24  5060.4  434.86  5120.4  434.65
  5130.4  435.05  5135.4  434.71  5140.4  435.18  5176.2  436.61  5230.5  439.55
  5250.5  441.57  5258.6  441.63  5270.5  442.12  5310.5  445.54  5369.9  449.01
#Mann=5,-1,0
  4737.5    0.16       0  4840.6    0.12       0  4997.3    0.07       0
  5003.3    0.12       0  5258.6    0.16       0
Bank Sta=4898.1,5176.2
Exp/Cntr=0.3,0.1

Type RM Length L Ch R = 1,12049,177,177,177
BEGIN DESCRIPTION:
XS3653A
END DESCRIPTION:
XS GIS Cut Line= 3
      2820831.54      7045105.91      2820623.18      7045029.51
      2820269.47      7045022.58
#Sta/Elev= 30
  4779.6  443.94  4786.6  444.35  4799.7  444.04  4861.1  438.63  4877.2  438.05
  4885.8  437.83  4911.0  436.19  4930.0  435.40  4966.7  433.40  4978.3  433.20
  4988.9  433.83  4994.2  430.92  4994.7  430.12  4999.7  430.12  5000.2  430.92
  5019.7  433.49  5049.7  433.96  5069.7  433.98  5089.7  432.61  5099.7  433.30
  5109.7  432.40  5119.7  433.12  5129.7  432.23  5139.7  433.71  5168.6  435.40
  5189.7  436.99  5199.7  437.38  5249.8  441.43  5319.8  445.94  5355.3  447.86
#Mann=4,-1,0
  4779.6    0.16       0  4877.2    0.12       0  4994.2    0.07       0
  5000.2    0.12       0
Bank Sta=4930,5168.6
Exp/Cntr=0.3,0.1

Type RM Length L Ch R = 1,11872,120,120,120
BEGIN DESCRIPTION:
XS3654A
END DESCRIPTION:
XS GIS Cut Line= 3
      2820834.98      7044991.31      2820675.26      7044859.37
      2820331.49      7044835.07
#Sta/Elev= 30
  4776.5  440.67  4780.8  440.18  4788.6  440.84  4809.4  440.57  4873.3  437.13
  4901.9  435.17  4936.3  434.26  4958.1  433.01  4986.3  433.02  4994.0  431.54
  5004.0  432.12  5014.0  433.46  5054.1  432.66  5094.2  433.11  5104.2  432.96
  5112.9  432.19  5134.3  432.78  5144.3  432.35  5151.4  430.99  5151.9  430.19
  5156.9  430.19  5157.4  430.99  5164.4  431.75  5174.4  433.84  5181.9  434.26
  5224.5  436.48  5254.0  439.27  5294.7  441.81  5317.0  444.43  5328.3  445.18
#Mann=5,-1,0
  4776.5    0.16       0  4873.3    0.12       0  5151.4    0.07       0
  5157.4    0.12       0  5317.0    0.16       0
Bank Sta=4936.3,5181.9
Exp/Cntr=0.3,0.1

Type RM Length L Ch R = 1,11752,200,200,200
BEGIN DESCRIPTION:
Mapping XS 48eb6663
END DESCRIPTION:
XS GIS Cut Line= 3
      2821304.93      7044934.57      2820660.38      7044737.09
      2820244.81      7044755.53
#Sta/Elev= 30
  4331.5  444.63  4445.4  439.36  4554.1  438.61  4613.0  436.29  4749.8  433.89
  4761.1  434.77  4775.8  433.46  4781.2  432.59  4788.6  434.29  4793.9  432.93
  4802.1  434.51  4821.4  434.81  4917.1  434.00  4979.9  432.03  4990.3  430.68
  4992.6  427.86  4993.1  427.06  4998.6  427.86  5005.6  428.29  5011.0  431.81
  5021.0  432.50  5051.0  430.75  5068.7  432.23  5161.2  432.42  5171.2  429.27
  5181.2  432.52  5189.1  433.46  5231.2  434.99  5321.5  442.17  5421.6  449.75
#Mann=5,-1,0
  4331.5    0.05       0  4613.0    0.12       0  4992.6    0.07       0
  4998.6    0.12       0  5321.5    0.16       0
Bank Sta=4775.8,5189.1
Exp/Cntr=0.3,0.1

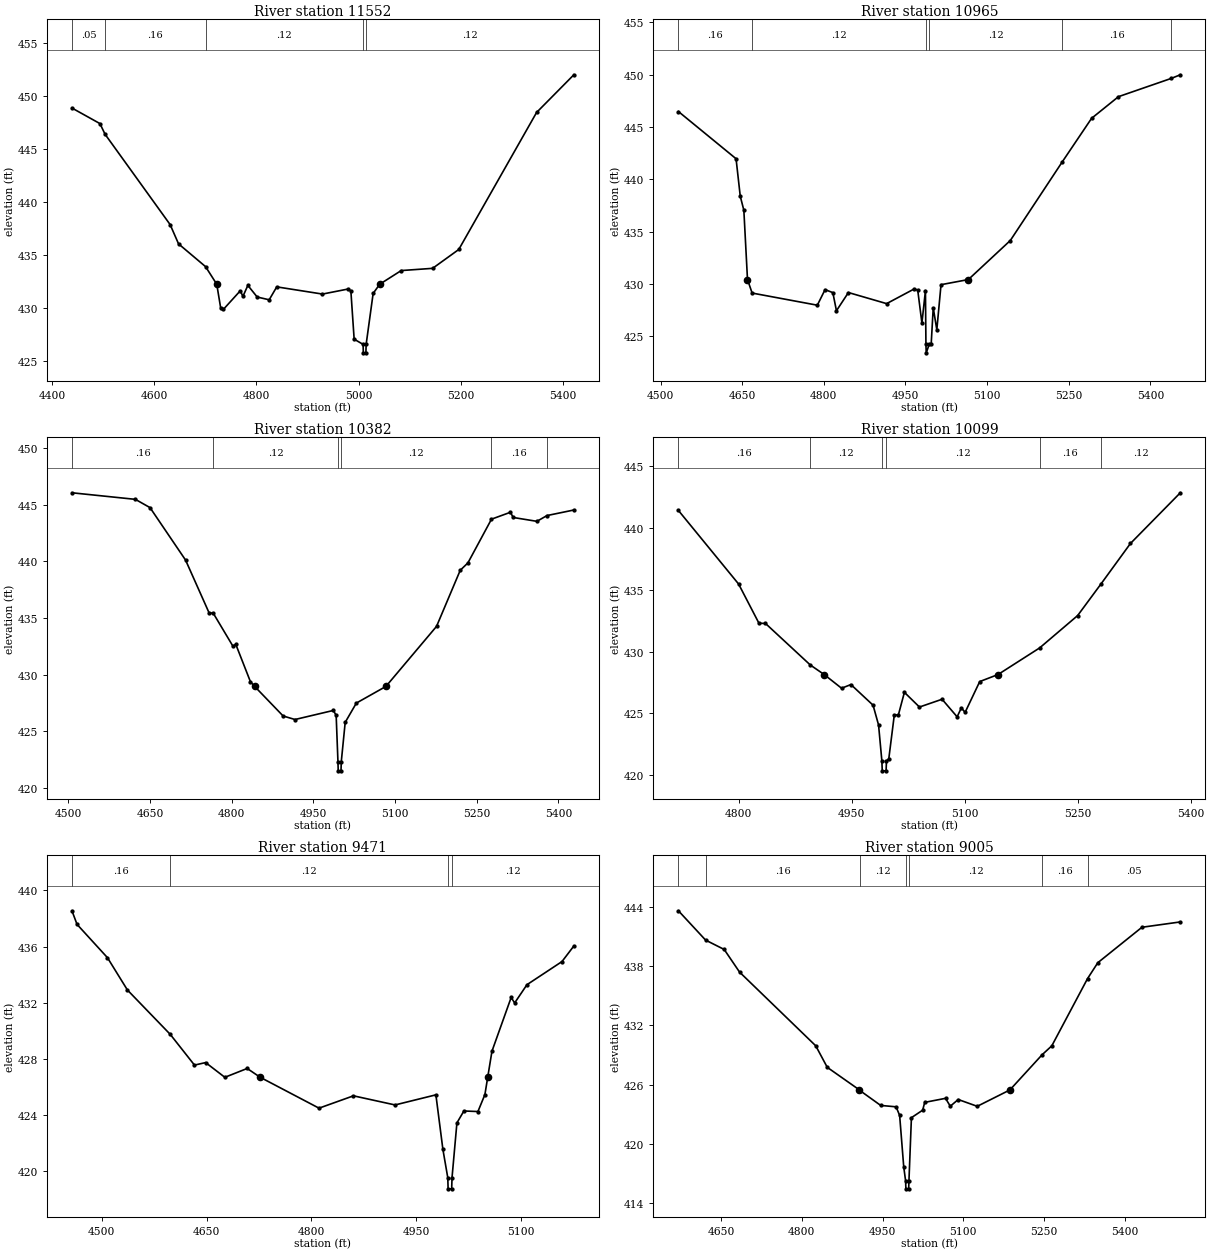
Type RM Length L Ch R = 1,11552,587,587,587
BEGIN DESCRIPTION:
UNT 090 in LFCCL Watershed 12.0
END DESCRIPTION:
XS GIS Cut Line= 3
      2821124.99      7044425.00      2820625.00      7044575.00
      2820174.98      7044675.00
#Sta/Elev= 30
  4438.6  448.88  4493.4  447.41  4503.5  446.40  4630.9  437.87  4647.4  436.05
  4700.3  433.90  4722.2  432.24  4730.0  429.97  4735.3  429.87  4768.3  431.62
  4773.5  431.09  4783.1  432.13  4801.4  431.03  4824.9  430.77  4839.7  431.99
  4929.3  431.31  4979.8  431.79  4984.9  431.59  4991.3  427.05  5008.8  426.56
  5009.3  425.76  5014.3  425.76  5014.8  426.56  5028.5  431.37  5041.4  432.24
  5083.5  433.53  5145.0  433.74  5196.2  435.52  5348.6  448.46  5421.6  452.02
#Mann=5,-1,0
  4438.6    0.05       0  4503.5    0.16       0  4700.3    0.12       0
  5008.8    0.07       0  5014.8    0.12       0
Bank Sta=4722.2,5041.4
Exp/Cntr=0.3,0.1

Type RM Length L Ch R = 1,10965,583,583,583
BEGIN DESCRIPTION:
UNT 090 in LFCCL Watershed 11.0
END DESCRIPTION:
XS GIS Cut Line= 3
      2820925.00      7043775.00      2820575.00      7044075.00
      2820224.96      7044375.03
#Sta/Elev= 30
  4532.9  446.47  4638.8  441.96  4646.5  438.38  4653.1  437.04  4659.8  430.42
  4668.3  429.13  4788.1  427.97  4802.3  429.46  4816.6  429.17  4823.2  427.44
  4845.2  429.18  4915.4  428.12  4965.9  429.52  4972.5  429.42  4980.2  426.27
  4986.7  429.37  4987.6  424.22  4988.1  423.42  4993.6  424.22  4997.2  424.22
  5001.0  427.73  5007.6  425.62  5015.3  429.93  5065.5  430.42  5142.6  434.15
  5238.4  441.69  5291.9  445.82  5341.3  447.89  5438.6  449.64  5454.9  449.98
#Mann=6,-1,0
  4532.9    0.16       0  4668.3    0.12       0  4987.6    0.07       0
  4993.6    0.12       0  5238.4    0.16       0  5438.6    0.12       0
Bank Sta=4659.8,5065.5
Exp/Cntr=0.3,0.1

Type RM Length L Ch R = 1,10382,283,283,283
BEGIN DESCRIPTION:
UNT 090 in LFCCL Watershed 10.0
END DESCRIPTION:
XS GIS Cut Line= 3
      2820924.95      7043674.99      2820475.00      7043575.00
      2820025.01      7043675.00
#Sta/Elev= 30
  4506.6  446.06  4623.1  445.48  4650.0  444.75  4715.3  440.12  4758.8  435.43
  4765.8  435.46  4802.3  432.52  4807.5  432.69  4834.4  429.39  4842.2  428.97
  4894.5  426.36  4916.3  426.05  4986.7  426.85  4991.9  426.42  4995.2  422.32
  4995.7  421.52  5000.8  421.52  5001.3  422.32  5008.5  425.80  5029.0  427.50
  5083.3  428.97  5176.3  434.27  5219.8  439.22  5233.9  439.87  5277.2  443.73
  5312.0  444.34  5317.1  443.88  5360.6  443.54  5379.2  444.05  5428.5  444.54
#Mann=6,-1,0
  4506.6    0.16       0  4765.8    0.12       0  4995.2    0.07       0
  5001.3    0.12       0  5277.2    0.16       0  5379.2    0.05       0
Bank Sta=4842.2,5083.3
Exp/Cntr=0.3,0.1

Type RM Length L Ch R = 1,10099,628,628,628
BEGIN DESCRIPTION:
XS3655A
END DESCRIPTION:
XS GIS Cut Line= 3
      2820762.10      7043498.28      2820525.96      7043331.60
      2820148.77      7043324.68
#Sta/Elev= 30
  4720.1  441.41  4800.0  435.46  4827.0  432.29  4835.7  432.27  4895.2  428.91
  4913.6  428.14  4936.7  427.03  4949.1  427.33  4978.5  425.66  4985.8  424.06
  4990.2  421.15  4990.7  420.35  4995.8  420.35  4996.3  421.15  4999.4  421.33
  5006.7  424.87  5012.1  424.87  5020.1  426.70  5040.1  425.51  5070.1  426.14
  5090.1  424.72  5095.7  425.44  5100.7  425.08  5120.1  427.57  5144.4  428.14
  5199.6  430.29  5250.1  432.91  5280.9  435.45  5320.2  438.74  5386.4  442.84
#Mann=6,-1,0
  4720.1    0.16       0  4895.2    0.12       0  4990.2    0.07       0
  4996.3    0.12       0  5199.6    0.16       0  5280.9    0.12       0
Bank Sta=4913.6,5144.4
Exp/Cntr=0.3,0.1

Type RM Length L Ch R = 1,9471,466,466,466
BEGIN DESCRIPTION:
XS3656A
END DESCRIPTION:
XS GIS Cut Line= 3
      2820824.56      7043404.50      2820578.04      7042960.07
      2820368.07      7042942.86
#Sta/Elev= 30
  4457.2  438.55  4464.5  437.58  4508.0  435.21  4536.7  432.90  4598.0  429.74
  4632.7  427.55  4648.7  427.73  4676.2  426.68  4708.2  427.31  4726.9  426.68
  4811.1  424.48  4860.4  425.36  4920.0  424.71  4978.5  425.43  4988.5  421.55
  4995.5  419.53  4996.0  418.73  5001.1  418.73  5001.6  419.53  5008.6  423.43
  5018.6  424.28  5038.7  424.24  5048.7  425.45  5052.7  426.68  5058.8  428.54
  5086.3  432.37  5091.3  431.98  5108.9  433.28  5159.1  434.93  5176.1  436.04
#Mann=4,-1,0
  4457.2    0.16       0  4598.0    0.12       0  4995.5    0.07       0
  5001.6    0.12       0
Bank Sta=4726.9,5052.7
Exp/Cntr=0.3,0.1

Type RM Length L Ch R = 1,9005,300,300,300
BEGIN DESCRIPTION:
UNT 090 in LFCCL Watershed 8.0
END DESCRIPTION:
XS GIS Cut Line= 3
      2821225.02      7043125.01      2820875.00      7042825.00
      2820475.00      7042575.00
#Sta/Elev= 30
  4570.6  443.61  4621.1  440.64  4655.7  439.69  4684.2  437.40  4825.8  429.93
  4847.2  427.75  4907.0  425.46  4908.4  425.38  4946.5  423.89  4975.1  423.75
  4981.7  422.88  4989.3  417.67  4992.8  416.24  4993.3  415.44  4998.5  415.44
  4999.0  416.24  5003.6  422.65  5024.5  423.41  5028.3  424.20  5067.0  424.61
  5075.8  423.81  5090.6  424.49  5125.9  423.80  5186.6  425.46  5246.2  429.01
  5264.5  429.93  5330.9  436.74  5350.0  438.35  5432.0  441.94  5503.3  442.48
#Mann=7,-1,0
  4570.6    0.05       0  4621.1    0.16       0  4908.4    0.12       0
  4992.8    0.07       0  4999.0    0.12       0  5246.2    0.16       0
  5330.9    0.05       0
Bank Sta=4907,5186.6
Exp/Cntr=0.3,0.1

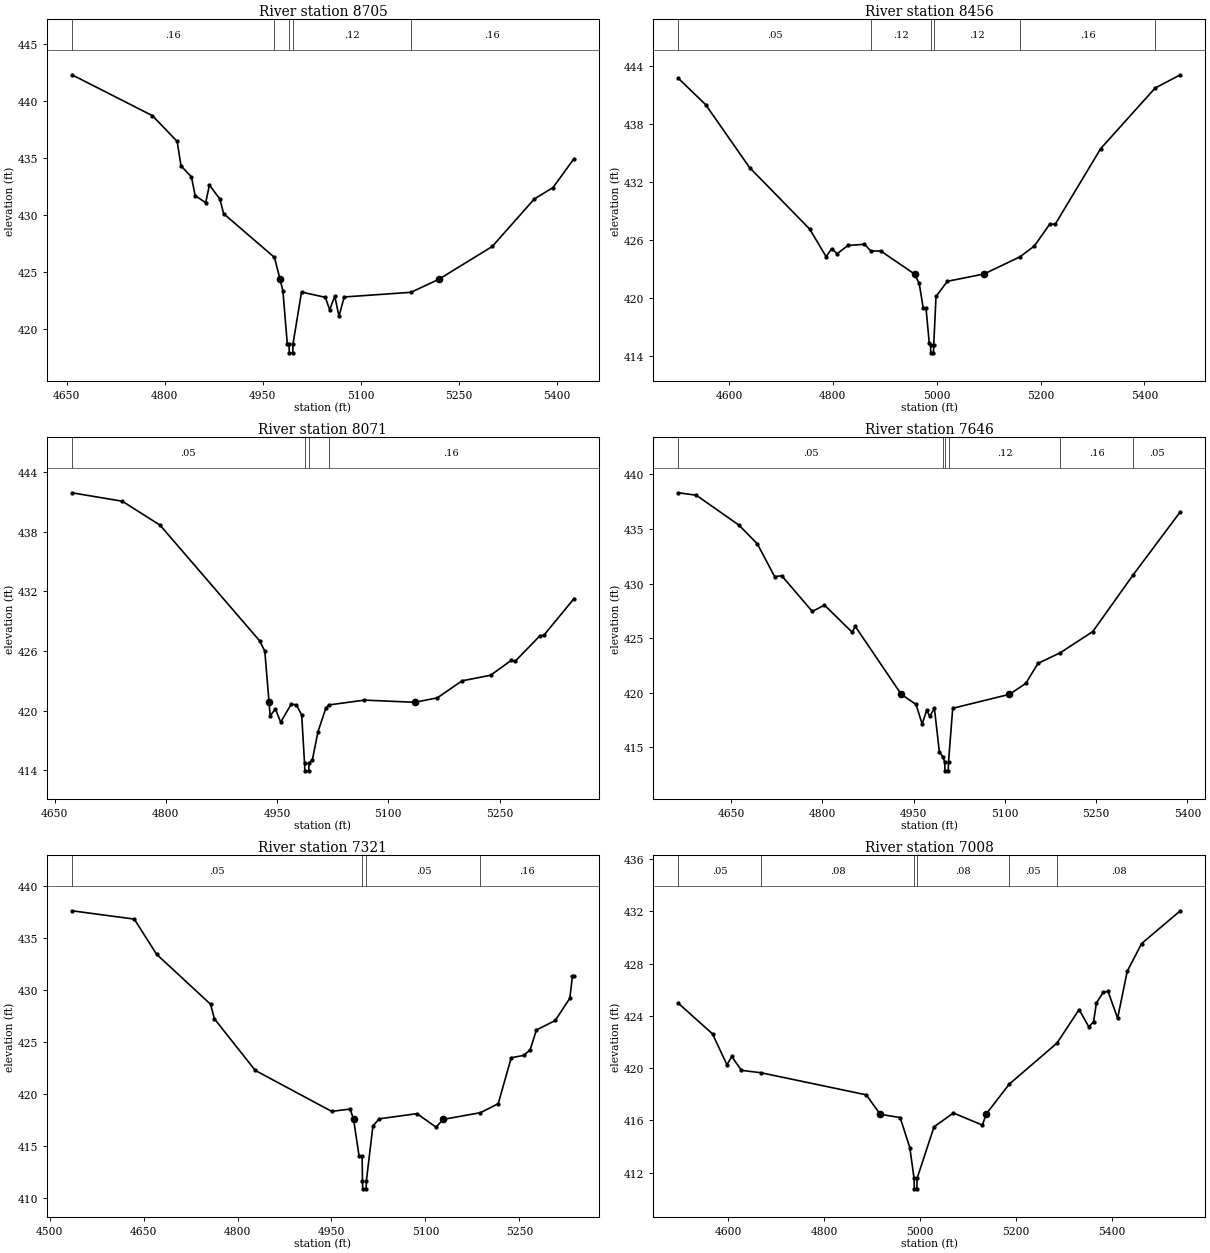
Type RM Length L Ch R = 1,8705,249,249,249
BEGIN DESCRIPTION:
XS3668A
END DESCRIPTION:
XS GIS Cut Line= 3
      2821249.91      7042997.39      2821069.36      7042671.01
      2820763.80      7042421.00
#Sta/Elev= 30
  4658.3  442.33  4781.5  438.74  4819.3  436.48  4825.1  434.34  4841.1  433.37
  4846.8  431.73  4862.9  431.11  4868.6  432.66  4884.6  431.43  4890.3  430.15
  4968.1  426.31  4976.7  424.38  4981.0  423.38  4987.7  418.74  4990.3  418.74
  4990.8  417.94  4996.0  417.94  4996.5  418.74  5009.5  423.27  5046.0  422.81
  5052.5  421.72  5060.4  422.91  5066.8  421.14  5074.7  422.84  5176.9  423.25
  5219.2  424.38  5301.3  427.27  5365.5  431.43  5394.2  432.44  5426.1  434.95
#Mann=5,-1,0
  4658.3    0.16       0  4968.1    0.12       0  4990.3    0.07       0
  4996.5    0.12       0  5176.9    0.16       0
Bank Sta=4976.7,5219.2
Exp/Cntr=0.3,0.1

Type RM Length L Ch R = 1,8456,385,385,385
BEGIN DESCRIPTION:
UNT 090 in LFCCL Watershed 7.0
END DESCRIPTION:
XS GIS Cut Line= 3
      2821324.99      7042924.97      2821175.00      7042475.00
      2820724.96      7042274.98
#Sta/Elev= 30
  4502.5  442.69  4555.2  439.96  4639.5  433.48  4755.4  427.12  4787.1  424.27
  4797.6  425.10  4808.2  424.58  4829.2  425.43  4860.9  425.55  4873.1  424.87
  4892.5  424.85  4957.3  422.48  4966.3  421.51  4974.2  418.92  4979.5  418.92
  4985.7  415.35  4988.1  415.14  4988.6  414.34  4993.8  414.34  4994.3  415.14
  4998.7  420.16  5020.6  421.73  5091.0  422.48  5160.2  424.25  5188.1  425.37
  5217.6  427.62  5228.5  427.64  5316.0  435.44  5420.8  441.69  5469.3  443.06
#Mann=6,-1,0
  4502.5    0.05       0  4873.1    0.12       0  4988.1    0.07       0
  4994.3    0.12       0  5160.2    0.16       0  5420.8    0.05       0
Bank Sta=4957.3,5091
Exp/Cntr=0.3,0.1

Type RM Length L Ch R = 1,8071,425,425,425
BEGIN DESCRIPTION:
XS3657A
END DESCRIPTION:
XS GIS Cut Line= 3
      2821546.81      7042480.93      2821324.57      7042248.26
      2820984.31      7042147.57
#Sta/Elev= 30
  4673.5  441.93  4741.3  441.08  4792.3  438.67  4926.6  427.02  4933.5  425.98
  4939.2  420.84  4940.7  419.47  4947.7  420.17  4954.9  418.84  4969.1  420.65
  4976.0  420.58  4983.2  419.57  4987.0  414.74  4987.5  413.94  4992.7  413.94
  4993.2  414.74  4997.6  415.05  5005.2  417.89  5015.7  420.23  5019.6  420.57
  5067.8  421.06  5135.8  420.84  5166.1  421.29  5199.4  423.00  5237.8  423.56
  5265.9  425.07  5271.1  424.98  5304.4  427.54  5309.6  427.58  5350.1  431.26
#Mann=4,-1,0
  4673.5    0.05       0  4987.0    0.03       0  4993.2    0.05       0
  5019.6    0.16       0
Bank Sta=4939.2,5135.8
Exp/Cntr=0.3,0.1

Type RM Length L Ch R = 1,7646,325,325,325
BEGIN DESCRIPTION:
XS3658A
END DESCRIPTION:
XS GIS Cut Line= 3
      2821734.25      7042032.98      2821303.74      7041998.26
      2820911.33      7041980.90
#Sta/Elev= 30
  4563.6  438.31  4592.9  438.09  4663.2  435.34  4693.3  433.63  4721.7  430.63
  4733.4  430.71  4783.6  427.44  4803.6  428.02  4849.1  425.54  4854.2  426.07
  4929.8  419.85  4954.1  418.92  4964.1  417.12  4971.5  418.39  4976.6  417.84
  4984.2  418.57  4992.4  414.58  4998.3  414.11  5001.1  413.64  5001.6  412.84
  5006.9  412.84  5007.4  413.64  5014.3  418.57  5107.6  419.85  5134.4  420.85
  5154.4  422.68  5191.2  423.66  5244.5  425.60  5310.8  430.79  5388.3  436.57
#Mann=6,-1,0
  4563.6    0.05       0  4998.3    0.12       0  5001.1    0.07       0
  5007.4    0.12       0  5191.2    0.16       0  5310.8    0.05       0
Bank Sta=4929.8,5107.6
Exp/Cntr=0.3,0.1

Type RM Length L Ch R = 1,7321,313,313,313
BEGIN DESCRIPTION:
XS3659A
END DESCRIPTION:
XS GIS Cut Line= 3
      2821810.69      7041987.85      2821432.21      7041720.49
      2821095.45      7041689.24
#Sta/Elev= 30
  4535.5  437.64  4635.0  436.84  4670.7  433.45  4756.9  428.64  4763.0  427.24
  4828.3  422.27  4950.2  418.33  4979.8  418.55  4985.3  417.56  4994.1  414.02
  4998.9  414.02  4999.5  411.67  5000.0  410.87  5005.3  410.87  5005.8  411.67
  5016.2  416.92  5026.2  417.61  5086.5  418.11  5117.0  416.81  5128.5  417.56
  5187.9  418.20  5216.3  419.07  5237.1  423.49  5257.2  423.72  5267.2  424.25
  5277.3  426.16  5307.4  427.08  5330.7  429.22  5334.8  431.33  5337.1  431.33
#Mann=4,-1,0
  4535.5    0.05       0  4999.5    0.03       0  5005.8    0.05       0
  5187.9    0.16       0
Bank Sta=4985.3,5128.5
Exp/Cntr=0.3,0.1

Type RM Length L Ch R = 1,7008,157,157,157
BEGIN DESCRIPTION:
XS3660A
END DESCRIPTION:
XS GIS Cut Line= 5
      2822196.06      7041602.43      2821817.62      7041585.07
      2821484.29      7041539.93      2821328.04      7041522.57
      2821154.40      7041529.51
#Sta/Elev= 30
  4496.7  424.96  4567.8  422.62  4597.9  420.25  4607.9  420.89  4627.9  419.83
  4669.2  419.64  4888.3  417.95  4917.3  416.46  4958.9  416.21  4979.1  413.90
  4987.9  411.55  4988.4  410.75  4993.7  410.75  4994.2  411.55  5029.5  415.50
  5069.9  416.56  5130.5  415.63  5137.8  416.46  5186.3  418.77  5285.7  421.91
  5331.9  424.48  5352.1  423.16  5362.1  423.55  5368.1  425.00  5382.2  425.80
  5392.2  425.88  5412.2  423.82  5432.2  427.41  5462.2  429.54  5542.9  432.05
#Mann=6,-1,0
  4496.7    0.05       0  4669.2    0.08       0  4987.9    0.07       0
  4994.2    0.08       0  5186.3    0.05       0  5285.7    0.08       0
Bank Sta=4917.3,5137.8
Exp/Cntr=0.3,0.1

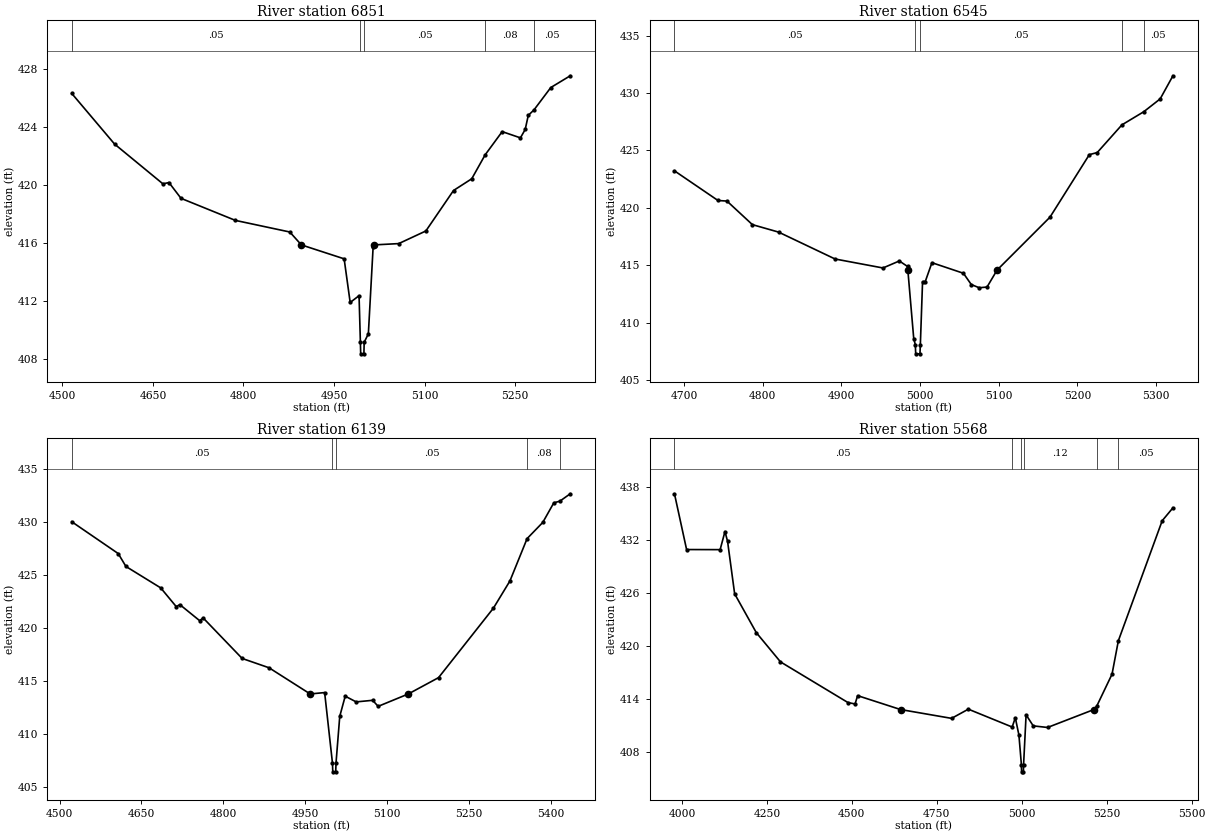
Type RM Length L Ch R = 1,6851,306,306,306
BEGIN DESCRIPTION:
XS3661A
END DESCRIPTION:
XS GIS Cut Line= 3
      2822275.92      7041460.07      2821800.26      7041453.12
      2821453.06      7041411.46
#Sta/Elev= 30
  4515.7  426.32  4586.6  422.83  4666.6  420.09  4676.6  420.18  4696.6  419.09
  4786.6  417.57  4876.7  416.77  4895.9  415.88  4966.7  414.92  4976.7  411.91
  4991.4  412.38  4993.6  409.17  4994.1  408.37  4999.4  408.37  4999.9  409.17
  5006.8  409.75  5014.7  415.74  5016.2  415.88  5057.1  415.97  5102.0  416.84
  5147.8  419.63  5178.0  420.44  5200.2  422.09  5228.4  423.69  5258.6  423.26
  5266.5  423.84  5271.6  424.81  5281.1  425.19  5308.9  426.73  5341.1  427.54
#Mann=5,-1,0
  4515.7    0.05       0  4993.6    0.03       0  4999.9    0.05       0
  5200.2    0.08       0  5281.1    0.05       0
Bank Sta=4895.9,5016.2
Exp/Cntr=0.3,0.1

Type RM Length L Ch R = 1,6545,406,406,406
BEGIN DESCRIPTION:
XS3662A
END DESCRIPTION:
XS GIS Cut Line= 3
      2822269.00      7041296.87      2821963.46      7041206.60
      2821648.78      7041203.14
#Sta/Elev= 30
  4688.0  423.23  4743.3  420.65  4754.7  420.60  4787.0  418.55  4820.3  417.90
  4892.1  415.56  4952.9  414.78  4973.7  415.39  4984.1  414.91  4984.5  414.60
  4992.0  408.63  4994.0  408.11  4994.5  407.31  4999.9  407.31  5000.4  408.11
  5003.2  413.59  5006.6  413.59  5015.1  415.24  5055.1  414.32  5065.1  413.34
  5075.1  413.06  5085.1  413.12  5097.9  414.60  5165.1  419.20  5215.1  424.64
  5225.1  424.82  5256.5  427.23  5284.2  428.37  5305.1  429.49  5321.3  431.50
#Mann=5,-1,0
  4688.0    0.05       0  4994.0    0.03       0  5000.4    0.05       0
  5256.5    0.08       0  5284.2    0.05       0
Bank Sta=4984.5,5097.9
Exp/Cntr=0.3,0.1

Type RM Length L Ch R = 1,6139,571,571,571
BEGIN DESCRIPTION:
UNT 090 in LFCCL Watershed 4.0
END DESCRIPTION:
XS GIS Cut Line= 3
      2822425.00      7041125.00      2822075.00      7040825.00
      2821625.05      7040775.01
#Sta/Elev= 30
  4522.2  430.03  4607.3  427.03  4621.5  425.81  4685.2  423.79  4713.7  422.02
  4720.3  422.21  4756.5  420.70  4763.1  420.95  4834.5  417.13  4883.8  416.25
  4959.2  413.78  4985.7  413.91  5000.1  407.23  5000.6  406.43  5006.0  406.43
  5006.5  407.23  5013.4  411.67  5023.4  413.57  5043.5  413.03  5073.7  413.18
  5083.8  412.61  5139.1  413.78  5194.5  415.32  5295.1  421.88  5325.3  424.44
  5356.8  428.44  5385.6  429.97  5405.8  431.82  5416.8  431.97  5435.9  432.67
#Mann=5,-1,0
  4522.2    0.05       0  5000.1    0.03       0  5006.5    0.05       0
  5356.8    0.08       0  5416.8    0.05       0
Bank Sta=4959.2,5139.1
Exp/Cntr=0.3,0.1

Type RM Length L Ch R = 1,5568,372,372,372
BEGIN DESCRIPTION:
UNT 090 in LFCCL Watershed 3.0
END DESCRIPTION:
XS GIS Cut Line= 3
      2822925.02      7040925.02      2822175.00      7040275.00
      2821725.04      7040125.01
#Sta/Elev= 30
  3978.1  437.26  4013.8  430.95  4112.5  430.94  4126.7  432.99  4134.4  431.87
  4155.2  425.94  4218.9  421.55  4290.1  418.24  4488.6  413.64  4509.5  413.48
  4517.1  414.42  4643.3  412.85  4793.5  411.85  4842.9  412.89  4971.8  410.87
  4981.1  411.92  4991.7  409.96  4999.0  406.60  4999.5  405.80  5004.9  405.80
  5005.4  406.60  5012.8  412.25  5033.8  411.00  5076.0  410.82  5212.5  412.85
  5220.9  413.25  5265.7  416.85  5284.3  420.63  5413.3  434.21  5444.9  435.67
#Mann=6,-1,0
  3978.1    0.05       0  4971.8    0.12       0  4999.0    0.07       0
  5005.4    0.12       0  5220.9    0.16       0  5284.3    0.05       0
Bank Sta=4643.3,5212.5
Exp/Cntr=0.3,0.1