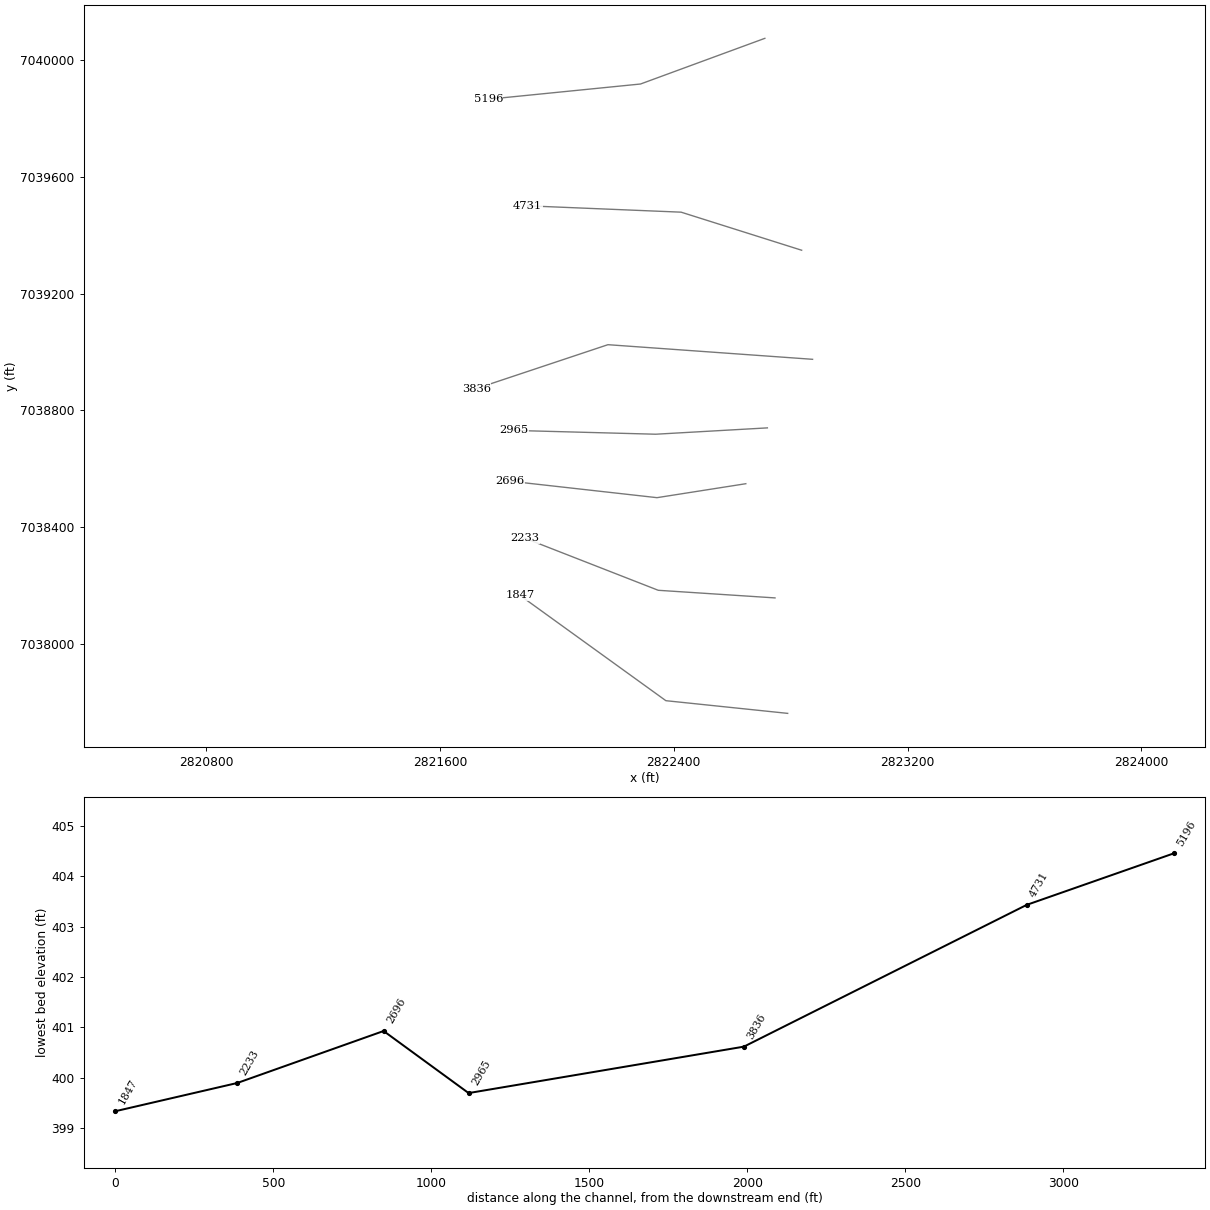
HEC-RAS study UNT 090 in LFCCL Watershed.prj: UNT 090 in LFCCL Watershed Base Level Engineering

--- UNT 090 in LFCCL Watershed.g01 (geometry) --- (continued)

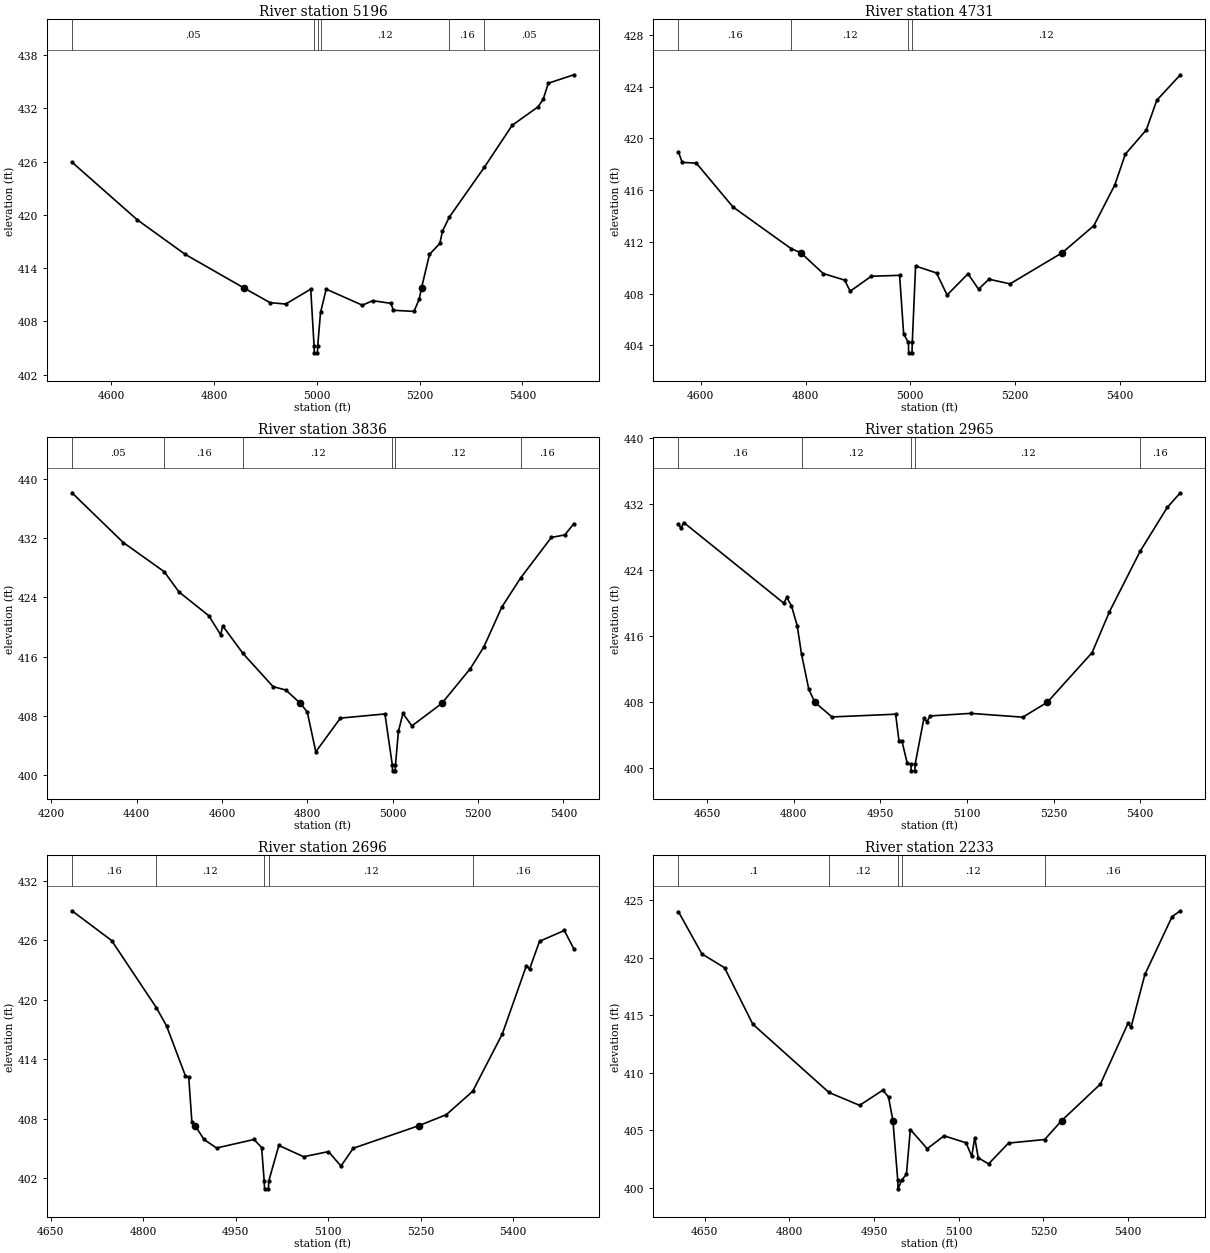
Type RM Length L Ch R = 1,5196,465,465,465
BEGIN DESCRIPTION:
XS3663A
END DESCRIPTION:
XS GIS Cut Line= 3
      2822711.71      7040072.91      2822286.37      7039916.67
      2821765.50      7039864.58
#Sta/Elev= 30
  4523.6  425.95  4650.7  419.45  4743.8  415.56  4858.1  411.77  4909.0  410.11
  4939.5  409.95  4988.2  411.63  4994.7  405.25  4995.2  404.45  5001.3  404.45
  5001.8  405.25  5007.3  409.00  5018.3  411.63  5088.7  409.82  5108.8  410.33
  5144.1  410.03  5149.1  409.25  5189.2  409.12  5199.2  410.49  5203.8  411.77
  5219.3  415.55  5239.4  416.78  5244.6  418.17  5257.7  419.74  5326.0  425.37
  5380.1  430.10  5430.4  432.18  5440.4  433.02  5450.6  434.85  5500.2  435.80
#Mann=6,-1,0
  4523.6    0.05       0  4994.7    0.03       0  5001.8    0.05       0
  5007.3    0.12       0  5257.7    0.16       0  5326.0    0.05       0
Bank Sta=4858.1,5203.8
Exp/Cntr=0.3,0.1

Type RM Length L Ch R = 1,4731,895,895,895
BEGIN DESCRIPTION:
XS3664A
END DESCRIPTION:
XS GIS Cut Line= 3
      2822837.62      7039348.08      2822425.26      7039478.30
      2821900.14      7039500.00
#Sta/Elev= 30
  4557.4  418.97  4564.6  418.15  4591.6  418.09  4661.6  414.70  4773.0  411.47
  4791.0  411.17  4833.7  409.56  4874.7  409.05  4885.2  408.19  4925.5  409.35
  4979.6  409.42  4987.3  404.89  4996.4  404.23  4996.9  403.43  5003.2  403.43
  5003.8  404.23  5010.1  410.14  5050.1  409.60  5070.2  407.90  5110.2  409.54
  5130.2  408.35  5150.2  409.12  5190.3  408.76  5290.1  411.17  5350.4  413.26
  5390.4  416.41  5410.4  418.78  5450.5  420.66  5470.5  422.95  5515.4  424.92
#Mann=4,-1,0
  4557.4    0.16       0  4773.0    0.12       0  4996.4    0.07       0
  5003.8    0.12       0
Bank Sta=4791,5290.1
Exp/Cntr=0.3,0.1

Type RM Length L Ch R = 1,3836,871,871,871
BEGIN DESCRIPTION:
UNT 090 in LFCCL Watershed 2.0
END DESCRIPTION:
XS GIS Cut Line= 3
      2822874.96      7038975.00      2822175.00      7039025.00
      2821724.98      7038874.99
#Sta/Elev= 30
  4248.4  438.11  4368.7  431.40  4464.7  427.47  4499.0  424.75  4569.2  421.53
  4596.7  418.97  4601.8  420.16  4649.1  416.45  4719.6  411.98  4749.6  411.51
  4783.9  409.71  4799.8  408.55  4819.8  403.19  4877.5  407.73  4981.8  408.29
  4999.1  401.42  4999.7  400.62  5006.0  400.62  5006.5  401.42  5013.4  405.93
  5023.9  408.36  5045.0  406.68  5115.1  409.71  5182.0  414.41  5213.7  417.34
  5255.8  422.71  5299.7  426.62  5371.8  432.09  5403.4  432.43  5424.5  433.95
#Mann=6,-1,0
  4248.4    0.05       0  4464.7    0.16       0  4649.1    0.12       0
  4999.1    0.07       0  5006.5    0.12       0  5299.7    0.16       0
Bank Sta=4783.9,5115.1
Exp/Cntr=0.3,0.1

Type RM Length L Ch R = 1,2965,269,269,269
BEGIN DESCRIPTION:
XS3667A
END DESCRIPTION:
XS GIS Cut Line= 3
      2822720.38      7038740.45      2822338.46      7038718.75
      2821852.38      7038731.77
#Sta/Elev= 30
  4600.7  429.64  4604.9  429.07  4609.9  429.78  4783.1  420.01  4788.2  420.70
  4796.4  419.70  4806.4  417.25  4813.8  413.83  4826.4  409.58  4836.9  408.00
  4866.5  406.23  4976.7  406.56  4982.5  403.34  4987.5  403.34  4996.7  400.65
  5003.0  400.50  5003.6  399.70  5009.9  399.70  5010.5  400.50  5025.8  406.12
  5030.8  405.65  5036.7  406.35  5106.7  406.66  5196.8  406.20  5239.2  408.00
  5316.8  414.02  5346.8  418.97  5400.0  426.30  5446.9  431.61  5469.5  433.38
#Mann=5,-1,0
  4600.7    0.16       0  4813.8    0.12       0  5003.0    0.07       0
  5010.5    0.12       0  5400.0    0.16       0
Bank Sta=4836.9,5239.2
Exp/Cntr=0.3,0.1

Type RM Length L Ch R = 1,2696,463,463,463
BEGIN DESCRIPTION:
XS3666A
END DESCRIPTION:
XS GIS Cut Line= 3
      2822646.64      7038549.48      2822342.80      7038501.74
      2821839.62      7038558.13
#Sta/Elev= 30
  4684.7  428.99  4749.0  425.99  4821.7  419.20  4838.2  417.36  4868.6  412.35
  4874.1  412.19  4879.2  407.67  4884.3  407.31  4898.9  405.91  4919.2  405.05
  4979.9  405.91  4992.3  405.10  4996.4  401.73  4997.0  400.93  5003.3  400.93
  5003.9  401.73  5020.2  405.31  5060.5  404.17  5100.7  404.69  5120.9  403.23
  5141.0  405.03  5247.5  407.31  5291.9  408.42  5334.5  410.77  5382.5  416.55
  5421.7  423.46  5426.7  423.09  5442.9  425.91  5483.1  427.00  5498.6  425.14
#Mann=5,-1,0
  4684.7    0.16       0  4821.7    0.12       0  4996.4    0.07       0
  5003.9    0.12       0  5334.5    0.16       0
Bank Sta=4884.3,5247.5
Exp/Cntr=0.3,0.1

Type RM Length L Ch R = 1,2233,386,386,386
BEGIN DESCRIPTION:
XS3665A
END DESCRIPTION:
XS GIS Cut Line= 3
      2822746.48      7038158.85      2822347.14      7038184.90
      2821891.44      7038362.84
#Sta/Elev= 30
  4603.3  424.00  4644.9  420.33  4685.0  419.13  4735.1  414.22  4870.1  408.28
  4924.4  407.16  4965.5  408.48  4975.6  407.89  4983.4  405.83  4991.9  400.70
  4992.5  399.90  4999.4  400.70  5007.3  401.15  5014.3  405.06  5044.2  403.39
  5074.0  404.51  5113.1  403.90  5123.0  402.72  5128.4  404.35  5134.6  402.60
  5152.9  402.07  5188.3  403.88  5252.4  404.19  5282.4  405.83  5351.1  409.01
  5400.0  414.29  5405.4  413.95  5429.9  418.54  5478.1  423.57  5492.7  424.08
#Mann=5,-1,0
  4603.3     0.1       0  4870.1    0.12       0  4991.9    0.07       0
  4999.4    0.12       0  5252.4    0.16       0
Bank Sta=4983.4,5282.4
Exp/Cntr=0.3,0.1

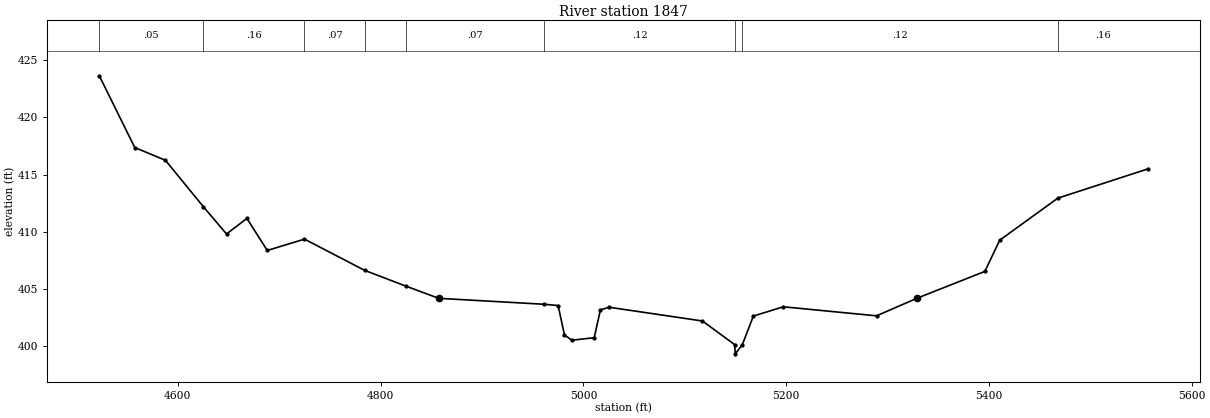
Type RM Length L Ch R = 1,1847,0,0,0
BEGIN DESCRIPTION:
UNT 090 in LFCCL Watershed 1.0
END DESCRIPTION:
XS GIS Cut Line= 3
      2822789.83      7037763.89      2822373.18      7037807.29
      2821874.01      7038167.56
#Sta/Elev= 30
  4522.5  423.63  4557.5  417.36  4587.7  416.25  4625.1  412.20  4648.0  409.81
  4668.1  411.17  4688.2  408.37  4724.9  409.36  4784.3  406.63  4824.8  405.26
  4857.3  404.19  4961.3  403.67  4975.1  403.56  4981.3  401.00  4988.5  400.53
  5010.7  400.75  5016.8  403.18  5025.4  403.41  5117.4  402.21  5149.3  400.14
  5149.8  399.34  5156.8  400.14  5167.7  402.64  5197.2  403.45  5289.2  402.66
  5328.9  404.19  5396.0  406.54  5410.7  409.27  5468.0  412.94  5557.0  415.50
#Mann=9,-1,0
  4522.5    0.05       0  4625.1    0.16       0  4724.9    0.07       0
  4784.3    0.12       0  4824.8    0.07       0  4961.3    0.12       0
  5149.3    0.07       0  5156.8    0.12       0  5468.0    0.16       0
Bank Sta=4857.3,5328.9
Exp/Cntr=0.3,0.1

Chan Stop Cuts=-1