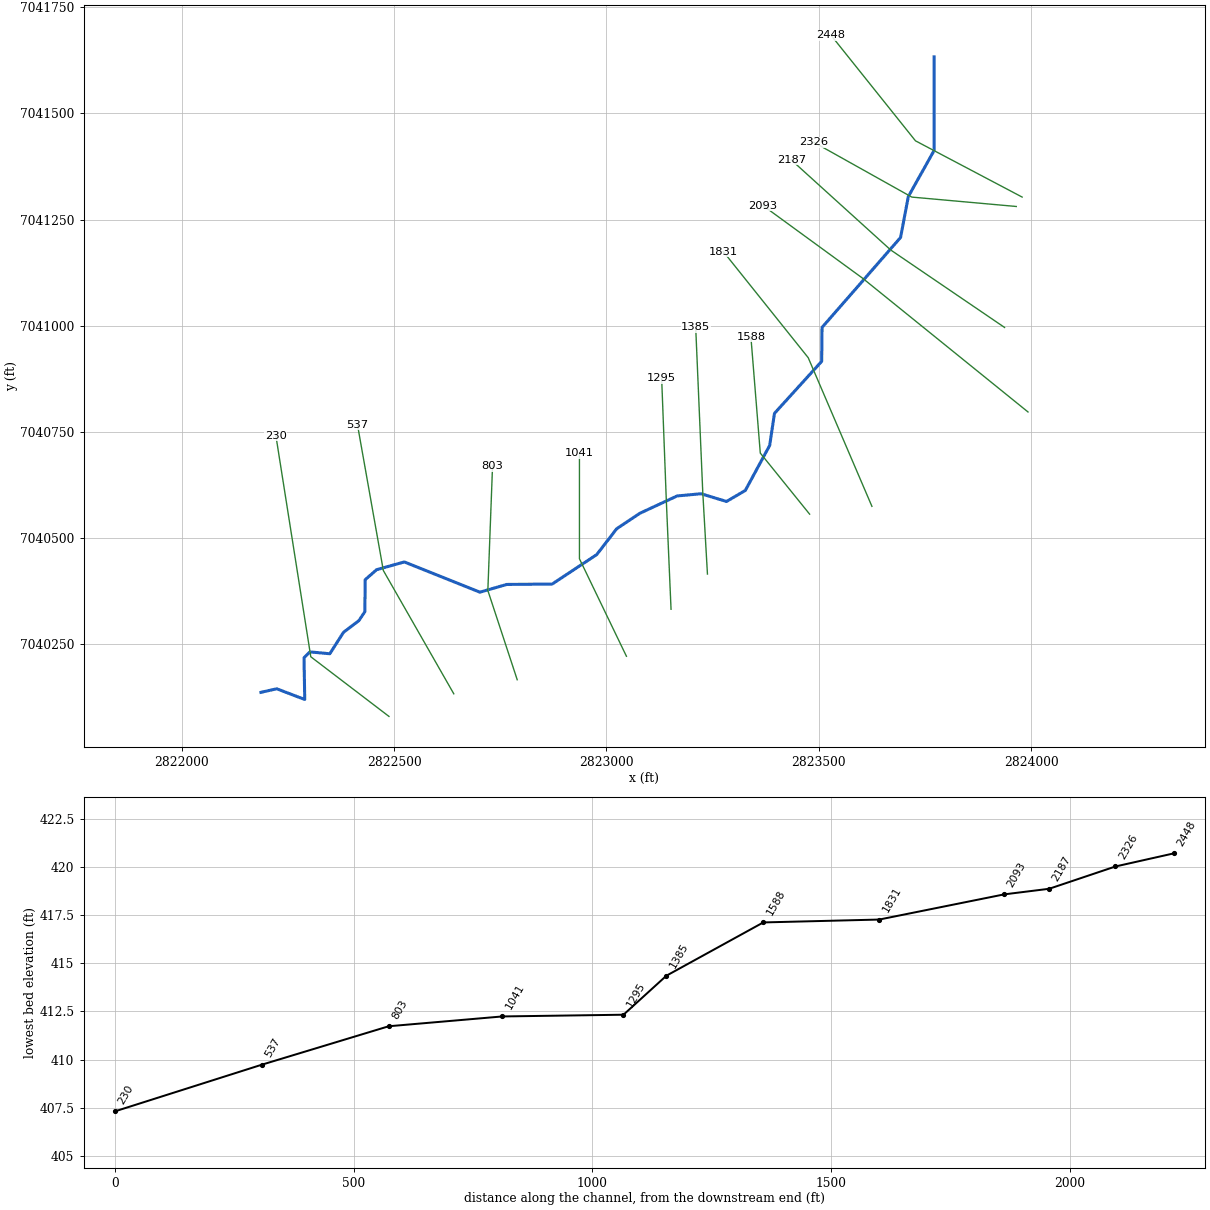
--- UNT 091 in LFCCL Watershed.prj (project) ---

Proj Title=UNT 091 in LFCCL Watershed Base Level Engineering
Current Plan=p01
Default Exp/Contr=0.3,0.1
English Units
Geom File=g01
Flow File=f01
Plan File=p01
BEGIN DESCRIPTION:
UNT 091 in LFCCL Watershed
END DESCRIPTION:

--- UNT 091 in LFCCL Watershed.p01 (plan) ---

Plan Title=Multiple Run
Short Identifier=Multiple
Geom File=g01
Flow File=f01
Subcritical Flow
K Sum by GR= 0
Std Step Tol= 0.01
Critical Tol= 0.01
Num of Std Step Trials= 20
Max Error Tol= 0.3
Flow Tol Ratio= 0.001
Split Flow NTrial= 30
Split Flow Tol= 0.02
Split Flow Ratio= 0.02
Log Output Level= 0
Friction Slope Method= 1
Unsteady Friction Slope Method= 2
Unsteady Bridges Friction Slope Method= 1
Parabolic Critical Depth
Global Vel Dist=  1 , 1 , 1
Global Log Level= 0
CheckData=True
Encroach Param= -1, 0, 0, 0
BEGIN DESCRIPTION:
Multiple Run
END DESCRIPTION:

--- UNT 091 in LFCCL Watershed.f01 (steady flow) ---

Flow Title=Multiple
Number of Profiles=7
Profile Names=10-year,25-year,50-year,1pct_min,100-year,1pct_plu,500-year
River Rch & RM= UNT 091 in LFCCL,Reach-1,2448
     390     508     600     353     705    1407     973
Boundary for River Rch & Prof#=UNT 091 in LFCCL,Reach-1,1
Up Type=0
Dn Type=3
Dn Slope=0.005
Boundary for River Rch & Prof#=UNT 091 in LFCCL,Reach-1,2
Up Type=0
Dn Type=3
Dn Slope=0.005
Boundary for River Rch & Prof#=UNT 091 in LFCCL,Reach-1,3
Up Type=0
Dn Type=3
Dn Slope=0.005
Boundary for River Rch & Prof#=UNT 091 in LFCCL,Reach-1,4
Up Type=0
Dn Type=3
Dn Slope=0.005
Boundary for River Rch & Prof#=UNT 091 in LFCCL,Reach-1,5
Up Type=0
Dn Type=3
Dn Slope=0.005
Boundary for River Rch & Prof#=UNT 091 in LFCCL,Reach-1,6
Up Type=0
Dn Type=3
Dn Slope=0.005
Boundary for River Rch & Prof#=UNT 091 in LFCCL,Reach-1,7
Up Type=0
Dn Type=3
Dn Slope=0.005

--- UNT 091 in LFCCL Watershed.g01 (geometry) ---

Geom Title=Existing Conditions

River Reach=UNT 091 in LFCCL,Reach-1
Reach XY= 30
      2823771.43      7041633.37      2823771.43      7041412.88
      2823710.67      7041304.38      2823692.44      7041208.02
      2823507.54      7040996.22      2823506.67      7040916.36
      2823395.56      7040793.96      2823384.28      7040718.44
      2823326.99      7040612.54      2823282.72      7040586.49
      2823222.82      7040604.72      2823166.40      7040599.51
      2823078.72      7040558.72      2823024.04      7040522.26
      2822977.16      7040461.49      2822872.13      7040392.05
      2822765.35      7040391.18      2822701.99      7040372.95
      2822524.04      7040444.13      2822458.93      7040425.90
      2822432.02      7040402.47      2822431.15      7040326.95
      2822417.26      7040306.11      2822380.81      7040278.33
      2822348.69      7040227.99      2822301.81      7040232.33
      2822287.92      7040218.44      2822289.66      7040120.35
      2822223.69      7040145.52      2822186.52      7040137.16

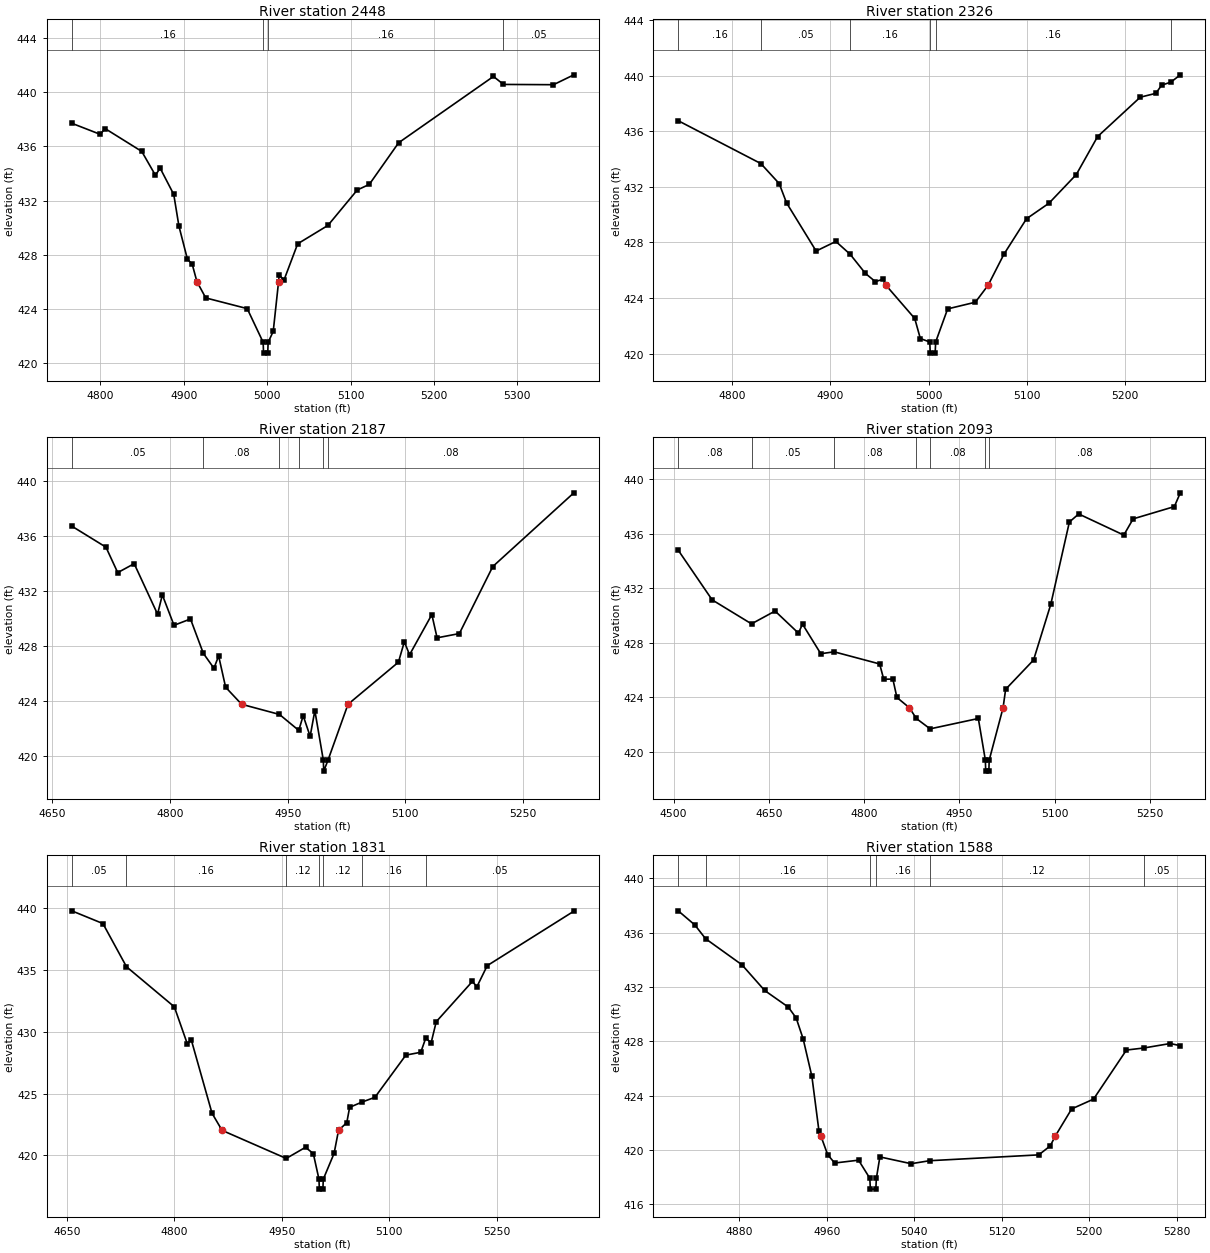
Type RM Length L Ch R = 1,2448,122,122,122
BEGIN DESCRIPTION:
UNT 091 in LFCCL Watershed 5.0
END DESCRIPTION:
XS GIS Cut Line= 3
      2823978.66      7041303.17      2823727.51      7041435.63
      2823528.76      7041684.06
#Sta/Elev= 30
  4765.6  437.71  4799.8  436.89  4805.5  437.32  4849.5  435.63  4865.9  433.87
  4871.6  434.39  4887.9  432.45  4894.1  430.11  4904.3  427.66  4910.0  427.30
  4915.7  426.00  4926.3  424.80  4976.0  424.01  4995.1  421.52  4995.6  420.72
  5000.6  420.72  5001.1  421.52  5007.2  422.33  5013.6  426.00  5014.4  426.49
  5020.1  426.12  5036.5  428.80  5072.8  430.16  5108.0  432.78  5122.4  433.19
  5157.6  436.27  5271.3  441.17  5283.3  440.58  5343.3  440.56  5367.7  441.29
#Mann=4,-1,0
  4765.6    0.16       0  4995.1    0.07       0  5001.1    0.16       0
  5283.3    0.05       0
Bank Sta=4915.7,5013.6
Exp/Cntr=0.3,0.1

Type RM Length L Ch R = 1,2326,139,139,139
BEGIN DESCRIPTION:
XS3670A
END DESCRIPTION:
XS GIS Cut Line= 3
      2823964.88      7041281.03      2823718.82      7041303.15
      2823488.30      7041432.13
#Sta/Elev= 30
  4745.1  436.75  4829.2  433.67  4847.9  432.23  4855.4  430.84  4885.5  427.38
  4905.6  428.07  4920.1  427.15  4935.7  425.77  4945.8  425.18  4953.9  425.36
  4956.6  424.92  4985.9  422.53  4991.6  421.09  5001.2  420.84  5001.7  420.04
  5006.7  420.04  5007.2  420.84  5019.4  423.22  5047.6  423.70  5060.6  424.92
  5076.7  427.15  5099.7  429.70  5122.6  430.82  5150.4  432.88  5172.1  435.61
  5215.5  438.44  5231.4  438.72  5237.2  439.30  5246.8  439.53  5256.3  440.05
#Mann=6,-1,0
  4745.1    0.16       0  4829.2    0.05       0  4920.1    0.16       0
  5001.2    0.07       0  5007.2    0.16       0  5246.8    0.08       0
Bank Sta=4956.6,5060.6
Exp/Cntr=0.3,0.1

Type RM Length L Ch R = 1,2187,94,94,94
BEGIN DESCRIPTION:
XS3669A
END DESCRIPTION:
XS GIS Cut Line= 3
      2823937.26      7040996.24      2823669.05      7041178.73
      2823434.93      7041390.82
#Sta/Elev= 30
  4674.6  436.69  4718.2  435.16  4733.2  433.31  4754.2  433.96  4784.0  430.29
  4790.1  431.69  4805.0  429.48  4826.0  429.94  4842.4  427.44  4855.9  426.36
  4861.9  427.25  4870.8  424.98  4891.2  423.74  4939.5  423.00  4964.1  421.84
  4969.7  422.91  4978.6  421.41  4984.6  423.28  4995.4  419.68  4995.9  418.88
  5001.4  419.68  5026.9  423.74  5091.2  426.80  5098.7  428.28  5105.4  427.34
  5133.8  430.26  5140.5  428.57  5168.9  428.88  5211.5  433.75  5314.9  439.11
#Mann=6,-1,0
  4674.6    0.05       0  4842.4    0.08       0  4939.5    0.16       0
  4964.1    0.08       0  4995.4    0.07       0  5001.4    0.08       0
Bank Sta=4891.2,5026.9
Exp/Cntr=0.3,0.1

Type RM Length L Ch R = 1,2093,262,262,262
BEGIN DESCRIPTION:
XS3671A
END DESCRIPTION:
XS GIS Cut Line= 3
      2823992.49      7040797.23      2823602.70      7041112.38
      2823368.85      7041282.95
#Sta/Elev= 30
  4507.2  434.79  4560.6  431.15  4622.6  429.39  4659.7  430.33  4696.5  428.71
  4702.9  429.37  4731.7  427.20  4752.7  427.34  4824.4  426.45  4830.8  425.33
  4845.2  425.34  4851.6  423.99  4871.2  423.24  4882.2  422.45  4903.9  421.69
  4979.8  422.45  4990.9  419.39  4991.4  418.59  4996.4  418.59  4996.9  419.39
  5018.8  423.24  5022.8  424.59  5066.8  426.74  5093.9  430.82  5123.2  436.86
  5137.9  437.45  5208.9  435.90  5223.6  437.09  5288.5  437.99  5297.9  439.00
#Mann=7,-1,0
  4507.2    0.08       0  4622.6    0.05       0  4752.7    0.08       0
  4882.2    0.16       0  4903.9    0.08       0  4990.9    0.07       0
  4996.9    0.08       0
Bank Sta=4871.2,5018.8
Exp/Cntr=0.3,0.1

Type RM Length L Ch R = 1,1831,243,243,243
BEGIN DESCRIPTION:
UNT 091 in LFCCL Watershed 4.0
END DESCRIPTION:
XS GIS Cut Line= 3
      2823624.98      7040575.04      2823475.00      7040925.00
      2823275.00      7041175.00
#Sta/Elev= 30
  4656.7  439.77  4700.2  438.74  4733.1  435.25  4799.9  432.01  4818.0  429.02
  4823.5  429.35  4852.5  423.41  4866.5  422.03  4956.1  419.76  4983.0  420.66
  4993.9  420.15  5001.8  418.08  5002.3  417.28  5007.3  417.28  5007.8  418.08
  5022.9  420.17  5029.1  422.03  5040.6  422.65  5044.6  423.89  5061.2  424.30
  5079.9  424.70  5123.1  428.11  5143.9  428.34  5150.9  429.49  5158.3  429.09
  5165.5  430.81  5215.9  434.06  5222.3  433.64  5236.7  435.34  5357.6  439.74
#Mann=7,-1,0
  4656.7    0.05       0  4733.1    0.16       0  4956.1    0.12       0
  5001.8    0.07       0  5007.8    0.12       0  5061.2    0.16       0
  5150.9    0.05       0
Bank Sta=4866.5,5029.1
Exp/Cntr=0.3,0.1

Type RM Length L Ch R = 1,1588,203,203,203
BEGIN DESCRIPTION:
XS3677A
END DESCRIPTION:
XS GIS Cut Line= 3
      2823478.29      7040556.66      2823362.17      7040700.43
      2823340.05      7040974.13
#Sta/Elev= 30
  4824.0  437.60  4839.2  436.56  4849.0  435.55  4882.3  433.63  4903.1  431.74
  4924.7  430.52  4931.9  429.72  4938.3  428.18  4946.3  425.42  4952.7  421.44
  4954.6  421.02  4960.7  419.67  4967.1  419.05  4989.0  419.26  4999.3  417.93
  4999.8  417.13  5004.8  417.13  5005.3  417.93  5008.5  419.50  5037.1  419.00
  5054.0  419.22  5153.9  419.65  5164.4  420.31  5168.9  421.02  5184.0  423.03
  5204.0  423.75  5234.1  427.36  5249.9  427.51  5274.2  427.84  5283.4  427.68
#Mann=6,-1,0
  4824.0    0.05       0  4849.0    0.16       0  4999.3    0.07       0
  5005.3    0.16       0  5054.0    0.12       0  5249.9    0.05       0
Bank Sta=4954.6,5168.9
Exp/Cntr=0.3,0.1

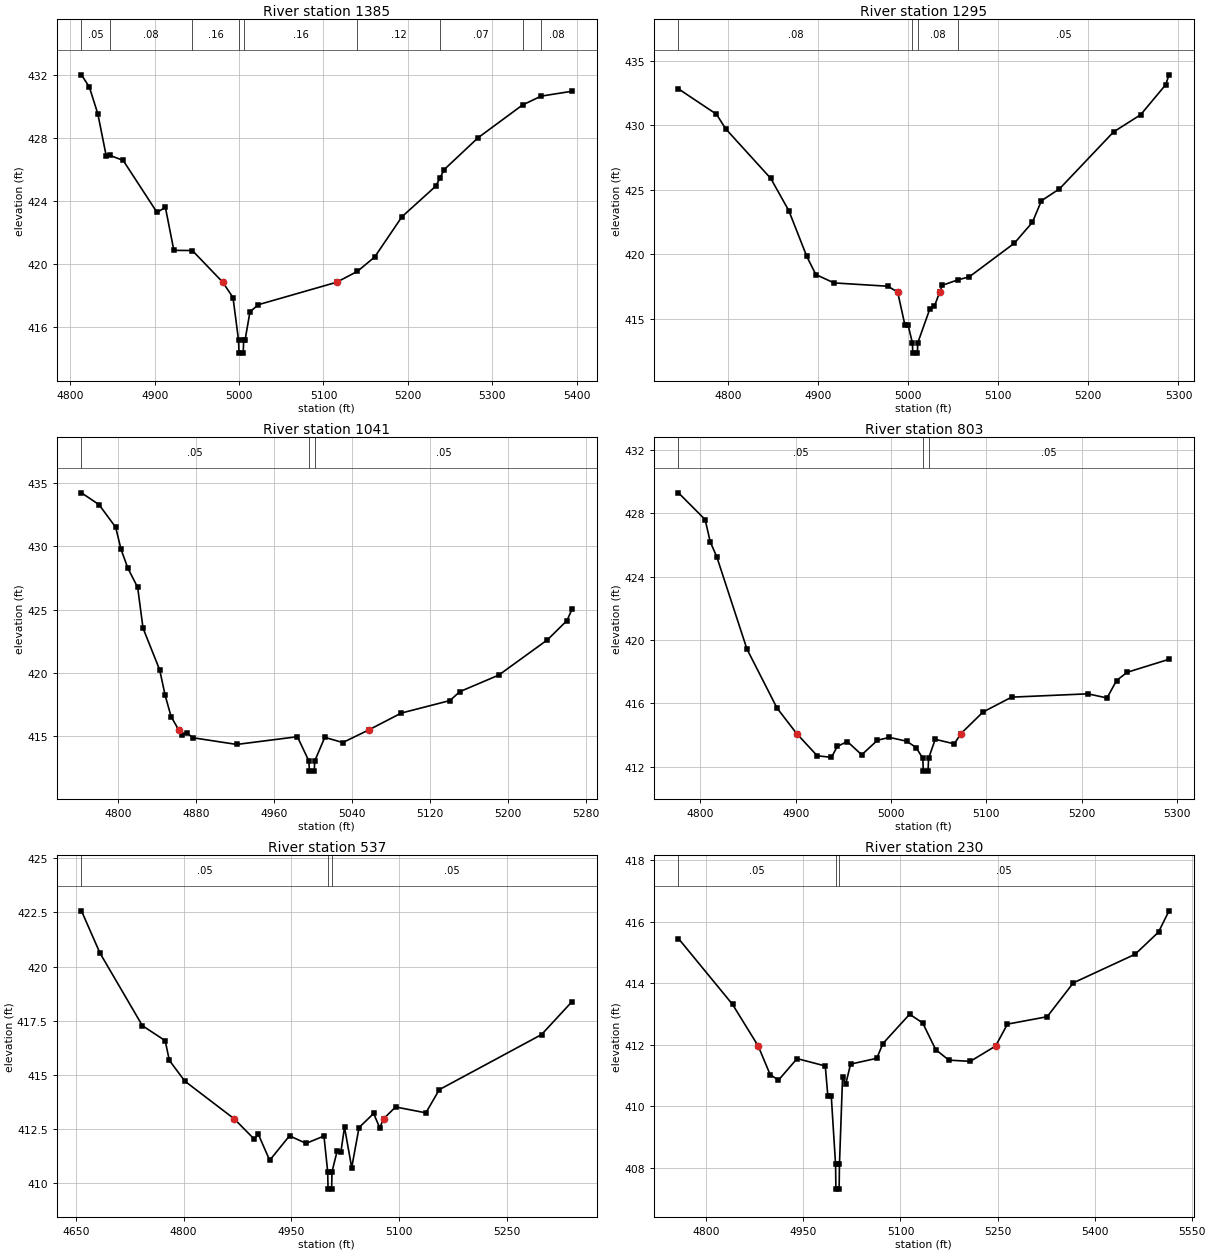
Type RM Length L Ch R = 1,1385,90,90,90
BEGIN DESCRIPTION:
XS3672A
END DESCRIPTION:
XS GIS Cut Line= 3
      2823237.75      7040415.66      2823226.69      7040609.19
      2823210.10      7040996.29
#Sta/Elev= 30
  4813.2  431.99  4822.6  431.21  4832.6  429.52  4842.6  426.84  4846.7  426.89
  4862.6  426.57  4902.7  423.28  4912.7  423.59  4922.7  420.87  4944.6  420.86
  4980.7  418.85  4992.8  417.88  4999.4  415.16  4999.9  414.36  5004.9  414.36
  5005.4  415.16  5007.0  415.16  5012.9  416.98  5022.9  417.43  5115.6  418.85
  5140.2  419.54  5160.7  420.45  5193.0  423.00  5233.1  424.94  5238.0  425.45
  5243.1  425.99  5283.1  428.00  5335.9  430.08  5357.9  430.64  5394.5  430.95
#Mann=9,-1,0
  4813.2    0.05       0  4846.7    0.08       0  4944.6    0.16       0
  4999.4    0.07       0  5005.4    0.16       0  5140.2    0.12       0
  5238.0    0.07       0  5335.9    0.05       0  5357.9    0.08       0
Bank Sta=4980.7,5115.6
Exp/Cntr=0.3,0.1

Type RM Length L Ch R = 1,1295,254,254,254
BEGIN DESCRIPTION:
XS3673A
END DESCRIPTION:
XS GIS Cut Line= 3
      2823152.05      7040332.70      2823140.99      7040587.07
      2823129.96      7040876.45
#Sta/Elev= 30
  4745.3  432.84  4787.5  430.87  4797.7  429.74  4847.7  425.89  4867.7  423.39
  4887.7  419.83  4897.7  418.43  4917.8  417.78  4977.8  417.52  4988.5  417.06
  4996.4  414.55  4999.9  414.55  5004.8  413.13  5005.3  412.33  5010.3  412.33
  5010.8  413.13  5024.3  415.79  5029.3  415.98  5035.1  417.06  5037.9  417.59
  5055.4  418.02  5067.9  418.25  5117.9  420.86  5137.9  422.48  5148.0  424.16
  5168.0  425.08  5228.0  429.50  5258.0  430.83  5285.8  433.16  5289.5  433.93
#Mann=4,-1,0
  4745.3    0.08       0  5004.8    0.07       0  5010.8    0.08       0
  5055.4    0.05       0
Bank Sta=4988.5,5035.1
Exp/Cntr=0.3,0.1

Type RM Length L Ch R = 1,1041,238,238,238
BEGIN DESCRIPTION:
XS3674A
END DESCRIPTION:
XS GIS Cut Line= 3
      2823047.00      7040222.08      2822936.39      7040451.60
      2822936.39      7040700.22
#Sta/Elev= 30
  4762.2  434.24  4780.2  433.31  4797.3  431.52  4802.8  429.78  4809.8  428.29
  4819.9  426.76  4825.4  423.54  4842.5  420.24  4848.1  418.23  4854.2  416.55
  4862.0  415.50  4865.1  415.08  4870.7  415.24  4876.4  414.88  4921.5  414.35
  4983.8  414.96  4995.6  413.04  4996.1  412.24  5001.1  412.24  5001.6  413.04
  5011.9  414.91  5030.4  414.50  5057.1  415.50  5090.4  416.83  5140.4  417.82
  5150.4  418.52  5190.4  419.83  5240.4  422.62  5260.4  424.14  5265.6  425.03
#Mann=3,-1,0
  4762.2    0.05       0  4995.6    0.03       0  5001.6    0.05       0
Bank Sta=4862,5057.1
Exp/Cntr=0.3,0.1

Type RM Length L Ch R = 1,803,266,266,266
BEGIN DESCRIPTION:
XS3675A
END DESCRIPTION:
XS GIS Cut Line= 3
      2822789.88      7040166.78      2822720.74      7040376.95
      2822731.80      7040670.00
#Sta/Elev= 30
  4777.0  429.30  4805.0  427.61  4810.3  426.21  4817.2  425.26  4848.8  419.44
  4880.4  415.71  4901.0  414.10  4922.5  412.70  4937.5  412.60  4943.6  413.29
  4954.1  413.60  4969.2  412.76  4985.7  413.68  4998.2  413.86  5016.3  413.62
  5026.3  413.22  5033.3  412.53  5033.8  411.73  5038.8  411.73  5039.3  412.53
  5046.3  413.74  5066.3  413.45  5073.3  414.10  5096.4  415.46  5126.4  416.40
  5206.4  416.61  5226.5  416.35  5236.5  417.45  5247.6  417.97  5291.5  418.79
#Mann=3,-1,0
  4777.0    0.05       0  5033.3    0.03       0  5039.3    0.05       0
Bank Sta=4901,5073.3
Exp/Cntr=0.3,0.1

Type RM Length L Ch R = 1,537,307,307,307
BEGIN DESCRIPTION:
XS3676A
END DESCRIPTION:
XS GIS Cut Line= 3
      2822640.56      7040133.65      2822474.68      7040423.95
      2822413.86      7040766.75
#Sta/Elev= 30
  4658.0  422.57  4683.8  420.62  4742.8  417.27  4774.5  416.58  4780.3  415.67
  4801.9  414.71  4870.3  412.98  4898.3  412.04  4904.1  412.26  4919.9  411.06
  4947.5  412.19  4970.5  411.84  4995.4  412.18  5000.6  410.53  5001.1  409.73
  5006.1  409.73  5006.6  410.53  5013.7  411.48  5019.0  411.45  5024.0  412.59
  5034.0  410.72  5044.2  412.57  5064.5  413.22  5073.0  412.56  5078.5  412.98
  5095.0  413.52  5137.2  413.25  5155.9  414.32  5298.1  416.86  5340.5  418.38
#Mann=3,-1,0
  4658.0    0.05       0  5000.6    0.03       0  5006.6    0.05       0
Bank Sta=4870.3,5078.5
Exp/Cntr=0.3,0.1

Type RM Length L Ch R = 1,230,0,0,0
BEGIN DESCRIPTION:
UNT 091 in LFCCL Watershed 1.0
END DESCRIPTION:
XS GIS Cut Line= 3
      2822487.93      7040080.45      2822303.87      7040220.92
      2822221.76      7040741.04
#Sta/Elev= 30
  4756.9  415.45  4840.5  413.31  4880.1  411.96  4898.6  411.03  4911.5  410.85
  4940.2  411.55  4983.8  411.31  4987.7  410.35  4993.0  410.35  4999.7  408.11
  5000.2  407.31  5005.2  407.31  5005.7  408.11  5010.5  410.94  5015.6  410.74
  5022.9  411.37  5063.4  411.56  5072.9  412.04  5114.1  412.99  5134.3  412.71
  5154.5  411.84  5174.8  411.50  5207.9  411.46  5247.1  411.96  5265.3  412.67
  5326.7  412.91  5367.1  414.01  5462.7  414.94  5498.8  415.66  5515.0  416.35
#Mann=3,-1,0
  4756.9    0.05       0  4999.7    0.03       0  5005.7    0.05       0
Bank Sta=4880.1,5247.1
Exp/Cntr=0.3,0.1

Chan Stop Cuts=-1