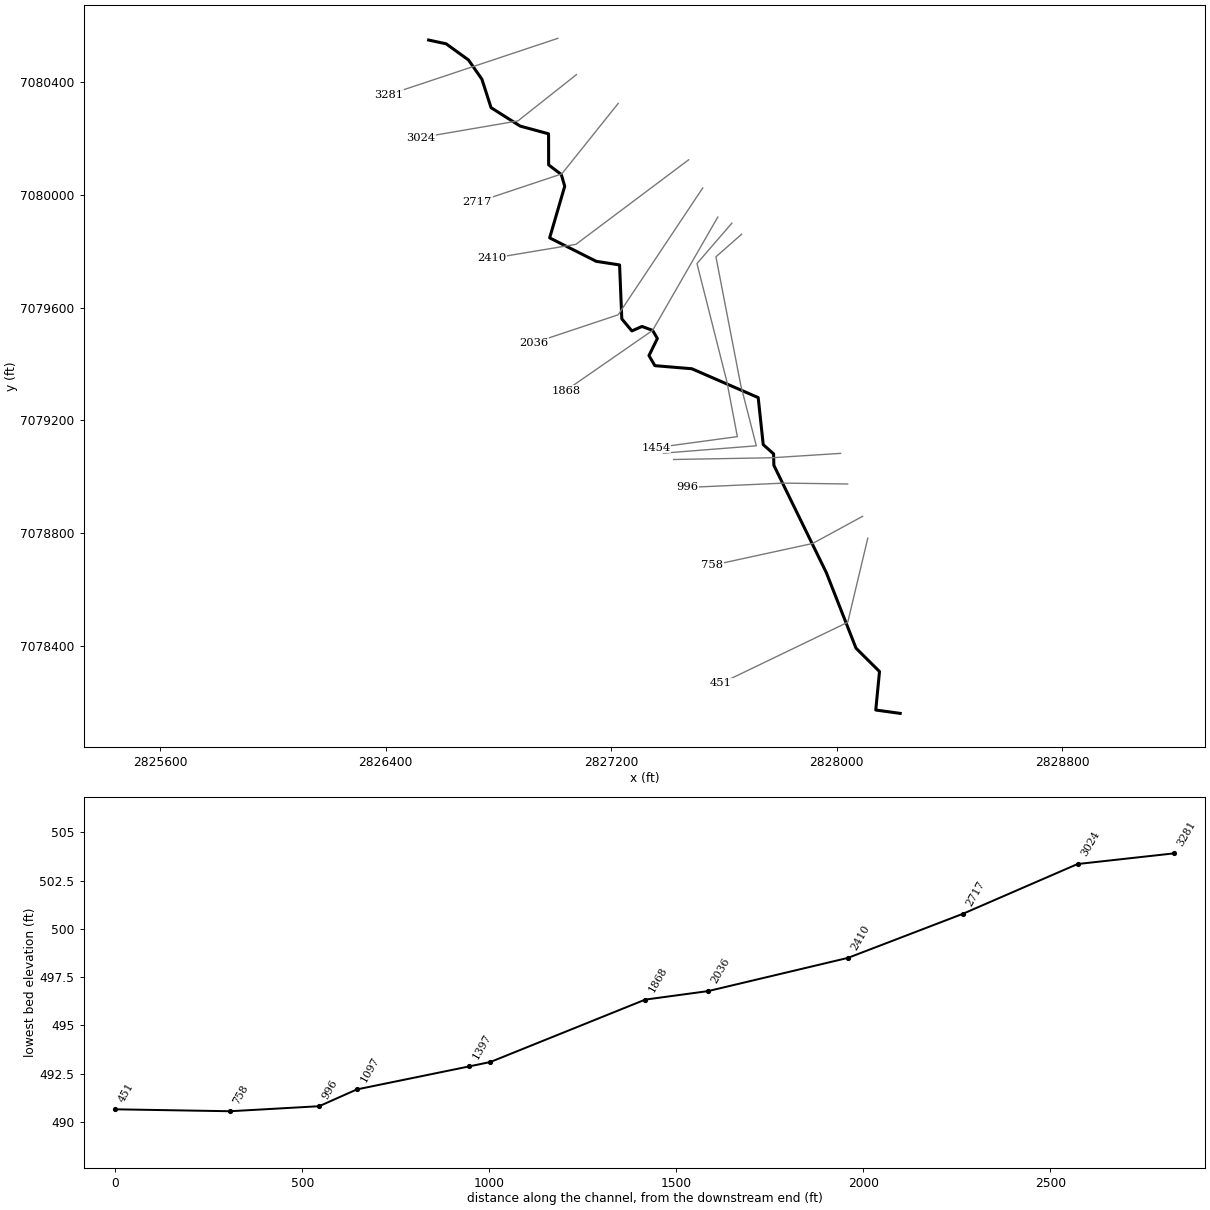
--- UNT 093 in LFCCL Watershed.prj (project) ---

Proj Title=UNT 093 in LFCCL Watershed Base Level Engineering
Current Plan=p01
Default Exp/Contr=0.3,0.1
English Units
Geom File=g01
Flow File=f01
Plan File=p01
BEGIN DESCRIPTION:
UNT 093 in LFCCL Watershed
END DESCRIPTION:

--- UNT 093 in LFCCL Watershed.p01 (plan) ---

Plan Title=Multiple Run
Short Identifier=Multiple
Geom File=g01
Flow File=f01
Subcritical Flow
K Sum by GR= 0
Std Step Tol= 0.01
Critical Tol= 0.01
Num of Std Step Trials= 20
Max Error Tol= 0.3
Flow Tol Ratio= 0.001
Split Flow NTrial= 30
Split Flow Tol= 0.02
Split Flow Ratio= 0.02
Log Output Level= 0
Friction Slope Method= 1
Unsteady Friction Slope Method= 2
Unsteady Bridges Friction Slope Method= 1
Parabolic Critical Depth
Global Vel Dist=  1 , 1 , 1
Global Log Level= 0
CheckData=True
Encroach Param= -1, 0, 0, 0
BEGIN DESCRIPTION:
Multiple Run
END DESCRIPTION:

--- UNT 093 in LFCCL Watershed.f01 (steady flow) ---

Flow Title=Multiple
Number of Profiles=7
Profile Names=10-year,25-year,50-year,1pct_min,100-year,1pct_plu,500-year
River Rch & RM= UNT 093 in LFCCL,Reach-1,3281
     531     696     827     487     973    1941    1341
Boundary for River Rch & Prof#=UNT 093 in LFCCL,Reach-1,1
Up Type=0
Dn Type=3
Dn Slope=0.005
Boundary for River Rch & Prof#=UNT 093 in LFCCL,Reach-1,2
Up Type=0
Dn Type=3
Dn Slope=0.005
Boundary for River Rch & Prof#=UNT 093 in LFCCL,Reach-1,3
Up Type=0
Dn Type=3
Dn Slope=0.005
Boundary for River Rch & Prof#=UNT 093 in LFCCL,Reach-1,4
Up Type=0
Dn Type=3
Dn Slope=0.005
Boundary for River Rch & Prof#=UNT 093 in LFCCL,Reach-1,5
Up Type=0
Dn Type=3
Dn Slope=0.005
Boundary for River Rch & Prof#=UNT 093 in LFCCL,Reach-1,6
Up Type=0
Dn Type=3
Dn Slope=0.005
Boundary for River Rch & Prof#=UNT 093 in LFCCL,Reach-1,7
Up Type=0
Dn Type=3
Dn Slope=0.005

--- UNT 093 in LFCCL Watershed.g01 (geometry) ---

Geom Title=Existing Conditions

River Reach=UNT 093 in LFCCL,Reach-1
Reach XY= 30
      2826552.31      7080549.95      2826614.54      7080536.53
      2826693.86      7080479.18      2826741.44      7080410.84
      2826773.85      7080309.98      2826877.21      7080244.59
      2826977.98      7080217.19      2826978.23      7080106.95
      2827023.13      7080072.74      2827035.26      7080031.04
      2826981.82      7079847.95      2827147.29      7079764.67
      2827229.91      7079751.92      2827237.84      7079560.46
      2827273.61      7079517.73      2827309.38      7079533.63
      2827347.14      7079519.72      2827364.04      7079490.90
      2827334.23      7079430.29      2827355.09      7079394.51
      2827486.26      7079383.58      2827721.76      7079281.23
      2827739.65      7079114.30      2827776.42      7079081.50
      2827777.41      7079040.76      2827963.61      7078659.89
      2828068.86      7078392.00      2828152.24      7078309.22
      2828138.94      7078172.58      2828225.59      7078160.71

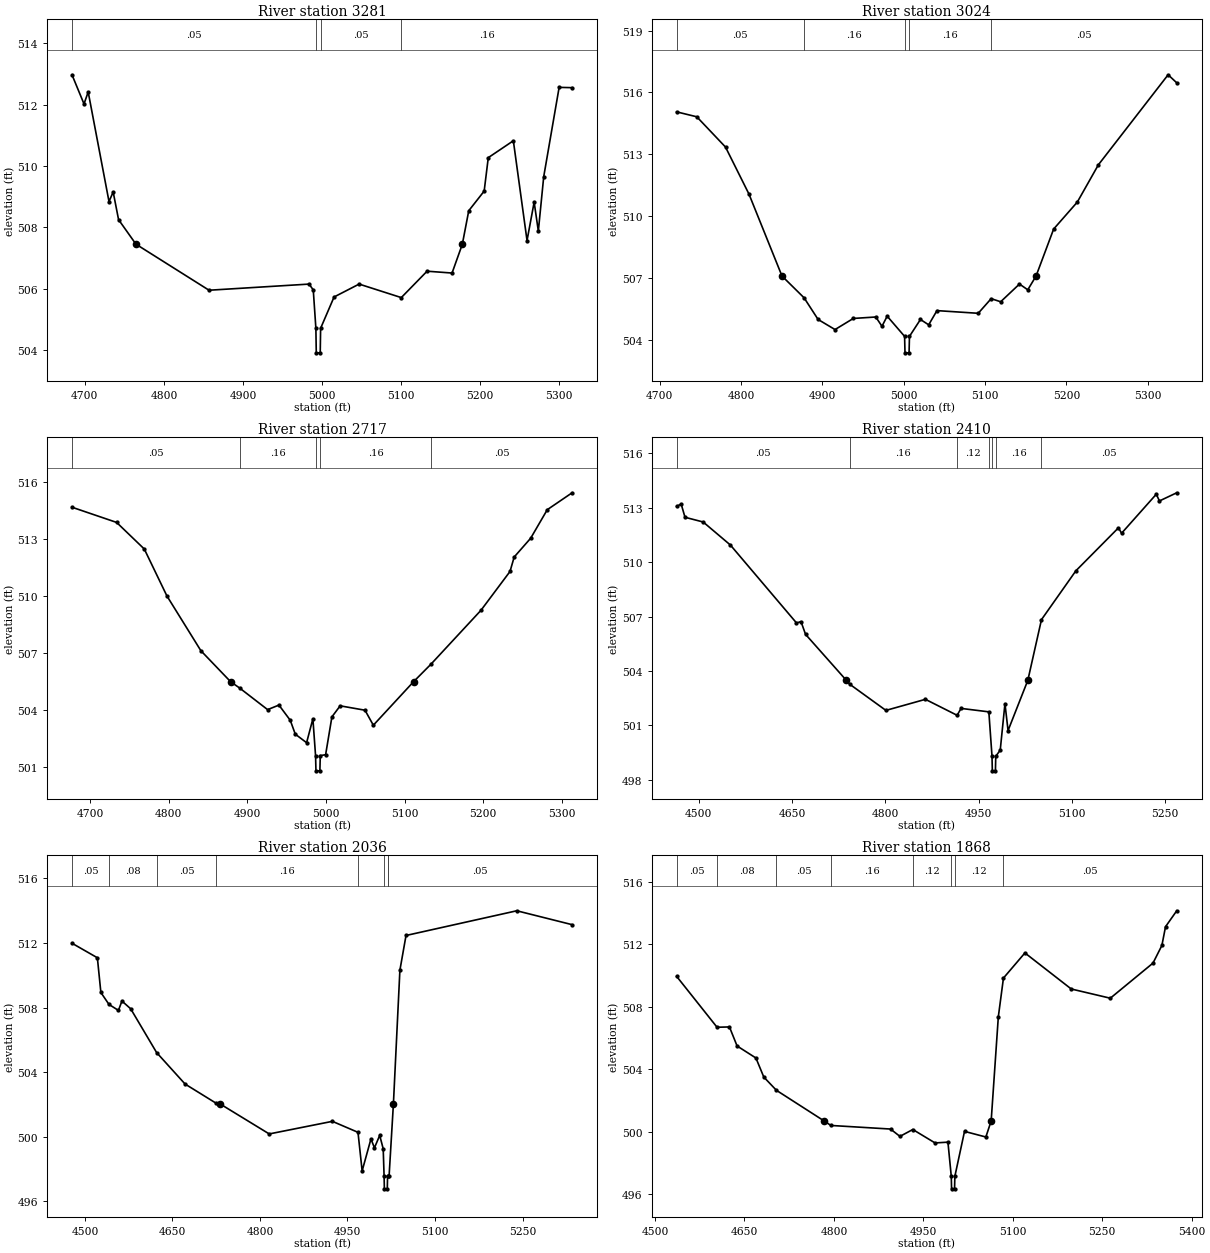
Type RM Length L Ch R = 1,3281,257,257,257
BEGIN DESCRIPTION:
UNT 093 in LFCCL Watershed 7.0
END DESCRIPTION:
XS GIS Cut Line= 3
      2827010.91      7080555.98      2826710.94      7080455.99
      2826410.97      7080356.00
#Sta/Elev= 30
  4683.8  512.97  4699.0  512.02  4704.3  512.41  4730.6  508.84  4735.9  509.15
  4742.7  508.25  4764.7  507.45  4857.1  505.95  4983.6  506.15  4988.9  505.96
  4992.2  504.71  4992.7  503.91  4997.7  503.91  4998.2  504.71  5015.2  505.73
  5046.9  506.15  5100.2  505.71  5132.8  506.57  5164.4  506.51  5177.4  507.45
  5185.5  508.54  5205.0  509.18  5210.2  510.27  5241.9  510.82  5259.2  507.57
  5268.2  508.82  5273.5  507.88  5280.3  509.65  5299.8  512.56  5316.2  512.55
#Mann=4,-1,0
  4683.8    0.05       0  4992.2    0.03       0  4998.2    0.05       0
  5100.2    0.16       0
Bank Sta=4764.7,5177.4
Exp/Cntr=0.3,0.1

Type RM Length L Ch R = 1,3024,307,307,307
BEGIN DESCRIPTION:
XS3678A
END DESCRIPTION:
XS GIS Cut Line= 3
      2827077.00      7080427.34      2826869.03      7080262.83
      2826524.51      7080203.86
#Sta/Elev= 30
  4721.0  515.06  4745.8  514.82  4781.1  513.35  4809.9  511.07  4850.5  507.09
  4877.7  506.03  4894.9  504.98  4915.7  504.49  4938.2  505.03  4965.8  505.10
  4973.4  504.65  4979.8  505.14  5001.2  504.16  5001.7  503.36  5006.7  503.36
  5007.2  504.16  5020.7  504.98  5030.8  504.72  5041.0  505.41  5091.7  505.28
  5107.6  505.99  5119.3  505.84  5142.4  506.70  5152.6  506.42  5162.8  507.09
  5184.4  509.37  5213.5  510.68  5239.4  512.49  5325.1  516.86  5335.7  516.47
#Mann=5,-1,0
  4721.0    0.05       0  4877.7    0.16       0  5001.2    0.07       0
  5007.2    0.16       0  5107.6    0.05       0
Bank Sta=4850.5,5162.8
Exp/Cntr=0.3,0.1

Type RM Length L Ch R = 1,2717,307,307,307
BEGIN DESCRIPTION:
UNT 093 in LFCCL Watershed 6.0
END DESCRIPTION:
XS GIS Cut Line= 3
      2827224.97      7080324.97      2827025.00      7080075.00
      2826725.04      7079975.01
#Sta/Elev= 30
  4676.8  514.65  4733.6  513.85  4768.8  512.45  4797.6  509.98  4840.8  507.10
  4878.6  505.47  4890.0  505.14  4925.7  504.00  4940.1  504.24  4954.5  503.44
  4960.9  502.71  4975.3  502.26  4983.3  503.52  4986.7  501.58  4987.2  500.78
  4992.2  500.78  4992.7  501.58  4999.5  501.63  5007.5  503.62  5018.0  504.20
  5049.6  503.97  5060.2  503.18  5111.4  505.47  5133.5  506.39  5197.2  509.23
  5234.1  511.27  5239.4  512.03  5260.4  513.02  5281.5  514.52  5313.1  515.41
#Mann=5,-1,0
  4676.8    0.05       0  4890.0    0.16       0  4986.7    0.07       0
  4992.7    0.16       0  5133.5    0.05       0
Bank Sta=4878.6,5111.4
Exp/Cntr=0.3,0.1

Type RM Length L Ch R = 1,2410,374,374,374
BEGIN DESCRIPTION:
UNT 093 in LFCCL Watershed 5.0
END DESCRIPTION:
XS GIS Cut Line= 3
      2827475.00      7080125.00      2827075.00      7079825.00
      2826775.04      7079775.01
#Sta/Elev= 30
  4464.4  513.07  4471.7  513.20  4477.9  512.47  4507.1  512.21  4550.9  510.94
  4657.1  506.65  4664.4  506.72  4671.7  506.02  4737.2  503.49  4742.4  503.28
  4800.9  501.83  4864.4  502.44  4915.4  501.56  4921.7  501.94  4966.4  501.75
  4971.5  499.30  4972.0  498.50  4977.0  498.50  4977.5  499.30  4984.7  499.64
  4992.3  502.20  4997.3  500.72  5029.1  503.49  5051.0  506.83  5106.3  509.52
  5174.8  511.89  5179.8  511.59  5235.6  513.74  5240.7  513.37  5268.5  513.82
#Mann=7,-1,0
  4464.4    0.05       0  4742.4    0.16       0  4915.4    0.12       0
  4966.4    0.16       0  4971.5    0.07       0  4977.5    0.16       0
  5051.0    0.05       0
Bank Sta=4737.2,5029.1
Exp/Cntr=0.3,0.1

Type RM Length L Ch R = 1,2036,168,168,168
BEGIN DESCRIPTION:
UNT 093 in LFCCL Watershed 4.0
END DESCRIPTION:
XS GIS Cut Line= 3
      2827524.98      7080024.98      2827225.00      7079575.00
      2826925.03      7079475.01
#Sta/Elev= 30
  4477.9  511.99  4521.4  511.09  4527.4  508.94  4541.3  508.20  4557.5  507.83
  4563.5  508.41  4578.5  507.93  4622.9  505.22  4671.7  503.27  4725.4  502.07
  4731.2  502.05  4815.9  500.18  4924.1  500.96  4968.0  500.28  4975.1  497.89
  4990.2  499.87  4996.2  499.32  5005.2  500.09  5011.2  499.26  5012.7  497.58
  5013.2  496.78  5018.2  496.78  5018.7  497.58  5019.7  497.58  5021.3  497.58
  5028.7  502.05  5039.8  510.32  5050.3  512.47  5240.1  514.00  5334.9  513.14
#Mann=8,-1,0
  4477.9    0.05       0  4541.3    0.08       0  4622.9    0.05       0
  4725.4    0.16       0  4968.0    0.12       0  5012.7    0.07       0
  5018.7    0.12       0  5019.7    0.05       0
Bank Sta=4731.2,5028.7
Exp/Cntr=0.3,0.1

Type RM Length L Ch R = 1,1868,414,414,414
BEGIN DESCRIPTION:
UNT 093 in LFCCL Watershed 3.0
END DESCRIPTION:
XS GIS Cut Line= 3
      2827578.37      7079921.77      2827347.14      7079519.72
      2827039.02      7079306.15
#Sta/Elev= 30
  4536.2  509.95  4604.0  506.69  4624.8  506.71  4637.6  505.49  4669.2  504.72
  4682.4  503.50  4703.6  502.65  4783.5  500.69  4794.9  500.40  4894.9  500.17
  4910.7  499.70  4932.3  500.14  4969.6  499.28  4991.2  499.33  4996.8  497.14
  4997.3  496.34  5002.3  496.34  5002.8  497.14  5019.0  500.02  5054.8  499.66
  5063.7  500.69  5075.7  507.36  5084.3  509.84  5120.3  511.45  5198.0  509.14
  5263.5  508.55  5335.1  510.80  5350.0  511.93  5356.1  513.13  5374.9  514.15
#Mann=8,-1,0
  4536.2    0.05       0  4604.0    0.08       0  4703.6    0.05       0
  4794.9    0.16       0  4932.3    0.12       0  4996.8    0.07       0
  5002.8    0.12       0  5084.3    0.05       0
Bank Sta=4783.5,5063.7
Exp/Cntr=0.3,0.1

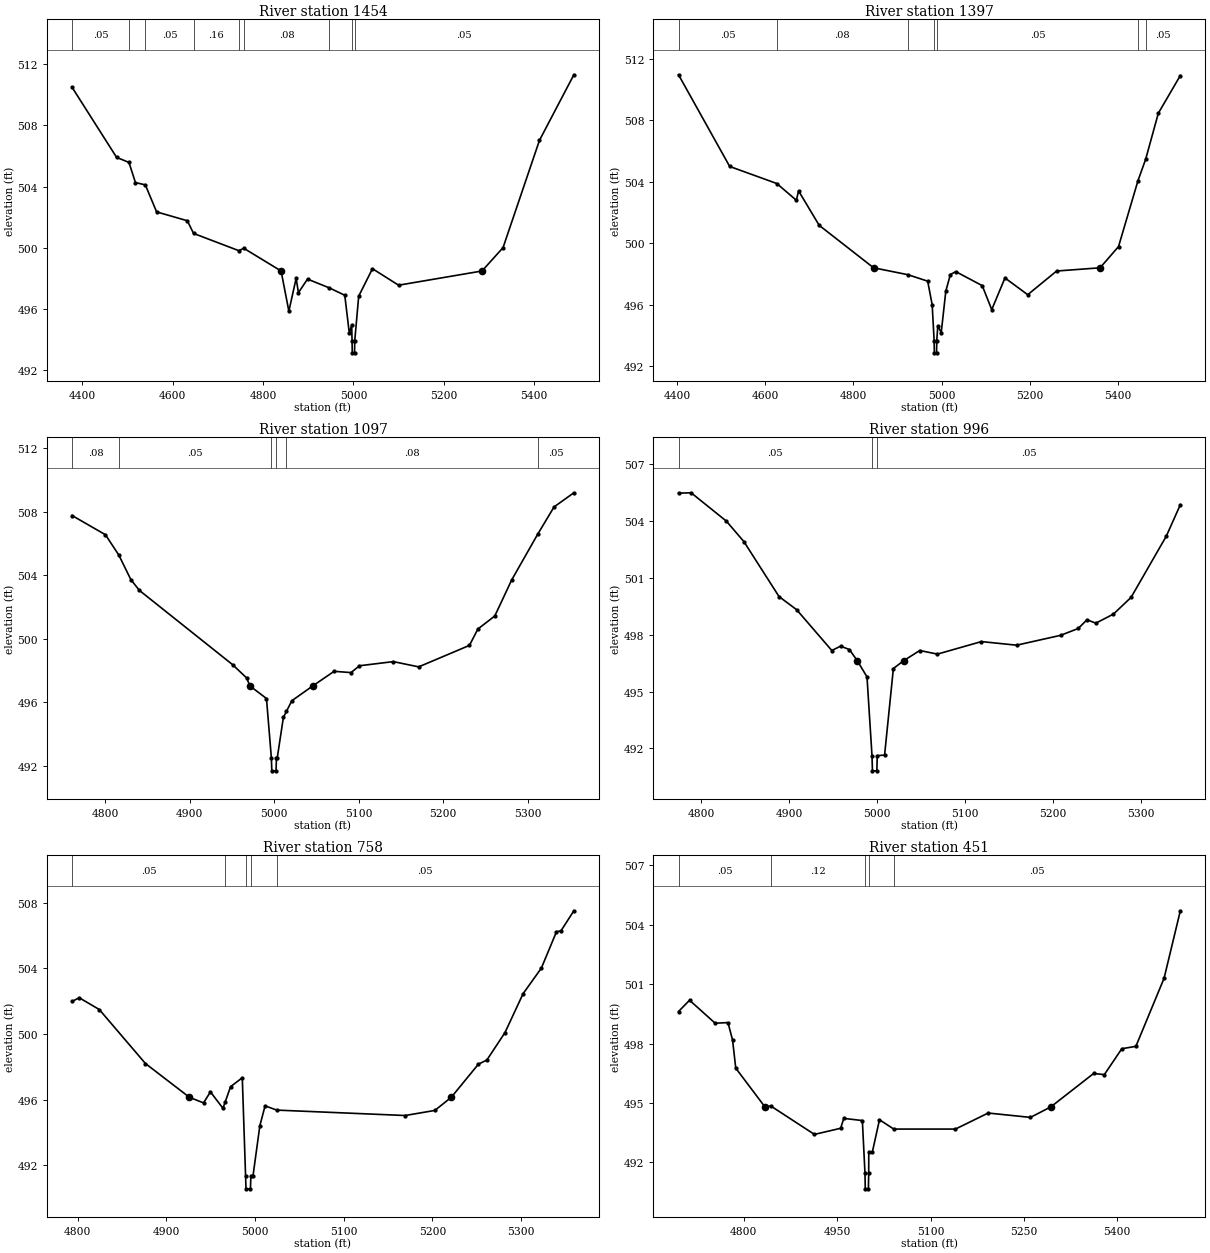
Type RM Length L Ch R = 1,1454,57,57,57
BEGIN DESCRIPTION:
Mapping XS e3891c63
END DESCRIPTION:
XS GIS Cut Line= 5
      2827628.30      7079900.09      2827504.58      7079756.83
      2827610.97      7079336.48      2827647.81      7079142.69
      2827359.60      7079103.68
#Sta/Elev= 30
  4377.1  510.50  4475.7  505.91  4503.1  505.58  4517.4  504.26  4539.3  504.11
  4564.3  502.34  4632.3  501.76  4646.1  500.93  4746.4  499.80  4757.2  499.96
  4839.9  498.47  4857.1  495.84  4873.2  497.99  4878.3  497.05  4898.4  497.94
  4947.0  497.36  4980.9  496.88  4991.0  494.38  4996.2  494.93  4997.0  493.91
  4997.5  493.11  5002.5  493.11  5003.0  493.91  5011.7  496.82  5042.2  498.62
  5100.0  497.54  5284.7  498.47  5331.3  500.00  5412.0  507.03  5488.1  511.32
#Mann=9,-1,0
  4377.1    0.05       0  4503.1    0.08       0  4539.3    0.05       0
  4646.1    0.16       0  4746.4    0.12       0  4757.2    0.08       0
  4947.0    0.05       0  4997.0    0.04       0  5003.0    0.05       0
Bank Sta=4839.9,5284.7
Exp/Cntr=0.3,0.1

Type RM Length L Ch R = 1,1397,300,300,300
BEGIN DESCRIPTION:
Mapping XS 12ed7067
END DESCRIPTION:
XS GIS Cut Line= 5
      2827663.00      7079861.00      2827571.85      7079780.71
      2827659.88      7079325.47      2827715.08      7079110.13
      2827385.24      7079084.09
#Sta/Elev= 30
  4403.2  510.96  4519.2  505.00  4626.1  503.89  4670.5  502.80  4675.5  503.41
  4722.3  501.17  4845.7  498.41  4923.6  497.96  4968.4  497.54  4978.6  496.00
  4983.0  493.68  4983.5  492.88  4988.5  492.88  4989.0  493.68  4991.4  494.64
  4999.1  494.19  5009.5  496.89  5019.8  497.97  5032.2  498.16  5092.1  497.25
  5113.7  495.69  5143.7  497.75  5195.3  496.66  5260.9  498.20  5359.5  498.41
  5401.3  499.79  5445.5  504.08  5462.9  505.47  5491.6  508.46  5541.5  510.91
#Mann=7,-1,0
  4403.2    0.05       0  4626.1    0.08       0  4923.6    0.05       0
  4983.0    0.04       0  4989.0    0.05       0  5445.5    0.08       0
  5462.9    0.05       0
Bank Sta=4845.7,5359.5
Exp/Cntr=0.3,0.1

Type RM Length L Ch R = 1,1097,101,101,101
BEGIN DESCRIPTION:
XS3681A
END DESCRIPTION:
XS GIS Cut Line= 3
      2828014.41      7079083.31      2827772.29      7079067.79
      2827421.56      7079061.58
#Sta/Elev= 30
  4761.0  507.75  4800.5  506.54  4816.3  505.26  4830.5  503.72  4840.6  503.04
  4950.8  498.37  4967.5  497.53  4971.3  497.03  4990.9  496.24  4996.7  492.49
  4997.2  491.69  5002.2  491.69  5002.7  492.49  5003.6  492.49  5010.9  495.05
  5014.5  495.43  5020.9  496.10  5045.6  497.03  5070.9  497.95  5090.9  497.87
  5100.9  498.30  5140.9  498.56  5170.9  498.23  5230.9  499.58  5240.9  500.61
  5260.9  501.43  5280.9  503.70  5311.7  506.58  5331.0  508.29  5354.4  509.18
#Mann=6,-1,0
  4761.0    0.08       0  4816.3    0.05       0  4996.7    0.04       0
  5002.7    0.05       0  5014.5    0.08       0  5311.7    0.05       0
Bank Sta=4971.3,5045.6
Exp/Cntr=0.3,0.1

Type RM Length L Ch R = 1,996,238,238,238
BEGIN DESCRIPTION:
XS3680A
END DESCRIPTION:
XS GIS Cut Line= 3
      2828039.27      7078974.67      2827812.64      7078977.78
      2827469.04      7078962.30
#Sta/Elev= 30
  4774.2  505.45  4788.5  505.47  4828.5  503.98  4848.5  502.90  4888.5  500.00
  4908.5  499.31  4948.5  497.16  4958.5  497.39  4968.5  497.21  4977.5  496.62
  4988.5  495.77  4994.2  491.62  4994.7  490.82  4999.7  490.82  5000.2  491.62
  5008.5  491.65  5018.5  496.21  5030.1  496.62  5048.5  497.16  5068.6  496.97
  5118.6  497.63  5158.6  497.44  5208.7  497.96  5228.7  498.32  5238.7  498.78
  5248.7  498.60  5268.8  499.08  5288.8  499.96  5328.8  503.18  5344.8  504.84
#Mann=3,-1,0
  4774.2    0.05       0  4994.2    0.03       0  5000.2    0.05       0
Bank Sta=4977.5,5030.1
Exp/Cntr=0.3,0.1

Type RM Length L Ch R = 1,758,307,307,307
BEGIN DESCRIPTION:
XS3679A
END DESCRIPTION:
XS GIS Cut Line= 3
      2828092.01      7078859.83      2827915.08      7078763.60
      2827559.10      7078686.21
#Sta/Elev= 30
  4793.7  501.98  4801.7  502.21  4824.4  501.49  4876.4  498.20  4926.0  496.14
  4941.9  495.80  4949.7  496.47  4963.8  495.47  4966.5  495.88  4972.4  496.79
  4985.6  497.33  4989.3  491.36  4989.8  490.56  4994.8  490.56  4995.3  491.36
  4997.7  491.36  5005.4  494.41  5011.3  495.62  5024.4  495.36  5169.2  495.03
  5202.7  495.34  5221.2  496.14  5251.8  498.16  5261.3  498.41  5281.7  500.08
  5302.2  502.46  5322.7  504.01  5339.8  506.23  5344.9  506.29  5359.4  507.51
#Mann=5,-1,0
  4793.7    0.05       0  4966.5    0.12       0  4989.3    0.07       0
  4995.3    0.12       0  5024.4    0.05       0
Bank Sta=4926,5221.2
Exp/Cntr=0.3,0.1

Type RM Length L Ch R = 1,451,0,0,0
BEGIN DESCRIPTION:
UNT 093 in LFCCL Watershed 1.0
END DESCRIPTION:
XS GIS Cut Line= 3
      2828110.63      7078782.24      2828039.51      7078483.90
      2827589.59      7078267.17
#Sta/Elev= 30
  4695.2  499.62  4712.9  500.19  4754.0  499.03  4774.6  499.06  4782.0  498.18
  4787.1  496.76  4834.0  494.80  4843.7  494.84  4913.5  493.41  4955.6  493.72
  4960.7  494.22  4990.5  494.11  4994.7  491.46  4995.2  490.66  5000.2  490.66
  5000.7  491.46  5000.8  492.50  5006.4  492.50  5018.0  494.15  5041.0  493.68
  5140.1  493.68  5192.6  494.49  5260.5  494.27  5293.2  494.80  5362.1  496.49
  5379.2  496.43  5407.3  497.74  5429.9  497.86  5475.2  501.30  5501.3  504.71
#Mann=5,-1,0
  4695.2    0.05       0  4843.7    0.12       0  4994.7    0.07       0
  5000.7    0.12       0  5041.0    0.05       0
Bank Sta=4834,5293.2
Exp/Cntr=0.3,0.1

Chan Stop Cuts=-1