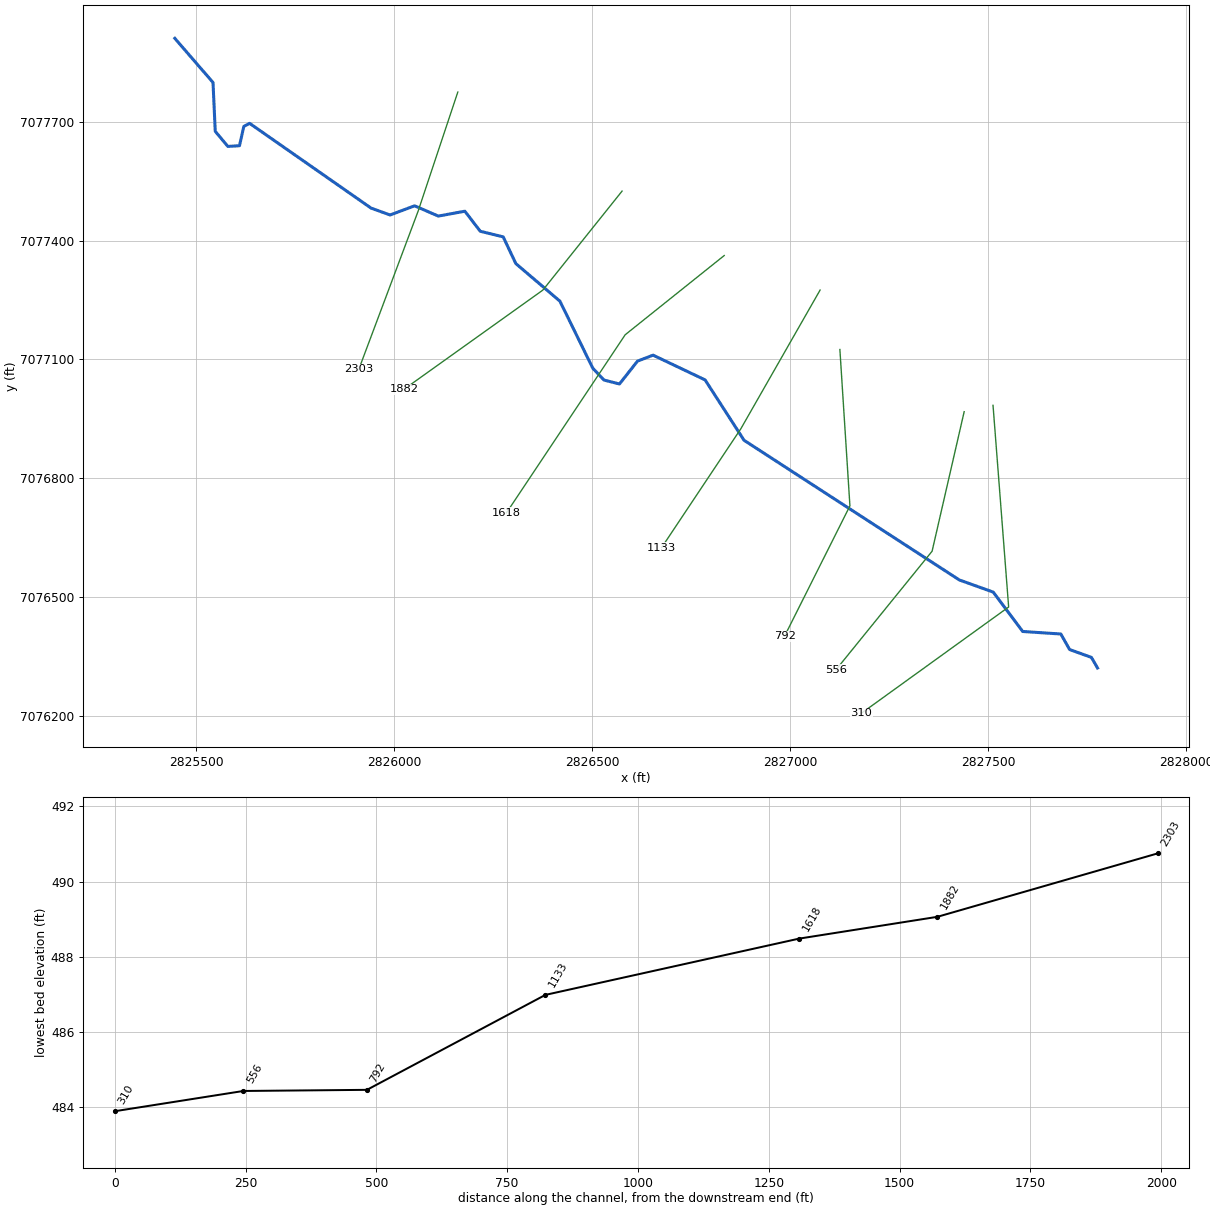
--- UNT 094 in LFCCL Watershed.prj (project) ---

Proj Title=UNT 094 in LFCCL Watershed Base Level Engineering
Current Plan=p01
Default Exp/Contr=0.3,0.1
English Units
Geom File=g01
Flow File=f01
Plan File=p01
BEGIN DESCRIPTION:
UNT 094 in LFCCL Watershed
END DESCRIPTION:

--- UNT 094 in LFCCL Watershed.p01 (plan) ---

Plan Title=Multiple Run
Short Identifier=Multiple
Geom File=g01
Flow File=f01
Subcritical Flow
K Sum by GR= 0
Std Step Tol= 0.01
Critical Tol= 0.01
Num of Std Step Trials= 20
Max Error Tol= 0.3
Flow Tol Ratio= 0.001
Split Flow NTrial= 30
Split Flow Tol= 0.02
Split Flow Ratio= 0.02
Log Output Level= 0
Friction Slope Method= 1
Unsteady Friction Slope Method= 2
Unsteady Bridges Friction Slope Method= 1
Parabolic Critical Depth
Global Vel Dist=  1 , 1 , 1
Global Log Level= 0
CheckData=True
Encroach Param= -1, 0, 0, 0
BEGIN DESCRIPTION:
Multiple Run
END DESCRIPTION:

--- UNT 094 in LFCCL Watershed.f01 (steady flow) ---

Flow Title=Multiple
Number of Profiles=7
Profile Names=10-year,25-year,50-year,1pct_min,100-year,1pct_plu,500-year
River Rch & RM= UNT 094 in LFCCL,Reach-1,2303
     569     752     898     532    1062    2119    1481
Boundary for River Rch & Prof#=UNT 094 in LFCCL,Reach-1,1
Up Type=0
Dn Type=3
Dn Slope=0.005
Boundary for River Rch & Prof#=UNT 094 in LFCCL,Reach-1,2
Up Type=0
Dn Type=3
Dn Slope=0.005
Boundary for River Rch & Prof#=UNT 094 in LFCCL,Reach-1,3
Up Type=0
Dn Type=3
Dn Slope=0.005
Boundary for River Rch & Prof#=UNT 094 in LFCCL,Reach-1,4
Up Type=0
Dn Type=3
Dn Slope=0.005
Boundary for River Rch & Prof#=UNT 094 in LFCCL,Reach-1,5
Up Type=0
Dn Type=3
Dn Slope=0.005
Boundary for River Rch & Prof#=UNT 094 in LFCCL,Reach-1,6
Up Type=0
Dn Type=3
Dn Slope=0.005
Boundary for River Rch & Prof#=UNT 094 in LFCCL,Reach-1,7
Up Type=0
Dn Type=3
Dn Slope=0.005

--- UNT 094 in LFCCL Watershed.g01 (geometry) ---

Geom Title=Existing Conditions

River Reach=UNT 094 in LFCCL,Reach-1
Reach XY= 30
      2825445.59      7077910.71      2825542.04      7077799.24
      2825547.73      7077675.88      2825579.48      7077637.84
      2825608.90      7077639.51      2825619.87      7077688.27
      2825634.56      7077696.00      2825941.27      7077481.96
      2825989.18      7077464.67      2826051.07      7077487.81
      2826110.95      7077461.89      2826178.01      7077474.16
      2826216.86      7077423.60      2826274.78      7077409.38
      2826306.77      7077341.87      2826418.01      7077247.08
      2826501.01      7077077.79      2826529.37      7077047.82
      2826568.44      7077037.90      2826613.97      7077095.64
      2826653.29      7077110.68      2826784.61      7077048.22
      2826882.99      7076895.76      2827426.57      7076543.08
      2827512.23      7076512.35      2827586.54      7076412.96
      2827682.98      7076406.55      2827704.97      7076367.41
      2827760.12      7076347.49      2827775.59      7076320.71

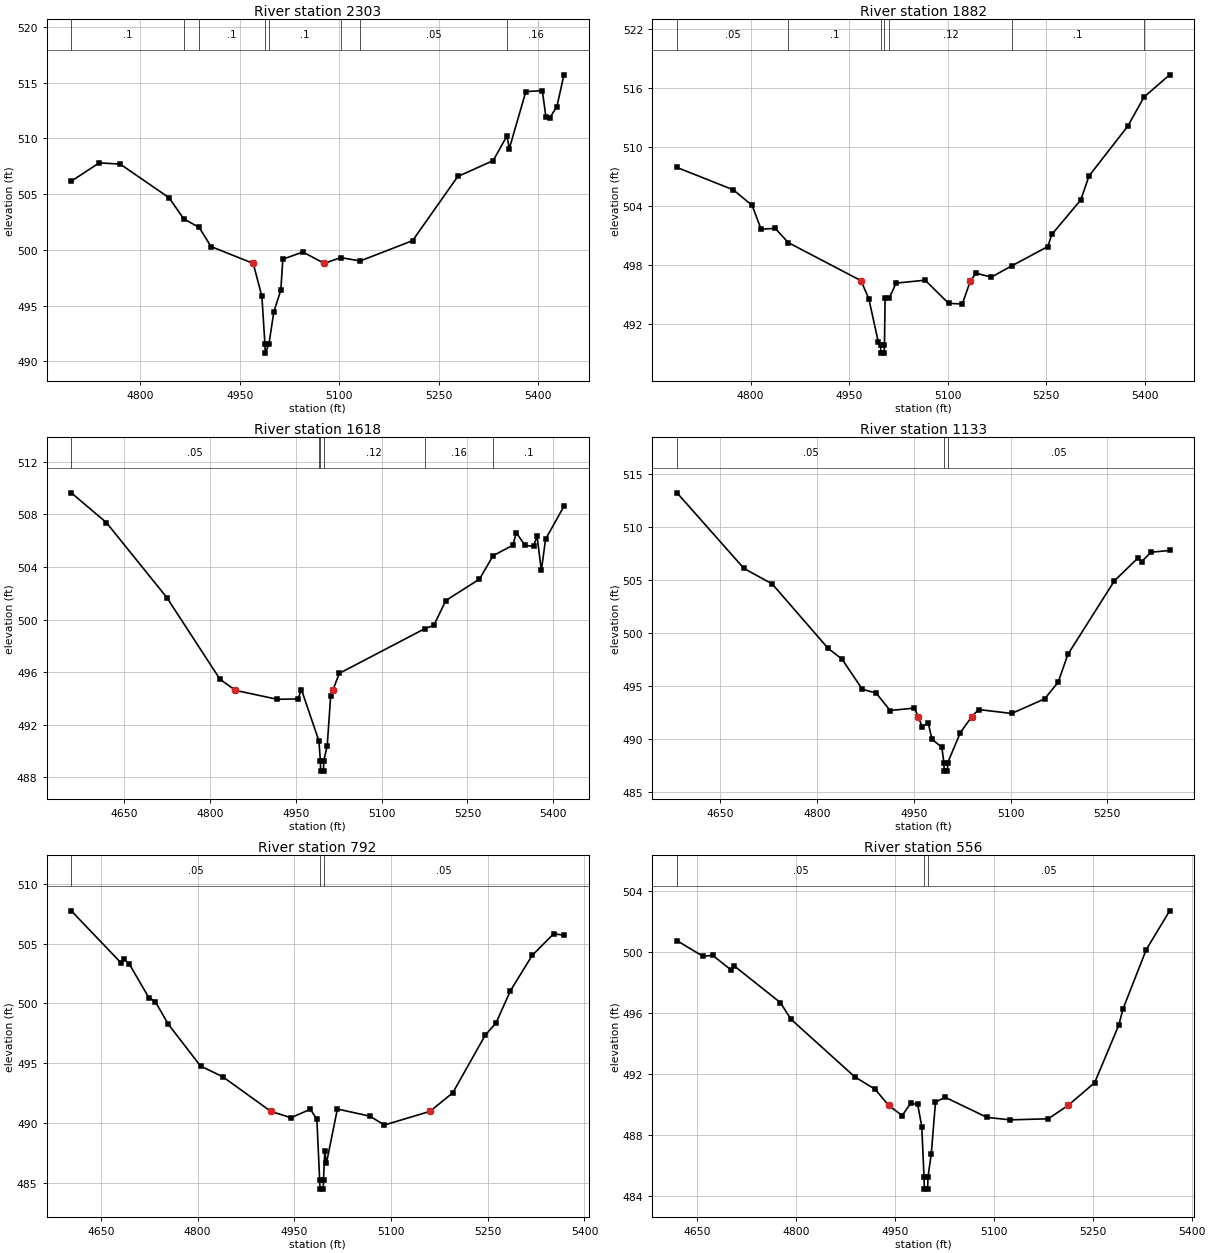
Type RM Length L Ch R = 1,2303,421,421,421
BEGIN DESCRIPTION:
UNT 094 in LFCCL Watershed 6.0
END DESCRIPTION:
XS GIS Cut Line= 3
      2826160.21      7077775.01      2826060.21      7077475.00
      2825910.22      7077075.04
#Sta/Elev= 30
  4695.7  506.16  4737.9  507.80  4769.5  507.69  4843.3  504.67  4865.4  502.78
  4888.8  502.01  4906.5  500.30  4970.2  498.79  4983.3  495.84  4987.9  491.55
  4988.4  490.75  4993.9  491.55  5001.4  494.47  5011.9  496.40  5014.9  499.17
  5045.2  499.81  5077.5  498.79  5102.3  499.31  5131.7  499.01  5210.7  500.83
  5278.9  506.58  5332.3  508.00  5353.1  510.21  5356.7  509.08  5381.6  514.19
  5406.5  514.27  5411.9  511.91  5417.8  511.84  5428.5  512.85  5439.1  515.69
#Mann=8,-1,0
  4695.7     0.1       0  4865.4    0.16       0  4888.8     0.1       0
  4987.9    0.07       0  4993.9     0.1       0  5102.3     0.1       0
  5131.7    0.05       0  5353.1    0.16       0
Bank Sta=4970.2,5077.5
Exp/Cntr=0.3,0.1

Type RM Length L Ch R = 1,1882,264,264,264
BEGIN DESCRIPTION:
UNT 094 in LFCCL Watershed 5.0
END DESCRIPTION:
XS GIS Cut Line= 3
      2826574.97      7077524.96      2826375.00      7077275.00
      2826025.02      7077025.01
#Sta/Elev= 30
  4687.9  507.92  4773.5  505.65  4802.3  504.07  4815.9  501.65  4837.5  501.73
  4857.3  500.29  4968.1  496.42  4980.0  494.58  4994.4  490.20  4997.8  489.86
  4998.3  489.06  5003.3  489.06  5003.8  489.86  5004.8  494.65  5011.2  494.67
  5021.5  496.17  5065.8  496.47  5101.4  494.12  5122.3  494.05  5134.8  496.42
  5143.2  497.18  5166.5  496.78  5197.3  497.91  5252.6  499.89  5258.7  501.12
  5302.9  504.63  5315.2  507.05  5374.2  512.10  5399.2  515.08  5438.1  517.33
#Mann=7,-1,0
  4687.9    0.05       0  4857.3     0.1       0  4997.8    0.07       0
  5003.8     0.1       0  5011.2    0.12       0  5197.3     0.1       0
  5399.2    0.16       0
Bank Sta=4968.1,5134.8
Exp/Cntr=0.3,0.1

Type RM Length L Ch R = 1,1618,485,485,485
BEGIN DESCRIPTION:
UNT 094 in LFCCL Watershed 4.0
END DESCRIPTION:
XS GIS Cut Line= 3
      2826832.90      7077362.23      2826582.89      7077162.22
      2826282.89      7076712.22
#Sta/Elev= 30
  4557.6  509.64  4618.9  507.38  4724.5  501.68  4817.4  495.47  4844.5  494.62
  4917.8  493.94  4953.8  493.97  4959.8  494.68  4990.4  490.77  4992.9  489.28
  4993.4  488.48  4998.4  488.48  4998.9  489.28  5004.9  490.40  5010.9  494.20
  5014.6  494.62  5025.9  495.91  5175.3  499.31  5191.2  499.56  5212.2  501.45
  5271.0  503.08  5294.8  504.86  5329.4  505.66  5335.4  506.61  5350.4  505.65
  5365.5  505.57  5371.5  506.37  5379.2  503.74  5386.5  506.12  5418.6  508.61
#Mann=6,-1,0
  4557.6    0.05       0  4990.4    0.12       0  4992.9    0.07       0
  4998.9    0.12       0  5175.3    0.16       0  5294.8     0.1       0
Bank Sta=4844.5,5014.6
Exp/Cntr=0.3,0.1

Type RM Length L Ch R = 1,1133,341,341,341
BEGIN DESCRIPTION:
UNT 094 in LFCCL Watershed 3.0
END DESCRIPTION:
XS GIS Cut Line= 3
      2827075.01      7077275.02      2826875.00      7076925.00
      2826674.99      7076624.99
#Sta/Elev= 30
  4582.9  513.24  4686.6  506.11  4730.5  504.64  4816.9  498.58  4838.5  497.56
  4870.1  494.71  4891.7  494.34  4913.3  492.70  4950.8  492.93  4956.9  492.11
  4963.0  491.16  4972.4  491.52  4978.1  489.99  4993.5  489.23  4996.6  487.78
  4997.1  486.98  5002.1  486.98  5002.6  487.78  5022.1  490.61  5039.7  492.11
  5050.6  492.79  5101.7  492.42  5152.8  493.80  5173.8  495.37  5188.8  497.99
  5261.0  504.94  5297.0  507.06  5303.0  506.75  5318.0  507.64  5346.6  507.80
#Mann=3,-1,0
  4582.9    0.05       0  4996.6    0.03       0  5002.6    0.05       0
Bank Sta=4956.9,5039.7
Exp/Cntr=0.3,0.1

Type RM Length L Ch R = 1,792,236,236,236
BEGIN DESCRIPTION:
UNT 094 in LFCCL Watershed 2.0
END DESCRIPTION:
XS GIS Cut Line= 3
      2827125.00      7077124.98      2827150.33      7076730.09
      2826985.26      7076400.97
#Sta/Elev= 30
  4604.3  507.76  4680.9  503.43  4685.9  503.74  4694.5  503.28  4724.5  500.49
  4734.5  500.16  4754.6  498.27  4804.7  494.76  4839.2  493.86  4913.8  490.96
  4945.0  490.43  4975.0  491.14  4985.1  490.30  4989.4  485.25  4989.9  484.45
  4994.9  484.45  4995.4  485.25  4997.4  487.64  5000.0  486.64  5016.9  491.16
  5067.4  490.56  5089.8  489.82  5160.3  490.96  5195.9  492.52  5246.2  497.35
  5262.9  498.37  5285.3  501.07  5318.9  504.02  5352.3  505.84  5368.2  505.72
#Mann=3,-1,0
  4604.3    0.05       0  4989.4    0.03       0  4995.4    0.05       0
Bank Sta=4913.8,5160.3
Exp/Cntr=0.3,0.1

Type RM Length L Ch R = 1,556,246,246,246
BEGIN DESCRIPTION:
XS3682A
END DESCRIPTION:
XS GIS Cut Line= 3
      2827438.81      7076967.91      2827357.82      7076615.61
      2827114.83      7076315.93
#Sta/Elev= 30
  4619.3  500.74  4658.4  499.72  4673.6  499.77  4701.2  498.82  4706.4  499.07
  4776.2  496.67  4792.1  495.58  4889.1  491.79  4919.8  490.98  4940.4  489.92
  4960.9  489.25  4973.7  490.06  4984.4  489.98  4990.6  488.53  4994.0  485.22
  4994.5  484.42  4999.5  484.42  5000.0  485.22  5005.0  486.73  5011.4  490.13
  5025.8  490.46  5089.7  489.13  5124.9  488.97  5182.4  489.04  5212.6  489.92
  5252.8  491.41  5289.5  495.20  5295.9  496.26  5331.1  500.15  5366.6  502.70
#Mann=3,-1,0
  4619.3    0.05       0  4994.0    0.03       0  5000.0    0.05       0
Bank Sta=4940.4,5212.6
Exp/Cntr=0.3,0.1

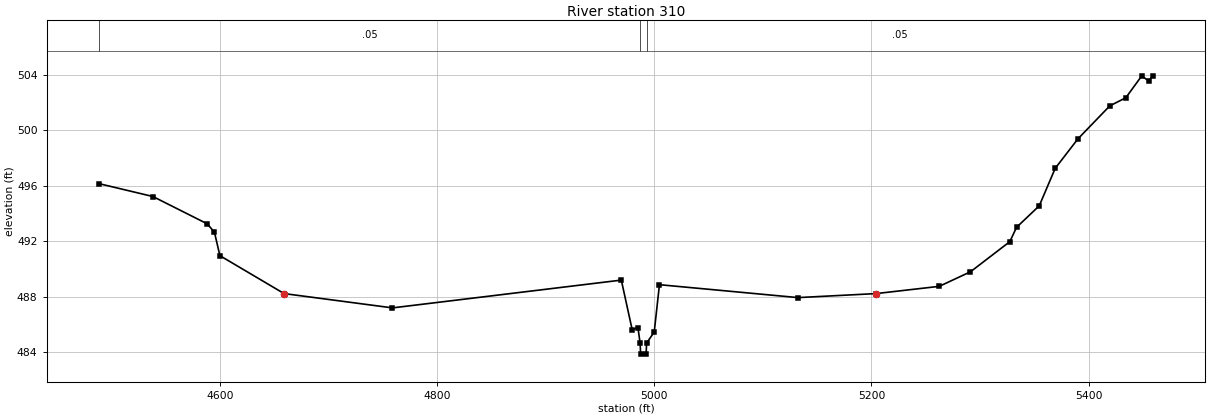
Type RM Length L Ch R = 1,310,0,0,0
BEGIN DESCRIPTION:
UNT 094 in LFCCL Watershed 1.0
END DESCRIPTION:
XS GIS Cut Line= 3
      2827511.69      7076984.14      2827551.13      7076474.76
      2827178.92      7076206.16
#Sta/Elev= 30
  4489.1  496.15  4538.4  495.23  4588.5  493.26  4595.1  492.65  4600.1  490.97
  4659.2  488.24  4759.0  487.21  4969.7  489.21  4979.7  485.64  4985.0  485.79
  4987.0  484.68  4987.5  483.88  4992.5  483.88  4993.0  484.68  5000.0  485.47
  5004.8  488.88  5132.4  487.95  5204.3  488.24  5262.4  488.76  5291.2  489.81
  5327.4  491.98  5333.6  493.01  5354.5  494.56  5369.2  497.26  5390.1  499.38
  5419.5  501.76  5434.2  502.34  5448.9  503.92  5455.1  503.55  5459.0  503.91
#Mann=3,-1,0
  4489.1    0.05       0  4987.0    0.03       0  4993.0    0.05       0
Bank Sta=4659.2,5204.3
Exp/Cntr=0.3,0.1

Chan Stop Cuts=-1