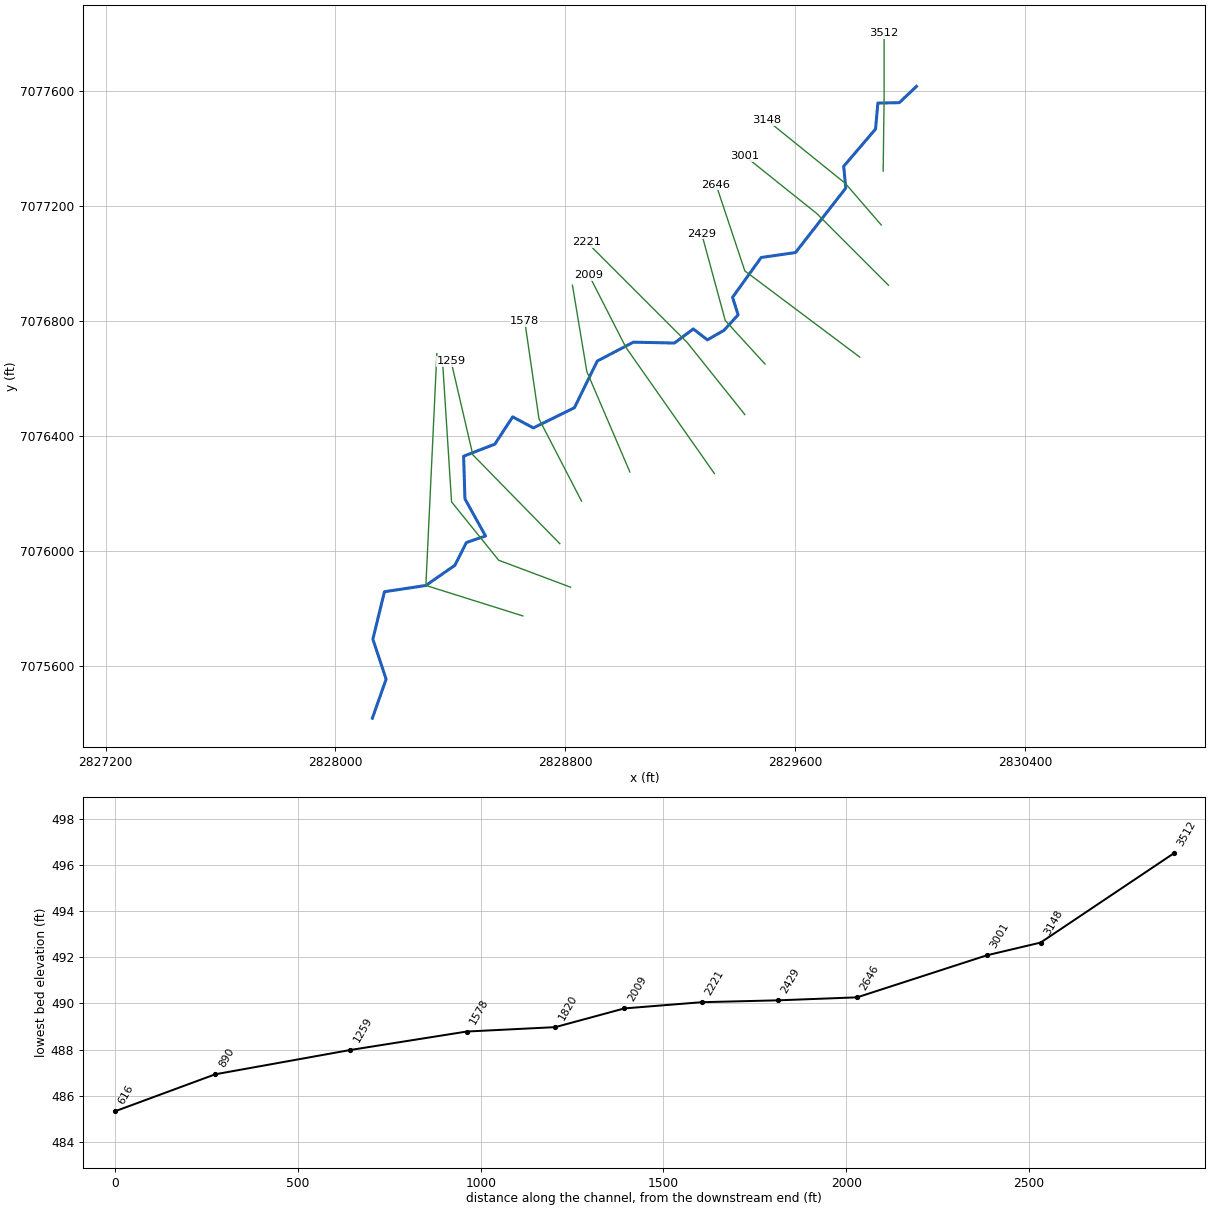
--- UNT 095 in LFCCL Watershed.prj (project) ---

Proj Title=UNT 095 in LFCCL Watershed Base Level Engineering
Current Plan=p01
Default Exp/Contr=0.3,0.1
English Units
Geom File=g01
Flow File=f01
Plan File=p01
BEGIN DESCRIPTION:
UNT 095 in LFCCL Watershed
END DESCRIPTION:

--- UNT 095 in LFCCL Watershed.p01 (plan) ---

Plan Title=Multiple Run
Short Identifier=Multiple
Geom File=g01
Flow File=f01
Subcritical Flow
K Sum by GR= 0
Std Step Tol= 0.01
Critical Tol= 0.01
Num of Std Step Trials= 20
Max Error Tol= 0.3
Flow Tol Ratio= 0.001
Split Flow NTrial= 30
Split Flow Tol= 0.02
Split Flow Ratio= 0.02
Log Output Level= 0
Friction Slope Method= 1
Unsteady Friction Slope Method= 2
Unsteady Bridges Friction Slope Method= 1
Parabolic Critical Depth
Global Vel Dist=  1 , 1 , 1
Global Log Level= 0
CheckData=True
Encroach Param= -1, 0, 0, 0
BEGIN DESCRIPTION:
Multiple Run
END DESCRIPTION:

--- UNT 095 in LFCCL Watershed.f01 (steady flow) ---

Flow Title=Multiple
Number of Profiles=7
Profile Names=10-year,25-year,50-year,1pct_min,100-year,1pct_plu,500-year
River Rch & RM= UNT 095 in LFCCL,Reach-1,3512
     526     690     821     484     966    1928    1336
Boundary for River Rch & Prof#=UNT 095 in LFCCL,Reach-1,1
Up Type=0
Dn Type=3
Dn Slope=0.005
Boundary for River Rch & Prof#=UNT 095 in LFCCL,Reach-1,2
Up Type=0
Dn Type=3
Dn Slope=0.005
Boundary for River Rch & Prof#=UNT 095 in LFCCL,Reach-1,3
Up Type=0
Dn Type=3
Dn Slope=0.005
Boundary for River Rch & Prof#=UNT 095 in LFCCL,Reach-1,4
Up Type=0
Dn Type=3
Dn Slope=0.005
Boundary for River Rch & Prof#=UNT 095 in LFCCL,Reach-1,5
Up Type=0
Dn Type=3
Dn Slope=0.005
Boundary for River Rch & Prof#=UNT 095 in LFCCL,Reach-1,6
Up Type=0
Dn Type=3
Dn Slope=0.005
Boundary for River Rch & Prof#=UNT 095 in LFCCL,Reach-1,7
Up Type=0
Dn Type=3
Dn Slope=0.005

--- UNT 095 in LFCCL Watershed.g01 (geometry) ---

Geom Title=Existing Conditions

River Reach=UNT 095 in LFCCL,Reach-1
Reach XY= 30
      2830022.48      7077617.25      2829962.67      7077560.57
      2829888.14      7077559.29      2829879.92      7077468.69
      2829769.15      7077339.12      2829776.36      7077263.29
      2829601.40      7077038.88      2829481.91      7077021.73
      2829382.28      7076883.14      2829401.57      7076822.11
      2829352.53      7076768.33      2829294.79      7076735.02
      2829245.47      7076772.97      2829180.07      7076723.97
      2829037.15      7076726.98      2828911.40      7076661.25
      2828831.88      7076498.80      2828689.00      7076428.49
      2828616.98      7076467.03      2828554.81      7076371.97
      2828446.22      7076330.05      2828450.79      7076181.68
      2828522.48      7076052.32      2828455.89      7076029.64
      2828415.78      7075950.27      2828314.83      7075880.20
      2828170.66      7075858.28      2828130.30      7075693.36
      2828176.43      7075553.82      2828128.52      7075418.04

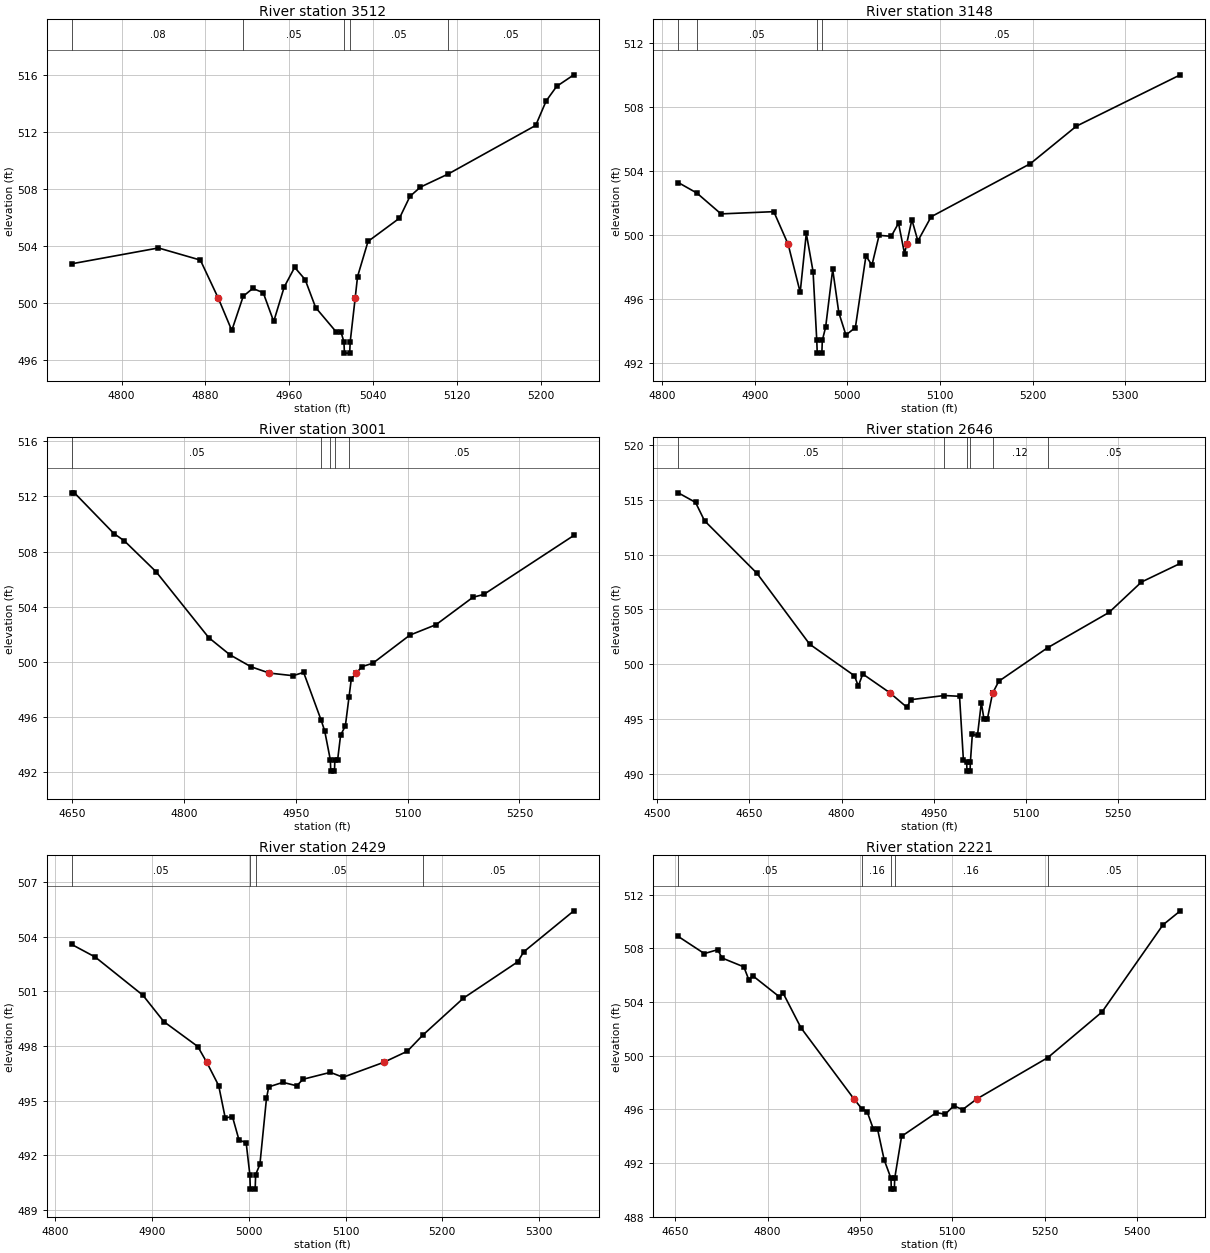
Type RM Length L Ch R = 1,3512,364,364,364
BEGIN DESCRIPTION:
XS3686A
END DESCRIPTION:
XS GIS Cut Line= 3
      2829906.54      7077322.33      2829909.83      7077579.07
      2829909.83      7077801.41
#Sta/Elev= 30
  4752.5  502.76  4835.2  503.87  4875.2  503.02  4892.4  500.33  4905.2  498.08
  4916.1  500.48  4925.2  501.03  4935.2  500.73  4945.2  498.71  4955.2  501.13
  4965.2  502.51  4975.2  501.65  4985.2  499.69  5004.7  497.99  5009.3  497.99
  5012.2  497.29  5012.7  496.49  5017.7  496.49  5018.2  497.29  5022.9  500.33
  5025.2  501.86  5035.2  504.33  5065.2  505.96  5075.2  507.49  5085.2  508.14
  5111.7  509.06  5195.2  512.47  5205.2  514.19  5215.2  515.21  5231.6  516.02
#Mann=5,-1,0
  4752.5    0.08       0  4916.1    0.05       0  5012.2    0.04       0
  5018.2    0.05       0  5111.7    0.05       0
Bank Sta=4892.4,5022.9
Exp/Cntr=0.3,0.1

Type RM Length L Ch R = 1,3148,147,147,147
BEGIN DESCRIPTION:
XS3687A
END DESCRIPTION:
XS GIS Cut Line= 3
      2829899.93      7077134.79      2829774.89      7077279.57
      2829501.85      7077499.97
#Sta/Elev= 30
  4817.4  503.29  4837.6  502.63  4863.6  501.33  4920.6  501.47  4936.1  499.43
  4949.1  496.43  4955.7  500.11  4963.0  497.73  4967.0  493.43  4967.5  492.63
  4972.5  492.63  4973.0  493.43  4976.6  494.26  4984.2  497.86  4990.8  495.16
  4998.5  493.76  5008.7  494.23  5020.1  498.70  5026.6  498.13  5034.3  499.99
  5047.4  499.93  5055.3  500.75  5061.8  498.84  5064.0  499.43  5069.7  500.97
  5076.2  499.64  5090.5  501.15  5197.7  504.47  5247.3  506.81  5359.6  510.02
#Mann=4,-1,0
  4817.4    0.08       0  4837.6    0.05       0  4967.0    0.03       0
  4973.0    0.05       0
Bank Sta=4936.1,5064
Exp/Cntr=0.3,0.1

Type RM Length L Ch R = 1,3001,355,355,355
BEGIN DESCRIPTION:
UNT 095 in LFCCL Watershed 5.0
END DESCRIPTION:
XS GIS Cut Line= 3
      2829924.97      7076925.03      2829675.00      7077175.00
      2829424.97      7077375.02
#Sta/Elev= 30
  4649.3  512.26  4652.8  512.26  4705.8  509.31  4720.0  508.77  4762.4  506.54
  4833.1  501.76  4861.4  500.52  4889.7  499.65  4914.4  499.19  4946.2  499.00
  4960.4  499.24  4984.0  495.76  4988.7  494.99  4996.3  492.88  4996.8  492.08
  5001.8  492.08  5002.3  492.88  5006.0  492.88  5010.0  494.68  5016.4  495.36
  5021.4  497.49  5024.4  498.77  5031.0  499.19  5038.8  499.66  5053.2  499.90
  5102.9  501.94  5138.1  502.70  5187.7  504.69  5202.1  504.89  5323.0  509.17
#Mann=5,-1,0
  4649.3    0.05       0  4984.0    0.16       0  4996.3    0.07       0
  5002.3    0.16       0  5021.4    0.05       0
Bank Sta=4914.4,5031
Exp/Cntr=0.3,0.1

Type RM Length L Ch R = 1,2646,217,217,217
BEGIN DESCRIPTION:
UNT 095 in LFCCL Watershed 4.0
END DESCRIPTION:
XS GIS Cut Line= 3
      2829825.02      7076674.99      2829425.00      7076975.00
      2829325.02      7077274.95
#Sta/Elev= 30
  4534.5  515.62  4562.6  514.75  4577.2  513.08  4662.6  508.28  4748.1  501.83
  4821.0  498.95  4827.2  498.01  4834.5  499.11  4878.0  497.42  4906.4  496.07
  4912.6  496.77  4966.8  497.15  4991.8  497.08  4998.1  491.25  5003.4  491.06
  5003.9  490.26  5008.9  490.26  5009.4  491.06  5012.6  493.60  5021.0  493.53
  5027.2  496.49  5031.4  495.05  5037.2  495.05  5045.4  497.34  5046.1  497.42
  5055.6  498.45  5134.9  501.50  5234.8  504.72  5287.5  507.49  5350.7  509.19
#Mann=6,-1,0
  4534.5    0.05       0  4966.8    0.16       0  5003.4    0.07       0
  5009.4    0.16       0  5045.4    0.12       0  5134.9    0.05       0
Bank Sta=4878,5046.1
Exp/Cntr=0.3,0.1

Type RM Length L Ch R = 1,2429,208,208,208
BEGIN DESCRIPTION:
XS3685A
END DESCRIPTION:
XS GIS Cut Line= 3
      2829495.16      7076650.91      2829356.90      7076802.34
      2829274.63      7077105.11
#Sta/Elev= 30
  4817.1  503.58  4841.3  502.89  4890.6  500.79  4912.2  499.34  4947.3  497.97
  4956.6  497.10  4968.9  495.82  4975.7  494.04  4983.1  494.12  4989.9  492.83
  4997.3  492.68  5001.1  490.93  5001.6  490.13  5006.6  490.13  5007.1  490.93
  5011.5  491.49  5018.3  495.12  5020.6  495.75  5035.3  496.00  5049.6  495.81
  5056.0  496.17  5084.3  496.55  5097.4  496.28  5139.4  497.10  5163.8  497.71
  5179.7  498.59  5221.8  500.63  5278.0  502.63  5284.0  503.17  5335.9  505.43
#Mann=4,-1,0
  4817.1    0.05       0  5001.1    0.03       0  5007.1    0.05       0
  5179.7    0.05       0
Bank Sta=4956.6,5139.4
Exp/Cntr=0.3,0.1

Type RM Length L Ch R = 1,2221,212,212,212
BEGIN DESCRIPTION:
UNT 095 in LFCCL Watershed 3.0
END DESCRIPTION:
XS GIS Cut Line= 3
      2829425.00      7076474.99      2829225.00      7076725.00
      2828875.03      7077074.97
#Sta/Elev= 30
  4655.0  508.90  4697.4  507.62  4719.0  507.91  4726.2  507.29  4761.5  506.63
  4769.5  505.68  4775.9  505.97  4819.1  504.40  4825.5  504.65  4854.3  502.08
  4940.4  496.77  4953.1  496.04  4961.6  495.84  4972.0  494.50  4978.7  494.50
  4989.3  492.24  5000.4  490.85  5000.9  490.05  5005.9  490.05  5006.4  490.85
  5017.6  493.99  5074.2  495.76  5088.3  495.63  5102.4  496.27  5116.6  495.98
  5139.5  496.77  5255.0  499.86  5342.9  503.26  5441.9  509.76  5470.1  510.81
#Mann=5,-1,0
  4655.0    0.05       0  4953.1    0.16       0  5000.4    0.07       0
  5006.4    0.16       0  5255.0    0.05       0
Bank Sta=4940.4,5139.5
Exp/Cntr=0.3,0.1

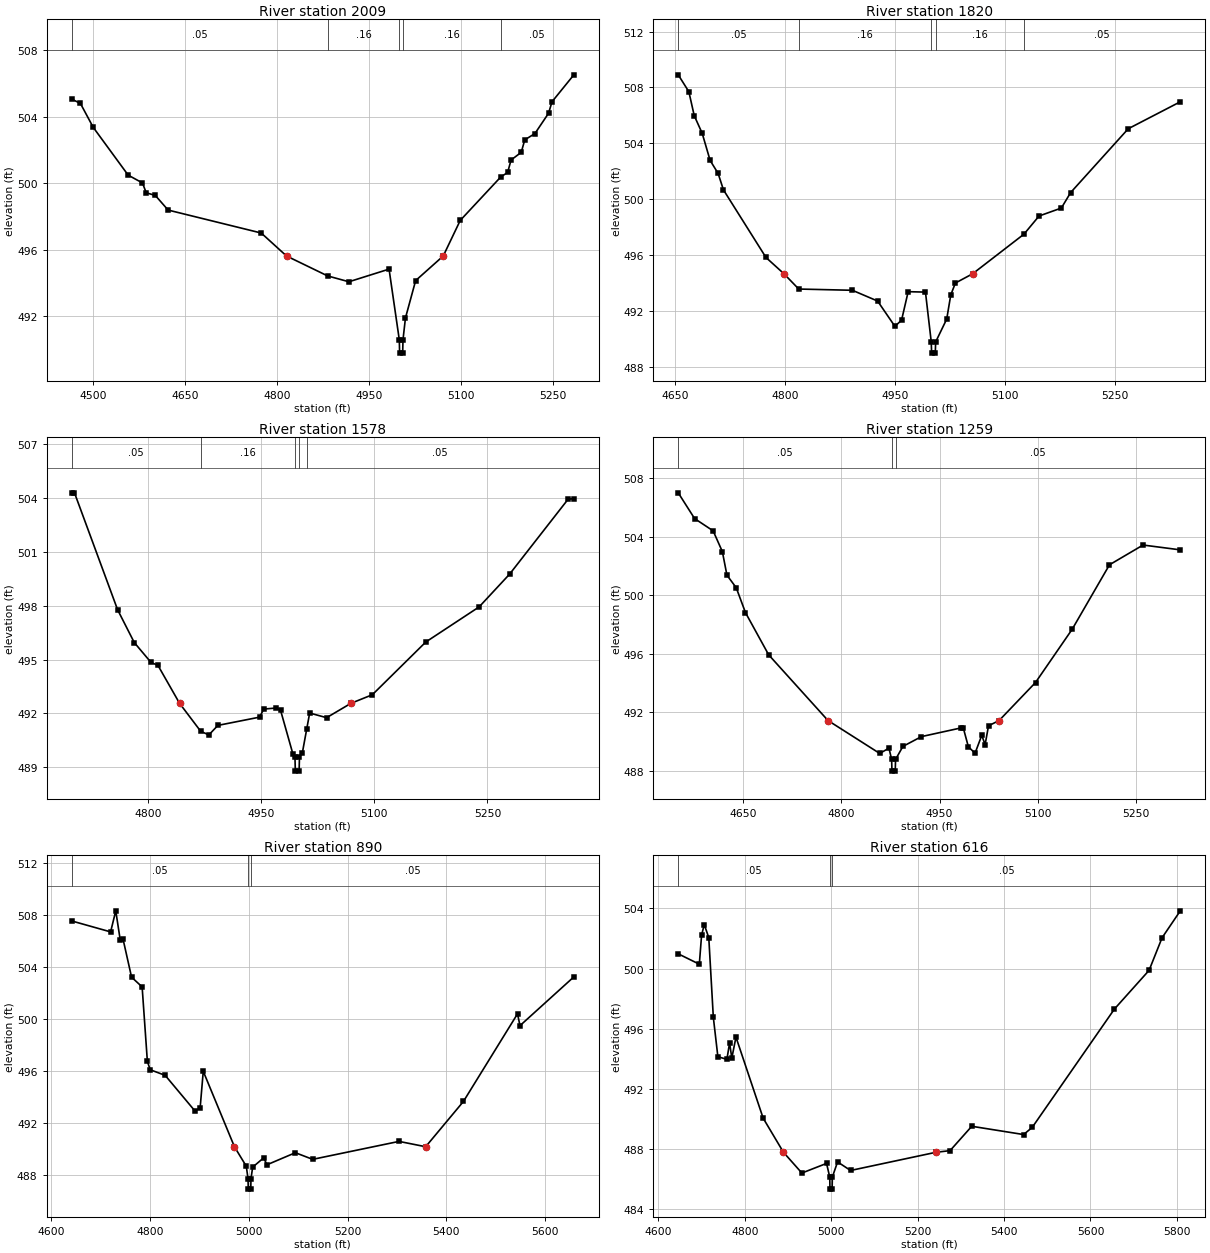
Type RM Length L Ch R = 1,2009,189,189,189
BEGIN DESCRIPTION:
Mapping XS 9e875469
END DESCRIPTION:
XS GIS Cut Line= 3
      2829318.98      7076269.77      2829010.85      7076709.19
      2828882.83      7076959.80
#Sta/Elev= 30
  4465.5  505.05  4479.6  504.79  4500.5  503.35  4557.4  500.48  4580.7  500.01
  4586.8  499.42  4601.6  499.26  4622.5  498.38  4774.2  497.00  4815.4  495.62
  4882.5  494.42  4917.1  494.07  4982.5  494.83  4999.2  490.58  4999.7  489.78
  5004.7  489.78  5005.2  490.58  5009.2  491.89  5025.8  494.14  5070.8  495.62
  5098.5  497.76  5164.5  500.37  5175.7  500.64  5181.3  501.39  5197.9  501.85
  5203.6  502.60  5220.2  502.98  5242.4  504.20  5248.0  504.89  5283.6  506.51
#Mann=5,-1,0
  4465.5    0.05       0  4882.5    0.16       0  4999.2    0.07       0
  5005.2    0.16       0  5164.5    0.05       0
Bank Sta=4815.4,5070.8
Exp/Cntr=0.3,0.1

Type RM Length L Ch R = 1,1820,242,242,242
BEGIN DESCRIPTION:
UNT 095 in LFCCL Watershed 2.0
END DESCRIPTION:
XS GIS Cut Line= 3
      2829025.01      7076274.97      2828875.00      7076625.00
      2828824.99      7076925.04
#Sta/Elev= 30
  4653.9  508.90  4668.4  507.69  4675.7  505.98  4686.6  504.71  4697.4  502.77
  4708.3  501.84  4715.6  500.66  4773.6  495.82  4798.2  494.65  4818.3  493.56
  4891.5  493.47  4925.9  492.70  4949.5  490.89  4958.6  491.33  4967.6  493.37
  4991.2  493.34  4999.1  489.77  4999.6  488.97  5004.6  488.97  5005.1  489.77
  5020.2  491.41  5025.7  493.13  5032.0  493.99  5055.5  494.65  5125.6  497.49
  5146.2  498.79  5176.6  499.36  5189.3  500.47  5267.9  505.04  5338.9  506.97
#Mann=5,-1,0
  4653.9    0.05       0  4818.3    0.16       0  4999.1    0.07       0
  5005.1    0.16       0  5125.6    0.05       0
Bank Sta=4798.2,5055.5
Exp/Cntr=0.3,0.1

Type RM Length L Ch R = 1,1578,319,319,319
BEGIN DESCRIPTION:
XS3684A
END DESCRIPTION:
XS GIS Cut Line= 3
      2828856.64      7076173.70      2828708.53      7076460.05
      2828659.15      7076799.08
#Sta/Elev= 30
  4699.4  504.30  4703.0  504.30  4760.1  497.78  4782.2  495.95  4804.4  494.84
  4813.5  494.68  4842.2  492.56  4870.2  491.00  4881.0  490.80  4892.9  491.33
  4948.1  491.79  4953.7  492.24  4970.2  492.30  4975.9  492.18  4992.4  489.72
  4995.0  489.58  4995.5  488.78  5000.5  488.78  5001.0  489.58  5004.8  489.80
  5010.6  491.13  5014.5  492.02  5036.9  491.76  5069.1  492.56  5097.5  493.04
  5168.3  495.98  5239.0  497.94  5279.4  499.77  5356.9  503.95  5364.4  503.97
#Mann=5,-1,0
  4699.4    0.05       0  4870.2    0.16       0  4995.0    0.07       0
  5001.0    0.16       0  5010.6    0.05       0
Bank Sta=4842.2,5069.1
Exp/Cntr=0.3,0.1

Type RM Length L Ch R = 1,1259,369,369,369
BEGIN DESCRIPTION:
XS3683A
END DESCRIPTION:
XS GIS Cut Line= 3
      2828780.92      7076025.62      2828478.14      7076334.98
      2828402.53      7076660.44
#Sta/Elev= 30
  4550.8  507.01  4575.8  505.25  4604.1  504.41  4618.2  502.99  4625.2  501.38
  4639.4  500.52  4653.5  498.82  4689.0  495.93  4779.6  491.44  4858.6  489.19
  4872.7  489.55  4876.8  488.78  4877.3  487.98  4882.3  487.98  4882.8  488.78
  4894.0  489.67  4922.3  490.34  4982.3  490.93  4986.3  490.93  4994.0  489.65
  5004.2  489.20  5014.5  490.43  5019.6  489.79  5024.8  491.08  5041.0  491.44
  5096.6  494.04  5152.6  497.68  5209.6  502.09  5260.9  503.44  5317.8  503.11
#Mann=3,-1,0
  4550.8    0.05       0  4876.8    0.03       0  4882.8    0.05       0
Bank Sta=4779.6,5041
Exp/Cntr=0.3,0.1

Type RM Length L Ch R = 1,890,274,274,274
BEGIN DESCRIPTION:
Mapping XS 9d51b746
END DESCRIPTION:
XS GIS Cut Line= 4
      2828818.29      7075874.17      2828568.29      7075967.92
      2828404.22      7076171.05      2828372.97      7076658.03
#Sta/Elev= 30
  4641.9  507.55  4720.5  506.71  4730.9  508.33  4740.1  506.06  4745.4  506.20
  4762.9  503.23  4784.3  502.48  4794.9  496.75  4800.6  496.11  4830.9  495.68
  4891.4  492.93  4901.7  493.18  4908.0  495.99  4971.1  490.19  4995.1  488.69
  4998.6  487.73  4999.1  486.93  5004.1  486.93  5004.6  487.73  5008.0  488.62
  5030.4  489.34  5036.8  488.80  5094.4  489.73  5129.5  489.22  5304.2  490.60
  5358.1  490.19  5434.5  493.67  5544.0  500.41  5549.0  499.50  5658.0  503.25
#Mann=3,-1,0
  4641.9    0.05       0  4998.6    0.03       0  5004.6    0.05       0
Bank Sta=4971.1,5358.1
Exp/Cntr=0.3,0.1

Type RM Length L Ch R = 1,616,0,0,0
BEGIN DESCRIPTION:
UNT 095 in LFCCL Watershed 1.0
END DESCRIPTION:
XS GIS Cut Line= 3
      2828652.45      7075774.10      2828314.83      7075880.20
      2828353.07      7076687.19
#Sta/Elev= 30
  4646.1  500.98  4694.9  500.29  4700.1  502.21  4706.3  502.93  4716.8  502.05
  4727.3  496.76  4737.8  494.14  4758.7  493.96  4764.9  495.05  4770.1  494.05
  4779.7  495.44  4842.6  490.05  4889.6  487.78  4932.2  486.40  4989.3  487.04
  4996.7  486.13  4997.2  485.33  5002.2  485.33  5002.7  486.13  5014.8  487.14
  5044.9  486.57  5242.4  487.78  5275.1  487.89  5325.3  489.51  5445.3  488.96
  5465.3  489.44  5655.5  497.31  5735.6  499.88  5765.7  502.05  5807.9  503.84
#Mann=3,-1,0
  4646.1    0.05       0  4996.7    0.03       0  5002.7    0.05       0
Bank Sta=4889.6,5242.4
Exp/Cntr=0.3,0.1

Chan Stop Cuts=-1