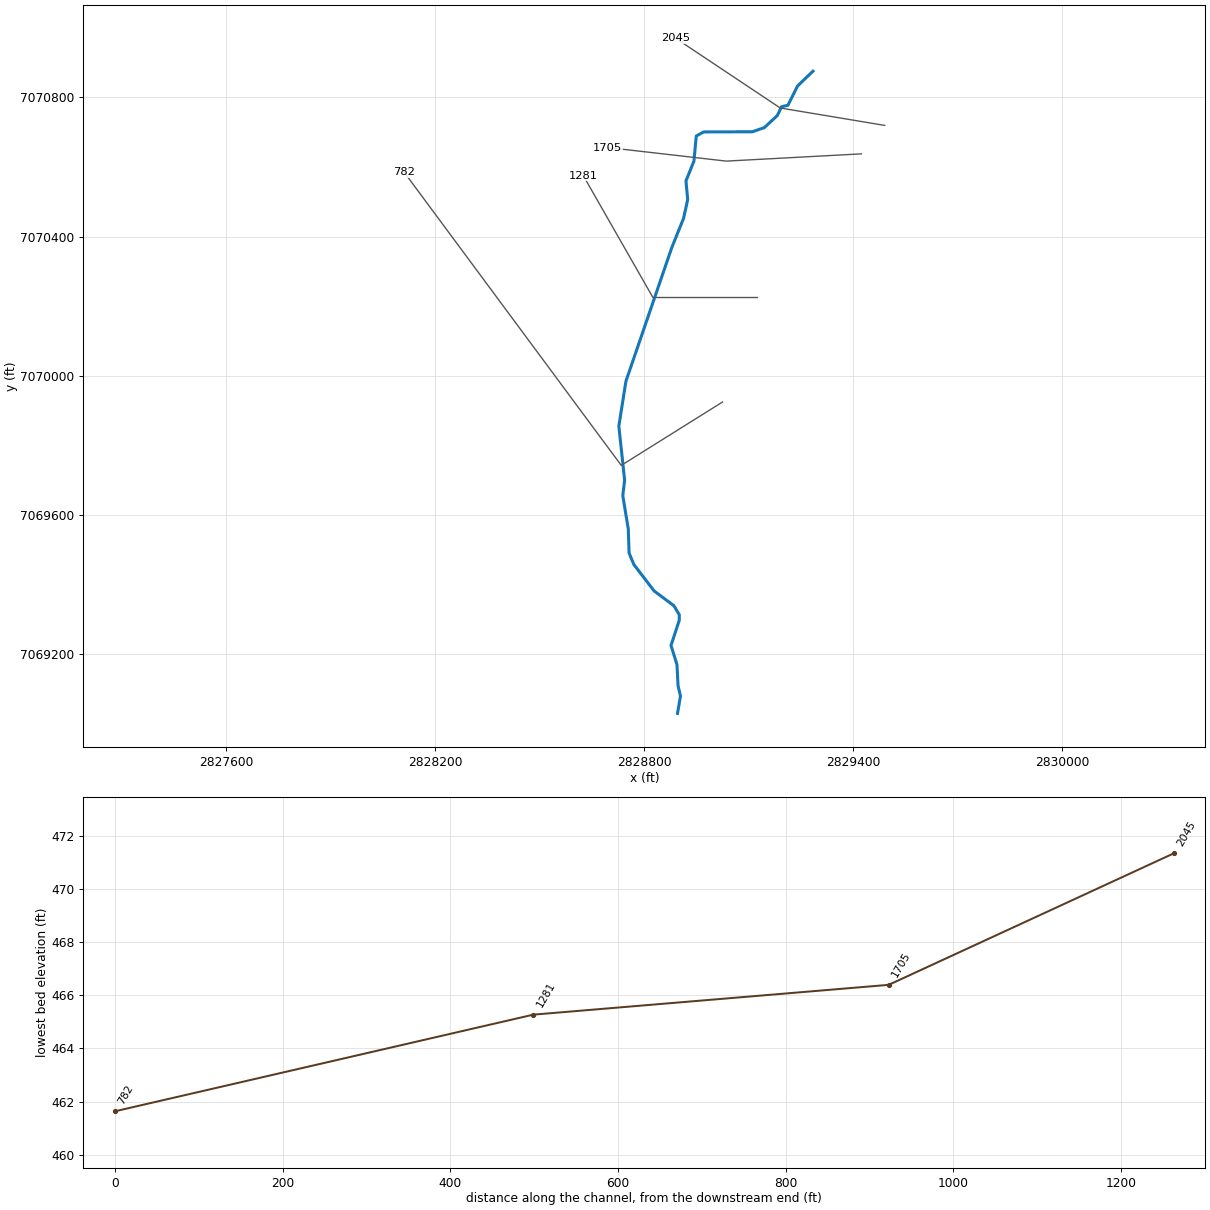
--- UNT 096 in LFCCL Watershed.prj (project) ---

Proj Title=UNT 096 in LFCCL Watershed Base Level Engineering
Current Plan=p01
Default Exp/Contr=0.3,0.1
English Units
Geom File=g01
Flow File=f01
Plan File=p01
BEGIN DESCRIPTION:
UNT 096 in LFCCL Watershed
END DESCRIPTION:

--- UNT 096 in LFCCL Watershed.p01 (plan) ---

Plan Title=Multiple Run
Short Identifier=Multiple
Geom File=g01
Flow File=f01
Subcritical Flow
K Sum by GR= 0
Std Step Tol= 0.01
Critical Tol= 0.01
Num of Std Step Trials= 20
Max Error Tol= 0.3
Flow Tol Ratio= 0.001
Split Flow NTrial= 30
Split Flow Tol= 0.02
Split Flow Ratio= 0.02
Log Output Level= 0
Friction Slope Method= 1
Unsteady Friction Slope Method= 2
Unsteady Bridges Friction Slope Method= 1
Parabolic Critical Depth
Global Vel Dist=  1 , 1 , 1
Global Log Level= 0
CheckData=True
Encroach Param= -1, 0, 0, 0
BEGIN DESCRIPTION:
Multiple Run
END DESCRIPTION:

--- UNT 096 in LFCCL Watershed.f01 (steady flow) ---

Flow Title=Multiple
Number of Profiles=7
Profile Names=10-year,25-year,50-year,1pct_min,100-year,1pct_plu,500-year
River Rch & RM= UNT 096 in LFCCL,Reach-1,2045
     830    1124    1365     822    1639    3271    2359
Boundary for River Rch & Prof#=UNT 096 in LFCCL,Reach-1,1
Up Type=0
Dn Type=3
Dn Slope=0.005
Boundary for River Rch & Prof#=UNT 096 in LFCCL,Reach-1,2
Up Type=0
Dn Type=3
Dn Slope=0.005
Boundary for River Rch & Prof#=UNT 096 in LFCCL,Reach-1,3
Up Type=0
Dn Type=3
Dn Slope=0.005
Boundary for River Rch & Prof#=UNT 096 in LFCCL,Reach-1,4
Up Type=0
Dn Type=3
Dn Slope=0.005
Boundary for River Rch & Prof#=UNT 096 in LFCCL,Reach-1,5
Up Type=0
Dn Type=3
Dn Slope=0.005
Boundary for River Rch & Prof#=UNT 096 in LFCCL,Reach-1,6
Up Type=0
Dn Type=3
Dn Slope=0.005
Boundary for River Rch & Prof#=UNT 096 in LFCCL,Reach-1,7
Up Type=0
Dn Type=3
Dn Slope=0.005

--- UNT 096 in LFCCL Watershed.g01 (geometry) ---

Geom Title=Existing Conditions

River Reach=UNT 096 in LFCCL,Reach-1
Reach XY= 30
      2829284.59      7070875.04      2829240.52      7070832.61
      2829212.77      7070777.12      2829194.45      7070772.93
      2829181.99      7070747.24      2829144.86      7070712.85
      2829110.50      7070700.99      2828970.37      7070700.48
      2828949.45      7070688.71      2828942.85      7070616.88
      2828919.89      7070560.02      2828924.83      7070506.06
      2828912.83      7070451.89      2828879.44      7070369.11
      2828747.53      7069984.90      2828727.09      7069855.74
      2828743.70      7069700.29      2828738.48      7069656.24
      2828754.19      7069560.14      2828756.54      7069491.10
      2828770.38      7069457.96      2828828.35      7069382.37
      2828885.26      7069339.83      2828900.65      7069314.02
      2828900.59      7069297.87      2828876.92      7069225.79
      2828894.05      7069170.74      2828897.09      7069110.65
      2828904.08      7069080.29      2828895.59      7069030.71

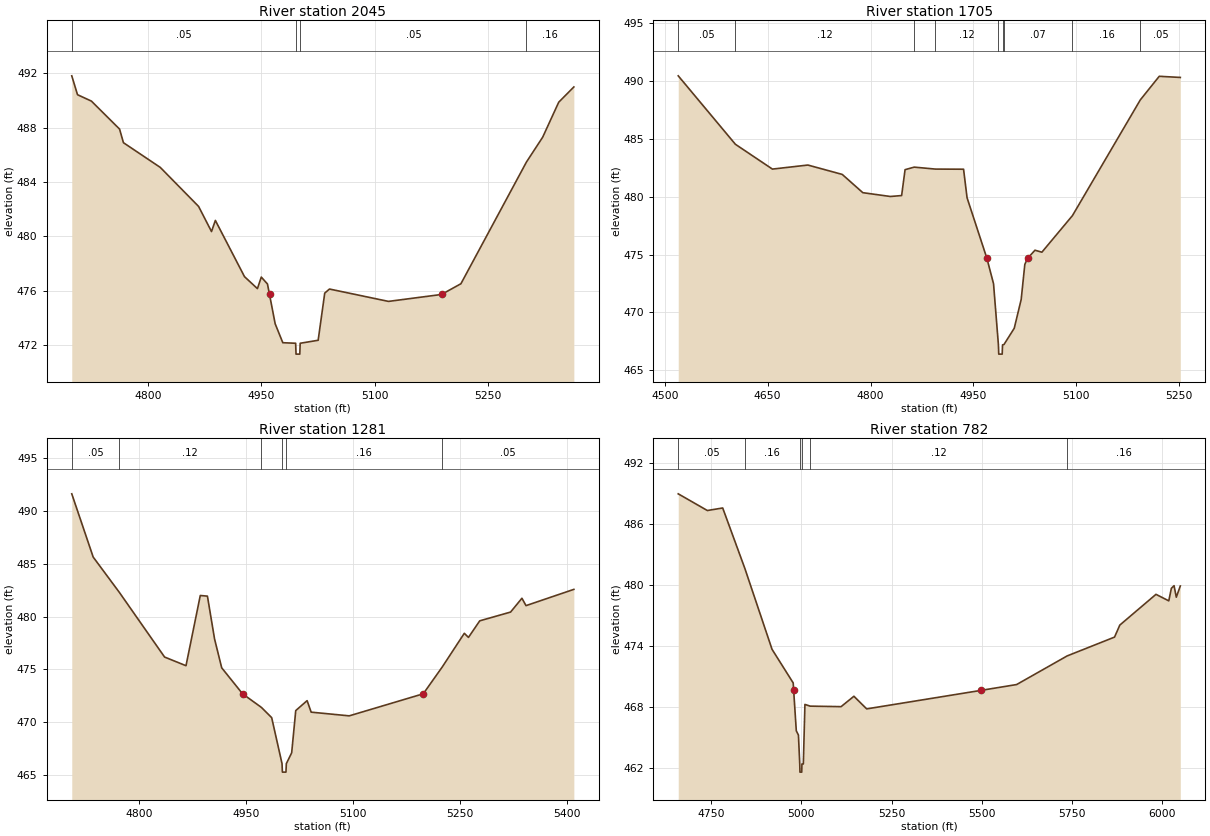
Type RM Length L Ch R = 1,2045,340,340,340
BEGIN DESCRIPTION:
UNT 096 in LFCCL Watershed 4.0
END DESCRIPTION:
XS GIS Cut Line= 3
      2829490.60      7070719.27      2829190.63      7070769.27
      2828890.60      7070969.29
#Sta/Elev= 30
  4698.9  491.81  4706.5  490.42  4724.9  489.95  4762.2  487.89  4767.3  486.89
  4816.1  485.07  4866.8  482.20  4883.9  480.35  4889.0  481.17  4927.6  477.03
  4944.7  476.15  4949.8  477.00  4958.0  476.49  4960.7  475.72  4968.2  473.56
  4978.3  472.17  4995.3  472.13  4995.8  471.33  5000.8  471.33  5001.3  472.13
  5025.1  472.35  5033.8  475.82  5040.1  476.12  5118.2  475.21  5188.4  475.72
  5214.1  476.51  5300.9  485.47  5322.3  487.29  5343.6  489.87  5363.6  490.99
#Mann=4,-1,0
  4698.9    0.05       0  4995.3    0.04       0  5001.3    0.05       0
  5300.9    0.16       0
Bank Sta=4960.7,5188.4
Exp/Cntr=0.3,0.1

Type RM Length L Ch R = 1,1705,424,424,424
BEGIN DESCRIPTION:
XS3688A
END DESCRIPTION:
XS GIS Cut Line= 3
      2829423.73      7070637.54      2829035.67      7070616.70
      2828694.51      7070655.77
#Sta/Elev= 30
  4519.6  490.47  4602.9  484.55  4656.9  482.40  4708.6  482.75  4758.7  481.94
  4788.7  480.36  4828.8  480.03  4845.3  480.11  4850.3  482.35  4863.6  482.57
  4894.6  482.40  4935.6  482.39  4940.7  479.92  4969.6  474.68  4979.3  472.48
  4986.4  467.19  4986.9  466.39  4991.9  466.39  4992.4  467.19  4994.5  467.22
  5009.5  468.63  5019.6  471.12  5024.9  474.15  5028.9  474.68  5039.7  475.38
  5049.8  475.21  5094.4  478.38  5193.3  488.39  5220.9  490.43  5251.6  490.33
#Mann=9,-1,0
  4519.6    0.05       0  4602.9    0.12       0  4863.6    0.16       0
  4894.6    0.12       0  4986.4    0.07       0  4992.4    0.12       0
  4994.5    0.07       0  5094.4    0.16       0  5193.3    0.05       0
Bank Sta=4969.6,5028.9
Exp/Cntr=0.3,0.1

Type RM Length L Ch R = 1,1281,499,499,499
BEGIN DESCRIPTION:
UNT 096 in LFCCL Watershed 2.0
END DESCRIPTION:
XS GIS Cut Line= 3
      2829125.05      7070225.00      2828825.00      7070225.00
      2828624.98      7070575.03
#Sta/Elev= 30
  4705.8  491.63  4735.8  485.64  4772.4  482.30  4835.8  476.17  4865.8  475.35
  4885.8  482.00  4895.8  481.94  4905.8  477.88  4915.8  475.15  4945.0  472.69
  4971.4  471.40  4985.8  470.43  5000.3  466.07  5000.8  465.27  5005.8  465.27
  5006.3  466.07  5013.8  467.10  5019.5  471.10  5035.4  472.04  5041.1  470.95
  5094.4  470.60  5198.1  472.69  5224.6  475.22  5255.6  478.42  5261.4  478.03
  5277.2  479.60  5320.4  480.43  5336.3  481.74  5342.0  481.04  5409.0  482.58
#Mann=6,-1,0
  4705.8    0.05       0  4772.4    0.12       0  4971.4    0.16       0
  5000.3    0.07       0  5006.3    0.16       0  5224.6    0.05       0
Bank Sta=4945,5198.1
Exp/Cntr=0.3,0.1

Type RM Length L Ch R = 1,782,0,0,0
BEGIN DESCRIPTION:
UNT 096 in LFCCL Watershed 1.0
END DESCRIPTION:
XS GIS Cut Line= 3
      2829024.97      7069924.98      2828734.02      7069742.90
      2828110.51      7070584.97
#Sta/Elev= 30
  4659.1  488.97  4739.8  487.33  4782.3  487.58  4843.9  481.62  4919.0  473.70
  4977.6  470.40  4978.9  469.66  4986.2  465.70  4992.1  465.28  4995.8  462.44
  4996.3  461.64  5001.3  461.64  5001.8  462.44  5005.7  462.44  5010.1  468.29
  5024.5  468.12  5110.3  468.07  5145.8  469.09  5181.2  467.85  5496.6  469.66
  5596.6  470.24  5736.5  473.05  5867.9  474.90  5882.5  476.08  5982.7  479.10
  6018.2  478.46  6025.3  479.69  6032.8  479.95  6039.0  478.82  6050.1  479.92
#Mann=6,-1,0
  4659.1    0.05       0  4843.9    0.16       0  4995.8    0.07       0
  5001.8    0.16       0  5024.5    0.12       0  5736.5    0.16       0
Bank Sta=4978.9,5496.6
Exp/Cntr=0.3,0.1

Chan Stop Cuts=-1