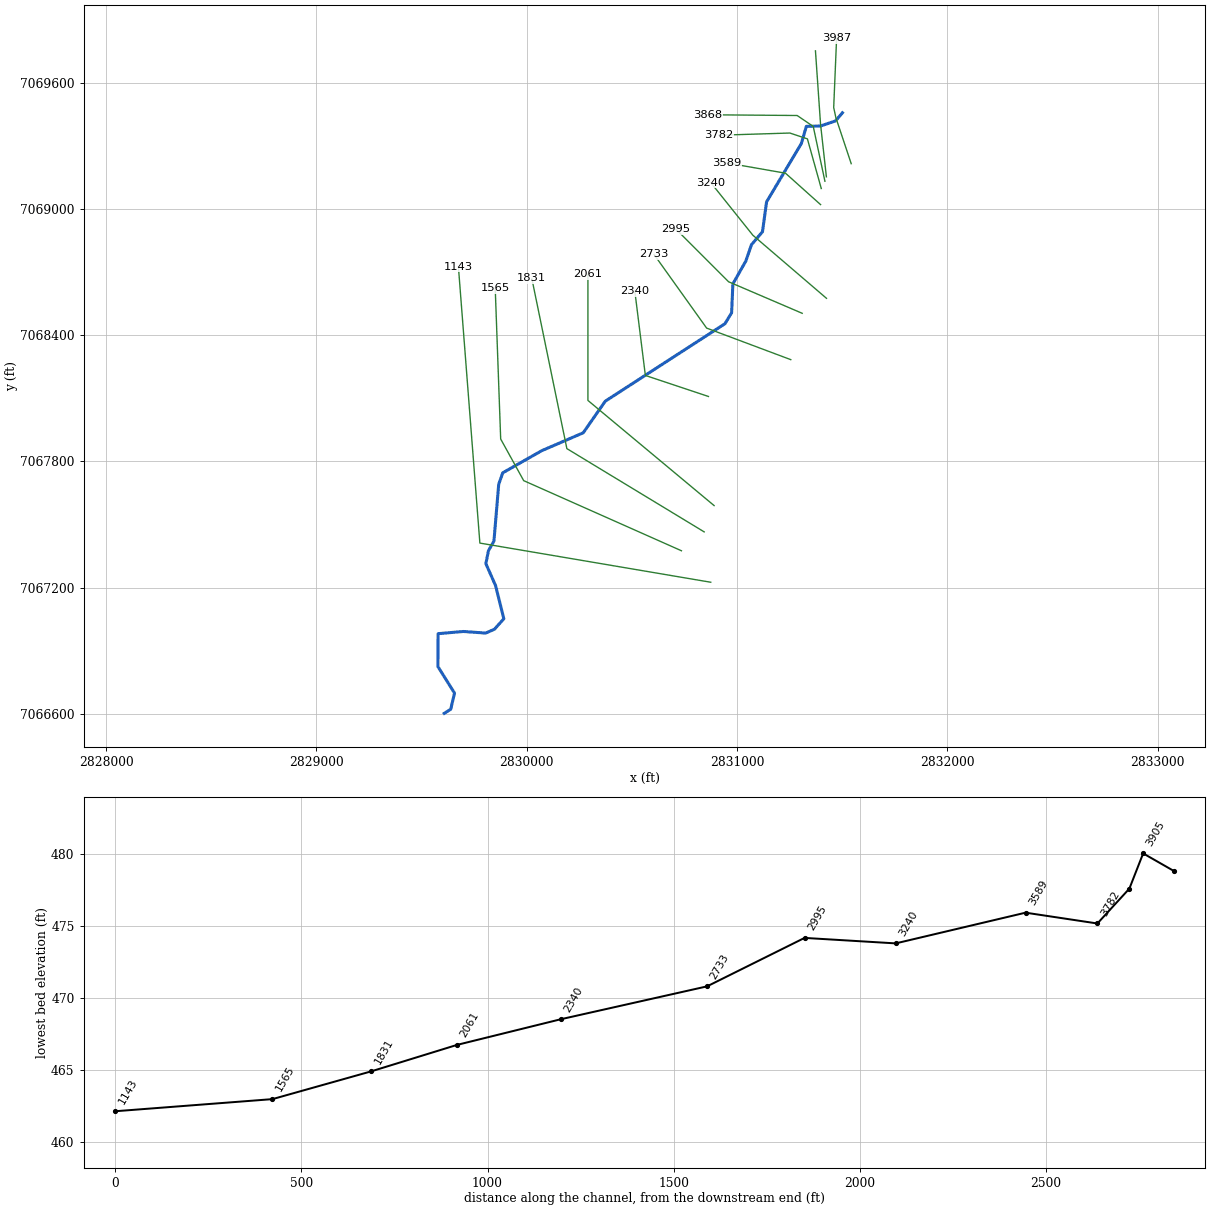
--- UNT 097 in LFCCL Watershed.prj (project) ---

Proj Title=UNT 097 in LFCCL Watershed Base Level Engineering
Current Plan=p01
Default Exp/Contr=0.3,0.1
English Units
Geom File=g01
Flow File=f01
Plan File=p01
BEGIN DESCRIPTION:
UNT 097 in LFCCL Watershed
END DESCRIPTION:

--- UNT 097 in LFCCL Watershed.p01 (plan) ---

Plan Title=Multiple Run
Short Identifier=Multiple
Geom File=g01
Flow File=f01
Subcritical Flow
K Sum by GR= 0
Std Step Tol= 0.01
Critical Tol= 0.01
Num of Std Step Trials= 20
Max Error Tol= 0.3
Flow Tol Ratio= 0.001
Split Flow NTrial= 30
Split Flow Tol= 0.02
Split Flow Ratio= 0.02
Log Output Level= 0
Friction Slope Method= 1
Unsteady Friction Slope Method= 2
Unsteady Bridges Friction Slope Method= 1
Parabolic Critical Depth
Global Vel Dist=  1 , 1 , 1
Global Log Level= 0
CheckData=True
Encroach Param= -1, 0, 0, 0
BEGIN DESCRIPTION:
Multiple Run
END DESCRIPTION:

--- UNT 097 in LFCCL Watershed.f01 (steady flow) ---

Flow Title=Multiple
Number of Profiles=7
Profile Names=10-year,25-year,50-year,1pct_min,100-year,1pct_plu,500-year
River Rch & RM= UNT 097 in LFCCL,Reach-1,3987
     563     743     887     525    1048    2091    1458
Boundary for River Rch & Prof#=UNT 097 in LFCCL,Reach-1,1
Up Type=0
Dn Type=3
Dn Slope=0.005
Boundary for River Rch & Prof#=UNT 097 in LFCCL,Reach-1,2
Up Type=0
Dn Type=3
Dn Slope=0.005
Boundary for River Rch & Prof#=UNT 097 in LFCCL,Reach-1,3
Up Type=0
Dn Type=3
Dn Slope=0.005
Boundary for River Rch & Prof#=UNT 097 in LFCCL,Reach-1,4
Up Type=0
Dn Type=3
Dn Slope=0.005
Boundary for River Rch & Prof#=UNT 097 in LFCCL,Reach-1,5
Up Type=0
Dn Type=3
Dn Slope=0.005
Boundary for River Rch & Prof#=UNT 097 in LFCCL,Reach-1,6
Up Type=0
Dn Type=3
Dn Slope=0.005
Boundary for River Rch & Prof#=UNT 097 in LFCCL,Reach-1,7
Up Type=0
Dn Type=3
Dn Slope=0.005

--- UNT 097 in LFCCL Watershed.g01 (geometry) ---

Geom Title=Existing Conditions

River Reach=UNT 097 in LFCCL,Reach-1
Reach XY= 30
      2831500.87      7069457.05      2831468.00      7069418.46
      2831396.55      7069394.17      2831329.38      7069392.74
      2831305.46      7069310.85      2831140.18      7069033.51
      2831120.76      7068891.62      2831068.21      7068829.66
      2831041.64      7068752.35      2830980.01      7068643.52
      2830974.00      7068506.37      2830942.37      7068454.21
      2830373.02      7068085.73      2830268.47      7067935.57
      2830070.75      7067850.31      2829885.85      7067745.31
      2829866.60      7067690.91      2829843.94      7067420.72
      2829817.80      7067374.72      2829805.52      7067313.47
      2829851.71      7067209.11      2829890.93      7067051.57
      2829846.33      7067001.59      2829804.59      7066983.33
      2829698.64      7066990.90      2829578.57      7066980.62
      2829577.30      7066824.42      2829656.46      7066698.01
      2829638.59      7066621.40      2829607.65      7066601.56

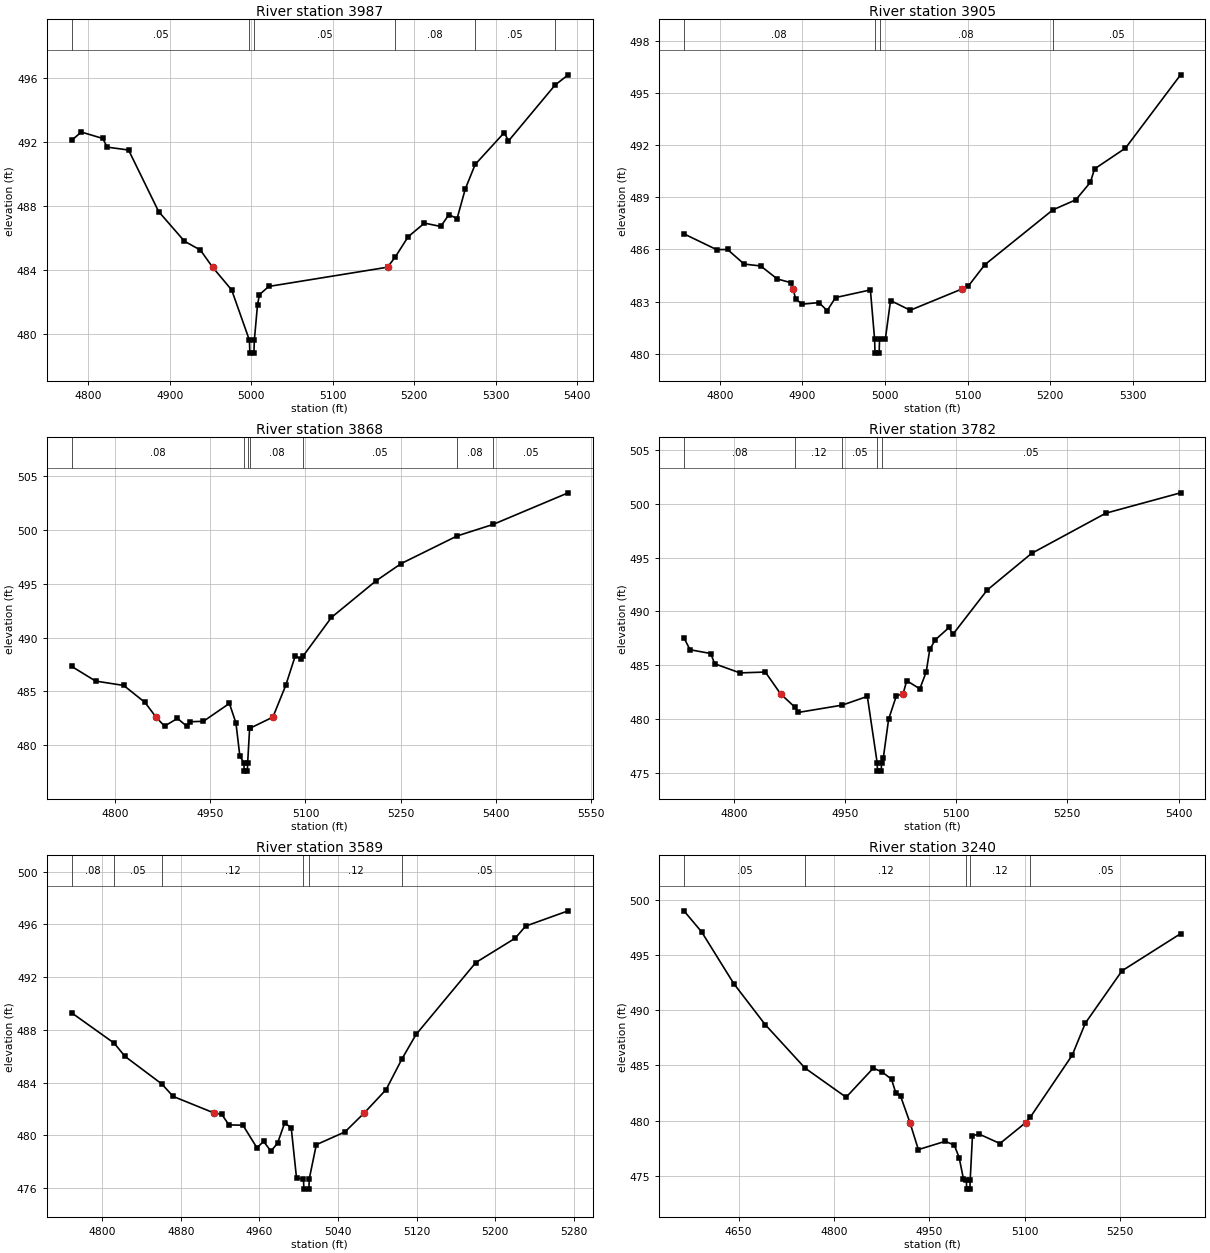
Type RM Length L Ch R = 1,3987,82,82,82
BEGIN DESCRIPTION:
UNT 097 in LFCCL Watershed 8.0
END DESCRIPTION:
XS GIS Cut Line= 4
      2831542.66      7069215.06      2831469.74      7069433.79
      2831459.33      7069482.41      2831473.17      7069811.13
#Sta/Elev= 30
  4779.5  492.09  4791.6  492.61  4817.9  492.21  4823.2  491.67  4849.5  491.49
  4886.4  487.65  4918.1  485.80  4937.6  485.25  4952.6  484.18  4976.0  482.76
  4997.8  479.62  4998.3  478.82  5003.3  478.82  5003.8  479.62  5007.7  481.84
  5010.1  482.47  5021.5  482.98  5167.2  484.18  5176.6  484.81  5192.5  486.08
  5212.5  486.93  5232.5  486.72  5242.5  487.46  5252.5  487.21  5262.6  489.06
  5274.7  490.59  5310.5  492.58  5315.5  492.05  5372.7  495.54  5388.8  496.18
#Mann=6,-1,0
  4779.5    0.05       0  4997.8    0.03       0  5003.8    0.05       0
  5176.6    0.08       0  5274.7    0.05       0  5372.7    0.16       0
Bank Sta=4952.6,5167.2
Exp/Cntr=0.3,0.1

Type RM Length L Ch R = 1,3905,37,37,37
BEGIN DESCRIPTION:
XS3690A
END DESCRIPTION:
XS GIS Cut Line= 3
      2831424.60      7069152.55      2831396.83      7069402.54
      2831372.64      7069751.58
#Sta/Elev= 30
  4756.5  486.90  4796.2  485.99  4809.3  486.00  4829.4  485.16  4849.5  485.05
  4869.6  484.30  4886.7  484.08  4888.7  483.72  4891.8  483.15  4899.8  482.85
  4919.9  482.94  4930.0  482.48  4940.1  483.23  4982.3  483.67  4987.4  480.83
  4987.9  480.03  4992.9  480.03  4993.4  480.83  5000.4  480.84  5006.7  483.06
  5030.5  482.50  5092.9  483.72  5100.7  483.88  5120.8  485.12  5203.2  488.28
  5231.0  488.86  5248.7  489.87  5253.7  490.64  5291.2  491.84  5357.9  496.06
#Mann=4,-1,0
  4756.5    0.08       0  4987.4    0.07       0  4993.4    0.08       0
  5203.2    0.05       0
Bank Sta=4888.7,5092.9
Exp/Cntr=0.3,0.1

Type RM Length L Ch R = 1,3868,86,86,86
BEGIN DESCRIPTION:
XS3691A
END DESCRIPTION:
XS GIS Cut Line= 4
      2831417.65      7069131.74      2831362.10      7069392.13
      2831285.72      7069444.21      2830862.13      7069447.68
#Sta/Elev= 30
  4731.5  487.33  4769.4  485.96  4813.8  485.55  4847.3  483.97  4864.6  482.61
  4878.0  481.77  4898.4  482.49  4912.9  481.77  4918.9  482.18  4939.3  482.22
  4980.2  483.88  4990.5  482.07  4996.7  478.97  5003.0  478.39  5003.5  477.59
  5008.5  477.59  5009.0  478.39  5012.1  481.60  5013.2  481.59  5048.7  482.61
  5068.9  485.55  5083.9  488.29  5093.1  488.01  5096.9  488.33  5140.9  491.87
  5210.9  495.26  5250.9  496.88  5338.8  499.44  5395.4  500.51  5513.8  503.45
#Mann=7,-1,0
  4731.5    0.08       0  5003.0    0.07       0  5009.0    0.08       0
  5013.2    0.08       0  5096.9    0.05       0  5338.8    0.08       0
  5395.4    0.05       0
Bank Sta=4864.6,5048.7
Exp/Cntr=0.3,0.1

Type RM Length L Ch R = 1,3782,193,193,193
BEGIN DESCRIPTION:
XS3692A
END DESCRIPTION:
XS GIS Cut Line= 4
      2831400.29      7069097.00      2831334.33      7069333.10
      2831250.99      7069360.88      2830914.23      7069350.46
#Sta/Elev= 30
  4732.8  487.55  4741.1  486.44  4769.1  486.09  4774.2  485.14  4808.4  484.29
  4842.6  484.37  4863.2  482.34  4882.6  481.10  4887.1  480.62  4946.5  481.30
  4980.2  482.11  4993.4  475.97  4993.9  475.17  4998.9  475.17  4999.4  475.97
  5001.7  476.38  5008.9  479.99  5019.4  482.17  5028.4  482.34  5033.3  483.57
  5051.0  482.81  5059.6  484.38  5064.4  486.47  5071.8  487.36  5090.5  488.51
  5095.5  487.86  5141.8  491.98  5201.8  495.39  5301.9  499.12  5402.7  501.01
#Mann=5,-1,0
  4732.8    0.08       0  4882.6    0.12       0  4946.5    0.05       0
  4993.4    0.04       0  4999.4    0.05       0
Bank Sta=4863.2,5028.4
Exp/Cntr=0.3,0.1

Type RM Length L Ch R = 1,3589,349,349,349
BEGIN DESCRIPTION:
XS3693A
END DESCRIPTION:
XS GIS Cut Line= 3
      2831396.85      7069020.58      2831230.16      7069169.91
      2830952.38      7069218.52
#Sta/Elev= 30
  4768.6  489.30  4812.1  486.99  4822.9  486.00  4860.5  483.90  4872.2  482.95
  4913.3  481.71  4921.5  481.60  4929.0  480.79  4943.2  480.77  4957.5  479.05
  4964.2  479.54  4971.7  478.80  4978.4  479.40  4985.8  480.96  4992.4  480.55
  4997.8  476.73  5004.8  476.72  5005.3  475.92  5010.3  475.92  5010.8  476.72
  5017.9  479.29  5047.1  480.26  5066.9  481.71  5089.0  483.47  5105.3  485.82
  5119.5  487.65  5180.4  493.11  5220.4  494.95  5231.1  495.87  5274.4  497.03
#Mann=6,-1,0
  4768.6    0.08       0  4812.1    0.05       0  4860.5    0.12       0
  5004.8    0.07       0  5010.8    0.12       0  5105.3    0.05       0
Bank Sta=4913.3,5066.9
Exp/Cntr=0.3,0.1

Type RM Length L Ch R = 1,3240,245,245,245
BEGIN DESCRIPTION:
UNT 097 in LFCCL Watershed 6.0
END DESCRIPTION:
XS GIS Cut Line= 3
      2831424.97      7068575.03      2831075.00      7068875.00
      2830875.00      7069125.01
#Sta/Elev= 30
  4563.9  498.99  4591.8  497.08  4642.3  492.40  4691.7  488.69  4754.4  484.75
  4819.0  482.11  4861.8  484.75  4876.1  484.38  4890.4  483.74  4897.0  482.52
  4904.7  482.20  4919.4  479.81  4932.6  477.37  4974.9  478.12  4989.2  477.77
  4996.8  476.63  5003.4  474.75  5008.1  474.59  5008.6  473.79  5013.6  473.79
  5014.1  474.59  5017.7  478.62  5028.0  478.78  5060.9  477.92  5101.4  479.81
  5108.4  480.28  5174.5  485.91  5195.3  488.83  5252.9  493.56  5345.0  496.92
#Mann=5,-1,0
  4563.9    0.05       0  4754.4    0.12       0  5008.1    0.07       0
  5014.1    0.12       0  5108.4    0.05       0
Bank Sta=4919.4,5101.4
Exp/Cntr=0.3,0.1

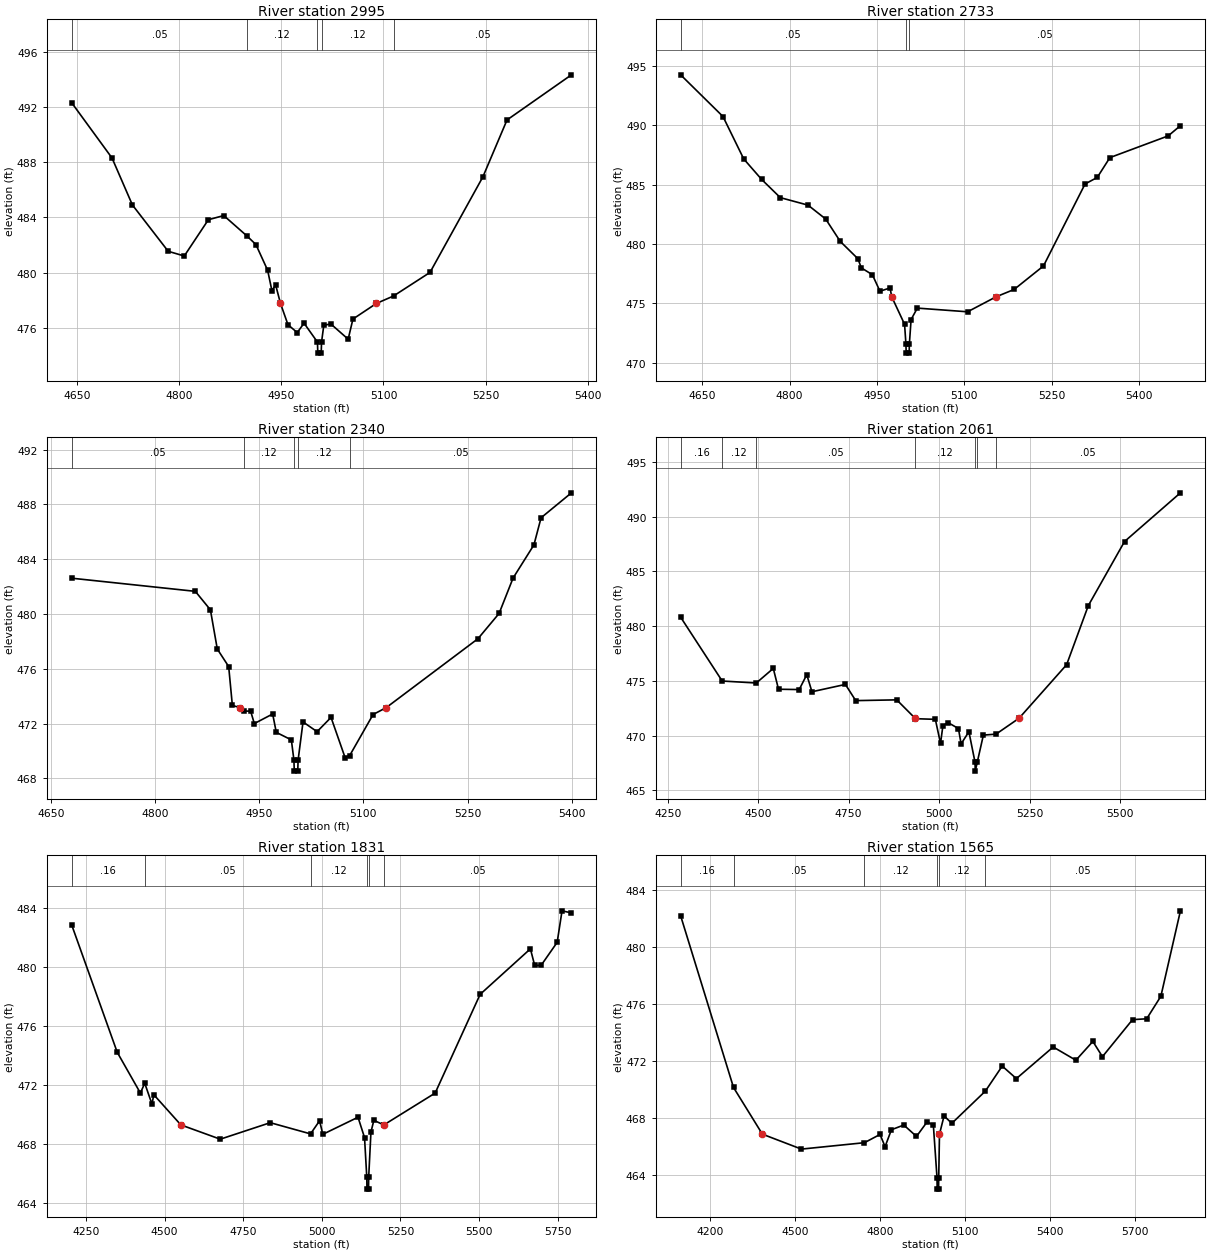
Type RM Length L Ch R = 1,2995,262,262,262
BEGIN DESCRIPTION:
UNT 097 in LFCCL Watershed 5.0
END DESCRIPTION:
XS GIS Cut Line= 3
      2831309.52      7068503.79      2830959.54      7068653.78
      2830709.77      7068903.55
#Sta/Elev= 30
  4642.1  492.32  4701.4  488.31  4731.3  484.91  4783.9  481.55  4807.5  481.21
  4842.9  483.84  4865.5  484.14  4899.8  482.65  4912.7  482.04  4929.9  480.18
  4936.2  478.70  4941.7  479.11  4948.8  477.77  4959.8  476.23  4973.4  475.66
  4983.4  476.34  5003.1  474.97  5003.6  474.17  5008.6  474.17  5009.1  474.97
  5012.4  476.18  5022.6  476.29  5048.2  475.18  5055.2  476.64  5089.6  477.77
  5114.8  478.31  5168.4  480.02  5246.1  486.95  5281.5  491.07  5376.1  494.34
#Mann=5,-1,0
  4642.1    0.05       0  4899.8    0.12       0  5003.1    0.07       0
  5009.1    0.12       0  5114.8    0.05       0
Bank Sta=4948.8,5089.6
Exp/Cntr=0.3,0.1

Type RM Length L Ch R = 1,2733,393,393,393
BEGIN DESCRIPTION:
UNT 097 in LFCCL Watershed 4.0
END DESCRIPTION:
XS GIS Cut Line= 3
      2831255.12      7068283.45      2830855.14      7068433.44
      2830605.14      7068783.44
#Sta/Elev= 30
  4613.2  494.24  4685.8  490.73  4721.4  487.16  4752.2  485.43  4784.2  483.90
  4831.7  483.27  4862.0  482.10  4886.9  480.22  4917.2  478.76  4923.1  477.99
  4942.1  477.41  4955.1  476.02  4972.4  476.30  4975.3  475.55  4997.3  473.24
  4999.6  471.61  5000.1  470.81  5005.1  470.81  5005.6  471.61  5008.5  473.64
  5019.2  474.60  5105.4  474.29  5154.2  475.55  5185.2  476.17  5235.6  478.15
  5306.9  485.05  5327.8  485.60  5349.5  487.27  5449.5  489.10  5470.5  489.96
#Mann=3,-1,0
  4613.2    0.05       0  4999.6    0.03       0  5005.6    0.05       0
Bank Sta=4975.3,5154.2
Exp/Cntr=0.3,0.1

Type RM Length L Ch R = 1,2340,279,279,279
BEGIN DESCRIPTION:
UNT 097 in LFCCL Watershed 3.0
END DESCRIPTION:
XS GIS Cut Line= 3
      2830863.87      7068108.34      2830563.89      7068208.33
      2830513.89      7068608.32
#Sta/Elev= 30
  4680.1  482.61  4858.1  481.65  4879.8  480.30  4889.7  477.44  4906.1  476.16
  4911.4  473.32  4922.5  473.17  4927.5  472.91  4937.7  472.91  4943.0  472.00
  4969.4  472.70  4974.6  471.36  4996.3  470.81  5000.0  469.33  5000.5  468.53
  5005.5  468.53  5006.0  469.33  5013.1  472.12  5033.3  471.41  5053.4  472.45
  5073.6  469.52  5080.3  469.67  5113.9  472.66  5133.0  473.17  5264.8  478.19
  5295.3  480.04  5315.4  482.62  5345.4  485.04  5355.7  487.02  5399.4  488.84
#Mann=5,-1,0
  4680.1    0.05       0  4927.5    0.12       0  5000.0    0.07       0
  5006.0    0.12       0  5080.3    0.05       0
Bank Sta=4922.5,5133
Exp/Cntr=0.3,0.1

Type RM Length L Ch R = 1,2061,230,230,230
BEGIN DESCRIPTION:
UNT 097 in LFCCL Watershed 2.0
END DESCRIPTION:
XS GIS Cut Line= 3
      2830890.79      7067589.50      2830290.80      7068089.49
      2830290.80      7068689.48
#Sta/Elev= 30
  4285.9  480.81  4400.7  474.98  4494.9  474.80  4541.9  476.13  4556.3  474.23
  4613.5  474.20  4634.4  475.56  4648.7  474.00  4741.1  474.67  4769.7  473.19
  4883.0  473.26  4933.7  471.58  4934.6  471.54  4989.7  471.48  5004.0  469.28
  5010.6  470.90  5024.9  471.18  5053.5  470.64  5060.9  469.24  5082.4  470.35
  5099.4  467.55  5099.9  466.75  5105.4  467.55  5122.4  470.04  5157.4  470.13
  5221.0  471.58  5352.4  476.47  5412.4  481.87  5512.4  487.72  5666.9  492.17
#Mann=7,-1,0
  4285.9    0.16       0  4400.7    0.12       0  4494.9    0.05       0
  4934.6    0.12       0  5099.4    0.07       0  5105.4    0.12       0
  5157.4    0.05       0
Bank Sta=4933.7,5221
Exp/Cntr=0.3,0.1

Type RM Length L Ch R = 1,1831,266,266,266
BEGIN DESCRIPTION:
Mapping XS ca89098d
END DESCRIPTION:
XS GIS Cut Line= 3
      2830843.43      7067464.59      2830190.69      7067860.40
      2830024.02      7068669.44
#Sta/Elev= 30
  4204.4  482.86  4349.3  474.21  4423.0  471.44  4436.8  472.11  4459.8  470.69
  4465.6  471.33  4551.7  469.28  4677.0  468.31  4836.0  469.43  4964.1  468.67
  4992.9  469.56  5003.1  468.64  5115.1  469.80  5135.8  468.42  5143.0  465.72
  5143.5  464.92  5148.5  464.92  5149.0  465.72  5156.2  468.79  5165.4  469.59
  5197.0  469.28  5197.4  469.28  5360.4  471.44  5503.4  478.14  5663.3  481.23
  5677.0  480.10  5697.4  480.11  5748.4  481.67  5763.9  483.81  5793.8  483.67
#Mann=6,-1,0
  4204.4    0.16       0  4436.8    0.05       0  4964.1    0.12       0
  5143.0    0.07       0  5149.0    0.12       0  5197.0    0.05       0
Bank Sta=4551.7,5197.4
Exp/Cntr=0.3,0.1

Type RM Length L Ch R = 1,1565,422,422,422
BEGIN DESCRIPTION:
XS3694A
END DESCRIPTION:
XS GIS Cut Line= 4
      2830735.37      7067374.77      2829985.37      7067708.10
      2829875.99      7067906.02      2829849.98      7068624.08
#Sta/Elev= 30
  4096.6  482.18  4283.3  470.13  4385.3  466.85  4523.2  465.80  4745.8  466.25
  4800.9  466.83  4818.7  465.97  4841.1  467.16  4884.9  467.49  4929.7  466.69
  4967.5  467.72  4989.3  467.47  5002.2  463.79  5002.7  462.99  5007.7  462.99
  5008.2  463.79  5010.9  466.85  5027.1  468.13  5054.5  467.61  5172.9  469.87
  5232.5  471.63  5282.5  470.75  5412.6  472.97  5492.7  472.04  5552.7  473.36
  5586.5  472.29  5692.8  474.89  5742.8  474.95  5792.9  476.53  5862.0  482.53
#Mann=6,-1,0
  4096.6    0.16       0  4283.3    0.05       0  4745.8    0.12       0
  5002.2    0.07       0  5008.2    0.12       0  5172.9    0.05       0
Bank Sta=4385.3,5010.9
Exp/Cntr=0.3,0.1

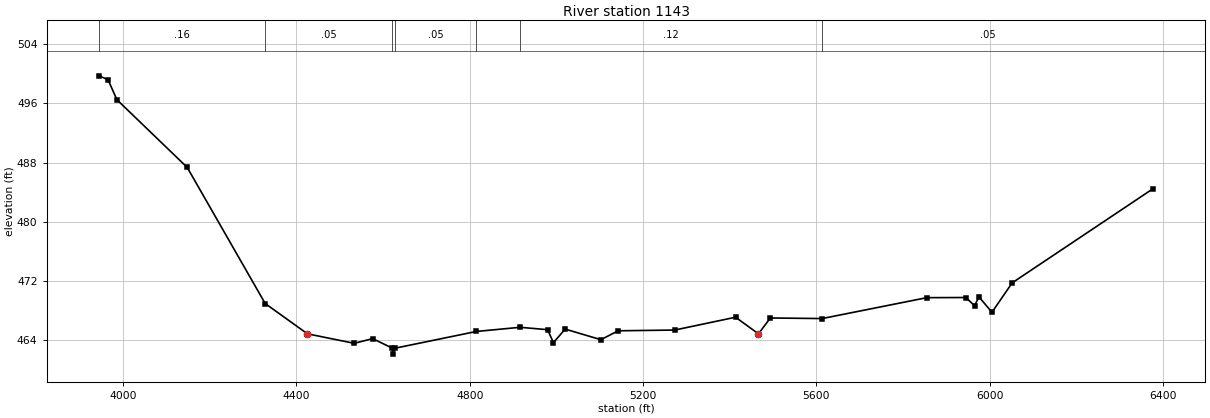
Type RM Length L Ch R = 1,1143,0,0,0
BEGIN DESCRIPTION:
UNT 097 in LFCCL Watershed 1.0
END DESCRIPTION:
XS GIS Cut Line= 3
      2830874.96      7067225.01      2829777.04      7067411.22
      2829675.00      7068724.96
#Sta/Elev= 30
  3945.2  499.71  3965.4  499.17  3985.7  496.49  4148.0  487.35  4328.0  468.98
  4425.5  464.89  4533.4  463.61  4576.1  464.24  4621.7  462.95  4622.2  462.15
  4627.7  462.95  4815.5  465.21  4916.3  465.77  4979.7  465.45  4993.3  463.70
  5020.3  465.53  5102.7  464.10  5142.8  465.30  5273.2  465.40  5413.6  467.13
  5466.5  464.89  5493.9  467.03  5613.4  466.95  5855.0  469.77  5945.2  469.79
  5965.3  468.68  5975.3  469.88  6005.4  467.80  6052.1  471.77  6376.5  484.45
#Mann=7,-1,0
  3945.2    0.16       0  4328.0    0.05       0  4621.7    0.07       0
  4627.7    0.05       0  4815.5    0.07       0  4916.3    0.12       0
  5613.4    0.05       0
Bank Sta=4425.5,5466.5
Exp/Cntr=0.3,0.1

Chan Stop Cuts=-1