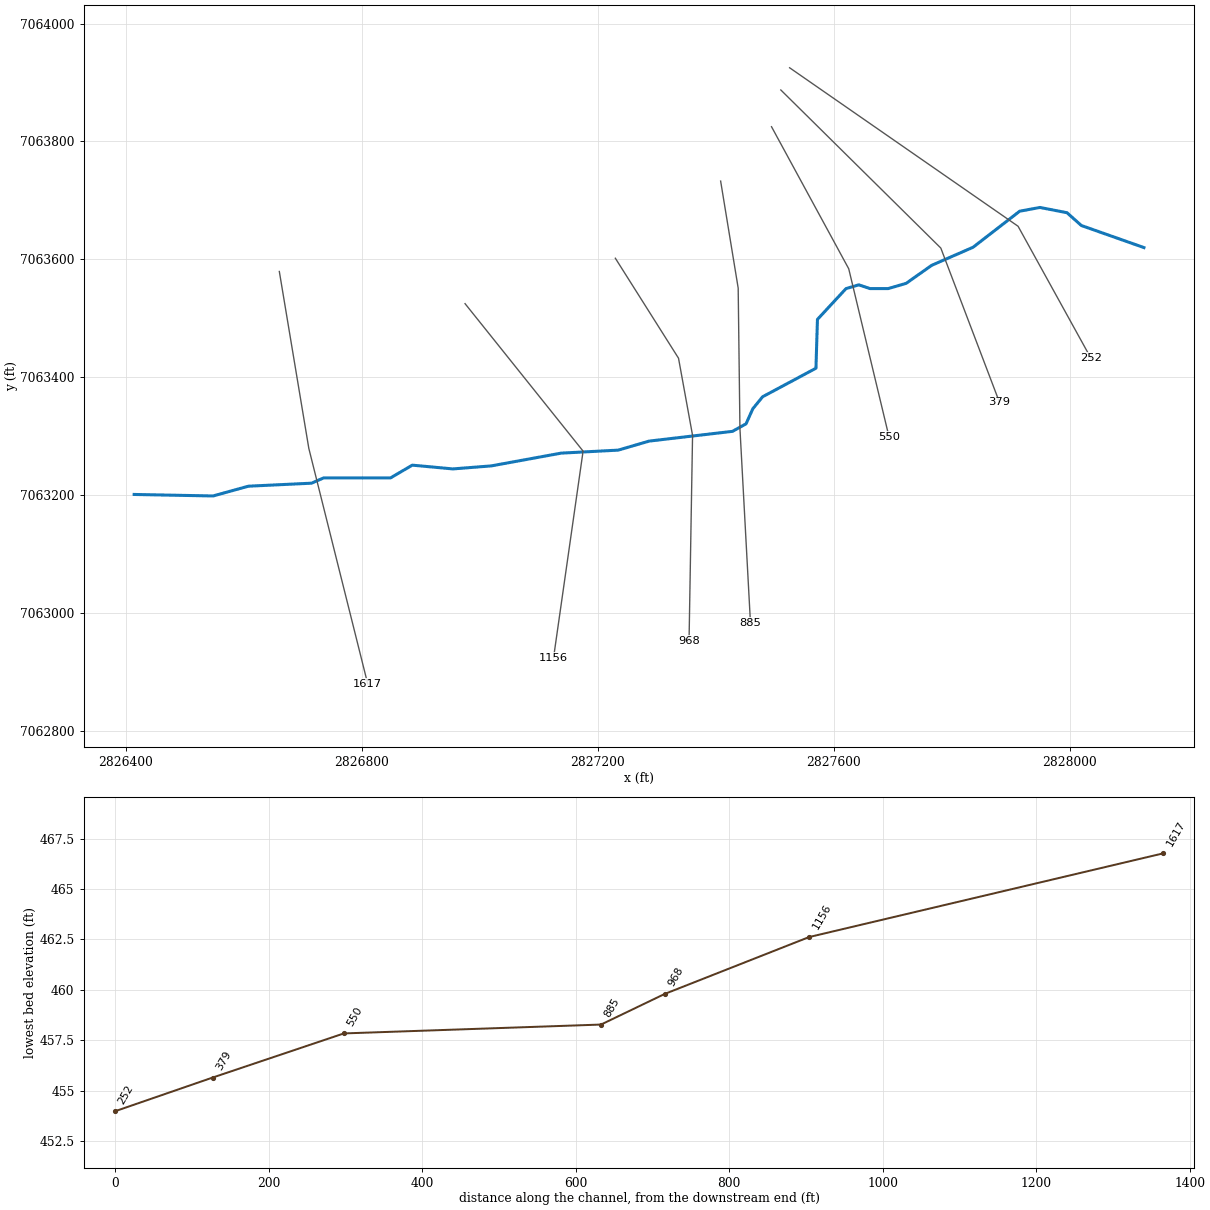
--- UNT 099 in LFCCL Watershed.prj (project) ---

Proj Title=UNT 099 in LFCCL Watershed Base Level Engineering
Current Plan=p01
Default Exp/Contr=0.3,0.1
English Units
Geom File=g01
Flow File=f01
Plan File=p01
BEGIN DESCRIPTION:
UNT 099 in LFCCL Watershed
END DESCRIPTION:

--- UNT 099 in LFCCL Watershed.p01 (plan) ---

Plan Title=Multiple Run
Short Identifier=Multiple
Geom File=g01
Flow File=f01
Subcritical Flow
K Sum by GR= 0
Std Step Tol= 0.01
Critical Tol= 0.01
Num of Std Step Trials= 20
Max Error Tol= 0.3
Flow Tol Ratio= 0.001
Split Flow NTrial= 30
Split Flow Tol= 0.02
Split Flow Ratio= 0.02
Log Output Level= 0
Friction Slope Method= 1
Unsteady Friction Slope Method= 2
Unsteady Bridges Friction Slope Method= 1
Parabolic Critical Depth
Global Vel Dist=  1 , 1 , 1
Global Log Level= 0
CheckData=True
Encroach Param= -1, 0, 0, 0
BEGIN DESCRIPTION:
Multiple Run
END DESCRIPTION:

--- UNT 099 in LFCCL Watershed.f01 (steady flow) ---

Flow Title=Multiple
Number of Profiles=7
Profile Names=10-year,25-year,50-year,1pct_min,100-year,1pct_plu,500-year
River Rch & RM= UNT 099 in LFCCL,Reach-1,1617
     371     479     562     329     656    1308     888
Boundary for River Rch & Prof#=UNT 099 in LFCCL,Reach-1,1
Up Type=0
Dn Type=3
Dn Slope=0.005
Boundary for River Rch & Prof#=UNT 099 in LFCCL,Reach-1,2
Up Type=0
Dn Type=3
Dn Slope=0.005
Boundary for River Rch & Prof#=UNT 099 in LFCCL,Reach-1,3
Up Type=0
Dn Type=3
Dn Slope=0.005
Boundary for River Rch & Prof#=UNT 099 in LFCCL,Reach-1,4
Up Type=0
Dn Type=3
Dn Slope=0.005
Boundary for River Rch & Prof#=UNT 099 in LFCCL,Reach-1,5
Up Type=0
Dn Type=3
Dn Slope=0.005
Boundary for River Rch & Prof#=UNT 099 in LFCCL,Reach-1,6
Up Type=0
Dn Type=3
Dn Slope=0.005
Boundary for River Rch & Prof#=UNT 099 in LFCCL,Reach-1,7
Up Type=0
Dn Type=3
Dn Slope=0.005

--- UNT 099 in LFCCL Watershed.g01 (geometry) ---

Geom Title=Existing Conditions

River Reach=UNT 099 in LFCCL,Reach-1
Reach XY= 30
      2826414.19      7063201.50      2826547.95      7063198.95
      2826607.82      7063215.51      2826714.83      7063220.61
      2826735.21      7063229.53      2826848.59      7063229.53
      2826885.54      7063251.18      2826954.33      7063244.81
      2827019.30      7063249.91      2827137.77      7063271.56
      2827234.59      7063276.66      2827286.82      7063291.95
      2827428.22      7063308.51      2827451.15      7063321.25
      2827462.62      7063346.73      2827479.18      7063367.11
      2827569.63      7063415.52      2827572.17      7063498.32
      2827620.58      7063550.55      2827642.24      7063556.92
      2827661.35      7063550.55      2827691.92      7063550.55
      2827722.50      7063559.47      2827765.81      7063590.04
      2827835.87      7063620.62      2827914.86      7063681.76
      2827949.25      7063688.13      2827995.11      7063679.22
      2828019.32      7063657.56      2828125.46      7063620.11

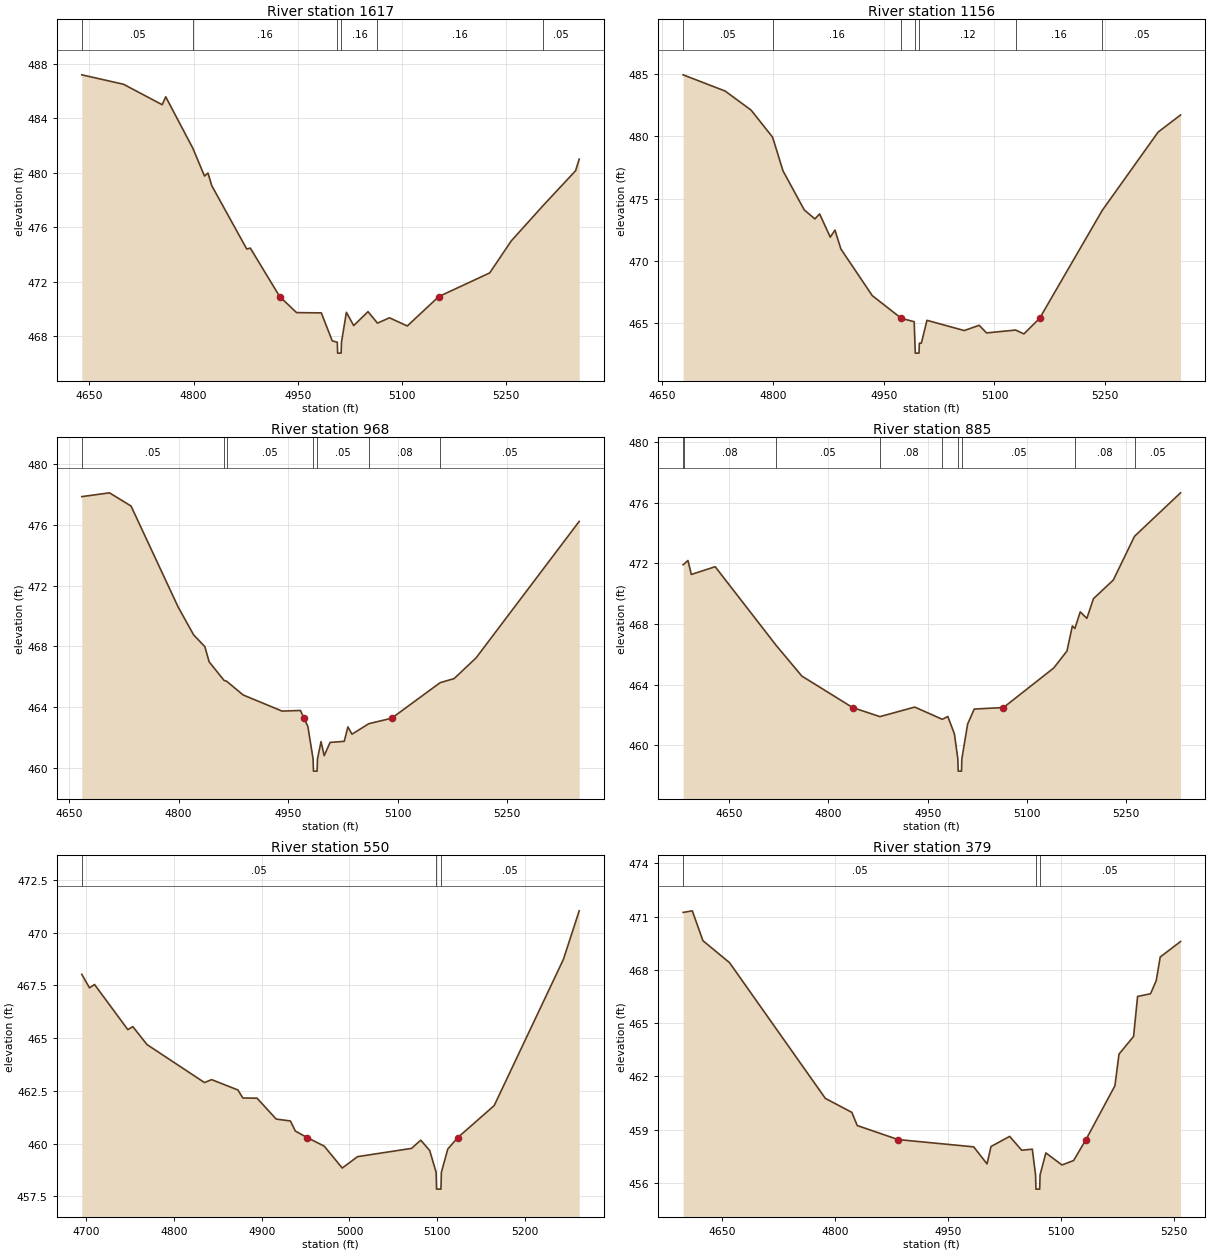
Type RM Length L Ch R = 1,1617,461,461,461
BEGIN DESCRIPTION:
UNT 099 in LFCCL Watershed 4.0
END DESCRIPTION:
XS GIS Cut Line= 3
      2826660.21      7063579.57      2826710.21      7063279.53
      2826810.05      7062880.20
#Sta/Elev= 30
  4639.2  487.17  4699.2  486.48  4754.9  484.98  4760.0  485.56  4799.1  481.78
  4815.8  479.75  4820.8  479.97  4826.3  479.04  4876.6  474.40  4881.7  474.47
  4924.1  470.91  4948.3  469.74  4983.9  469.72  4999.6  467.67  5006.9  467.57
  5007.4  466.77  5012.4  466.77  5012.9  467.57  5020.0  469.76  5030.5  468.79
  5051.1  469.81  5064.7  468.97  5082.0  469.36  5107.6  468.76  5152.8  470.91
  5226.2  472.65  5257.3  475.00  5303.3  477.60  5349.8  480.14  5355.0  480.99
#Mann=6,-1,0
  4639.2    0.05       0  4799.1    0.16       0  5006.9    0.07       0
  5012.9    0.16       0  5064.7    0.16       0  5303.3    0.05       0
Bank Sta=4924.1,5152.8
Exp/Cntr=0.3,0.1

Type RM Length L Ch R = 1,1156,188,188,188
BEGIN DESCRIPTION:
UNT 099 in LFCCL Watershed 3.0
END DESCRIPTION:
XS GIS Cut Line= 3
      2826974.97      7063525.03      2827175.00      7063275.00
      2827124.99      7062924.95
#Sta/Elev= 30
  4678.3  484.93  4735.2  483.63  4770.4  482.10  4799.5  479.93  4813.6  477.23
  4842.4  474.10  4856.8  473.38  4863.2  473.78  4877.6  471.92  4884.0  472.48
  4892.0  470.97  4934.5  467.23  4973.0  465.45  4973.9  465.41  4991.3  465.14
  4992.3  463.42  4992.8  462.62  4997.8  462.62  4998.3  463.42  5001.0  463.42
  5008.6  465.25  5059.1  464.43  5079.3  464.85  5089.4  464.24  5128.8  464.47
  5139.9  464.16  5161.2  465.41  5246.0  474.06  5321.7  480.34  5352.1  481.71
#Mann=7,-1,0
  4678.3    0.05       0  4799.5    0.16       0  4973.0    0.12       0
  4992.3    0.07       0  4998.3    0.12       0  5128.8    0.16       0
  5246.0    0.05       0
Bank Sta=4973.9,5161.2
Exp/Cntr=0.3,0.1

Type RM Length L Ch R = 1,968,83,83,83
BEGIN DESCRIPTION:
XS3695A
END DESCRIPTION:
XS GIS Cut Line= 4
      2827229.66      7063602.04      2827336.73      7063432.50
      2827360.52      7063301.65      2827354.58      7062953.71
#Sta/Elev= 30
  4667.3  477.86  4705.3  478.11  4734.8  477.24  4799.4  470.59  4820.6  468.76
  4835.9  467.99  4841.8  466.99  4862.4  465.76  4865.6  465.72  4888.4  464.81
  4941.7  463.75  4966.9  463.79  4971.8  463.28  4977.1  462.73  4984.2  460.60
  4984.7  459.80  4989.7  459.80  4990.2  460.60  4995.1  461.74  4999.4  460.82
  5007.5  461.69  5026.9  461.76  5031.9  462.71  5037.5  462.23  5060.5  462.92
  5091.8  463.28  5158.3  465.62  5177.5  465.89  5207.5  467.25  5348.8  476.23
#Mann=7,-1,0
  4667.3    0.05       0  4862.4    0.16       0  4865.6    0.05       0
  4984.2    0.04       0  4990.2    0.05       0  5060.5    0.08       0
  5158.3    0.05       0
Bank Sta=4971.8,5091.8
Exp/Cntr=0.3,0.1

Type RM Length L Ch R = 1,885,335,335,335
BEGIN DESCRIPTION:
XS3696A
END DESCRIPTION:
XS GIS Cut Line= 4
      2827408.10      7063732.85      2827437.84      7063551.45
      2827440.81      7063313.55      2827458.66      7062983.47
#Sta/Elev= 30
  4580.2  471.91  4580.8  471.93  4587.5  472.19  4592.6  471.27  4628.7  471.78
  4721.0  466.58  4759.7  464.56  4836.5  462.48  4877.8  461.88  4930.5  462.51
  4972.3  461.70  4980.5  461.89  4990.5  460.74  4995.7  459.08  4996.2  458.28
  5001.2  458.28  5001.7  459.08  5010.5  461.39  5020.5  462.38  5064.7  462.48
  5140.7  465.09  5160.7  466.21  5168.9  467.87  5172.7  467.70  5180.8  468.80
  5190.8  468.37  5200.8  469.67  5230.8  470.90  5262.9  473.79  5332.5  476.66
#Mann=9,-1,0
  4580.2    0.05       0  4580.8    0.08       0  4721.0    0.05       0
  4877.8    0.08       0  4972.3    0.05       0  4995.7    0.03       0
  5001.7    0.05       0  5172.7    0.08       0  5262.9    0.05       0
Bank Sta=4836.5,5064.7
Exp/Cntr=0.3,0.1

Type RM Length L Ch R = 1,550,171,171,171
BEGIN DESCRIPTION:
XS3697A
END DESCRIPTION:
XS GIS Cut Line= 3
      2827494.34      7063825.03      2827625.19      7063584.16
      2827693.43      7063299.34
#Sta/Elev= 30
  4694.9  468.02  4703.7  467.38  4709.4  467.54  4747.4  465.40  4753.1  465.54
  4769.3  464.69  4834.8  462.89  4842.9  463.03  4872.8  462.54  4878.5  462.16
  4894.7  462.15  4916.5  461.16  4932.7  461.07  4938.4  460.59  4952.0  460.28
  4971.2  459.88  4991.8  458.84  5009.3  459.38  5070.7  459.77  5081.3  460.16
  5091.5  459.67  5098.8  458.64  5099.3  457.84  5104.3  457.84  5104.8  458.64
  5112.1  459.74  5123.4  460.28  5165.0  461.80  5243.9  468.73  5261.9  471.03
#Mann=3,-1,0
  4694.9    0.05       0  5098.8    0.03       0  5104.8    0.05       0
Bank Sta=4952,5123.4
Exp/Cntr=0.3,0.1

Type RM Length L Ch R = 1,379,127,127,127
BEGIN DESCRIPTION:
Mapping XS 367be7dd
END DESCRIPTION:
XS GIS Cut Line= 3
      2827510.12      7063887.32      2827781.24      7063619.28
      2827880.68      7063357.69
#Sta/Elev= 30
  4598.1  471.23  4610.3  471.32  4624.4  469.64  4659.8  468.40  4787.1  460.76
  4822.4  459.97  4829.5  459.23  4883.9  458.44  4984.3  458.03  5002.0  457.07
  5007.3  458.05  5032.1  458.62  5048.1  457.84  5062.2  457.90  5066.5  456.45
  5067.0  455.65  5072.0  455.65  5072.5  456.45  5080.2  457.69  5101.6  457.01
  5117.1  457.26  5133.5  458.44  5172.0  461.47  5177.4  463.25  5196.8  464.25
  5202.1  466.50  5219.3  466.65  5226.9  467.39  5232.2  468.72  5259.2  469.59
#Mann=3,-1,0
  4598.1    0.05       0  5066.5    0.03       0  5072.5    0.05       0
Bank Sta=4883.9,5133.5
Exp/Cntr=0.3,0.1

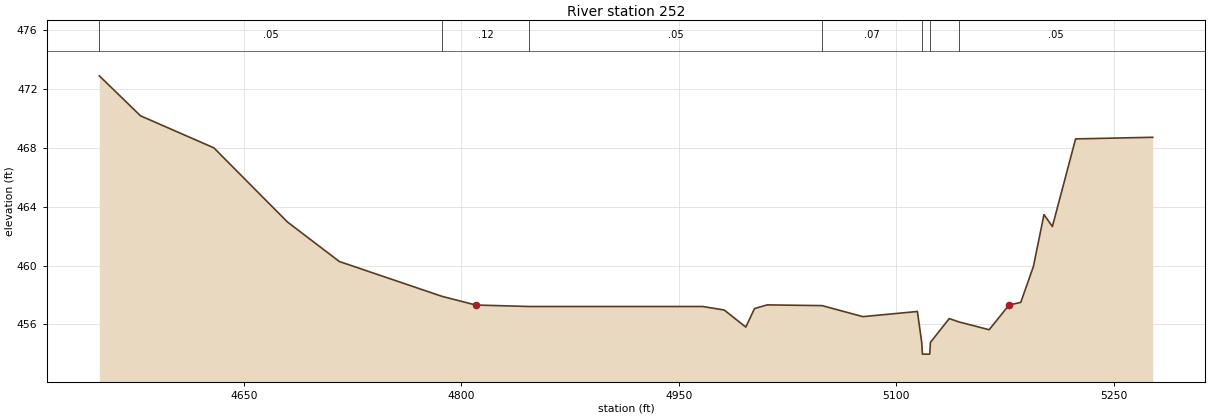
Type RM Length L Ch R = 1,252,0,0,0
BEGIN DESCRIPTION:
UNT 099 in LFCCL Watershed 1.0
END DESCRIPTION:
XS GIS Cut Line= 3
      2827525.00      7063925.00      2827912.18      7063656.25
      2828035.41      7063432.91
#Sta/Elev= 30
  4550.4  472.91  4578.8  470.19  4629.4  468.01  4680.1  462.97  4715.9  460.28
  4786.7  457.91  4810.0  457.32  4846.9  457.22  4966.5  457.22  4981.3  456.98
  4996.2  455.82  5002.2  457.08  5011.0  457.33  5048.8  457.28  5076.9  456.53
  5114.5  456.88  5117.5  454.78  5118.0  453.98  5123.0  453.98  5123.5  454.78
  5136.5  456.40  5143.2  456.17  5164.0  455.64  5177.7  457.32  5185.8  457.50
  5194.5  459.94  5201.8  463.47  5207.6  462.66  5223.6  468.62  5276.8  468.73
#Mann=7,-1,0
  4550.4    0.05       0  4786.7    0.12       0  4846.9    0.05       0
  5048.8    0.07       0  5117.5    0.03       0  5123.5    0.07       0
  5143.2    0.05       0
Bank Sta=4810,5177.7
Exp/Cntr=0.3,0.1

Chan Stop Cuts=-1