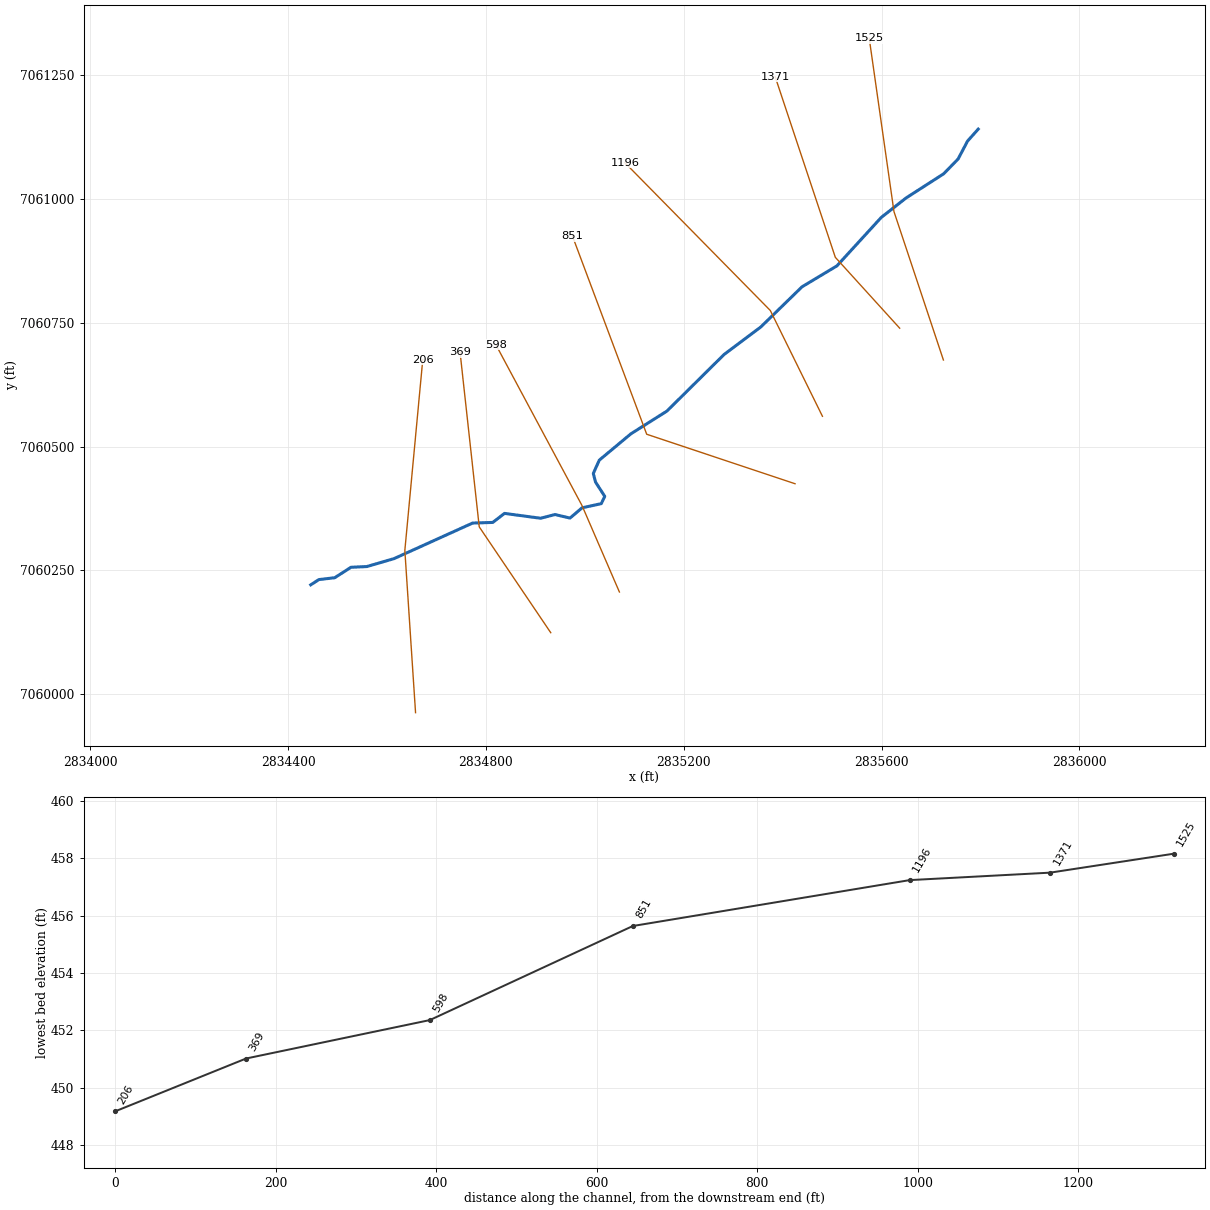
--- UNT 101 in LFCCL Watershed.prj (project) ---

Proj Title=UNT 101 in LFCCL Watershed Base Level Engineering
Current Plan=p01
Default Exp/Contr=0.3,0.1
English Units
Geom File=g01
Flow File=f01
Plan File=p01
BEGIN DESCRIPTION:
UNT 101 in LFCCL Watershed
END DESCRIPTION:

--- UNT 101 in LFCCL Watershed.p01 (plan) ---

Plan Title=Multiple Run
Short Identifier=Multiple
Geom File=g01
Flow File=f01
Subcritical Flow
K Sum by GR= 0
Std Step Tol= 0.01
Critical Tol= 0.01
Num of Std Step Trials= 20
Max Error Tol= 0.3
Flow Tol Ratio= 0.001
Split Flow NTrial= 30
Split Flow Tol= 0.02
Split Flow Ratio= 0.02
Log Output Level= 0
Friction Slope Method= 1
Unsteady Friction Slope Method= 2
Unsteady Bridges Friction Slope Method= 1
Parabolic Critical Depth
Global Vel Dist=  1 , 1 , 1
Global Log Level= 0
CheckData=True
Encroach Param= -1, 0, 0, 0
BEGIN DESCRIPTION:
Multiple Run
END DESCRIPTION:

--- UNT 101 in LFCCL Watershed.f01 (steady flow) ---

Flow Title=Multiple
Number of Profiles=7
Profile Names=10-year,25-year,50-year,1pct_min,100-year,1pct_plu,500-year
River Rch & RM= UNT 101 in LFCCL,Reach-1,1525
     599     795     951     565    1128    2251    1581
Boundary for River Rch & Prof#=UNT 101 in LFCCL,Reach-1,1
Up Type=0
Dn Type=3
Dn Slope=0.005
Boundary for River Rch & Prof#=UNT 101 in LFCCL,Reach-1,2
Up Type=0
Dn Type=3
Dn Slope=0.005
Boundary for River Rch & Prof#=UNT 101 in LFCCL,Reach-1,3
Up Type=0
Dn Type=3
Dn Slope=0.005
Boundary for River Rch & Prof#=UNT 101 in LFCCL,Reach-1,4
Up Type=0
Dn Type=3
Dn Slope=0.005
Boundary for River Rch & Prof#=UNT 101 in LFCCL,Reach-1,5
Up Type=0
Dn Type=3
Dn Slope=0.005
Boundary for River Rch & Prof#=UNT 101 in LFCCL,Reach-1,6
Up Type=0
Dn Type=3
Dn Slope=0.005
Boundary for River Rch & Prof#=UNT 101 in LFCCL,Reach-1,7
Up Type=0
Dn Type=3
Dn Slope=0.005

--- UNT 101 in LFCCL Watershed.g01 (geometry) ---

Geom Title=Existing Conditions

River Reach=UNT 101 in LFCCL,Reach-1
Reach XY= 30
      2835795.42      7061141.55      2835773.83      7061117.35
      2835754.68      7061081.11      2835725.52      7061051.24
      2835649.57      7061002.46      2835599.26      7060963.04
      2835509.63      7060865.18      2835439.08      7060822.88
      2835355.67      7060741.69      2835281.72      7060686.38
      2835165.85      7060571.78      2835092.86      7060525.76
      2835029.16      7060472.72      2835017.01      7060445.69
      2835021.57      7060428.29      2835040.18      7060399.53
      2835033.19      7060384.80      2834994.29      7060376.35
      2834969.90      7060355.63      2834939.64      7060362.79
      2834910.42      7060355.28      2834837.45      7060365.08
      2834813.67      7060346.83      2834772.95      7060345.54
      2834614.23      7060273.76      2834559.10      7060257.68
      2834527.03      7060256.21      2834494.12      7060235.10
      2834462.04      7060231.34      2834445.59      7060220.71

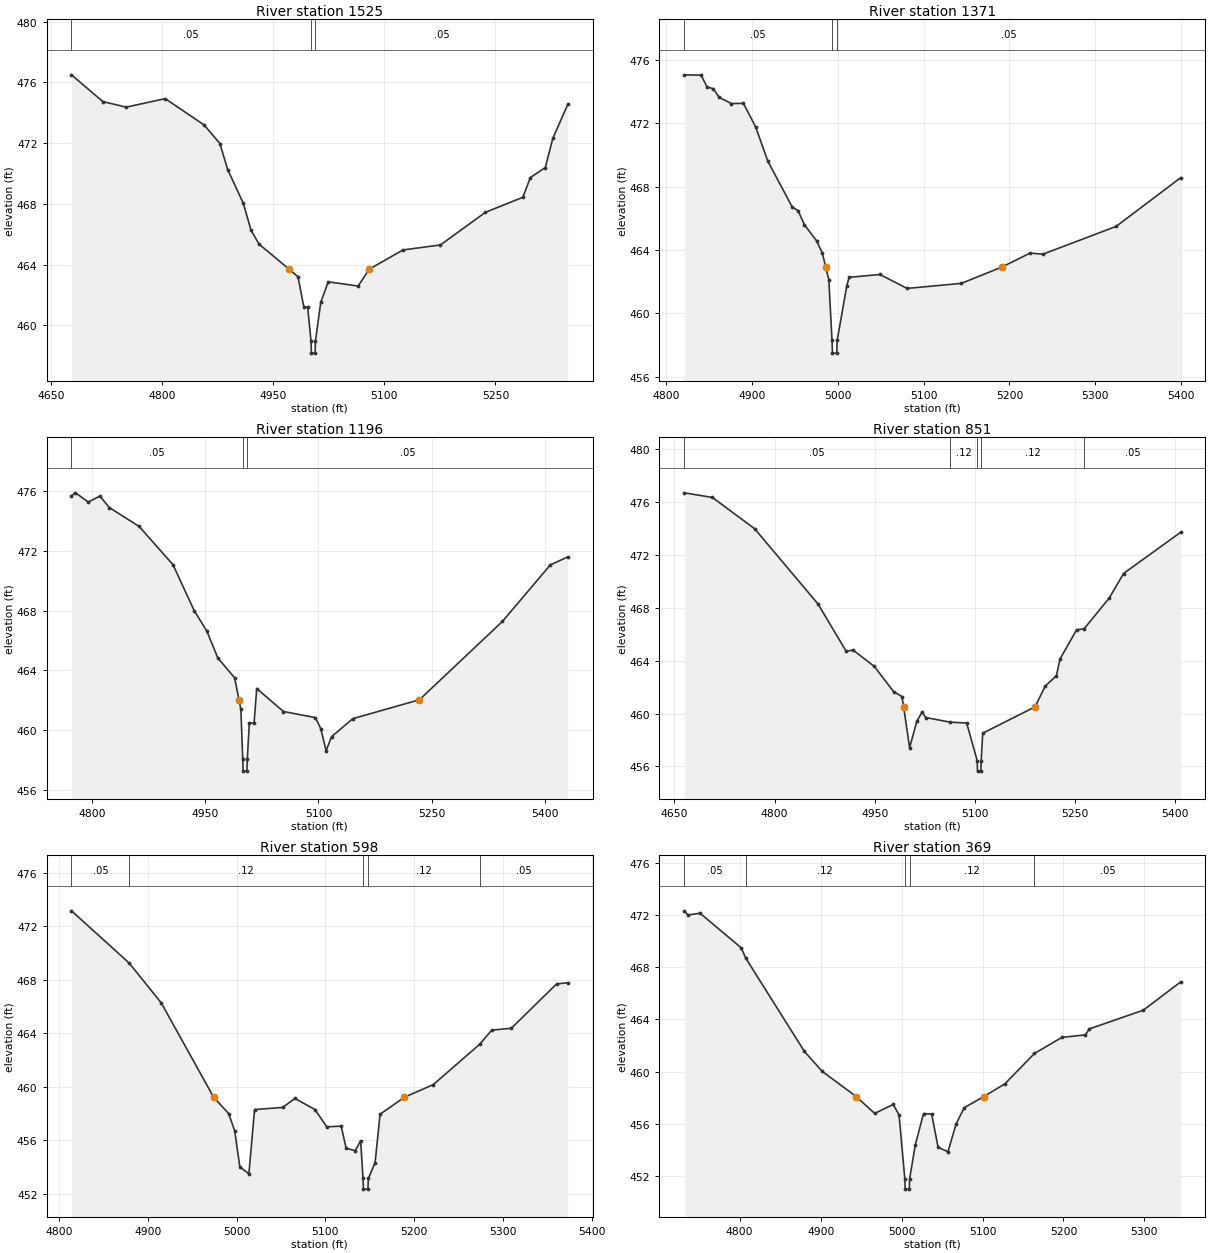
Type RM Length L Ch R = 1,1525,154,154,154
BEGIN DESCRIPTION:
UNT 101 in LFCCL Watershed 4.0
END DESCRIPTION:
XS GIS Cut Line= 3
      2835725.00      7060675.01      2835625.00      7060975.00
      2835575.00      7061325.03
#Sta/Elev= 30
  4677.9  476.50  4720.1  474.74  4751.7  474.37  4804.4  474.93  4857.1  473.19
  4878.2  471.97  4888.7  470.26  4909.8  468.03  4920.3  466.25  4930.9  465.35
  4971.6  463.69  4983.6  463.19  4991.5  461.20  4996.6  461.20  5001.2  458.96
  5001.7  458.16  5006.7  458.16  5007.2  458.96  5014.3  461.50  5024.4  462.86
  5064.8  462.58  5079.7  463.69  5125.4  464.96  5175.9  465.29  5236.6  467.44
  5287.1  468.43  5297.2  469.73  5317.4  470.39  5327.5  472.31  5347.7  474.55
#Mann=3,-1,0
  4677.9    0.05       0  5001.2    0.03       0  5007.2    0.05       0
Bank Sta=4971.6,5079.7
Exp/Cntr=0.3,0.1

Type RM Length L Ch R = 1,1371,175,175,175
BEGIN DESCRIPTION:
XS3699A
END DESCRIPTION:
XS GIS Cut Line= 3
      2835636.62      7060739.28      2835506.42      7060882.50
      2835384.88      7061247.12
#Sta/Elev= 30
  4821.4  475.05  4841.0  475.03  4847.8  474.29  4855.2  474.17  4862.0  473.63
  4876.1  473.24  4890.3  473.25  4904.5  471.76  4918.7  469.60  4947.1  466.71
  4953.8  466.49  4961.3  465.59  4975.5  464.58  4982.2  463.79  4986.0  462.94
  4989.7  462.12  4993.4  458.30  4993.9  457.50  4998.9  457.50  4999.4  458.30
  5010.6  461.74  5013.3  462.28  5049.2  462.46  5080.8  461.58  5144.1  461.90
  5191.7  462.94  5224.1  463.81  5239.0  463.74  5324.2  465.49  5399.3  468.56
#Mann=3,-1,0
  4821.4    0.05       0  4993.4    0.03       0  4999.4    0.05       0
Bank Sta=4986,5191.7
Exp/Cntr=0.3,0.1

Type RM Length L Ch R = 1,1196,345,345,345
BEGIN DESCRIPTION:
UNT 101 in LFCCL Watershed 3.0
END DESCRIPTION:
XS GIS Cut Line= 3
      2835480.39      7060561.30      2835375.00      7060775.00
      2835081.06      7061073.49
#Sta/Elev= 30
  4772.9  475.71  4778.2  475.91  4795.1  475.29  4810.5  475.69  4823.1  474.92
  4862.4  473.66  4907.3  471.09  4935.4  468.01  4952.3  466.62  4966.6  464.84
  4988.9  463.50  4994.7  462.03  4997.2  461.39  4999.7  458.04  5000.2  457.24
  5005.2  457.24  5005.7  458.04  5008.4  460.47  5014.7  460.47  5018.2  462.78
  5053.6  461.24  5096.0  460.83  5103.1  460.08  5110.1  458.61  5117.3  459.55
  5145.5  460.76  5233.7  462.03  5343.5  467.28  5407.1  471.08  5430.1  471.61
#Mann=3,-1,0
  4772.9    0.05       0  4999.7    0.03       0  5005.7    0.05       0
Bank Sta=4994.7,5233.7
Exp/Cntr=0.3,0.1

Type RM Length L Ch R = 1,851,253,253,253
BEGIN DESCRIPTION:
UNT 101 in LFCCL Watershed 2.0
END DESCRIPTION:
XS GIS Cut Line= 3
      2835424.96      7060425.01      2835125.00      7060525.00
      2834975.00      7060925.01
#Sta/Elev= 30
  4664.9  476.71  4707.0  476.36  4770.3  473.99  4865.1  468.30  4907.3  464.72
  4917.8  464.80  4949.5  463.57  4978.5  461.65  4990.9  461.29  4993.4  460.51
  5002.4  457.41  5013.1  459.40  5021.1  460.12  5026.5  459.70  5062.7  459.35
  5087.9  459.28  5103.6  456.44  5104.1  455.64  5109.1  455.64  5109.6  456.44
  5111.9  458.51  5190.3  460.51  5205.4  462.07  5222.3  462.86  5227.6  464.12
  5252.5  466.34  5263.8  466.42  5301.5  468.75  5322.8  470.60  5408.3  473.72
#Mann=5,-1,0
  4664.9    0.05       0  5062.7    0.12       0  5103.6    0.03       0
  5109.6    0.12       0  5263.8    0.05       0
Bank Sta=4993.4,5190.3
Exp/Cntr=0.3,0.1

Type RM Length L Ch R = 1,598,229,229,229
BEGIN DESCRIPTION:
XS3698A
END DESCRIPTION:
XS GIS Cut Line= 3
      2835069.79      7060206.27      2834994.27      7060380.76
      2834819.92      7060706.05
#Sta/Elev= 30
  4814.0  473.17  4879.1  469.26  4915.2  466.28  4974.2  459.23  4991.1  458.01
  4997.9  456.72  5003.7  454.02  5013.9  453.51  5020.3  458.31  5052.1  458.47
  5065.7  459.14  5088.4  458.31  5101.6  457.02  5117.9  457.07  5123.5  455.41
  5133.8  455.24  5139.8  455.98  5142.5  453.16  5143.0  452.36  5148.0  452.36
  5148.5  453.16  5156.1  454.34  5161.7  457.96  5189.1  459.23  5221.8  460.18
  5273.9  463.19  5287.6  464.25  5309.6  464.39  5360.7  467.71  5373.2  467.79
#Mann=5,-1,0
  4814.0    0.05       0  4879.1    0.12       0  5142.5    0.07       0
  5148.5    0.12       0  5273.9    0.05       0
Bank Sta=4974.2,5189.1
Exp/Cntr=0.3,0.1

Type RM Length L Ch R = 1,369,163,163,163
BEGIN DESCRIPTION:
Mapping XS 20ed0ec3
END DESCRIPTION:
XS GIS Cut Line= 3
      2834930.95      7060124.02      2834786.36      7060337.87
      2834747.56      7060690.70
#Sta/Elev= 30
  4731.6  472.31  4736.1  471.99  4751.0  472.13  4801.9  469.48  4807.6  468.68
  4879.9  461.56  4901.8  460.04  4944.0  458.10  4966.8  456.81  4989.7  457.50
  4996.9  456.69  5004.0  451.82  5004.5  451.02  5009.5  451.02  5010.0  451.82
  5017.0  454.41  5027.1  456.80  5037.2  456.76  5045.1  454.22  5057.3  453.88
  5067.3  456.00  5077.4  457.25  5101.6  458.10  5127.7  459.08  5164.2  461.40
  5198.1  462.63  5227.1  462.82  5232.1  463.28  5298.7  464.71  5344.7  466.87
#Mann=5,-1,0
  4731.6    0.05       0  4807.6    0.12       0  5004.0    0.07       0
  5010.0    0.12       0  5164.2    0.05       0
Bank Sta=4944,5101.6
Exp/Cntr=0.3,0.1

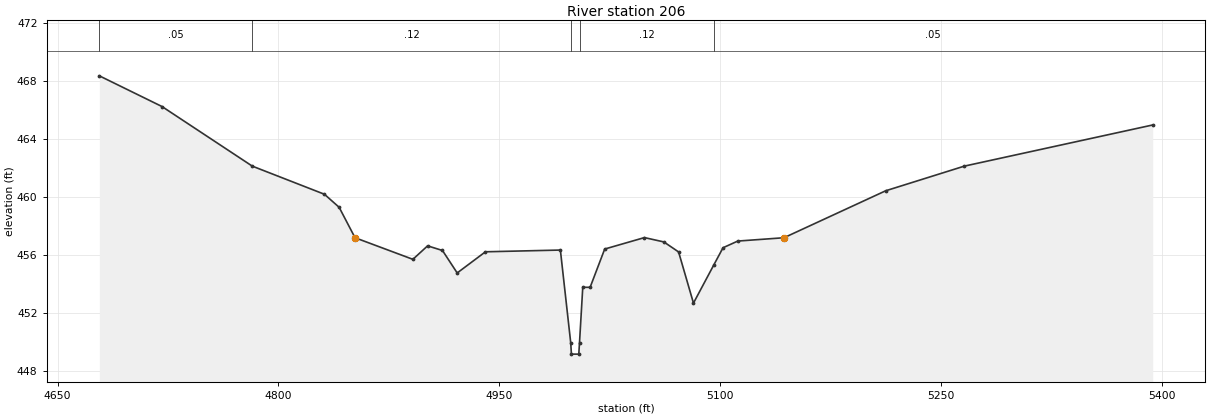
Type RM Length L Ch R = 1,206,0,0,0
BEGIN DESCRIPTION:
UNT 101 in LFCCL Watershed 1.0
END DESCRIPTION:
XS GIS Cut Line= 3
      2834657.56      7059962.45      2834635.91      7060290.28
      2834672.14      7060675.64
#Sta/Elev= 30
  4678.3  468.38  4720.9  466.26  4782.2  462.15  4831.2  460.21  4841.2  459.31
  4852.0  457.21  4891.3  455.72  4901.3  456.65  4911.4  456.33  4921.4  454.78
  4940.6  456.24  4991.5  456.36  4998.5  449.98  4999.0  449.18  5004.0  449.18
  5004.5  449.98  5006.7  453.79  5011.7  453.79  5021.6  456.43  5048.6  457.22
  5061.8  456.92  5071.8  456.23  5081.9  452.70  5095.7  455.33  5102.0  456.52
  5112.0  456.98  5143.4  457.21  5212.5  460.45  5265.9  462.15  5393.9  464.99
#Mann=5,-1,0
  4678.3    0.05       0  4782.2    0.12       0  4998.5    0.07       0
  5004.5    0.12       0  5095.7    0.05       0
Bank Sta=4852,5143.4
Exp/Cntr=0.3,0.1

Chan Stop Cuts=-1