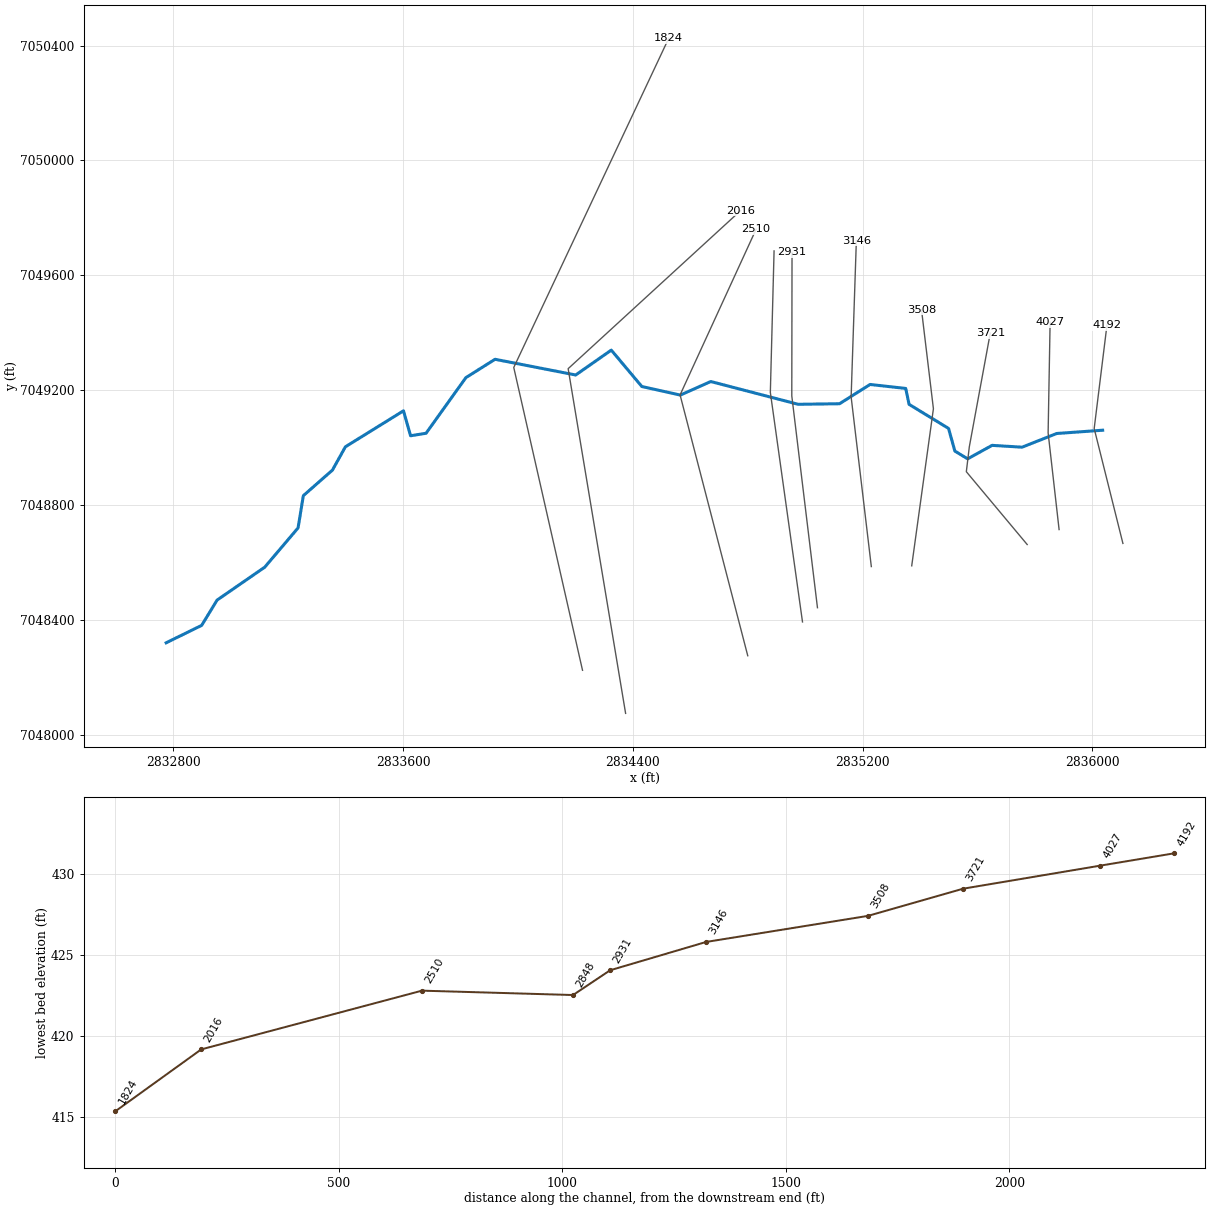
--- UNT 103 in LFCCL Watershed.prj (project) ---

Proj Title=UNT 103 in LFCCL Watershed Base Level Engineering
Current Plan=p01
Default Exp/Contr=0.3,0.1
English Units
Geom File=g01
Flow File=f01
Plan File=p01
BEGIN DESCRIPTION:
UNT 103 in LFCCL Watershed
END DESCRIPTION:

--- UNT 103 in LFCCL Watershed.p01 (plan) ---

Plan Title=Multiple Run
Short Identifier=Multiple
Geom File=g01
Flow File=f01
Subcritical Flow
K Sum by GR= 0
Std Step Tol= 0.01
Critical Tol= 0.01
Num of Std Step Trials= 20
Max Error Tol= 0.3
Flow Tol Ratio= 0.001
Split Flow NTrial= 30
Split Flow Tol= 0.02
Split Flow Ratio= 0.02
Log Output Level= 0
Friction Slope Method= 1
Unsteady Friction Slope Method= 2
Unsteady Bridges Friction Slope Method= 1
Parabolic Critical Depth
Global Vel Dist=  1 , 1 , 1
Global Log Level= 0
CheckData=True
Encroach Param= -1, 0, 0, 0
BEGIN DESCRIPTION:
Multiple Run
END DESCRIPTION:

--- UNT 103 in LFCCL Watershed.f01 (steady flow) ---

Flow Title=Multiple
Number of Profiles=7
Profile Names=10-year,25-year,50-year,1pct_min,100-year,1pct_plu,500-year
River Rch & RM= UNT 103 in LFCCL,Reach-1,4192
     500     663     794     473     945    1885    1338
Boundary for River Rch & Prof#=UNT 103 in LFCCL,Reach-1,1
Up Type=0
Dn Type=3
Dn Slope=0.005
Boundary for River Rch & Prof#=UNT 103 in LFCCL,Reach-1,2
Up Type=0
Dn Type=3
Dn Slope=0.005
Boundary for River Rch & Prof#=UNT 103 in LFCCL,Reach-1,3
Up Type=0
Dn Type=3
Dn Slope=0.005
Boundary for River Rch & Prof#=UNT 103 in LFCCL,Reach-1,4
Up Type=0
Dn Type=3
Dn Slope=0.005
Boundary for River Rch & Prof#=UNT 103 in LFCCL,Reach-1,5
Up Type=0
Dn Type=3
Dn Slope=0.005
Boundary for River Rch & Prof#=UNT 103 in LFCCL,Reach-1,6
Up Type=0
Dn Type=3
Dn Slope=0.005
Boundary for River Rch & Prof#=UNT 103 in LFCCL,Reach-1,7
Up Type=0
Dn Type=3
Dn Slope=0.005

--- UNT 103 in LFCCL Watershed.g01 (geometry) ---

Geom Title=Existing Conditions

River Reach=UNT 103 in LFCCL,Reach-1
Reach XY= 30
      2836035.59      7049060.71      2835875.84      7049049.31
      2835755.11      7049001.65      2835650.81      7049008.03
      2835565.77      7048961.08      2835521.25      7048988.13
      2835499.20      7049067.06      2835361.87      7049150.73
      2835350.14      7049206.18      2835226.10      7049220.02
      2835119.68      7049152.91      2834975.70      7049150.96
      2834671.46      7049230.25      2834565.55      7049183.10
      2834431.48      7049212.90      2834325.14      7049339.60
      2834201.21      7049252.98      2833920.57      7049307.64
      2833819.09      7049243.91      2833680.31      7049050.17
      2833626.35      7049041.45      2833601.78      7049128.29
      2833399.52      7049003.00      2833354.38      7048921.83
      2833253.19      7048832.97      2833234.70      7048720.57
      2833118.75      7048583.96      2832952.85      7048469.39
      2832899.20      7048381.41      2832775.59      7048320.71

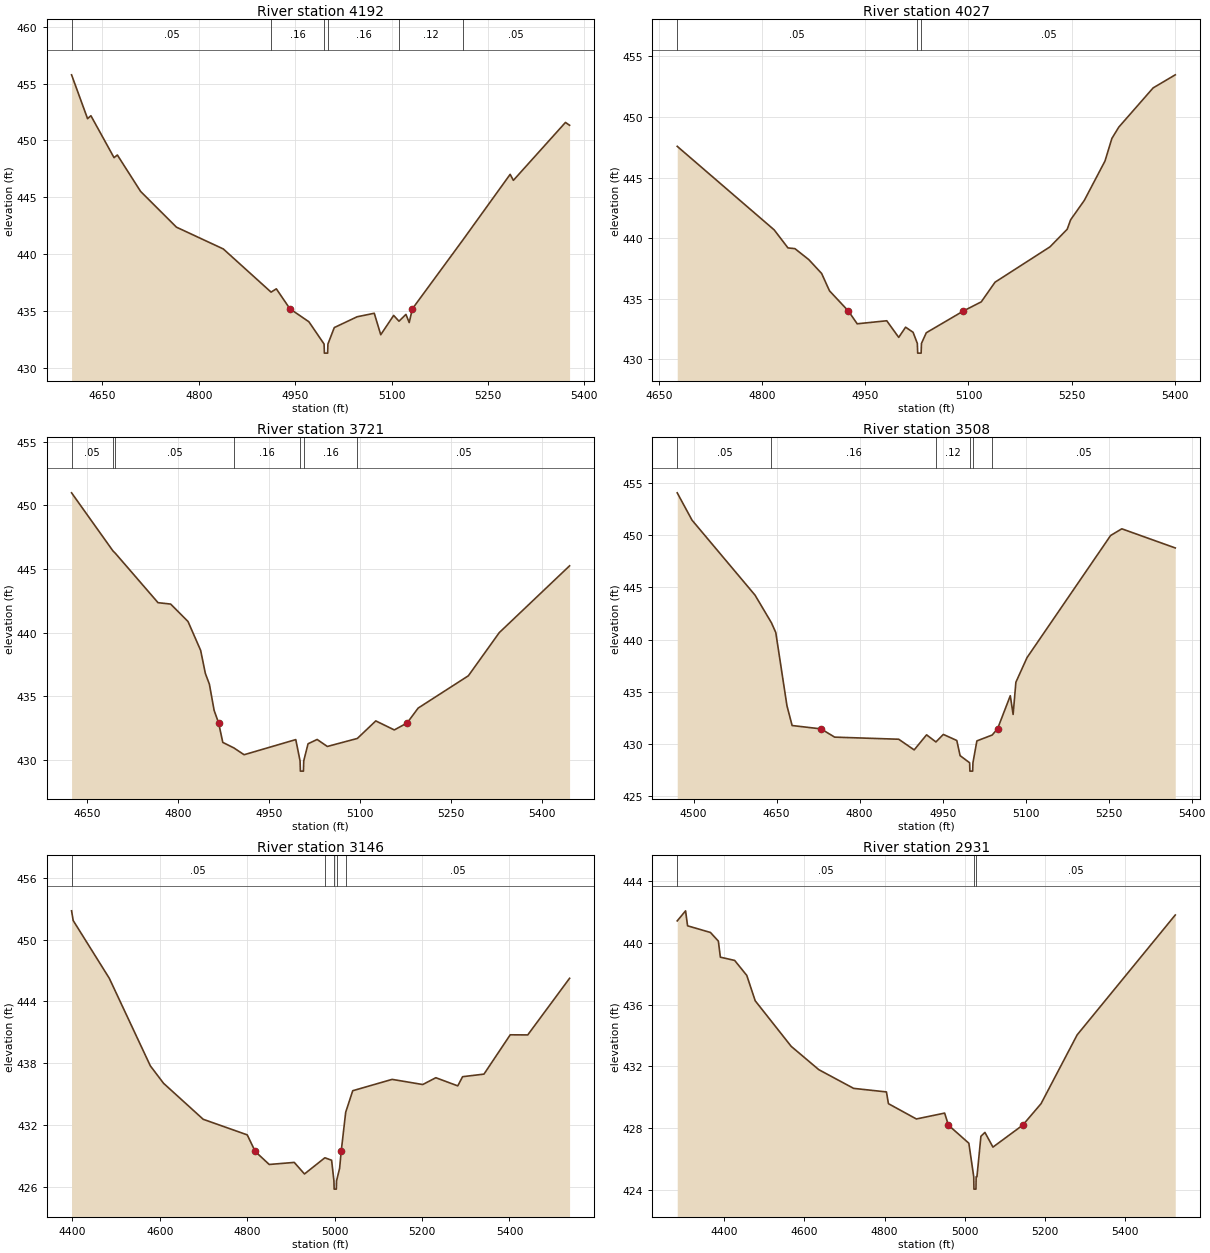
Type RM Length L Ch R = 1,4192,165,165,165
BEGIN DESCRIPTION:
UNT 103 in LFCCL Watershed 7.0
END DESCRIPTION:
XS GIS Cut Line= 3
      2836106.25      7048666.66      2836006.25      7049066.67
      2836050.75      7049426.71
#Sta/Elev= 30
  4601.9  455.78  4626.8  451.92  4632.0  452.18  4668.0  448.49  4673.2  448.72
  4709.3  445.52  4765.1  442.37  4838.1  440.45  4912.4  436.65  4920.6  436.94
  4941.8  435.18  4971.3  434.04  4994.9  432.08  4995.4  431.28  5000.4  431.28
  5000.9  432.08  5010.8  433.53  5046.3  434.48  5073.0  434.79  5083.1  432.90
  5103.2  434.60  5111.5  434.09  5122.3  434.69  5127.4  433.97  5132.3  435.18
  5210.4  441.20  5284.5  447.02  5289.5  446.49  5370.6  451.59  5377.0  451.34
#Mann=6,-1,0
  4601.9    0.05       0  4912.4    0.16       0  4994.9    0.07       0
  5000.9    0.16       0  5111.5    0.12       0  5210.4    0.05       0
Bank Sta=4941.8,5132.3
Exp/Cntr=0.3,0.1

Type RM Length L Ch R = 1,4027,306,306,306
BEGIN DESCRIPTION:
XS3704A
END DESCRIPTION:
XS GIS Cut Line= 3
      2835884.08      7048714.90      2835845.89      7049051.71
      2835852.83      7049437.17
#Sta/Elev= 30
  4676.3  447.58  4817.3  440.69  4837.4  439.20  4847.5  439.14  4867.6  438.24
  4886.4  437.09  4897.8  435.66  4925.2  434.00  4938.1  432.94  4981.1  433.19
  4998.5  431.82  5008.5  432.66  5019.4  432.24  5025.6  431.32  5026.1  430.52
  5031.1  430.52  5031.6  431.32  5038.6  432.20  5092.7  434.00  5118.6  434.75
  5138.6  436.37  5218.6  439.29  5243.6  440.74  5248.6  441.52  5268.6  443.13
  5298.6  446.37  5308.6  448.23  5318.6  449.16  5368.6  452.40  5400.8  453.48
#Mann=3,-1,0
  4676.3    0.05       0  5025.6    0.03       0  5031.6    0.05       0
Bank Sta=4925.2,5092.7
Exp/Cntr=0.3,0.1

Type RM Length L Ch R = 1,3721,213,213,213
BEGIN DESCRIPTION:
XS3703A
END DESCRIPTION:
XS GIS Cut Line= 4
      2835772.99      7048662.80      2835561.17      7048916.29
      2835571.58      7049003.10      2835644.51      7049398.96
#Sta/Elev= 30
  4624.6  450.99  4692.8  446.42  4696.8  446.23  4767.0  442.35  4787.8  442.24
  4816.4  440.87  4837.2  438.60  4845.0  436.78  4851.6  435.94  4859.4  433.88
  4866.8  432.89  4873.7  431.36  4891.8  430.93  4908.8  430.39  4993.9  431.58
  5001.0  429.90  5001.5  429.10  5006.5  429.10  5007.0  429.90  5014.1  431.25
  5029.1  431.59  5045.9  431.04  5095.3  431.67  5125.7  433.05  5156.2  432.34
  5177.3  432.89  5195.5  434.06  5278.2  436.60  5329.0  439.99  5444.9  445.25
#Mann=7,-1,0
  4624.6    0.05       0  4692.8    0.16       0  4696.8    0.05       0
  4891.8    0.16       0  5001.0    0.07       0  5007.0    0.16       0
  5095.3    0.05       0
Bank Sta=4866.8,5177.3
Exp/Cntr=0.3,0.1

Type RM Length L Ch R = 1,3508,362,362,362
BEGIN DESCRIPTION:
Mapping XS 166dd2dc
END DESCRIPTION:
XS GIS Cut Line= 3
      2835371.03      7048588.60      2835446.55      7049135.49
      2835405.00      7049480.91
#Sta/Elev= 30
  4470.4  454.03  4497.1  451.42  4611.1  444.24  4640.7  441.60  4648.5  440.67
  4668.7  433.67  4678.0  431.78  4730.2  431.46  4754.9  430.67  4870.6  430.47
  4898.6  429.45  4921.0  430.89  4937.9  430.21  4951.3  430.93  4975.6  430.35
  4981.6  428.90  4998.8  428.22  4999.3  427.42  5004.3  427.42  5004.8  428.22
  5011.9  430.31  5039.5  430.87  5049.2  431.46  5072.3  434.63  5077.4  432.84
  5082.4  435.92  5102.6  438.28  5253.6  449.95  5273.8  450.59  5370.4  448.76
#Mann=6,-1,0
  4470.4    0.05       0  4640.7    0.16       0  4937.9    0.12       0
  4998.8    0.07       0  5004.8    0.12       0  5039.5    0.05       0
Bank Sta=4730.2,5049.2
Exp/Cntr=0.3,0.1

Type RM Length L Ch R = 1,3146,215,215,215
BEGIN DESCRIPTION:
XS3702A
END DESCRIPTION:
XS GIS Cut Line= 3
      2835230.40      7048586.06      2835160.12      7049176.71
      2835178.30      7049720.69
#Sta/Elev= 30
  4398.4  452.79  4402.1  451.85  4484.7  446.25  4578.6  437.76  4608.8  436.07
  4699.5  432.58  4800.2  431.07  4818.5  429.46  4850.5  428.20  4907.8  428.40
  4931.1  427.28  4977.8  428.85  4993.2  428.61  4998.5  426.61  4999.0  425.81
  5004.0  425.81  5004.5  426.61  5011.5  427.83  5015.1  429.46  5025.4  433.26
  5041.5  435.35  5131.6  436.45  5201.6  435.95  5231.6  436.61  5281.7  435.82
  5292.8  436.71  5341.7  436.96  5401.7  440.77  5441.8  440.76  5537.5  446.25
#Mann=5,-1,0
  4398.4    0.05       0  4977.8    0.12       0  4998.5    0.07       0
  5004.5    0.12       0  5025.4    0.05       0
Bank Sta=4818.5,5015.1
Exp/Cntr=0.3,0.1

Type RM Length L Ch R = 1,2931,83,83,83
BEGIN DESCRIPTION:
XS3701A
END DESCRIPTION:
XS GIS Cut Line= 3
      2835042.91      7048442.77      2834953.53      7049180.18
      2834954.36      7049679.77
#Sta/Elev= 30
  4282.8  441.42  4303.6  442.07  4308.6  441.10  4365.6  440.67  4385.4  440.11
  4390.4  439.07  4426.1  438.86  4456.3  437.89  4477.3  436.25  4567.1  433.30
  4636.0  431.79  4722.9  430.58  4804.7  430.35  4809.7  429.59  4879.4  428.60
  4949.9  428.98  4959.3  428.20  5010.3  427.03  5022.5  424.86  5023.0  424.06
  5028.0  424.06  5028.5  424.86  5030.5  424.86  5040.4  427.48  5050.4  427.73
  5070.4  426.78  5144.7  428.20  5190.4  429.59  5280.4  434.04  5525.2  441.80
#Mann=3,-1,0
  4282.8    0.05       0  5022.5    0.03       0  5028.5    0.05       0
Bank Sta=4959.3,5144.7
Exp/Cntr=0.3,0.1

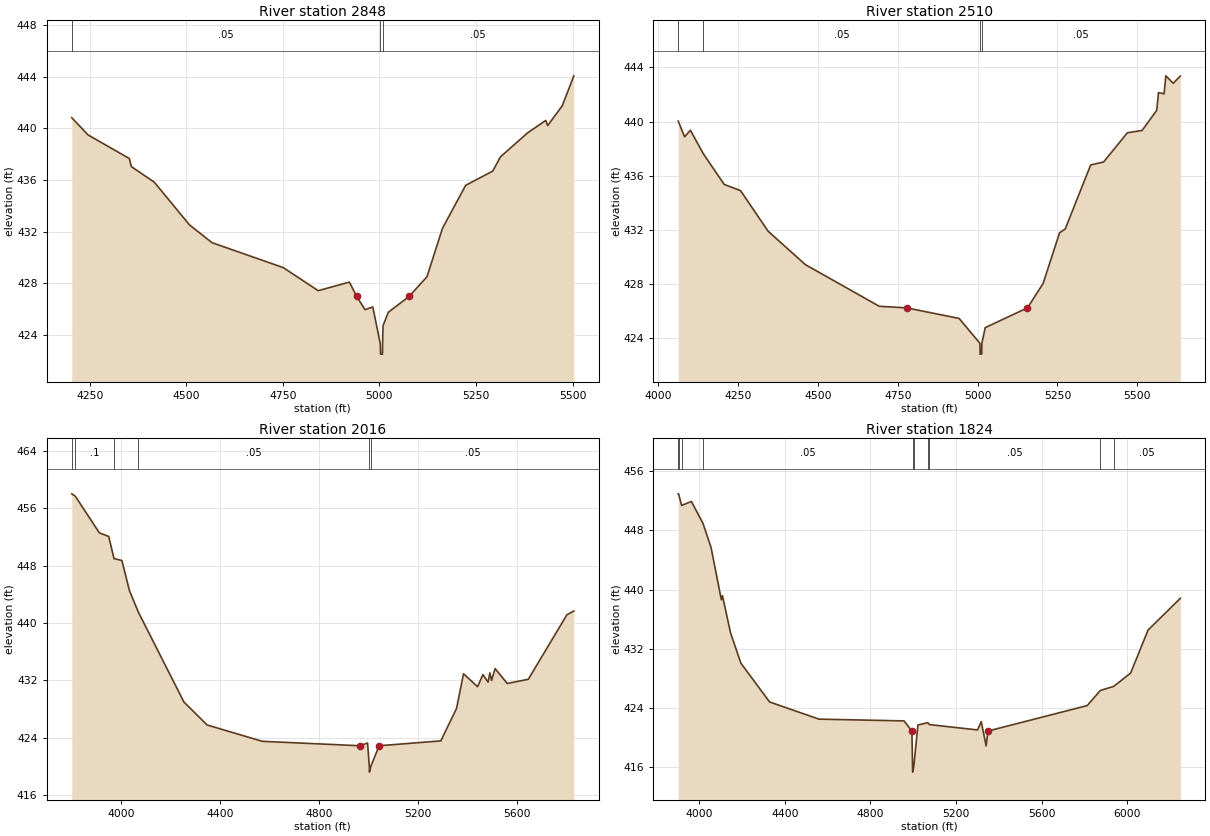
Type RM Length L Ch R = 1,2848,338,338,338
BEGIN DESCRIPTION:
XS3700A
END DESCRIPTION:
XS GIS Cut Line= 3
      2834990.82      7048393.32      2834878.87      7049192.33
      2834891.86      7049684.94
#Sta/Elev= 30
  4203.7  440.82  4245.8  439.49  4352.8  437.66  4357.8  437.04  4417.4  435.83
  4508.3  432.53  4566.9  431.15  4750.7  429.23  4841.6  427.44  4922.3  428.10
  4941.0  427.01  4962.7  425.97  4982.9  426.18  5002.3  423.33  5002.8  422.53
  5007.8  422.53  5008.3  423.33  5009.3  424.73  5023.2  425.77  5077.5  427.01
  5123.2  428.52  5163.2  432.26  5223.3  435.59  5293.3  436.69  5313.3  437.79
  5383.3  439.64  5430.5  440.61  5435.5  440.21  5473.3  441.74  5503.3  444.06
#Mann=3,-1,0
  4203.7    0.05       0  5002.3    0.03       0  5008.3    0.05       0
Bank Sta=4941,5077.5
Exp/Cntr=0.3,0.1

Type RM Length L Ch R = 1,2510,494,494,494
BEGIN DESCRIPTION:
UNT 103 in LFCCL Watershed 3.0
END DESCRIPTION:
XS GIS Cut Line= 3
      2834800.22      7048275.67      2834564.64      7049183.65
      2834829.27      7049760.29
#Sta/Elev= 30
  4062.5  440.03  4082.5  438.87  4100.6  439.36  4140.8  437.63  4206.4  435.35
  4257.7  434.89  4344.0  431.89  4460.6  429.42  4692.0  426.34  4778.1  426.22
  4942.2  425.44  5007.5  423.60  5008.0  422.80  5013.0  422.80  5013.5  423.60
  5024.0  424.76  5156.3  426.22  5205.4  428.03  5256.9  431.78  5274.4  432.05
  5354.3  436.79  5394.8  437.01  5469.3  439.17  5515.3  439.34  5561.2  440.83
  5566.7  442.14  5584.2  442.05  5589.7  443.38  5612.7  442.83  5635.0  443.36
#Mann=4,-1,0
  4062.5    0.08       0  4140.8    0.05       0  5007.5    0.03       0
  5013.5    0.05       0
Bank Sta=4778.1,5156.3
Exp/Cntr=0.3,0.1

Type RM Length L Ch R = 1,2016,192,192,192
BEGIN DESCRIPTION:
UNT 103 in LFCCL Watershed 2.0
END DESCRIPTION:
XS GIS Cut Line= 3
      2834375.00      7048075.00      2834175.00      7049275.00
      2834775.01      7049825.01
#Sta/Elev= 30
  3801.4  458.01  3815.7  457.68  3912.9  452.57  3950.9  452.06  3972.2  448.97
  4004.2  448.70  4034.6  444.51  4071.0  441.48  4255.1  428.95  4348.8  425.75
  4571.9  423.47  4966.9  422.85  4997.7  423.23  5004.8  419.97  5005.3  419.17
  5010.8  419.97  5044.4  422.85  5293.9  423.53  5357.4  428.05  5385.8  432.90
  5442.5  431.09  5464.1  432.77  5485.0  431.73  5492.4  433.02  5499.2  431.96
  5513.4  433.62  5562.7  431.54  5647.8  432.13  5803.8  441.13  5831.9  441.65
#Mann=6,-1,0
  3801.4    0.16       0  3815.7     0.1       0  3972.2    0.08       0
  4071.0    0.05       0  5004.8    0.03       0  5010.8    0.05       0
Bank Sta=4966.9,5044.4
Exp/Cntr=0.3,0.1

Type RM Length L Ch R = 1,1824,0,0,0
BEGIN DESCRIPTION:
UNT 103 in LFCCL Watershed 1.0
END DESCRIPTION:
XS GIS Cut Line= 3
      2834225.00      7048225.00      2833985.64      7049279.14
      2834524.99      7050424.98
#Sta/Elev= 30
  3901.5  452.95  3903.0  452.95  3917.4  451.38  3963.0  451.92  4017.2  448.96
  4054.9  445.71  4103.1  438.63  4108.2  439.20  4146.2  434.15  4194.4  430.07
  4328.8  424.83  4559.6  422.51  4957.7  422.27  4994.0  420.90  4997.0  416.15
  4997.5  415.35  5003.0  416.15  5022.1  421.72  5068.1  422.03  5076.1  421.77
  5300.9  421.05  5318.2  422.17  5341.0  418.90  5349.7  420.90  5813.4  424.34
  5875.1  426.38  5937.9  426.94  6016.8  428.74  6098.0  434.54  6248.9  438.83
#Mann=10,-1,0
  3901.5     0.1       0  3903.0    0.16       0  3917.4    0.08       0
  4017.2    0.05       0  4997.0    0.03       0  5003.0    0.05       0
  5068.1    0.12       0  5076.1    0.05       0  5875.1     0.1       0
  5937.9    0.05       0
Bank Sta=4994,5349.7
Exp/Cntr=0.3,0.1

Chan Stop Cuts=-1