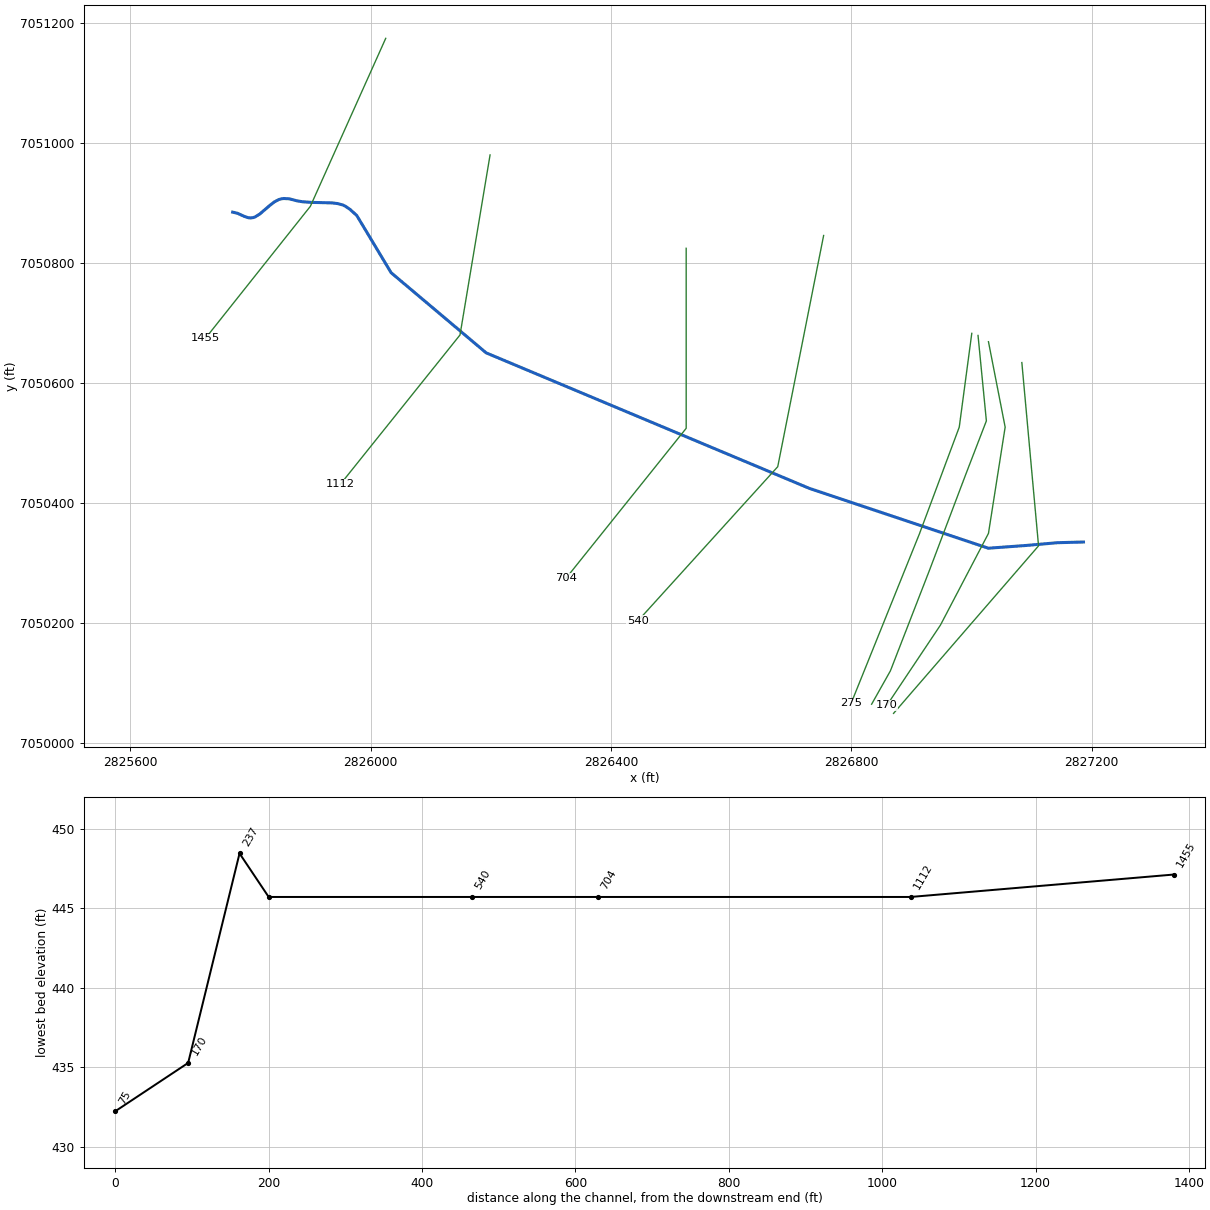
--- UNT 105 in LFCCL Watershed.prj (project) ---

Proj Title=UNT 105 in LFCCL Watershed Base Level Engineering
Current Plan=p01
Default Exp/Contr=0.3,0.1
English Units
Geom File=g01
Flow File=f01
Plan File=p01
BEGIN DESCRIPTION:
UNT 105 in LFCCL Watershed
END DESCRIPTION:

--- UNT 105 in LFCCL Watershed.p01 (plan) ---

Plan Title=Multiple Run
Short Identifier=Multiple
Geom File=g01
Flow File=f01
Subcritical Flow
K Sum by GR= 0
Std Step Tol= 0.01
Critical Tol= 0.01
Num of Std Step Trials= 20
Max Error Tol= 0.3
Flow Tol Ratio= 0.001
Split Flow NTrial= 30
Split Flow Tol= 0.02
Split Flow Ratio= 0.02
Log Output Level= 0
Friction Slope Method= 1
Unsteady Friction Slope Method= 2
Unsteady Bridges Friction Slope Method= 1
Parabolic Critical Depth
Global Vel Dist=  1 , 1 , 1
Global Log Level= 0
CheckData=True
Encroach Param= -1, 0, 0, 0
BEGIN DESCRIPTION:
Multiple Run
END DESCRIPTION:

--- UNT 105 in LFCCL Watershed.f01 (steady flow) ---

Flow Title=Multiple
Number of Profiles=7
Profile Names=10-year,25-year,50-year,1pct_min,100-year,1pct_plu,500-year
River Rch & RM= UNT 105 in LFCCL,Reach-1,1455
     272     348     406     237     473     943     640
Boundary for River Rch & Prof#=UNT 105 in LFCCL,Reach-1,1
Up Type=0
Dn Type=3
Dn Slope=0.005
Boundary for River Rch & Prof#=UNT 105 in LFCCL,Reach-1,2
Up Type=0
Dn Type=3
Dn Slope=0.005
Boundary for River Rch & Prof#=UNT 105 in LFCCL,Reach-1,3
Up Type=0
Dn Type=3
Dn Slope=0.005
Boundary for River Rch & Prof#=UNT 105 in LFCCL,Reach-1,4
Up Type=0
Dn Type=3
Dn Slope=0.005
Boundary for River Rch & Prof#=UNT 105 in LFCCL,Reach-1,5
Up Type=0
Dn Type=3
Dn Slope=0.005
Boundary for River Rch & Prof#=UNT 105 in LFCCL,Reach-1,6
Up Type=0
Dn Type=3
Dn Slope=0.005
Boundary for River Rch & Prof#=UNT 105 in LFCCL,Reach-1,7
Up Type=0
Dn Type=3
Dn Slope=0.005

--- UNT 105 in LFCCL Watershed.g01 (geometry) ---

Geom Title=Existing Conditions

River Reach=UNT 105 in LFCCL,Reach-1
Reach XY= 30
      2825770.32      7050885.28      2825778.23      7050883.42
      2825789.20      7050878.34      2825796.55      7050875.89
      2825800.54      7050875.63      2825804.52      7050876.24
      2825808.16      7050877.60      2825815.21      7050881.99
      2825832.38      7050896.72      2825839.45      7050902.19
      2825846.95      7050906.23      2825851.19      7050907.43
      2825855.56      7050908.01      2825864.38      7050907.50
      2825876.75      7050904.26      2825886.05      7050902.64
      2825900.69      7050901.59      2825935.49      7050900.67
      2825945.06      7050899.55      2825954.03      7050897.03
      2825958.17      7050894.96      2825965.91      7050889.53
      2825976.81      7050879.67      2826033.92      7050784.37
      2826192.14      7050650.73      2826729.76      7050424.93
      2827027.75      7050325.09      2827090.73      7050329.70
      2827142.96      7050334.30      2827186.17      7050335.44

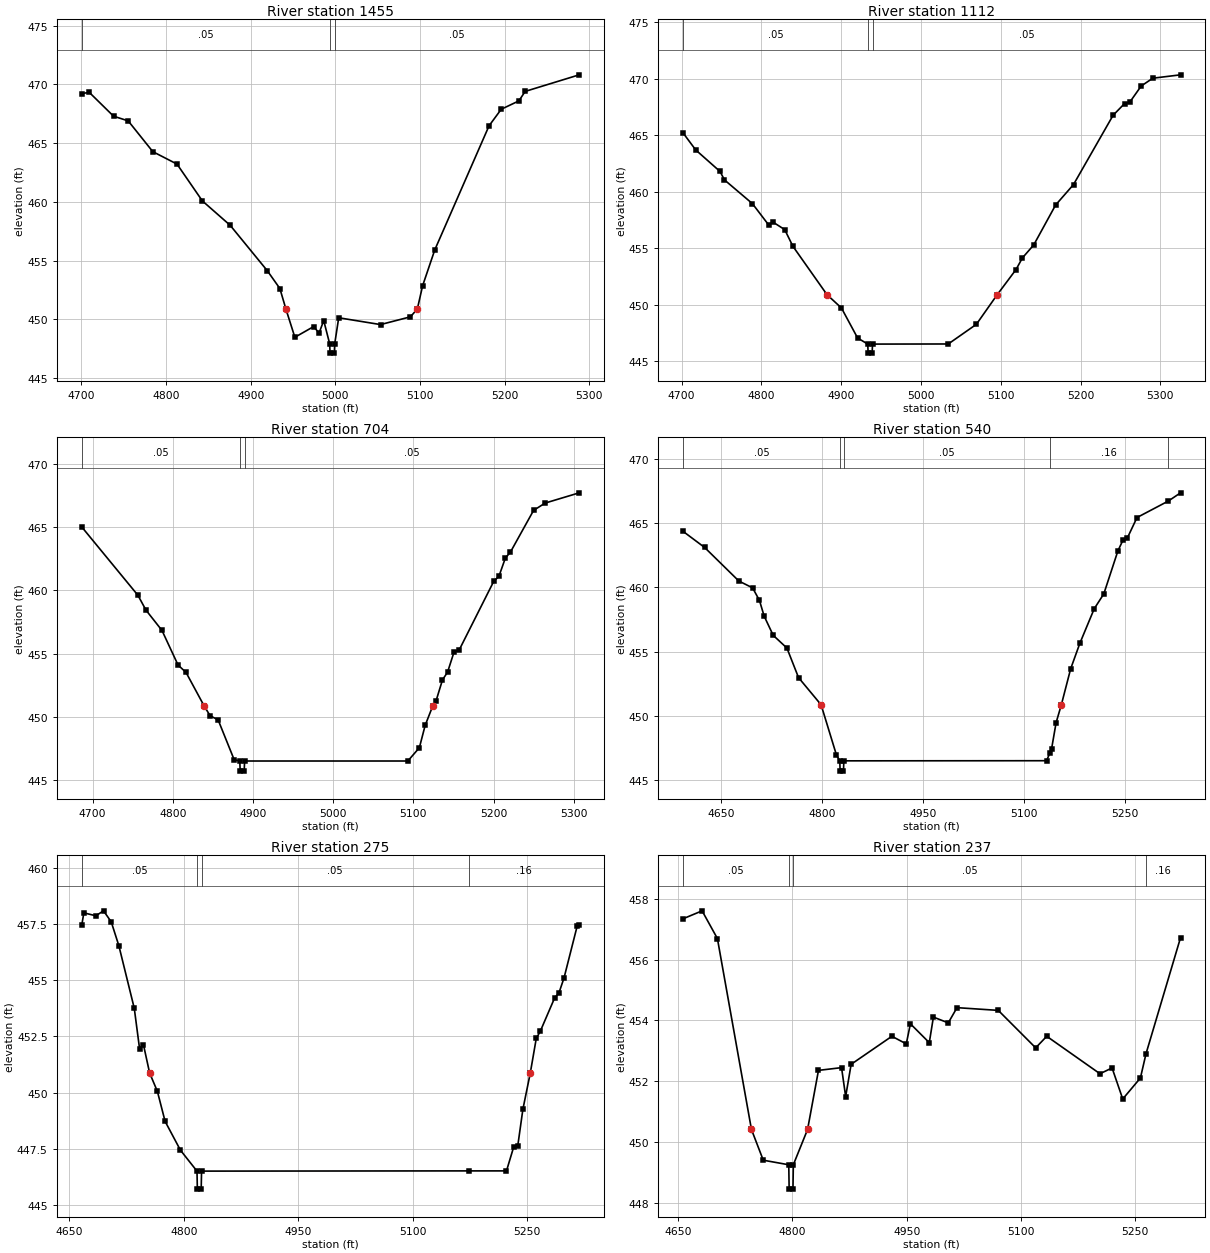
Type RM Length L Ch R = 1,1455,343,343,343
BEGIN DESCRIPTION:
UNT 105 in LFCCL Watershed 4.0
END DESCRIPTION:
XS GIS Cut Line= 3
      2826024.99      7051174.98      2825899.57      7050894.99
      2825725.02      7050675.03
#Sta/Elev= 30
  4700.4  469.22  4709.2  469.33  4737.9  467.30  4755.2  466.90  4784.3  464.28
  4812.9  463.22  4842.8  460.09  4875.7  458.01  4919.5  454.15  4934.4  452.63
  4941.5  450.89  4952.1  448.48  4974.3  449.39  4980.7  448.84  4986.2  449.90
  4993.2  447.93  4993.7  447.13  4998.7  447.13  4999.2  447.93  5003.9  450.14
  5053.3  449.56  5088.6  450.22  5096.8  450.89  5103.0  452.86  5117.4  455.92
  5181.5  466.48  5195.9  467.89  5216.7  468.60  5224.2  469.41  5288.0  470.82
#Mann=3,-1,0
  4700.4    0.05       0  4993.2    0.03       0  4999.2    0.05       0
Bank Sta=4941.5,5096.8
Exp/Cntr=0.3,0.1

Type RM Length L Ch R = 1,1112,408,408,408
BEGIN DESCRIPTION:
UNT 105 in LFCCL Watershed 3.0
END DESCRIPTION:
XS GIS Cut Line= 3
      2826198.62      7050980.59      2826148.61      7050680.56
      2825949.31      7050431.43
#Sta/Elev= 30
  4702.0  465.20  4717.8  463.70  4748.2  461.80  4753.8  461.05  4788.8  458.95
  4809.0  457.08  4814.7  457.31  4829.3  456.65  4839.5  455.18  4882.3  450.89
  4900.3  449.72  4920.6  447.06  4933.3  446.52  4933.8  445.72  4938.8  445.72
  4939.3  446.52  5034.2  446.53  5069.4  448.27  5095.5  450.89  5119.1  453.12
  5127.1  454.15  5141.3  455.30  5168.7  458.83  5191.1  460.64  5240.7  466.77
  5255.1  467.81  5261.5  467.92  5275.9  469.36  5290.4  470.05  5325.2  470.35
#Mann=3,-1,0
  4702.0    0.05       0  4933.3    0.03       0  4939.3    0.05       0
Bank Sta=4882.3,5095.5
Exp/Cntr=0.3,0.1

Type RM Length L Ch R = 1,704,164,164,164
BEGIN DESCRIPTION:
UNT 105 in LFCCL Watershed 2.0
END DESCRIPTION:
XS GIS Cut Line= 3
      2826525.00      7050825.01      2826525.00      7050525.00
      2826324.98      7050274.98
#Sta/Elev= 30
  4686.5  465.02  4756.5  459.62  4766.5  458.45  4786.5  456.84  4806.5  454.11
  4816.5  453.52  4838.9  450.89  4846.5  450.10  4856.5  449.77  4876.5  446.62
  4883.5  446.52  4884.0  445.72  4889.0  445.72  4889.5  446.52  5093.0  446.52
  5107.4  447.57  5114.6  449.33  5124.2  450.89  5128.2  451.27  5136.2  452.93
  5142.6  453.55  5150.6  455.13  5157.0  455.29  5200.2  460.73  5206.6  461.12
  5214.6  462.56  5221.0  463.04  5249.8  466.33  5264.2  466.91  5306.7  467.72
#Mann=3,-1,0
  4686.5    0.05       0  4883.5   0.033       0  4889.5    0.05       0
Bank Sta=4838.9,5124.2
Exp/Cntr=0.3,0.1

Type RM Length L Ch R = 1,540,265,265,265
BEGIN DESCRIPTION:
XS3708A
END DESCRIPTION:
XS GIS Cut Line= 3
      2826753.74      7050846.36      2826677.35      7050460.96
      2826444.72      7050204.03
#Sta/Elev= 30
  4593.4  464.36  4625.4  463.11  4676.3  460.50  4696.7  459.97  4706.9  458.99
  4713.8  457.78  4727.3  456.28  4747.7  455.29  4765.0  452.99  4798.5  450.88
  4821.3  446.98  4826.3  446.52  4826.8  445.72  4831.8  445.72  4832.3  446.52
  5133.7  446.53  5138.8  447.15  5141.1  447.43  5147.9  449.49  5155.7  450.88
  5169.5  453.67  5183.2  455.66  5204.6  458.35  5218.8  459.50  5239.8  462.85
  5247.2  463.67  5254.0  463.87  5268.2  465.44  5314.7  466.72  5332.9  467.36
#Mann=5,-1,0
  4593.4    0.05       0  4826.3   0.033       0  4832.3    0.05       0
  5138.8    0.16       0  5314.7    0.05       0
Bank Sta=4798.5,5155.7
Exp/Cntr=0.3,0.1

Type RM Length L Ch R = 1,275,38,38,38
BEGIN DESCRIPTION:
XS3705A
END DESCRIPTION:
XS GIS Cut Line= 4
      2827000.27      7050683.22      2826979.43      7050526.93
      2826913.46      7050349.85      2826799.46      7050066.57
#Sta/Elev= 30
  4666.2  457.45  4668.9  457.99  4684.6  457.86  4694.7  458.08  4704.8  457.59
  4714.8  456.53  4735.0  453.75  4742.0  451.94  4747.0  452.14  4755.1  450.88
  4765.3  450.06  4775.4  448.73  4795.5  447.45  4817.2  446.52  4817.7  445.72
  4822.7  445.72  4823.2  446.52  5173.3  446.53  5222.9  446.53  5232.3  447.59
  5237.7  447.65  5244.4  449.27  5254.1  450.88  5261.9  452.41  5267.3  452.74
  5286.1  454.22  5291.5  454.42  5298.3  455.10  5315.6  457.41  5318.2  457.44
#Mann=4,-1,0
  4666.2    0.05       0  4817.2   0.033       0  4823.2    0.05       0
  5173.3    0.16       0
Bank Sta=4755.1,5254.1
Exp/Cntr=0.3,0.1

Type RM Length L Ch R = 1,237,67,67,67
BEGIN DESCRIPTION:
XS3706A
END DESCRIPTION:
XS GIS Cut Line= 6
      2827010.68      7050679.75      2827024.57      7050537.35
      2826989.85      7050447.07      2826930.82      7050290.82
      2826864.85      7050120.68      2826833.58      7050065.09
#Sta/Elev= 30
  4656.5  457.34  4681.4  457.60  4701.5  456.69  4746.2  450.42  4761.7  449.41
  4795.2  449.26  4795.7  448.46  4800.7  448.46  4801.2  449.26  4819.9  450.42
  4834.2  452.36  4864.5  452.45  4869.9  451.50  4877.1  452.56  4930.6  453.48
  4949.5  453.23  4954.9  453.89  4979.7  453.27  4985.1  454.11  5004.6  453.92
  5016.1  454.42  5070.3  454.33  5119.4  453.10  5133.9  453.48  5203.8  452.25
  5219.7  452.44  5233.7  451.42  5256.9  452.11  5264.3  452.91  5309.6  456.72
#Mann=4,-1,0
  4656.5    0.05       0  4795.2    0.03       0  4801.2    0.05       0
  5264.3    0.16       0
Bank Sta=4746.2,4819.9
Exp/Cntr=0.3,0.1

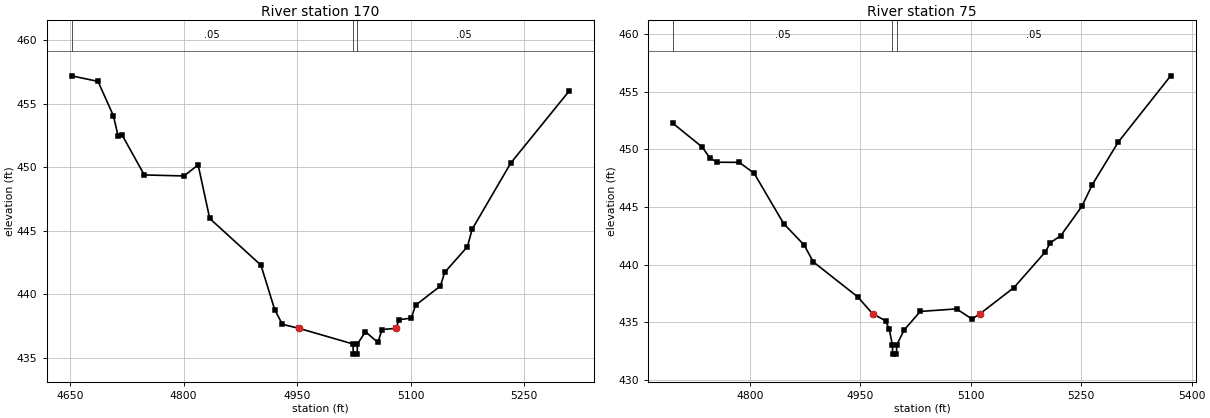
Type RM Length L Ch R = 1,170,95,95,95
BEGIN DESCRIPTION:
XS3707A
END DESCRIPTION:
XS GIS Cut Line= 5
      2827028.04      7050669.33      2827055.82      7050526.93
      2827028.05      7050349.85      2826948.18      7050197.07
      2826858.94      7050063.21
#Sta/Elev= 30
  4651.8  457.21  4686.8  456.77  4707.2  454.05  4713.3  452.47  4718.3  452.58
  4747.9  449.40  4800.4  449.32  4819.1  450.19  4834.4  445.97  4902.1  442.29
  4920.3  438.78  4930.4  437.63  4952.5  437.31  5023.7  436.08  5024.2  435.28
  5029.2  435.28  5029.7  436.08  5040.2  437.05  5056.6  436.20  5062.2  437.22
  5080.9  437.31  5084.3  437.99  5100.8  438.12  5106.4  439.13  5139.3  440.65
  5144.9  441.72  5175.0  443.75  5181.2  445.12  5232.3  450.34  5309.4  456.01
#Mann=3,-1,0
  4651.8    0.05       0  5023.7    0.03       0  5029.7    0.05       0
Bank Sta=4952.5,5080.9
Exp/Cntr=0.3,0.1

Type RM Length L Ch R = 1,75,0,0,0
BEGIN DESCRIPTION:
UNT 105 in LFCCL Watershed 1.0
END DESCRIPTION:
XS GIS Cut Line= 3
      2827083.60      7050634.55      2827111.38      7050329.02
      2826870.10      7050049.82
#Sta/Elev= 30
  4695.7  452.23  4735.4  450.18  4745.5  449.25  4755.5  448.87  4785.6  448.86
  4805.7  447.92  4845.9  443.55  4873.9  441.68  4886.0  440.24  4946.3  437.21
  4966.7  435.74  4984.3  435.13  4989.4  434.39  4993.5  433.04  4994.0  432.24
  4999.0  432.24  4999.5  433.04  5009.5  434.33  5031.4  435.94  5080.8  436.16
  5101.6  435.28  5112.6  435.74  5158.7  438.01  5201.4  441.11  5208.0  441.89
  5222.3  442.51  5250.8  445.04  5265.1  446.93  5300.2  450.61  5371.5  456.36
#Mann=3,-1,0
  4695.7    0.05       0  4993.5    0.03       0  4999.5    0.05       0
Bank Sta=4966.7,5112.6
Exp/Cntr=0.3,0.1

Chan Stop Cuts=-1