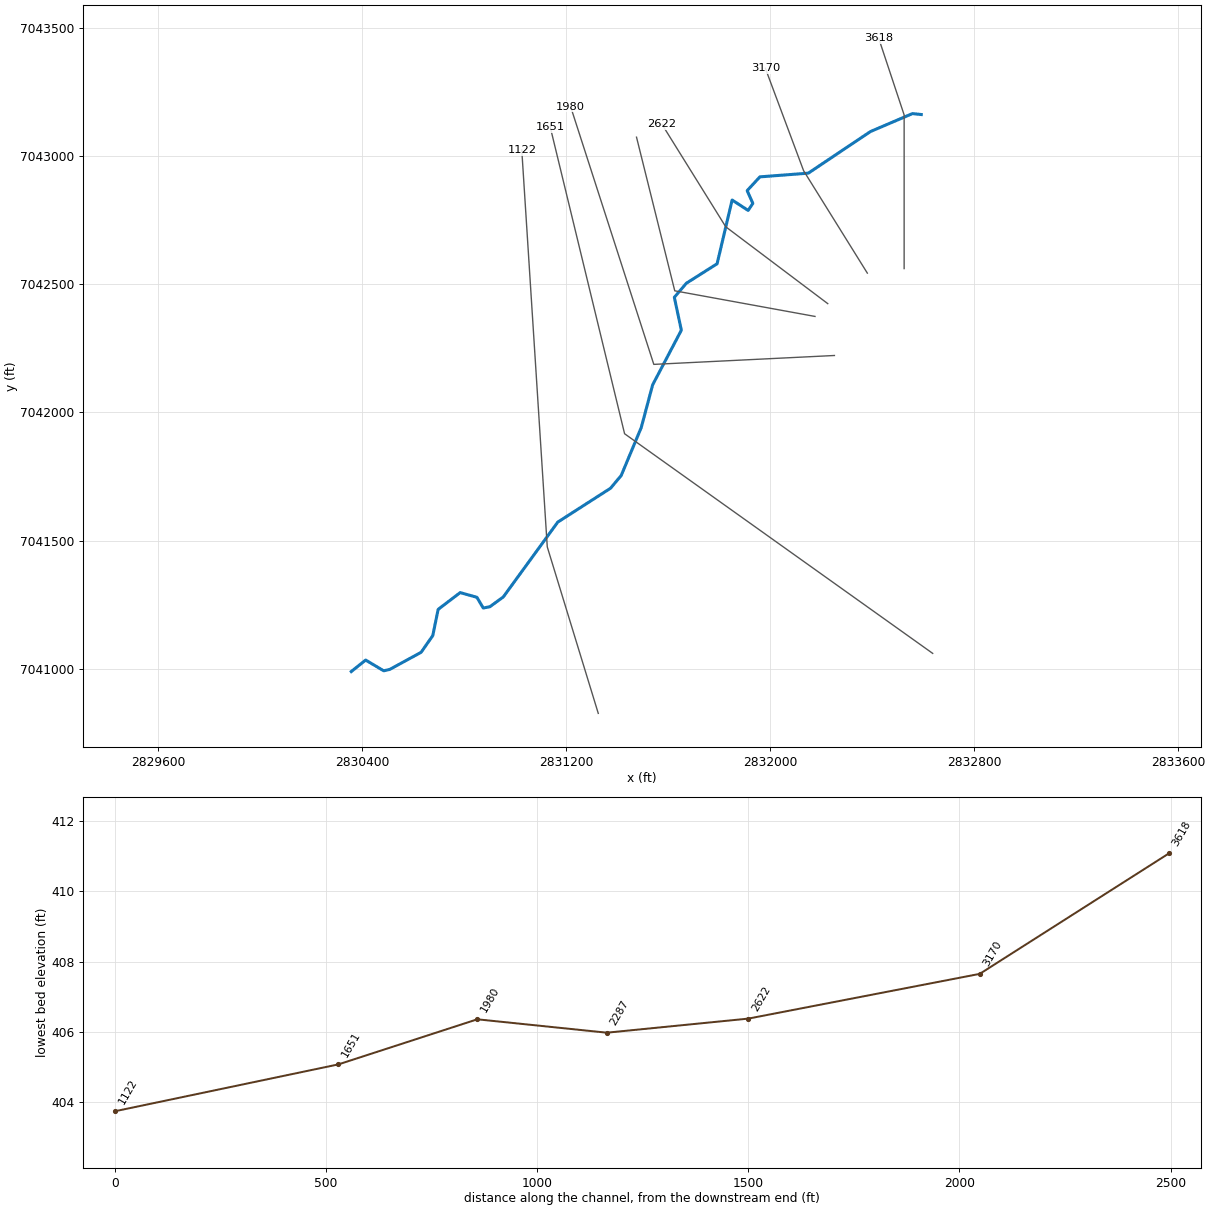
--- UNT 106 in LFCCL Watershed.prj (project) ---

Proj Title=UNT 106 in LFCCL Watershed Base Level Engineering
Current Plan=p01
Default Exp/Contr=0.3,0.1
English Units
Geom File=g01
Flow File=f01
Plan File=p01
BEGIN DESCRIPTION:
UNT 106 in LFCCL Watershed
END DESCRIPTION:

--- UNT 106 in LFCCL Watershed.p01 (plan) ---

Plan Title=Multiple Run
Short Identifier=Multiple
Geom File=g01
Flow File=f01
Subcritical Flow
K Sum by GR= 0
Std Step Tol= 0.01
Critical Tol= 0.01
Num of Std Step Trials= 20
Max Error Tol= 0.3
Flow Tol Ratio= 0.001
Split Flow NTrial= 30
Split Flow Tol= 0.02
Split Flow Ratio= 0.02
Log Output Level= 0
Friction Slope Method= 1
Unsteady Friction Slope Method= 2
Unsteady Bridges Friction Slope Method= 1
Parabolic Critical Depth
Global Vel Dist=  1 , 1 , 1
Global Log Level= 0
CheckData=True
Encroach Param= -1, 0, 0, 0
BEGIN DESCRIPTION:
Multiple Run
END DESCRIPTION:

--- UNT 106 in LFCCL Watershed.f01 (steady flow) ---

Flow Title=Multiple
Number of Profiles=7
Profile Names=10-year,25-year,50-year,1pct_min,100-year,1pct_plu,500-year
River Rch & RM= UNT 106 in LFCCL,Reach-1,3618
     424     556     661     391     781    1558    1090
River Rch & RM= UNT 106 in LFCCL,Reach-1,2622
     567     756     907     542    1081    2157    1536
Boundary for River Rch & Prof#=UNT 106 in LFCCL,Reach-1,1
Up Type=0
Dn Type=3
Dn Slope=0.005
Boundary for River Rch & Prof#=UNT 106 in LFCCL,Reach-1,2
Up Type=0
Dn Type=3
Dn Slope=0.005
Boundary for River Rch & Prof#=UNT 106 in LFCCL,Reach-1,3
Up Type=0
Dn Type=3
Dn Slope=0.005
Boundary for River Rch & Prof#=UNT 106 in LFCCL,Reach-1,4
Up Type=0
Dn Type=3
Dn Slope=0.005
Boundary for River Rch & Prof#=UNT 106 in LFCCL,Reach-1,5
Up Type=0
Dn Type=3
Dn Slope=0.005
Boundary for River Rch & Prof#=UNT 106 in LFCCL,Reach-1,6
Up Type=0
Dn Type=3
Dn Slope=0.005
Boundary for River Rch & Prof#=UNT 106 in LFCCL,Reach-1,7
Up Type=0
Dn Type=3
Dn Slope=0.005

--- UNT 106 in LFCCL Watershed.g01 (geometry) ---

Geom Title=Existing Conditions

River Reach=UNT 106 in LFCCL,Reach-1
Reach XY= 30
      2832591.78      7043163.41      2832557.27      7043167.02
      2832392.44      7043096.92      2832148.75      7042934.38
      2831958.77      7042919.96      2831908.98      7042866.24
      2831931.25      7042816.45      2831912.91      7042788.94
      2831850.02      7042829.56      2831791.05      7042580.61
      2831670.51      7042504.61      2831623.34      7042449.58
      2831650.86      7042321.18      2831538.18      7042107.61
      2831493.63      7041941.21      2831415.01      7041753.84
      2831373.08      7041704.05      2831166.06      7041571.72
      2830952.49      7041279.53      2830900.08      7041241.53
      2830873.88      7041236.29      2830848.98      7041278.22
      2830783.47      7041296.56      2830696.99      7041231.05
      2830676.03      7041128.85      2830630.17      7041063.34
      2830507.01      7040996.52      2830483.42      7040991.27
      2830412.67      7041033.20      2830356.22      7040988.31

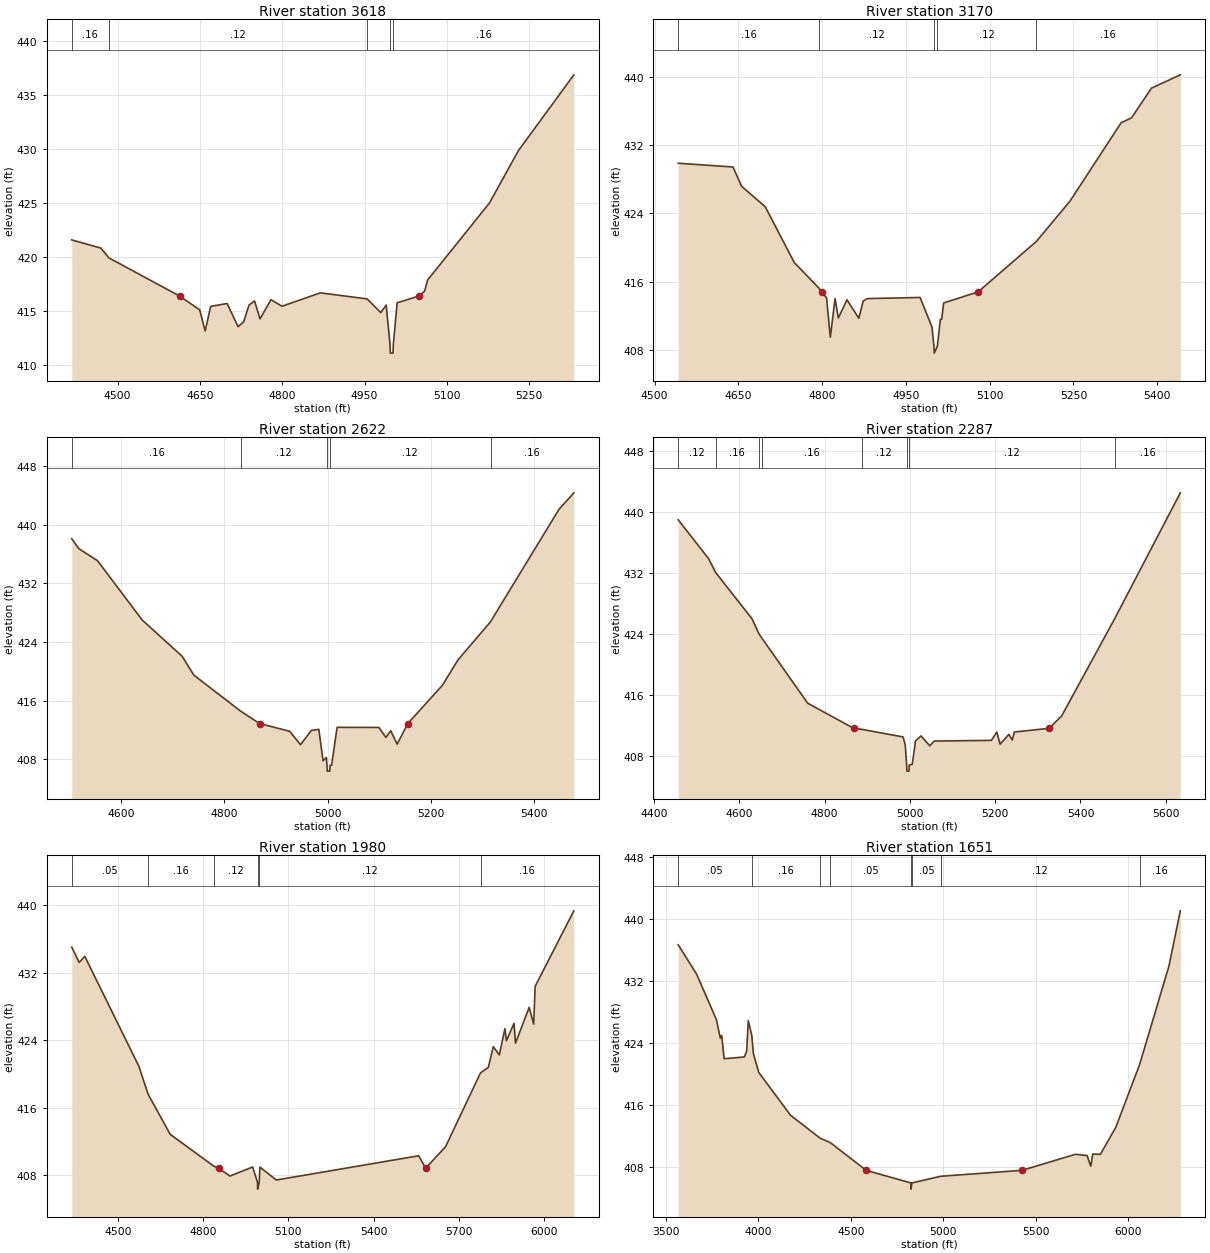
Type RM Length L Ch R = 1,3618,448,448,448
BEGIN DESCRIPTION:
UNT 106 in LFCCL Watershed 5.0
END DESCRIPTION:
XS GIS Cut Line= 3
      2832524.65      7042561.80      2832524.65      7043161.81
      2832424.95      7043460.92
#Sta/Elev= 30
  4416.3  421.55  4469.5  420.79  4483.9  419.89  4612.7  416.36  4649.5  415.08
  4659.5  413.12  4669.5  415.40  4699.5  415.66  4719.5  413.52  4729.5  413.96
  4739.5  415.52  4749.5  415.90  4759.5  414.24  4779.5  416.02  4799.5  415.41
  4869.5  416.65  4954.7  416.09  4979.5  414.83  4989.5  415.52  4996.5  411.87
  4997.0  411.07  5002.0  411.07  5002.5  411.87  5009.5  415.73  5049.3  416.36
  5059.6  416.81  5064.9  417.83  5177.8  424.97  5230.5  429.81  5331.6  436.83
#Mann=5,-1,0
  4416.3    0.16       0  4483.9    0.12       0  4954.7    0.16       0
  4996.5    0.07       0  5002.5    0.16       0
Bank Sta=4612.7,5049.3
Exp/Cntr=0.3,0.1

Type RM Length L Ch R = 1,3170,548,548,548
BEGIN DESCRIPTION:
UNT 106 in LFCCL Watershed 4.0
END DESCRIPTION:
XS GIS Cut Line= 3
      2832380.27      7042544.13      2832130.25      7042944.17
      2831980.27      7043344.13
#Sta/Elev= 30
  4542.4  429.86  4640.5  429.42  4655.8  427.17  4698.2  424.77  4750.1  418.25
  4794.2  415.26  4799.0  414.81  4807.9  414.13  4814.7  409.52  4823.2  414.03
  4829.1  411.76  4844.5  413.89  4865.7  411.73  4873.6  413.75  4881.0  414.03
  4975.4  414.16  4996.6  410.72  5000.3  408.45  5000.8  407.65  5006.3  408.45
  5011.7  411.61  5014.1  411.61  5017.6  413.52  5079.2  414.81  5183.6  420.71
  5243.7  425.42  5335.4  434.60  5354.0  435.17  5389.6  438.64  5441.3  440.20
#Mann=5,-1,0
  4542.4    0.16       0  4794.2    0.12       0  5000.3    0.07       0
  5006.3    0.12       0  5183.6    0.16       0
Bank Sta=4799,5079.2
Exp/Cntr=0.3,0.1

Type RM Length L Ch R = 1,2622,335,335,335
BEGIN DESCRIPTION:
UNT 106 in LFCCL Watershed 3.0
END DESCRIPTION:
XS GIS Cut Line= 3
      2832224.98      7042425.01      2831825.00      7042725.00
      2831574.99      7043125.02
#Sta/Elev= 30
  4504.7  438.07  4518.2  436.73  4554.7  435.06  4641.1  426.98  4718.2  422.05
  4741.1  419.46  4832.6  414.51  4868.2  412.87  4926.6  411.81  4947.4  409.98
  4968.2  411.92  4982.8  412.08  4991.1  407.79  4997.4  408.24  4998.6  407.18
  4999.1  406.38  5004.1  406.38  5004.6  407.18  5007.6  407.18  5018.2  412.35
  5099.0  412.34  5112.6  410.98  5122.0  411.88  5134.4  410.06  5155.1  412.87
  5222.2  418.10  5252.3  421.56  5315.1  426.74  5447.5  442.07  5476.4  444.33
#Mann=5,-1,0
  4504.7    0.16       0  4832.6    0.12       0  4998.6    0.07       0
  5004.6    0.12       0  5315.1    0.16       0
Bank Sta=4868.2,5155.1
Exp/Cntr=0.3,0.1

Type RM Length L Ch R = 1,2287,307,307,307
BEGIN DESCRIPTION:
UNT 106 in LFCCL Watershed 2.0
END DESCRIPTION:
XS GIS Cut Line= 3
      2832175.05      7042374.99      2831625.00      7042475.00
      2831475.01      7043074.97
#Sta/Elev= 30
  4456.6  438.99  4527.8  433.89  4544.6  432.05  4629.4  426.02  4645.7  424.04
  4653.1  423.42  4760.3  414.90  4868.2  411.60  4887.1  411.47  4983.9  410.47
  4989.0  409.44  4992.3  406.78  4992.8  405.98  4997.8  405.98  4998.3  406.78
  5005.5  406.88  5013.1  409.95  5026.0  410.60  5046.6  409.31  5056.9  409.93
  5190.9  410.02  5203.8  411.11  5211.5  409.52  5232.1  410.81  5239.9  410.06
  5245.0  411.12  5326.4  411.60  5355.8  413.23  5479.9  425.97  5634.1  442.54
#Mann=8,-1,0
  4456.6    0.12       0  4544.6    0.16       0  4645.7    0.05       0
  4653.1    0.16       0  4887.1    0.12       0  4992.3    0.07       0
  4998.3    0.12       0  5479.9    0.16       0
Bank Sta=4868.2,5326.4
Exp/Cntr=0.3,0.1

Type RM Length L Ch R = 1,1980,329,329,329
BEGIN DESCRIPTION:
Mapping XS 8d865ec1
END DESCRIPTION:
XS GIS Cut Line= 3
      2832251.17      7042222.45      2831542.82      7042187.73
      2831216.44      7043194.65
#Sta/Elev= 30
  4337.5  435.01  4363.7  433.19  4383.2  433.93  4574.0  420.89  4606.1  417.61
  4684.1  412.85  4837.9  409.07  4854.4  408.84  4894.3  407.91  4974.4  408.98
  4991.5  407.16  4992.0  406.36  4997.5  407.16  4999.9  408.97  5057.7  407.44
  5558.9  410.31  5583.4  408.84  5653.5  411.38  5776.7  420.13  5803.9  420.76
  5821.7  423.23  5842.8  422.25  5862.6  425.36  5867.8  423.94  5894.6  425.98
  5899.8  423.65  5947.9  427.88  5963.8  425.90  5969.0  430.37  6105.2  439.31
#Mann=6,-1,0
  4337.5    0.05       0  4606.1    0.16       0  4837.9    0.12       0
  4991.5    0.07       0  4997.5    0.12       0  5776.7    0.16       0
Bank Sta=4854.4,5583.4
Exp/Cntr=0.3,0.1

Type RM Length L Ch R = 1,1651,529,529,529
BEGIN DESCRIPTION:
Mapping XS 2977f0db
END DESCRIPTION:
XS GIS Cut Line= 3
      2832636.59      7041059.24      2831428.23      7041916.90
      2831136.57      7043114.82
#Sta/Elev= 30
  3566.4  436.65  3665.8  432.86  3772.9  426.97  3793.8  424.59  3801.3  424.95
  3814.7  421.93  3924.0  422.16  3936.4  422.91  3945.1  426.84  3963.9  424.96
  3973.0  422.57  4001.7  420.16  4173.9  414.62  4334.5  411.65  4388.5  411.09
  4582.6  407.51  4824.1  405.88  4824.6  405.08  4830.1  405.88  4985.5  406.74
  5426.0  407.51  5713.6  409.58  5777.0  409.42  5797.0  408.05  5807.9  409.61
  5849.0  409.58  5932.5  413.08  6061.1  421.18  6219.4  433.88  6281.1  441.04
#Mann=8,-1,0
  3566.4    0.05       0  3963.9    0.16       0  4334.5    0.12       0
  4388.5    0.05       0  4824.1    0.07       0  4830.1    0.05       0
  4985.5    0.12       0  6061.1    0.16       0
Bank Sta=4582.6,5426
Exp/Cntr=0.3,0.1

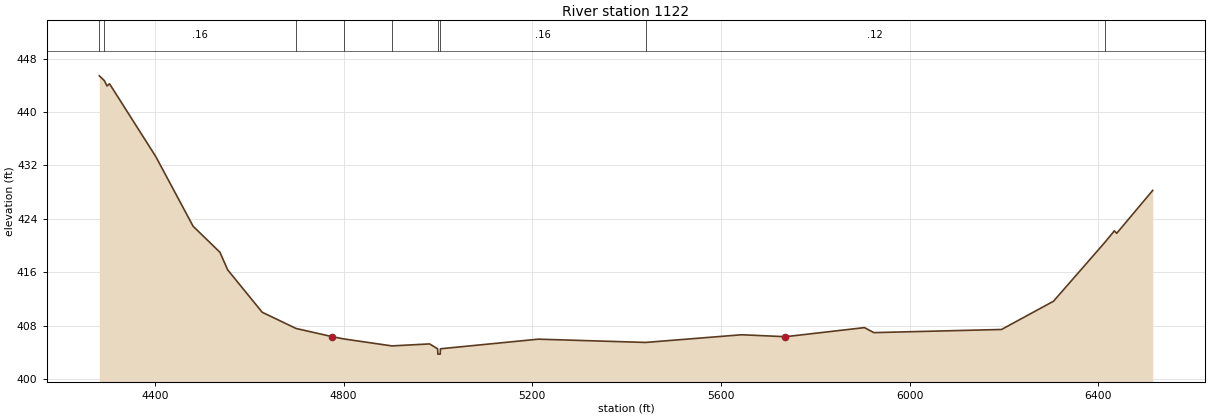
Type RM Length L Ch R = 1,1122,0,0,0
BEGIN DESCRIPTION:
UNT 106 in LFCCL Watershed 1.0
END DESCRIPTION:
XS GIS Cut Line= 3
      2831325.01      7040824.96      2831125.00      7041475.00
      2831025.00      7043024.96
#Sta/Elev= 30
  4282.0  445.42  4292.6  444.70  4298.4  443.90  4303.6  444.23  4401.7  433.33
  4480.8  422.90  4537.7  419.00  4554.1  416.37  4627.3  410.02  4699.1  407.59
  4776.1  406.36  4800.7  406.02  4902.3  404.98  4982.2  405.28  4999.2  404.55
  4999.7  403.75  5004.7  403.75  5005.2  404.55  5212.6  405.99  5440.2  405.50
  5643.5  406.65  5736.7  406.36  5904.1  407.72  5924.1  406.97  6194.7  407.44
  6304.9  411.67  6414.1  420.51  6433.9  422.21  6438.9  421.84  6515.3  428.27
#Mann=9,-1,0
  4282.0    0.05       0  4292.6    0.16       0  4699.1    0.12       0
  4800.7    0.07       0  4902.3    0.16       0  4999.2    0.07       0
  5005.2    0.16       0  5440.2    0.12       0  6414.1    0.16       0
Bank Sta=4776.1,5736.7
Exp/Cntr=0.3,0.1

Chan Stop Cuts=-1