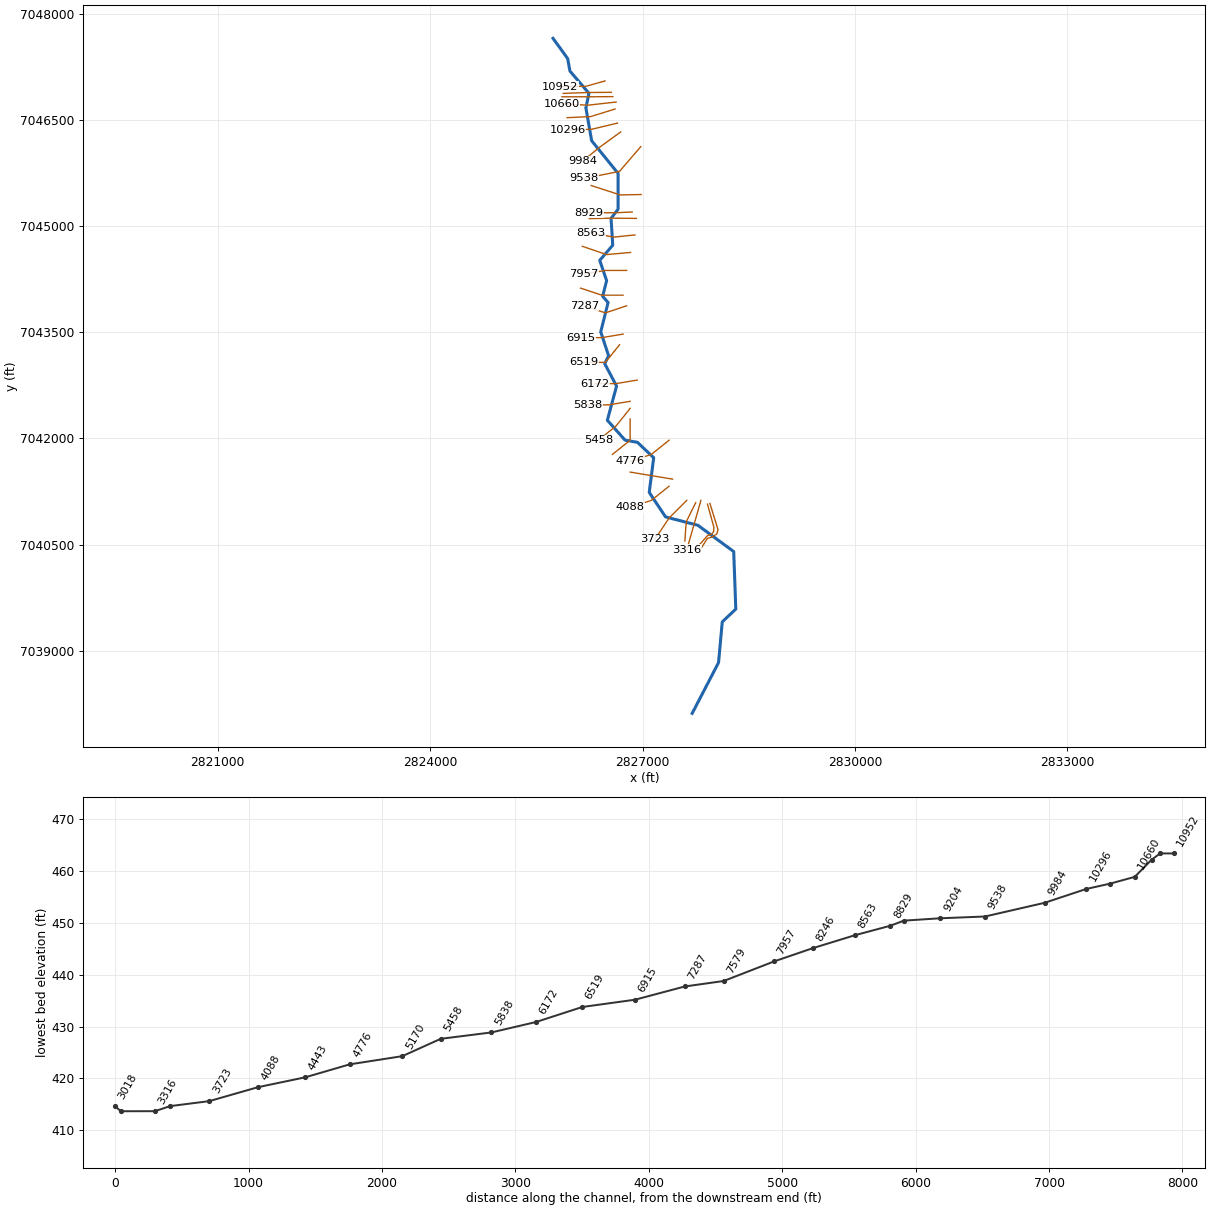
--- UNT 107 in LFCCL Watershed.prj (project) ---

Proj Title=UNT 107 in LFCCL Watershed Base Level Engineering
Current Plan=p01
Default Exp/Contr=0.3,0.1
English Units
Geom File=g01
Flow File=f01
Plan File=p01
BEGIN DESCRIPTION:
UNT 107 in LFCCL Watershed
END DESCRIPTION:

--- UNT 107 in LFCCL Watershed.p01 (plan) ---

Plan Title=Multiple Run
Short Identifier=Multiple
Geom File=g01
Flow File=f01
Subcritical Flow
K Sum by GR= 0
Std Step Tol= 0.01
Critical Tol= 0.01
Num of Std Step Trials= 20
Max Error Tol= 0.3
Flow Tol Ratio= 0.001
Split Flow NTrial= 30
Split Flow Tol= 0.02
Split Flow Ratio= 0.02
Log Output Level= 0
Friction Slope Method= 1
Unsteady Friction Slope Method= 2
Unsteady Bridges Friction Slope Method= 1
Parabolic Critical Depth
Global Vel Dist=  1 , 1 , 1
Global Log Level= 0
CheckData=True
Encroach Param= -1, 0, 0, 0
BEGIN DESCRIPTION:
Multiple Run
END DESCRIPTION:

--- UNT 107 in LFCCL Watershed.f01 (steady flow) ---

Flow Title=Multiple
Number of Profiles=7
Profile Names=10-year,25-year,50-year,1pct_min,100-year,1pct_plu,500-year
River Rch & RM= UNT 107 in LFCCL,Reach-1,10952
     255     322     374     216     431     860     573
River Rch & RM= UNT 107 in LFCCL,Reach-1,5458
     385     500     589     346     691    1378     949
Boundary for River Rch & Prof#=UNT 107 in LFCCL,Reach-1,1
Up Type=0
Dn Type=3
Dn Slope=0.005
Boundary for River Rch & Prof#=UNT 107 in LFCCL,Reach-1,2
Up Type=0
Dn Type=3
Dn Slope=0.005
Boundary for River Rch & Prof#=UNT 107 in LFCCL,Reach-1,3
Up Type=0
Dn Type=3
Dn Slope=0.005
Boundary for River Rch & Prof#=UNT 107 in LFCCL,Reach-1,4
Up Type=0
Dn Type=3
Dn Slope=0.005
Boundary for River Rch & Prof#=UNT 107 in LFCCL,Reach-1,5
Up Type=0
Dn Type=3
Dn Slope=0.005
Boundary for River Rch & Prof#=UNT 107 in LFCCL,Reach-1,6
Up Type=0
Dn Type=3
Dn Slope=0.005
Boundary for River Rch & Prof#=UNT 107 in LFCCL,Reach-1,7
Up Type=0
Dn Type=3
Dn Slope=0.005

--- UNT 107 in LFCCL Watershed.g01 (geometry) ---

Geom Title=Existing Conditions

River Reach=UNT 107 in LFCCL,Reach-1
Reach XY= 30
      2825735.59      7047655.71      2825942.37      7047369.38
      2825973.70      7047194.11      2826242.28      7046879.05
      2826199.84      7046671.27      2826280.97      7046208.26
      2826655.18      7045745.75      2826654.53      7045241.15
      2826555.42      7045110.67      2826578.87      7044731.34
      2826395.23      7044517.31      2826492.75      7044230.61
      2826436.48      7044010.36      2826513.16      7043920.84
      2826409.26      7043507.20      2826520.68      7043169.66
      2826465.80      7043056.11      2826633.13      7042740.60
      2826502.75      7042257.29      2826753.13      7041975.65
      2826928.12      7041945.16      2827157.45      7041727.19
      2827094.38      7041237.45      2827325.51      7040890.75
      2827782.22      7040772.26      2828287.84      7040401.18
      2828317.26      7039588.03      2828126.05      7039407.33
      2828073.52      7038831.61      2827701.07      7038113.86

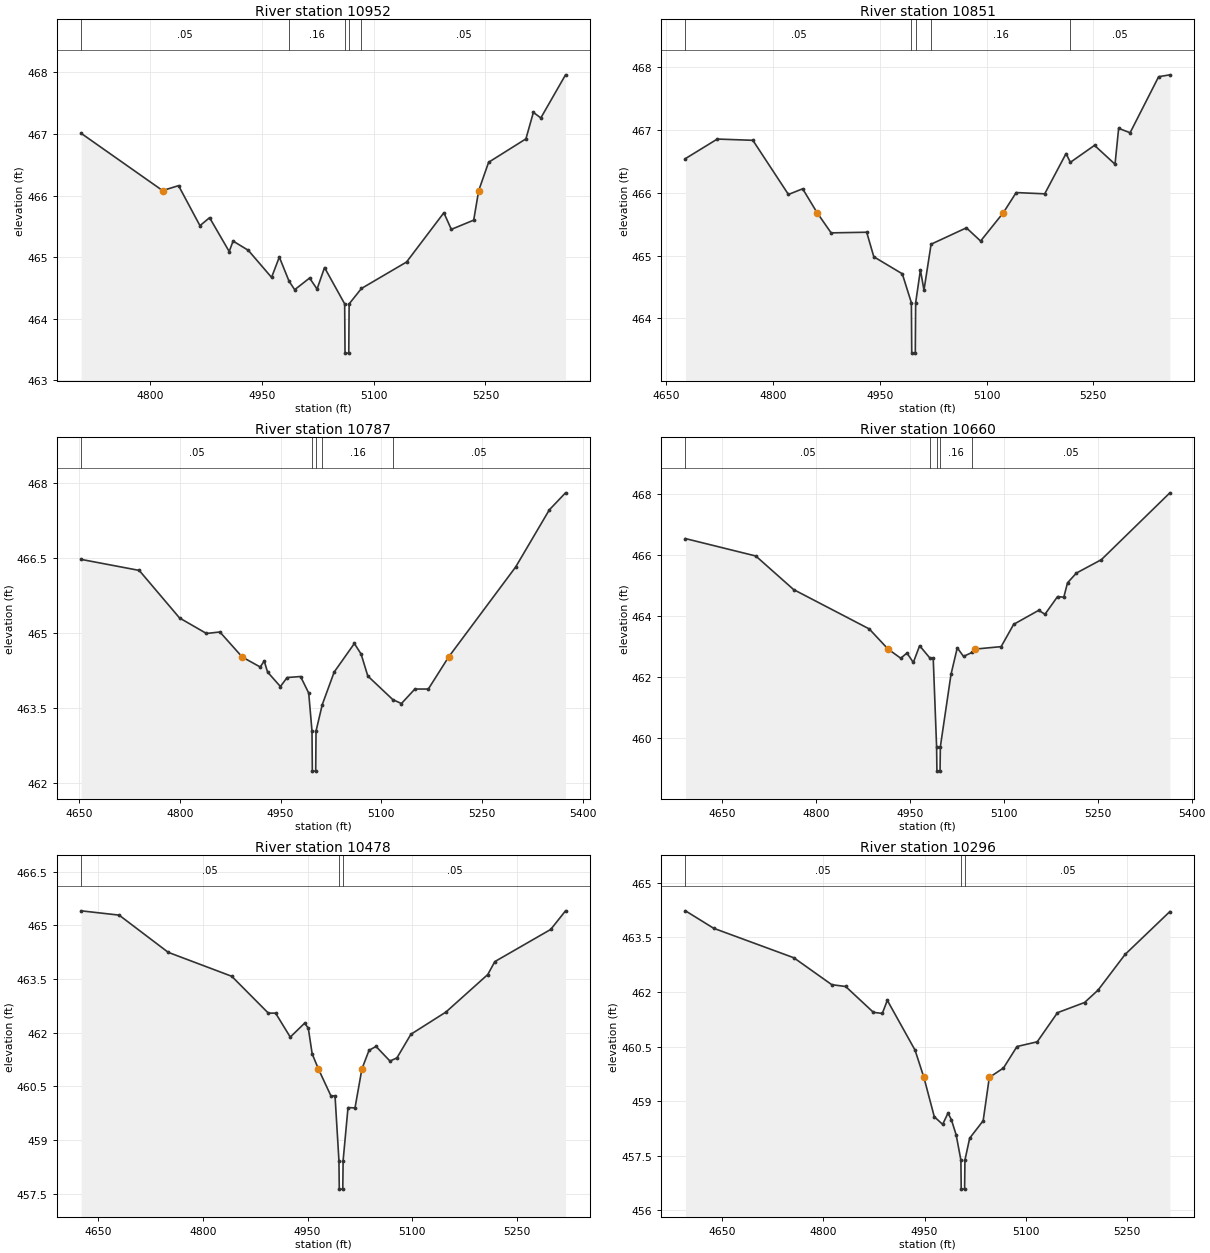
Type RM Length L Ch R = 1,10952,101,101,101
BEGIN DESCRIPTION:
UNT 107 in LFCCL Watershed 23.0
END DESCRIPTION:
XS GIS Cut Line= 3
      2826470.73      7047053.96      2826199.93      7046977.58
      2825831.91      7046974.11
#Sta/Elev= 30
  4707.9  467.01  4817.1  466.08  4838.5  466.16  4867.2  465.51  4880.1  465.64
  4906.4  465.09  4911.6  465.26  4932.0  465.11  4963.2  464.67  4973.6  465.00
  4986.6  464.61  4994.2  464.47  5014.2  464.66  5024.2  464.48  5034.2  464.83
  5061.2  464.24  5061.7  463.44  5066.7  463.44  5067.2  464.24  5083.7  464.49
  5144.2  464.92  5194.2  465.72  5204.2  465.45  5234.2  465.60  5240.9  466.08
  5254.2  466.54  5304.2  466.92  5314.2  467.35  5324.2  467.26  5357.3  467.96
#Mann=5,-1,0
  4707.9    0.05       0  4986.6    0.16       0  5061.2    0.07       0
  5067.2    0.16       0  5083.7    0.05       0
Bank Sta=4817.1,5240.9
Exp/Cntr=0.3,0.1

Type RM Length L Ch R = 1,10851,64,64,64
BEGIN DESCRIPTION:
XS3709A
END DESCRIPTION:
XS GIS Cut Line= 3
      2826559.73      7046892.52      2826238.56      7046890.35
      2825879.17      7046877.36
#Sta/Elev= 30
  4676.8  466.54  4721.5  466.85  4771.5  466.83  4821.5  465.97  4841.5  466.06
  4861.8  465.68  4881.5  465.36  4931.5  465.37  4941.5  464.98  4981.5  464.71
  4994.3  464.25  4994.8  463.45  4999.8  463.45  5000.3  464.25  5007.0  464.77
  5012.0  464.45  5022.0  465.18  5071.6  465.44  5091.6  465.23  5123.5  465.68
  5141.6  466.00  5181.7  465.98  5211.7  466.62  5217.7  466.48  5251.7  466.75
  5280.5  466.45  5285.6  467.02  5301.7  466.95  5341.8  467.84  5357.6  467.87
#Mann=5,-1,0
  4676.8    0.05       0  4994.3    0.03       0  5000.3    0.05       0
  5022.0    0.16       0  5217.7    0.05       0
Bank Sta=4861.8,5123.5
Exp/Cntr=0.3,0.1

Type RM Length L Ch R = 1,10787,127,127,127
BEGIN DESCRIPTION:
XS3710A
END DESCRIPTION:
XS GIS Cut Line= 3
      2826581.41      7046831.75      2826242.90      7046829.58
      2825860.92      7046829.58
#Sta/Elev= 30
  4653.4  466.47  4739.8  466.25  4799.8  465.30  4839.8  464.99  4859.8  465.02
  4893.0  464.52  4919.8  464.32  4925.7  464.44  4930.7  464.22  4949.8  463.93
  4959.8  464.11  4979.8  464.13  4991.9  463.80  4996.8  463.04  4997.3  462.24
  5002.3  462.24  5002.8  463.04  5012.1  463.57  5029.8  464.22  5059.8  464.79
  5069.8  464.58  5079.8  464.14  5116.9  463.67  5129.8  463.59  5149.8  463.88
  5169.8  463.88  5200.0  464.52  5299.8  466.32  5349.8  467.46  5373.9  467.80
#Mann=5,-1,0
  4653.4    0.05       0  4996.8    0.03       0  5002.8    0.05       0
  5012.1    0.16       0  5116.9    0.05       0
Bank Sta=4893,5200
Exp/Cntr=0.3,0.1

Type RM Length L Ch R = 1,10660,182,182,182
BEGIN DESCRIPTION:
XS3711A
END DESCRIPTION:
XS GIS Cut Line= 3
      2826626.61      7046755.37      2826233.35      7046711.09
      2825855.72      7046726.72
#Sta/Elev= 30
  4591.5  466.54  4703.8  465.97  4764.2  464.87  4885.0  463.58  4915.1  462.92
  4935.3  462.62  4945.3  462.79  4955.4  462.48  4965.5  463.03  4981.7  462.63
  4987.2  462.62  4992.6  459.72  4993.1  458.92  4998.1  458.92  4998.6  459.72
  5015.6  462.09  5025.6  462.96  5035.6  462.68  5049.3  462.81  5054.7  462.92
  5095.7  463.00  5115.7  463.73  5155.7  464.19  5165.7  464.06  5185.8  464.64
  5195.8  464.62  5201.7  465.09  5215.8  465.41  5255.8  465.85  5365.2  468.04
#Mann=5,-1,0
  4591.5    0.05       0  4981.7    0.16       0  4992.6    0.07       0
  4998.6    0.16       0  5049.3    0.05       0
Bank Sta=4915.1,5054.7
Exp/Cntr=0.3,0.1

Type RM Length L Ch R = 1,10478,182,182,182
BEGIN DESCRIPTION:
XS3712A
END DESCRIPTION:
XS GIS Cut Line= 3
      2826610.99      7046656.42      2826267.20      7046549.63
      2825933.86      7046534.01
#Sta/Elev= 30
  4625.7  465.41  4680.1  465.29  4750.4  464.25  4841.4  463.58  4893.8  462.55
  4904.2  462.55  4925.2  461.88  4945.8  462.27  4951.0  462.13  4956.6  461.41
  4965.5  460.99  4983.6  460.23  4989.3  460.24  4994.9  458.43  4995.4  457.63
  5000.4  457.63  5000.9  458.43  5007.9  459.91  5017.9  459.90  5027.8  460.99
  5038.0  461.51  5048.0  461.62  5068.0  461.21  5078.0  461.30  5098.0  461.96
  5148.1  462.58  5208.1  463.63  5218.1  463.99  5298.2  464.89  5319.4  465.41
#Mann=3,-1,0
  4625.7    0.05       0  4994.9    0.03       0  5000.9    0.05       0
Bank Sta=4965.5,5027.8
Exp/Cntr=0.3,0.1

Type RM Length L Ch R = 1,10296,312,312,312
BEGIN DESCRIPTION:
XS3713A
END DESCRIPTION:
XS GIS Cut Line= 3
      2826645.69      7046457.62      2826284.57      7046370.81
      2825938.65      7046356.98
#Sta/Elev= 30
  4595.9  464.23  4637.7  463.75  4756.4  462.94  4812.6  462.20  4833.2  462.15
  4874.3  461.44  4887.5  461.41  4894.9  461.77  4936.0  460.40  4949.1  459.65
  4964.5  458.57  4976.9  458.36  4984.8  458.67  4989.8  458.49  4996.9  458.07
  5003.9  457.38  5004.4  456.58  5009.4  456.58  5009.9  457.38  5016.9  457.98
  5036.9  458.46  5046.0  459.65  5067.0  459.91  5087.0  460.50  5117.0  460.63
  5147.0  461.43  5187.1  461.71  5207.1  462.05  5247.1  463.03  5313.5  464.21
#Mann=3,-1,0
  4595.9    0.05       0  5003.9    0.03       0  5009.9    0.05       0
Bank Sta=4949.1,5046
Exp/Cntr=0.3,0.1

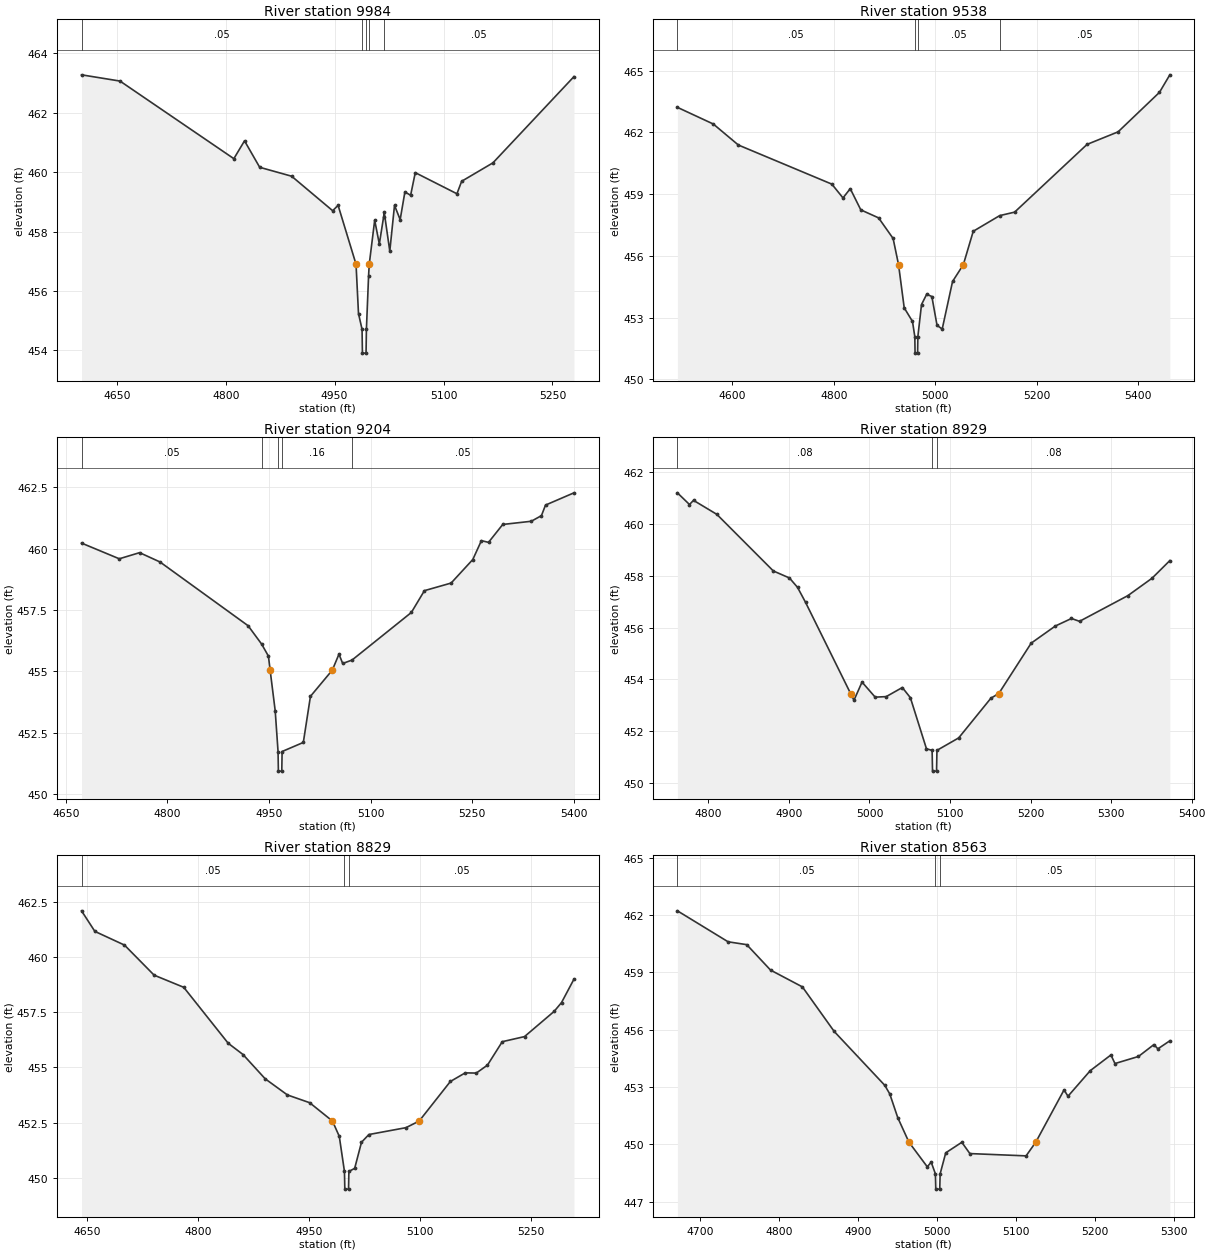
Type RM Length L Ch R = 1,9984,446,446,446
BEGIN DESCRIPTION:
XS3714A
END DESCRIPTION:
XS GIS Cut Line= 3
      2826690.82      7046332.62      2826385.26      7046110.40
      2826153.01      7045919.74
#Sta/Elev= 30
  4601.4  463.27  4654.4  463.06  4811.2  460.45  4825.9  461.05  4846.8  460.16
  4890.8  459.86  4947.3  458.70  4954.8  458.88  4979.5  456.90  4982.9  455.24
  4987.8  454.71  4988.3  453.91  4993.3  453.91  4993.8  454.71  4996.8  456.52
  4997.7  456.90  5005.2  458.38  5011.6  457.58  5017.4  458.48  5018.4  458.64
  5026.0  457.34  5032.5  458.88  5040.3  458.40  5046.8  459.33  5054.7  459.22
  5061.1  459.98  5118.5  459.27  5125.0  459.69  5168.1  460.31  5279.7  463.21
#Mann=5,-1,0
  4601.4    0.05       0  4987.8    0.07       0  4993.8    0.05       0
  4996.8    0.16       0  5017.4    0.05       0
Bank Sta=4979.5,4997.7
Exp/Cntr=0.3,0.1

Type RM Length L Ch R = 1,9538,334,334,334
BEGIN DESCRIPTION:
UNT 107 in LFCCL Watershed 22.0
END DESCRIPTION:
XS GIS Cut Line= 3
      2826974.98      7046124.98      2826675.00      7045775.00
      2826174.95      7045674.99
#Sta/Elev= 30
  4491.6  463.21  4562.4  462.40  4611.8  461.38  4796.1  459.48  4818.1  458.81
  4832.4  459.26  4853.2  458.23  4888.3  457.84  4916.9  456.84  4927.6  455.57
  4938.8  453.47  4955.1  452.81  4959.7  452.07  4960.2  451.27  4965.2  451.27
  4965.7  452.07  4972.9  453.63  4983.1  454.13  4993.3  454.02  5003.5  452.62
  5013.7  452.44  5034.1  454.75  5055.4  455.57  5074.9  457.19  5127.0  457.95
  5156.5  458.12  5299.3  461.41  5360.5  462.02  5442.1  463.94  5462.5  464.79
#Mann=4,-1,0
  4491.6    0.05       0  4959.7    0.07       0  4965.7    0.05       0
  5127.0    0.05       0
Bank Sta=4927.6,5055.4
Exp/Cntr=0.3,0.1

Type RM Length L Ch R = 1,9204,275,275,275
BEGIN DESCRIPTION:
UNT 107 in LFCCL Watershed 21.0
END DESCRIPTION:
XS GIS Cut Line= 3
      2826980.73      7045447.90      2826685.47      7045442.21
      2826275.03      7045574.99
#Sta/Elev= 30
  4673.3  460.23  4729.0  459.59  4759.0  459.84  4789.1  459.46  4919.1  456.86
  4939.1  456.11  4949.1  455.62  4951.6  455.05  4959.1  453.39  4963.3  451.73
  4963.8  450.93  4968.8  450.93  4969.3  451.73  5000.6  452.10  5011.1  453.98
  5043.4  455.05  5053.2  455.70  5058.7  455.32  5072.5  455.46  5160.0  457.40
  5179.3  458.29  5218.7  458.60  5250.7  459.56  5263.4  460.33  5273.9  460.26
  5294.9  460.99  5337.0  461.12  5352.0  461.35  5358.0  461.78  5400.0  462.28
#Mann=5,-1,0
  4673.3    0.05       0  4939.1    0.16       0  4963.3    0.07       0
  4969.3    0.16       0  5072.5    0.05       0
Bank Sta=4951.6,5043.4
Exp/Cntr=0.3,0.1

Type RM Length L Ch R = 1,8929,100,100,100
BEGIN DESCRIPTION:
XS3715A
END DESCRIPTION:
XS GIS Cut Line= 3
      2826854.00      7045200.67      2826607.48      7045190.26
      2826242.92      7045190.26
#Sta/Elev= 30
  4761.6  461.19  4776.6  460.74  4781.6  460.90  4810.6  460.36  4880.7  458.18
  4900.7  457.91  4910.7  457.55  4920.7  456.97  4976.6  453.46  4980.8  453.20
  4990.8  453.90  5007.1  453.32  5020.8  453.34  5040.8  453.69  5050.8  453.30
  5070.8  451.33  5077.8  451.27  5078.3  450.47  5083.3  450.47  5083.8  451.27
  5110.8  451.75  5150.8  453.28  5160.6  453.46  5200.8  455.40  5230.8  456.06
  5250.8  456.35  5260.8  456.24  5320.8  457.23  5350.8  457.90  5372.9  458.58
#Mann=3,-1,0
  4761.6    0.08       0  5077.8    0.07       0  5083.8    0.08       0
Bank Sta=4976.6,5160.6
Exp/Cntr=0.3,0.1

Type RM Length L Ch R = 1,8829,266,266,266
BEGIN DESCRIPTION:
XS3716A
END DESCRIPTION:
XS GIS Cut Line= 3
      2826912.99      7045110.40      2826548.45      7045113.87
      2826248.19      7045106.97
#Sta/Elev= 30
  4642.7  462.08  4660.7  461.15  4700.7  460.53  4740.7  459.17  4780.7  458.62
  4840.7  456.09  4860.7  455.58  4890.7  454.48  4920.7  453.75  4950.7  453.40
  4981.5  452.57  4990.7  451.88  4997.7  450.29  4998.2  449.49  5003.2  449.49
  5003.7  450.29  5011.5  450.43  5020.7  451.61  5030.7  451.96  5080.7  452.27
  5098.6  452.57  5140.7  454.36  5160.8  454.75  5175.7  454.74  5190.8  455.10
  5210.8  456.16  5240.8  456.39  5280.8  457.53  5290.8  457.93  5307.6  458.99
#Mann=3,-1,0
  4642.7    0.05       0  4997.7    0.03       0  5003.7    0.05       0
Bank Sta=4981.5,5098.6
Exp/Cntr=0.3,0.1

Type RM Length L Ch R = 1,8563,317,317,317
BEGIN DESCRIPTION:
XS3717A
END DESCRIPTION:
XS GIS Cut Line= 3
      2826892.22      7044876.72      2826597.07      7044846.33
      2826275.90      7044902.76
#Sta/Elev= 30
  4671.7  462.22  4735.8  460.60  4759.4  460.45  4789.5  459.12  4829.8  458.24
  4870.0  455.91  4934.0  453.09  4940.3  452.64  4950.4  451.40  4964.5  450.12
  4987.7  448.83  4992.7  449.07  4998.0  448.46  4998.5  447.66  5003.5  447.66
  5004.0  448.46  5011.1  449.56  5031.4  450.11  5041.6  449.52  5112.7  449.40
  5125.0  450.12  5160.7  452.85  5165.7  452.52  5193.9  453.86  5220.0  454.68
  5225.1  454.23  5254.8  454.60  5274.3  455.22  5279.4  455.00  5294.5  455.42
#Mann=3,-1,0
  4671.7    0.05       0  4998.0    0.03       0  5004.0    0.05       0
Bank Sta=4964.5,5125
Exp/Cntr=0.3,0.1

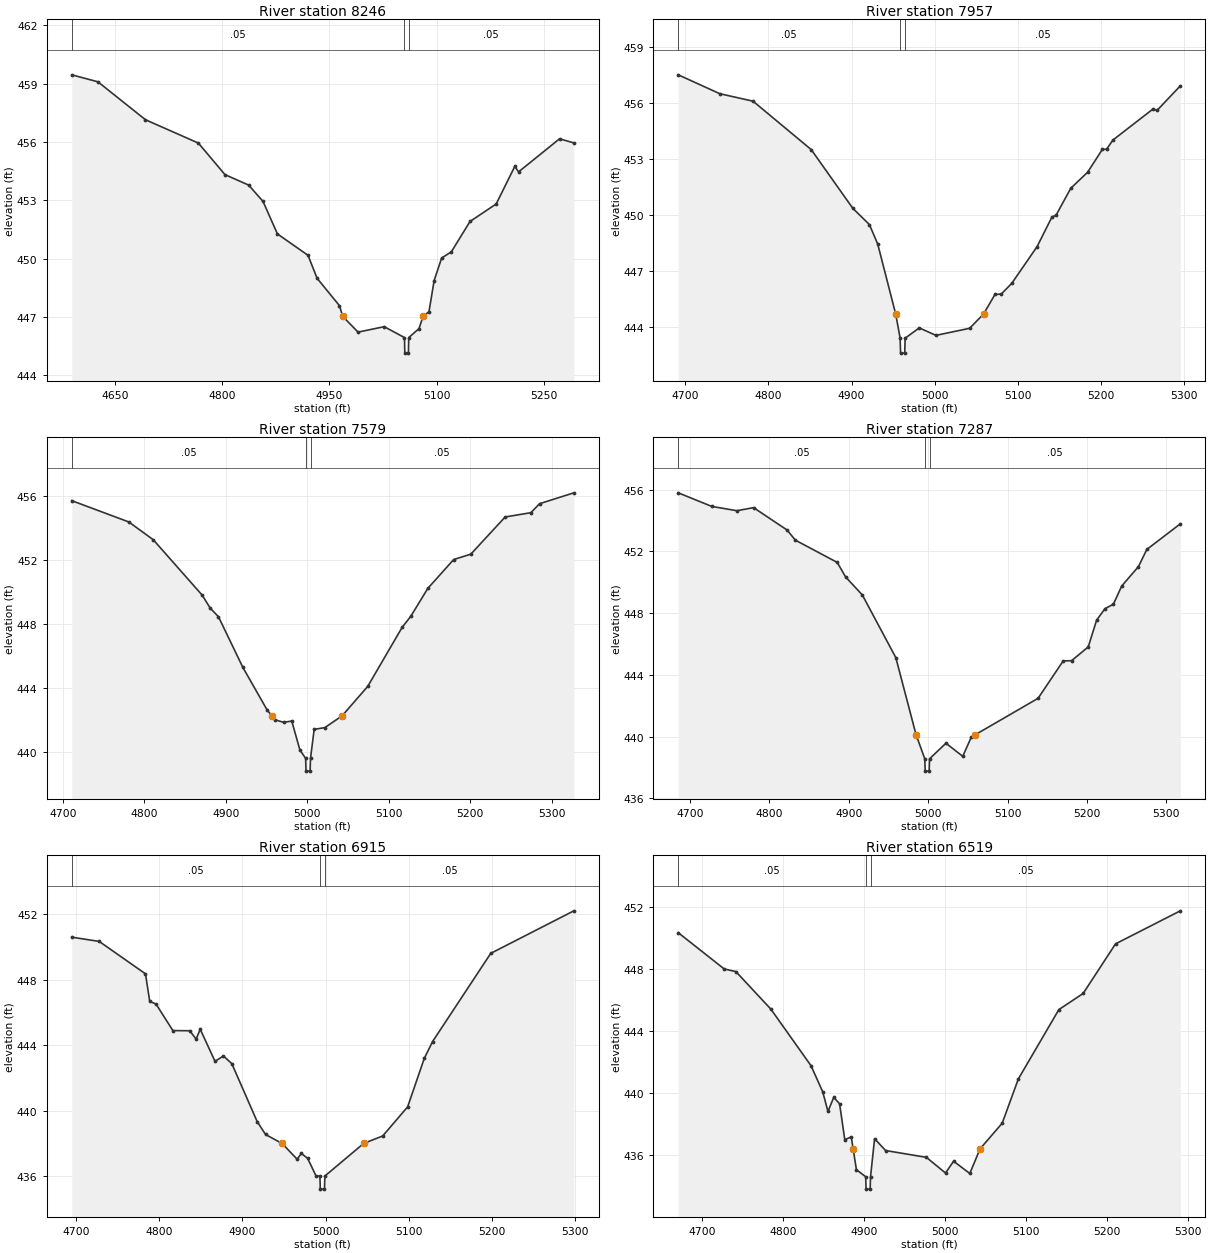
Type RM Length L Ch R = 1,8246,289,289,289
BEGIN DESCRIPTION:
XS3718A
END DESCRIPTION:
XS GIS Cut Line= 3
      2826831.43      7044629.32      2826492.90      7044598.94
      2826150.06      7044716.11
#Sta/Elev= 30
  4589.6  459.46  4626.2  459.10  4692.7  457.15  4766.7  455.95  4803.8  454.33
  4837.0  453.79  4857.1  452.95  4877.2  451.28  4920.0  450.18  4932.7  449.00
  4964.0  447.59  4968.5  447.04  4990.0  446.23  5026.6  446.51  5054.9  445.95
  5055.4  445.15  5060.4  445.15  5060.9  445.95  5075.2  446.41  5081.0  447.04
  5089.2  447.28  5096.4  448.88  5106.9  450.04  5120.5  450.36  5146.6  451.92
  5183.2  452.82  5209.2  454.75  5214.5  454.47  5271.8  456.17  5291.8  455.96
#Mann=3,-1,0
  4589.6    0.05       0  5054.9    0.03       0  5060.9    0.05       0
Bank Sta=4968.5,5081
Exp/Cntr=0.3,0.1

Type RM Length L Ch R = 1,7957,378,378,378
BEGIN DESCRIPTION:
UNT 107 in LFCCL Watershed 18.0
END DESCRIPTION:
XS GIS Cut Line= 3
      2826774.98      7044375.00      2826475.00      7044375.00
      2826175.02      7044325.00
#Sta/Elev= 30
  4691.5  457.49  4741.5  456.48  4781.5  456.08  4851.5  453.49  4901.5  450.35
  4921.5  449.48  4931.5  448.44  4953.1  444.70  4958.5  443.40  4959.0  442.60
  4964.0  442.60  4964.5  443.40  4981.5  443.95  5001.6  443.55  5042.2  443.93
  5059.0  444.70  5072.6  445.74  5080.2  445.76  5092.9  446.34  5123.3  448.30
  5141.0  449.87  5146.1  449.98  5163.8  451.42  5184.1  452.28  5201.8  453.50
  5206.9  453.51  5214.5  454.00  5262.7  455.66  5267.7  455.59  5295.6  456.90
#Mann=3,-1,0
  4691.5    0.05       0  4958.5    0.03       0  4964.5    0.05       0
Bank Sta=4953.1,5059
Exp/Cntr=0.3,0.1

Type RM Length L Ch R = 1,7579,292,292,292
BEGIN DESCRIPTION:
UNT 107 in LFCCL Watershed 17.0
END DESCRIPTION:
XS GIS Cut Line= 3
      2826725.01      7044025.00      2826425.00      7044025.00
      2826125.04      7044124.99
#Sta/Elev= 30
  4710.9  455.72  4780.9  454.39  4810.9  453.28  4870.9  449.82  4880.9  449.00
  4890.9  448.47  4920.9  445.30  4950.9  442.62  4956.6  442.28  4960.9  442.02
  4970.9  441.87  4980.9  441.95  4990.9  440.14  4997.9  439.62  4998.4  438.82
  5003.4  438.82  5003.9  439.62  5008.4  441.43  5021.5  441.54  5042.8  442.28
  5074.2  444.12  5116.3  447.80  5126.9  448.49  5147.9  450.24  5179.6  452.04
  5200.7  452.38  5242.8  454.70  5274.4  454.97  5285.0  455.53  5327.1  456.21
#Mann=3,-1,0
  4710.9    0.05       0  4997.9    0.03       0  5003.9    0.05       0
Bank Sta=4956.6,5042.8
Exp/Cntr=0.3,0.1

Type RM Length L Ch R = 1,7287,372,372,372
BEGIN DESCRIPTION:
UNT 107 in LFCCL Watershed 16.0
END DESCRIPTION:
XS GIS Cut Line= 3
      2826775.03      7043875.01      2826475.00      7043775.00
      2826174.98      7043875.01
#Sta/Elev= 30
  4685.2  455.80  4727.4  454.92  4759.0  454.64  4780.1  454.84  4822.3  453.39
  4832.8  452.73  4885.5  451.29  4896.0  450.35  4917.1  449.18  4959.3  445.12
  4984.8  440.12  4995.8  438.56  4996.3  437.76  5001.3  437.76  5001.8  438.56
  5022.5  439.57  5043.6  438.72  5054.2  439.94  5059.4  440.12  5138.5  442.48
  5170.1  444.90  5180.7  444.92  5201.7  445.81  5212.3  447.55  5222.8  448.29
  5233.4  448.58  5243.9  449.76  5265.0  451.02  5275.5  452.13  5317.7  453.79
#Mann=3,-1,0
  4685.2    0.05       0  4995.8    0.03       0  5001.8    0.05       0
Bank Sta=4984.8,5059.4
Exp/Cntr=0.3,0.1

Type RM Length L Ch R = 1,6915,396,396,396
BEGIN DESCRIPTION:
UNT 107 in LFCCL Watershed 15.0
END DESCRIPTION:
XS GIS Cut Line= 3
      2826725.02      7043475.00      2826425.00      7043425.00
      2826124.96      7043425.00
#Sta/Elev= 30
  4694.6  450.61  4727.6  450.35  4783.3  448.37  4788.4  446.69  4796.0  446.52
  4816.3  444.90  4836.6  444.89  4844.2  444.38  4849.2  444.98  4867.0  443.02
  4877.1  443.35  4887.2  442.88  4917.7  439.34  4927.8  438.55  4947.7  438.00
  4965.8  437.04  4970.9  437.39  4978.5  437.09  4988.6  436.01  4993.2  436.01
  4993.7  435.21  4998.7  435.21  4999.2  436.01  5045.8  438.00  5068.8  438.46
  5098.8  440.24  5118.8  443.20  5128.8  444.23  5198.8  449.62  5298.8  452.22
#Mann=3,-1,0
  4694.6    0.05       0  4993.2    0.03       0  4999.2    0.05       0
Bank Sta=4947.7,5045.8
Exp/Cntr=0.3,0.1

Type RM Length L Ch R = 1,6519,347,347,347
BEGIN DESCRIPTION:
UNT 107 in LFCCL Watershed 14.0
END DESCRIPTION:
XS GIS Cut Line= 3
      2826674.98      7043324.98      2826475.00      7043075.00
      2826175.03      7043075.00
#Sta/Elev= 30
  4670.6  450.34  4727.4  448.00  4741.8  447.83  4785.0  445.41  4834.6  441.76
  4849.1  440.07  4855.5  438.81  4862.7  439.72  4869.9  439.30  4876.3  436.99
  4884.3  437.17  4886.6  436.40  4890.7  435.05  4902.1  434.60  4902.6  433.80
  4907.6  433.80  4908.1  434.60  4913.1  437.05  4926.7  436.29  4977.1  435.85
  5000.7  434.84  5010.7  435.60  5030.7  434.81  5043.4  436.40  5070.7  438.05
  5090.7  440.91  5140.7  445.38  5170.7  446.42  5210.7  449.62  5290.7  451.75
#Mann=3,-1,0
  4670.6    0.05       0  4902.1    0.03       0  4908.1    0.05       0
Bank Sta=4886.6,5043.4
Exp/Cntr=0.3,0.1

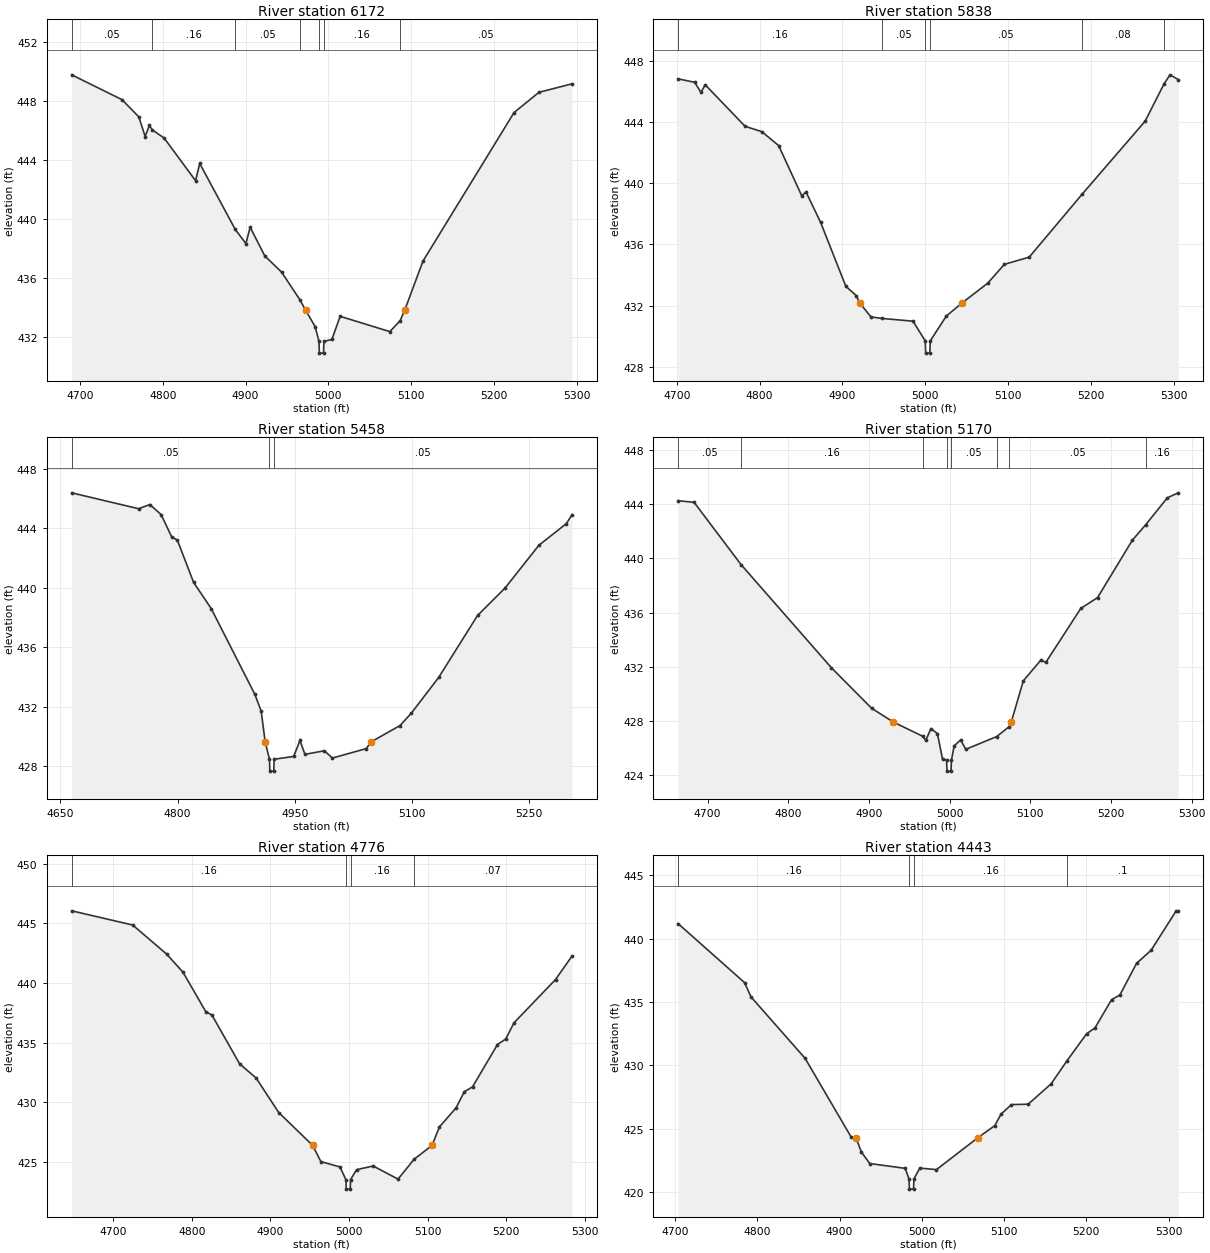
Type RM Length L Ch R = 1,6172,334,334,334
BEGIN DESCRIPTION:
UNT 107 in LFCCL Watershed 13.0
END DESCRIPTION:
XS GIS Cut Line= 3
      2826925.03      7042825.01      2826625.00      7042775.00
      2826324.97      7042775.00
#Sta/Elev= 30
  4690.0  449.80  4750.9  448.11  4771.1  446.94  4778.7  445.61  4783.8  446.36
  4787.5  446.05  4801.6  445.51  4839.6  442.61  4844.6  443.78  4887.5  439.30
  4900.4  438.34  4905.5  439.45  4923.2  437.50  4943.5  436.40  4965.8  434.50
  4972.4  433.82  4984.0  432.70  4988.6  431.70  4989.1  430.90  4994.1  430.90
  4994.6  431.70  5004.2  431.83  5014.2  433.40  5074.2  432.36  5086.7  433.11
  5092.2  433.82  5114.2  437.15  5224.2  447.24  5254.2  448.61  5294.2  449.19
#Mann=7,-1,0
  4690.0    0.05       0  4787.5    0.16       0  4887.5    0.05       0
  4965.8    0.16       0  4988.6    0.07       0  4994.6    0.16       0
  5086.7    0.05       0
Bank Sta=4972.4,5092.2
Exp/Cntr=0.3,0.1

Type RM Length L Ch R = 1,5838,380,380,380
BEGIN DESCRIPTION:
UNT 107 in LFCCL Watershed 12.0
END DESCRIPTION:
XS GIS Cut Line= 3
      2826824.95      7042524.99      2826525.00      7042475.00
      2826224.99      7042475.00
#Sta/Elev= 30
  4701.4  446.84  4721.6  446.61  4729.2  445.95  4734.3  446.45  4782.5  443.73
  4802.7  443.38  4823.0  442.47  4850.9  439.18  4856.0  439.44  4873.7  437.44
  4904.1  433.26  4916.8  432.65  4920.7  432.18  4934.5  431.26  4947.7  431.16
  4985.2  430.98  5000.0  429.69  5000.5  428.89  5005.5  428.89  5006.0  429.69
  5025.5  431.32  5044.6  432.18  5075.5  433.47  5095.5  434.70  5125.5  435.17
  5189.1  439.27  5265.5  444.07  5288.1  446.49  5295.5  447.10  5305.5  446.79
#Mann=6,-1,0
  4701.4    0.16       0  4947.7    0.05       0  5000.0   0.035       0
  5006.0    0.05       0  5189.1    0.08       0  5288.1    0.05       0
Bank Sta=4920.7,5044.6
Exp/Cntr=0.3,0.1

Type RM Length L Ch R = 1,5458,288,288,288
BEGIN DESCRIPTION:
UNT 107 in LFCCL Watershed 11.0
END DESCRIPTION:
XS GIS Cut Line= 3
      2826824.98      7042424.97      2826625.00      7042175.00
      2826374.98      7041974.99
#Sta/Elev= 30
  4664.5  446.40  4750.1  445.33  4764.5  445.61  4778.9  444.94  4792.5  443.43
  4799.7  443.22  4820.5  440.37  4843.0  438.61  4899.0  432.82  4907.0  431.70
  4912.1  429.63  4917.6  428.46  4918.1  427.66  4923.1  427.66  4923.6  428.46
  4948.6  428.65  4956.6  429.73  4963.0  428.79  4987.8  429.03  4998.2  428.54
  5041.5  429.18  5047.7  429.63  5084.7  430.73  5099.1  431.56  5134.3  433.98
  5183.9  438.14  5219.1  439.99  5262.4  442.87  5297.6  444.33  5304.8  444.93
#Mann=3,-1,0
  4664.5    0.05       0  4917.6   0.035       0  4923.6    0.05       0
Bank Sta=4912.1,5047.7
Exp/Cntr=0.3,0.1

Type RM Length L Ch R = 1,5170,394,394,394
BEGIN DESCRIPTION:
UNT 107 in LFCCL Watershed 10.0
END DESCRIPTION:
XS GIS Cut Line= 3
      2826825.00      7042275.01      2826825.00      7041975.00
      2826574.97      7041774.98
#Sta/Elev= 30
  4663.3  444.26  4683.3  444.14  4741.6  439.54  4853.3  431.95  4903.3  428.95
  4930.0  427.94  4966.7  426.88  4970.5  426.58  4976.9  427.45  4984.9  427.08
  4991.3  425.19  4996.3  425.11  4996.8  424.31  5001.8  424.31  5002.3  425.11
  5005.7  426.18  5013.7  426.61  5020.1  425.92  5058.4  426.86  5073.8  427.59
  5076.5  427.94  5091.4  430.97  5113.0  432.49  5119.4  432.34  5162.6  436.31
  5183.4  437.11  5226.6  441.35  5243.0  442.48  5269.9  444.47  5283.5  444.84
#Mann=8,-1,0
  4663.3    0.05       0  4741.6    0.16       0  4966.7    0.05       0
  4996.3   0.035       0  5002.3    0.05       0  5058.4    0.16       0
  5073.8    0.05       0  5243.0    0.16       0
Bank Sta=4930,5076.5
Exp/Cntr=0.3,0.1

Type RM Length L Ch R = 1,4776,333,333,333
BEGIN DESCRIPTION:
UNT 107 in LFCCL Watershed 9.0
END DESCRIPTION:
XS GIS Cut Line= 3
      2827374.97      7041974.97      2827125.00      7041775.00
      2826825.04      7041675.01
#Sta/Elev= 30
  4647.3  446.06  4724.9  444.87  4768.1  442.43  4788.9  440.91  4817.7  437.62
  4825.7  437.32  4861.0  433.22  4881.8  432.05  4910.6  429.15  4953.7  426.40
  4964.2  425.04  4988.5  424.59  4996.0  423.53  4996.5  422.73  5001.5  422.73
  5002.0  423.53  5009.6  424.36  5030.7  424.67  5062.3  423.57  5082.7  425.23
  5105.6  426.40  5115.0  427.95  5136.1  429.54  5146.6  430.89  5157.1  431.31
  5188.8  434.85  5199.3  435.32  5209.9  436.68  5262.6  440.30  5283.6  442.27
#Mann=4,-1,0
  4647.3    0.16       0  4996.0    0.07       0  5002.0    0.16       0
  5082.7    0.07       0
Bank Sta=4953.7,5105.6
Exp/Cntr=0.3,0.1

Type RM Length L Ch R = 1,4443,355,355,355
BEGIN DESCRIPTION:
UNT 107 in LFCCL Watershed 8.0
END DESCRIPTION:
XS GIS Cut Line= 3
      2827424.99      7041425.00      2827125.00      7041475.00
      2826824.97      7041525.00
#Sta/Elev= 30
  4703.5  441.19  4784.6  436.52  4792.2  435.41  4858.1  430.55  4913.9  424.36
  4920.0  424.28  4926.5  423.16  4936.7  422.25  4979.8  421.87  4984.4  421.03
  4984.9  420.23  4989.9  420.23  4990.4  421.03  4997.5  421.89  5017.8  421.77
  5068.0  424.28  5088.7  425.24  5096.3  426.15  5109.0  426.90  5129.3  426.93
  5157.2  428.54  5176.4  430.35  5200.3  432.49  5210.4  432.94  5230.7  435.18
  5240.8  435.55  5261.1  438.05  5278.8  439.08  5309.2  442.19  5311.8  442.19
#Mann=4,-1,0
  4703.5    0.16       0  4984.4    0.07       0  4990.4    0.16       0
  5176.4     0.1       0
Bank Sta=4920,5068
Exp/Cntr=0.3,0.1

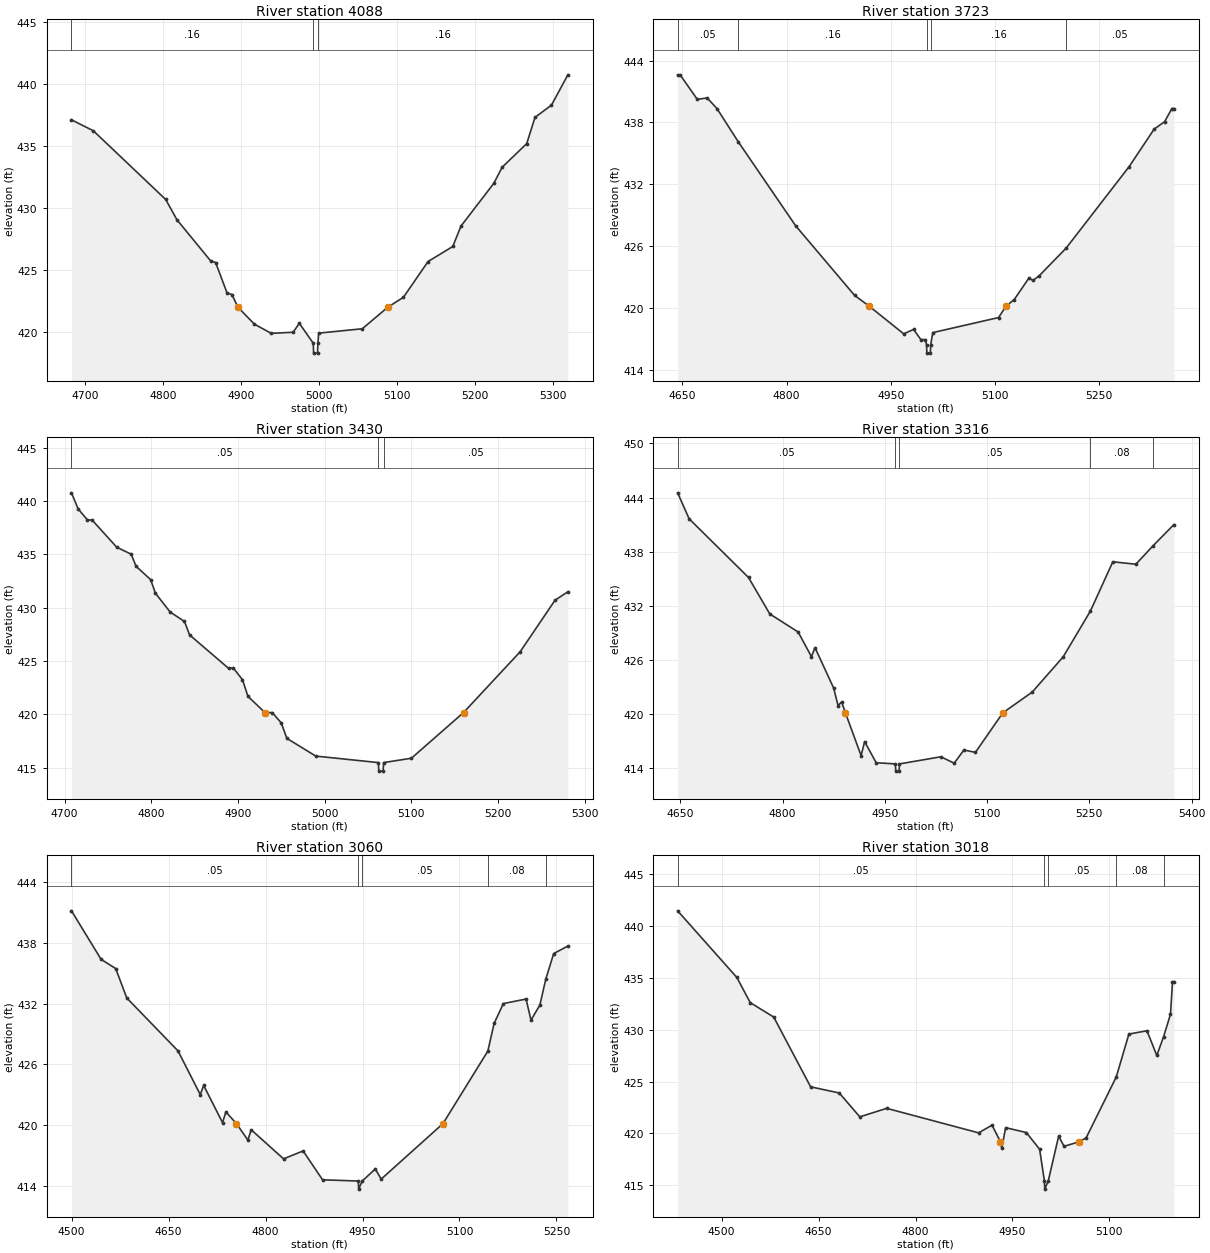
Type RM Length L Ch R = 1,4088,365,365,365
BEGIN DESCRIPTION:
UNT 107 in LFCCL Watershed 7.0
END DESCRIPTION:
XS GIS Cut Line= 3
      2827374.96      7041324.97      2827125.00      7041125.00
      2826825.04      7041025.01
#Sta/Elev= 30
  4682.6  437.09  4710.6  436.21  4803.4  430.68  4817.8  429.05  4861.0  425.74
  4867.4  425.61  4881.9  423.18  4888.3  423.03  4896.0  422.01  4917.1  420.65
  4938.7  419.91  4966.7  420.00  4974.7  420.72  4992.5  419.12  4993.0  418.32
  4998.0  418.32  4998.5  419.12  4999.5  419.93  5055.4  420.28  5088.0  422.01
  5108.1  422.81  5139.7  425.69  5171.4  426.90  5181.9  428.54  5224.1  431.99
  5234.6  433.27  5266.2  435.18  5276.8  437.29  5297.9  438.27  5318.9  440.71
#Mann=3,-1,0
  4682.6    0.16       0  4992.5    0.07       0  4998.5    0.16       0
Bank Sta=4896,5088
Exp/Cntr=0.3,0.1

Type RM Length L Ch R = 1,3723,293,293,293
BEGIN DESCRIPTION:
UNT 107 in LFCCL Watershed 6.0
END DESCRIPTION:
XS GIS Cut Line= 3
      2827625.02      7041125.02      2827375.00      7040875.00
      2827175.02      7040575.03
#Sta/Elev= 30
  4643.3  442.62  4646.9  442.62  4671.6  440.24  4685.8  440.38  4699.9  439.35
  4730.7  436.11  4813.0  427.99  4897.9  421.23  4919.0  420.18  4968.6  417.50
  4982.7  417.93  4993.3  416.94  4999.9  416.94  5001.4  416.43  5001.9  415.63
  5006.9  415.63  5007.4  416.43  5010.4  417.62  5105.0  419.08  5115.8  420.18
  5127.6  420.83  5148.6  422.90  5154.6  422.68  5163.6  423.14  5202.2  425.81
  5292.8  433.71  5328.9  437.36  5343.9  438.07  5354.4  439.35  5357.4  439.35
#Mann=5,-1,0
  4643.3    0.05       0  4730.7    0.16       0  5001.4    0.07       0
  5007.4    0.16       0  5202.2    0.05       0
Bank Sta=4919,5115.8
Exp/Cntr=0.3,0.1

Type RM Length L Ch R = 1,3430,114,114,114
BEGIN DESCRIPTION:
XS3719A
END DESCRIPTION:
XS GIS Cut Line= 4
      2827750.34      7041091.86      2827625.35      7040838.41
      2827611.46      7040751.60      2827597.57      7040550.19
#Sta/Elev= 30
  4708.0  440.76  4715.7  439.25  4726.3  438.23  4731.9  438.20  4760.2  435.66
  4776.8  435.01  4782.5  433.87  4799.2  432.63  4804.8  431.35  4821.7  429.59
  4838.3  428.70  4844.2  427.44  4889.1  424.31  4894.6  424.34  4905.2  423.24
  4911.5  421.68  4931.1  420.16  4939.5  420.16  4949.8  419.20  4956.4  417.74
  4989.7  416.08  5061.9  415.47  5062.4  414.67  5067.4  414.67  5067.9  415.47
  5100.0  415.88  5160.1  420.16  5225.5  425.87  5265.6  430.69  5280.4  431.48
#Mann=3,-1,0
  4708.0    0.05       0  5061.9    0.03       0  5067.9    0.05       0
Bank Sta=4931.1,5160.1
Exp/Cntr=0.3,0.1

Type RM Length L Ch R = 1,3316,256,256,256
BEGIN DESCRIPTION:
UNT 107 in LFCCL Watershed 5.0
END DESCRIPTION:
XS GIS Cut Line= 3
      2827825.00      7041125.02      2827725.00      7040775.00
      2827625.01      7040425.03
#Sta/Elev= 30
  4646.1  444.52  4663.0  441.64  4750.1  435.14  4781.3  431.10  4822.9  429.10
  4842.4  426.36  4847.6  427.37  4874.9  422.90  4881.4  420.95  4886.6  421.35
  4892.2  420.15  4915.2  415.41  4920.4  416.96  4937.3  414.62  4965.5  414.49
  4966.0  413.69  4971.0  413.69  4971.5  414.49  5032.2  415.28  5051.7  414.57
  5066.0  416.03  5082.9  415.77  5123.1  420.15  5166.1  422.44  5211.6  426.35
  5251.5  431.42  5284.4  436.88  5318.2  436.61  5343.1  438.63  5374.1  441.01
#Mann=5,-1,0
  4646.1    0.05       0  4965.5    0.03       0  4971.5    0.05       0
  5251.5    0.08       0  5343.1    0.05       0
Bank Sta=4892.2,5123.1
Exp/Cntr=0.3,0.1

Type RM Length L Ch R = 1,3060,42,42,42
BEGIN DESCRIPTION:
XS3720A
END DESCRIPTION:
XS GIS Cut Line= 6
      2827917.02      7041071.02      2828007.29      7040748.13
      2828003.82      7040682.16      2827972.57      7040643.96
      2827920.49      7040630.07      2827746.86      7040432.13
#Sta/Elev= 30
  4499.7  441.16  4545.5  436.37  4568.1  435.46  4585.2  432.56  4664.5  427.33
  4699.0  423.01  4704.2  423.92  4733.4  420.25  4738.6  421.30  4755.0  420.15
  4772.6  418.52  4777.8  419.54  4827.8  416.67  4858.1  417.45  4888.2  414.60
  4943.5  414.48  4944.0  413.68  4949.5  414.48  4969.8  415.67  4978.9  414.67
  5074.5  420.15  5143.9  427.31  5153.6  430.04  5167.9  432.00  5203.0  432.45
  5210.7  430.37  5224.4  431.85  5233.6  434.43  5245.8  436.94  5267.7  437.68
#Mann=5,-1,0
  4499.7    0.05       0  4943.5    0.03       0  4949.5    0.05       0
  5143.9    0.08       0  5233.6    0.05       0
Bank Sta=4755,5074.5
Exp/Cntr=0.3,0.1

Type RM Length L Ch R = 1,3018,118,118,118
BEGIN DESCRIPTION:
XS3721A
END DESCRIPTION:
XS GIS Cut Line= 6
      2827951.75      7041081.44      2828066.32      7040709.93
      2828048.96      7040650.91      2827982.99      7040605.77
      2827917.02      7040588.41      2827826.74      7040446.04
#Sta/Elev= 30
  4431.9  441.44  4523.6  435.02  4544.2  432.60  4580.6  431.21  4637.7  424.49
  4682.0  423.90  4713.8  421.60  4755.4  422.42  4897.6  420.06  4918.4  420.80
  4931.4  419.20  4933.5  418.58  4939.4  420.56  4971.4  420.09  4992.0  418.48
  4999.4  415.44  4999.9  414.64  5005.4  415.44  5021.5  419.75  5029.8  418.76
  5053.0  419.20  5064.0  419.58  5110.6  425.44  5130.1  429.57  5158.1  429.89
  5173.3  427.51  5183.9  429.33  5194.5  431.49  5197.6  434.61  5199.9  434.61
#Mann=5,-1,0
  4431.9    0.05       0  4999.4    0.03       0  5005.4    0.05       0
  5110.6    0.08       0  5183.9    0.05       0
Bank Sta=4931.4,5053
Exp/Cntr=0.3,0.1