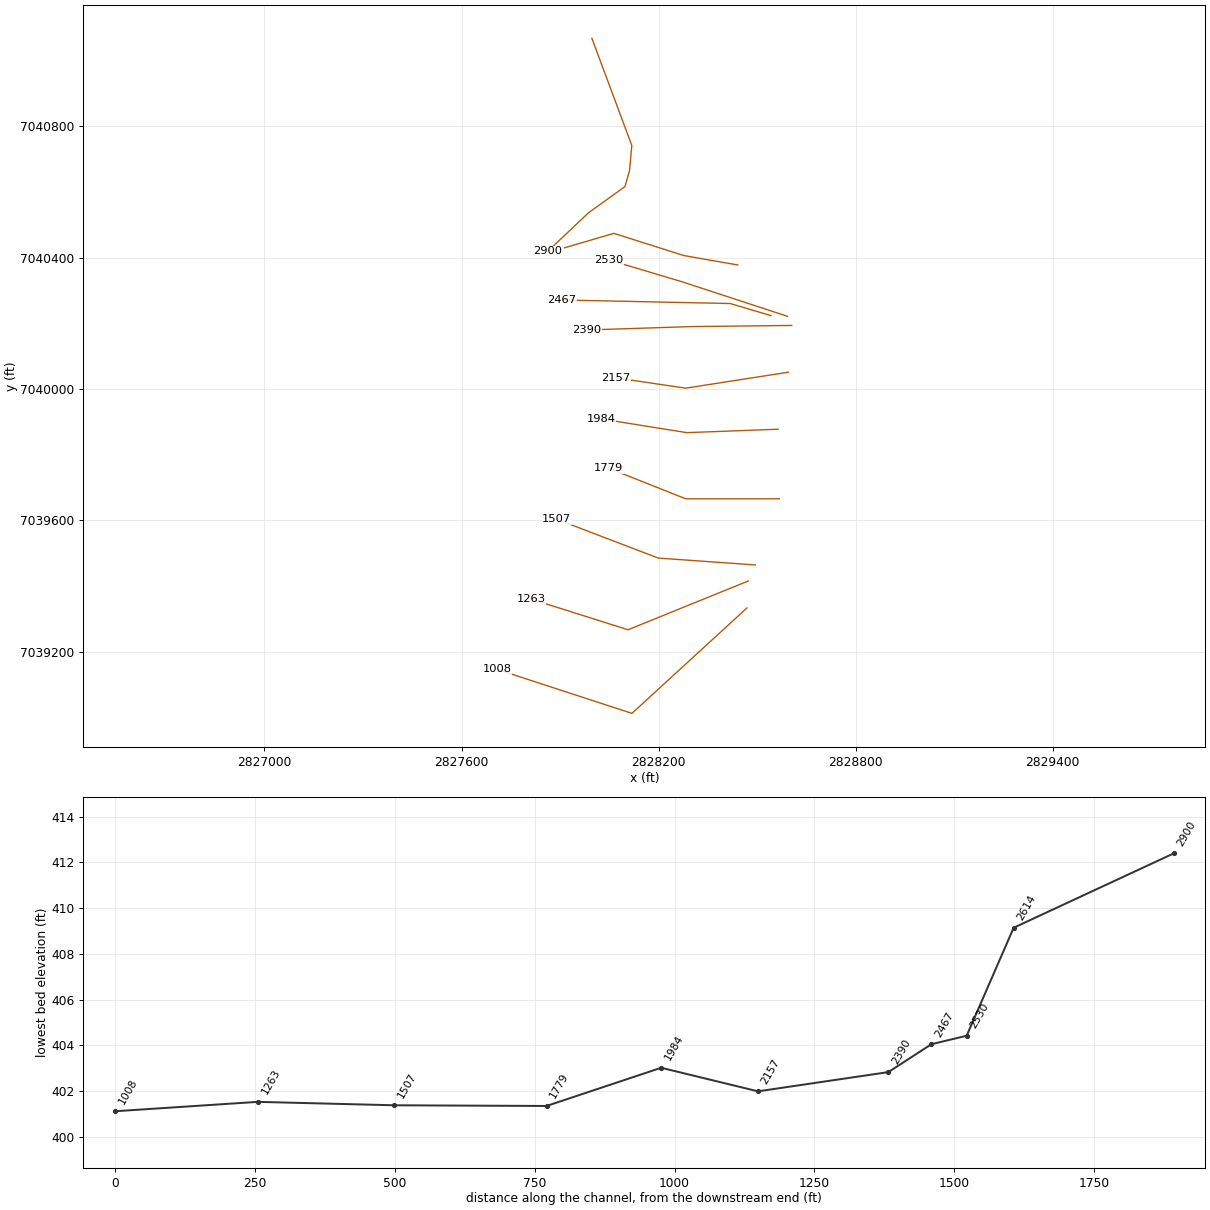
HEC-RAS study UNT 107 in LFCCL Watershed.prj: UNT 107 in LFCCL Watershed Base Level Engineering

--- UNT 107 in LFCCL Watershed.g01 (geometry) --- (continued)

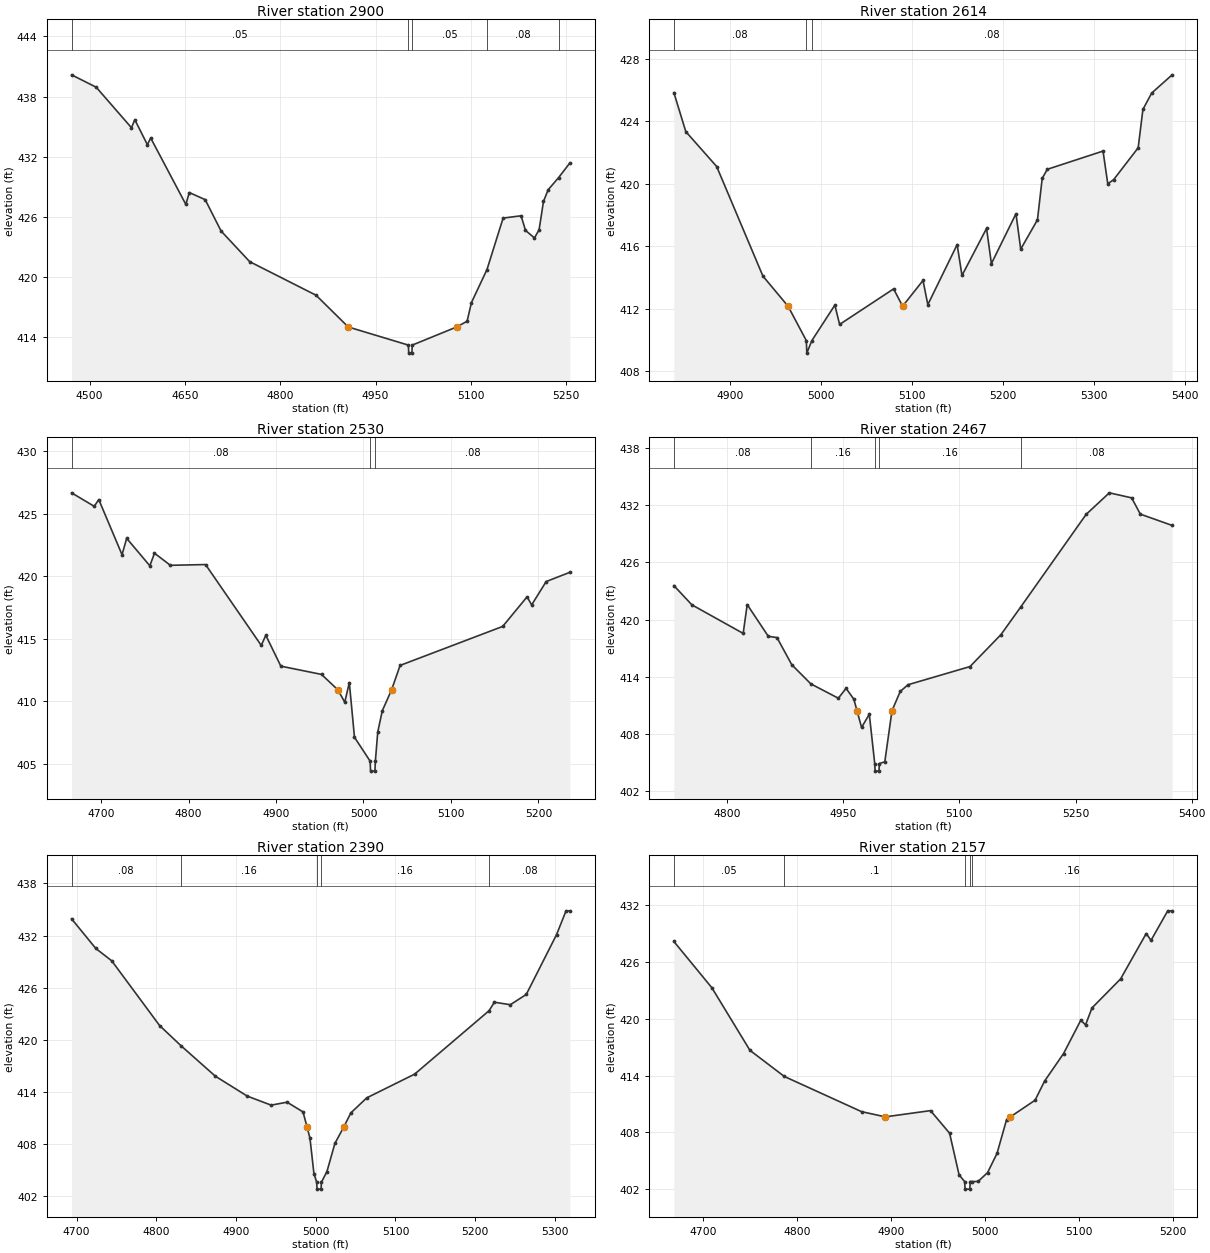
Type RM Length L Ch R = 1,2900,286,286,286
BEGIN DESCRIPTION:
XS3722A
END DESCRIPTION:
XS GIS Cut Line= 6
      2827996.88      7041067.56      2828118.41      7040741.18
      2828111.46      7040664.80      2828097.57      7040616.18
      2827986.46      7040536.32      2827862.35      7040419.11
#Sta/Elev= 30
  4471.7  440.17  4510.5  438.93  4565.9  434.89  4571.2  435.69  4590.9  433.20
  4596.2  433.86  4651.5  427.23  4656.9  428.42  4681.9  427.71  4706.9  424.58
  4751.9  421.52  4856.3  418.17  4907.0  415.00  5001.6  413.19  5002.1  412.39
  5007.1  412.39  5007.6  413.19  5077.5  415.00  5093.9  415.57  5100.8  417.44
  5125.2  420.73  5150.6  425.87  5178.9  426.10  5185.8  424.64  5199.9  423.89
  5207.2  424.70  5214.1  427.53  5221.4  428.69  5238.0  429.92  5255.6  431.37
#Mann=5,-1,0
  4471.7    0.05       0  5001.6    0.03       0  5007.6    0.05       0
  5125.2    0.08       0  5238.0    0.05       0
Bank Sta=4907,5077.5
Exp/Cntr=0.3,0.1

Type RM Length L Ch R = 1,2614,84,84,84
BEGIN DESCRIPTION:
XS3723A
END DESCRIPTION:
XS GIS Cut Line= 4
      2828441.31      7040377.47      2828277.26      7040406.11
      2828063.72      7040473.82      2827913.40      7040429.76
#Sta/Elev= 30
  4838.4  425.85  4851.5  423.35  4885.4  421.11  4936.2  414.08  4963.8  412.15
  4983.9  409.94  4984.4  409.14  4989.9  409.94  5015.2  412.22  5020.4  410.98
  5079.7  413.26  5089.6  412.15  5112.0  413.80  5117.3  412.25  5149.5  416.10
  5154.8  414.12  5181.8  417.14  5187.1  414.88  5214.1  418.08  5219.3  415.81
  5237.7  417.69  5242.9  420.35  5248.5  420.93  5309.7  422.10  5314.9  420.00
  5321.4  420.27  5348.3  422.31  5353.5  424.77  5363.1  425.82  5385.6  426.99
#Mann=3,-1,0
  4838.4    0.08       0  4983.9    0.07       0  4989.9    0.08       0
Bank Sta=4963.8,5089.6
Exp/Cntr=0.3,0.1

Type RM Length L Ch R = 1,2530,63,63,63
BEGIN DESCRIPTION:
XS3724A
END DESCRIPTION:
XS GIS Cut Line= 3
      2828592.37      7040221.22      2828274.66      7040325.39
      2828049.07      7040392.80
#Sta/Elev= 30
  4666.2  426.69  4692.1  425.61  4697.3  426.15  4723.9  421.74  4729.2  423.05
  4755.7  420.85  4761.0  421.86  4779.2  420.89  4819.4  420.95  4883.1  414.48
  4888.3  415.29  4905.5  412.82  4952.0  412.16  4970.8  410.92  4978.6  409.93
  4983.8  411.51  4989.7  407.13  5007.6  405.22  5008.1  404.42  5013.1  404.42
  5013.6  405.22  5016.3  407.54  5021.5  409.25  5032.1  410.92  5041.9  412.88
  5159.2  416.00  5187.1  418.37  5192.3  417.72  5208.9  419.59  5236.0  420.33
#Mann=3,-1,0
  4666.2    0.08       0  5007.6    0.07       0  5013.6    0.08       0
Bank Sta=4970.8,5032.1
Exp/Cntr=0.3,0.1

Type RM Length L Ch R = 1,2467,77,77,77
BEGIN DESCRIPTION:
Mapping XS f16a0dc3
END DESCRIPTION:
XS GIS Cut Line= 3
      2828541.95      7040223.27      2828418.23      7040260.17
      2827903.95      7040271.02
#Sta/Elev= 30
  4731.3  423.57  4754.5  421.55  4820.8  418.54  4826.0  421.57  4853.3  418.23
  4864.5  418.10  4883.6  415.24  4908.2  413.23  4943.7  411.72  4953.7  412.76
  4963.7  411.62  4967.8  410.41  4973.7  408.65  4983.7  410.03  4990.7  404.85
  4991.2  404.05  4996.2  404.05  4996.7  404.85  5003.7  405.03  5013.0  410.41
  5023.7  412.44  5033.7  413.14  5113.7  415.05  5153.7  418.41  5179.0  421.29
  5263.7  431.06  5293.7  433.33  5322.5  432.80  5333.7  431.09  5374.8  429.90
#Mann=5,-1,0
  4731.3    0.08       0  4908.2    0.16       0  4990.7    0.07       0
  4996.7    0.16       0  5179.0    0.08       0
Bank Sta=4967.8,5013
Exp/Cntr=0.3,0.1

Type RM Length L Ch R = 1,2390,233,233,233
BEGIN DESCRIPTION:
XS3725A
END DESCRIPTION:
XS GIS Cut Line= 3
      2828605.38      7040193.44      2828299.83      7040189.97
      2827980.36      7040179.55
#Sta/Elev= 30
  4693.6  433.92  4724.0  430.51  4744.0  429.09  4804.0  421.65  4830.7  419.34
  4874.0  415.82  4914.0  413.53  4944.0  412.49  4964.0  412.83  4984.0  411.71
  4989.0  409.99  4992.7  408.69  4997.7  404.61  5001.1  403.63  5001.6  402.83
  5006.6  402.83  5007.1  403.63  5014.0  404.85  5024.0  408.09  5035.2  409.99
  5044.0  411.60  5064.0  413.33  5124.1  416.06  5217.4  423.35  5224.1  424.33
  5244.1  424.04  5264.1  425.22  5302.1  432.10  5314.0  434.84  5318.8  434.84
#Mann=5,-1,0
  4693.6    0.08       0  4830.7    0.16       0  5001.1    0.07       0
  5007.1    0.16       0  5217.4    0.08       0
Bank Sta=4989,5035.2
Exp/Cntr=0.3,0.1

Type RM Length L Ch R = 1,2157,173,173,173
BEGIN DESCRIPTION:
XS3729A
END DESCRIPTION:
XS GIS Cut Line= 3
      2828594.99      7040051.08      2828282.47      7040002.47
      2828070.64      7040033.72
#Sta/Elev= 30
  4668.7  428.17  4709.2  423.27  4749.7  416.66  4786.3  413.90  4868.5  410.18
  4893.8  409.63  4941.9  410.29  4962.2  407.90  4972.3  403.50  4978.2  402.79
  4978.7  401.99  4983.7  401.99  4984.2  402.79  4986.0  402.79  4992.5  402.80
  5002.6  403.73  5012.7  405.77  5022.9  409.35  5026.9  409.63  5053.2  411.39
  5063.3  413.41  5083.5  416.32  5101.9  419.85  5106.9  419.35  5113.8  421.15
  5144.2  424.21  5171.5  429.01  5176.6  428.29  5194.4  431.41  5199.1  431.41
#Mann=5,-1,0
  4668.7    0.05       0  4786.3     0.1       0  4978.2    0.07       0
  4984.2     0.1       0  4986.0    0.16       0
Bank Sta=4893.8,5026.9
Exp/Cntr=0.3,0.1

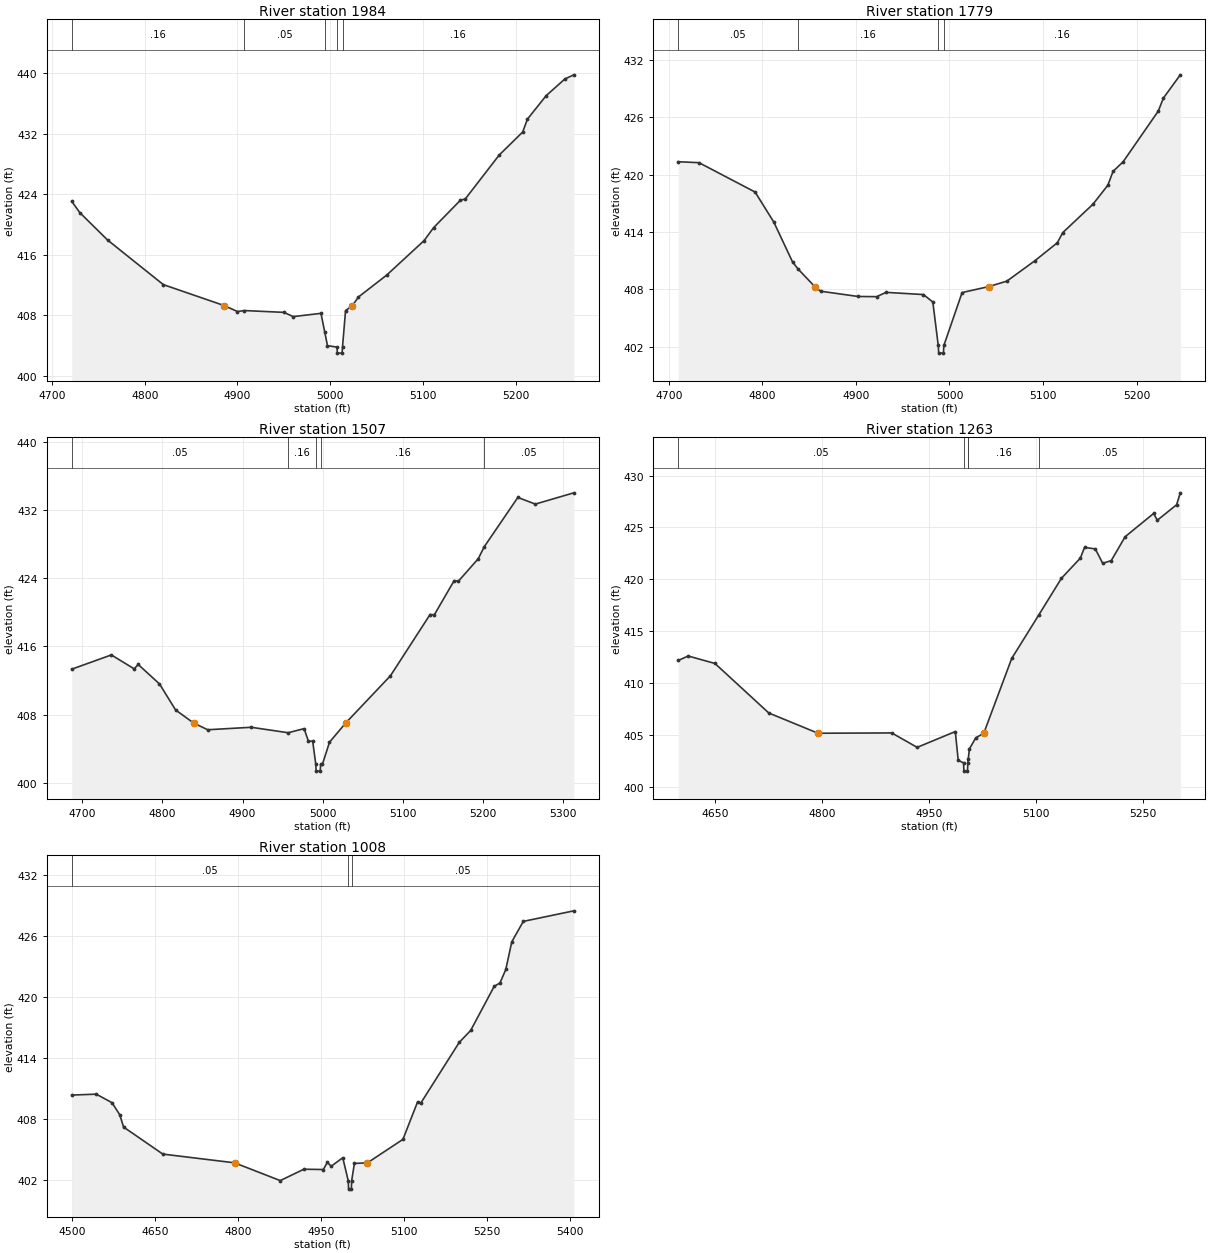
Type RM Length L Ch R = 1,1984,205,205,205
BEGIN DESCRIPTION:
XS3728A
END DESCRIPTION:
XS GIS Cut Line= 3
      2828563.72      7039877.47      2828285.94      7039867.05
      2828025.53      7039908.72
#Sta/Elev= 30
  4721.2  423.05  4729.9  421.56  4759.9  417.94  4820.0  412.06  4885.8  409.29
  4900.0  408.51  4907.3  408.64  4950.1  408.40  4960.1  407.84  4990.1  408.27
  4994.1  405.83  4997.1  404.00  5007.3  403.82  5007.8  403.02  5012.8  403.02
  5013.3  403.82  5016.6  408.64  5024.0  409.29  5030.5  410.43  5060.9  413.31
  5101.4  417.88  5111.5  419.57  5140.6  423.21  5145.7  423.36  5182.4  429.17
  5207.7  432.20  5212.8  433.90  5233.1  437.01  5253.3  439.21  5262.9  439.75
#Mann=5,-1,0
  4721.2    0.16       0  4907.3    0.05       0  4994.1    0.16       0
  5007.3    0.07       0  5013.3    0.16       0
Bank Sta=4885.8,5024
Exp/Cntr=0.3,0.1

Type RM Length L Ch R = 1,1779,272,272,272
BEGIN DESCRIPTION:
XS3727A
END DESCRIPTION:
XS GIS Cut Line= 3
      2828567.19      7039665.66      2828282.47      7039665.66
      2828048.19      7039758.69
#Sta/Elev= 30
  4710.0  421.35  4732.2  421.25  4792.2  418.18  4812.2  415.04  4832.2  410.88
  4838.2  410.13  4856.0  408.30  4862.2  407.82  4902.2  407.27  4922.2  407.25
  4932.2  407.70  4972.2  407.47  4982.2  406.69  4988.0  402.15  4988.5  401.35
  4993.5  401.35  4994.0  402.15  5013.5  407.68  5041.9  408.30  5061.3  408.87
  5091.0  410.98  5115.3  412.88  5121.1  413.94  5153.4  416.91  5169.3  418.89
  5174.9  420.34  5185.7  421.35  5223.3  426.65  5228.7  428.00  5246.8  430.43
#Mann=4,-1,0
  4710.0    0.05       0  4838.2    0.16       0  4988.0    0.07       0
  4994.0    0.16       0
Bank Sta=4856,5041.9
Exp/Cntr=0.3,0.1

Type RM Length L Ch R = 1,1507,244,244,244
BEGIN DESCRIPTION:
XS3726A
END DESCRIPTION:
XS GIS Cut Line= 3
      2828494.24      7039464.28      2828199.13      7039485.11
      2827890.06      7039603.18
#Sta/Elev= 30
  4686.8  413.33  4736.2  415.00  4764.7  413.37  4769.7  413.88  4796.3  411.60
  4816.4  408.55  4838.9  407.02  4856.5  406.23  4910.8  406.52  4956.9  405.88
  4976.8  406.36  4982.2  404.89  4987.5  404.89  4991.4  402.18  4991.9  401.38
  4996.9  401.38  4997.4  402.18  4999.7  402.19  5008.5  404.77  5028.7  407.02
  5084.6  412.56  5134.0  419.73  5139.4  419.71  5164.1  423.71  5169.4  423.64
  5194.2  426.28  5201.6  427.67  5243.6  433.46  5265.4  432.68  5313.5  434.00
#Mann=5,-1,0
  4686.8    0.05       0  4956.9    0.16       0  4991.4    0.07       0
  4997.4    0.16       0  5201.6    0.05       0
Bank Sta=4838.9,5028.7
Exp/Cntr=0.3,0.1

Type RM Length L Ch R = 1,1263,255,255,255
BEGIN DESCRIPTION:
Mapping XS 2f51ad5b
END DESCRIPTION:
XS GIS Cut Line= 3
      2828472.84      7039415.35      2828106.93      7039266.90
      2827811.10      7039360.32
#Sta/Elev= 30
  4597.7  412.19  4611.7  412.62  4649.3  411.90  4724.9  407.13  4794.0  405.18
  4897.5  405.21  4933.2  403.82  4986.8  405.34  4990.9  402.57  4998.4  402.33
  4998.9  401.53  5003.9  401.53  5004.4  402.33  5005.0  402.70  5006.6  403.67
  5015.6  404.74  5026.8  405.18  5066.0  412.38  5103.9  416.56  5135.9  420.11
  5162.4  422.05  5168.3  423.08  5183.4  422.94  5193.8  421.55  5205.8  421.81
  5225.3  424.11  5265.3  426.35  5270.5  425.70  5297.6  427.19  5302.8  428.34
#Mann=5,-1,0
  4597.7    0.05       0  4998.4    0.03       0  5004.4    0.05       0
  5005.0    0.16       0  5103.9    0.05       0
Bank Sta=4794,5026.8
Exp/Cntr=0.3,0.1

Type RM Length L Ch R = 1,1008,0,0,0
BEGIN DESCRIPTION:
UNT 107 in LFCCL Watershed 1.0
END DESCRIPTION:
XS GIS Cut Line= 3
      2828468.93      7039333.33      2828118.76      7039012.34
      2827708.19      7039146.31
#Sta/Elev= 30
  4499.8  410.38  4544.1  410.47  4572.5  409.63  4586.5  408.44  4593.4  407.23
  4664.3  404.57  4793.9  403.71  4876.4  401.96  4919.0  403.08  4954.1  403.05
  4961.5  403.76  4968.3  403.37  4989.3  404.21  4999.3  401.92  4999.8  401.12
  5004.8  401.12  5005.3  401.92  5010.3  403.65  5033.9  403.71  5098.0  406.02
  5124.6  409.73  5129.9  409.56  5199.7  415.57  5220.3  416.74  5262.8  421.08
  5273.3  421.42  5283.8  422.75  5294.6  425.47  5315.4  427.48  5406.7  428.52
#Mann=3,-1,0
  4499.8    0.05       0  4999.3    0.03       0  5005.3    0.05       0
Bank Sta=4793.9,5033.9
Exp/Cntr=0.3,0.1

Chan Stop Cuts=-1