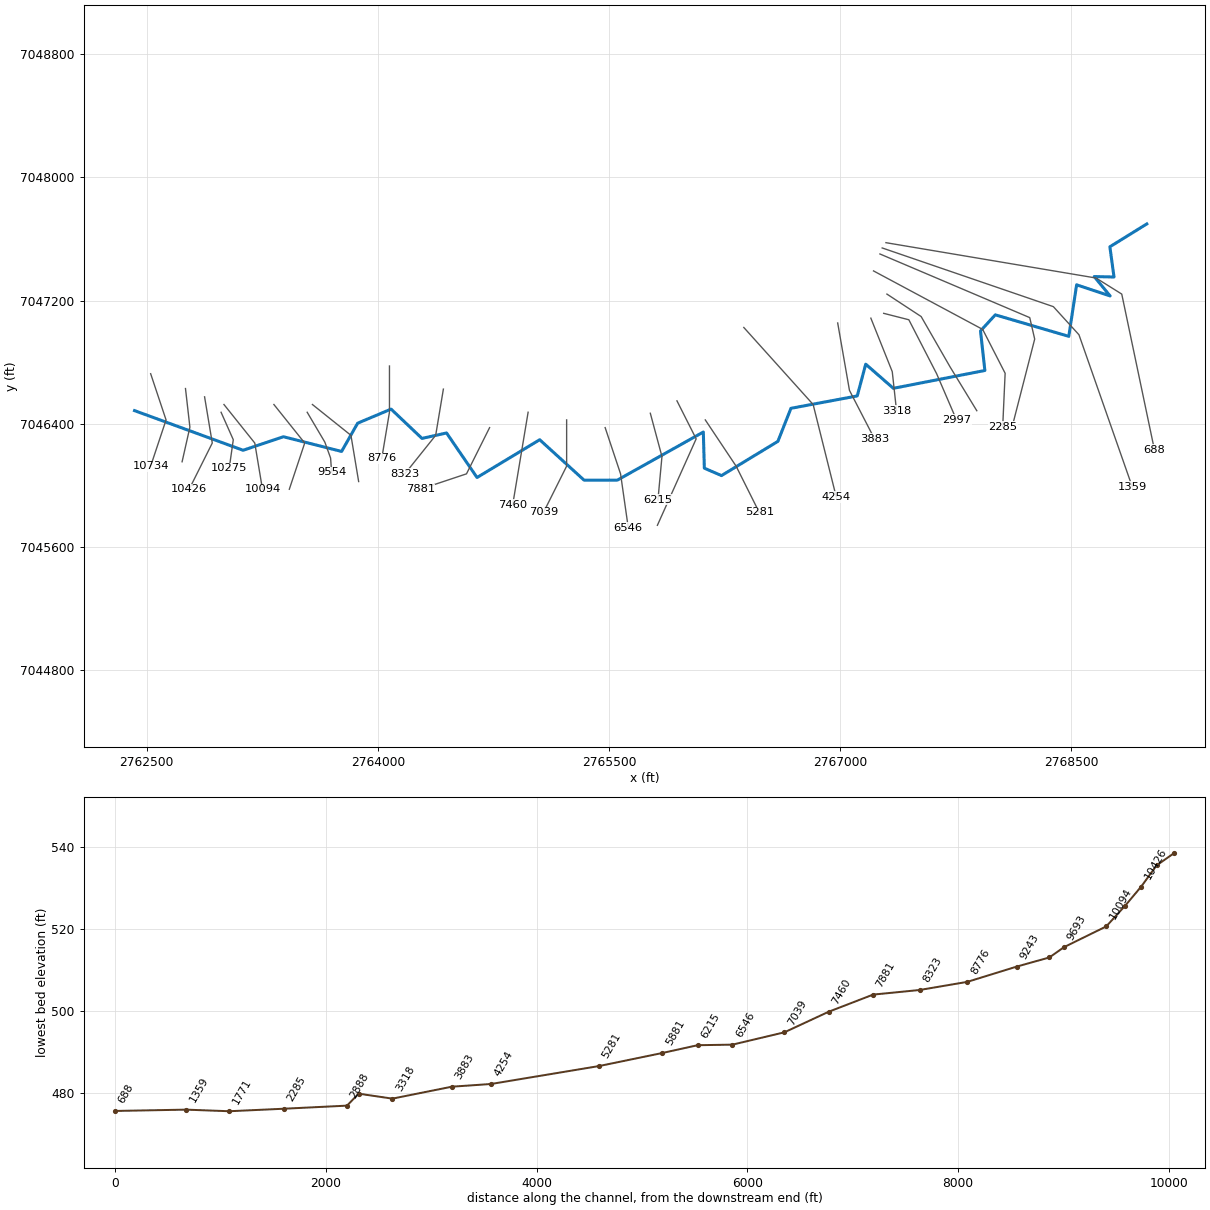
--- UNT 109 in LFCCL Watershed.prj (project) ---

Proj Title=UNT 109 in LFCCL Watershed Base Level Engineering
Current Plan=p01
Default Exp/Contr=0.3,0.1
English Units
Geom File=g01
Flow File=f01
Plan File=p01
BEGIN DESCRIPTION:
UNT 109 in LFCCL Watershed
END DESCRIPTION:

--- UNT 109 in LFCCL Watershed.p01 (plan) ---

Plan Title=Multiple Run
Short Identifier=Multiple
Geom File=g01
Flow File=f01
Subcritical Flow
K Sum by GR= 0
Std Step Tol= 0.01
Critical Tol= 0.01
Num of Std Step Trials= 20
Max Error Tol= 0.3
Flow Tol Ratio= 0.001
Split Flow NTrial= 30
Split Flow Tol= 0.02
Split Flow Ratio= 0.02
Log Output Level= 0
Friction Slope Method= 1
Unsteady Friction Slope Method= 2
Unsteady Bridges Friction Slope Method= 1
Parabolic Critical Depth
Global Vel Dist=  1 , 1 , 1
Global Log Level= 0
CheckData=True
Encroach Param= -1, 0, 0, 0
BEGIN DESCRIPTION:
Multiple Run
END DESCRIPTION:

--- UNT 109 in LFCCL Watershed.f01 (steady flow) ---

Flow Title=Multiple
Number of Profiles=7
Profile Names=10-year,25-year,50-year,1pct_min,100-year,1pct_plu,500-year
River Rch & RM= UNT 109 in LFCCL,Reach-1,10734
     240     306     357     208     415     828     560
River Rch & RM= UNT 109 in LFCCL,Reach-1,7039
     548     733     884     530    1057    2108    1513
Boundary for River Rch & Prof#=UNT 109 in LFCCL,Reach-1,1
Up Type=0
Dn Type=3
Dn Slope=0.005
Boundary for River Rch & Prof#=UNT 109 in LFCCL,Reach-1,2
Up Type=0
Dn Type=3
Dn Slope=0.005
Boundary for River Rch & Prof#=UNT 109 in LFCCL,Reach-1,3
Up Type=0
Dn Type=3
Dn Slope=0.005
Boundary for River Rch & Prof#=UNT 109 in LFCCL,Reach-1,4
Up Type=0
Dn Type=3
Dn Slope=0.005
Boundary for River Rch & Prof#=UNT 109 in LFCCL,Reach-1,5
Up Type=0
Dn Type=3
Dn Slope=0.005
Boundary for River Rch & Prof#=UNT 109 in LFCCL,Reach-1,6
Up Type=0
Dn Type=3
Dn Slope=0.005
Boundary for River Rch & Prof#=UNT 109 in LFCCL,Reach-1,7
Up Type=0
Dn Type=3
Dn Slope=0.005

--- UNT 109 in LFCCL Watershed.g01 (geometry) ---

Geom Title=Existing Conditions

River Reach=UNT 109 in LFCCL,Reach-1
Reach XY= 30
      2762420.39      7046485.35      2763125.25      7046227.97
      2763386.75      7046315.86      2763764.36      7046220.38
      2763868.52      7046403.75      2764085.57      7046495.14
      2764286.09      7046305.04      2764445.51      7046340.35
      2764643.42      7046051.21      2765050.15      7046296.37
      2765338.01      7046034.27      2765554.08      7046034.17
      2766112.17      7046346.46      2766118.81      7046111.88
      2766229.99      7046063.65      2766596.13      7046285.77
      2766680.80      7046500.27      2767111.21      7046580.70
      2767166.24      7046786.73      2767345.46      7046630.09
      2767939.56      7046745.81      2767911.33      7047002.64
      2768007.29      7047107.06      2768484.26      7046967.36
      2768535.06      7047301.80      2768752.38      7047229.84
      2768649.37      7047355.43      2768777.78      7047352.61
      2768750.97      7047548.76      2768990.50      7047697.06

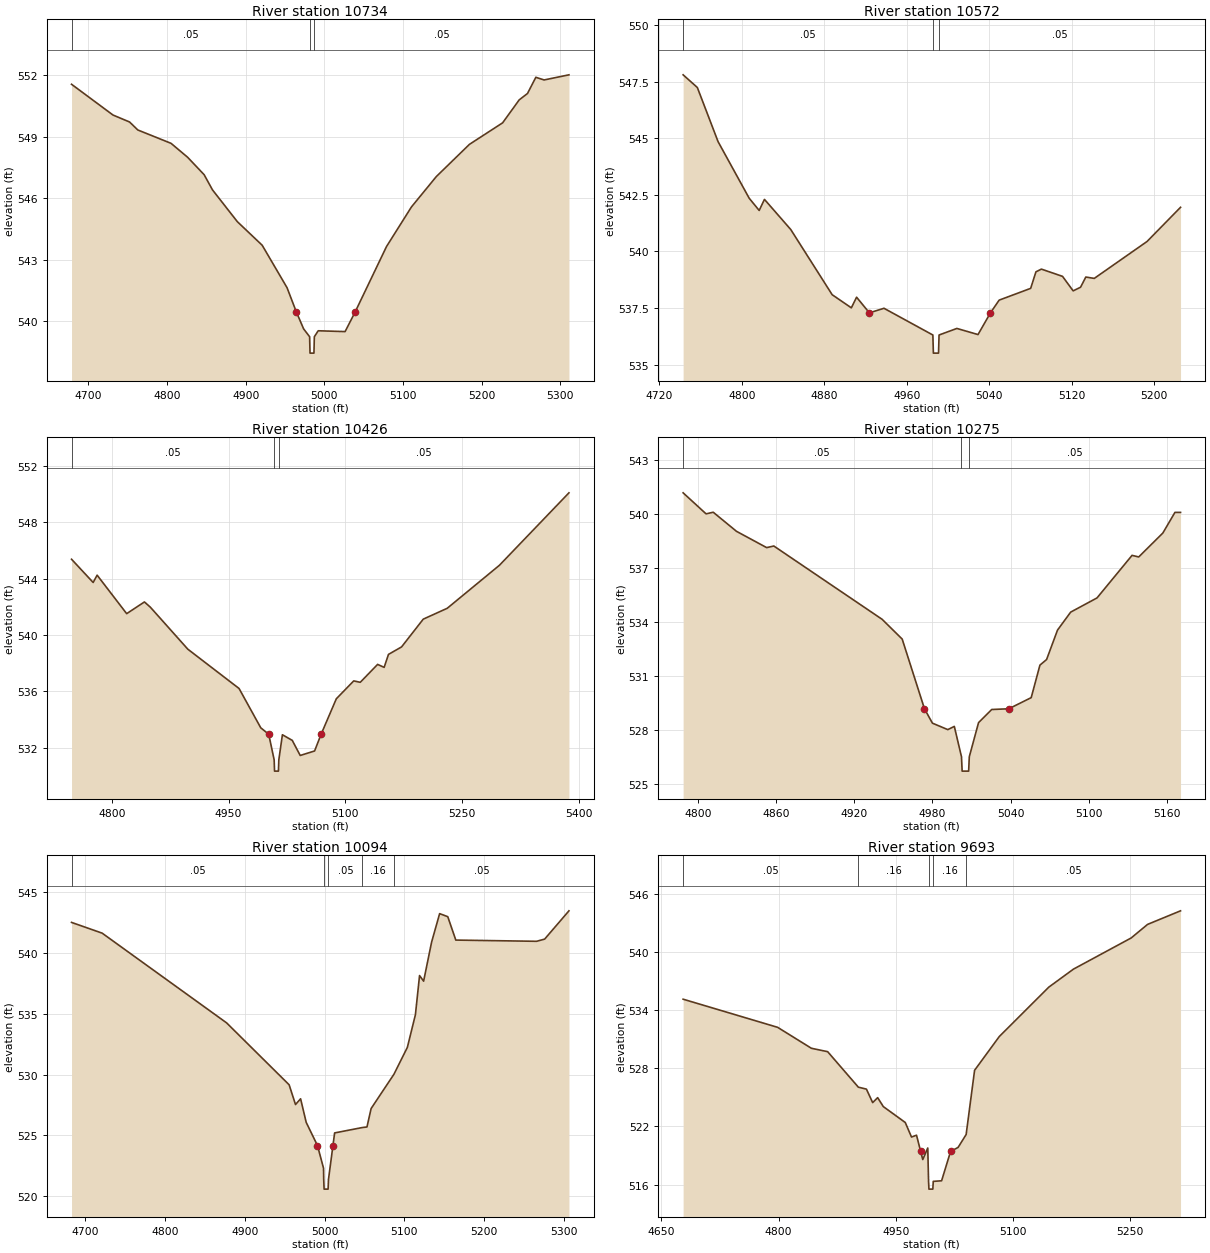
Type RM Length L Ch R = 1,10734,162,162,162
BEGIN DESCRIPTION:
UNT 109 in LFCCL Watershed 19.0
END DESCRIPTION:
XS GIS Cut Line= 3
      2762525.00      7046724.99      2762625.00      7046425.00
      2762525.01      7046125.04
#Sta/Elev= 30
  4678.5  551.56  4731.2  550.06  4752.3  549.72  4762.8  549.33  4805.0  548.68
  4826.1  548.00  4847.1  547.15  4857.7  546.41  4889.3  544.86  4920.9  543.71
  4952.5  541.64  4964.4  540.45  4973.6  539.63  4981.2  539.25  4981.7  538.45
  4986.7  538.45  4987.2  539.25  4992.1  539.54  5026.3  539.50  5039.0  540.45
  5079.0  543.65  5110.7  545.58  5142.3  547.06  5184.4  548.63  5226.6  549.68
  5247.7  550.80  5258.2  551.11  5268.8  551.90  5279.3  551.77  5310.9  552.02
#Mann=3,-1,0
  4678.5    0.05       0  4981.2    0.03       0  4987.2    0.05       0
Bank Sta=4964.4,5039
Exp/Cntr=0.3,0.1

Type RM Length L Ch R = 1,10572,146,146,146
BEGIN DESCRIPTION:
XS3730A
END DESCRIPTION:
XS GIS Cut Line= 3
      2762751.10      7046628.68      2762779.71      7046377.79
      2762729.11      7046153.34
#Sta/Elev= 30
  4743.0  547.80  4756.8  547.24  4776.9  544.85  4807.1  542.35  4816.8  541.81
  4821.9  542.30  4847.4  540.97  4887.6  538.09  4906.2  537.51  4911.3  537.98
  4923.7  537.29  4937.9  537.49  4985.3  536.31  4985.8  535.51  4990.8  535.51
  4991.3  536.31  5008.6  536.60  5029.1  536.33  5041.2  537.29  5049.6  537.85
  5080.2  538.37  5085.3  539.10  5090.6  539.22  5111.1  538.90  5121.4  538.26
  5128.6  538.42  5133.7  538.87  5141.9  538.81  5193.1  540.44  5225.6  541.95
#Mann=3,-1,0
  4743.0    0.05       0  4985.3    0.03       0  4991.3    0.05       0
Bank Sta=4923.7,5041.2
Exp/Cntr=0.3,0.1

Type RM Length L Ch R = 1,10426,151,151,151
BEGIN DESCRIPTION:
UNT 109 in LFCCL Watershed 18.0
END DESCRIPTION:
XS GIS Cut Line= 3
      2762875.01      7046574.95      2762925.00      7046275.00
      2762775.00      7045975.00
#Sta/Elev= 30
  4748.1  545.37  4775.9  543.72  4781.0  544.24  4819.0  541.51  4841.8  542.34
  4849.4  541.97  4897.6  538.99  4963.5  536.20  4991.4  533.41  5001.6  532.96
  5008.6  531.14  5009.1  530.34  5014.1  530.34  5014.6  531.14  5019.2  532.92
  5031.9  532.52  5042.1  531.45  5060.6  531.77  5069.0  532.96  5088.5  535.47
  5110.9  536.74  5119.3  536.64  5141.6  537.91  5150.0  537.70  5155.6  538.62
  5172.4  539.15  5200.3  541.12  5231.1  541.89  5298.2  544.94  5387.6  550.08
#Mann=3,-1,0
  4748.1    0.05       0  5008.6    0.03       0  5014.6    0.05       0
Bank Sta=5001.6,5069
Exp/Cntr=0.3,0.1

Type RM Length L Ch R = 1,10275,181,181,181
BEGIN DESCRIPTION:
XS3731A
END DESCRIPTION:
XS GIS Cut Line= 3
      2762982.17      7046474.57      2763061.38      7046296.37
      2763034.97      7046111.56
#Sta/Elev= 30
  4788.7  541.20  4806.3  540.03  4811.8  540.12  4829.6  539.06  4852.8  538.15
  4858.3  538.24  4941.4  534.16  4956.8  533.06  4973.9  529.18  4980.0  528.38
  4991.8  528.02  4996.8  528.20  5002.3  526.51  5002.8  525.71  5007.8  525.71
  5008.3  526.51  5015.4  528.41  5025.5  529.14  5038.6  529.18  5055.8  529.80
  5062.5  531.61  5067.6  531.92  5076.0  533.56  5086.1  534.56  5106.3  535.35
  5133.2  537.72  5138.3  537.63  5156.8  538.96  5166.1  540.11  5170.4  540.11
#Mann=3,-1,0
  4788.7    0.05       0  5002.3    0.03       0  5008.3    0.05       0
Bank Sta=4973.9,5038.6
Exp/Cntr=0.3,0.1

Type RM Length L Ch R = 1,10094,401,401,401
BEGIN DESCRIPTION:
UNT 109 in LFCCL Watershed 17.0
END DESCRIPTION:
XS GIS Cut Line= 3
      2763000.82      7046524.97      2763200.79      7046275.00
      2763250.80      7045974.95
#Sta/Elev= 30
  4682.5  542.48  4720.9  541.60  4877.1  534.24  4955.6  529.16  4963.6  527.54
  4970.0  528.01  4977.0  526.08  4991.2  524.17  4998.8  522.31  4999.0  521.40
  4999.5  520.60  5004.5  520.60  5005.0  521.40  5010.6  524.17  5012.7  525.21
  5047.3  525.65  5053.3  525.70  5058.5  527.21  5087.2  530.03  5104.0  532.23
  5114.1  534.91  5119.3  538.12  5124.4  537.66  5134.4  540.86  5144.5  543.20
  5154.7  542.95  5164.8  541.03  5266.2  540.93  5276.3  541.11  5306.8  543.43
#Mann=5,-1,0
  4682.5    0.05       0  4999.0    0.03       0  5005.0    0.05       0
  5047.3    0.16       0  5087.2    0.05       0
Bank Sta=4991.2,5010.6
Exp/Cntr=0.3,0.1

Type RM Length L Ch R = 1,9693,139,139,139
BEGIN DESCRIPTION:
UNT 109 in LFCCL Watershed 16.0
END DESCRIPTION:
XS GIS Cut Line= 3
      2763324.99      7046525.02      2763525.00      7046275.00
      2763425.00      7045975.01
#Sta/Elev= 30
  4677.8  535.11  4798.7  532.21  4841.9  530.05  4862.7  529.70  4902.0  526.04
  4912.3  525.84  4920.3  524.45  4926.7  524.96  4933.9  524.04  4962.0  522.40
  4970.0  520.90  4976.4  521.09  4981.7  519.42  4984.4  518.58  4990.8  519.77
  4991.8  516.33  4992.3  515.53  4997.3  515.53  4997.8  516.33  5008.5  516.39
  5020.0  519.42  5029.6  519.83  5039.9  521.16  5050.7  527.78  5082.3  531.26
  5145.6  536.35  5177.2  538.21  5251.0  541.42  5272.0  542.82  5314.2  544.22
#Mann=5,-1,0
  4677.8    0.05       0  4902.0    0.16       0  4991.8    0.07       0
  4997.8    0.16       0  5039.9    0.05       0
Bank Sta=4981.7,5020
Exp/Cntr=0.3,0.1

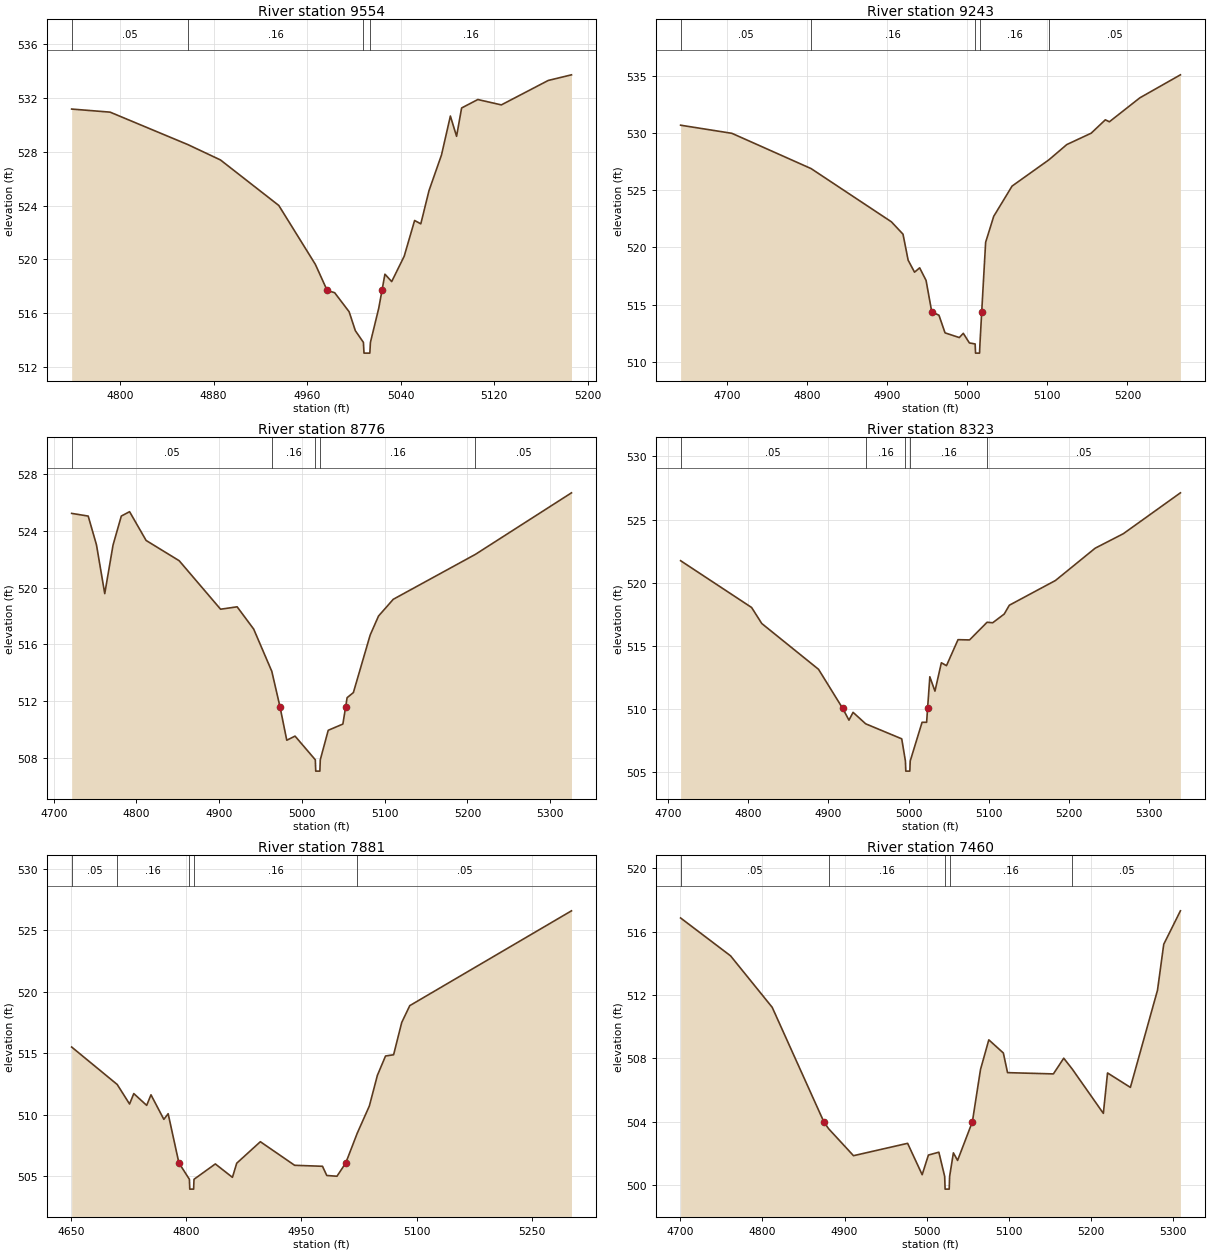
Type RM Length L Ch R = 1,9554,311,311,311
BEGIN DESCRIPTION:
XS3732A
END DESCRIPTION:
XS GIS Cut Line= 4
      2763541.07      7046474.63      2763655.51      7046280.97
      2763692.91      7046177.54      2763699.52      7046085.11
#Sta/Elev= 30
  4758.5  531.19  4791.4  530.96  4858.0  528.54  4885.8  527.40  4935.7  524.01
  4967.0  519.62  4977.1  517.68  4983.5  517.51  4995.9  516.09  5001.2  514.68
  5008.1  513.81  5008.6  513.01  5013.6  513.01  5014.1  513.81  5021.2  516.35
  5024.0  517.68  5026.5  518.89  5032.3  518.34  5043.0  520.23  5051.9  522.89
  5057.2  522.64  5064.2  525.11  5074.9  527.77  5082.5  530.67  5087.8  529.16
  5092.1  531.27  5106.0  531.90  5126.1  531.50  5166.2  533.32  5186.1  533.74
#Mann=4,-1,0
  4758.5    0.05       0  4858.0    0.16       0  5008.1    0.07       0
  5014.1    0.16       0
Bank Sta=4977.1,5024
Exp/Cntr=0.3,0.1

Type RM Length L Ch R = 1,9243,467,467,467
BEGIN DESCRIPTION:
UNT 109 in LFCCL Watershed 15.0
END DESCRIPTION:
XS GIS Cut Line= 3
      2763574.98      7046525.01      2763825.00      7046325.00
      2763875.00      7046025.01
#Sta/Elev= 30
  4641.9  530.68  4706.0  529.97  4804.9  526.89  4905.2  522.24  4919.7  521.16
  4926.1  518.89  4934.1  517.84  4940.5  518.22  4948.5  517.12  4955.6  514.38
  4964.6  514.08  4972.2  512.54  4990.0  512.13  4995.0  512.50  5002.6  511.66
  5009.8  511.57  5010.3  510.77  5015.3  510.77  5015.8  511.57  5018.0  514.38
  5022.9  520.45  5033.0  522.72  5055.9  525.36  5102.0  527.66  5124.3  528.99
  5154.7  529.98  5172.4  531.15  5177.5  530.98  5215.5  533.07  5266.2  535.08
#Mann=5,-1,0
  4641.9    0.05       0  4804.9    0.16       0  5009.8    0.07       0
  5015.8    0.16       0  5102.0    0.05       0
Bank Sta=4955.6,5018
Exp/Cntr=0.3,0.1

Type RM Length L Ch R = 1,8776,453,453,453
BEGIN DESCRIPTION:
UNT 109 in LFCCL Watershed 14.0
END DESCRIPTION:
XS GIS Cut Line= 3
      2764075.00      7046774.95      2764075.00      7046475.00
      2764025.00      7046174.99
#Sta/Elev= 30
  4721.7  525.23  4741.7  525.04  4751.7  523.01  4761.7  519.57  4771.7  522.99
  4781.7  525.04  4791.7  525.35  4811.7  523.32  4851.7  521.89  4901.7  518.47
  4921.7  518.64  4941.7  517.07  4963.6  514.09  4973.5  511.59  4981.7  509.23
  4991.7  509.52  5016.2  507.85  5016.7  507.05  5021.7  507.05  5022.2  507.85
  5031.8  509.93  5049.5  510.37  5052.9  511.59  5054.6  512.23  5062.2  512.59
  5082.5  516.65  5092.6  517.99  5110.4  519.17  5209.7  522.34  5325.8  526.68
#Mann=5,-1,0
  4721.7    0.05       0  4963.6    0.16       0  5016.2    0.07       0
  5022.2    0.16       0  5209.7    0.05       0
Bank Sta=4973.5,5052.9
Exp/Cntr=0.3,0.1

Type RM Length L Ch R = 1,8323,442,442,442
BEGIN DESCRIPTION:
UNT 109 in LFCCL Watershed 13.0
END DESCRIPTION:
XS GIS Cut Line= 3
      2764425.00      7046624.98      2764375.00      7046325.00
      2764174.98      7046074.98
#Sta/Elev= 30
  4715.3  521.74  4804.0  518.03  4816.7  516.76  4887.6  513.13  4917.7  510.04
  4925.6  509.10  4930.7  509.72  4946.5  508.81  4991.5  507.62  4996.1  505.86
  4996.6  505.06  5001.6  505.06  5002.1  505.86  5016.9  508.93  5022.6  508.93
  5023.8  510.04  5026.6  512.54  5033.0  511.40  5041.0  513.65  5047.4  513.42
  5061.8  515.48  5076.2  515.46  5098.1  516.86  5105.1  516.82  5119.5  517.51
  5125.9  518.21  5183.5  520.17  5233.1  522.73  5268.3  523.88  5339.6  527.12
#Mann=5,-1,0
  4715.3    0.05       0  4946.5    0.16       0  4996.1    0.07       0
  5002.1    0.16       0  5098.1    0.05       0
Bank Sta=4917.7,5023.8
Exp/Cntr=0.3,0.1

Type RM Length L Ch R = 1,7881,421,421,421
BEGIN DESCRIPTION:
UNT 109 in LFCCL Watershed 12.0
END DESCRIPTION:
XS GIS Cut Line= 3
      2764724.99      7046374.99      2764575.00      7046075.00
      2764275.02      7045975.01
#Sta/Elev= 30
  4650.4  515.50  4709.8  512.45  4725.9  510.86  4731.4  511.71  4748.2  510.75
  4753.8  511.61  4770.6  509.61  4776.2  510.07  4790.2  506.07  4803.9  504.73
  4804.4  503.93  4809.4  503.93  4809.9  504.73  4837.7  505.98  4860.0  504.89
  4865.6  506.04  4896.4  507.79  4941.1  505.87  4977.4  505.79  4983.0  505.04
  4996.3  504.98  5007.8  506.07  5022.7  508.48  5038.5  510.70  5049.0  513.20
  5059.6  514.77  5070.1  514.87  5080.7  517.50  5091.2  518.87  5302.0  526.59
#Mann=5,-1,0
  4650.4    0.05       0  4709.8    0.16       0  4803.9    0.07       0
  4809.9    0.16       0  5022.7    0.05       0
Bank Sta=4790.2,5007.8
Exp/Cntr=0.3,0.1

Type RM Length L Ch R = 1,7460,421,421,421
BEGIN DESCRIPTION:
UNT 109 in LFCCL Watershed 11.0
END DESCRIPTION:
XS GIS Cut Line= 3
      2764975.00      7046475.00      2764925.00      7046175.00
      2764875.00      7045874.97
#Sta/Elev= 30
  4700.5  516.86  4761.3  514.47  4812.0  511.22  4874.8  504.00  4880.5  503.57
  4910.9  501.86  4976.8  502.64  4994.5  500.66  5002.1  501.90  5014.8  502.08
  5021.9  500.55  5022.4  499.75  5027.4  499.75  5027.9  500.55  5032.5  502.04
  5037.6  501.56  5055.6  504.00  5065.5  507.30  5075.6  509.17  5093.3  508.34
  5098.4  507.10  5154.2  507.02  5166.8  508.01  5177.1  507.33  5215.0  504.53
  5220.1  507.08  5247.9  506.17  5280.9  512.30  5288.5  515.20  5308.8  517.31
#Mann=5,-1,0
  4700.5    0.05       0  4880.5    0.16       0  5021.9    0.07       0
  5027.9    0.16       0  5177.1    0.05       0
Bank Sta=4874.8,5055.6
Exp/Cntr=0.3,0.1

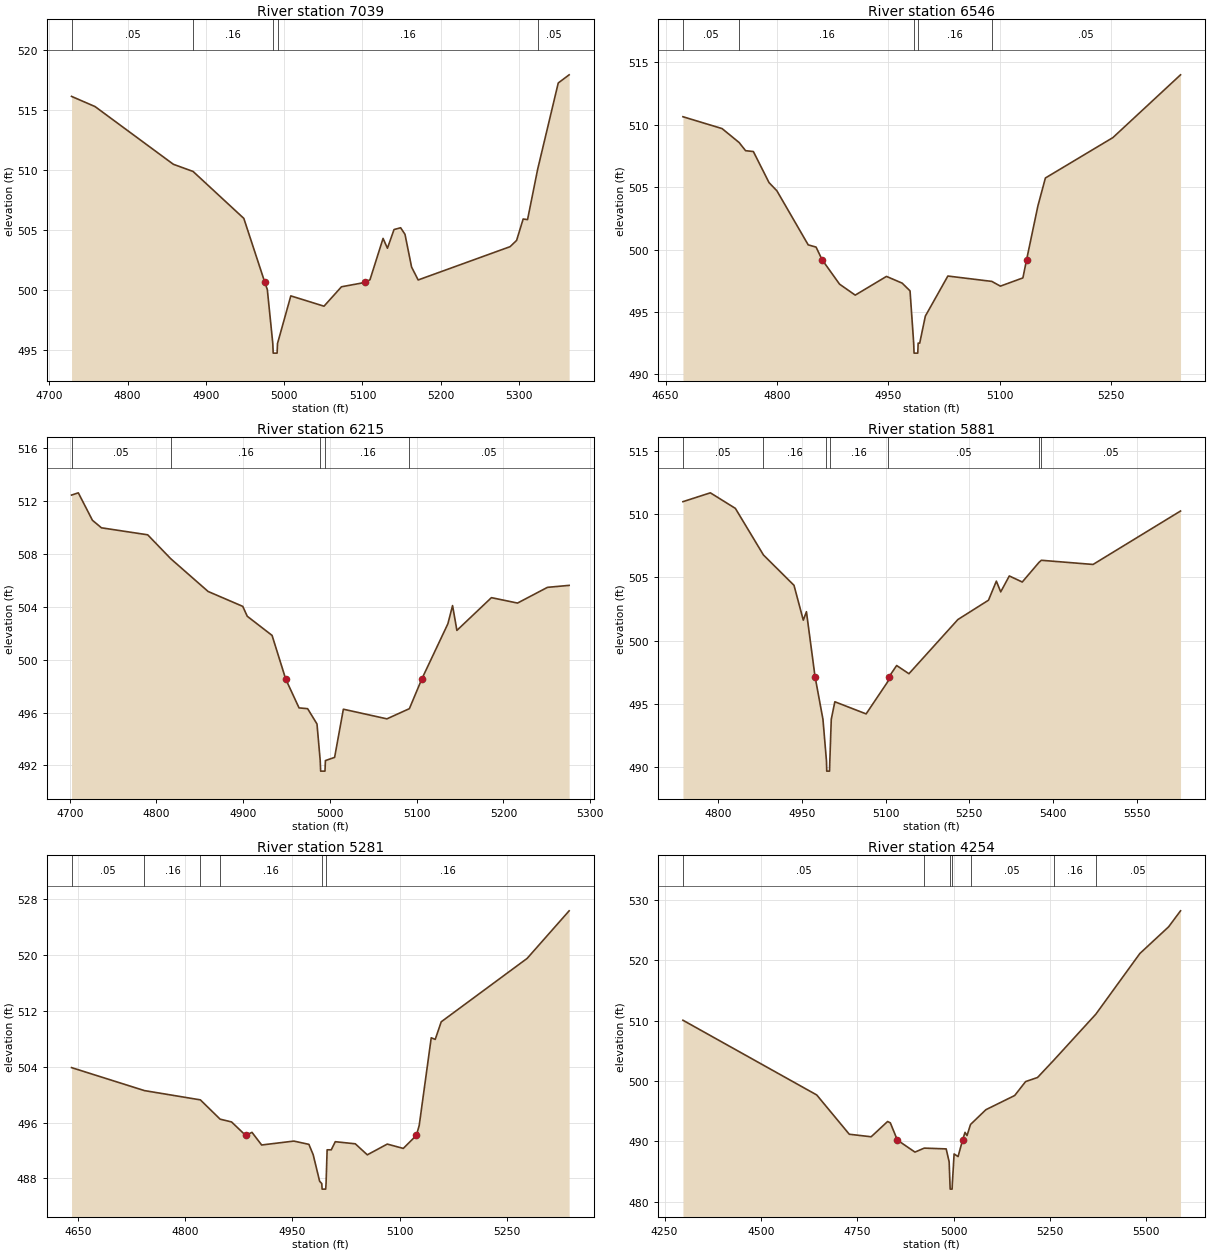
Type RM Length L Ch R = 1,7039,493,493,493
BEGIN DESCRIPTION:
UNT 109 in LFCCL Watershed 10.0
END DESCRIPTION:
XS GIS Cut Line= 3
      2765225.00      7046425.02      2765225.00      7046125.00
      2765075.01      7045825.02
#Sta/Elev= 30
  4728.5  516.15  4758.5  515.30  4858.5  510.48  4883.7  509.88  4948.5  505.96
  4975.3  500.62  4978.5  500.02  4985.5  495.51  4986.0  494.71  4991.0  494.71
  4991.5  495.51  5008.5  499.49  5050.9  498.63  5073.2  500.25  5103.8  500.62
  5109.6  500.84  5126.3  504.29  5131.9  503.47  5140.3  505.03  5148.7  505.18
  5154.3  504.63  5162.7  501.90  5171.1  500.82  5288.5  503.60  5296.8  504.12
  5305.2  505.91  5310.8  505.86  5323.7  510.06  5350.0  517.27  5363.9  517.95
#Mann=5,-1,0
  4728.5    0.05       0  4883.7    0.16       0  4985.5    0.07       0
  4991.5    0.16       0  5323.7    0.05       0
Bank Sta=4975.3,5103.8
Exp/Cntr=0.3,0.1

Type RM Length L Ch R = 1,6546,331,331,331
BEGIN DESCRIPTION:
UNT 109 in LFCCL Watershed 9.0
END DESCRIPTION:
XS GIS Cut Line= 3
      2765475.01      7046374.98      2765575.00      7046075.00
      2765625.01      7045724.96
#Sta/Elev= 30
  4673.4  510.65  4726.1  509.70  4749.1  508.58  4757.7  507.93  4768.2  507.86
  4789.3  505.37  4799.9  504.71  4842.0  500.38  4852.6  500.20  4860.7  499.19
  4884.2  497.23  4905.3  496.35  4947.4  497.85  4968.5  497.31  4979.1  496.69
  4984.0  492.50  4984.5  491.70  4989.5  491.70  4990.0  492.50  4992.1  492.50
  4999.7  494.67  5030.0  497.88  5089.2  497.45  5100.7  497.07  5131.0  497.73
  5136.0  499.19  5151.2  503.50  5161.3  505.74  5252.2  508.98  5343.2  514.01
#Mann=5,-1,0
  4673.4    0.05       0  4749.1    0.16       0  4984.0    0.07       0
  4990.0    0.16       0  5089.2    0.05       0
Bank Sta=4860.7,5136
Exp/Cntr=0.3,0.1

Type RM Length L Ch R = 1,6215,334,334,334
BEGIN DESCRIPTION:
XS3733A
END DESCRIPTION:
XS GIS Cut Line= 3
      2765768.17      7046468.32      2765843.69      7046187.08
      2765817.64      7045905.79
#Sta/Elev= 30
  4702.1  512.47  4709.9  512.64  4726.2  510.56  4736.6  509.99  4789.9  509.46
  4816.3  507.66  4859.5  505.17  4899.5  504.04  4904.7  503.29  4933.3  501.84
  4949.1  498.52  4964.4  496.35  4974.3  496.29  4985.1  495.13  4988.8  492.36
  4989.3  491.56  4994.3  491.56  4994.8  492.36  5005.4  492.60  5015.5  496.25
  5065.7  495.52  5091.6  496.29  5105.8  498.52  5136.0  502.72  5141.4  504.10
  5146.4  502.22  5186.2  504.70  5216.3  504.29  5250.8  505.48  5275.8  505.63
#Mann=5,-1,0
  4702.1    0.05       0  4816.3    0.16       0  4988.8    0.07       0
  4994.8    0.16       0  5091.6    0.05       0
Bank Sta=4949.1,5105.8
Exp/Cntr=0.3,0.1

Type RM Length L Ch R = 1,5881,600,600,600
BEGIN DESCRIPTION:
Mapping XS bb4b1cdb
END DESCRIPTION:
XS GIS Cut Line= 3
      2765941.05      7046548.86      2766065.69      7046302.03
      2765814.08      7045741.09
#Sta/Elev= 30
  4737.0  510.99  4786.1  511.69  4830.9  510.46  4881.2  506.77  4935.9  504.37
  4952.6  501.61  4958.2  502.28  4973.6  497.15  4987.8  493.76  4994.1  490.46
  4994.6  489.66  4999.6  489.66  5000.1  490.46  5002.7  493.77  5009.1  495.15
  5065.1  494.19  5105.1  496.82  5106.5  497.15  5119.8  498.02  5141.8  497.37
  5229.5  501.66  5284.3  503.19  5298.4  504.70  5306.2  503.85  5321.6  505.11
  5344.8  504.63  5374.7  506.18  5379.0  506.35  5471.6  506.02  5628.3  510.25
#Mann=7,-1,0
  4737.0    0.05       0  4881.2    0.16       0  4994.1    0.07       0
  5000.1    0.16       0  5105.1    0.05       0  5374.7    0.16       0
  5379.0    0.05       0
Bank Sta=4973.6,5106.5
Exp/Cntr=0.3,0.1

Type RM Length L Ch R = 1,5281,1027,1027,1027
BEGIN DESCRIPTION:
UNT 109 in LFCCL Watershed 7.0
END DESCRIPTION:
XS GIS Cut Line= 3
      2766125.01      7046424.99      2766325.00      7046125.00
      2766475.02      7045824.96
#Sta/Elev= 30
  4641.2  503.87  4743.1  500.58  4821.4  499.25  4849.0  496.49  4865.0  496.09
  4884.8  494.16  4893.6  494.60  4907.1  492.79  4952.2  493.35  4973.2  492.88
  4979.2  491.40  4988.2  487.60  4991.2  487.27  4991.7  486.47  4996.7  486.47
  4997.2  487.27  4998.7  492.10  5004.5  492.10  5010.1  493.26  5038.1  492.96
  5054.9  491.38  5082.8  492.92  5105.2  492.30  5123.5  494.16  5127.5  495.59
  5144.3  508.14  5149.9  507.91  5158.3  510.43  5278.5  519.51  5337.2  526.32
#Mann=6,-1,0
  4641.2    0.05       0  4743.1    0.16       0  4821.4    0.05       0
  4849.0    0.16       0  4991.2    0.07       0  4997.2    0.16       0
Bank Sta=4884.8,5123.5
Exp/Cntr=0.3,0.1

Type RM Length L Ch R = 1,4254,371,371,371
BEGIN DESCRIPTION:
UNT 109 in LFCCL Watershed 5.0
END DESCRIPTION:
XS GIS Cut Line= 3
      2766375.00      7047025.00      2766825.00      7046525.00
      2766974.99      7045925.04
#Sta/Elev= 30
  4297.7  510.08  4644.9  497.69  4729.3  491.18  4786.1  490.76  4828.7  493.29
  4835.8  493.07  4854.1  490.21  4899.7  488.22  4923.8  488.88  4980.7  488.75
  4988.4  486.62  4990.6  482.88  4991.1  482.08  4996.1  482.08  4996.6  482.88
  5001.3  487.91  5011.6  487.48  5023.3  490.21  5029.6  491.49  5034.8  490.96
  5043.9  492.80  5083.8  495.25  5158.5  497.60  5186.8  499.91  5217.8  500.59
  5260.0  503.46  5369.1  511.09  5483.2  521.14  5557.9  525.57  5588.8  528.22
#Mann=7,-1,0
  4297.7    0.05       0  4923.8    0.16       0  4990.6    0.07       0
  4996.6    0.16       0  5043.9    0.05       0  5260.0    0.16       0
  5369.1    0.05       0
Bank Sta=4854.1,5023.3
Exp/Cntr=0.3,0.1

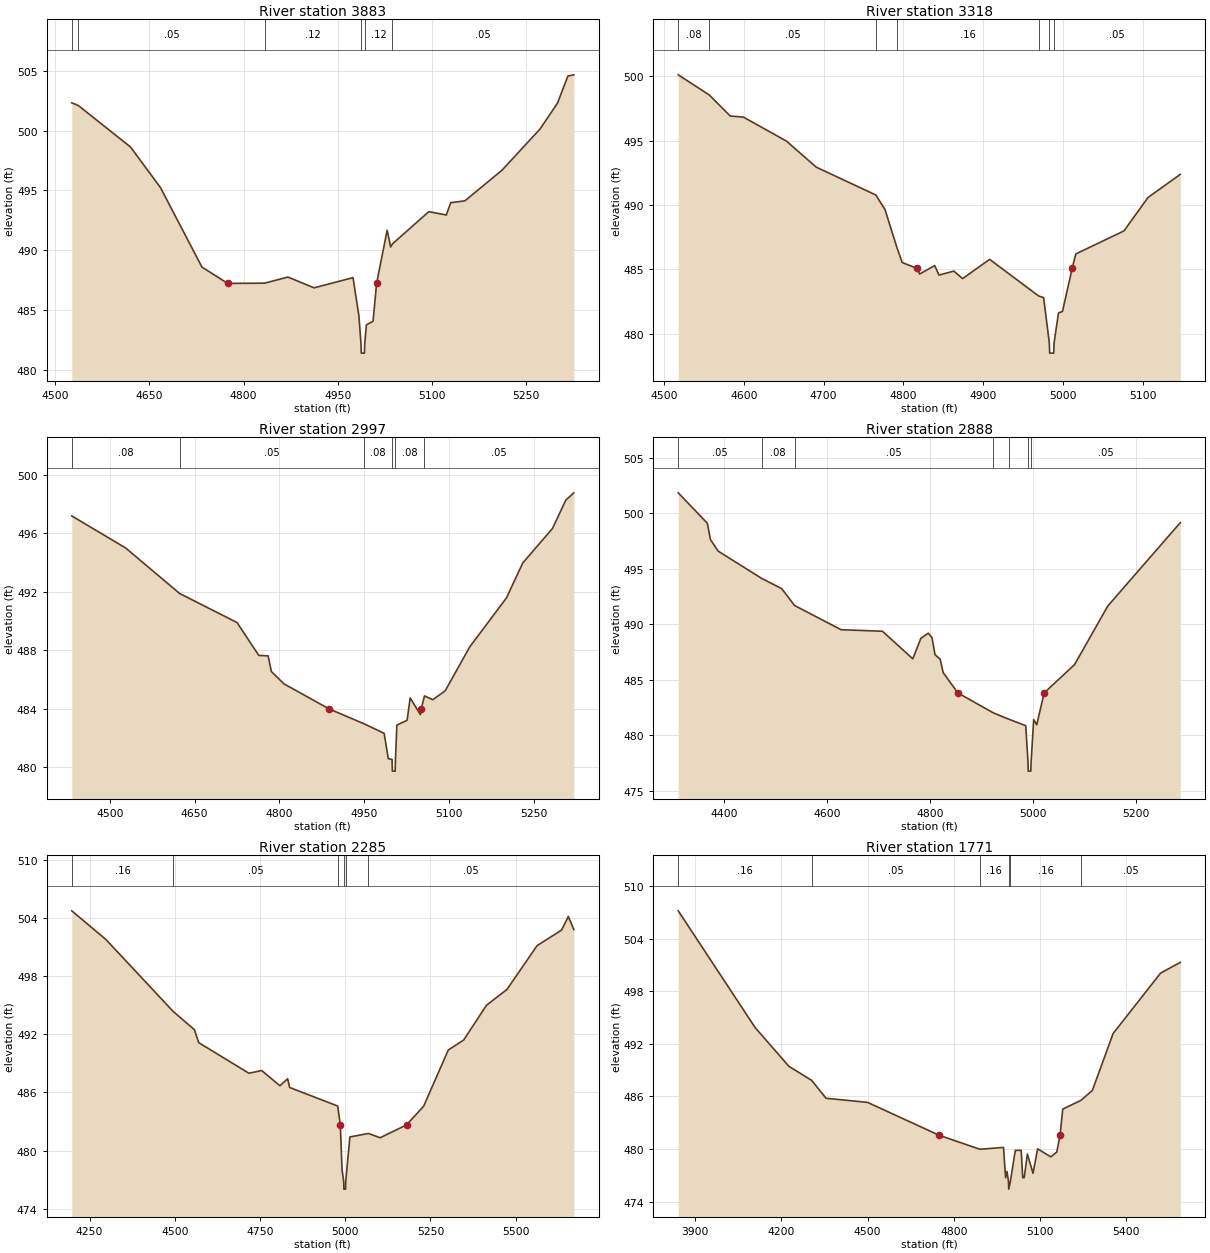
Type RM Length L Ch R = 1,3883,565,565,565
BEGIN DESCRIPTION:
XS3734A
END DESCRIPTION:
XS GIS Cut Line= 3
      2766984.31      7047054.29      2767060.70      7046616.77
      2767223.91      7046300.77
#Sta/Elev= 30
  4526.3  502.31  4536.7  502.09  4619.8  498.63  4667.7  495.23  4733.7  488.60
  4774.8  487.24  4833.4  487.26  4870.7  487.77  4912.3  486.87  4974.3  487.72
  4983.7  484.54  4987.0  482.22  4987.5  481.42  4992.5  481.42  4993.0  482.22
  4995.6  483.78  5006.2  484.08  5011.9  487.24  5028.7  491.68  5034.3  490.28
  5037.2  490.54  5095.1  493.23  5122.9  492.95  5130.0  493.98  5152.5  494.13
  5211.5  496.68  5272.3  500.13  5300.1  502.29  5316.6  504.55  5326.1  504.65
#Mann=6,-1,0
  4526.3    0.08       0  4536.7    0.05       0  4833.4    0.12       0
  4987.0    0.07       0  4993.0    0.12       0  5037.2    0.05       0
Bank Sta=4774.8,5011.9
Exp/Cntr=0.3,0.1

Type RM Length L Ch R = 1,3318,321,321,321
BEGIN DESCRIPTION:
XS3735A
END DESCRIPTION:
XS GIS Cut Line= 3
      2767199.60      7047085.50      2767338.48      7046738.30
      2767366.25      7046484.87
#Sta/Elev= 30
  4518.0  500.11  4556.8  498.55  4583.2  496.91  4599.6  496.83  4653.4  494.97
  4690.9  492.94  4765.5  490.78  4777.0  489.65  4792.2  486.65  4798.6  485.53
  4817.0  485.09  4820.4  484.64  4839.2  485.30  4844.6  484.56  4863.2  484.87
  4874.2  484.29  4908.1  485.78  4969.4  482.94  4975.7  482.81  4982.8  479.30
  4983.3  478.50  4988.3  478.50  4988.8  479.30  4994.3  481.62  4999.3  481.74
  5011.5  485.09  5016.0  486.20  5076.3  487.99  5106.5  490.59  5146.9  492.38
#Mann=7,-1,0
  4518.0    0.08       0  4556.8    0.05       0  4765.5    0.12       0
  4792.2    0.16       0  4969.4    0.05       0  4982.8    0.03       0
  4988.8    0.05       0
Bank Sta=4817,5011.5
Exp/Cntr=0.3,0.1

Type RM Length L Ch R = 1,2997,109,109,109
BEGIN DESCRIPTION:
XS3736A
END DESCRIPTION:
XS GIS Cut Line= 4
      2767282.88      7047116.78      2767446.12      7047075.10
      2767626.67      7046724.41      2767755.15      7046425.79
#Sta/Elev= 30
  4432.7  497.19  4527.8  495.00  4623.5  491.88  4725.0  489.89  4763.5  487.64
  4780.0  487.61  4785.7  486.54  4807.8  485.70  4887.3  483.99  4949.6  482.96
  4985.2  482.31  4992.5  480.57  4999.2  480.52  4999.7  479.72  5004.7  479.72
  5005.2  480.52  5007.7  482.87  5025.8  483.20  5031.2  484.73  5049.3  483.59
  5050.9  483.99  5056.5  484.87  5071.2  484.61  5093.0  485.21  5136.5  488.22
  5201.4  491.57  5230.4  493.97  5282.9  496.33  5306.5  498.27  5320.7  498.77
#Mann=6,-1,0
  4432.7    0.08       0  4623.5    0.05       0  4949.6    0.08       0
  4999.2    0.07       0  5005.2    0.08       0  5056.5    0.05       0
Bank Sta=4887.3,5050.9
Exp/Cntr=0.3,0.1

Type RM Length L Ch R = 1,2888,603,603,603
BEGIN DESCRIPTION:
XS3737A
END DESCRIPTION:
XS GIS Cut Line= 4
      2767303.77      7047241.76      2767525.98      7047095.94
      2767713.48      7046769.55      2767887.10      7046484.80
#Sta/Elev= 30
  4311.3  501.84  4367.9  499.10  4373.9  497.63  4389.0  496.59  4473.7  494.13
  4512.6  493.21  4537.3  491.70  4627.7  489.52  4708.2  489.38  4767.1  486.90
  4782.9  488.75  4797.3  489.21  4804.5  488.80  4810.3  487.27  4820.3  486.87
  4826.1  485.66  4854.7  483.83  4923.4  482.04  4953.4  481.47  4986.7  480.88
  4991.0  477.59  4991.5  476.79  4996.5  476.79  4997.0  477.59  5002.1  481.43
  5008.0  480.96  5022.4  483.83  5081.5  486.38  5146.2  491.66  5287.0  499.16
#Mann=7,-1,0
  4311.3    0.05       0  4473.7    0.08       0  4537.3    0.05       0
  4923.4    0.16       0  4953.4    0.05       0  4991.0    0.03       0
  4997.0    0.05       0
Bank Sta=4854.7,5022.4
Exp/Cntr=0.3,0.1

Type RM Length L Ch R = 1,2285,514,514,514
BEGIN DESCRIPTION:
XS3738A
END DESCRIPTION:
XS GIS Cut Line= 4
      2767216.86      7047392.11      2767925.28      7047012.60
      2768071.12      7046727.88      2768055.26      7046378.92
#Sta/Elev= 30
  4197.7  504.73  4297.7  501.78  4495.6  494.34  4557.6  492.47  4570.0  491.14
  4717.4  487.98  4755.0  488.26  4808.2  486.69  4830.9  487.41  4837.0  486.51
  4977.8  484.60  4985.5  482.65  4990.5  478.06  4995.4  476.83  4995.9  476.03
  5000.9  476.03  5001.4  476.83  5013.6  481.41  5068.0  481.77  5102.4  481.33
  5179.7  482.65  5230.0  484.58  5302.3  490.38  5347.5  491.41  5414.3  494.99
  5474.3  496.62  5562.8  501.14  5634.5  502.74  5654.5  504.15  5670.6  502.79
#Mann=6,-1,0
  4197.7    0.16       0  4495.6    0.05       0  4977.8    0.16       0
  4995.4    0.07       0  5001.4    0.16       0  5068.0    0.05       0
Bank Sta=4985.5,5179.7
Exp/Cntr=0.3,0.1

Type RM Length L Ch R = 1,1771,412,412,412
BEGIN DESCRIPTION:
XS3739A
END DESCRIPTION:
XS GIS Cut Line= 4
      2767258.41      7047502.09      2768230.84      7047088.99
      2768262.96      7046949.72      2768126.48      7046418.43
#Sta/Elev= 30
  3840.8  507.18  4108.7  493.85  4226.3  489.43  4305.4  487.83  4355.4  485.79
  4499.9  485.32  4749.8  481.56  4891.2  479.97  4973.3  480.18  4980.5  476.72
  4985.6  477.43  4990.8  476.22  4991.3  475.42  4996.8  476.22  5014.3  479.84
  5034.8  479.85  5040.1  476.73  5045.3  476.73  5056.4  479.42  5076.1  477.23
  5092.0  480.02  5138.1  479.10  5158.7  479.65  5170.2  481.56  5179.4  484.55
  5242.3  485.54  5282.6  486.68  5354.9  493.18  5520.1  500.07  5588.8  501.30
#Mann=6,-1,0
  3840.8    0.16       0  4305.4    0.05       0  4891.2    0.16       0
  4990.8    0.07       0  4996.8    0.16       0  5242.3    0.05       0
Bank Sta=4749.8,5170.2
Exp/Cntr=0.3,0.1

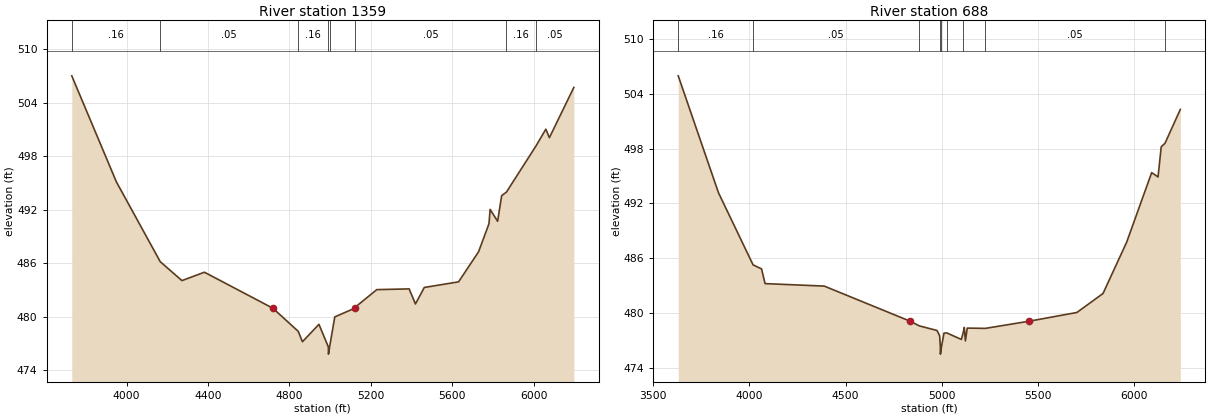
Type RM Length L Ch R = 1,1359,671,671,671
BEGIN DESCRIPTION:
XS3740A
END DESCRIPTION:
XS GIS Cut Line= 4
      2767273.10      7047541.19      2768384.15      7047160.23
      2768550.28      7046977.88      2768895.98      7045991.64
#Sta/Elev= 30
  3731.0  507.00  3950.1  495.12  4165.6  486.17  4272.2  484.05  4382.6  484.99
  4718.5  480.96  4843.2  478.37  4864.2  477.20  4945.2  479.15  4991.5  476.61
  4992.0  475.81  4997.5  476.61  5022.9  479.98  5121.2  480.96  5121.9  481.04
  5229.5  483.04  5388.2  483.12  5419.2  481.43  5462.6  483.28  5631.0  483.91
  5729.3  487.28  5780.5  490.43  5786.0  492.03  5822.9  490.70  5842.7  493.57
  5866.2  493.97  6011.9  499.16  6059.8  501.02  6077.2  500.07  6197.3  505.70
#Mann=8,-1,0
  3731.0    0.16       0  4165.6    0.05       0  4843.2    0.16       0
  4991.5    0.07       0  4997.5    0.16       0  5121.9    0.05       0
  5866.2    0.16       0  6011.9    0.05       0
Bank Sta=4718.5,5121.2
Exp/Cntr=0.3,0.1

Type RM Length L Ch R = 1,688,0,0,0
BEGIN DESCRIPTION:
UNT 109 in LFCCL Watershed 4.0
END DESCRIPTION:
XS GIS Cut Line= 4
      2767297.57      7047575.41      2768661.39      7047345.94
      2768828.06      7047241.77      2769040.09      7046231.61
#Sta/Elev= 30
  3629.6  505.96  3838.9  493.16  4019.0  485.26  4063.0  484.82  4081.2  483.21
  4389.0  482.94  4836.4  479.09  4884.1  478.58  4975.7  478.08  4989.5  477.49
  4993.0  476.29  4993.5  475.49  4999.0  476.29  5011.9  477.79  5026.9  477.81
  5102.3  477.10  5112.0  477.85  5117.6  478.41  5123.5  476.94  5132.9  478.34
  5227.4  478.31  5453.7  479.09  5703.4  480.05  5839.3  482.13  5962.0  487.73
  6092.3  495.36  6125.4  494.89  6142.1  498.19  6161.5  498.57  6241.3  502.28
#Mann=9,-1,0
  3629.6    0.16       0  4019.0    0.05       0  4884.1    0.16       0
  4993.0    0.07       0  4999.0    0.16       0  5026.9    0.12       0
  5112.0    0.16       0  5227.4    0.05       0  6161.5    0.16       0
Bank Sta=4836.4,5453.7
Exp/Cntr=0.3,0.1

Chan Stop Cuts=-1