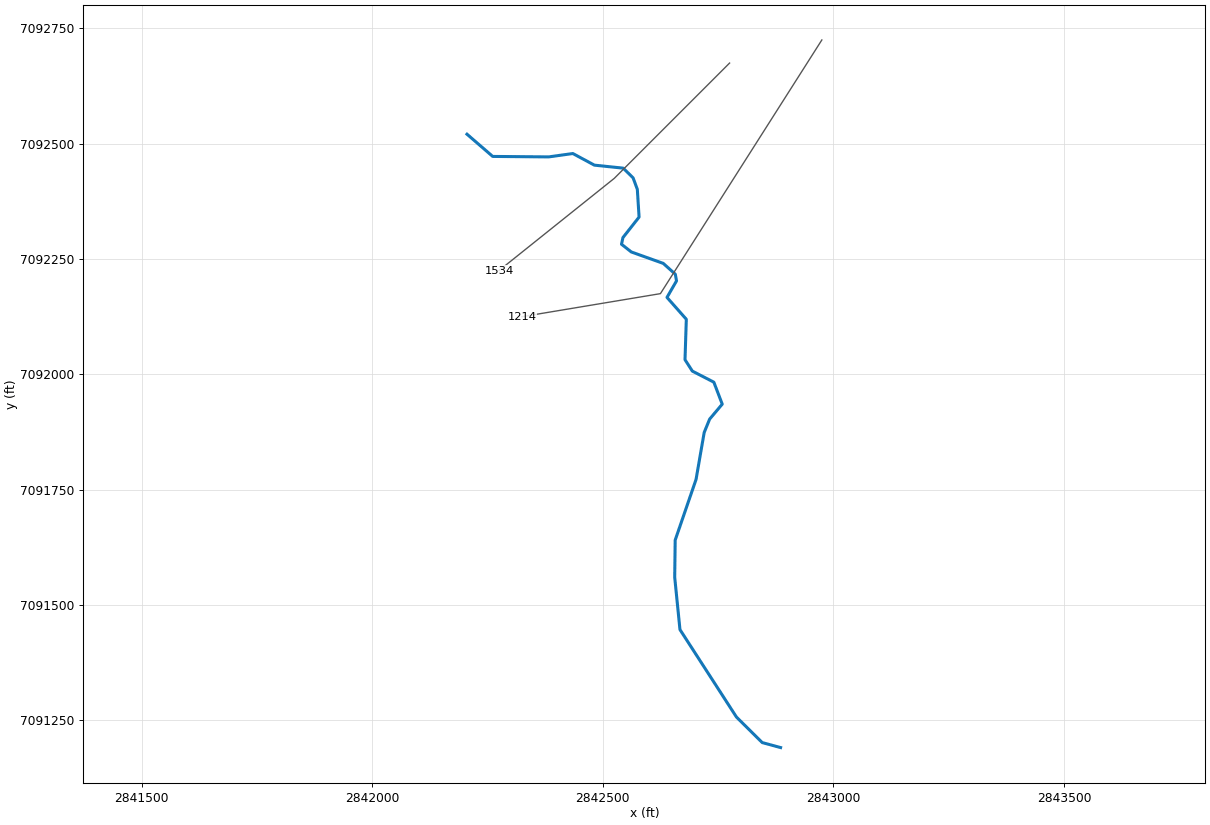
--- UNT 112 in LFCCL Watershed.prj (project) ---

Proj Title=UNT 112 in LFCCL Watershed Base Level Engineering
Current Plan=p01
Default Exp/Contr=0.3,0.1
English Units
Geom File=g01
Flow File=f01
Plan File=p01
BEGIN DESCRIPTION:
UNT 112 in LFCCL Watershed
END DESCRIPTION:

--- UNT 112 in LFCCL Watershed.p01 (plan) ---

Plan Title=Multiple Run
Short Identifier=Multiple
Geom File=g01
Flow File=f01
Subcritical Flow
K Sum by GR= 0
Std Step Tol= 0.01
Critical Tol= 0.01
Num of Std Step Trials= 20
Max Error Tol= 0.3
Flow Tol Ratio= 0.001
Split Flow NTrial= 30
Split Flow Tol= 0.02
Split Flow Ratio= 0.02
Log Output Level= 0
Friction Slope Method= 1
Unsteady Friction Slope Method= 2
Unsteady Bridges Friction Slope Method= 1
Parabolic Critical Depth
Global Vel Dist=  1 , 1 , 1
Global Log Level= 0
CheckData=True
Encroach Param= -1, 0, 0, 0
BEGIN DESCRIPTION:
Multiple Run
END DESCRIPTION:

--- UNT 112 in LFCCL Watershed.f01 (steady flow) ---

Flow Title=Multiple
Number of Profiles=7
Profile Names=10-year,25-year,50-year,1pct_min,100-year,1pct_plu,500-year
River Rch & RM= UNT 112 in LFCCL,Reach-1,1534
     866    1174    1428     861    1718    3428    2480
Boundary for River Rch & Prof#=UNT 112 in LFCCL,Reach-1,1
Up Type=0
Dn Type=3
Dn Slope=0.005
Boundary for River Rch & Prof#=UNT 112 in LFCCL,Reach-1,2
Up Type=0
Dn Type=3
Dn Slope=0.005
Boundary for River Rch & Prof#=UNT 112 in LFCCL,Reach-1,3
Up Type=0
Dn Type=3
Dn Slope=0.005
Boundary for River Rch & Prof#=UNT 112 in LFCCL,Reach-1,4
Up Type=0
Dn Type=3
Dn Slope=0.005
Boundary for River Rch & Prof#=UNT 112 in LFCCL,Reach-1,5
Up Type=0
Dn Type=3
Dn Slope=0.005
Boundary for River Rch & Prof#=UNT 112 in LFCCL,Reach-1,6
Up Type=0
Dn Type=3
Dn Slope=0.005
Boundary for River Rch & Prof#=UNT 112 in LFCCL,Reach-1,7
Up Type=0
Dn Type=3
Dn Slope=0.005

--- UNT 112 in LFCCL Watershed.g01 (geometry) ---

Geom Title=Existing Conditions

River Reach=UNT 112 in LFCCL,Reach-1
Reach XY= 30
      2842205.59      7092520.71      2842261.38      7092472.50
      2842382.82      7092471.49      2842435.14      7092478.79
      2842481.79      7092453.63      2842544.35      7092447.08
      2842565.77      7092426.05      2842574.92      7092401.22
      2842578.74      7092340.97      2842543.76      7092296.56
      2842540.61      7092282.13      2842561.93      7092265.34
      2842631.19      7092240.56      2842657.29      7092217.15
      2842659.93      7092202.69      2842639.26      7092166.82
      2842681.17      7092119.42      2842678.32      7092031.75
      2842694.21      7092007.03      2842740.86      7091983.02
      2842759.05      7091935.33      2842731.72      7091902.91
      2842719.88      7091873.81      2842702.26      7091772.09
      2842657.02      7091640.52      2842655.99      7091559.98
      2842667.38      7091446.54      2842789.86      7091256.91
      2842845.75      7091201.56      2842885.59      7091190.71

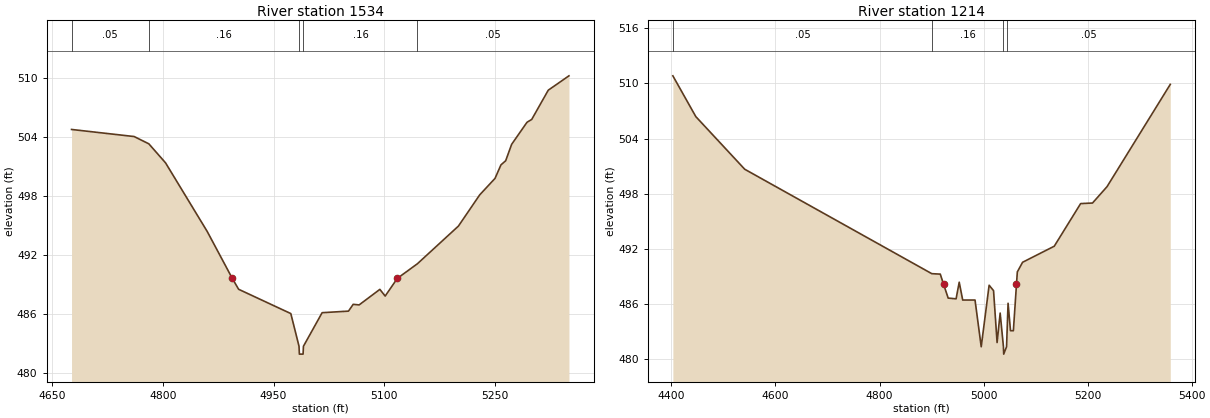
Type RM Length L Ch R = 1,1534,320,320,320
BEGIN DESCRIPTION:
UNT 112 in LFCCL Watershed 2.0
END DESCRIPTION:
XS GIS Cut Line= 3
      2842774.98      7092674.98      2842525.00      7092425.00
      2842274.99      7092224.99
#Sta/Elev= 30
  4676.4  504.79  4761.2  504.07  4781.1  503.33  4803.7  501.40  4860.2  494.42
  4894.1  489.66  4902.7  488.55  4973.4  486.08  4984.5  482.76  4985.0  481.96
  4990.0  481.96  4990.5  482.76  5015.8  486.17  5051.5  486.33  5057.9  487.02
  5065.9  486.96  5094.0  488.54  5101.2  487.86  5117.7  489.66  5144.8  491.14
  5200.4  494.97  5229.2  498.14  5250.0  499.82  5258.0  501.19  5264.4  501.61
  5272.5  503.28  5293.3  505.52  5299.7  505.81  5322.1  508.78  5350.1  510.24
#Mann=5,-1,0
  4676.4    0.05       0  4781.1    0.16       0  4984.5    0.07       0
  4990.5    0.16       0  5144.8    0.05       0
Bank Sta=4894.1,5117.7
Exp/Cntr=0.3,0.1

Type RM Length L Ch R = 1,1214,0,0,0
BEGIN DESCRIPTION:
UNT 112 in LFCCL Watershed 1.0
END DESCRIPTION:
XS GIS Cut Line= 3
      2842975.03      7092725.04      2842625.00      7092175.00
      2842325.01      7092125.00
#Sta/Elev= 30
  4402.8  510.83  4446.9  506.39  4540.9  500.66  4900.5  489.29  4916.8  489.24
  4923.1  488.14  4932.0  486.63  4947.2  486.55  4953.2  488.36  4959.9  486.42
  4983.6  486.42  4995.5  481.33  5010.7  488.03  5019.2  487.44  5026.0  481.79
  5031.9  485.00  5038.2  481.33  5038.7  480.53  5044.2  481.33  5047.1  486.07
  5051.8  483.08  5057.3  483.08  5063.3  488.14  5064.9  489.48  5075.0  490.53
  5135.9  492.28  5186.6  496.92  5209.4  496.98  5237.3  498.76  5358.9  509.90
#Mann=4,-1,0
  4402.8    0.05       0  4900.5    0.16       0  5038.2    0.07       0
  5044.2    0.05       0
Bank Sta=4923.1,5063.3
Exp/Cntr=0.3,0.1

Chan Stop Cuts=-1