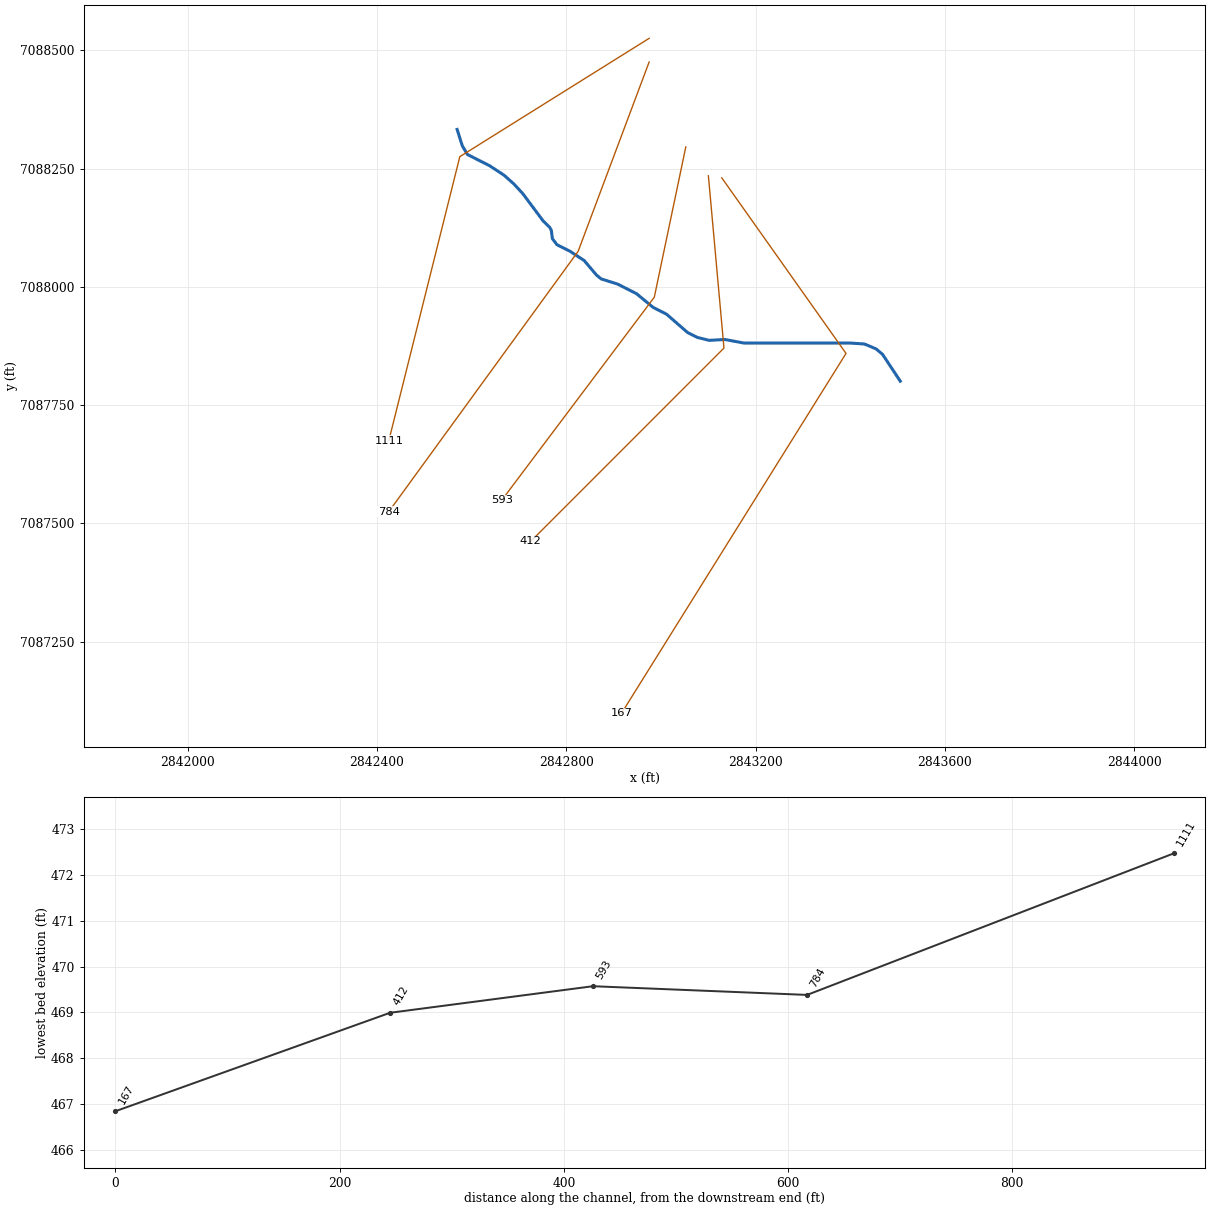
--- UNT 113 in LFCCL Watershed.prj (project) ---

Proj Title=UNT 113 in LFCCL Watershed Base Level Engineering
Current Plan=p01
Default Exp/Contr=0.3,0.1
English Units
Geom File=g01
Flow File=f01
Plan File=p01
BEGIN DESCRIPTION:
UNT 113 in LFCCL Watershed
END DESCRIPTION:

--- UNT 113 in LFCCL Watershed.p01 (plan) ---

Plan Title=Multiple Run
Short Identifier=Multiple
Geom File=g01
Flow File=f01
Subcritical Flow
K Sum by GR= 0
Std Step Tol= 0.01
Critical Tol= 0.01
Num of Std Step Trials= 20
Max Error Tol= 0.3
Flow Tol Ratio= 0.001
Split Flow NTrial= 30
Split Flow Tol= 0.02
Split Flow Ratio= 0.02
Log Output Level= 0
Friction Slope Method= 1
Unsteady Friction Slope Method= 2
Unsteady Bridges Friction Slope Method= 1
Parabolic Critical Depth
Global Vel Dist=  1 , 1 , 1
Global Log Level= 0
CheckData=True
Encroach Param= -1, 0, 0, 0
BEGIN DESCRIPTION:
Multiple Run
END DESCRIPTION:

--- UNT 113 in LFCCL Watershed.f01 (steady flow) ---

Flow Title=Multiple
Number of Profiles=7
Profile Names=10-year,25-year,50-year,1pct_min,100-year,1pct_plu,500-year
River Rch & RM= UNT 113 in LFCCL,Reach-1,1111
     548     725     867     515    1028    2052    1442
Boundary for River Rch & Prof#=UNT 113 in LFCCL,Reach-1,1
Up Type=0
Dn Type=3
Dn Slope=0.005
Boundary for River Rch & Prof#=UNT 113 in LFCCL,Reach-1,2
Up Type=0
Dn Type=3
Dn Slope=0.005
Boundary for River Rch & Prof#=UNT 113 in LFCCL,Reach-1,3
Up Type=0
Dn Type=3
Dn Slope=0.005
Boundary for River Rch & Prof#=UNT 113 in LFCCL,Reach-1,4
Up Type=0
Dn Type=3
Dn Slope=0.005
Boundary for River Rch & Prof#=UNT 113 in LFCCL,Reach-1,5
Up Type=0
Dn Type=3
Dn Slope=0.005
Boundary for River Rch & Prof#=UNT 113 in LFCCL,Reach-1,6
Up Type=0
Dn Type=3
Dn Slope=0.005
Boundary for River Rch & Prof#=UNT 113 in LFCCL,Reach-1,7
Up Type=0
Dn Type=3
Dn Slope=0.005

--- UNT 113 in LFCCL Watershed.g01 (geometry) ---

Geom Title=Existing Conditions

River Reach=UNT 113 in LFCCL,Reach-1
Reach XY= 30
      2842569.31      7088332.50      2842580.27      7088297.86
      2842591.17      7088279.53      2842638.14      7088255.80
      2842668.36      7088235.90      2842689.05      7088217.50
      2842707.95      7088197.03      2842751.12      7088139.15
      2842765.17      7088125.40      2842768.26      7088119.42
      2842770.62      7088101.74      2842780.14      7088089.10
      2842807.75      7088075.17      2842837.83      7088055.48
      2842863.60      7088025.04      2842873.56      7088016.72
      2842908.22      7088005.86      2842948.18      7087985.63
      2842983.32      7087956.61      2843011.56      7087942.34
      2843056.68      7087903.10      2843076.63      7087893.17
      2843101.72      7087886.92      2843135.13      7087888.71
      2843175.33      7087881.17      2843401.41      7087881.11
      2843430.13      7087879.15      2843454.75      7087868.66
      2843468.15      7087857.31      2843505.59      7087800.71

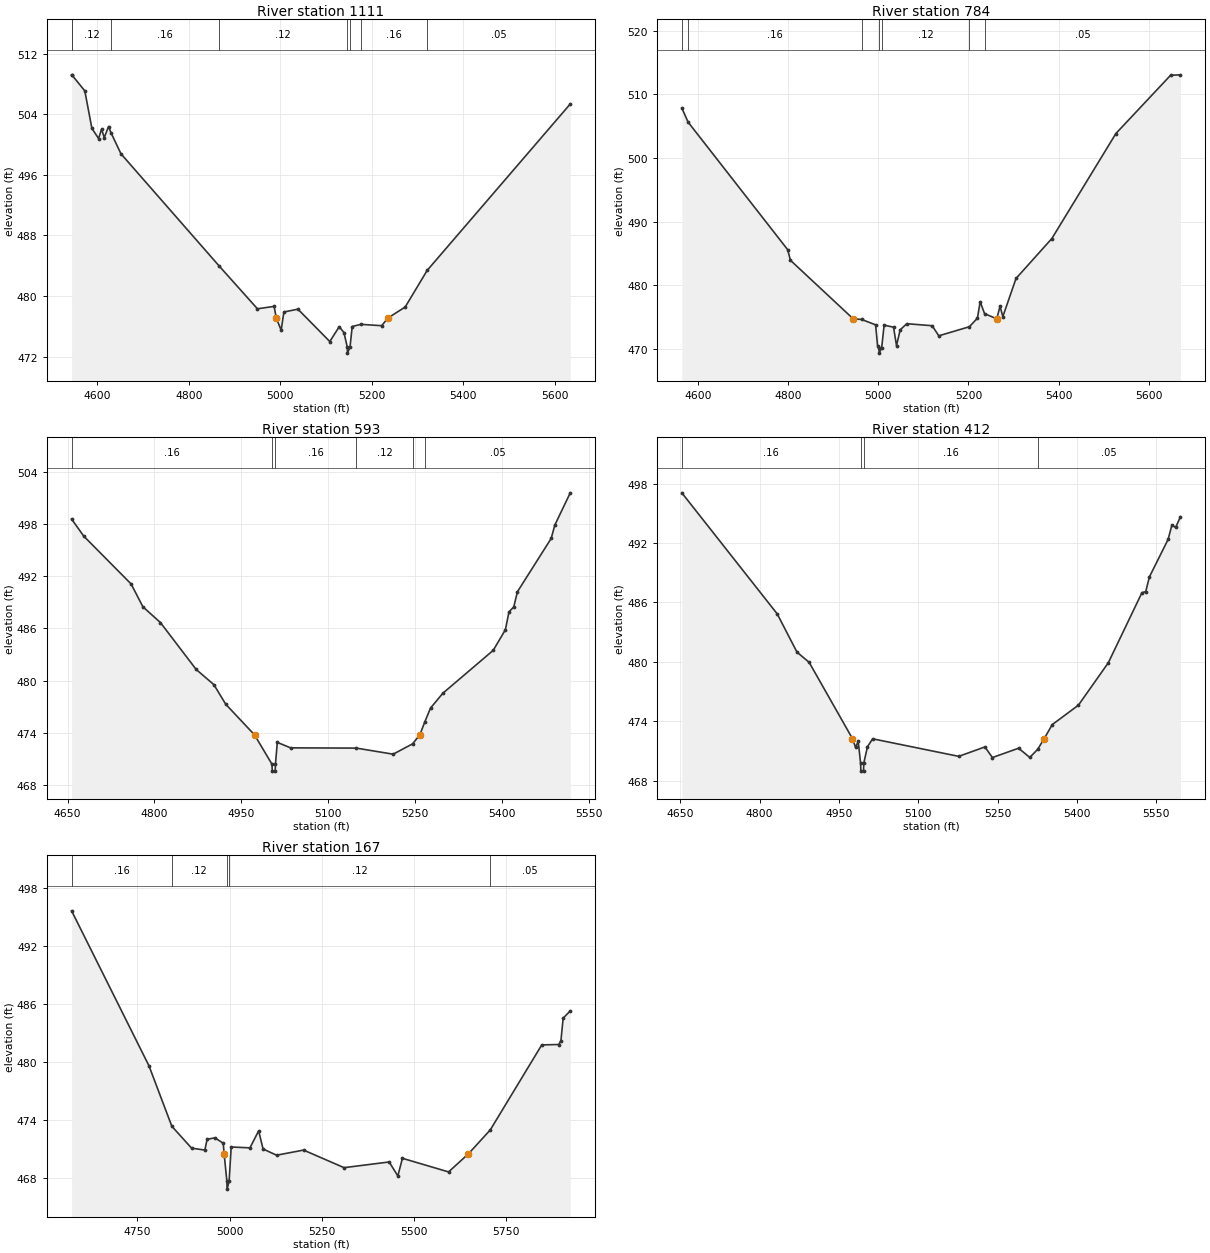
Type RM Length L Ch R = 1,1111,327,327,327
BEGIN DESCRIPTION:
UNT 113 in LFCCL Watershed 3.0
END DESCRIPTION:
XS GIS Cut Line= 3
      2842975.03      7088525.02      2842575.00      7088275.00
      2842425.00      7087675.00
#Sta/Elev= 30
  4543.8  509.20  4544.3  509.20  4572.7  507.08  4588.1  502.15  4602.8  500.79
  4609.3  502.03  4615.2  500.92  4624.6  502.38  4630.2  501.52  4651.7  498.78
  4866.7  483.95  4950.1  478.32  4986.6  478.64  4991.3  477.10  5002.0  475.49
  5007.9  477.90  5038.7  478.27  5108.3  474.00  5128.9  475.96  5139.2  475.19
  5146.5  473.27  5147.0  472.47  5152.5  473.27  5157.3  475.98  5176.2  476.27
  5221.7  476.09  5235.4  477.10  5273.2  478.56  5321.2  483.39  5634.0  505.35
#Mann=8,-1,0
  4543.8    0.16       0  4544.3    0.12       0  4630.2    0.16       0
  4866.7    0.12       0  5146.5    0.07       0  5152.5    0.12       0
  5176.2    0.16       0  5321.2    0.05       0
Bank Sta=4991.3,5235.4
Exp/Cntr=0.3,0.1

Type RM Length L Ch R = 1,784,191,191,191
BEGIN DESCRIPTION:
UNT 113 in LFCCL Watershed 2.0
END DESCRIPTION:
XS GIS Cut Line= 3
      2842975.01      7088475.02      2842825.00      7088075.00
      2842425.00      7087525.00
#Sta/Elev= 30
  4563.5  507.85  4577.4  505.64  4798.5  485.62  4804.7  483.95  4944.1  474.76
  4962.6  474.67  4993.8  473.82  4998.1  470.56  5001.2  470.18  5001.7  469.38
  5007.2  470.18  5012.7  473.77  5033.6  473.45  5040.2  470.56  5048.3  473.03
  5063.0  474.00  5119.4  473.68  5134.1  472.10  5202.0  473.52  5219.9  474.87
  5226.0  477.45  5235.7  475.58  5262.9  474.76  5270.1  476.75  5276.3  475.11
  5305.6  481.10  5385.2  487.37  5527.4  503.85  5648.8  512.99  5670.8  513.06
#Mann=7,-1,0
  4563.5    0.12       0  4577.4    0.16       0  4962.6    0.12       0
  5001.2    0.07       0  5007.2    0.12       0  5202.0    0.16       0
  5235.7    0.05       0
Bank Sta=4944.1,5262.9
Exp/Cntr=0.3,0.1

Type RM Length L Ch R = 1,593,181,181,181
BEGIN DESCRIPTION:
XS3741A
END DESCRIPTION:
XS GIS Cut Line= 3
      2843052.45      7088295.48      2842985.94      7087978.06
      2842663.63      7087549.18
#Sta/Elev= 30
  4656.9  498.59  4677.8  496.63  4759.6  491.12  4780.0  488.49  4810.3  486.67
  4871.9  481.28  4902.6  479.52  4923.0  477.27  4972.7  473.74  5002.8  470.37
  5003.3  469.57  5008.3  469.57  5008.8  470.37  5012.0  472.88  5034.9  472.25
  5148.6  472.22  5212.0  471.52  5245.5  472.71  5258.0  473.74  5266.7  475.25
  5276.5  476.83  5297.8  478.54  5384.8  483.48  5405.7  485.84  5411.9  487.90
  5420.2  488.48  5426.5  490.22  5484.8  496.36  5491.1  497.90  5517.7  501.61
#Mann=6,-1,0
  4656.9    0.16       0  5002.8    0.07       0  5008.8    0.16       0
  5148.6    0.12       0  5245.5    0.16       0  5266.7    0.05       0
Bank Sta=4972.7,5258
Exp/Cntr=0.3,0.1

Type RM Length L Ch R = 1,412,245,245,245
BEGIN DESCRIPTION:
Mapping XS bd1fb6f8
END DESCRIPTION:
XS GIS Cut Line= 3
      2843100.19      7088234.69      2843133.10      7087870.60
      2842724.79      7087462.16
#Sta/Elev= 30
  4652.8  497.06  4833.2  484.85  4870.6  480.99  4893.5  479.97  4975.5  472.27
  4981.4  471.38  4986.4  472.00  4990.9  469.79  4991.4  468.99  4996.4  468.99
  4996.9  469.79  5003.9  471.45  5013.7  472.25  5176.5  470.48  5226.0  471.43
  5240.2  470.36  5289.7  471.30  5310.9  470.37  5325.8  471.19  5338.2  472.27
  5353.3  473.68  5402.8  475.64  5459.4  479.92  5523.0  486.99  5530.1  487.09
  5537.2  488.59  5572.5  492.36  5579.6  493.80  5586.7  493.57  5595.9  494.65
#Mann=4,-1,0
  4652.8    0.16       0  4990.9    0.07       0  4996.9    0.16       0
  5325.8    0.05       0
Bank Sta=4975.5,5338.2
Exp/Cntr=0.3,0.1

Type RM Length L Ch R = 1,167,0,0,0
BEGIN DESCRIPTION:
UNT 113 in LFCCL Watershed 1.0
END DESCRIPTION:
XS GIS Cut Line= 3
      2843128.41      7088230.35      2843390.99      7087859.27
      2842916.48      7087098.75
#Sta/Elev= 30
  4572.0  495.63  4781.6  479.60  4843.6  473.34  4897.1  471.08  4933.0  470.88
  4939.1  471.99  4960.0  472.15  4982.8  471.59  4985.3  470.49  4992.7  467.64
  4993.2  466.84  4998.7  467.64  5004.4  471.20  5055.2  471.11  5078.8  472.87
  5090.8  470.99  5127.4  470.35  5200.5  470.88  5310.2  469.06  5432.4  469.65
  5455.9  468.20  5468.3  470.03  5593.3  468.62  5647.1  470.49  5706.4  472.97
  5845.8  481.76  5891.8  481.80  5897.7  482.18  5903.8  484.53  5923.0  485.28
#Mann=5,-1,0
  4572.0    0.16       0  4843.6    0.12       0  4992.7    0.07       0
  4998.7    0.12       0  5706.4    0.05       0
Bank Sta=4985.3,5647.1
Exp/Cntr=0.3,0.1

Chan Stop Cuts=-1