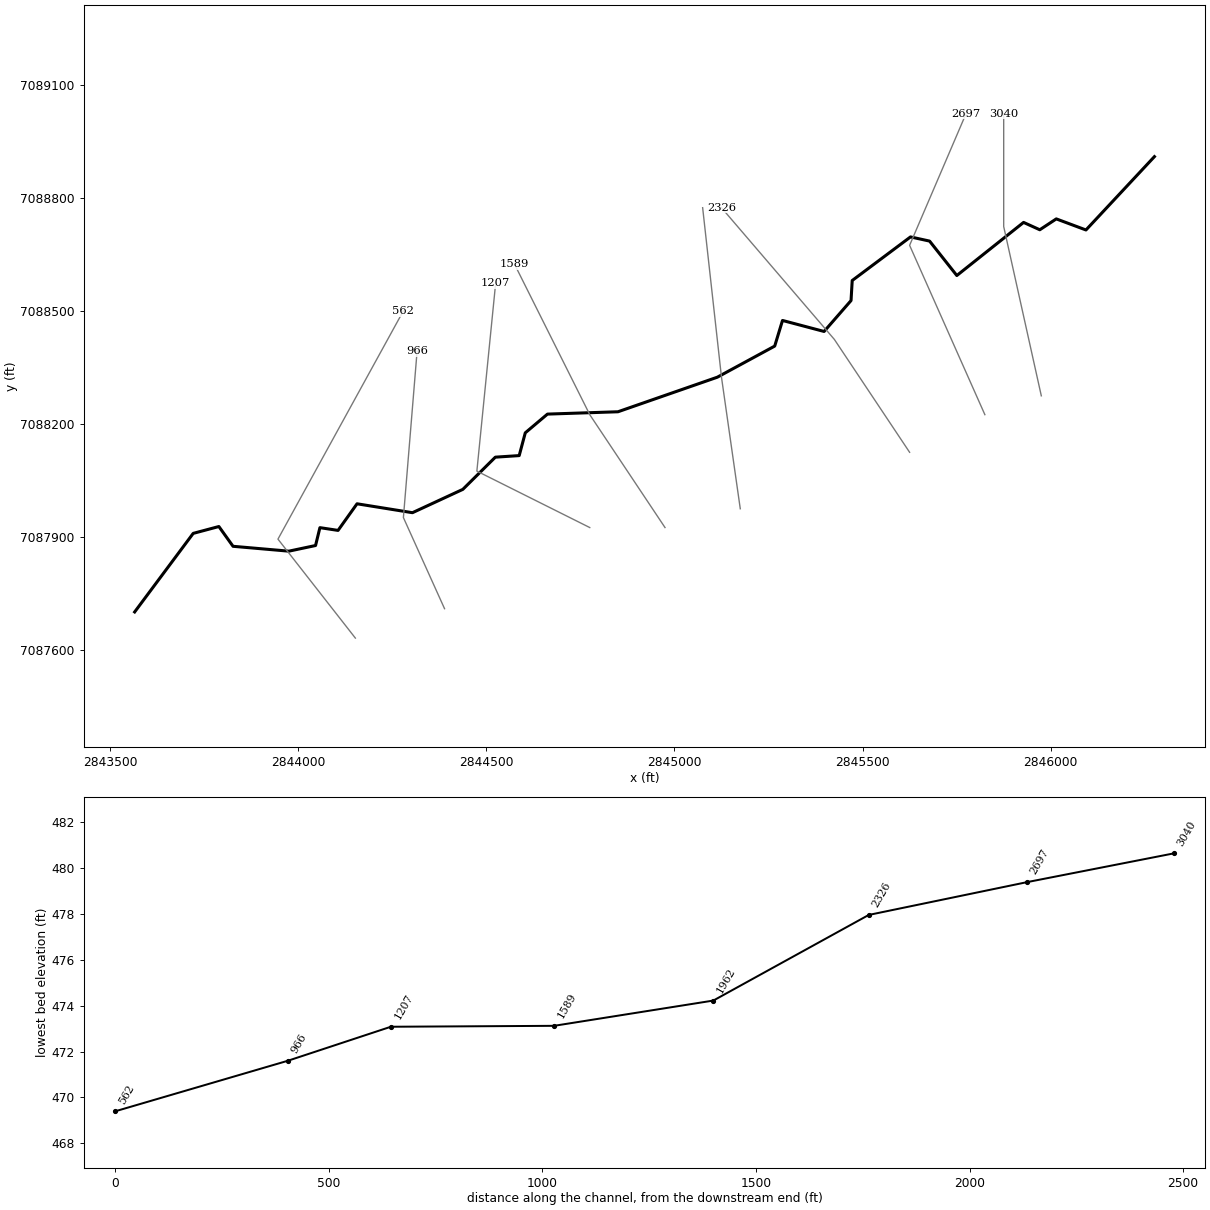
--- UNT 114 in LFCCL Watershed.prj (project) ---

Proj Title=UNT 114 in LFCCL Watershed Base Level Engineering
Current Plan=p01
Default Exp/Contr=0.3,0.1
English Units
Geom File=g01
Flow File=f01
Plan File=p01
BEGIN DESCRIPTION:
UNT 114 in LFCCL Watershed
END DESCRIPTION:

--- UNT 114 in LFCCL Watershed.p01 (plan) ---

Plan Title=Multiple Run
Short Identifier=Multiple
Geom File=g01
Flow File=f01
Subcritical Flow
K Sum by GR= 0
Std Step Tol= 0.01
Critical Tol= 0.01
Num of Std Step Trials= 20
Max Error Tol= 0.3
Flow Tol Ratio= 0.001
Split Flow NTrial= 30
Split Flow Tol= 0.02
Split Flow Ratio= 0.02
Log Output Level= 0
Friction Slope Method= 1
Unsteady Friction Slope Method= 2
Unsteady Bridges Friction Slope Method= 1
Parabolic Critical Depth
Global Vel Dist=  1 , 1 , 1
Global Log Level= 0
CheckData=True
Encroach Param= -1, 0, 0, 0
BEGIN DESCRIPTION:
Multiple Run
END DESCRIPTION:

--- UNT 114 in LFCCL Watershed.f01 (steady flow) ---

Flow Title=Multiple
Number of Profiles=7
Profile Names=10-year,25-year,50-year,1pct_min,100-year,1pct_plu,500-year
River Rch & RM= UNT 114 in LFCCL,Reach-1,3040
     727     967    1160     690    1376    2746    1931
Boundary for River Rch & Prof#=UNT 114 in LFCCL,Reach-1,1
Up Type=0
Dn Type=3
Dn Slope=0.005
Boundary for River Rch & Prof#=UNT 114 in LFCCL,Reach-1,2
Up Type=0
Dn Type=3
Dn Slope=0.005
Boundary for River Rch & Prof#=UNT 114 in LFCCL,Reach-1,3
Up Type=0
Dn Type=3
Dn Slope=0.005
Boundary for River Rch & Prof#=UNT 114 in LFCCL,Reach-1,4
Up Type=0
Dn Type=3
Dn Slope=0.005
Boundary for River Rch & Prof#=UNT 114 in LFCCL,Reach-1,5
Up Type=0
Dn Type=3
Dn Slope=0.005
Boundary for River Rch & Prof#=UNT 114 in LFCCL,Reach-1,6
Up Type=0
Dn Type=3
Dn Slope=0.005
Boundary for River Rch & Prof#=UNT 114 in LFCCL,Reach-1,7
Up Type=0
Dn Type=3
Dn Slope=0.005

--- UNT 114 in LFCCL Watershed.g01 (geometry) ---

Geom Title=Existing Conditions

River Reach=UNT 114 in LFCCL,Reach-1
Reach XY= 30
      2846275.59      7088910.71      2846093.66      7088715.81
      2846014.78      7088745.26      2845970.96      7088716.36
      2845927.85      7088735.92      2845750.46      7088594.77
      2845678.07      7088686.28      2845627.38      7088697.35
      2845472.47      7088581.51      2845469.34      7088528.25
      2845397.74      7088446.09      2845287.22      7088475.36
      2845266.51      7088407.25      2845114.00      7088324.55
      2844850.03      7088232.72      2844662.59      7088226.49
      2844603.67      7088176.77      2844587.49      7088116.23
      2844524.12      7088112.06      2844437.71      7088026.48
      2844303.82      7087964.49      2844156.54      7087988.16
      2844106.11      7087917.44      2844057.91      7087924.73
      2844046.31      7087877.26      2843975.36      7087862.26
      2843827.02      7087875.19      2843789.40      7087927.74
      2843721.16      7087909.50      2843565.59      7087700.71

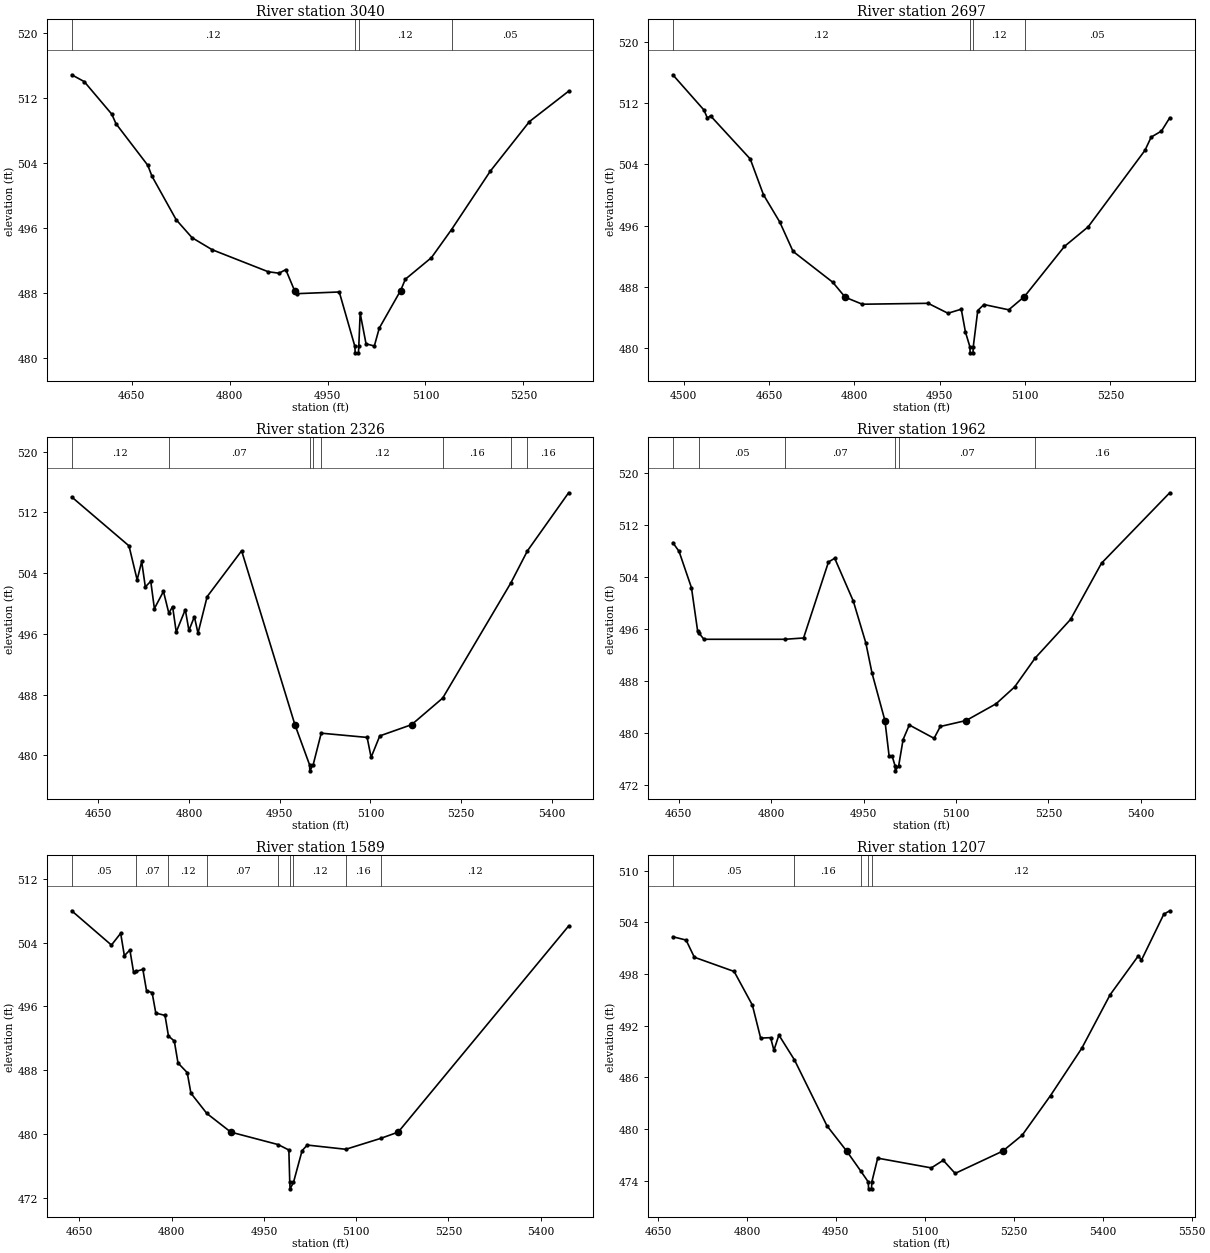
Type RM Length L Ch R = 1,3040,343,343,343
BEGIN DESCRIPTION:
UNT 114 in LFCCL Watershed 7.0
END DESCRIPTION:
XS GIS Cut Line= 3
      2845974.99      7088275.05      2845875.00      7088725.00
      2845875.00      7089024.97
#Sta/Elev= 30
  4558.3  514.85  4577.5  514.01  4619.7  510.00  4626.1  508.83  4674.8  503.71
  4681.2  502.37  4718.3  497.01  4742.6  494.80  4773.4  493.32  4859.2  490.61
  4875.8  490.43  4886.1  490.87  4899.6  488.28  4902.7  487.91  4968.0  488.12
  4991.9  481.43  4992.4  480.63  4997.4  480.63  4997.9  481.43  5000.0  485.51
  5009.0  481.74  5021.7  481.47  5029.2  483.66  5061.9  488.29  5069.2  489.69
  5109.2  492.35  5139.9  495.80  5199.2  502.98  5259.2  509.09  5319.2  512.83
#Mann=4,-1,0
  4558.3    0.12       0  4991.9    0.07       0  4997.9    0.12       0
  5139.9    0.05       0
Bank Sta=4899.6,5061.9
Exp/Cntr=0.3,0.1

Type RM Length L Ch R = 1,2697,371,371,371
BEGIN DESCRIPTION:
UNT 114 in LFCCL Watershed 6.0
END DESCRIPTION:
XS GIS Cut Line= 3
      2845824.98      7088225.04      2845625.00      7088675.00
      2845775.00      7089025.01
#Sta/Elev= 30
  4481.0  515.70  4535.7  511.10  4541.8  510.04  4547.3  510.34  4617.1  504.70
  4640.3  500.03  4669.0  496.46  4692.3  492.63  4762.1  488.60  4784.0  486.64
  4814.0  485.73  4929.6  485.85  4964.5  484.55  4987.9  485.08  4995.2  482.11
  5003.0  480.18  5003.5  479.38  5008.5  479.38  5009.0  480.18  5016.9  484.91
  5027.8  485.69  5071.3  485.00  5097.4  486.64  5099.4  486.78  5169.2  493.28
  5210.9  495.84  5310.7  505.83  5321.6  507.56  5339.7  508.35  5354.2  510.08
#Mann=4,-1,0
  4481.0    0.12       0  5003.0    0.07       0  5009.0    0.12       0
  5099.4    0.05       0
Bank Sta=4784,5097.4
Exp/Cntr=0.3,0.1

Type RM Length L Ch R = 1,2326,364,364,364
BEGIN DESCRIPTION:
UNT 114 in LFCCL Watershed 5.0
END DESCRIPTION:
XS GIS Cut Line= 3
      2845625.01      7088124.99      2845425.00      7088425.00
      2845125.03      7088774.97
#Sta/Elev= 30
  4606.2  514.02  4700.9  507.58  4714.4  503.10  4721.9  505.52  4727.9  502.18
  4736.9  502.91  4742.9  499.32  4757.9  501.58  4766.8  498.71  4773.0  499.59
  4779.0  496.23  4794.0  499.18  4800.0  496.44  4809.0  498.25  4815.0  496.08
  4830.1  500.89  4887.1  506.93  4975.2  484.03  4999.4  478.75  4999.9  477.95
  5005.4  478.75  5018.7  482.91  5094.6  482.35  5101.2  479.73  5115.5  482.55
  5168.1  484.03  5219.5  487.53  5332.3  502.71  5359.6  506.92  5427.7  514.57
#Mann=8,-1,0
  4606.2    0.12       0  4766.8    0.07       0  4999.4    0.07       0
  5005.4    0.07       0  5018.7    0.12       0  5219.5    0.16       0
  5332.3    0.12       0  5359.6    0.16       0
Bank Sta=4975.2,5168.1
Exp/Cntr=0.3,0.1

Type RM Length L Ch R = 1,1962,373,373,373
BEGIN DESCRIPTION:
UNT 114 in LFCCL Watershed 4.0
END DESCRIPTION:
XS GIS Cut Line= 3
      2845175.00      7087974.97      2845125.00      7088325.00
      2845074.99      7088775.05
#Sta/Elev= 30
  4640.5  509.31  4650.6  507.98  4670.8  502.37  4680.9  495.65  4683.4  495.35
  4691.0  494.45  4822.1  494.45  4852.7  494.65  4893.1  506.33  4903.2  506.91
  4933.5  500.30  4953.7  493.90  4963.8  489.25  4984.7  481.96  4991.6  476.43
  4996.6  476.43  5001.1  475.02  5001.6  474.22  5007.1  475.02  5014.2  479.03
  5024.3  481.27  5064.5  479.22  5074.6  481.04  5116.6  481.96  5165.1  484.53
  5195.3  487.13  5228.4  491.55  5285.9  497.50  5336.2  506.15  5446.9  516.98
#Mann=6,-1,0
  4640.5    0.12       0  4683.4    0.05       0  4822.1    0.07       0
  5001.1    0.07       0  5007.1    0.07       0  5228.4    0.16       0
Bank Sta=4984.7,5116.6
Exp/Cntr=0.3,0.1

Type RM Length L Ch R = 1,1589,382,382,382
BEGIN DESCRIPTION:
UNT 114 in LFCCL Watershed 3.0
END DESCRIPTION:
XS GIS Cut Line= 3
      2844975.00      7087925.00      2844775.00      7088225.00
      2844574.98      7088625.03
#Sta/Elev= 30
  4637.5  507.98  4702.1  503.68  4717.1  505.16  4723.1  502.35  4732.1  503.06
  4738.1  500.28  4741.5  500.37  4753.2  500.63  4759.2  497.93  4768.2  497.73
  4774.2  495.16  4789.2  494.86  4794.8  492.28  4804.3  491.65  4810.3  488.90
  4825.3  487.69  4831.3  485.11  4857.2  482.57  4896.2  480.23  4973.0  478.67
  4990.5  477.99  4992.0  473.92  4992.5  473.12  4998.0  473.92  5012.0  477.90
  5020.4  478.61  5083.1  478.08  5139.6  479.44  5168.2  480.23  5445.3  506.07
#Mann=9,-1,0
  4637.5    0.05       0  4741.5    0.07       0  4794.8    0.12       0
  4857.2    0.07       0  4973.0    0.12       0  4992.0    0.07       0
  4998.0    0.12       0  5083.1    0.16       0  5139.6    0.12       0
Bank Sta=4896.2,5168.2
Exp/Cntr=0.3,0.1

Type RM Length L Ch R = 1,1207,241,241,241
BEGIN DESCRIPTION:
UNT 114 in LFCCL Watershed 2.0
END DESCRIPTION:
XS GIS Cut Line= 3
      2844775.00      7087925.00      2844475.00      7088075.00
      2844525.00      7088574.99
#Sta/Elev= 30
  4675.1  502.33  4697.5  501.94  4711.4  499.95  4778.5  498.30  4809.3  494.39
  4823.2  490.57  4840.0  490.62  4845.6  489.16  4854.0  490.92  4880.3  488.03
  4935.0  480.40  4968.3  477.46  4992.4  475.11  5004.7  473.88  5005.2  473.08
  5010.2  473.08  5010.7  473.88  5020.6  476.64  5111.0  475.51  5131.1  476.39
  5151.2  474.87  5231.5  477.46  5264.3  479.31  5312.0  483.90  5364.8  489.40
  5412.5  495.60  5460.2  500.12  5465.3  499.61  5503.0  504.94  5513.0  505.34
#Mann=5,-1,0
  4675.1    0.05       0  4880.3    0.16       0  4992.4    0.12       0
  5004.7    0.07       0  5010.7    0.12       0
Bank Sta=4968.3,5231.5
Exp/Cntr=0.3,0.1

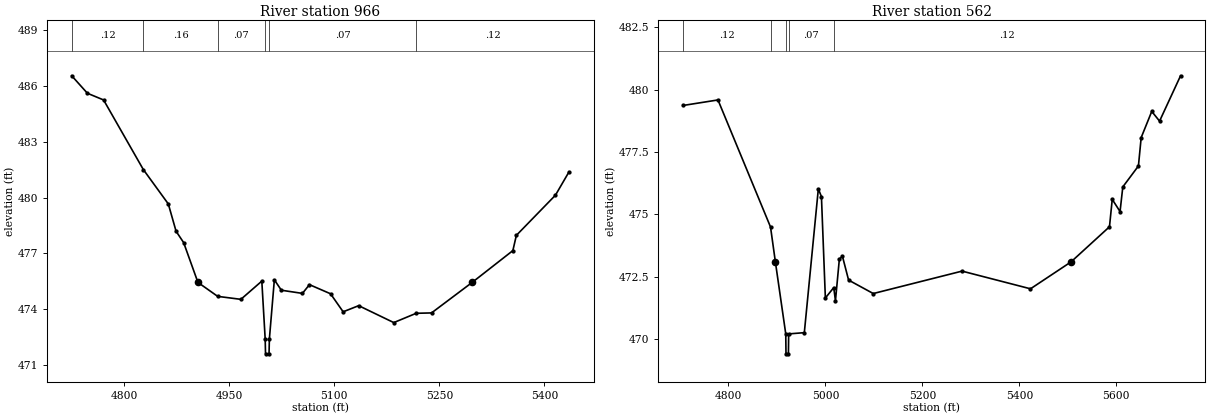
Type RM Length L Ch R = 1,966,404,404,404
BEGIN DESCRIPTION:
XS3742A
END DESCRIPTION:
XS GIS Cut Line= 3
      2844389.12      7087709.37      2844279.76      7087951.53
      2844316.21      7088394.22
#Sta/Elev= 30
  4725.1  486.55  4747.5  485.61  4770.6  485.25  4827.3  481.51  4863.0  479.66
  4874.1  478.19  4884.9  477.58  4905.3  475.44  4933.5  474.69  4966.6  474.53
  4996.5  475.51  5001.3  472.40  5001.8  471.60  5006.8  471.60  5007.3  472.40
  5014.4  475.58  5024.4  475.02  5054.5  474.85  5064.5  475.32  5094.6  474.83
  5112.6  473.86  5134.8  474.19  5184.9  473.28  5216.9  473.78  5238.8  473.80
  5296.8  475.44  5354.9  477.15  5359.9  477.97  5415.7  480.13  5435.0  481.38
#Mann=6,-1,0
  4725.1    0.12       0  4827.3    0.16       0  4933.5    0.07       0
  5001.3    0.07       0  5007.3    0.07       0  5216.9    0.12       0
Bank Sta=4905.3,5296.8
Exp/Cntr=0.3,0.1

Type RM Length L Ch R = 1,562,0,0,0
BEGIN DESCRIPTION:
UNT 114 in LFCCL Watershed 1.0
END DESCRIPTION:
XS GIS Cut Line= 3
      2844152.12      7087631.26      2843946.42      7087894.24
      2844279.48      7088500.51
#Sta/Elev= 30
  4706.9  479.37  4778.4  479.59  4886.8  474.49  4896.8  473.09  4918.2  470.20
  4918.7  469.40  4923.7  469.40  4924.2  470.20  4956.5  470.25  4985.4  476.02
  4991.8  475.71  4999.9  471.64  5017.2  472.06  5020.7  471.53  5028.8  473.21
  5035.2  473.31  5047.8  472.36  5098.7  471.82  5281.8  472.72  5423.0  472.01
  5506.6  473.09  5585.9  474.50  5591.6  475.60  5607.7  475.11  5613.4  476.10
  5645.6  476.94  5651.3  478.08  5673.1  479.13  5689.2  478.74  5732.5  480.56
#Mann=5,-1,0
  4706.9    0.12       0  4886.8    0.07       0  4918.2    0.07       0
  4924.2    0.07       0  5017.2    0.12       0
Bank Sta=4896.8,5506.6
Exp/Cntr=0.3,0.1

Chan Stop Cuts=-1