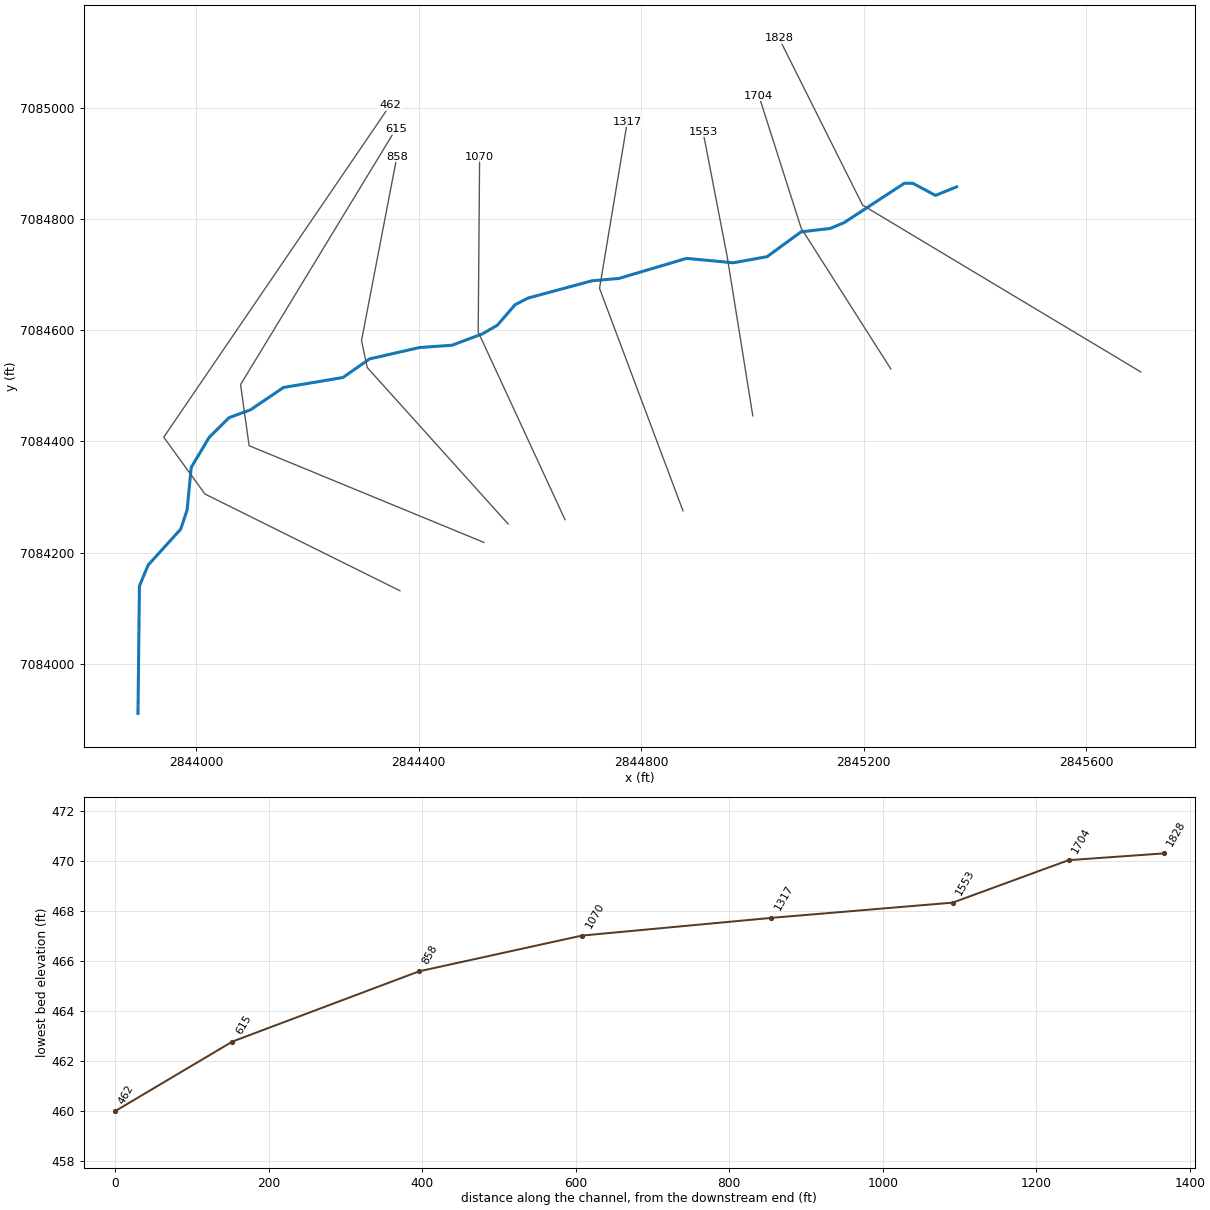
--- UNT 115 in LFCCL Watershed.prj (project) ---

Proj Title=UNT 115 in LFCCL Watershed Base Level Engineering
Current Plan=p01
Default Exp/Contr=0.3,0.1
English Units
Geom File=g01
Flow File=f01
Plan File=p01
BEGIN DESCRIPTION:
UNT 115 in LFCCL Watershed
END DESCRIPTION:

--- UNT 115 in LFCCL Watershed.p01 (plan) ---

Plan Title=Multiple Run
Short Identifier=Multiple
Geom File=g01
Flow File=f01
Subcritical Flow
K Sum by GR= 0
Std Step Tol= 0.01
Critical Tol= 0.01
Num of Std Step Trials= 20
Max Error Tol= 0.3
Flow Tol Ratio= 0.001
Split Flow NTrial= 30
Split Flow Tol= 0.02
Split Flow Ratio= 0.02
Log Output Level= 0
Friction Slope Method= 1
Unsteady Friction Slope Method= 2
Unsteady Bridges Friction Slope Method= 1
Parabolic Critical Depth
Global Vel Dist=  1 , 1 , 1
Global Log Level= 0
CheckData=True
Encroach Param= -1, 0, 0, 0
BEGIN DESCRIPTION:
Multiple Run
END DESCRIPTION:

--- UNT 115 in LFCCL Watershed.f01 (steady flow) ---

Flow Title=Multiple
Number of Profiles=7
Profile Names=10-year,25-year,50-year,1pct_min,100-year,1pct_plu,500-year
River Rch & RM= UNT 115 in LFCCL,Reach-1,1828
     408     530     628     370     738    1472    1014
Boundary for River Rch & Prof#=UNT 115 in LFCCL,Reach-1,1
Up Type=0
Dn Type=3
Dn Slope=0.005
Boundary for River Rch & Prof#=UNT 115 in LFCCL,Reach-1,2
Up Type=0
Dn Type=3
Dn Slope=0.005
Boundary for River Rch & Prof#=UNT 115 in LFCCL,Reach-1,3
Up Type=0
Dn Type=3
Dn Slope=0.005
Boundary for River Rch & Prof#=UNT 115 in LFCCL,Reach-1,4
Up Type=0
Dn Type=3
Dn Slope=0.005
Boundary for River Rch & Prof#=UNT 115 in LFCCL,Reach-1,5
Up Type=0
Dn Type=3
Dn Slope=0.005
Boundary for River Rch & Prof#=UNT 115 in LFCCL,Reach-1,6
Up Type=0
Dn Type=3
Dn Slope=0.005
Boundary for River Rch & Prof#=UNT 115 in LFCCL,Reach-1,7
Up Type=0
Dn Type=3
Dn Slope=0.005

--- UNT 115 in LFCCL Watershed.g01 (geometry) ---

Geom Title=Existing Conditions

River Reach=UNT 115 in LFCCL,Reach-1
Reach XY= 30
      2845366.67      7084857.64      2845328.77      7084842.21
      2845288.20      7084863.89      2845272.95      7084864.15
      2845164.53      7084793.26      2845139.72      7084782.81
      2845087.25      7084776.69      2845026.11      7084732.05
      2844965.49      7084721.05      2844881.42      7084728.96
      2844759.69      7084692.89      2844711.45      7084688.64
      2844596.77      7084657.67      2844573.18      7084645.63
      2844541.34      7084608.69      2844514.62      7084593.24
      2844459.77      7084572.73      2844401.45      7084568.63
      2844311.65      7084548.15      2844263.92      7084514.73
      2844157.20      7084496.81      2844097.82      7084456.63
      2844059.37      7084442.59      2844023.49      7084407.06
      2843991.27      7084353.08      2843983.85      7084276.43
      2843972.39      7084242.03      2843913.70      7084177.25
      2843898.18      7084139.64      2843895.59      7083910.71

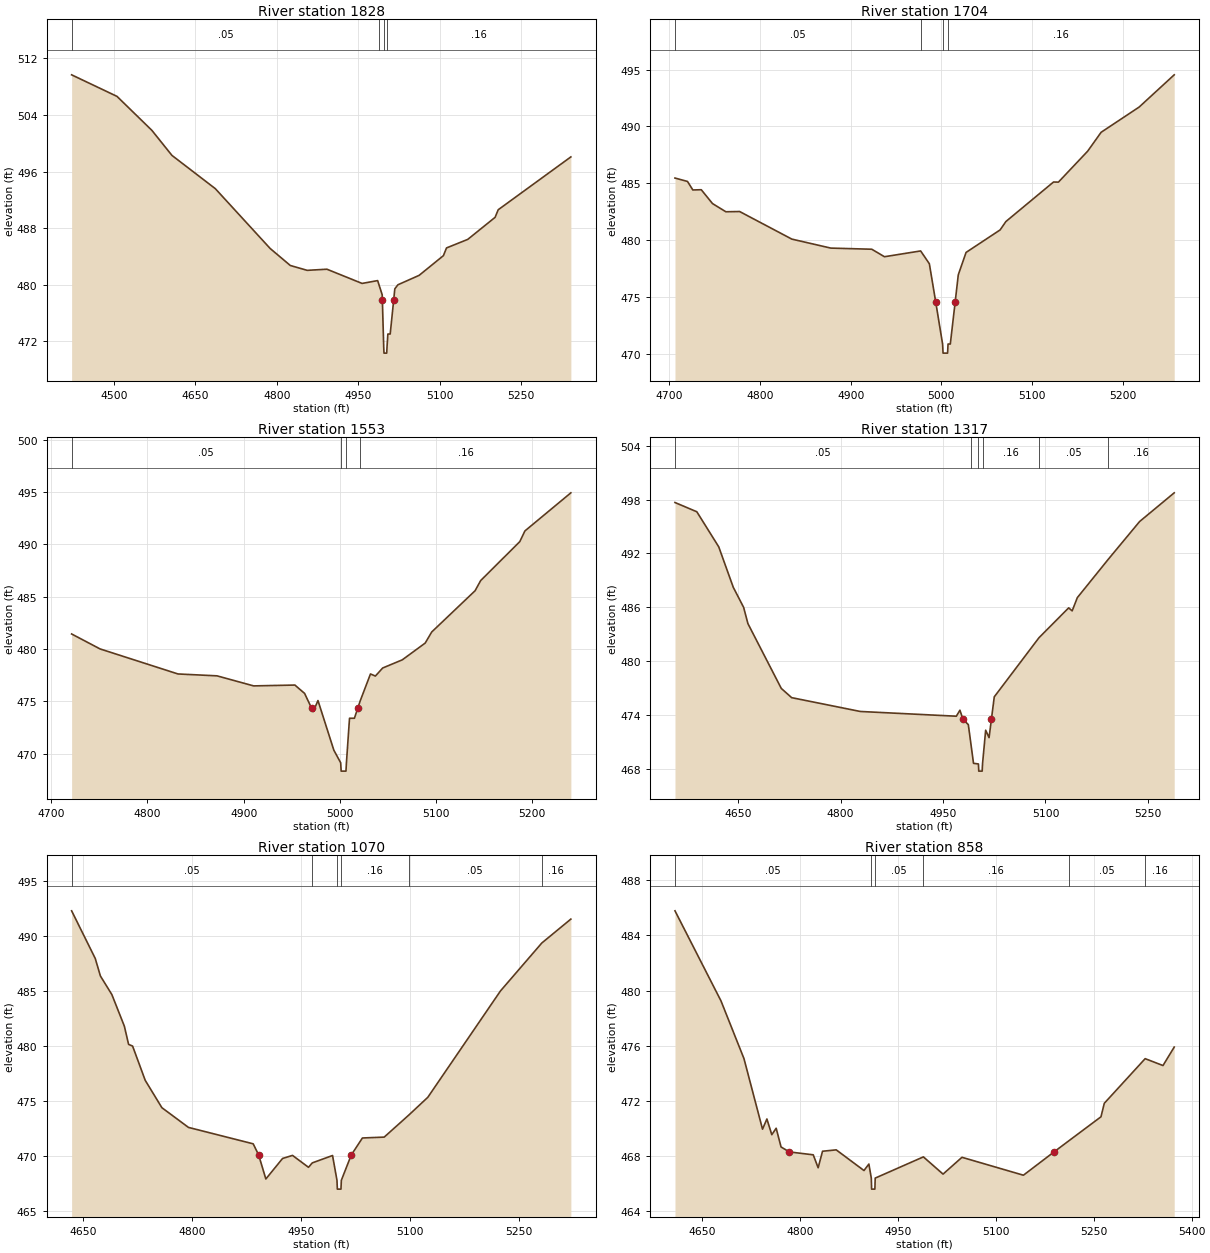
Type RM Length L Ch R = 1,1828,124,124,124
BEGIN DESCRIPTION:
UNT 115 in LFCCL Watershed 3.0
END DESCRIPTION:
XS GIS Cut Line= 3
      2845697.75      7084524.71      2845197.73      7084824.72
      2845047.74      7085124.70
#Sta/Elev= 30
  4422.6  509.68  4506.1  506.63  4570.3  501.82  4607.2  498.28  4686.9  493.58
  4787.9  485.11  4824.9  482.71  4856.0  482.02  4892.3  482.18  4957.0  480.17
  4985.6  480.57  4988.2  479.95  4994.0  478.56  4994.3  477.81  4996.8  471.11
  4997.3  470.31  5002.3  470.31  5002.8  471.11  5004.4  473.01  5008.7  473.01
  5015.1  477.81  5017.2  479.40  5022.9  479.98  5061.9  481.31  5106.6  484.10
  5112.3  485.19  5151.4  486.40  5201.7  489.52  5207.4  490.59  5341.1  498.07
#Mann=4,-1,0
  4422.6    0.05       0  4988.2    0.16       0  4996.8    0.07       0
  5002.8    0.16       0
Bank Sta=4994.3,5015.1
Exp/Cntr=0.3,0.1

Type RM Length L Ch R = 1,1704,151,151,151
BEGIN DESCRIPTION:
XS3746A
END DESCRIPTION:
XS GIS Cut Line= 3
      2845248.49      7084530.10      2845087.39      7084783.27
      2845011.25      7085021.83
#Sta/Elev= 30
  4706.3  485.46  4720.1  485.16  4726.0  484.41  4735.3  484.43  4747.7  483.21
  4762.4  482.49  4777.6  482.51  4835.2  480.08  4878.1  479.29  4923.3  479.19
  4937.3  478.53  4977.2  479.04  4986.8  477.91  4993.9  474.50  5001.4  470.84
  5001.9  470.04  5006.9  470.04  5007.4  470.84  5009.9  470.84  5015.2  474.50
  5018.7  476.94  5027.3  478.91  5064.8  480.89  5071.2  481.63  5123.7  485.11
  5129.1  485.10  5161.3  487.82  5176.2  489.49  5218.1  491.71  5256.8  494.55
#Mann=4,-1,0
  4706.3    0.05       0  4977.2    0.16       0  5001.4    0.07       0
  5007.4    0.16       0
Bank Sta=4993.9,5015.2
Exp/Cntr=0.3,0.1

Type RM Length L Ch R = 1,1553,236,236,236
BEGIN DESCRIPTION:
XS3747A
END DESCRIPTION:
XS GIS Cut Line= 3
      2845000.45      7084445.76      2844954.43      7084732.13
      2844910.96      7084957.12
#Sta/Elev= 30
  4721.1  481.44  4750.7  480.01  4831.7  477.62  4872.3  477.44  4910.4  476.48
  4953.3  476.56  4963.4  475.76  4970.6  474.36  4972.3  474.02  4977.3  475.08
  4993.8  470.34  5000.9  469.14  5001.4  468.34  5006.4  468.34  5006.9  469.14
  5010.1  473.39  5015.2  473.39  5018.7  474.36  5021.3  475.07  5031.9  477.62
  5037.0  477.42  5044.6  478.19  5065.0  478.97  5088.8  480.57  5095.6  481.63
  5140.7  485.57  5146.5  486.54  5187.2  490.26  5192.5  491.28  5240.3  494.92
#Mann=4,-1,0
  4721.1    0.05       0  5000.9    0.03       0  5006.9    0.05       0
  5021.3    0.16       0
Bank Sta=4970.6,5018.7
Exp/Cntr=0.3,0.1

Type RM Length L Ch R = 1,1317,247,247,247
BEGIN DESCRIPTION:
UNT 115 in LFCCL Watershed 2.0
END DESCRIPTION:
XS GIS Cut Line= 3
      2844875.00      7084275.00      2844725.00      7084675.00
      2844774.99      7084974.97
#Sta/Elev= 30
  4557.3  497.67  4589.3  496.64  4621.4  492.73  4642.7  488.22  4657.9  485.98
  4664.1  484.18  4713.0  476.95  4728.2  475.92  4828.7  474.38  4969.4  473.85
  4974.7  474.52  4979.2  473.50  4987.0  472.91  4990.9  470.70  4994.6  468.60
  5001.8  468.53  5002.3  467.73  5007.3  467.73  5007.8  468.53  5012.4  472.29
  5017.4  471.46  5020.8  473.50  5025.0  476.01  5090.5  482.60  5134.0  485.93
  5139.1  485.59  5146.7  487.07  5192.1  491.35  5237.9  495.55  5288.6  498.75
#Mann=6,-1,0
  4557.3    0.05       0  4990.9    0.16       0  5001.8    0.07       0
  5007.8    0.16       0  5090.5    0.05       0  5192.1    0.16       0
Bank Sta=4979.2,5020.8
Exp/Cntr=0.3,0.1

Type RM Length L Ch R = 1,1070,212,212,212
BEGIN DESCRIPTION:
XS3745A
END DESCRIPTION:
XS GIS Cut Line= 3
      2844662.95      7084259.06      2844506.97      7084596.61
      2844509.51      7084911.85
#Sta/Elev= 30
  4633.9  492.27  4666.4  487.95  4673.5  486.36  4689.3  484.67  4706.5  481.80
  4712.3  480.15  4717.8  480.00  4735.2  476.89  4758.1  474.41  4794.7  472.62
  4883.8  471.13  4891.3  470.12  4901.2  467.94  4924.2  469.80  4937.9  470.08
  4959.9  469.00  4965.1  469.40  4993.0  470.07  4999.1  467.82  4999.6  467.02
  5004.6  467.02  5005.1  467.82  5018.8  470.12  5034.1  471.66  5064.1  471.74
  5097.8  473.73  5124.1  475.35  5224.1  485.00  5281.0  489.35  5321.0  491.52
#Mann=6,-1,0
  4633.9    0.05       0  4965.1    0.16       0  4999.1    0.07       0
  5005.1    0.16       0  5097.8    0.05       0  5281.0    0.16       0
Bank Sta=4891.3,5018.8
Exp/Cntr=0.3,0.1

Type RM Length L Ch R = 1,858,243,243,243
BEGIN DESCRIPTION:
XS3744A
END DESCRIPTION:
XS GIS Cut Line= 4
      2844560.65      7084251.44      2844307.53      7084532.69
      2844297.30      7084581.27      2844360.88      7084911.88
#Sta/Elev= 30
  4608.6  485.79  4679.1  479.25  4714.3  475.06  4742.7  469.94  4749.4  470.68
  4756.9  469.54  4763.6  470.01  4771.1  468.65  4783.8  468.29  4820.4  468.08
  4827.9  467.14  4834.6  468.34  4855.6  468.44  4898.1  466.94  4905.6  467.41
  4909.3  466.39  4909.8  465.59  4914.8  465.59  4915.3  466.39  4989.1  467.93
  5019.2  466.68  5048.2  467.90  5142.3  466.60  5189.2  468.29  5211.4  469.08
  5261.1  470.84  5266.2  471.82  5328.8  475.06  5356.1  474.56  5373.3  475.90
#Mann=6,-1,0
  4608.6    0.05       0  4909.3    0.07       0  4915.3    0.05       0
  4989.1    0.16       0  5211.4    0.05       0  5328.8    0.16       0
Bank Sta=4783.8,5189.2
Exp/Cntr=0.3,0.1

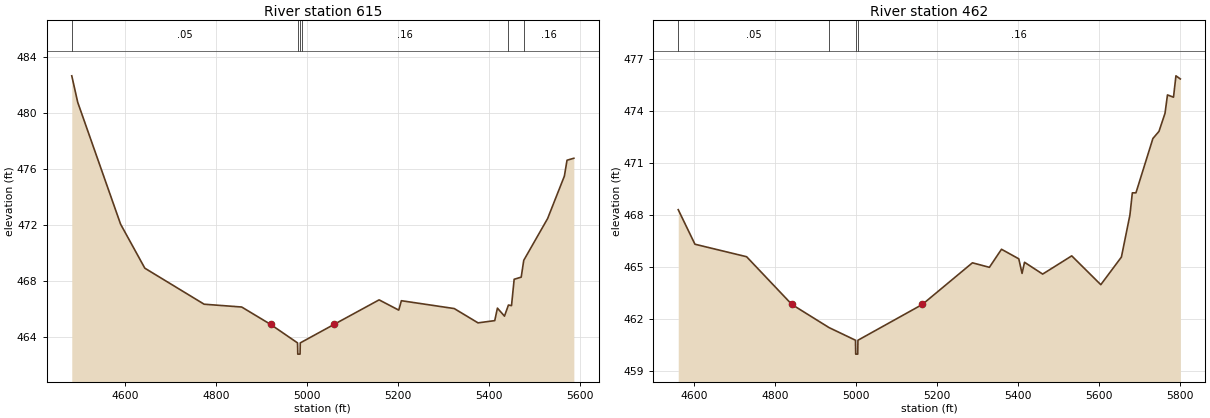
Type RM Length L Ch R = 1,615,153,153,153
BEGIN DESCRIPTION:
XS3743A
END DESCRIPTION:
XS GIS Cut Line= 4
      2844517.16      7084218.20      2844095.30      7084392.06
      2844079.96      7084502.00      2844358.74      7084961.22
#Sta/Elev= 30
  4482.7  482.63  4495.8  480.74  4590.1  472.05  4643.4  468.91  4773.9  466.34
  4856.5  466.14  4920.1  464.90  4979.4  463.58  4979.9  462.78  4984.9  462.78
  4985.4  463.58  4988.1  463.63  5059.7  464.90  5158.8  466.65  5202.0  465.92
  5207.8  466.59  5324.1  466.03  5376.4  465.01  5413.2  465.17  5419.1  466.06
  5434.6  465.49  5443.3  466.28  5450.1  466.24  5455.9  468.12  5471.4  468.27
  5477.0  469.47  5529.5  472.45  5566.4  475.48  5572.2  476.61  5587.2  476.75
#Mann=6,-1,0
  4482.7    0.05       0  4979.4    0.07       0  4985.4    0.05       0
  4988.1    0.16       0  5443.3    0.05       0  5477.0    0.16       0
Bank Sta=4920.1,5059.7
Exp/Cntr=0.3,0.1

Type RM Length L Ch R = 1,462,0,0,0
BEGIN DESCRIPTION:
UNT 115 in LFCCL Watershed 1.0
END DESCRIPTION:
XS GIS Cut Line= 4
      2844366.29      7084131.27      2844016.04      7084305.12
      2843941.88      7084407.40      2844348.86      7085004.78
#Sta/Elev= 30
  4560.9  468.31  4602.2  466.32  4729.8  465.60  4841.6  462.85  4933.3  461.52
  4998.8  460.79  4999.3  459.99  5004.3  459.99  5004.8  460.79  5163.8  462.85
  5287.6  465.25  5329.5  464.99  5359.4  466.03  5402.1  465.48  5410.2  464.64
  5416.3  465.28  5461.1  464.60  5532.9  465.65  5604.7  463.99  5655.6  465.58
  5676.6  468.00  5682.6  469.28  5691.5  469.28  5733.4  472.41  5748.4  472.82
  5763.3  473.86  5769.4  474.92  5784.3  474.79  5790.3  476.02  5801.1  475.84
#Mann=4,-1,0
  4560.9    0.05       0  4933.3    0.16       0  4998.8    0.07       0
  5004.8    0.16       0
Bank Sta=4841.6,5163.8
Exp/Cntr=0.3,0.1

Chan Stop Cuts=-1