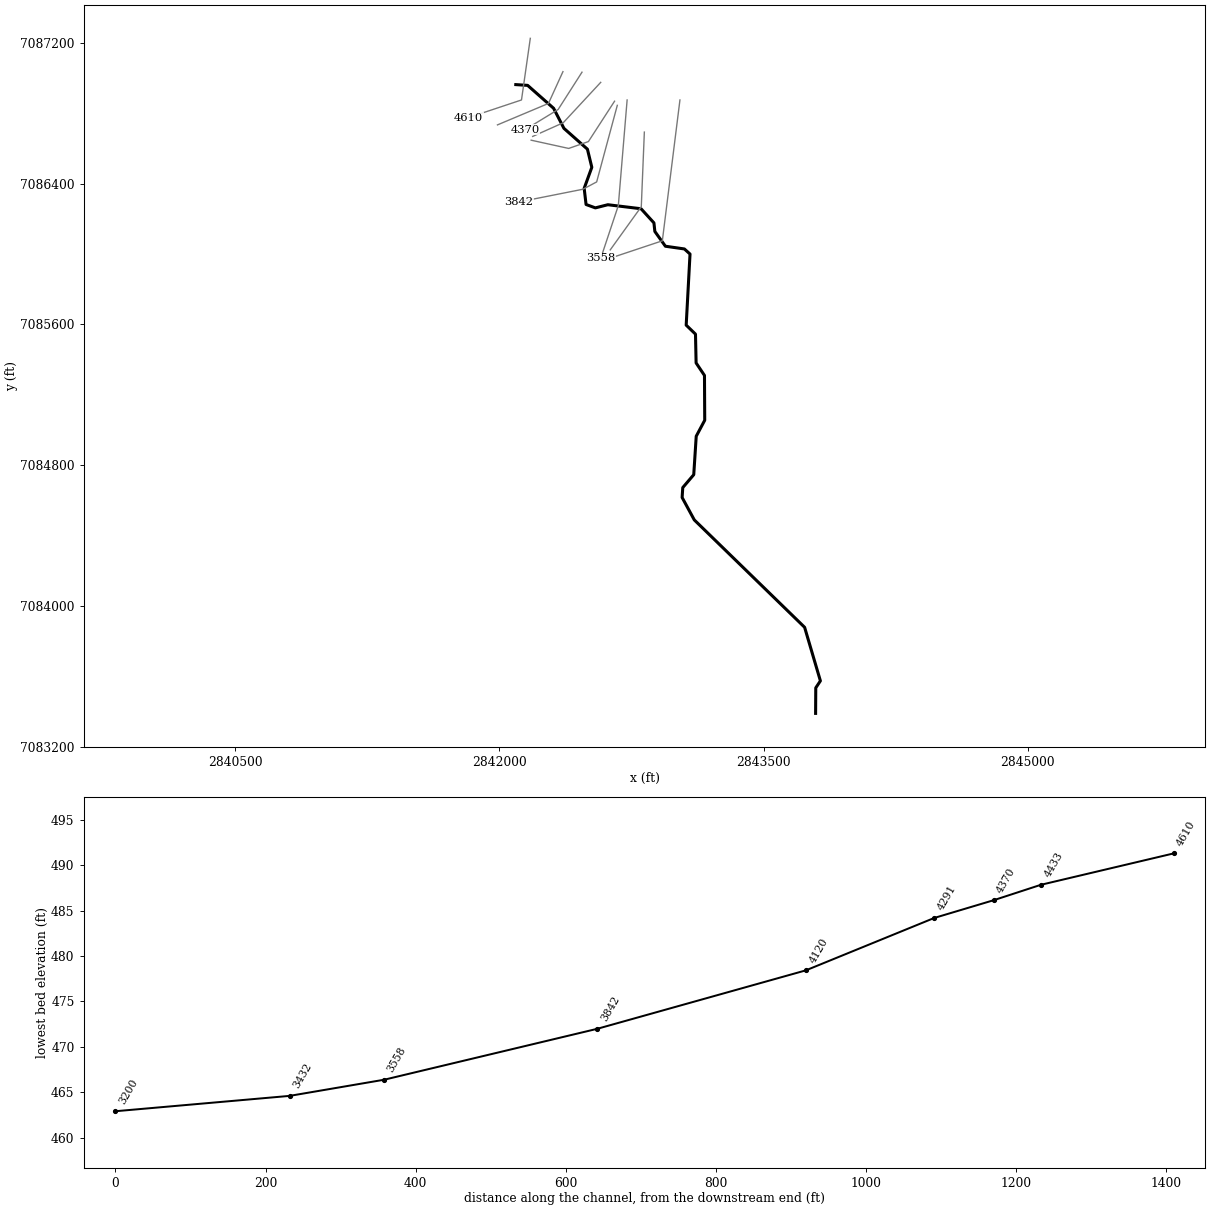
--- UNT 116 in LFCCL Watershed.prj (project) ---

Proj Title=UNT 116 in LFCCL Watershed Base Level Engineering
Current Plan=p01
Default Exp/Contr=0.3,0.1
English Units
Geom File=g01
Flow File=f01
Plan File=p01
BEGIN DESCRIPTION:
UNT 116 in LFCCL Watershed
END DESCRIPTION:

--- UNT 116 in LFCCL Watershed.p01 (plan) ---

Plan Title=Multiple Run
Short Identifier=Multiple
Geom File=g01
Flow File=f01
Subcritical Flow
K Sum by GR= 0
Std Step Tol= 0.01
Critical Tol= 0.01
Num of Std Step Trials= 20
Max Error Tol= 0.3
Flow Tol Ratio= 0.001
Split Flow NTrial= 30
Split Flow Tol= 0.02
Split Flow Ratio= 0.02
Log Output Level= 0
Friction Slope Method= 1
Unsteady Friction Slope Method= 2
Unsteady Bridges Friction Slope Method= 1
Parabolic Critical Depth
Global Vel Dist=  1 , 1 , 1
Global Log Level= 0
CheckData=True
Encroach Param= -1, 0, 0, 0
BEGIN DESCRIPTION:
Multiple Run
END DESCRIPTION:

--- UNT 116 in LFCCL Watershed.f01 (steady flow) ---

Flow Title=Multiple
Number of Profiles=7
Profile Names=10-year,25-year,50-year,1pct_min,100-year,1pct_plu,500-year
River Rch & RM= UNT 116 in LFCCL,Reach-1,4610
     251     316     366     211     422     842     557
River Rch & RM= UNT 116 in LFCCL,Reach-1,3200
     370     476     559     327     652    1301     882
Boundary for River Rch & Prof#=UNT 116 in LFCCL,Reach-1,1
Up Type=0
Dn Type=3
Dn Slope=0.005
Boundary for River Rch & Prof#=UNT 116 in LFCCL,Reach-1,2
Up Type=0
Dn Type=3
Dn Slope=0.005
Boundary for River Rch & Prof#=UNT 116 in LFCCL,Reach-1,3
Up Type=0
Dn Type=3
Dn Slope=0.005
Boundary for River Rch & Prof#=UNT 116 in LFCCL,Reach-1,4
Up Type=0
Dn Type=3
Dn Slope=0.005
Boundary for River Rch & Prof#=UNT 116 in LFCCL,Reach-1,5
Up Type=0
Dn Type=3
Dn Slope=0.005
Boundary for River Rch & Prof#=UNT 116 in LFCCL,Reach-1,6
Up Type=0
Dn Type=3
Dn Slope=0.005
Boundary for River Rch & Prof#=UNT 116 in LFCCL,Reach-1,7
Up Type=0
Dn Type=3
Dn Slope=0.005

--- UNT 116 in LFCCL Watershed.g01 (geometry) ---

Geom Title=Existing Conditions

River Reach=UNT 116 in LFCCL,Reach-1
Reach XY= 30
      2842092.59      7086962.21      2842159.87      7086957.87
      2842307.43      7086827.66      2842366.03      7086713.73
      2842499.49      7086595.46      2842524.45      7086492.37
      2842481.05      7086373.02      2842491.77      7086281.21
      2842544.57      7086262.01      2842615.51      7086279.92
      2842804.17      7086257.07      2842877.26      7086176.77
      2842882.46      7086128.14      2842942.39      7086044.17
      2843050.37      7086028.69      2843082.26      7085999.72
      2843060.49      7085595.93      2843113.32      7085544.90
      2843116.81      7085381.22      2843164.37      7085310.20
      2843165.77      7085055.63      2843117.49      7084964.92
      2843103.42      7084746.45      2843041.02      7084673.21
      2843037.43      7084616.79      2843106.51      7084489.59
      2843733.14      7083879.69      2843822.82      7083575.32
      2843796.49      7083535.75      2843795.59      7083390.71

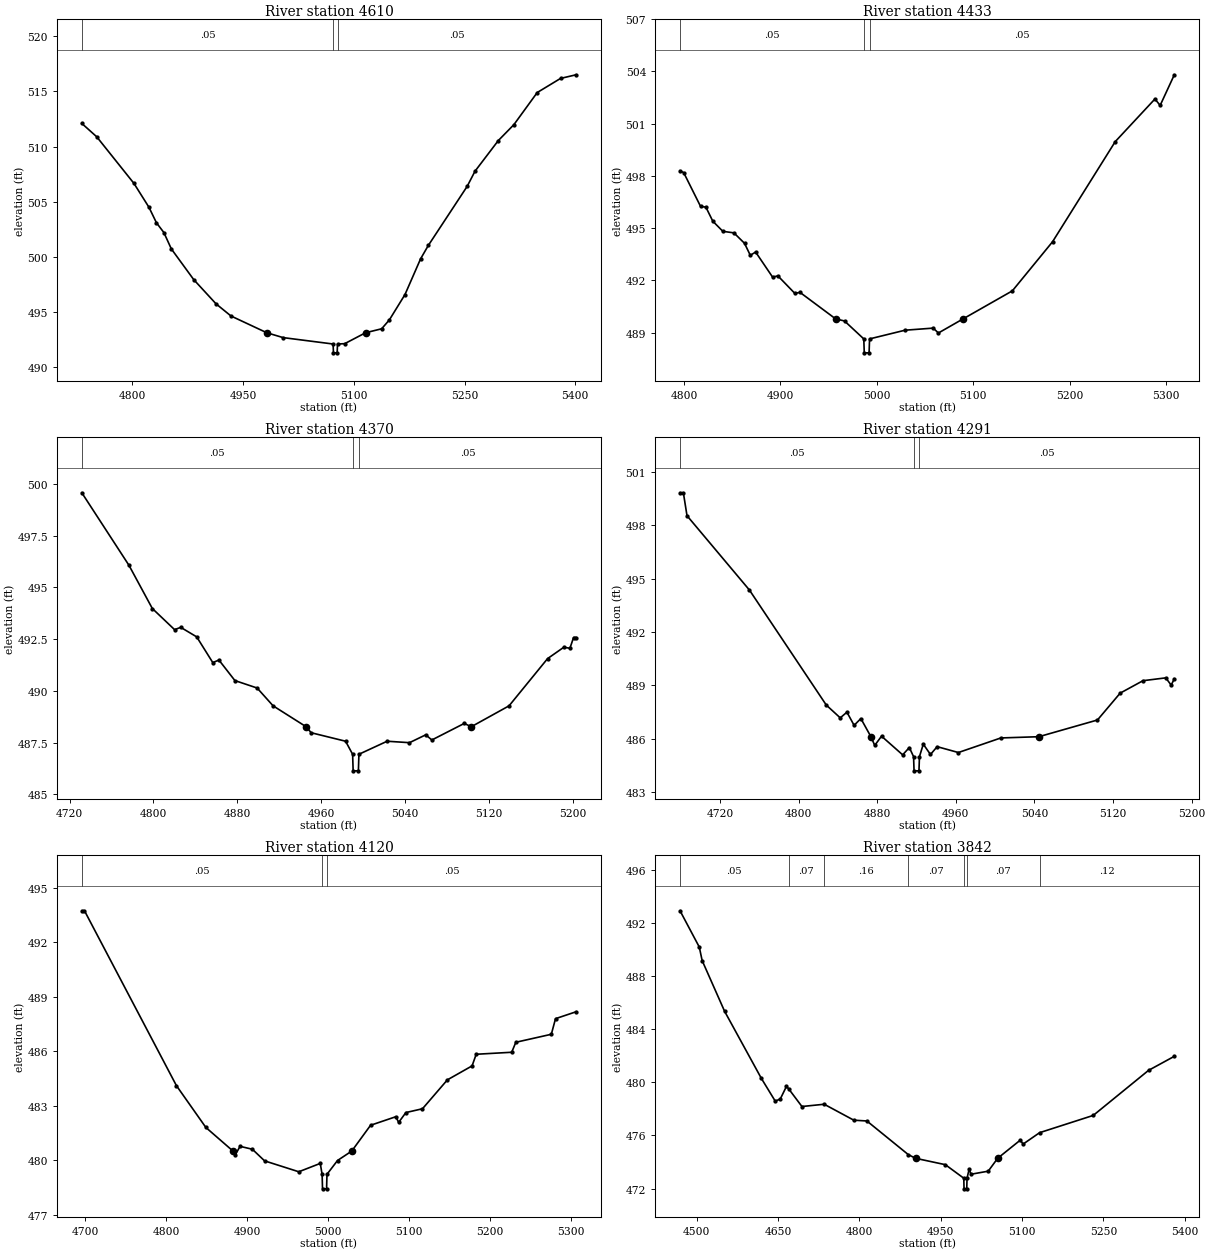
Type RM Length L Ch R = 1,4610,177,177,177
BEGIN DESCRIPTION:
UNT 116 in LFCCL Watershed 4.0
END DESCRIPTION:
XS GIS Cut Line= 3
      2842175.01      7087225.04      2842125.00      7086875.00
      2841825.02      7086775.01
#Sta/Elev= 30
  4731.4  512.09  4751.6  510.88  4802.1  506.65  4822.4  504.49  4832.5  503.09
  4842.6  502.20  4852.7  500.72  4883.0  497.94  4913.3  495.74  4933.5  494.64
  4982.1  493.12  5004.2  492.68  5071.9  492.10  5072.4  491.30  5077.4  491.30
  5077.9  492.10  5087.6  492.13  5115.9  493.12  5137.7  493.48  5148.2  494.29
  5169.3  496.58  5190.4  499.81  5200.9  501.03  5253.6  506.39  5264.2  507.76
  5295.8  510.54  5316.9  511.98  5348.5  514.89  5380.1  516.17  5401.2  516.50
#Mann=3,-1,0
  4731.4    0.05       0  5071.9    0.03       0  5077.9    0.05       0
Bank Sta=4982.1,5115.9
Exp/Cntr=0.3,0.1

Type RM Length L Ch R = 1,4433,63,63,63
BEGIN DESCRIPTION:
XS3748A
END DESCRIPTION:
XS GIS Cut Line= 3
      2842360.43      7087035.90      2842278.13      7086855.23
      2841988.54      7086733.41
#Sta/Elev= 30
  4795.8  498.29  4799.6  498.19  4817.1  496.25  4822.6  496.21  4829.8  495.40
  4840.2  494.82  4851.7  494.73  4862.7  494.13  4868.7  493.44  4874.2  493.63
  4891.8  492.19  4897.3  492.26  4914.8  491.26  4920.3  491.31  4957.2  489.79
  4966.4  489.67  4986.4  488.64  4986.9  487.84  4991.9  487.84  4992.4  488.64
  5029.2  489.14  5058.4  489.26  5063.8  488.98  5089.4  489.79  5140.5  491.40
  5182.2  494.22  5247.2  499.97  5288.4  502.42  5293.8  502.05  5308.5  503.81
#Mann=3,-1,0
  4795.8    0.05       0  4986.4    0.03       0  4992.4    0.05       0
Bank Sta=4957.2,5089.4
Exp/Cntr=0.3,0.1

Type RM Length L Ch R = 1,4370,79,79,79
BEGIN DESCRIPTION:
XS3751A
END DESCRIPTION:
XS GIS Cut Line= 3
      2842468.67      7087032.81      2842333.25      7086821.00
      2842145.79      7086706.44
#Sta/Elev= 30
  4731.7  499.57  4776.6  496.07  4798.9  493.98  4820.1  492.96  4826.0  493.07
  4841.2  492.61  4856.5  491.37  4862.4  491.49  4877.6  490.50  4898.8  490.14
  4914.0  489.28  4945.5  488.27  4950.3  487.98  4983.1  487.57  4989.8  486.94
  4990.3  486.14  4995.3  486.14  4995.8  486.94  5022.7  487.57  5044.0  487.50
  5059.5  487.88  5065.3  487.63  5096.2  488.43  5102.9  488.27  5138.9  489.28
  5175.6  491.56  5191.1  492.11  5196.9  492.06  5200.4  492.58  5202.8  492.58
#Mann=3,-1,0
  4731.7    0.05       0  4989.8    0.03       0  4995.8    0.05       0
Bank Sta=4945.5,5102.9
Exp/Cntr=0.3,0.1

Type RM Length L Ch R = 1,4291,171,171,171
BEGIN DESCRIPTION:
UNT 116 in LFCCL Watershed 3.0
END DESCRIPTION:
XS GIS Cut Line= 3
      2842574.99      7086974.99      2842361.90      7086745.48
      2842188.75      7086667.95
#Sta/Elev= 30
  4679.4  499.83  4682.8  499.83  4686.5  498.54  4750.0  494.36  4828.2  487.89
  4842.4  487.17  4849.2  487.49  4856.5  486.75  4863.4  487.13  4873.6  486.11
  4877.5  485.62  4884.4  486.14  4905.9  485.09  4912.7  485.50  4917.0  484.99
  4917.5  484.19  4922.5  484.19  4923.0  484.99  4926.9  485.69  4934.2  485.11
  4941.0  485.55  4962.6  485.22  5005.8  486.04  5044.5  486.11  5104.1  487.05
  5127.2  488.56  5150.4  489.26  5173.6  489.42  5179.1  489.01  5182.3  489.37
#Mann=3,-1,0
  4679.4    0.05       0  4917.0    0.03       0  4923.0    0.05       0
Bank Sta=4873.6,5044.5
Exp/Cntr=0.3,0.1

Type RM Length L Ch R = 1,4120,278,278,278
BEGIN DESCRIPTION:
XS3749A
END DESCRIPTION:
XS GIS Cut Line= 4
      2842653.59      7086867.91      2842505.13      7086638.71
      2842393.15      7086599.65      2842179.80      7086646.48
#Sta/Elev= 30
  4696.2  493.73  4699.5  493.73  4813.0  484.10  4849.3  481.80  4882.8  480.50
  4885.5  480.28  4891.5  480.76  4906.7  480.60  4921.8  479.96  4964.0  479.36
  4990.5  479.82  4992.8  479.22  4993.3  478.42  4998.3  478.42  4998.8  479.22
  5011.8  479.98  5029.4  480.50  5052.6  481.92  5083.7  482.39  5087.3  482.08
  5096.2  482.62  5116.7  482.83  5147.4  484.42  5177.9  485.19  5183.0  485.83
  5226.8  485.94  5231.9  486.49  5275.7  486.93  5280.9  487.79  5306.3  488.17
#Mann=3,-1,0
  4696.2    0.05       0  4992.8    0.03       0  4998.8    0.05       0
Bank Sta=4882.8,5029.4
Exp/Cntr=0.3,0.1

Type RM Length L Ch R = 1,3842,284,284,284
BEGIN DESCRIPTION:
XS3750A
END DESCRIPTION:
XS GIS Cut Line= 4
      2842669.18      7086844.42      2842552.00      7086409.54
      2842473.88      7086367.88      2842108.34      7086295.29
#Sta/Elev= 30
  4469.2  492.92  4504.7  490.19  4510.0  489.17  4551.4  485.35  4619.3  480.29
  4644.7  478.59  4654.0  478.74  4665.4  479.69  4669.4  479.52  4694.0  478.18
  4735.1  478.35  4789.7  477.15  4813.8  477.09  4890.1  474.56  4903.5  474.28
  4958.5  473.80  4992.5  472.78  4993.0  471.98  4998.0  471.98  4998.5  472.78
  5002.4  473.46  5005.9  473.08  5037.6  473.31  5055.0  474.28  5096.8  475.65
  5101.9  475.35  5132.4  476.21  5231.3  477.51  5333.2  480.90  5380.8  481.96
#Mann=7,-1,0
  4469.2    0.05       0  4669.4    0.07       0  4735.1    0.16       0
  4890.1    0.07       0  4992.5    0.07       0  4998.5    0.07       0
  5132.4    0.12       0
Bank Sta=4903.5,5055
Exp/Cntr=0.3,0.1

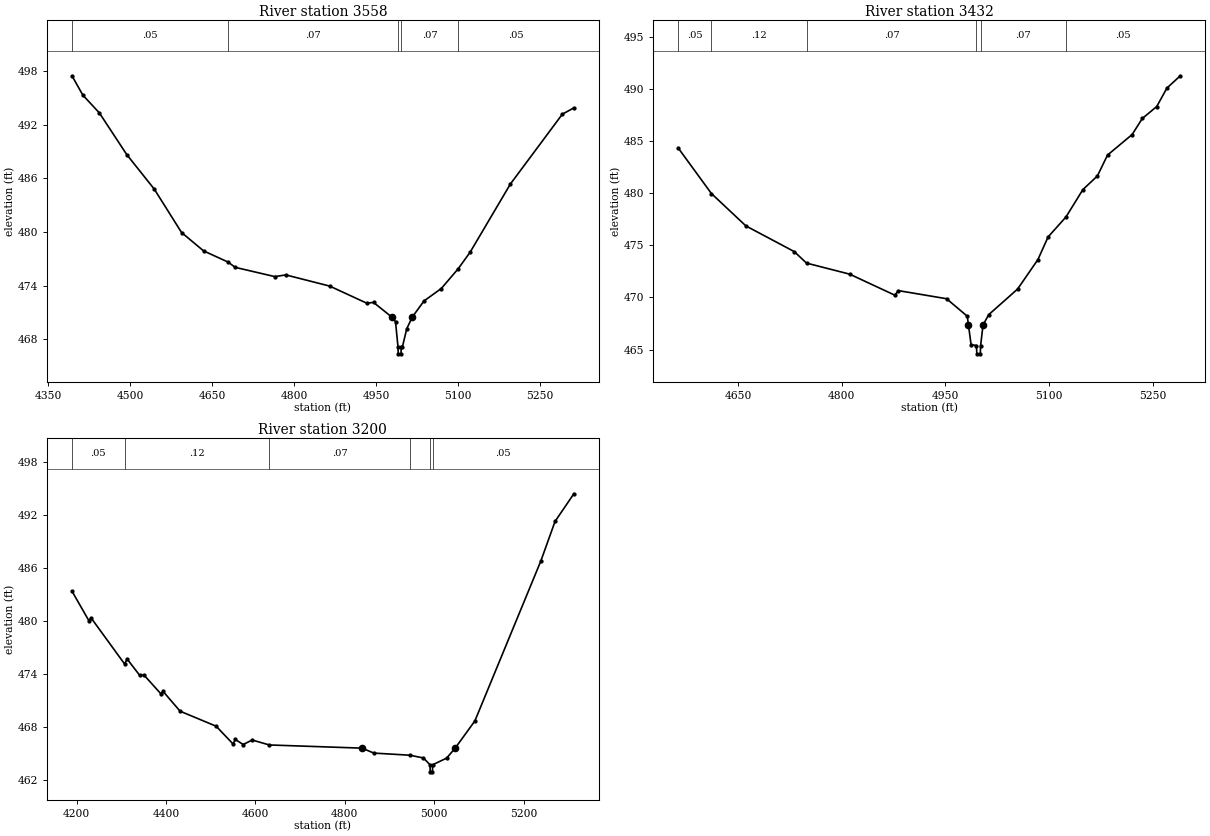
Type RM Length L Ch R = 1,3558,126,126,126
BEGIN DESCRIPTION:
UNT 116 in LFCCL Watershed 2.0
END DESCRIPTION:
XS GIS Cut Line= 3
      2842725.00      7086874.95      2842675.00      7086275.00
      2842574.99      7085974.96
#Sta/Elev= 30
  4393.8  497.48  4413.8  495.31  4443.9  493.33  4494.1  488.66  4544.3  484.81
  4594.4  479.94  4634.6  477.89  4679.7  476.63  4692.3  476.05  4765.0  475.01
  4785.1  475.20  4865.4  473.95  4933.1  472.04  4945.7  472.12  4979.3  470.47
  4985.8  469.96  4990.3  467.17  4990.8  466.37  4995.8  466.37  4996.3  467.17
  4998.5  467.17  5006.4  469.18  5016.3  470.47  5038.0  472.29  5069.6  473.68
  5100.1  475.86  5122.3  477.74  5196.1  485.38  5291.0  493.18  5312.1  493.89
#Mann=5,-1,0
  4393.8    0.05       0  4679.7    0.07       0  4990.3    0.07       0
  4996.3    0.07       0  5100.1    0.05       0
Bank Sta=4979.3,5016.3
Exp/Cntr=0.3,0.1

Type RM Length L Ch R = 1,3432,232,232,232
BEGIN DESCRIPTION:
XS3752A
END DESCRIPTION:
XS GIS Cut Line= 3
      2842822.84      7086692.54      2842805.47      7086268.92
      2842629.22      7086023.54
#Sta/Elev= 30
  4563.7  484.32  4611.4  479.98  4661.3  476.87  4731.4  474.40  4749.0  473.30
  4811.4  472.24  4876.8  470.22  4881.8  470.66  4951.6  469.88  4981.6  468.20
  4983.3  467.36  4987.1  465.47  4994.9  465.39  4995.4  464.59  5000.4  464.59
  5000.9  465.39  5004.4  467.36  5012.6  468.35  5054.4  470.81  5083.8  473.64
  5098.5  475.81  5124.4  477.73  5148.9  480.36  5169.8  481.66  5184.5  483.67
  5220.1  485.64  5234.8  487.18  5255.7  488.33  5270.4  490.10  5289.8  491.28
#Mann=6,-1,0
  4563.7    0.05       0  4611.4    0.12       0  4749.0    0.07       0
  4994.9    0.07       0  5000.9    0.07       0  5124.4    0.05       0
Bank Sta=4983.3,5004.4
Exp/Cntr=0.3,0.1

Type RM Length L Ch R = 1,3200,0,0,0
BEGIN DESCRIPTION:
UNT 116 in LFCCL Watershed 1.0
END DESCRIPTION:
XS GIS Cut Line= 3
      2843025.00      7086874.97      2842925.00      7086075.00
      2842625.02      7085975.01
#Sta/Elev= 30
  4189.7  483.34  4227.5  480.00  4232.5  480.31  4307.4  475.10  4313.1  475.66
  4340.8  473.84  4350.9  473.84  4388.7  471.72  4393.7  471.99  4431.5  469.76
  4512.2  468.06  4550.0  466.05  4555.0  466.56  4572.6  465.99  4592.8  466.50
  4631.0  465.94  4838.3  465.58  4864.9  465.02  4945.5  464.78  4975.7  464.47
  4990.4  463.70  4990.9  462.90  4995.9  462.90  4996.4  463.70  5027.5  464.45
  5046.7  465.58  5090.8  468.66  5238.3  486.75  5270.0  491.22  5312.1  494.35
#Mann=6,-1,0
  4189.7    0.05       0  4307.4    0.12       0  4631.0    0.07       0
  4945.5    0.05       0  4990.4    0.03       0  4996.4    0.05       0
Bank Sta=4838.3,5046.7
Exp/Cntr=0.3,0.1

Chan Stop Cuts=-1