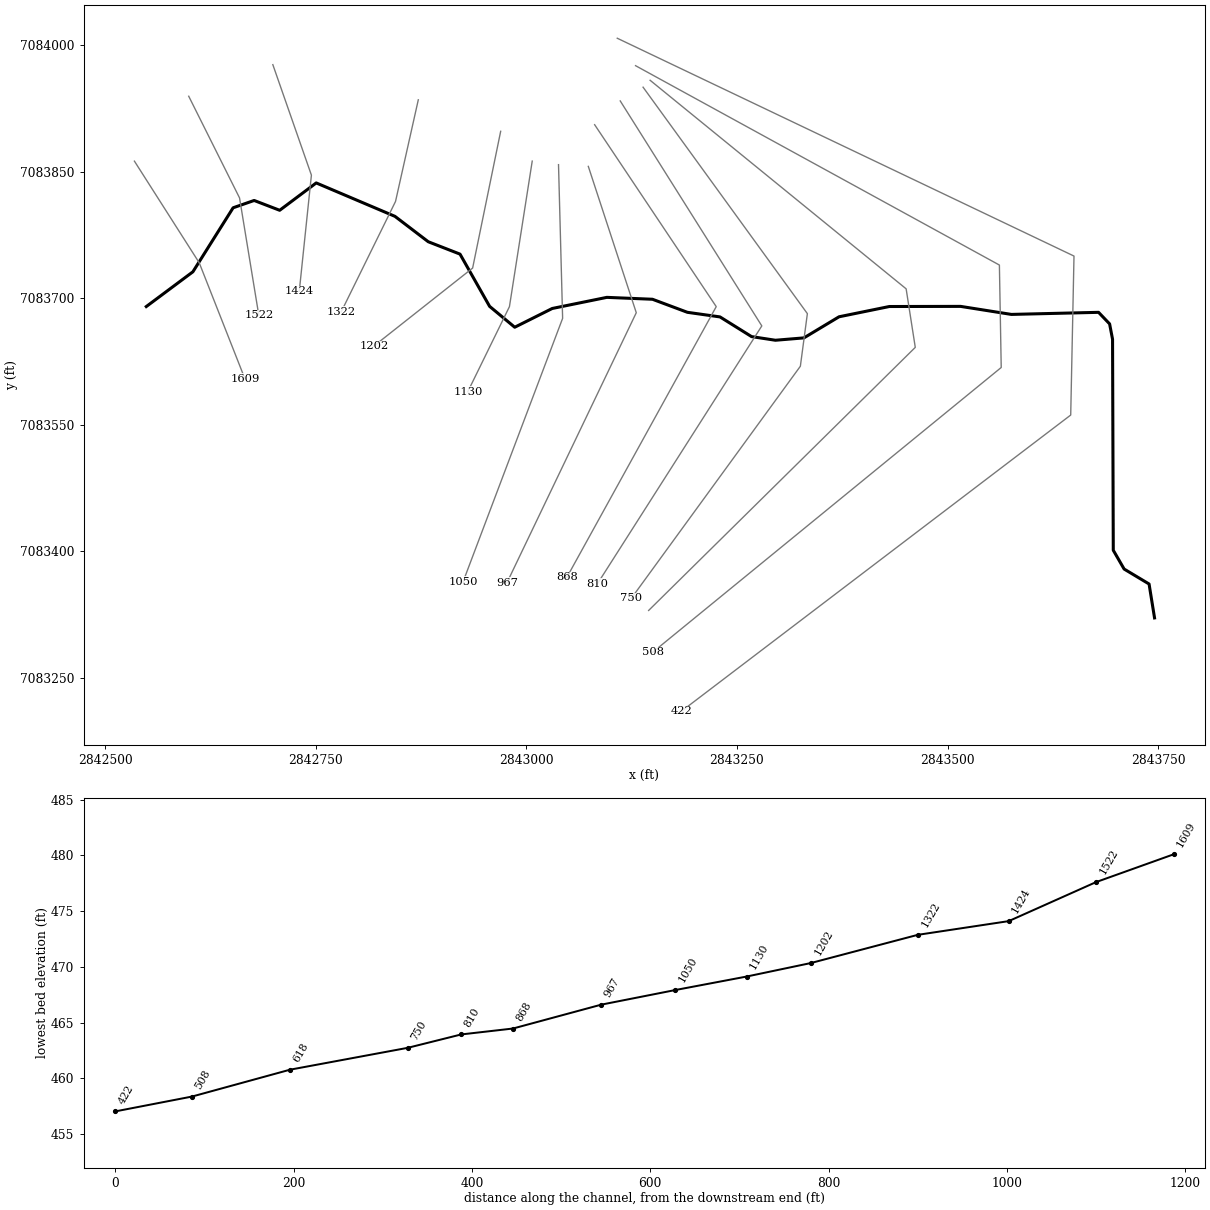
--- UNT 117 in LFCCL Watershed.prj (project) ---

Proj Title=UNT 117 in LFCCL Watershed Base Level Engineering
Current Plan=p01
Default Exp/Contr=0.3,0.1
English Units
Geom File=g01
Flow File=f01
Plan File=p01
BEGIN DESCRIPTION:
UNT 117 in LFCCL Watershed
END DESCRIPTION:

--- UNT 117 in LFCCL Watershed.p01 (plan) ---

Plan Title=Multiple Run
Short Identifier=Multiple
Geom File=g01
Flow File=f01
Subcritical Flow
K Sum by GR= 0
Std Step Tol= 0.01
Critical Tol= 0.01
Num of Std Step Trials= 20
Max Error Tol= 0.3
Flow Tol Ratio= 0.001
Split Flow NTrial= 30
Split Flow Tol= 0.02
Split Flow Ratio= 0.02
Log Output Level= 0
Friction Slope Method= 1
Unsteady Friction Slope Method= 2
Unsteady Bridges Friction Slope Method= 1
Parabolic Critical Depth
Global Vel Dist=  1 , 1 , 1
Global Log Level= 0
CheckData=True
Encroach Param= -1, 0, 0, 0
BEGIN DESCRIPTION:
Multiple Run
END DESCRIPTION:

--- UNT 117 in LFCCL Watershed.f01 (steady flow) ---

Flow Title=Multiple
Number of Profiles=7
Profile Names=10-year,25-year,50-year,1pct_min,100-year,1pct_plu,500-year
River Rch & RM= UNT 117 in LFCCL,Reach-1,1609
     244     306     354     204     408     813     536
Boundary for River Rch & Prof#=UNT 117 in LFCCL,Reach-1,1
Up Type=0
Dn Type=3
Dn Slope=0.005
Boundary for River Rch & Prof#=UNT 117 in LFCCL,Reach-1,2
Up Type=0
Dn Type=3
Dn Slope=0.005
Boundary for River Rch & Prof#=UNT 117 in LFCCL,Reach-1,3
Up Type=0
Dn Type=3
Dn Slope=0.005
Boundary for River Rch & Prof#=UNT 117 in LFCCL,Reach-1,4
Up Type=0
Dn Type=3
Dn Slope=0.005
Boundary for River Rch & Prof#=UNT 117 in LFCCL,Reach-1,5
Up Type=0
Dn Type=3
Dn Slope=0.005
Boundary for River Rch & Prof#=UNT 117 in LFCCL,Reach-1,6
Up Type=0
Dn Type=3
Dn Slope=0.005
Boundary for River Rch & Prof#=UNT 117 in LFCCL,Reach-1,7
Up Type=0
Dn Type=3
Dn Slope=0.005

--- UNT 117 in LFCCL Watershed.g01 (geometry) ---

Geom Title=Existing Conditions

River Reach=UNT 117 in LFCCL,Reach-1
Reach XY= 30
      2842548.96      7083690.10      2842604.30      7083731.33
      2842652.05      7083807.28      2842677.00      7083815.96
      2842707.30      7083804.31      2842750.66      7083836.77
      2842844.10      7083797.13      2842883.62      7083767.00
      2842921.33      7083752.30      2842956.43      7083690.34
      2842986.26      7083665.57      2843030.74      7083687.81
      2843095.61      7083701.01      2843149.72      7083698.76
      2843191.19      7083683.27      2843229.87      7083677.81
      2843267.32      7083654.46      2843295.64      7083650.13
      2843329.47      7083652.93      2843371.14      7083677.96
      2843430.84      7083690.15      2843515.39      7083690.31
      2843575.68      7083680.78      2843679.14      7083683.25
      2843692.26      7083669.54      2843695.76      7083651.31
      2843696.62      7083400.99      2843709.49      7083378.70
      2843739.10      7083360.95      2843745.59      7083320.71

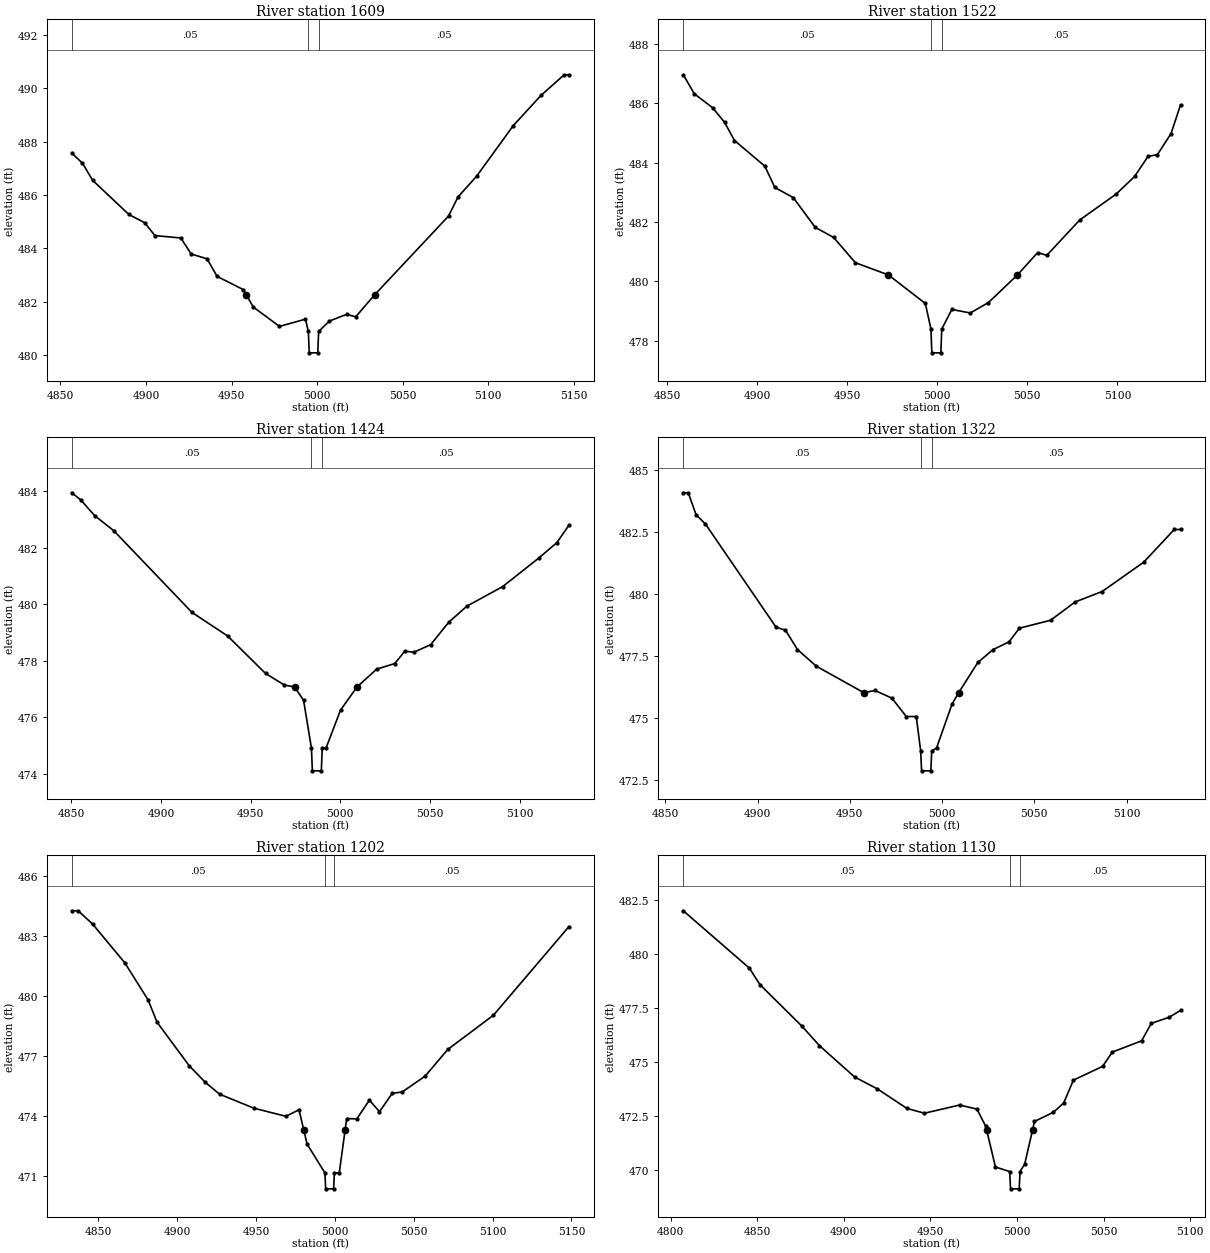
Type RM Length L Ch R = 1,1609,87,87,87
BEGIN DESCRIPTION:
UNT 117 in LFCCL Watershed 2.0
END DESCRIPTION:
XS GIS Cut Line= 3
      2842534.90      7083862.61      2842611.83      7083742.01
      2842665.91      7083604.73
#Sta/Elev= 30
  4856.6  487.57  4862.9  487.19  4868.8  486.55  4890.0  485.27  4899.3  484.96
  4905.2  484.48  4920.4  484.39  4926.4  483.79  4935.7  483.61  4941.6  482.95
  4956.8  482.46  4958.6  482.26  4962.8  481.80  4978.0  481.08  4993.2  481.35
  4994.9  480.89  4995.4  480.09  5000.4  480.09  5000.9  480.89  5007.2  481.28
  5017.2  481.53  5022.6  481.44  5033.6  482.26  5076.8  485.21  5082.4  485.93
  5093.2  486.70  5114.7  488.60  5130.9  489.73  5144.4  490.50  5147.2  490.50
#Mann=3,-1,0
  4856.6    0.05       0  4994.9    0.03       0  5000.9    0.05       0
Bank Sta=4958.6,5033.6
Exp/Cntr=0.3,0.1

Type RM Length L Ch R = 1,1522,98,98,98
BEGIN DESCRIPTION:
XS3753A
END DESCRIPTION:
XS GIS Cut Line= 3
      2842599.36      7083939.60      2842659.67      7083818.97
      2842682.52      7083679.80
#Sta/Elev= 30
  4859.1  486.95  4865.2  486.31  4875.4  485.84  4882.0  485.35  4887.5  484.74
  4904.3  483.88  4909.9  483.16  4920.1  482.82  4932.3  481.82  4942.5  481.48
  4954.6  480.63  4972.9  480.22  4993.4  479.26  4996.5  478.40  4997.0  477.60
  5002.0  477.60  5002.5  478.40  5008.1  479.06  5018.3  478.94  5028.4  479.29
  5044.5  480.22  5055.7  480.97  5060.8  480.88  5079.1  482.07  5099.3  482.94
  5109.5  483.53  5117.0  484.21  5122.1  484.26  5129.7  484.97  5135.0  485.94
#Mann=3,-1,0
  4859.1    0.05       0  4996.5    0.03       0  5002.5    0.05       0
Bank Sta=4972.9,5044.5
Exp/Cntr=0.3,0.1

Type RM Length L Ch R = 1,1424,102,102,102
BEGIN DESCRIPTION:
XS3754A
END DESCRIPTION:
XS GIS Cut Line= 3
      2842699.18      7083977.07      2842744.95      7083846.01
      2842730.56      7083708.29
#Sta/Elev= 28
  4850.2  483.95  4855.2  483.70  4863.0  483.14  4873.6  482.61  4917.3  479.71
  4937.1  478.88  4958.3  477.55  4968.8  477.14  4974.5  477.07  4979.5  476.60
  4983.9  474.90  4984.4  474.10  4989.4  474.10  4989.9  474.90  4992.0  474.90
  5000.1  476.25  5009.3  477.07  5020.2  477.70  5030.3  477.90  5036.0  478.34
  5041.0  478.30  5050.4  478.57  5060.4  479.36  5070.5  479.93  5090.6  480.63
  5110.7  481.64  5120.7  482.18  5127.5  482.80
#Mann=3,-1,0
  4850.2    0.05       0  4983.9    0.03       0  4989.9    0.05       0
Bank Sta=4974.5,5009.3
Exp/Cntr=0.3,0.1

Type RM Length L Ch R = 1,1322,120,120,120
BEGIN DESCRIPTION:
XS3755A
END DESCRIPTION:
XS GIS Cut Line= 3
      2842871.82      7083935.40      2842844.79      7083814.81
      2842780.32      7083683.80
#Sta/Elev= 30
  4859.7  484.08  4862.4  484.08  4866.6  483.20  4871.7  482.82  4910.0  478.66
  4915.1  478.54  4921.6  477.76  4931.8  477.09  4957.6  476.02  4963.6  476.11
  4972.8  475.80  4980.6  475.06  4986.0  475.06  4988.4  473.67  4988.9  472.87
  4993.9  472.87  4994.4  473.67  4997.0  473.79  5005.4  475.56  5009.0  476.02
  5019.4  477.24  5027.7  477.76  5036.3  478.07  5041.9  478.62  5058.8  478.94
  5072.2  479.68  5086.8  480.10  5109.3  481.28  5125.9  482.60  5129.3  482.60
#Mann=3,-1,0
  4859.7    0.05       0  4988.4    0.03       0  4994.4    0.05       0
Bank Sta=4957.6,5009
Exp/Cntr=0.3,0.1

Type RM Length L Ch R = 1,1202,72,72,72
BEGIN DESCRIPTION:
XS3756A
END DESCRIPTION:
XS GIS Cut Line= 3
      2842969.58      7083898.02      2842936.30      7083735.77
      2842818.90      7083643.09
#Sta/Elev= 30
  4833.2  484.26  4837.3  484.26  4846.5  483.59  4866.9  481.65  4881.6  479.80
  4887.3  478.68  4907.7  476.50  4917.9  475.67  4926.9  475.08  4948.6  474.38
  4969.0  473.97  4977.3  474.30  4980.3  473.28  4982.4  472.58  4993.7  471.14
  4994.2  470.34  4999.2  470.34  4999.7  471.14  5002.8  471.14  5006.5  473.28
  5007.5  473.86  5013.9  473.84  5021.9  474.78  5028.3  474.20  5036.4  475.12
  5042.7  475.19  5057.2  475.98  5071.6  477.32  5100.5  479.03  5148.4  483.47
#Mann=3,-1,0
  4833.2    0.05       0  4993.7    0.03       0  4999.7    0.05       0
Bank Sta=4980.3,5006.5
Exp/Cntr=0.3,0.1

Type RM Length L Ch R = 1,1130,80,80,80
BEGIN DESCRIPTION:
XS3757A
END DESCRIPTION:
XS GIS Cut Line= 3
      2843007.02      7083862.66      2842979.98      7083690.01
      2842930.52      7083589.03
#Sta/Elev= 30
  4807.3  482.00  4845.4  479.35  4851.6  478.58  4875.8  476.66  4885.9  475.76
  4906.2  474.31  4919.3  473.76  4936.5  472.85  4946.6  472.63  4966.9  473.01
  4976.9  472.82  4982.0  472.02  4982.5  471.85  4987.6  470.14  4995.8  469.93
  4996.3  469.13  5001.3  469.13  5001.8  469.93  5004.5  470.28  5009.0  471.85
  5010.1  472.25  5021.0  472.67  5027.0  473.10  5032.6  474.16  5049.5  474.80
  5055.1  475.46  5072.0  475.98  5077.6  476.79  5087.9  477.07  5094.5  477.39
#Mann=3,-1,0
  4807.3    0.05       0  4995.8    0.03       0  5001.8    0.05       0
Bank Sta=4982.5,5009
Exp/Cntr=0.3,0.1

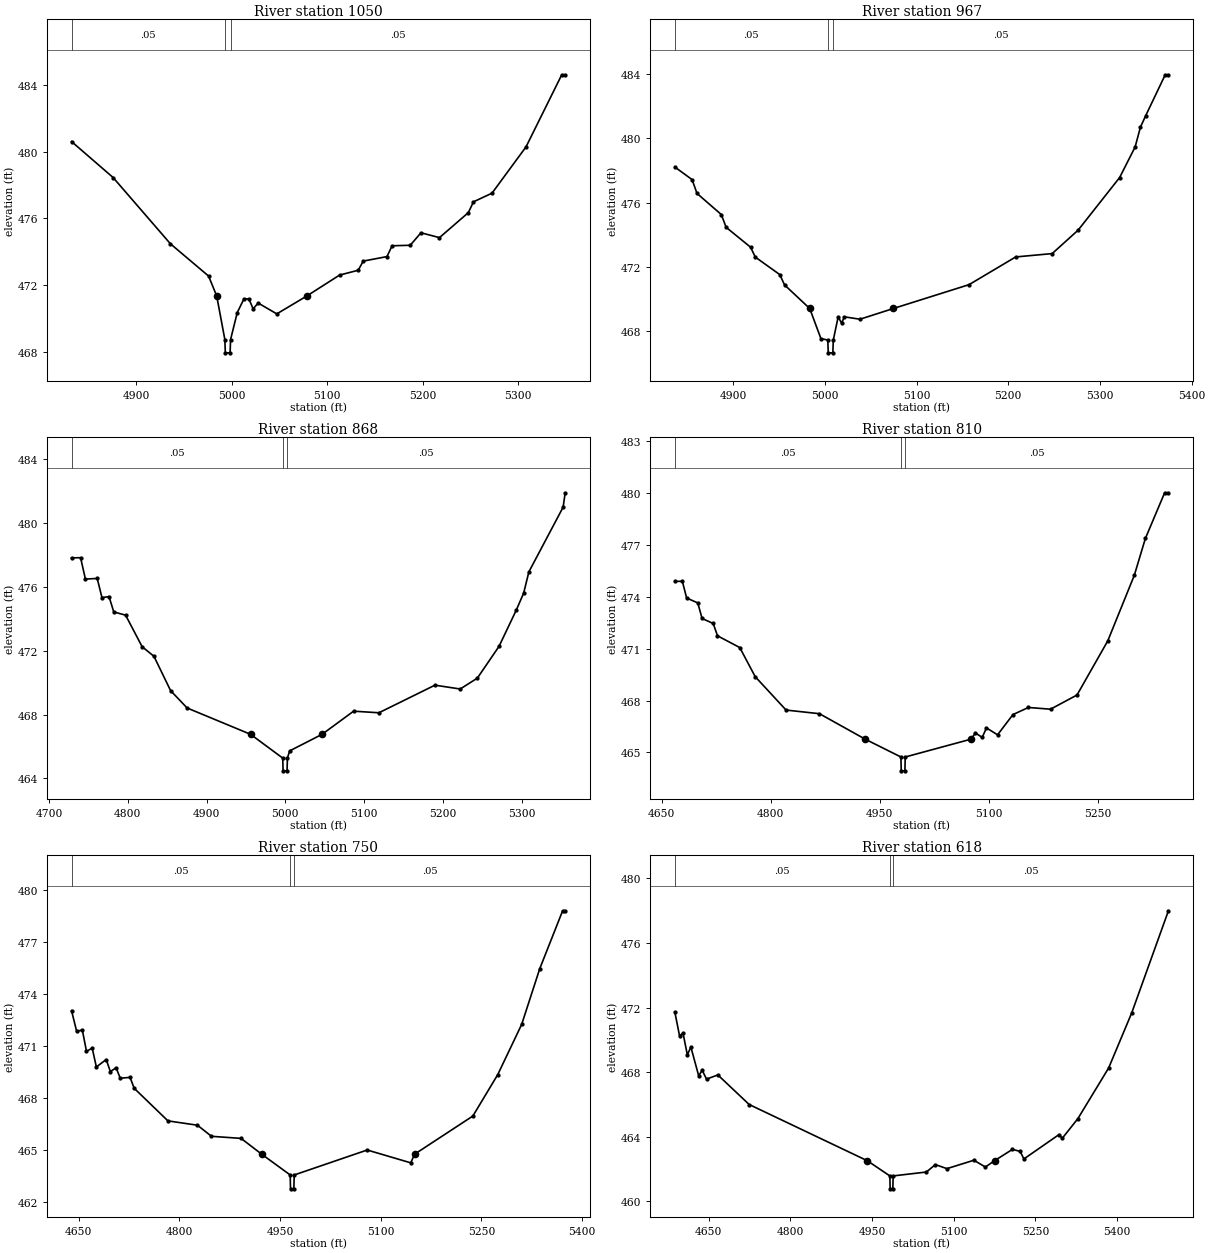
Type RM Length L Ch R = 1,1050,83,83,83
BEGIN DESCRIPTION:
XS3758A
END DESCRIPTION:
XS GIS Cut Line= 3
      2843038.22      7083858.45      2843043.10      7083676.13
      2842924.85      7083363.32
#Sta/Elev= 30
  4832.5  480.61  4876.0  478.45  4936.0  474.47  4976.0  472.53  4984.5  471.33
  4993.0  468.72  4993.5  467.92  4998.5  467.92  4999.0  468.72  5006.0  470.34
  5013.0  471.16  5018.2  471.16  5022.6  470.56  5027.9  470.91  5047.4  470.26
  5078.7  471.33  5113.1  472.59  5132.6  472.88  5137.9  473.43  5162.7  473.70
  5168.1  474.35  5187.1  474.38  5198.3  475.13  5217.7  474.84  5247.9  476.34
  5253.3  476.99  5272.7  477.51  5308.3  480.29  5345.7  484.62  5349.3  484.62
#Mann=3,-1,0
  4832.5    0.05       0  4993.0    0.03       0  4999.0    0.05       0
Bank Sta=4984.5,5078.7
Exp/Cntr=0.3,0.1

Type RM Length L Ch R = 1,967,99,99,99
BEGIN DESCRIPTION:
XS3759A
END DESCRIPTION:
XS GIS Cut Line= 3
      2843073.59      7083856.38      2843130.51      7083682.80
      2842976.94      7083362.26
#Sta/Elev= 30
  4836.5  478.22  4855.4  477.43  4860.7  476.57  4887.2  475.25  4892.5  474.45
  4919.1  473.21  4924.3  472.59  4950.9  471.50  4956.2  470.85  4983.6  469.38
  4995.8  467.50  5003.3  467.41  5003.8  466.61  5008.8  466.61  5009.3  467.41
  5014.6  468.86  5018.4  468.46  5021.3  468.86  5038.4  468.71  5074.8  469.38
  5157.3  470.87  5208.1  472.60  5247.9  472.81  5276.1  474.27  5321.4  477.56
  5338.3  479.47  5344.1  480.71  5349.7  481.41  5371.1  483.98  5374.6  483.98
#Mann=3,-1,0
  4836.5    0.05       0  5003.3    0.03       0  5009.3    0.05       0
Bank Sta=4983.6,5074.8
Exp/Cntr=0.3,0.1

Type RM Length L Ch R = 1,868,58,58,58
BEGIN DESCRIPTION:
XS3760A
END DESCRIPTION:
XS GIS Cut Line= 3
      2843081.09      7083905.85      2843225.41      7083690.01
      2843048.12      7083368.84
#Sta/Elev= 30
  4728.7  477.82  4740.2  477.83  4746.3  476.49  4761.3  476.53  4767.3  475.33
  4776.3  475.39  4782.3  474.43  4797.3  474.23  4818.3  472.25  4833.3  471.65
  4854.4  469.50  4875.4  468.41  4955.9  466.76  4996.7  465.27  4997.2  464.47
  5002.2  464.47  5002.7  465.27  5005.5  465.72  5046.7  466.76  5086.7  468.21
  5118.8  468.11  5189.9  469.84  5222.0  469.60  5243.7  470.28  5271.2  472.27
  5293.0  474.53  5302.5  475.61  5309.1  476.94  5352.6  481.00  5355.2  481.90
#Mann=3,-1,0
  4728.7    0.05       0  4996.7    0.03       0  5002.7    0.05       0
Bank Sta=4955.9,5046.7
Exp/Cntr=0.3,0.1

Type RM Length L Ch R = 1,810,60,60,60
BEGIN DESCRIPTION:
XS3761A
END DESCRIPTION:
XS GIS Cut Line= 3
      2843111.48      7083934.04      2843279.49      7083667.13
      2843084.35      7083361.14
#Sta/Elev= 30
  4668.2  474.88  4678.6  474.89  4684.5  473.92  4699.8  473.64  4705.7  472.74
  4721.0  472.45  4726.9  471.74  4757.5  471.06  4778.7  469.38  4821.1  467.45
  4867.0  467.24  4929.8  465.77  4978.9  464.74  4979.4  463.94  4984.4  463.94
  4984.9  464.74  5075.3  465.77  5081.3  466.13  5090.6  465.87  5096.5  466.42
  5111.7  466.02  5132.9  467.19  5154.1  467.60  5184.5  467.50  5220.9  468.32
  5263.2  471.45  5299.6  475.23  5314.8  477.36  5341.3  480.00  5346.5  480.00
#Mann=3,-1,0
  4668.2    0.05       0  4978.9    0.03       0  4984.9    0.05       0
Bank Sta=4929.8,5075.3
Exp/Cntr=0.3,0.1

Type RM Length L Ch R = 1,750,132,132,132
BEGIN DESCRIPTION:
XS3762A
END DESCRIPTION:
XS GIS Cut Line= 4
      2843138.57      7083950.36      2843333.57      7083681.69
      2843325.25      7083619.30      2843124.51      7083343.79
#Sta/Elev= 30
  4639.1  473.02  4646.7  471.83  4655.2  471.90  4661.4  470.67  4669.9  470.86
  4676.1  469.77  4690.8  470.20  4697.0  469.50  4705.5  469.73  4711.7  469.12
  4726.3  469.17  4732.5  468.54  4782.8  466.66  4826.8  466.41  4847.7  465.77
  4891.8  465.65  4922.5  464.74  4965.0  463.54  4965.5  462.74  4970.5  462.74
  4971.0  463.54  5079.8  464.98  5144.7  464.24  5150.5  464.74  5237.3  466.94
  5274.4  469.33  5310.0  472.22  5337.0  475.44  5371.1  478.78  5374.9  478.78
#Mann=3,-1,0
  4639.1    0.05       0  4965.0    0.03       0  4971.0    0.05       0
Bank Sta=4922.5,5150.5
Exp/Cntr=0.3,0.1

Type RM Length L Ch R = 1,618,110,110,110
BEGIN DESCRIPTION:
Mapping XS e8df9ad8
END DESCRIPTION:
XS GIS Cut Line= 4
      2843146.94      7083958.54      2843450.78      7083711.13
      2843461.63      7083641.68      2843145.18      7083329.56
#Sta/Elev= 30
  4587.7  471.74  4596.4  470.26  4602.9  470.41  4610.8  469.07  4617.2  469.56
  4631.6  467.78  4638.1  468.12  4646.0  467.57  4666.8  467.83  4724.3  466.00
  4941.3  462.52  4982.7  461.58  4983.2  460.78  4988.2  460.78  4988.7  461.58
  5049.8  461.82  5066.3  462.28  5087.5  462.03  5137.0  462.55  5158.2  462.13
  5174.9  462.52  5207.7  463.22  5221.9  463.10  5228.9  462.63  5292.6  464.12
  5299.6  463.92  5327.9  465.12  5384.5  468.26  5426.9  471.67  5494.3  477.99
#Mann=3,-1,0
  4587.7    0.05       0  4982.7    0.03       0  4988.7    0.05       0
Bank Sta=4941.3,5174.9
Exp/Cntr=0.3,0.1

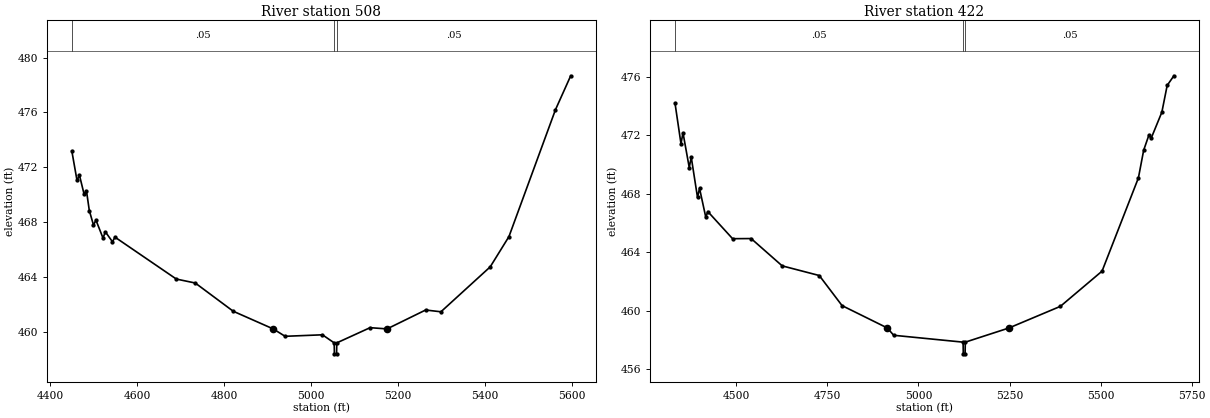
Type RM Length L Ch R = 1,508,86,86,86
BEGIN DESCRIPTION:
Mapping XS e375da5f
END DESCRIPTION:
XS GIS Cut Line= 4
      2843129.64      7083975.87      2843561.46      7083739.34
      2843563.63      7083617.81      2843150.05      7083280.02
#Sta/Elev= 30
  4449.7  473.19  4461.7  471.03  4467.4  471.40  4477.8  470.05  4483.5  470.26
  4490.0  468.83  4499.6  467.77  4505.3  468.13  4521.4  466.83  4527.1  467.27
  4543.3  466.55  4549.0  466.89  4690.2  463.83  4733.8  463.54  4821.1  461.48
  4913.1  460.19  4940.5  459.65  5026.4  459.76  5053.4  459.17  5053.9  458.37
  5058.9  458.37  5059.4  459.17  5136.0  460.28  5175.0  460.19  5263.8  461.57
  5299.0  461.44  5412.4  464.72  5455.5  466.93  5562.5  476.19  5597.6  478.67
#Mann=3,-1,0
  4449.7    0.05       0  5053.4    0.03       0  5059.4    0.05       0
Bank Sta=4913.1,5175
Exp/Cntr=0.3,0.1

Type RM Length L Ch R = 1,422,0,0,0
BEGIN DESCRIPTION:
UNT 117 in LFCCL Watershed 1.0
END DESCRIPTION:
XS GIS Cut Line= 4
      2843107.94      7084008.42      2843650.00      7083750.00
      2843646.10      7083561.39      2843183.94      7083209.89
#Sta/Elev= 30
  4331.4  474.21  4347.9  471.42  4353.4  472.17  4370.6  469.79  4376.1  470.50
  4393.3  467.74  4398.8  468.37  4416.0  466.39  4421.5  466.78  4489.6  464.92
  4540.5  464.93  4625.8  463.06  4727.6  462.40  4790.2  460.34  4914.5  458.81
  4931.9  458.31  5122.5  457.84  5123.0  457.04  5128.0  457.04  5128.5  457.84
  5248.4  458.81  5389.6  460.29  5504.0  462.70  5603.8  469.08  5618.3  470.98
  5632.9  472.03  5639.1  471.81  5668.2  473.58  5682.8  475.41  5701.2  476.07
#Mann=3,-1,0
  4331.4    0.05       0  5122.5    0.03       0  5128.5    0.05       0
Bank Sta=4914.5,5248.4
Exp/Cntr=0.3,0.1

Chan Stop Cuts=-1