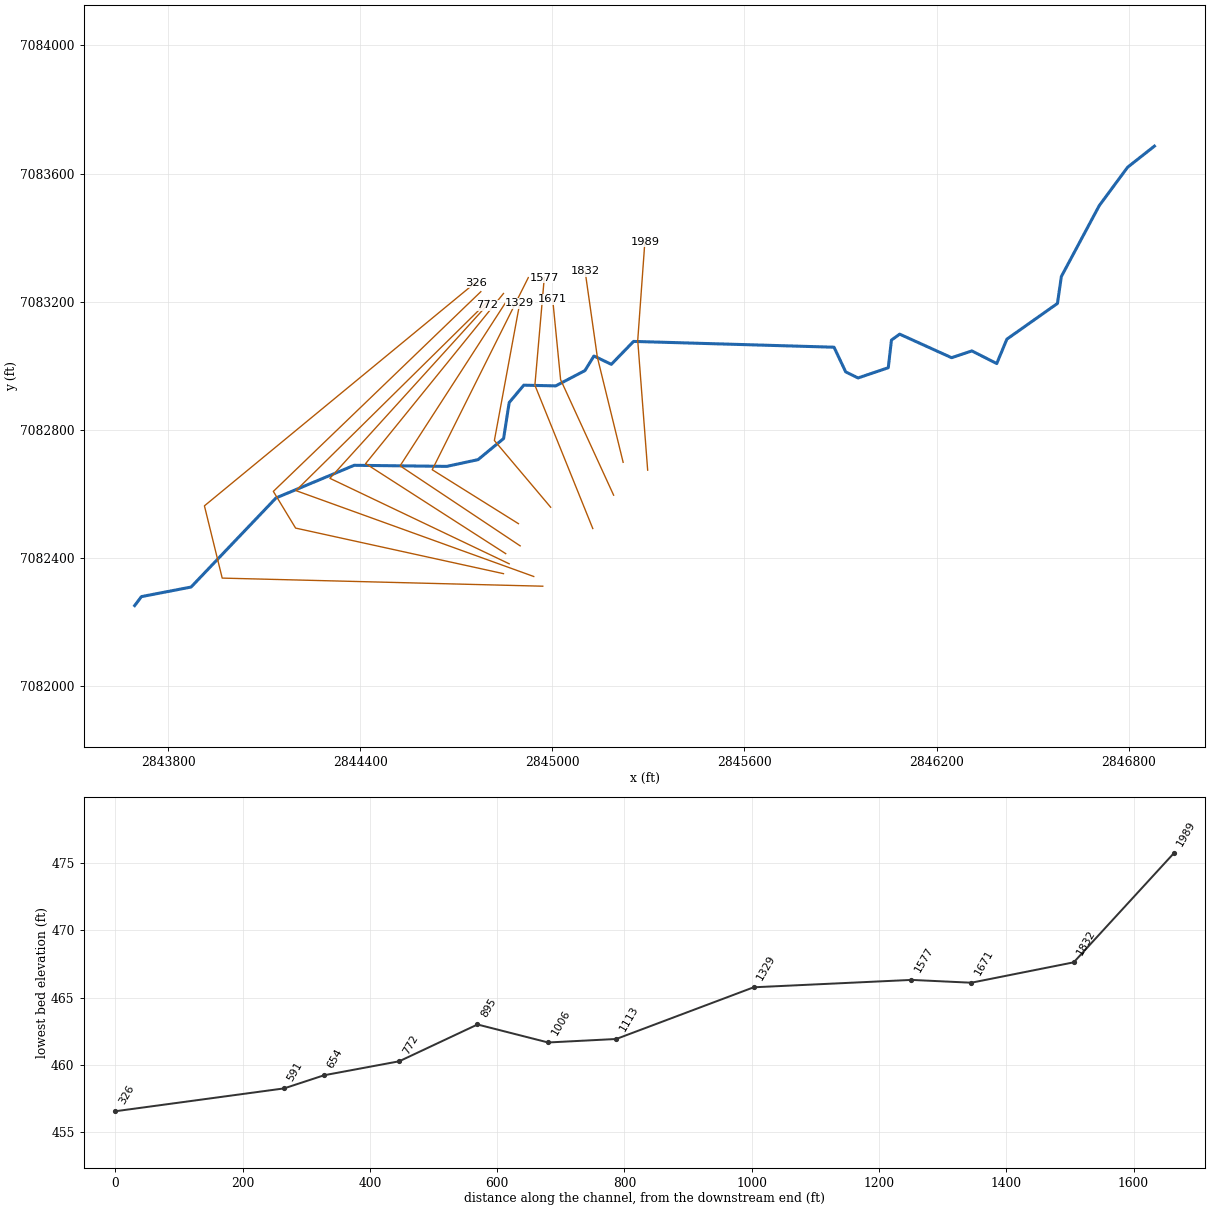
--- UNT 118 in LFCCL Watershed.prj (project) ---

Proj Title=UNT 118 in LFCCL Watershed Base Level Engineering
Current Plan=p01
Default Exp/Contr=0.3,0.1
English Units
Geom File=g01
Flow File=f01
Plan File=p01
BEGIN DESCRIPTION:
UNT 118 in LFCCL Watershed
END DESCRIPTION:

--- UNT 118 in LFCCL Watershed.p01 (plan) ---

Plan Title=Multiple Run
Short Identifier=Multiple
Geom File=g01
Flow File=f01
Subcritical Flow
K Sum by GR= 0
Std Step Tol= 0.01
Critical Tol= 0.01
Num of Std Step Trials= 20
Max Error Tol= 0.3
Flow Tol Ratio= 0.001
Split Flow NTrial= 30
Split Flow Tol= 0.02
Split Flow Ratio= 0.02
Log Output Level= 0
Friction Slope Method= 1
Unsteady Friction Slope Method= 2
Unsteady Bridges Friction Slope Method= 1
Parabolic Critical Depth
Global Vel Dist=  1 , 1 , 1
Global Log Level= 0
CheckData=True
Encroach Param= -1, 0, 0, 0
BEGIN DESCRIPTION:
Multiple Run
END DESCRIPTION:

--- UNT 118 in LFCCL Watershed.f01 (steady flow) ---

Flow Title=Multiple
Number of Profiles=7
Profile Names=10-year,25-year,50-year,1pct_min,100-year,1pct_plu,500-year
River Rch & RM= UNT 118 in LFCCL,Reach-1,1989
     386     499     588     345     688    1373     937
Boundary for River Rch & Prof#=UNT 118 in LFCCL,Reach-1,1
Up Type=0
Dn Type=3
Dn Slope=0.005
Boundary for River Rch & Prof#=UNT 118 in LFCCL,Reach-1,2
Up Type=0
Dn Type=3
Dn Slope=0.005
Boundary for River Rch & Prof#=UNT 118 in LFCCL,Reach-1,3
Up Type=0
Dn Type=3
Dn Slope=0.005
Boundary for River Rch & Prof#=UNT 118 in LFCCL,Reach-1,4
Up Type=0
Dn Type=3
Dn Slope=0.005
Boundary for River Rch & Prof#=UNT 118 in LFCCL,Reach-1,5
Up Type=0
Dn Type=3
Dn Slope=0.005
Boundary for River Rch & Prof#=UNT 118 in LFCCL,Reach-1,6
Up Type=0
Dn Type=3
Dn Slope=0.005
Boundary for River Rch & Prof#=UNT 118 in LFCCL,Reach-1,7
Up Type=0
Dn Type=3
Dn Slope=0.005

--- UNT 118 in LFCCL Watershed.g01 (geometry) ---

Geom Title=Existing Conditions

River Reach=UNT 118 in LFCCL,Reach-1
Reach XY= 30
      2846880.59      7083685.71      2846796.74      7083619.73
      2846708.14      7083499.65      2846589.84      7083278.33
      2846577.73      7083194.41      2846419.67      7083082.75
      2846388.12      7083006.64      2846310.41      7083046.11
      2846247.12      7083024.94      2846084.92      7083098.45
      2846059.22      7083079.81      2846049.34      7082993.63
      2845954.88      7082961.66      2845916.33      7082980.61
      2845879.92      7083057.68      2845253.79      7083075.79
      2845184.35      7083004.18      2845130.10      7083030.22
      2845101.88      7082984.65      2845010.74      7082936.90
      2844910.91      7082939.07      2844865.34      7082884.82
      2844847.84      7082772.38      2844768.16      7082706.51
      2844670.33      7082685.49      2844381.35      7082688.88
      2844137.14      7082586.95      2843871.84      7082308.62
      2843716.82      7082278.74      2843695.59      7082250.71

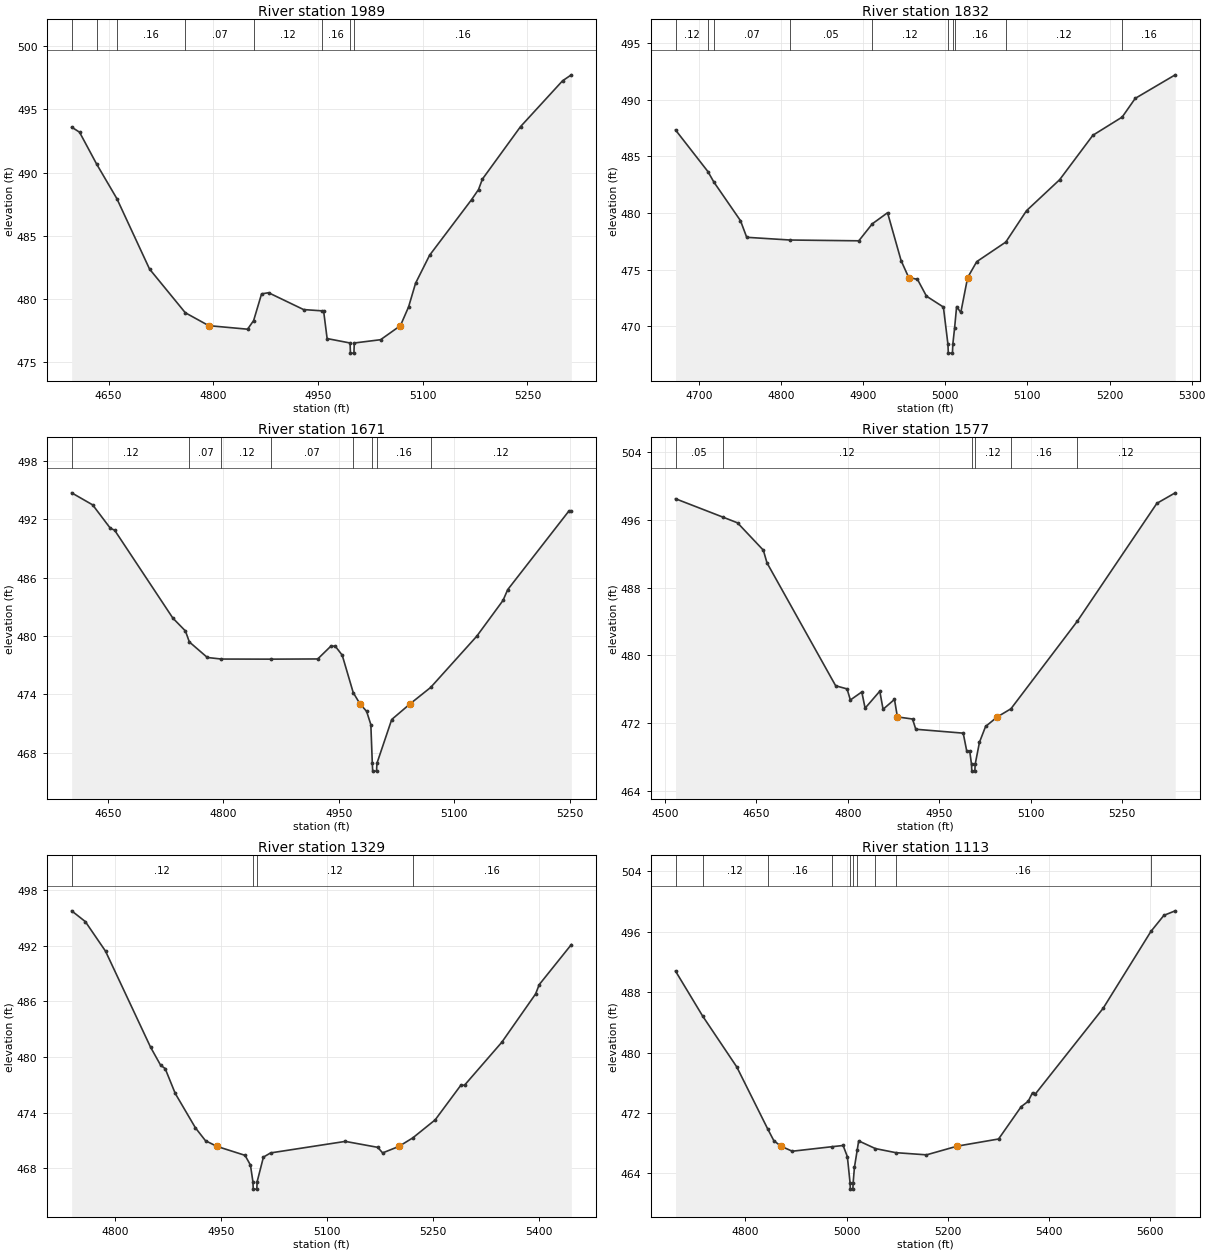
Type RM Length L Ch R = 1,1989,157,157,157
BEGIN DESCRIPTION:
UNT 118 in LFCCL Watershed 4.0
END DESCRIPTION:
XS GIS Cut Line= 3
      2845297.86      7082673.71      2845266.82      7083078.83
      2845289.18      7083387.62
#Sta/Elev= 30
  4597.0  493.59  4608.3  493.19  4632.8  490.67  4661.8  487.94  4708.6  482.38
  4759.8  478.93  4793.4  477.91  4849.0  477.63  4857.7  478.31  4869.1  480.42
  4879.1  480.51  4929.3  479.18  4955.6  479.08  4958.0  479.06  4963.0  476.89
  4995.9  476.54  4996.4  475.74  5001.4  475.74  5001.9  476.54  5039.6  476.80
  5068.0  477.91  5079.7  479.39  5089.7  481.26  5109.8  483.47  5169.9  487.86
  5179.9  488.66  5185.4  489.48  5240.1  493.63  5300.3  497.25  5312.9  497.72
#Mann=8,-1,0
  4597.0    0.05       0  4632.8    0.12       0  4661.8    0.16       0
  4759.8    0.07       0  4857.7    0.12       0  4955.6    0.16       0
  4995.9    0.07       0  5001.9    0.16       0
Bank Sta=4793.4,5068
Exp/Cntr=0.3,0.1

Type RM Length L Ch R = 1,1832,161,161,161
BEGIN DESCRIPTION:
XS3764A
END DESCRIPTION:
XS GIS Cut Line= 3
      2845221.23      7082698.22      2845140.71      7083026.53
      2845102.56      7083294.28
#Sta/Elev= 30
  4671.5  487.34  4710.9  483.67  4718.2  482.74  4750.6  479.33  4758.2  477.86
  4811.0  477.62  4894.7  477.55  4911.1  479.05  4929.7  480.03  4946.2  475.80
  4955.5  474.30  4966.1  474.15  4977.1  472.66  4997.7  471.70  5003.2  468.43
  5003.7  467.63  5008.7  467.63  5009.2  468.43  5011.3  469.82  5013.8  471.74
  5018.9  471.22  5027.2  474.30  5038.3  475.71  5073.7  477.44  5098.9  480.21
  5139.3  482.95  5179.7  486.87  5215.4  488.48  5231.3  490.13  5280.0  492.21
#Mann=10,-1,0
  4671.5    0.12       0  4710.9    0.16       0  4718.2    0.07       0
  4811.0    0.05       0  4911.1    0.12       0  5003.2    0.07       0
  5009.2    0.12       0  5011.3    0.16       0  5073.7    0.12       0
  5215.4    0.16       0
Bank Sta=4955.5,5027.2
Exp/Cntr=0.3,0.1

Type RM Length L Ch R = 1,1671,94,94,94
BEGIN DESCRIPTION:
XS3763A
END DESCRIPTION:
XS GIS Cut Line= 3
      2845191.54      7082595.52      2845025.93      7082956.44
      2845001.19      7083207.32
#Sta/Elev= 30
  4602.9  494.74  4630.2  493.50  4653.2  491.09  4658.7  490.90  4734.4  481.85
  4750.7  480.53  4755.8  479.40  4779.2  477.80  4797.5  477.64  4862.3  477.63
  4922.6  477.65  4940.1  479.00  4945.6  478.94  4954.4  478.04  4968.7  474.19
  4977.4  473.04  4986.1  472.26  4991.6  470.89  4993.5  466.91  4994.0  466.11
  4999.0  466.11  4999.5  466.91  5018.7  471.42  5042.7  473.04  5069.3  474.72
  5129.2  479.99  5163.3  483.67  5169.4  484.78  5248.4  492.82  5252.1  492.82
#Mann=8,-1,0
  4602.9    0.12       0  4755.8    0.07       0  4797.5    0.12       0
  4862.3    0.07       0  4968.7    0.16       0  4993.5    0.07       0
  4999.5    0.16       0  5069.3    0.12       0
Bank Sta=4977.4,5042.7
Exp/Cntr=0.3,0.1

Type RM Length L Ch R = 1,1577,248,248,248
BEGIN DESCRIPTION:
UNT 118 in LFCCL Watershed 3.0
END DESCRIPTION:
XS GIS Cut Line= 3
      2845126.41      7082491.40      2844945.63      7082939.07
      2844975.00      7083274.99
#Sta/Elev= 30
  4517.2  498.52  4594.9  496.35  4619.0  495.67  4661.3  492.44  4667.3  490.94
  4780.0  476.41  4798.7  476.04  4804.1  474.73  4822.9  475.68  4828.3  473.76
  4852.4  475.77  4857.8  473.63  4876.5  474.80  4881.3  472.73  4906.1  472.48
  4911.5  471.27  4989.3  470.81  4995.1  468.69  5000.0  468.69  5002.9  467.12
  5003.4  466.32  5008.4  466.32  5008.9  467.12  5016.0  469.74  5026.0  471.60
  5045.2  472.73  5067.6  473.69  5176.8  484.07  5307.1  497.98  5337.2  499.22
#Mann=6,-1,0
  4517.2    0.05       0  4594.9    0.12       0  5002.9    0.07       0
  5008.9    0.12       0  5067.6    0.16       0  5176.8    0.12       0
Bank Sta=4881.3,5045.2
Exp/Cntr=0.3,0.1

Type RM Length L Ch R = 1,1329,216,216,216
BEGIN DESCRIPTION:
Mapping XS c0bae2bb
END DESCRIPTION:
XS GIS Cut Line= 3
      2844994.87      7082557.91      2844819.08      7082766.26
      2844898.29      7083194.89
#Sta/Elev= 30
  4737.9  495.74  4757.3  494.58  4785.9  491.40  4849.7  481.07  4864.0  479.12
  4870.5  478.75  4884.8  476.07  4913.4  472.37  4927.7  470.98  4944.0  470.37
  4983.7  469.41  4991.4  468.36  4994.9  466.57  4995.4  465.77  5000.4  465.77
  5000.9  466.57  5009.8  469.22  5020.0  469.67  5125.9  470.91  5171.9  470.27
  5178.8  469.67  5201.9  470.37  5221.6  471.29  5253.3  473.23  5289.8  476.97
  5294.9  476.96  5347.8  481.59  5395.7  486.79  5400.8  487.79  5446.4  492.11
#Mann=4,-1,0
  4737.9    0.12       0  4994.9    0.07       0  5000.9    0.12       0
  5221.6    0.16       0
Bank Sta=4944,5201.9
Exp/Cntr=0.3,0.1

Type RM Length L Ch R = 1,1113,107,107,107
BEGIN DESCRIPTION:
UNT 118 in LFCCL Watershed 2.0
END DESCRIPTION:
XS GIS Cut Line= 3
      2844894.20      7082506.58      2844625.00      7082675.00
      2844925.02      7083275.03
#Sta/Elev= 30
  4661.7  490.80  4715.3  484.85  4782.9  478.10  4843.7  469.94  4856.0  468.36
  4869.7  467.62  4892.6  466.94  4971.3  467.54  4993.2  467.70  5001.6  466.22
  5007.0  462.72  5007.5  461.92  5012.5  461.92  5013.0  462.72  5015.6  464.81
  5021.2  467.14  5024.0  468.31  5057.0  467.29  5097.4  466.75  5158.1  466.46
  5219.3  467.62  5300.7  468.56  5345.4  472.84  5359.4  473.56  5367.8  474.69
  5373.4  474.52  5507.5  485.87  5602.0  496.05  5627.7  498.18  5650.1  498.78
#Mann=10,-1,0
  4661.7    0.05       0  4715.3    0.12       0  4843.7    0.16       0
  4971.3    0.12       0  5007.0    0.07       0  5013.0    0.12       0
  5021.2    0.16       0  5057.0    0.12       0  5097.4    0.16       0
  5602.0    0.12       0
Bank Sta=4869.7,5219.3
Exp/Cntr=0.3,0.1

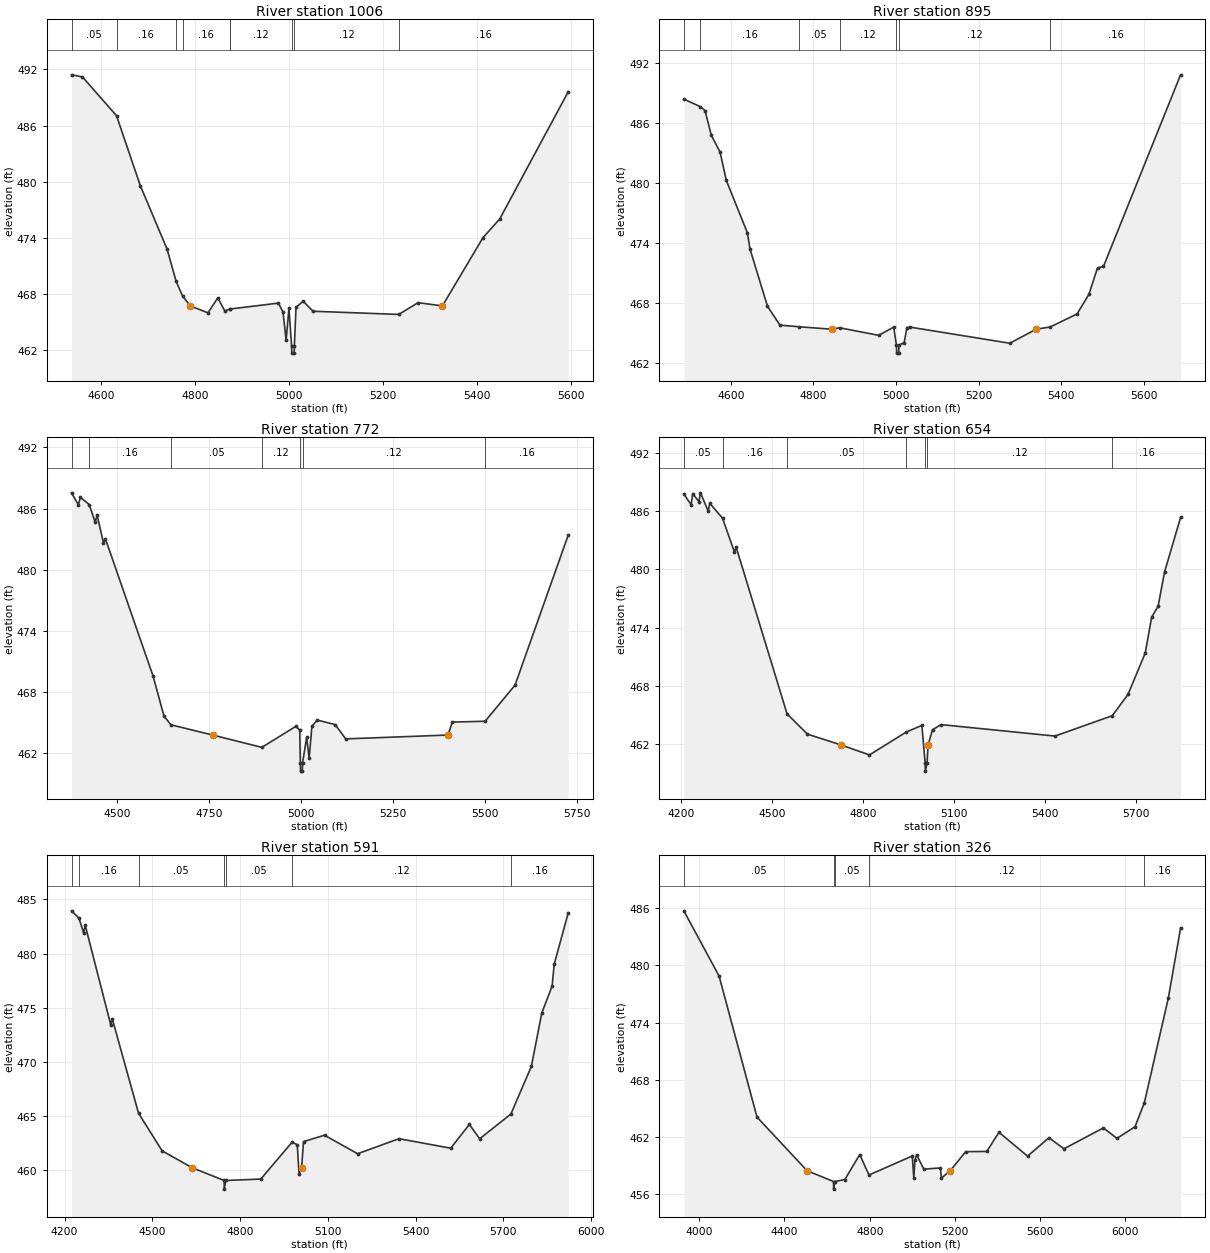
Type RM Length L Ch R = 1,1006,111,111,111
BEGIN DESCRIPTION:
Mapping XS 2892312c
END DESCRIPTION:
XS GIS Cut Line= 3
      2844899.60      7082437.23      2844524.60      7082687.23
      2844854.45      7083197.63
#Sta/Elev= 30
  4536.6  491.43  4559.9  491.21  4632.6  487.05  4683.1  479.59  4740.2  472.79
  4759.6  469.33  4773.3  467.76  4789.8  466.71  4827.3  465.97  4848.3  467.57
  4863.4  466.16  4874.5  466.39  4874.6  466.38  4977.5  467.01  4987.3  466.05
  4993.9  463.04  4999.9  466.46  5005.5  462.46  5006.0  461.66  5011.0  461.66
  5011.5  462.46  5015.0  466.56  5030.2  467.21  5051.3  466.14  5233.9  465.80
  5275.0  467.06  5326.9  466.71  5413.3  474.01  5449.0  476.01  5595.0  489.62
#Mann=9,-1,0
  4536.6    0.05       0  4632.6    0.16       0  4759.6    0.12       0
  4773.3    0.16       0  4874.5    0.05       0  4874.6    0.12       0
  5005.5    0.07       0  5011.5    0.12       0  5233.9    0.16       0
Bank Sta=4789.8,5326.9
Exp/Cntr=0.3,0.1

Type RM Length L Ch R = 1,895,123,123,123
BEGIN DESCRIPTION:
Mapping XS 10b784c8
END DESCRIPTION:
XS GIS Cut Line= 3
      2844854.43      7082412.94      2844416.96      7082694.17
      2844847.53      7083225.44
#Sta/Elev= 30
  4485.8  488.42  4525.5  487.67  4537.2  487.28  4552.4  484.80  4573.6  483.12
  4588.7  480.29  4639.7  475.05  4646.2  473.41  4688.5  467.69  4718.8  465.80
  4764.6  465.64  4845.1  465.39  4863.1  465.54  4957.9  464.78  4994.3  465.60
  5001.1  463.80  5001.6  463.00  5006.6  463.00  5007.1  463.80  5019.8  464.06
  5026.4  465.55  5032.8  465.61  5275.7  463.99  5339.6  465.39  5373.9  465.62
  5438.8  466.92  5467.6  468.89  5488.4  471.53  5502.8  471.67  5689.7  490.85
#Mann=7,-1,0
  4485.8    0.05       0  4525.5    0.16       0  4764.6    0.05       0
  4863.1    0.12       0  5001.1    0.07       0  5007.1    0.12       0
  5373.9    0.16       0
Bank Sta=4845.1,5339.6
Exp/Cntr=0.3,0.1

Type RM Length L Ch R = 1,772,118,118,118
BEGIN DESCRIPTION:
Mapping XS 5122bbaa
END DESCRIPTION:
XS GIS Cut Line= 3
      2844865.33      7082381.23      2844305.42      7082648.17
      2844795.84      7083188.50
#Sta/Elev= 30
  4375.5  487.55  4394.2  486.38  4399.7  487.11  4423.7  486.40  4439.6  484.68
  4445.1  485.36  4462.3  482.65  4467.8  483.03  4597.4  469.56  4626.7  465.67
  4645.7  464.80  4759.2  463.80  4892.8  462.59  4985.2  464.65  4995.8  464.29
  4997.4  461.06  4997.9  460.26  5002.9  460.26  5003.4  461.06  5014.6  463.56
  5021.4  461.51  5028.8  464.64  5043.0  465.27  5092.3  464.82  5120.7  463.42
  5398.7  463.80  5410.6  465.07  5499.6  465.15  5580.9  468.69  5725.5  483.41
#Mann=7,-1,0
  4375.5    0.05       0  4423.7    0.16       0  4645.7    0.05       0
  4892.8    0.12       0  4997.4    0.07       0  5003.4    0.12       0
  5499.6    0.16       0
Bank Sta=4759.2,5398.7
Exp/Cntr=0.3,0.1

Type RM Length L Ch R = 1,654,63,63,63
BEGIN DESCRIPTION:
XS3765A
END DESCRIPTION:
XS GIS Cut Line= 3
      2844941.98      7082341.63      2844199.31      7082609.78
      2844801.20      7083203.43
#Sta/Elev= 30
  4210.4  487.75  4234.4  486.66  4239.7  487.80  4259.8  486.98  4265.1  487.88
  4290.4  486.01  4295.8  486.80  4337.7  485.27  4377.1  481.76  4382.5  482.29
  4550.2  465.11  4617.2  463.03  4729.3  461.90  4821.3  460.89  4942.2  463.24
  4993.9  463.93  5004.8  460.02  5005.3  459.22  5010.8  460.02  5014.3  461.90
  5028.9  463.49  5057.2  464.01  5432.0  462.83  5620.7  464.93  5672.4  467.12
  5729.0  471.38  5750.2  475.08  5771.4  476.19  5792.7  479.74  5845.4  485.34
#Mann=7,-1,0
  4210.4    0.05       0  4337.7    0.16       0  4550.2    0.05       0
  4942.2    0.12       0  5004.8    0.07       0  5010.8    0.12       0
  5620.7    0.16       0
Bank Sta=4729.3,5014.3
Exp/Cntr=0.3,0.1

Type RM Length L Ch R = 1,591,265,265,265
BEGIN DESCRIPTION:
Mapping XS eda2e10b
END DESCRIPTION:
XS GIS Cut Line= 4
      2844847.52      7082350.42      2844198.21      7082492.79
      2844128.77      7082607.37      2844776.81      7083231.16
#Sta/Elev= 30
  4223.7  483.95  4248.9  483.29  4265.3  481.90  4270.4  482.64  4358.0  473.40
  4363.1  473.98  4452.8  465.26  4533.4  461.78  4636.5  460.21  4745.4  459.04
  4745.9  458.24  4751.4  459.04  4870.8  459.17  4977.9  462.58  4995.6  462.34
  5001.4  459.66  5010.3  460.21  5016.9  462.63  5088.7  463.22  5201.9  461.51
  5343.4  462.90  5520.1  462.02  5584.0  464.22  5619.2  462.89  5725.9  465.18
  5795.9  469.58  5831.4  474.51  5866.7  476.99  5873.9  479.01  5921.9  483.77
#Mann=7,-1,0
  4223.7    0.05       0  4248.9    0.16       0  4452.8    0.05       0
  4745.4    0.07       0  4751.4    0.05       0  4977.9    0.12       0
  5725.9    0.16       0
Bank Sta=4636.5,5010.3
Exp/Cntr=0.3,0.1

Type RM Length L Ch R = 1,326,0,0,0
BEGIN DESCRIPTION:
UNT 118 in LFCCL Watershed 1.0
END DESCRIPTION:
XS GIS Cut Line= 4
      2844970.21      7082311.25      2843969.04      7082336.54
      2843913.49      7082562.23      2844760.26      7083259.78
#Sta/Elev= 30
  3927.8  485.73  4093.1  478.89  4271.2  464.09  4506.2  458.47  4630.2  457.34
  4630.7  456.54  4636.2  457.34  4683.3  457.54  4753.3  460.17  4796.5  458.02
  4999.8  460.02  5007.0  457.69  5012.1  459.59  5020.4  460.14  5053.6  458.64
  5131.5  458.76  5136.7  457.71  5178.1  458.47  5250.2  460.47  5349.2  460.49
  5406.6  462.50  5540.8  460.00  5641.2  461.93  5711.5  460.77  5896.6  462.96
  5960.4  461.86  6045.1  463.09  6089.0  465.62  6201.4  476.59  6258.8  483.93
#Mann=5,-1,0
  3927.8    0.05       0  4630.2    0.07       0  4636.2    0.05       0
  4796.5    0.12       0  6089.0    0.16       0
Bank Sta=4506.2,5178.1
Exp/Cntr=0.3,0.1

Chan Stop Cuts=-1