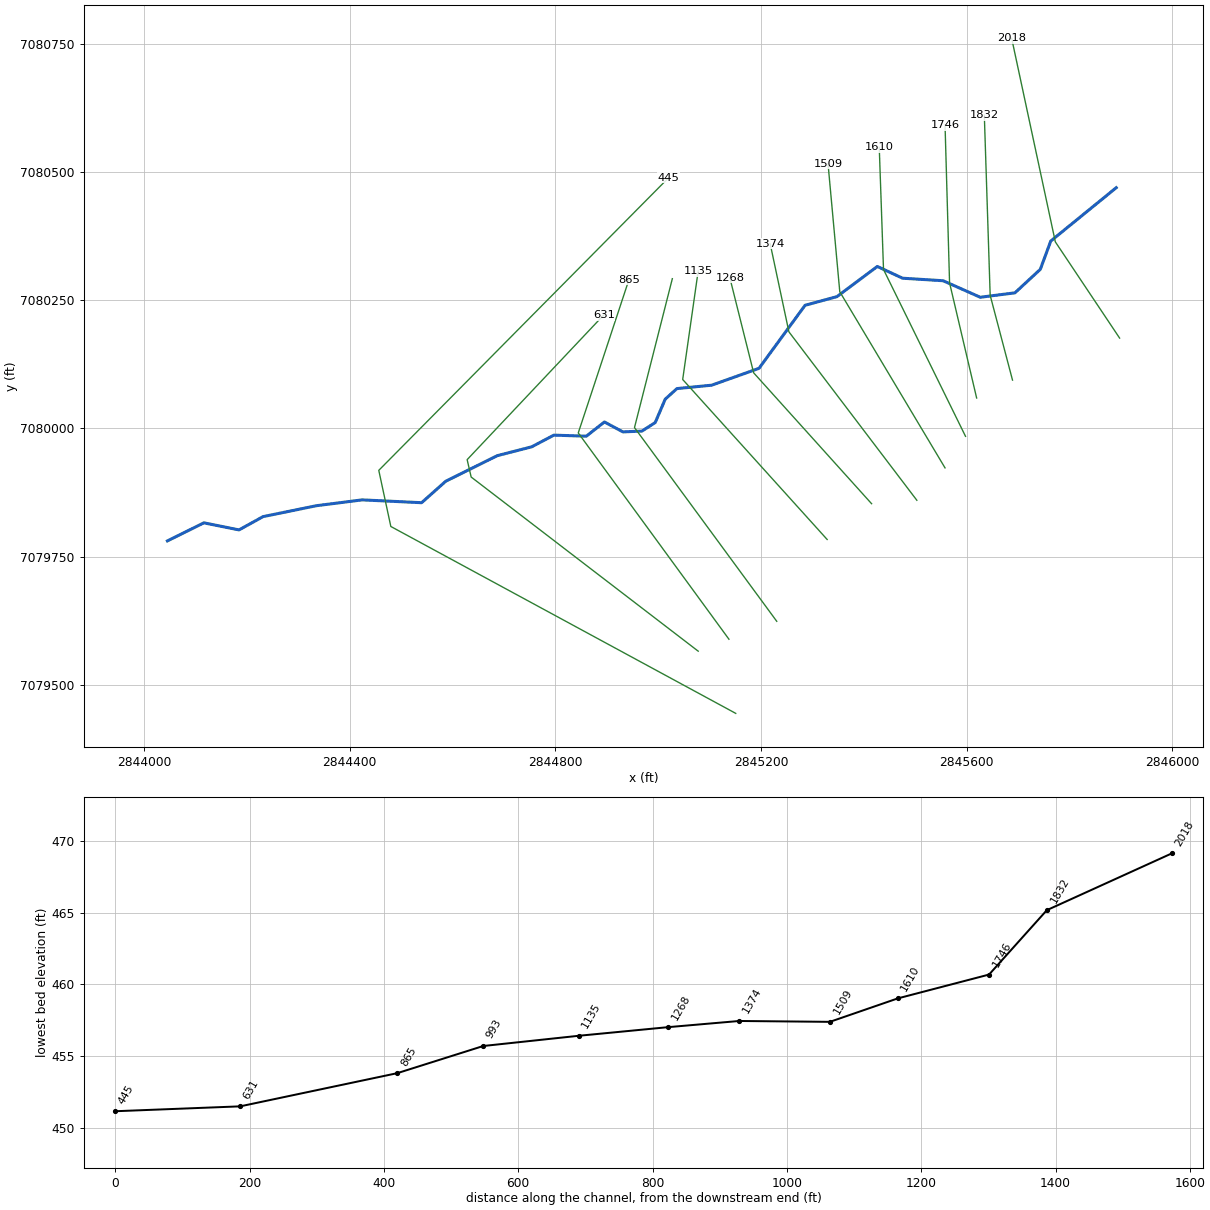
--- UNT 119 in LFCCL Watershed.prj (project) ---

Proj Title=UNT 119 in LFCCL Watershed Base Level Engineering
Current Plan=p01
Default Exp/Contr=0.3,0.1
English Units
Geom File=g01
Flow File=f01
Plan File=p01
BEGIN DESCRIPTION:
UNT 119 in LFCCL Watershed
END DESCRIPTION:

--- UNT 119 in LFCCL Watershed.p01 (plan) ---

Plan Title=Multiple Run
Short Identifier=Multiple
Geom File=g01
Flow File=f01
Subcritical Flow
K Sum by GR= 0
Std Step Tol= 0.01
Critical Tol= 0.01
Num of Std Step Trials= 20
Max Error Tol= 0.3
Flow Tol Ratio= 0.001
Split Flow NTrial= 30
Split Flow Tol= 0.02
Split Flow Ratio= 0.02
Log Output Level= 0
Friction Slope Method= 1
Unsteady Friction Slope Method= 2
Unsteady Bridges Friction Slope Method= 1
Parabolic Critical Depth
Global Vel Dist=  1 , 1 , 1
Global Log Level= 0
CheckData=True
Encroach Param= -1, 0, 0, 0
BEGIN DESCRIPTION:
Multiple Run
END DESCRIPTION:

--- UNT 119 in LFCCL Watershed.f01 (steady flow) ---

Flow Title=Multiple
Number of Profiles=7
Profile Names=10-year,25-year,50-year,1pct_min,100-year,1pct_plu,500-year
River Rch & RM= UNT 119 in LFCCL,Reach-1,2018
     430     560     662     390     779    1554    1070
Boundary for River Rch & Prof#=UNT 119 in LFCCL,Reach-1,1
Up Type=0
Dn Type=3
Dn Slope=0.005
Boundary for River Rch & Prof#=UNT 119 in LFCCL,Reach-1,2
Up Type=0
Dn Type=3
Dn Slope=0.005
Boundary for River Rch & Prof#=UNT 119 in LFCCL,Reach-1,3
Up Type=0
Dn Type=3
Dn Slope=0.005
Boundary for River Rch & Prof#=UNT 119 in LFCCL,Reach-1,4
Up Type=0
Dn Type=3
Dn Slope=0.005
Boundary for River Rch & Prof#=UNT 119 in LFCCL,Reach-1,5
Up Type=0
Dn Type=3
Dn Slope=0.005
Boundary for River Rch & Prof#=UNT 119 in LFCCL,Reach-1,6
Up Type=0
Dn Type=3
Dn Slope=0.005
Boundary for River Rch & Prof#=UNT 119 in LFCCL,Reach-1,7
Up Type=0
Dn Type=3
Dn Slope=0.005

--- UNT 119 in LFCCL Watershed.g01 (geometry) ---

Geom Title=Existing Conditions

River Reach=UNT 119 in LFCCL,Reach-1
Reach XY= 30
      2845891.19      7080469.08      2845763.88      7080365.18
      2845743.48      7080309.93      2845694.16      7080264.19
      2845626.70      7080255.55      2845554.40      7080287.77
      2845475.62      7080292.68      2845426.51      7080315.57
      2845347.80      7080256.73      2845285.95      7080239.93
      2845196.38      7080117.08      2845104.20      7080084.16
      2845036.69      7080077.57      2845013.89      7080056.90
      2844994.41      7080011.34      2844968.57      7079994.72
      2844931.66      7079993.19      2844895.68      7080012.47
      2844860.33      7079984.79      2844797.32      7079986.86
      2844754.23      7079964.09      2844687.20      7079946.81
      2844587.00      7079896.99      2844540.08      7079855.16
      2844424.53      7079860.67      2844335.40      7079849.32
      2844231.63      7079828.02      2844184.91      7079802.15
      2844116.58      7079815.92      2844045.59      7079780.71

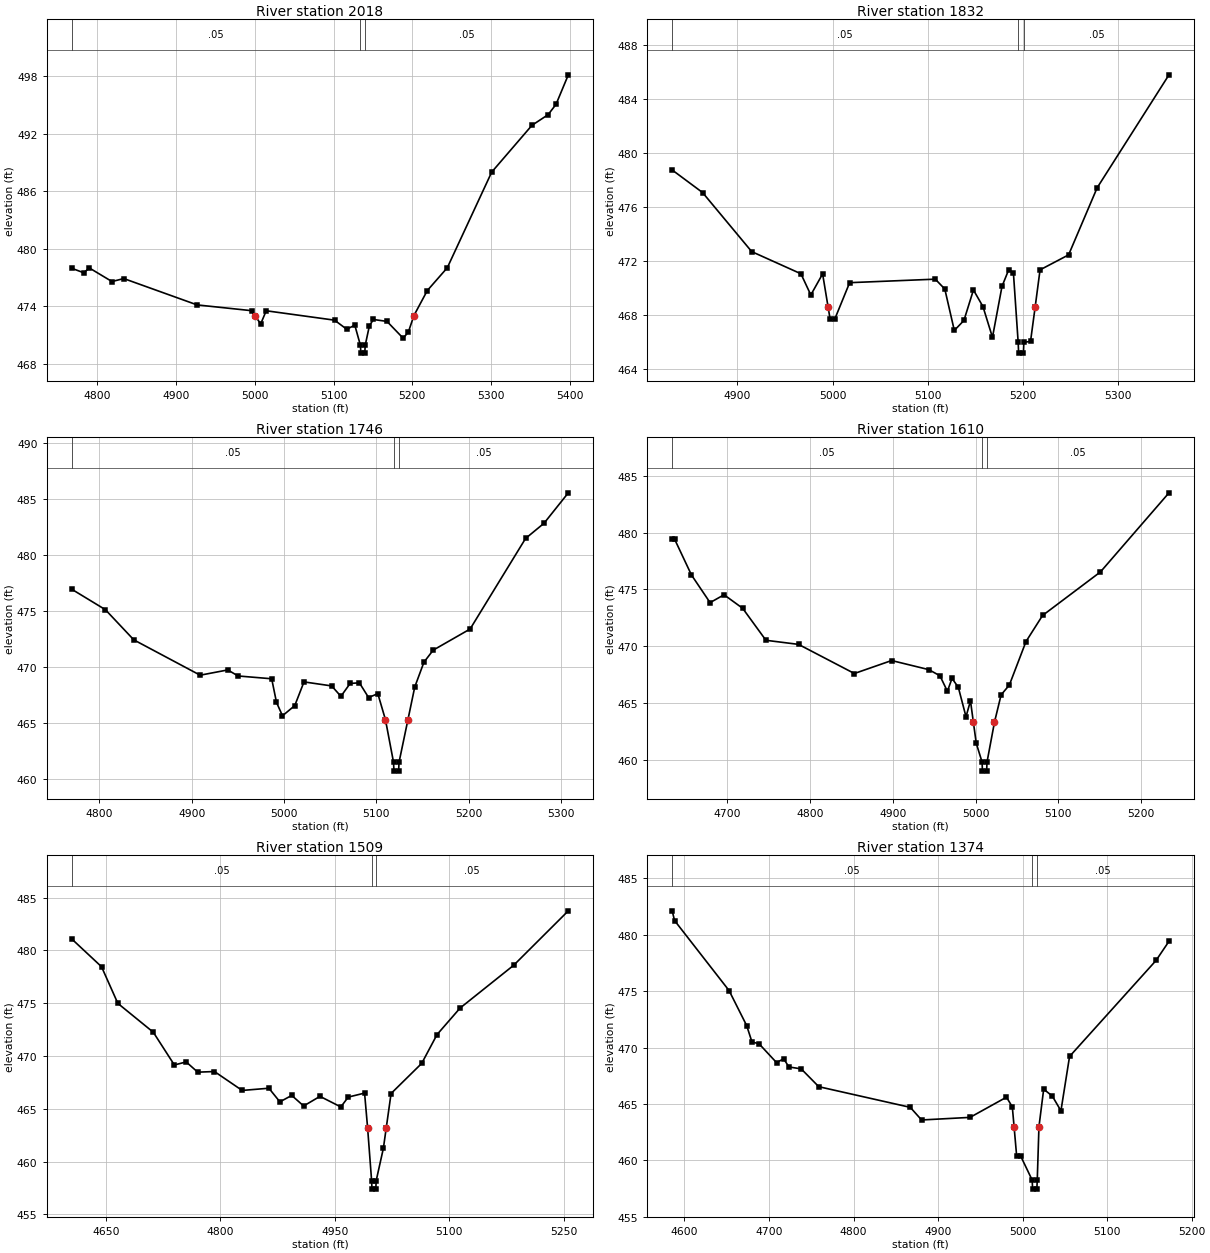
Type RM Length L Ch R = 1,2018,186,186,186
BEGIN DESCRIPTION:
UNT 119 in LFCCL Watershed 3.0
END DESCRIPTION:
XS GIS Cut Line= 3
      2845897.73      7080176.02      2845772.73      7080363.53
      2845687.79      7080760.18
#Sta/Elev= 30
  4767.1  477.98  4782.5  477.51  4789.9  478.00  4818.5  476.59  4833.5  476.90
  4926.7  474.15  4995.8  473.55  5000.0  473.04  5007.4  472.17  5014.4  473.54
  5101.2  472.56  5116.7  471.61  5126.9  472.04  5134.1  469.92  5134.6  469.12
  5139.6  469.12  5140.1  469.92  5145.5  471.99  5150.6  472.63  5167.8  472.43
  5188.3  470.68  5194.9  471.31  5202.0  473.04  5219.0  475.65  5244.4  478.03
  5300.8  488.01  5351.9  492.89  5372.4  494.00  5382.5  495.08  5398.1  498.16
#Mann=3,-1,0
  4767.1    0.05       0  5134.1    0.03       0  5140.1    0.05       0
Bank Sta=5000,5202
Exp/Cntr=0.3,0.1

Type RM Length L Ch R = 1,1832,86,86,86
BEGIN DESCRIPTION:
XS3766A
END DESCRIPTION:
XS GIS Cut Line= 3
      2845689.42      7080094.13      2845645.99      7080259.36
      2845634.60      7080610.43
#Sta/Elev= 30
  4831.5  478.74  4863.4  477.07  4915.1  472.69  4966.8  471.05  4977.2  469.48
  4989.6  471.04  4995.3  468.61  4997.5  467.68  5002.3  467.68  5018.0  470.39
  5108.0  470.65  5118.0  469.92  5128.0  466.85  5138.1  467.59  5148.1  469.85
  5158.1  468.62  5168.1  466.34  5178.1  470.11  5185.1  471.34  5190.1  471.13
  5195.1  465.97  5195.6  465.17  5200.6  465.17  5201.1  465.97  5208.1  466.04
  5213.0  468.61  5218.1  471.34  5248.1  472.45  5278.1  477.42  5353.6  485.79
#Mann=3,-1,0
  4831.5    0.05       0  5195.1    0.03       0  5201.1    0.05       0
Bank Sta=4995.3,5213
Exp/Cntr=0.3,0.1

Type RM Length L Ch R = 1,1746,136,136,136
BEGIN DESCRIPTION:
XS3775A
END DESCRIPTION:
XS GIS Cut Line= 3
      2845619.64      7080059.25      2845567.00      7080283.67
      2845558.20      7080591.33
#Sta/Elev= 30
  4769.8  476.97  4806.5  475.13  4837.3  472.43  4909.2  469.27  4939.1  469.74
  4950.3  469.20  4986.7  468.95  4991.9  466.84  4998.4  465.64  5011.7  466.55
  5021.7  468.67  5051.7  468.31  5061.7  467.38  5071.7  468.53  5081.7  468.59
  5091.7  467.27  5101.7  467.62  5110.0  465.28  5118.7  461.49  5119.2  460.69
  5124.2  460.69  5124.7  461.49  5134.3  465.28  5141.7  468.21  5151.7  470.44
  5161.7  471.51  5201.7  473.40  5261.8  481.50  5281.8  482.86  5308.1  485.58
#Mann=3,-1,0
  4769.8    0.05       0  5118.7    0.03       0  5124.7    0.05       0
Bank Sta=5110,5134.3
Exp/Cntr=0.3,0.1

Type RM Length L Ch R = 1,1610,101,101,101
BEGIN DESCRIPTION:
XS3774A
END DESCRIPTION:
XS GIS Cut Line= 3
      2845598.04      7079984.50      2845438.52      7080309.71
      2845430.24      7080547.74
#Sta/Elev= 30
  4633.4  479.39  4636.5  479.39  4656.7  476.27  4679.2  473.84  4696.1  474.53
  4718.6  473.34  4746.7  470.53  4786.1  470.17  4853.6  467.61  4898.6  468.75
  4943.6  467.95  4957.0  467.41  4966.0  466.05  4971.6  467.18  4979.2  466.40
  4988.5  463.81  4993.9  465.21  4997.4  463.33  5000.9  461.47  5007.9  459.83
  5008.4  459.03  5013.4  459.03  5013.9  459.83  5022.9  463.33  5030.9  465.73
  5040.9  466.60  5061.0  470.42  5081.0  472.71  5151.0  476.54  5233.8  483.49
#Mann=3,-1,0
  4633.4    0.05       0  5007.9    0.03       0  5013.9    0.05       0
Bank Sta=4997.4,5022.9
Exp/Cntr=0.3,0.1

Type RM Length L Ch R = 1,1509,135,135,135
BEGIN DESCRIPTION:
XS3773A
END DESCRIPTION:
XS GIS Cut Line= 3
      2845558.18      7079923.01      2845353.45      7080266.31
      2845330.56      7080516.15
#Sta/Elev= 30
  4605.2  481.10  4644.5  478.45  4665.9  474.98  4712.3  472.25  4739.9  469.15
  4755.4  469.44  4770.5  468.47  4792.4  468.53  4828.7  466.74  4863.7  466.95
  4878.1  465.66  4893.6  466.27  4909.2  465.27  4930.6  466.18  4957.9  465.18
  4967.6  466.11  4989.0  466.49  4993.0  463.16  4998.2  458.20  4998.7  457.40
  5003.7  457.40  5004.2  458.20  5013.6  461.26  5017.3  463.16  5023.7  466.45
  5063.8  469.30  5083.9  472.03  5114.1  474.54  5184.3  478.59  5255.8  483.74
#Mann=3,-1,0
  4605.2    0.05       0  4998.2    0.03       0  5004.2    0.05       0
Bank Sta=4993,5017.3
Exp/Cntr=0.3,0.1

Type RM Length L Ch R = 1,1374,106,106,106
BEGIN DESCRIPTION:
XS3772A
END DESCRIPTION:
XS GIS Cut Line= 3
      2845503.35      7079859.89      2845254.50      7080188.18
      2845218.05      7080360.01
#Sta/Elev= 30
  4585.5  482.13  4588.3  481.27  4652.8  475.06  4673.6  471.96  4679.9  470.50
  4688.2  470.35  4709.0  468.67  4717.3  469.02  4723.6  468.29  4738.1  468.12
  4758.9  466.54  4867.1  464.71  4880.5  463.59  4937.8  463.82  4980.9  465.61
  4987.8  464.75  4989.9  462.99  4992.9  460.42  4997.5  460.42  5011.3  458.26
  5011.8  457.46  5016.8  457.46  5017.3  458.26  5019.3  462.99  5024.9  466.32
  5035.1  465.71  5045.3  464.40  5055.5  469.22  5157.8  477.73  5173.1  479.43
#Mann=3,-1,0
  4585.5    0.05       0  5011.3    0.03       0  5017.3    0.05       0
Bank Sta=4989.9,5019.3
Exp/Cntr=0.3,0.1

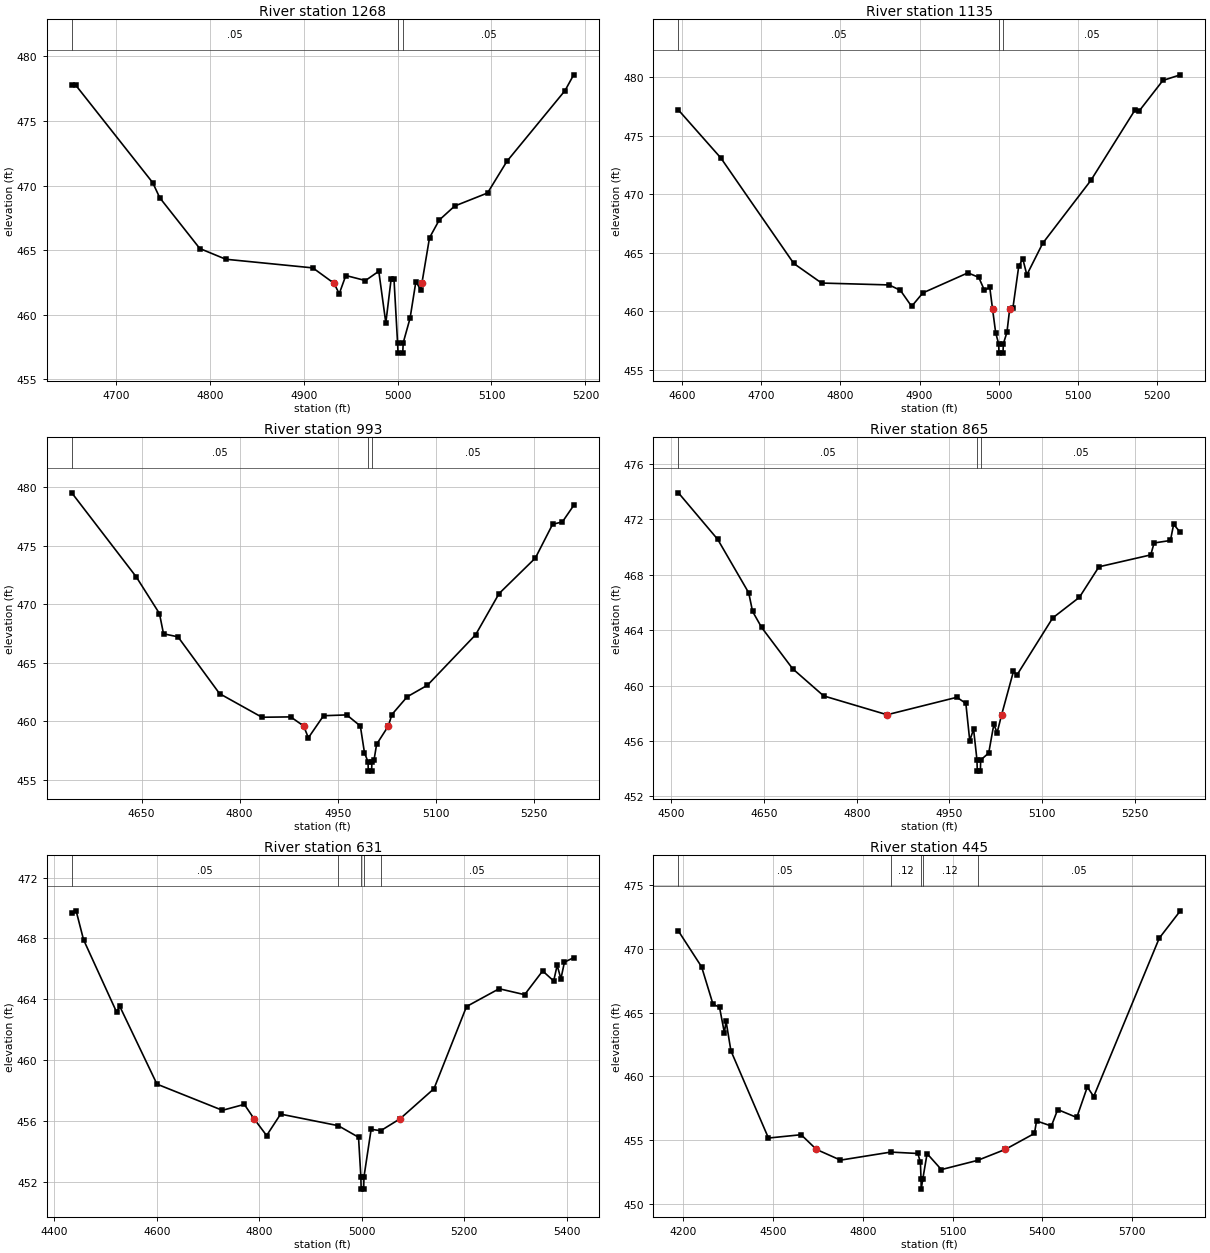
Type RM Length L Ch R = 1,1268,133,133,133
BEGIN DESCRIPTION:
XS3771A
END DESCRIPTION:
XS GIS Cut Line= 3
      2845415.31      7079853.24      2845185.92      7080108.32
      2845139.51      7080293.96
#Sta/Elev= 30
  4653.1  477.80  4657.1  477.80  4739.3  470.23  4746.8  469.06  4789.4  465.13
  4817.1  464.30  4909.8  463.63  4932.3  462.44  4937.9  461.63  4944.9  463.04
  4965.8  462.65  4980.0  463.37  4987.5  459.37  4993.1  462.74  4996.2  462.74
  5000.0  457.83  5000.5  457.03  5005.5  457.03  5006.0  457.83  5013.3  459.73
  5019.5  462.57  5024.7  461.92  5025.9  462.44  5034.0  465.96  5044.3  467.33
  5060.8  468.42  5095.8  469.43  5116.4  471.88  5178.3  477.36  5187.5  478.58
#Mann=3,-1,0
  4653.1    0.05       0  5000.0    0.03       0  5006.0    0.05       0
Bank Sta=4932.3,5025.9
Exp/Cntr=0.3,0.1

Type RM Length L Ch R = 1,1135,142,142,142
BEGIN DESCRIPTION:
XS3770A
END DESCRIPTION:
XS GIS Cut Line= 3
      2845328.90      7079783.49      2845047.90      7080095.30
      2845078.04      7080306.82
#Sta/Elev= 30
  4595.7  477.18  4649.3  473.08  4741.3  464.08  4776.4  462.41  4861.6  462.25
  4875.8  461.79  4890.0  460.42  4904.2  461.57  4961.0  463.28  4974.7  462.90
  4981.9  461.79  4988.6  462.05  4992.2  460.16  4996.1  458.16  4999.8  457.23
  5000.3  456.43  5005.3  456.43  5005.8  457.23  5010.3  458.21  5013.7  460.16
  5017.8  460.27  5025.2  463.85  5030.3  464.48  5035.4  463.11  5055.5  465.81
  5116.2  471.17  5171.9  477.18  5177.0  477.08  5207.1  479.70  5229.1  480.18
#Mann=3,-1,0
  4595.7    0.05       0  4999.8    0.03       0  5005.8    0.05       0
Bank Sta=4992.2,5013.7
Exp/Cntr=0.3,0.1

Type RM Length L Ch R = 1,993,128,128,128
BEGIN DESCRIPTION:
XS3769A
END DESCRIPTION:
XS GIS Cut Line= 3
      2845230.87      7079624.01      2844954.15      7080001.55
      2845027.76      7080291.77
#Sta/Elev= 30
  4543.3  479.53  4641.9  472.34  4677.4  469.20  4683.6  467.47  4705.7  467.21
  4769.3  462.35  4834.1  460.33  4878.1  460.36  4897.9  459.58  4905.1  458.57
  4928.3  460.46  4963.8  460.53  4984.6  459.58  4990.9  457.29  4996.3  456.52
  4996.8  455.72  5001.8  455.72  5002.3  456.52  5005.5  456.67  5009.5  458.02
  5027.4  459.58  5032.8  460.56  5056.2  462.08  5087.2  463.07  5160.9  467.39
  5196.7  470.91  5252.2  473.95  5278.6  476.84  5293.5  477.04  5310.8  478.45
#Mann=3,-1,0
  4543.3    0.05       0  4996.3    0.03       0  5002.3    0.05       0
Bank Sta=4897.9,5027.4
Exp/Cntr=0.3,0.1

Type RM Length L Ch R = 1,865,234,234,234
BEGIN DESCRIPTION:
XS3768A
END DESCRIPTION:
XS GIS Cut Line= 3
      2845137.85      7079589.11      2844844.77      7079991.13
      2844943.43      7080290.06
#Sta/Elev= 30
  4511.3  473.92  4574.9  470.56  4625.1  466.70  4631.3  465.36  4646.0  464.20
  4696.2  461.22  4746.4  459.26  4849.0  457.90  4962.0  459.16  4976.5  458.72
  4982.8  456.03  4989.0  456.86  4994.5  454.63  4995.0  453.83  5000.0  453.83
  5000.5  454.63  5013.5  455.14  5021.8  457.21  5027.1  456.60  5034.4  457.90
  5053.6  461.04  5058.8  460.74  5117.1  464.89  5160.3  466.38  5191.9  468.58
  5275.8  469.44  5281.1  470.30  5307.6  470.48  5312.8  471.65  5323.6  471.06
#Mann=3,-1,0
  4511.3    0.05       0  4994.5    0.03       0  5000.5    0.05       0
Bank Sta=4849,5034.4
Exp/Cntr=0.3,0.1

Type RM Length L Ch R = 1,631,186,186,186
BEGIN DESCRIPTION:
XS3767A
END DESCRIPTION:
XS GIS Cut Line= 4
      2845078.05      7079565.84      2844636.44      7079905.20
      2844628.63      7079939.05      2844894.30      7080221.02
#Sta/Elev= 30
  4434.3  469.70  4442.8  469.81  4457.3  467.91  4521.7  463.16  4528.0  463.53
  4600.5  458.42  4728.2  456.70  4770.9  457.09  4789.8  456.15  4814.4  455.04
  4841.7  456.45  4954.1  455.69  4993.7  454.93  4998.3  452.32  4998.8  451.52
  5003.8  451.52  5004.3  452.32  5018.3  455.45  5037.1  455.36  5075.0  456.15
  5140.9  458.12  5204.4  463.52  5268.0  464.69  5317.7  464.30  5352.9  465.86
  5374.4  465.20  5381.2  466.23  5388.5  465.34  5395.4  466.44  5413.4  466.73
#Mann=5,-1,0
  4434.3    0.05       0  4954.1    0.12       0  4998.3    0.07       0
  5004.3    0.12       0  5037.1    0.05       0
Bank Sta=4789.8,5075
Exp/Cntr=0.3,0.1

Type RM Length L Ch R = 1,445,0,0,0
BEGIN DESCRIPTION:
UNT 119 in LFCCL Watershed 1.0
END DESCRIPTION:
XS GIS Cut Line= 4
      2845151.10      7079444.59      2844480.19      7079808.84
      2844456.75      7079918.22      2845020.74      7080488.74
#Sta/Elev= 30
  4183.5  471.39  4261.1  468.58  4299.1  465.66  4320.9  465.42  4337.1  463.43
  4342.8  464.32  4359.0  462.01  4484.4  455.18  4593.7  455.44  4644.7  454.29
  4725.2  453.45  4893.3  454.08  4983.9  453.97  4992.3  453.27  4994.4  451.98
  4994.9  451.18  5000.4  451.98  5014.6  453.96  5062.3  452.71  5183.3  453.43
  5276.0  454.29  5373.5  455.54  5380.5  456.52  5430.0  456.12  5451.2  457.41
  5514.9  456.79  5550.2  459.18  5571.5  458.43  5790.6  470.83  5861.0  472.97
#Mann=5,-1,0
  4183.5    0.05       0  4893.3    0.12       0  4994.4    0.07       0
  5000.4    0.12       0  5183.3    0.05       0
Bank Sta=4644.7,5276
Exp/Cntr=0.3,0.1

Chan Stop Cuts=-1