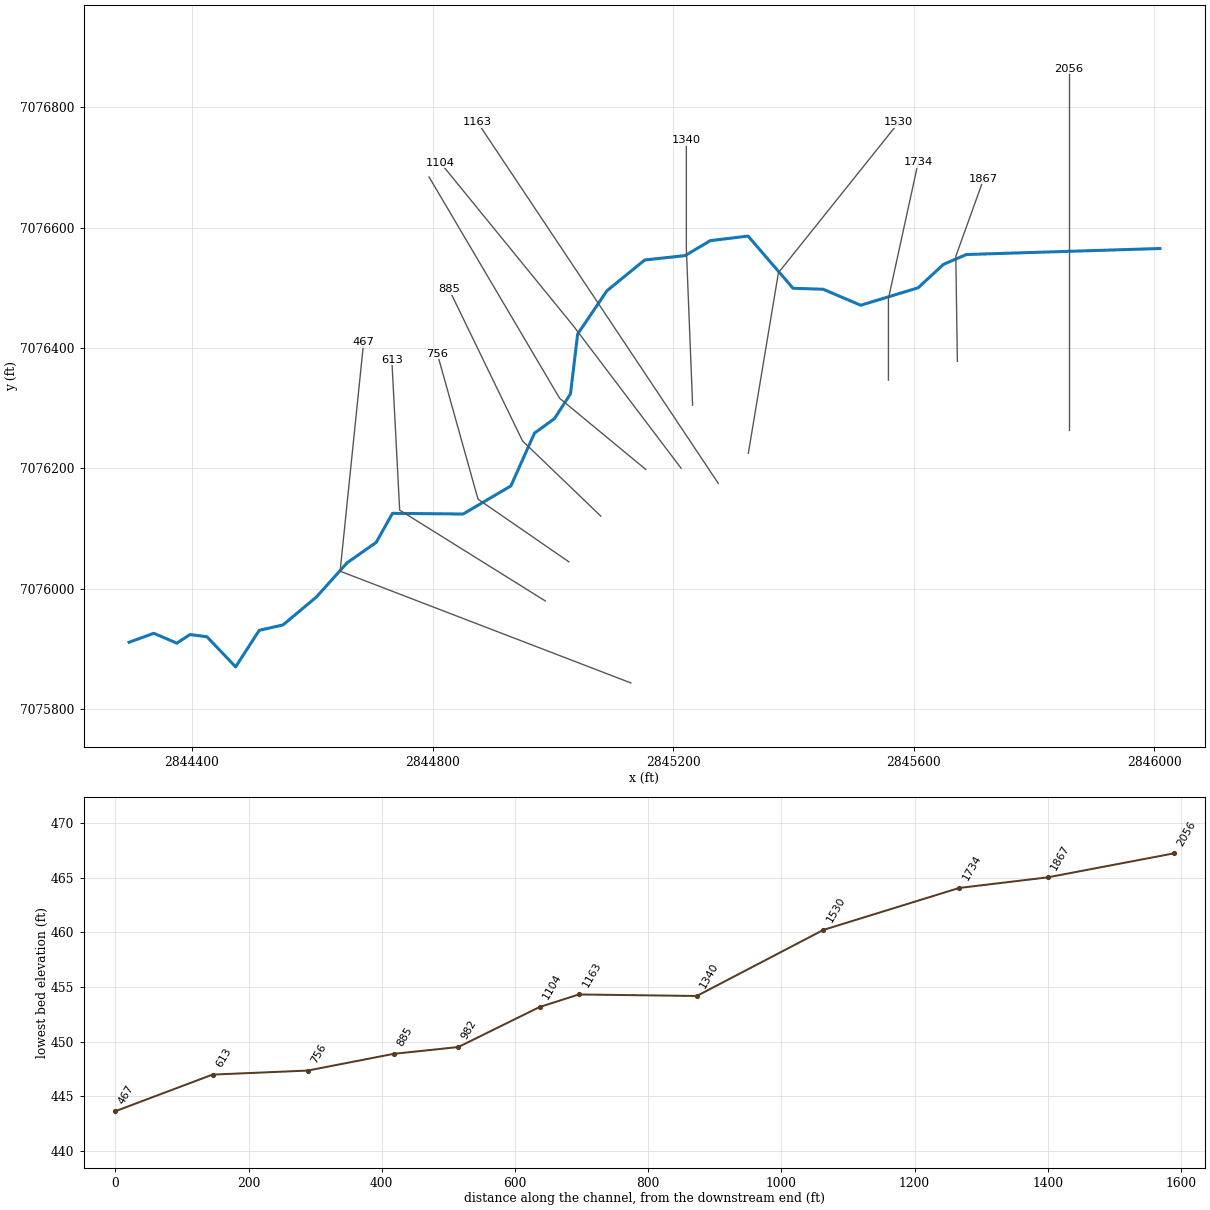
--- UNT 120 in LFCCL Watershed.prj (project) ---

Proj Title=UNT 120 in LFCCL Watershed Base Level Engineering
Current Plan=p01
Default Exp/Contr=0.3,0.1
English Units
Geom File=g01
Flow File=f01
Plan File=p01
BEGIN DESCRIPTION:
UNT 120 in LFCCL Watershed
END DESCRIPTION:

--- UNT 120 in LFCCL Watershed.p01 (plan) ---

Plan Title=Multiple Run
Short Identifier=Multiple
Geom File=g01
Flow File=f01
Subcritical Flow
K Sum by GR= 0
Std Step Tol= 0.01
Critical Tol= 0.01
Num of Std Step Trials= 20
Max Error Tol= 0.3
Flow Tol Ratio= 0.001
Split Flow NTrial= 30
Split Flow Tol= 0.02
Split Flow Ratio= 0.02
Log Output Level= 0
Friction Slope Method= 1
Unsteady Friction Slope Method= 2
Unsteady Bridges Friction Slope Method= 1
Parabolic Critical Depth
Global Vel Dist=  1 , 1 , 1
Global Log Level= 0
CheckData=True
Encroach Param= -1, 0, 0, 0
BEGIN DESCRIPTION:
Multiple Run
END DESCRIPTION:

--- UNT 120 in LFCCL Watershed.f01 (steady flow) ---

Flow Title=Multiple
Number of Profiles=7
Profile Names=10-year,25-year,50-year,1pct_min,100-year,1pct_plu,500-year
River Rch & RM= UNT 120 in LFCCL,Reach-1,2056
     233     292     336     193     386     770     505
Boundary for River Rch & Prof#=UNT 120 in LFCCL,Reach-1,1
Up Type=0
Dn Type=3
Dn Slope=0.005
Boundary for River Rch & Prof#=UNT 120 in LFCCL,Reach-1,2
Up Type=0
Dn Type=3
Dn Slope=0.005
Boundary for River Rch & Prof#=UNT 120 in LFCCL,Reach-1,3
Up Type=0
Dn Type=3
Dn Slope=0.005
Boundary for River Rch & Prof#=UNT 120 in LFCCL,Reach-1,4
Up Type=0
Dn Type=3
Dn Slope=0.005
Boundary for River Rch & Prof#=UNT 120 in LFCCL,Reach-1,5
Up Type=0
Dn Type=3
Dn Slope=0.005
Boundary for River Rch & Prof#=UNT 120 in LFCCL,Reach-1,6
Up Type=0
Dn Type=3
Dn Slope=0.005
Boundary for River Rch & Prof#=UNT 120 in LFCCL,Reach-1,7
Up Type=0
Dn Type=3
Dn Slope=0.005

--- UNT 120 in LFCCL Watershed.g01 (geometry) ---

Geom Title=Existing Conditions

River Reach=UNT 120 in LFCCL,Reach-1
Reach XY= 30
      2846009.12      7076565.32      2845687.51      7076555.33
      2845649.53      7076539.06      2845607.21      7076500.00
      2845511.78      7076470.99      2845449.45      7076497.58
      2845399.27      7076499.25      2845324.54      7076586.00
      2845261.81      7076578.37      2845219.78      7076553.54
      2845152.70      7076546.23      2845089.84      7076494.94
      2845041.25      7076423.08      2845029.35      7076323.75
      2845002.80      7076282.66      2844969.44      7076258.29
      2844930.35      7076170.67      2844850.85      7076123.97
      2844733.38      7076125.08      2844706.41      7076076.80
      2844658.06      7076042.90      2844607.07      7075986.11
      2844551.55      7075939.63      2844511.97      7075930.62
      2844472.70      7075869.90      2844425.04      7075919.91
      2844396.91      7075923.62      2844374.86      7075909.30
      2844336.74      7075925.72      2844295.59      7075910.71

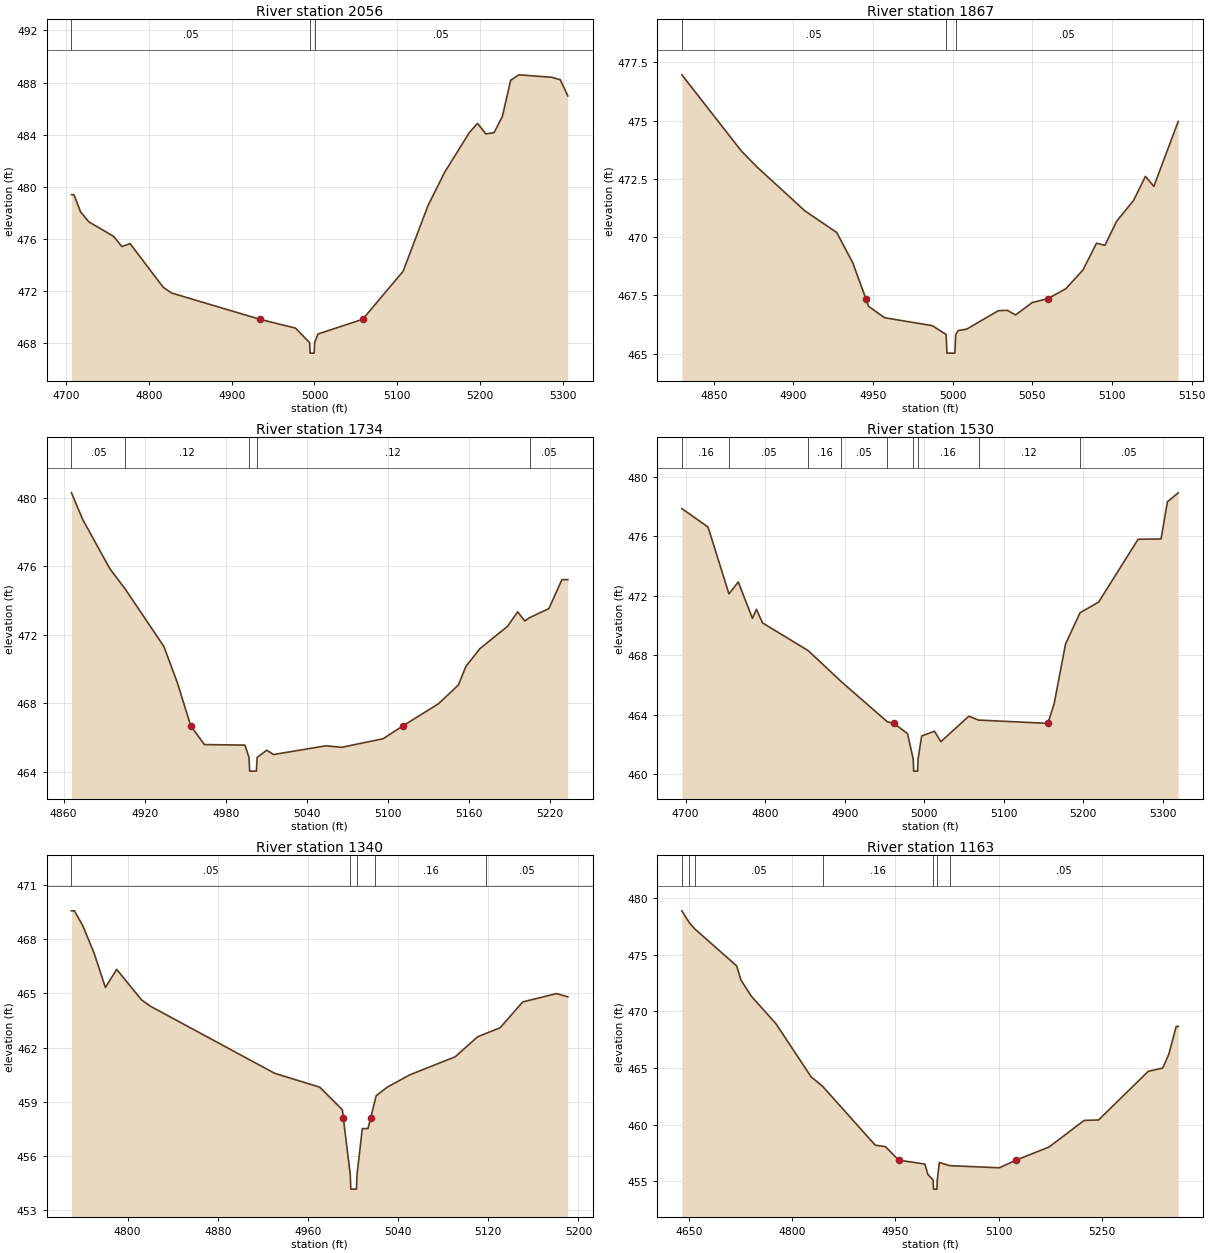
Type RM Length L Ch R = 1,2056,189,189,189
BEGIN DESCRIPTION:
UNT 120 in LFCCL Watershed 4.0
END DESCRIPTION:
XS GIS Cut Line= 3
      2845857.29      7076264.06      2845857.29      7076564.06
      2845857.29      7076864.06
#Sta/Elev= 30
  4706.3  479.38  4709.3  479.38  4717.2  478.07  4727.2  477.30  4757.2  476.18
  4767.2  475.40  4777.2  475.62  4817.2  472.27  4827.2  471.83  4934.0  469.81
  4977.2  469.13  4994.2  468.01  4994.7  467.21  4999.7  467.21  5000.2  468.01
  5004.3  468.68  5058.3  469.81  5107.2  473.50  5137.2  478.53  5157.2  481.08
  5187.2  484.15  5197.2  484.86  5207.2  484.05  5217.2  484.15  5227.2  485.40
  5237.2  488.17  5247.2  488.59  5287.2  488.40  5297.2  488.21  5306.3  486.97
#Mann=3,-1,0
  4706.3    0.05       0  4994.2    0.03       0  5000.2    0.05       0
Bank Sta=4934,5058.3
Exp/Cntr=0.3,0.1

Type RM Length L Ch R = 1,1867,133,133,133
BEGIN DESCRIPTION:
XS3776A
END DESCRIPTION:
XS GIS Cut Line= 3
      2845672.47      7076377.82      2845669.87      7076552.34
      2845716.29      7076681.30
#Sta/Elev= 30
  4830.0  476.97  4867.2  473.71  4877.2  473.01  4907.2  471.13  4927.2  470.20
  4937.2  468.91  4945.5  467.36  4947.2  467.03  4957.2  466.54  4987.2  466.20
  4995.9  465.82  4996.4  465.02  5001.4  465.02  5001.9  465.82  5003.4  465.99
  5008.8  466.05  5028.6  466.84  5034.2  466.86  5039.5  466.66  5049.9  467.19
  5059.9  467.36  5071.1  467.79  5081.8  468.59  5090.3  469.74  5095.6  469.65
  5103.0  470.69  5113.6  471.58  5121.0  472.61  5126.3  472.18  5141.6  474.97
#Mann=3,-1,0
  4830.0    0.05       0  4995.9    0.03       0  5001.9    0.05       0
Bank Sta=4945.5,5059.9
Exp/Cntr=0.3,0.1

Type RM Length L Ch R = 1,1734,204,204,204
BEGIN DESCRIPTION:
XS3782A
END DESCRIPTION:
XS GIS Cut Line= 3
      2845557.89      7076346.57      2845557.89      7076482.03
      2845607.37      7076708.63
#Sta/Elev= 30
  4865.8  480.30  4874.2  478.73  4894.2  475.87  4905.7  474.67  4934.2  471.33
  4944.2  469.21  4954.1  466.69  4964.2  465.60  4994.2  465.57  4997.2  464.85
  4997.7  464.05  5002.7  464.05  5003.2  464.85  5010.3  465.27  5015.4  465.02
  5054.2  465.53  5065.7  465.44  5096.4  465.94  5111.1  466.69  5137.4  467.98
  5152.2  469.08  5157.8  470.17  5168.1  471.20  5188.5  472.50  5196.1  473.35
  5201.3  472.82  5204.9  473.01  5219.2  473.54  5228.8  475.23  5233.2  475.23
#Mann=5,-1,0
  4865.8    0.05       0  4905.7    0.12       0  4997.2    0.07       0
  5003.2    0.12       0  5204.9    0.05       0
Bank Sta=4954.1,5111.1
Exp/Cntr=0.3,0.1

Type RM Length L Ch R = 1,1530,190,190,190
BEGIN DESCRIPTION:
UNT 120 in LFCCL Watershed 3.0
END DESCRIPTION:
XS GIS Cut Line= 3
      2845325.00      7076225.02      2845375.00      7076525.00
      2845575.02      7076775.02
#Sta/Elev= 30
  4695.3  477.85  4728.2  476.61  4754.5  472.12  4766.2  472.92  4784.0  470.48
  4789.1  471.08  4796.7  470.17  4854.1  468.31  4895.7  466.23  4953.6  463.53
  4961.9  463.42  4979.1  462.73  4986.3  461.01  4986.8  460.21  4991.8  460.21
  4992.3  461.01  4996.9  462.57  5013.0  462.89  5021.0  462.19  5056.2  463.90
  5068.4  463.64  5155.6  463.42  5163.5  464.73  5177.9  468.76  5196.1  470.85
  5219.5  471.57  5269.1  475.79  5298.0  475.81  5306.0  478.31  5319.6  478.91
#Mann=9,-1,0
  4695.3    0.16       0  4754.5    0.05       0  4854.1    0.16       0
  4895.7    0.05       0  4953.6    0.16       0  4986.3    0.07       0
  4992.3    0.16       0  5068.4    0.12       0  5196.1    0.05       0
Bank Sta=4961.9,5155.6
Exp/Cntr=0.3,0.1

Type RM Length L Ch R = 1,1340,177,177,177
BEGIN DESCRIPTION:
XS3777A
END DESCRIPTION:
XS GIS Cut Line= 3
      2845232.37      7076304.92      2845221.95      7076565.37
      2845221.95      7076745.02
#Sta/Elev= 30
  4750.3  469.57  4752.9  469.57  4760.4  468.74  4770.4  467.22  4780.4  465.33
  4790.4  466.33  4812.5  464.64  4820.4  464.29  4930.5  460.58  4970.6  459.81
  4990.6  458.56  4991.4  458.13  4997.6  454.97  4998.1  454.17  5003.1  454.17
  5003.6  454.97  5008.3  457.52  5013.3  457.52  5015.8  458.13  5019.8  459.14
  5020.6  459.34  5030.6  459.82  5050.6  460.50  5090.6  461.49  5110.6  462.60
  5117.7  462.78  5130.6  463.10  5150.6  464.53  5180.6  464.99  5190.6  464.81
#Mann=5,-1,0
  4750.3    0.05       0  4997.6    0.03       0  5003.6    0.05       0
  5019.8    0.16       0  5117.7    0.05       0
Bank Sta=4991.4,5015.8
Exp/Cntr=0.3,0.1

Type RM Length L Ch R = 1,1163,59,59,59
BEGIN DESCRIPTION:
UNT 120 in LFCCL Watershed 2.0
END DESCRIPTION:
XS GIS Cut Line= 3
      2845274.97      7076175.04      2845075.00      7076475.00
      2844874.98      7076775.03
#Sta/Elev= 30
  4639.9  478.86  4650.8  477.80  4659.1  477.24  4719.5  474.00  4725.5  472.78
  4740.5  471.35  4776.6  468.90  4827.6  464.22  4844.2  463.39  4920.8  458.19
  4935.8  458.05  4954.8  456.87  4992.9  456.52  4997.4  455.60  5004.9  455.11
  5005.4  454.31  5010.4  454.31  5010.9  455.11  5013.9  456.66  5029.3  456.38
  5101.1  456.19  5125.4  456.87  5173.2  458.02  5224.3  460.37  5245.3  460.41
  5317.4  464.70  5338.4  464.99  5347.4  466.22  5358.0  468.66  5361.0  468.66
#Mann=7,-1,0
  4639.9    0.05       0  4650.8    0.16       0  4659.1    0.05       0
  4844.2    0.16       0  5004.9    0.07       0  5010.9    0.16       0
  5029.3    0.05       0
Bank Sta=4954.8,5125.4
Exp/Cntr=0.3,0.1

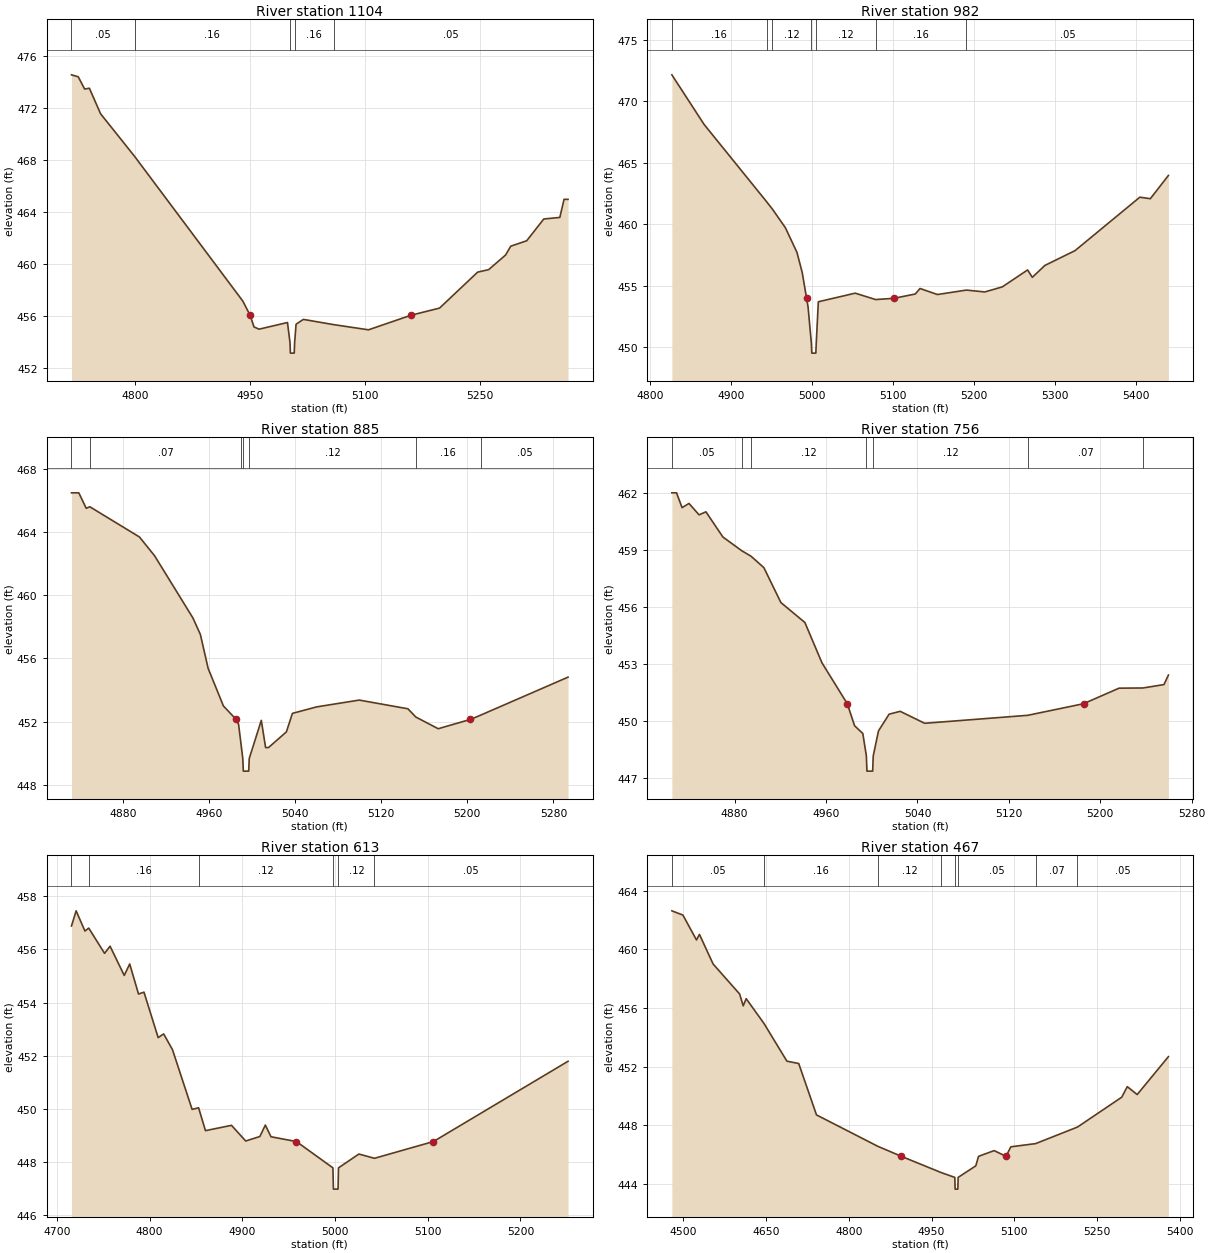
Type RM Length L Ch R = 1,1104,122,122,122
BEGIN DESCRIPTION:
XS3781A
END DESCRIPTION:
XS GIS Cut Line= 3
      2845213.17      7076200.17      2845034.11      7076436.75
      2844813.02      7076708.08
#Sta/Elev= 30
  4717.5  474.53  4726.3  474.38  4734.6  473.44  4740.8  473.50  4755.4  471.54
  4799.8  468.26  4940.6  457.16  4950.2  456.06  4955.2  455.17  4961.8  455.00
  4998.8  455.51  5002.1  453.96  5002.6  453.16  5007.6  453.16  5008.1  453.96
  5010.0  455.38  5019.5  455.75  5058.8  455.35  5104.3  454.95  5159.2  456.06
  5196.9  456.62  5246.5  459.38  5260.8  459.57  5282.8  460.69  5289.6  461.37
  5310.4  461.79  5332.6  463.46  5353.5  463.58  5359.0  464.97  5364.2  464.97
#Mann=5,-1,0
  4717.5    0.05       0  4799.8    0.16       0  5002.1    0.07       0
  5008.1    0.16       0  5058.8    0.05       0
Bank Sta=4950.2,5159.2
Exp/Cntr=0.3,0.1

Type RM Length L Ch R = 1,982,97,97,97
BEGIN DESCRIPTION:
Mapping XS 1e61ec7c
END DESCRIPTION:
XS GIS Cut Line= 3
      2845154.59      7076198.01      2845011.32      7076316.31
      2844794.30      7076684.17
#Sta/Elev= 30
  4827.2  472.15  4866.9  468.12  4944.3  461.81  4951.2  461.23  4967.3  459.71
  4981.6  457.70  4988.1  456.06  4993.5  453.96  4995.3  453.27  4999.4  450.30
  4999.9  449.50  5004.9  449.50  5005.4  450.30  5008.0  453.68  5053.5  454.38
  5078.7  453.86  5101.1  453.96  5127.6  454.31  5133.5  454.76  5155.0  454.27
  5190.7  454.63  5213.5  454.48  5235.0  454.89  5266.3  456.27  5272.1  455.67
  5287.7  456.64  5324.8  457.84  5404.8  462.19  5417.8  462.07  5440.1  463.96
#Mann=7,-1,0
  4827.2    0.16       0  4944.3    0.07       0  4951.2    0.12       0
  4999.4    0.07       0  5005.4    0.12       0  5078.7    0.16       0
  5190.7    0.05       0
Bank Sta=4993.5,5101.1
Exp/Cntr=0.3,0.1

Type RM Length L Ch R = 1,885,129,129,129
BEGIN DESCRIPTION:
XS3780A
END DESCRIPTION:
XS GIS Cut Line= 3
      2845079.83      7076120.46      2844949.60      7076245.49
      2844827.21      7076498.07
#Sta/Elev= 30
  4832.4  466.47  4839.2  466.47  4846.1  465.49  4849.4  465.59  4895.5  463.68
  4909.6  462.49  4945.2  458.56  4952.1  457.52  4959.3  455.38  4973.5  453.00
  4985.3  452.15  4987.6  451.84  4989.9  450.57  4991.5  449.68  4992.0  448.88
  4997.0  448.88  4997.5  449.68  5008.7  452.09  5012.7  450.37  5015.4  450.37
  5032.0  451.36  5037.6  452.53  5060.1  452.94  5099.7  453.37  5144.9  452.82
  5152.2  452.30  5173.0  451.56  5203.0  452.15  5212.5  452.42  5293.6  454.82
#Mann=7,-1,0
  4832.4    0.12       0  4849.4    0.07       0  4989.9    0.12       0
  4991.5    0.07       0  4997.5    0.12       0  5152.2    0.16       0
  5212.5    0.05       0
Bank Sta=4985.3,5203
Exp/Cntr=0.3,0.1

Type RM Length L Ch R = 1,756,143,143,143
BEGIN DESCRIPTION:
XS3779A
END DESCRIPTION:
XS GIS Cut Line= 3
      2845026.66      7076044.51      2844875.59      7076148.70
      2844808.02      7076390.42
#Sta/Elev= 30
  4825.1  462.01  4829.2  462.01  4834.0  461.23  4840.1  461.45  4848.9  460.85
  4854.9  461.01  4869.8  459.68  4886.5  458.95  4894.4  458.67  4905.6  458.07
  4920.5  456.23  4941.5  455.18  4956.4  453.06  4978.6  450.90  4985.0  449.74
  4992.2  449.33  4995.3  448.15  4995.8  447.35  5000.8  447.35  5001.3  448.15
  5005.9  449.47  5015.2  450.35  5024.9  450.50  5046.3  449.87  5136.5  450.29
  5185.3  450.90  5216.4  451.72  5237.4  451.73  5255.7  451.91  5259.6  452.41
#Mann=7,-1,0
  4825.1    0.05       0  4886.5    0.07       0  4894.4    0.12       0
  4995.3    0.07       0  5001.3    0.12       0  5136.5    0.07       0
  5237.4    0.05       0
Bank Sta=4978.6,5185.3
Exp/Cntr=0.3,0.1

Type RM Length L Ch R = 1,613,146,146,146
BEGIN DESCRIPTION:
XS3778A
END DESCRIPTION:
XS GIS Cut Line= 3
      2844987.60      7075979.41      2844745.39      7076130.47
      2844732.38      7076380.28
#Sta/Elev= 30
  4715.8  456.88  4720.8  457.45  4730.3  456.69  4734.4  456.80  4751.5  455.85
  4757.4  456.12  4772.7  455.02  4778.6  455.45  4788.1  454.32  4794.0  454.39
  4809.3  452.68  4815.2  452.82  4824.7  452.23  4845.9  449.98  4852.9  450.04
  4860.3  449.18  4888.4  449.38  4903.7  448.79  4919.0  448.96  4924.9  449.39
  4931.0  448.95  4958.4  448.77  4997.8  447.78  4998.3  446.98  5003.3  446.98
  5003.8  447.78  5025.8  448.30  5042.6  448.14  5106.2  448.77  5251.4  451.79
#Mann=6,-1,0
  4715.8    0.05       0  4734.4    0.16       0  4852.9    0.12       0
  4997.8    0.07       0  5003.8    0.12       0  5042.6    0.05       0
Bank Sta=4958.4,5106.2
Exp/Cntr=0.3,0.1

Type RM Length L Ch R = 1,467,0,0,0
BEGIN DESCRIPTION:
UNT 120 in LFCCL Watershed 1.0
END DESCRIPTION:
XS GIS Cut Line= 3
      2845129.64      7075843.20      2844646.43      7076028.91
      2844685.49      7076409.14
#Sta/Elev= 30
  4479.3  462.64  4499.3  462.35  4523.9  460.65  4529.3  461.03  4554.0  459.01
  4602.1  456.96  4608.6  456.15  4614.0  456.64  4646.2  454.95  4687.8  452.37
  4709.2  452.21  4741.4  448.70  4852.3  446.56  4895.2  445.87  4967.5  444.76
  4992.1  444.43  4992.6  443.63  4997.6  443.63  4998.1  444.43  5030.1  445.22
  5035.1  445.87  5063.4  446.26  5084.9  445.87  5093.6  446.52  5138.6  446.74
  5214.4  447.87  5294.6  449.91  5304.7  450.63  5322.6  450.09  5379.2  452.68
#Mann=8,-1,0
  4479.3    0.05       0  4646.2    0.16       0  4852.3    0.12       0
  4967.5    0.05       0  4992.1    0.03       0  4998.1    0.05       0
  5138.6    0.07       0  5214.4    0.05       0
Bank Sta=4895.2,5084.9
Exp/Cntr=0.3,0.1

Chan Stop Cuts=-1