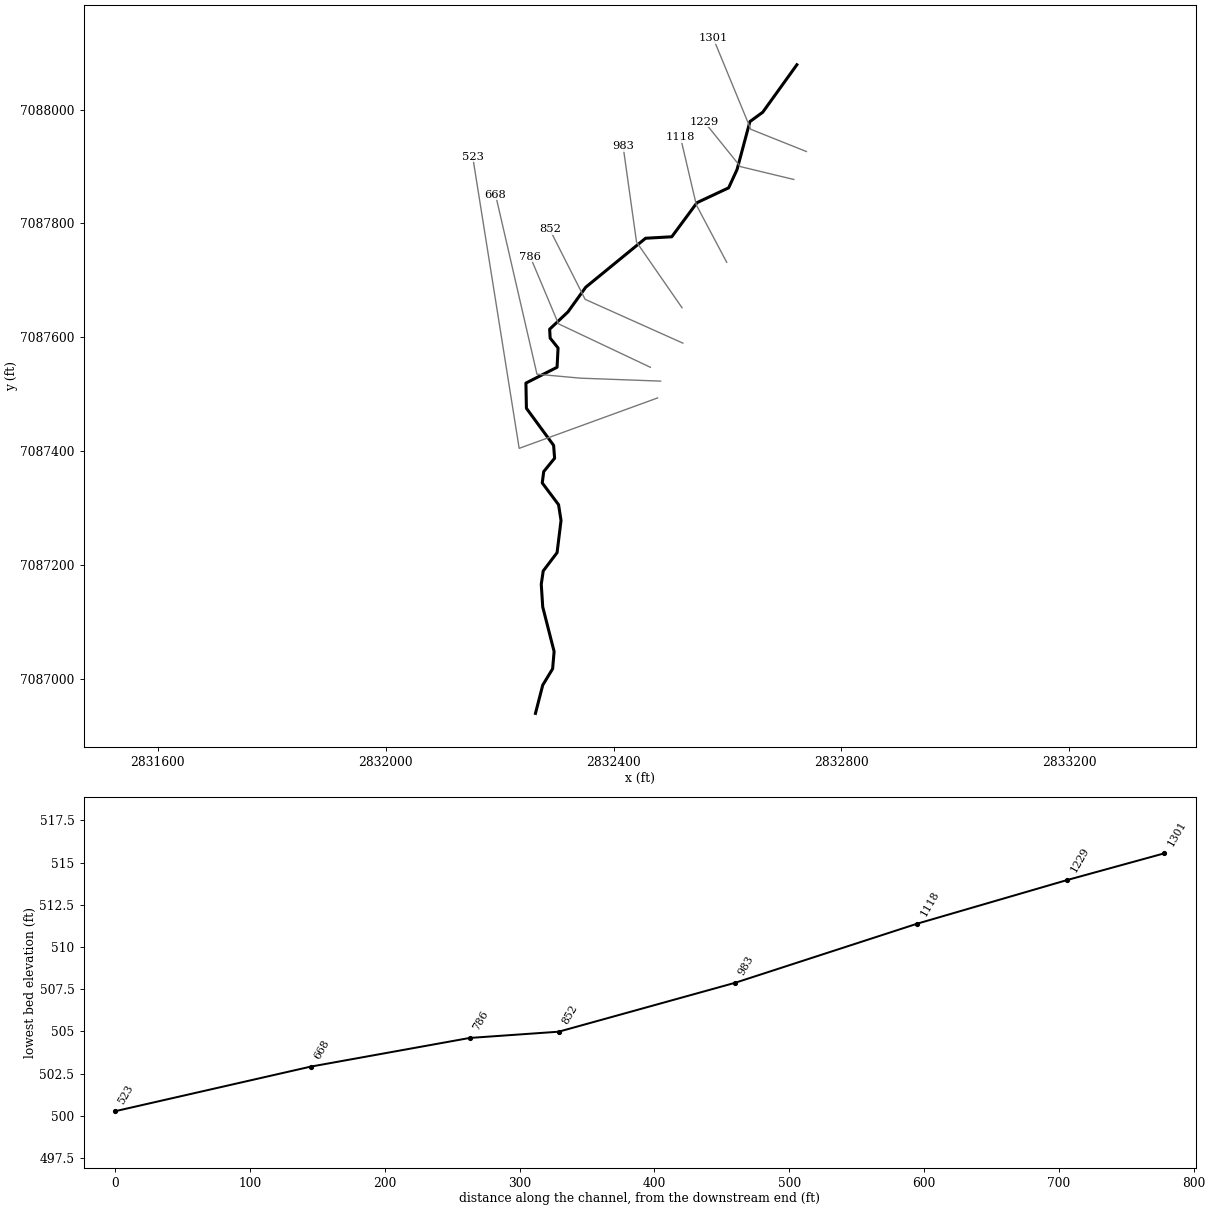
--- UNT 122 in LFCCL Watershed.prj (project) ---

Proj Title=UNT 122 in LFCCL Watershed Base Level Engineering
Current Plan=p01
Default Exp/Contr=0.3,0.1
English Units
Geom File=g01
Flow File=f01
Plan File=p01
BEGIN DESCRIPTION:
UNT 122 in LFCCL Watershed
END DESCRIPTION:

--- UNT 122 in LFCCL Watershed.p01 (plan) ---

Plan Title=Multiple Run
Short Identifier=Multiple
Geom File=g01
Flow File=f01
Subcritical Flow
K Sum by GR= 0
Std Step Tol= 0.01
Critical Tol= 0.01
Num of Std Step Trials= 20
Max Error Tol= 0.3
Flow Tol Ratio= 0.001
Split Flow NTrial= 30
Split Flow Tol= 0.02
Split Flow Ratio= 0.02
Log Output Level= 0
Friction Slope Method= 1
Unsteady Friction Slope Method= 2
Unsteady Bridges Friction Slope Method= 1
Parabolic Critical Depth
Global Vel Dist=  1 , 1 , 1
Global Log Level= 0
CheckData=True
Encroach Param= -1, 0, 0, 0
BEGIN DESCRIPTION:
Multiple Run
END DESCRIPTION:

--- UNT 122 in LFCCL Watershed.f01 (steady flow) ---

Flow Title=Multiple
Number of Profiles=7
Profile Names=10-year,25-year,50-year,1pct_min,100-year,1pct_plu,500-year
River Rch & RM= UNT 122 in LFCCL,Reach-1,1301
     174     213     242     137     273     546     347
Boundary for River Rch & Prof#=UNT 122 in LFCCL,Reach-1,1
Up Type=0
Dn Type=3
Dn Slope=0.005
Boundary for River Rch & Prof#=UNT 122 in LFCCL,Reach-1,2
Up Type=0
Dn Type=3
Dn Slope=0.005
Boundary for River Rch & Prof#=UNT 122 in LFCCL,Reach-1,3
Up Type=0
Dn Type=3
Dn Slope=0.005
Boundary for River Rch & Prof#=UNT 122 in LFCCL,Reach-1,4
Up Type=0
Dn Type=3
Dn Slope=0.005
Boundary for River Rch & Prof#=UNT 122 in LFCCL,Reach-1,5
Up Type=0
Dn Type=3
Dn Slope=0.005
Boundary for River Rch & Prof#=UNT 122 in LFCCL,Reach-1,6
Up Type=0
Dn Type=3
Dn Slope=0.005
Boundary for River Rch & Prof#=UNT 122 in LFCCL,Reach-1,7
Up Type=0
Dn Type=3
Dn Slope=0.005

--- UNT 122 in LFCCL Watershed.g01 (geometry) ---

Geom Title=Existing Conditions

River Reach=UNT 122 in LFCCL,Reach-1
Reach XY= 30
      2832721.75      7088078.60      2832661.86      7087995.26
      2832639.29      7087978.77      2832616.72      7087894.57
      2832601.96      7087862.45      2832546.40      7087836.41
      2832502.13      7087776.51      2832456.13      7087773.91
      2832351.09      7087687.97      2832319.84      7087644.57
      2832287.72      7087614.19      2832288.59      7087598.56
      2832302.48      7087581.20      2832300.74      7087547.35
      2832246.06      7087519.57      2832246.92      7087475.30
      2832294.67      7087410.19      2832296.40      7087387.62
      2832277.31      7087364.19      2832274.70      7087344.22
      2832303.35      7087306.03      2832307.69      7087278.25
      2832300.74      7087221.82      2832276.44      7087189.71
      2832272.97      7087166.27      2832275.57      7087126.34
      2832295.54      7087048.21      2832292.93      7087017.83
      2832275.57      7086989.19      2832262.78      7086939.55

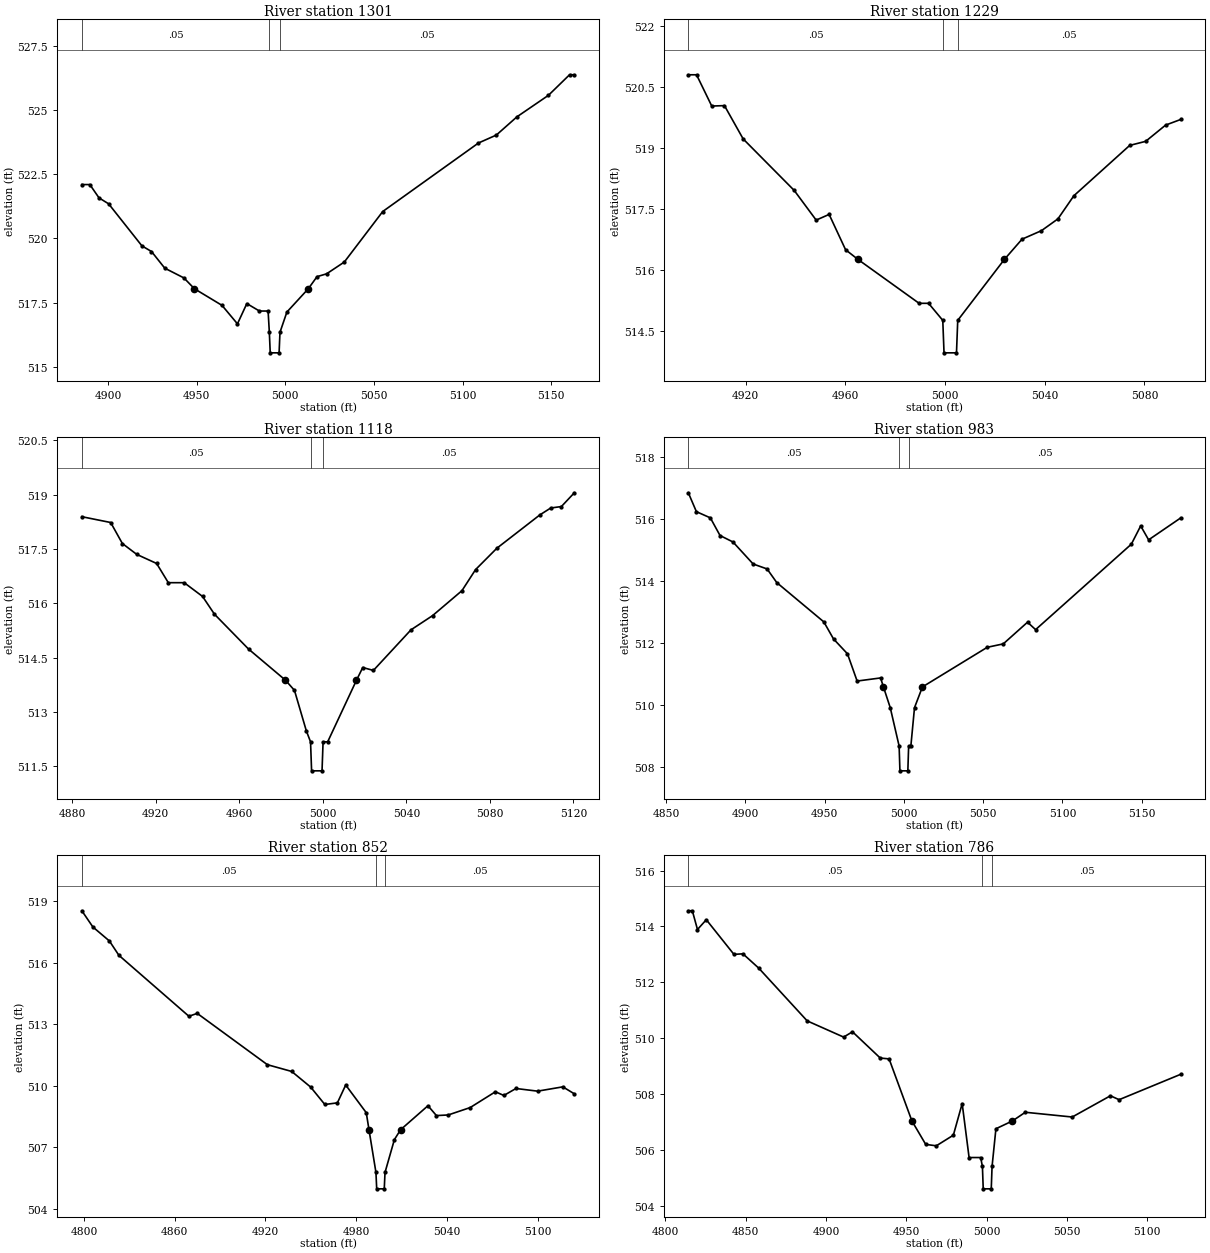
Type RM Length L Ch R = 1,1301,72,72,72
BEGIN DESCRIPTION:
UNT 122 in LFCCL Watershed 2.0
END DESCRIPTION:
XS GIS Cut Line= 3
      2832738.44      7087926.20      2832640.82      7087965.25
      2832575.01      7088124.98
#Sta/Elev= 30
  4885.2  522.10  4889.7  522.10  4894.9  521.58  4900.3  521.35  4919.1  519.71
  4924.5  519.49  4932.0  518.84  4942.8  518.46  4948.7  518.04  4964.3  517.39
  4973.0  516.67  4978.3  517.46  4985.4  517.17  4990.3  517.17  4991.0  516.34
  4991.5  515.54  4996.5  515.54  4997.0  516.34  5000.9  517.13  5013.0  518.04
  5017.9  518.51  5023.3  518.62  5033.3  519.08  5055.0  521.05  5109.0  523.72
  5119.1  524.03  5130.7  524.74  5148.5  525.58  5160.4  526.38  5163.1  526.38
#Mann=3,-1,0
  4885.2    0.05       0  4991.0    0.03       0  4997.0    0.05       0
Bank Sta=4948.7,5013
Exp/Cntr=0.3,0.1

Type RM Length L Ch R = 1,1229,111,111,111
BEGIN DESCRIPTION:
XS3786A
END DESCRIPTION:
XS GIS Cut Line= 3
      2832716.36      7087877.13      2832622.59      7087899.71
      2832559.19      7087978.53
#Sta/Elev= 25
  4897.0  520.81  4900.3  520.81  4906.4  520.04  4911.5  520.05  4919.0  519.23
  4939.5  517.96  4948.3  517.23  4953.5  517.37  4960.1  516.50  4965.1  516.26
  4989.6  515.18  4993.4  515.18  4999.1  514.76  4999.6  513.96  5004.6  513.96
  5005.1  514.76  5023.8  516.26  5030.9  516.76  5038.7  516.97  5045.3  517.26
  5051.7  517.83  5074.1  519.07  5080.5  519.17  5088.5  519.57  5094.6  519.71
#Mann=3,-1,0
  4897.0    0.05       0  4999.1    0.03       0  5005.1    0.05       0
Bank Sta=4965.1,5023.8
Exp/Cntr=0.3,0.1

Type RM Length L Ch R = 1,1118,135,135,135
BEGIN DESCRIPTION:
XS3785A
END DESCRIPTION:
XS GIS Cut Line= 3
      2832598.53      7087731.74      2832545.29      7087832.29
      2832517.43      7087951.09
#Sta/Elev= 30
  4884.6  518.39  4898.4  518.23  4904.0  517.65  4910.9  517.35  4920.4  517.10
  4926.0  516.57  4933.6  516.57  4942.4  516.19  4948.1  515.70  4964.4  514.74
  4982.1  513.88  4986.4  513.60  4992.1  512.48  4994.1  512.18  4994.6  511.38
  4999.6  511.38  5000.1  512.18  5002.3  512.18  5016.1  513.88  5019.1  514.23
  5024.2  514.15  5042.2  515.27  5052.5  515.66  5066.6  516.35  5073.1  516.93
  5083.3  517.52  5103.9  518.44  5109.1  518.63  5114.2  518.67  5120.4  519.05
#Mann=3,-1,0
  4884.6    0.05       0  4994.1    0.03       0  5000.1    0.05       0
Bank Sta=4982.1,5016.1
Exp/Cntr=0.3,0.1

Type RM Length L Ch R = 1,983,131,131,131
BEGIN DESCRIPTION:
XS3783A
END DESCRIPTION:
XS GIS Cut Line= 3
      2832520.16      7087651.80      2832440.26      7087767.21
      2832416.59      7087935.89
#Sta/Elev= 30
  4864.0  516.86  4869.1  516.25  4877.9  516.05  4884.0  515.48  4892.2  515.27
  4904.9  514.56  4913.7  514.40  4919.8  513.96  4949.5  512.69  4955.6  512.14
  4964.4  511.66  4970.5  510.78  4985.3  510.88  4987.1  510.59  4991.4  509.92
  4997.0  508.68  4997.5  507.88  5002.5  507.88  5003.0  508.68  5004.4  508.68
  5006.7  509.92  5011.7  510.59  5052.6  511.87  5062.7  511.98  5078.0  512.68
  5083.1  512.44  5143.5  515.20  5149.4  515.79  5154.4  515.34  5174.7  516.05
#Mann=3,-1,0
  4864.0    0.05       0  4997.0    0.03       0  5003.0    0.05       0
Bank Sta=4987.1,5011.7
Exp/Cntr=0.3,0.1

Type RM Length L Ch R = 1,852,66,66,66
BEGIN DESCRIPTION:
XS3784A
END DESCRIPTION:
XS GIS Cut Line= 3
      2832521.63      7087589.69      2832350.03      7087666.61
      2832287.88      7087789.43
#Sta/Elev= 30
  4798.6  518.53  4805.9  517.74  4816.8  517.06  4823.1  516.36  4869.4  513.39
  4874.9  513.53  4921.3  511.03  4937.4  510.70  4949.9  509.94  4959.3  509.09
  4967.6  509.17  4973.1  510.04  4986.7  508.69  4988.5  507.86  4993.1  505.78
  4993.6  504.98  4998.6  504.98  4999.1  505.78  5005.3  507.38  5009.4  507.86
  5027.5  509.03  5033.1  508.55  5040.9  508.58  5055.4  508.94  5072.1  509.71
  5077.7  509.53  5085.7  509.87  5100.0  509.74  5116.7  509.95  5124.3  509.61
#Mann=3,-1,0
  4798.6    0.05       0  4993.1    0.03       0  4999.1    0.05       0
Bank Sta=4988.5,5009.4
Exp/Cntr=0.3,0.1

Type RM Length L Ch R = 1,786,118,118,118
BEGIN DESCRIPTION:
XS3787A
END DESCRIPTION:
XS GIS Cut Line= 3
      2832464.57      7087547.29      2832303.15      7087623.67
      2832253.54      7087741.68
#Sta/Elev= 30
  4814.3  514.56  4816.8  514.56  4820.0  513.89  4825.5  514.24  4842.7  513.00
  4848.3  513.02  4858.1  512.51  4888.3  510.62  4911.0  510.04  4916.5  510.23
  4933.8  509.29  4939.3  509.26  4953.5  507.04  4962.1  506.20  4968.7  506.15
  4979.3  506.53  4984.8  507.66  4989.1  505.73  4996.3  505.73  4997.4  505.41
  4997.9  504.61  5002.9  504.61  5003.4  505.41  5005.8  506.76  5016.1  507.04
  5024.1  507.35  5053.3  507.18  5077.1  507.94  5082.5  507.80  5120.9  508.71
#Mann=3,-1,0
  4814.3    0.05       0  4997.4    0.03       0  5003.4    0.05       0
Bank Sta=4953.5,5016.1
Exp/Cntr=0.3,0.1

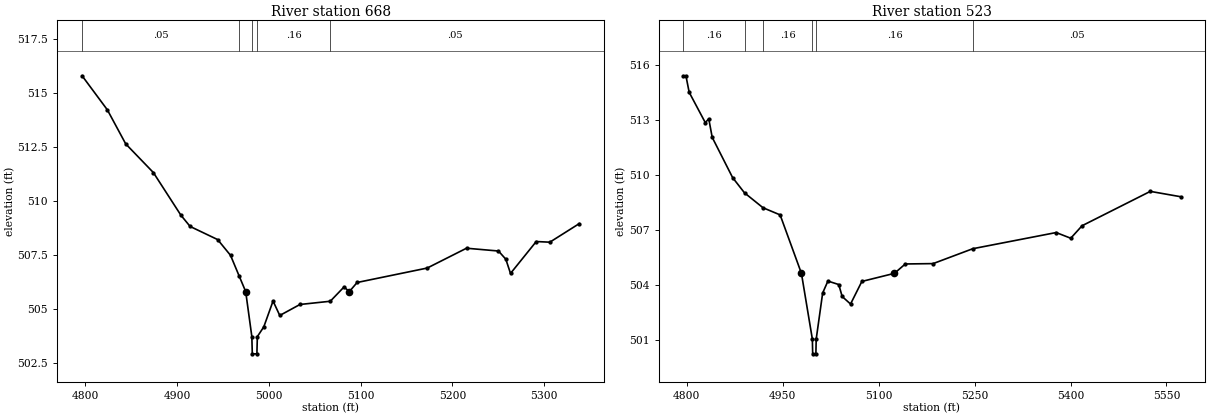
Type RM Length L Ch R = 1,668,145,145,145
BEGIN DESCRIPTION:
Mapping XS 3477b1d4
END DESCRIPTION:
XS GIS Cut Line= 4
      2832482.50      7087523.01      2832341.84      7087528.21
      2832265.45      7087535.16      2832192.65      7087850.61
#Sta/Elev= 30
  4796.8  515.81  4824.3  514.23  4844.3  512.65  4874.4  511.32  4904.4  509.34
  4914.4  508.82  4944.4  508.21  4958.4  507.48  4967.9  506.51  4974.9  505.80
  4981.6  503.71  4982.1  502.91  4987.1  502.91  4987.6  503.71  4994.6  504.16
  5004.7  505.36  5012.0  504.69  5034.0  505.20  5067.0  505.35  5081.9  506.01
  5087.8  505.80  5096.2  506.22  5172.5  506.89  5215.3  507.81  5250.1  507.68
  5258.1  507.30  5263.2  506.64  5291.2  508.12  5306.0  508.09  5338.0  508.95
#Mann=5,-1,0
  4796.8    0.05       0  4967.9    0.16       0  4981.6    0.07       0
  4987.6    0.16       0  5067.0    0.05       0
Bank Sta=4974.9,5087.8
Exp/Cntr=0.3,0.1

Type RM Length L Ch R = 1,523,0,0,0
BEGIN DESCRIPTION:
UNT 122 in LFCCL Watershed 1.0
END DESCRIPTION:
XS GIS Cut Line= 3
      2832477.27      7087493.50      2832234.20      7087404.95
      2832152.60      7087917.09
#Sta/Elev= 30
  4794.7  515.40  4798.6  515.40  4803.7  514.50  4828.9  512.85  4834.3  513.06
  4839.7  512.05  4871.6  509.86  4890.2  509.03  4919.1  508.22  4945.9  507.83
  4979.2  504.65  4996.3  501.07  4996.8  500.27  5001.8  500.27  5002.3  501.07
  5012.4  503.58  5020.6  504.23  5037.6  504.04  5042.9  503.39  5056.0  502.98
  5073.7  504.21  5124.6  504.65  5141.6  505.16  5185.1  505.18  5247.1  505.99
  5377.5  506.87  5400.3  506.56  5418.0  507.24  5524.7  509.11  5572.0  508.82
#Mann=6,-1,0
  4794.7    0.16       0  4890.2    0.05       0  4919.1    0.16       0
  4996.3    0.07       0  5002.3    0.16       0  5247.1    0.05       0
Bank Sta=4979.2,5124.6
Exp/Cntr=0.3,0.1

Chan Stop Cuts=-1