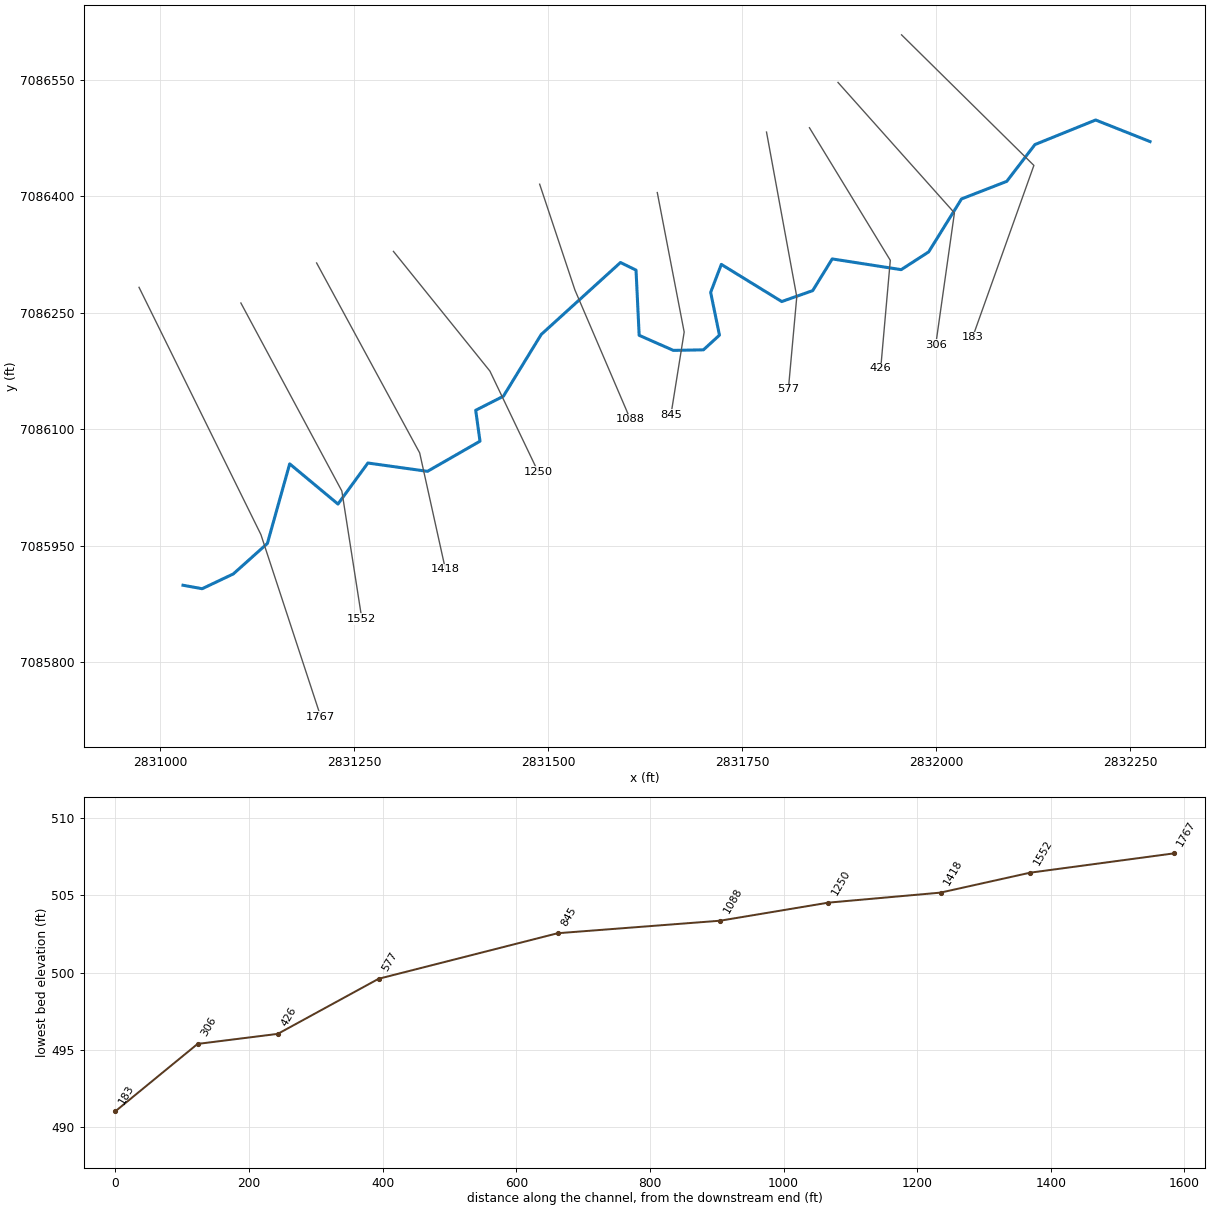
--- UNT 123 in LFCCL Watershed.prj (project) ---

Proj Title=UNT 123 in LFCCL Watershed Base Level Engineering
Current Plan=p01
Default Exp/Contr=0.3,0.1
English Units
Geom File=g01
Flow File=f01
Plan File=p01
BEGIN DESCRIPTION:
UNT 123 in LFCCL Watershed
END DESCRIPTION:

--- UNT 123 in LFCCL Watershed.p01 (plan) ---

Plan Title=Multiple Run
Short Identifier=Multiple
Geom File=g01
Flow File=f01
Subcritical Flow
K Sum by GR= 0
Std Step Tol= 0.01
Critical Tol= 0.01
Num of Std Step Trials= 20
Max Error Tol= 0.3
Flow Tol Ratio= 0.001
Split Flow NTrial= 30
Split Flow Tol= 0.02
Split Flow Ratio= 0.02
Log Output Level= 0
Friction Slope Method= 1
Unsteady Friction Slope Method= 2
Unsteady Bridges Friction Slope Method= 1
Parabolic Critical Depth
Global Vel Dist=  1 , 1 , 1
Global Log Level= 0
CheckData=True
Encroach Param= -1, 0, 0, 0
BEGIN DESCRIPTION:
Multiple Run
END DESCRIPTION:

--- UNT 123 in LFCCL Watershed.f01 (steady flow) ---

Flow Title=Multiple
Number of Profiles=7
Profile Names=10-year,25-year,50-year,1pct_min,100-year,1pct_plu,500-year
River Rch & RM= UNT 123 in LFCCL,Reach-1,1767
     245     305     350     200     400     798     518
Boundary for River Rch & Prof#=UNT 123 in LFCCL,Reach-1,1
Up Type=0
Dn Type=3
Dn Slope=0.005
Boundary for River Rch & Prof#=UNT 123 in LFCCL,Reach-1,2
Up Type=0
Dn Type=3
Dn Slope=0.005
Boundary for River Rch & Prof#=UNT 123 in LFCCL,Reach-1,3
Up Type=0
Dn Type=3
Dn Slope=0.005
Boundary for River Rch & Prof#=UNT 123 in LFCCL,Reach-1,4
Up Type=0
Dn Type=3
Dn Slope=0.005
Boundary for River Rch & Prof#=UNT 123 in LFCCL,Reach-1,5
Up Type=0
Dn Type=3
Dn Slope=0.005
Boundary for River Rch & Prof#=UNT 123 in LFCCL,Reach-1,6
Up Type=0
Dn Type=3
Dn Slope=0.005
Boundary for River Rch & Prof#=UNT 123 in LFCCL,Reach-1,7
Up Type=0
Dn Type=3
Dn Slope=0.005

--- UNT 123 in LFCCL Watershed.g01 (geometry) ---

Geom Title=Existing Conditions

River Reach=UNT 123 in LFCCL,Reach-1
Reach XY= 30
      2831029.57      7085899.04      2831054.23      7085894.58
      2831094.39      7085913.61      2831138.27      7085952.89
      2831167.01      7086055.44      2831229.22      7086003.67
      2831267.77      7086056.53      2831344.55      7086045.81
      2831412.22      7086084.65      2831406.70      7086124.50
      2831442.37      7086142.59      2831491.12      7086222.17
      2831593.23      7086314.89      2831613.27      7086305.08
      2831617.31      7086221.07      2831661.35      7086201.66
      2831700.16      7086202.37      2831720.78      7086221.30
      2831709.41      7086276.38      2831723.18      7086312.46
      2831801.02      7086264.59      2831840.89      7086278.65
      2831866.07      7086319.51      2831954.91      7086305.68
      2831990.31      7086328.53      2832032.68      7086396.83
      2832090.91      7086419.42      2832127.27      7086466.86
      2832205.50      7086498.51      2832275.59      7086470.71

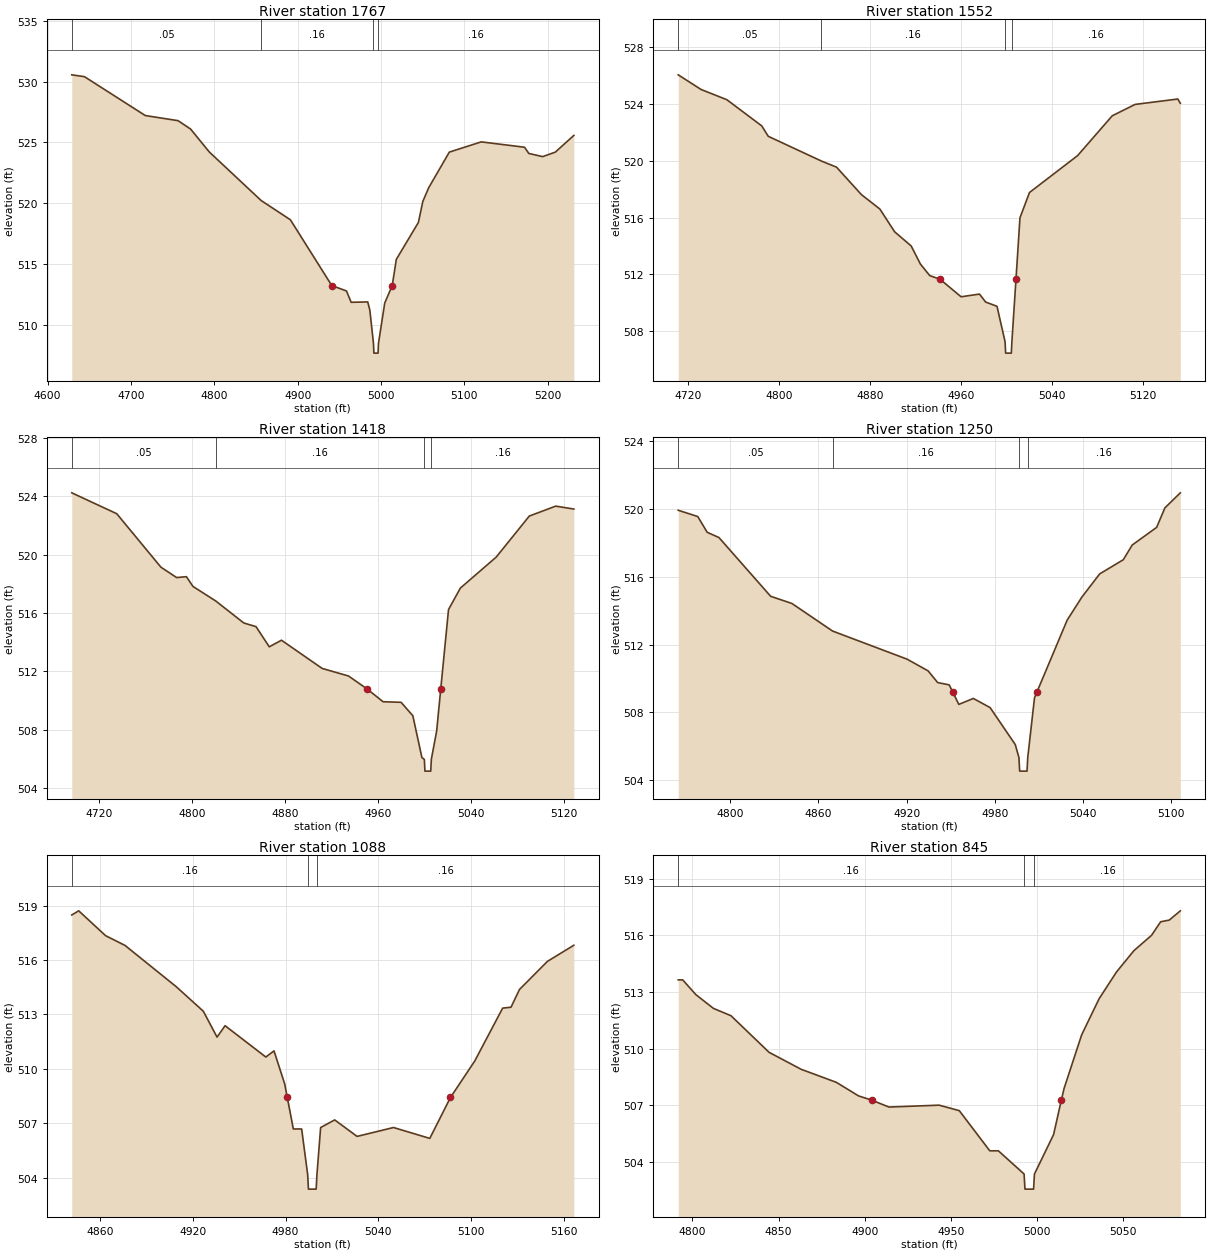
Type RM Length L Ch R = 1,1767,215,215,215
BEGIN DESCRIPTION:
UNT 123 in LFCCL Watershed 4.0
END DESCRIPTION:
XS GIS Cut Line= 3
      2830972.89      7086282.91      2831129.90      7085964.41
      2831207.10      7085729.46
#Sta/Elev= 30
  4628.9  530.55  4644.1  530.40  4717.1  527.21  4756.4  526.79  4771.5  526.10
  4793.8  524.23  4856.1  520.24  4891.2  518.66  4940.9  513.26  4958.5  512.82
  4964.1  511.89  4984.0  511.92  4986.5  511.26  4990.9  508.52  4991.4  507.72
  4996.4  507.72  4996.9  508.52  5004.4  511.83  5013.4  513.26  5018.3  515.41
  5044.8  518.44  5050.1  520.16  5057.1  521.28  5081.9  524.21  5120.2  525.05
  5172.1  524.61  5177.3  524.10  5193.9  523.84  5209.1  524.21  5231.3  525.58
#Mann=4,-1,0
  4628.9    0.05       0  4856.1    0.16       0  4990.9    0.07       0
  4996.9    0.16       0
Bank Sta=4940.9,5013.4
Exp/Cntr=0.3,0.1

Type RM Length L Ch R = 1,1552,134,134,134
BEGIN DESCRIPTION:
Mapping XS 5fc00938
END DESCRIPTION:
XS GIS Cut Line= 3
      2831104.13      7086262.72      2831234.21      7086020.49
      2831260.00      7085855.64
#Sta/Elev= 30
  4711.4  526.03  4731.5  525.00  4754.2  524.28  4784.9  522.44  4790.6  521.71
  4837.4  519.97  4850.7  519.54  4872.6  517.61  4888.8  516.60  4901.8  515.00
  4916.4  514.00  4924.5  512.73  4932.7  511.92  4941.8  511.66  4960.3  510.43
  4976.5  510.62  4981.9  510.06  4991.9  509.76  4999.0  507.27  4999.5  506.47
  5004.5  506.47  5005.0  507.27  5008.6  511.66  5012.1  515.98  5020.5  517.76
  5062.8  520.35  5093.3  523.15  5113.4  523.95  5151.0  524.33  5153.2  524.03
#Mann=4,-1,0
  4711.4    0.05       0  4837.4    0.16       0  4999.0    0.07       0
  5005.0    0.16       0
Bank Sta=4941.8,5008.6
Exp/Cntr=0.3,0.1

Type RM Length L Ch R = 1,1418,168,168,168
BEGIN DESCRIPTION:
XS3791A
END DESCRIPTION:
XS GIS Cut Line= 3
      2831201.71      7086314.31      2831334.50      7086069.57
      2831367.64      7085919.74
#Sta/Elev= 30
  4696.5  524.23  4735.2  522.80  4773.2  519.14  4786.7  518.43  4795.1  518.49
  4800.8  517.82  4820.3  516.83  4844.5  515.32  4855.0  515.07  4866.4  513.69
  4876.9  514.14  4911.9  512.21  4934.6  511.69  4950.6  510.80  4964.3  509.93
  4979.8  509.89  4989.9  508.97  4997.7  506.11  4999.8  505.98  5000.3  505.18
  5005.3  505.18  5005.8  505.98  5010.4  507.93  5013.9  510.80  5020.6  516.24
  5030.8  517.71  5061.6  519.83  5090.1  522.64  5112.8  523.32  5128.4  523.12
#Mann=4,-1,0
  4696.5    0.05       0  4820.3    0.16       0  4999.8    0.07       0
  5005.8    0.16       0
Bank Sta=4950.6,5013.9
Exp/Cntr=0.3,0.1

Type RM Length L Ch R = 1,1250,162,162,162
BEGIN DESCRIPTION:
UNT 123 in LFCCL Watershed 3.0
END DESCRIPTION:
XS GIS Cut Line= 3
      2831300.71      7086329.20      2831425.00      7086175.00
      2831486.95      7086045.51
#Sta/Elev= 30
  4764.6  519.93  4777.9  519.56  4784.3  518.63  4792.3  518.32  4827.5  514.85
  4841.9  514.43  4869.6  512.80  4920.3  511.14  4934.6  510.45  4941.1  509.76
  4949.0  509.62  4951.3  509.21  4955.5  508.47  4965.4  508.82  4976.8  508.28
  4993.9  506.10  4996.4  505.33  4996.9  504.53  5001.9  504.53  5002.4  505.33
  5007.0  508.86  5008.7  509.21  5029.2  513.44  5039.2  514.80  5051.3  516.17
  5067.4  517.01  5073.5  517.88  5090.1  518.92  5095.7  520.07  5106.2  520.96
#Mann=4,-1,0
  4764.6    0.05       0  4869.6    0.16       0  4996.4    0.07       0
  5002.4    0.16       0
Bank Sta=4951.3,5008.7
Exp/Cntr=0.3,0.1

Type RM Length L Ch R = 1,1088,243,243,243
BEGIN DESCRIPTION:
XS3792A
END DESCRIPTION:
XS GIS Cut Line= 3
      2831489.10      7086415.80      2831534.57      7086279.39
      2831606.03      7086112.64
#Sta/Elev= 30
  4841.5  518.49  4846.0  518.72  4863.4  517.35  4876.0  516.81  4909.2  514.53
  4926.7  513.18  4935.6  511.75  4940.8  512.38  4967.2  510.65  4972.5  510.99
  4979.4  509.17  4981.1  508.42  4985.0  506.68  4990.4  506.68  4994.3  504.16
  4994.8  503.36  4999.8  503.36  5000.3  504.16  5002.7  506.76  5011.8  507.18
  5026.3  506.27  5049.9  506.76  5073.4  506.16  5086.8  508.42  5102.5  510.43
  5120.6  513.35  5126.0  513.40  5131.5  514.38  5149.6  515.93  5166.7  516.82
#Mann=3,-1,0
  4841.5    0.16       0  4994.3    0.07       0  5000.3    0.16       0
Bank Sta=4981.1,5086.8
Exp/Cntr=0.3,0.1

Type RM Length L Ch R = 1,845,268,268,268
BEGIN DESCRIPTION:
XS3790A
END DESCRIPTION:
XS GIS Cut Line= 3
      2831640.66      7086405.02      2831675.31      7086225.25
      2831658.23      7086118.48
#Sta/Elev= 30
  4791.8  513.64  4794.4  513.64  4802.0  512.86  4812.2  512.13  4822.4  511.74
  4844.5  509.80  4863.1  508.90  4883.5  508.21  4896.4  507.49  4903.9  507.27
  4914.0  506.90  4943.1  507.00  4954.8  506.71  4972.5  504.58  4977.5  504.58
  4992.4  503.35  4992.9  502.55  4997.9  502.55  4998.4  503.35  5009.5  505.44
  5014.0  507.27  5015.6  507.89  5025.8  510.73  5035.9  512.64  5046.0  514.06
  5056.1  515.19  5066.3  516.00  5071.6  516.72  5076.6  516.81  5083.0  517.30
#Mann=3,-1,0
  4791.8    0.16       0  4992.4    0.07       0  4998.4    0.16       0
Bank Sta=4903.9,5014
Exp/Cntr=0.3,0.1

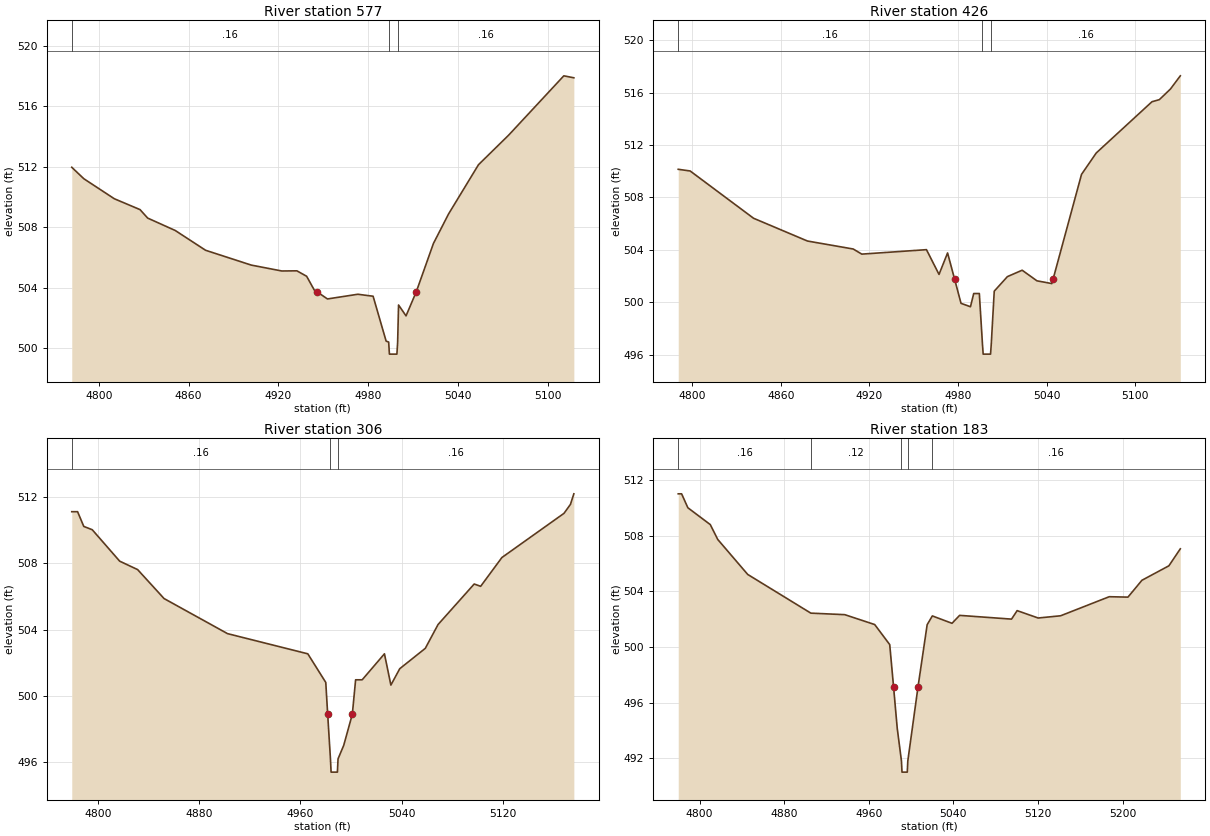
Type RM Length L Ch R = 1,577,151,151,151
BEGIN DESCRIPTION:
XS3789A
END DESCRIPTION:
XS GIS Cut Line= 3
      2831781.40      7086482.96      2831820.39      7086270.72
      2831809.56      7086151.61
#Sta/Elev= 30
  4782.0  511.96  4790.1  511.20  4810.4  509.88  4827.6  509.16  4832.7  508.60
  4851.1  507.78  4871.4  506.47  4901.9  505.49  4922.3  505.10  4932.4  505.11
  4938.9  504.75  4944.0  503.84  4945.6  503.74  4952.8  503.25  4973.1  503.56
  4983.3  503.43  4992.0  500.46  4993.7  500.40  4994.2  499.60  4999.2  499.60
  4999.7  500.40  5000.3  502.85  5005.3  502.13  5012.2  503.74  5023.6  506.92
  5033.7  508.87  5053.7  512.13  5073.8  514.08  5110.7  518.01  5117.4  517.88
#Mann=3,-1,0
  4782.0    0.16       0  4993.7    0.07       0  4999.7    0.16       0
Bank Sta=4945.6,5012.2
Exp/Cntr=0.3,0.1

Type RM Length L Ch R = 1,426,120,120,120
BEGIN DESCRIPTION:
XS3788A
END DESCRIPTION:
XS GIS Cut Line= 3
      2831836.73      7086488.53      2831940.89      7086317.72
      2831928.53      7086178.33
#Sta/Elev= 30
  4790.5  510.15  4798.6  510.02  4841.5  506.41  4878.0  504.67  4909.0  504.06
  4914.8  503.67  4958.6  504.01  4967.1  502.12  4972.9  503.76  4977.6  501.78
  4982.0  499.91  4988.4  499.65  4990.6  500.66  4994.4  500.66  4996.5  496.83
  4997.0  496.03  5002.0  496.03  5002.5  496.83  5004.5  500.84  5013.4  501.95
  5023.4  502.44  5033.4  501.63  5043.5  501.42  5044.4  501.78  5063.6  509.76
  5073.6  511.40  5111.3  515.31  5116.3  515.47  5123.8  516.28  5130.5  517.29
#Mann=3,-1,0
  4790.5    0.16       0  4996.5    0.07       0  5002.5    0.16       0
Bank Sta=4977.6,5044.4
Exp/Cntr=0.3,0.1

Type RM Length L Ch R = 1,306,123,123,123
BEGIN DESCRIPTION:
Mapping XS 482f4c16
END DESCRIPTION:
XS GIS Cut Line= 3
      2831873.52      7086546.89      2832023.53      7086378.83
      2831999.42      7086208.70
#Sta/Elev= 30
  4779.2  511.12  4783.8  511.12  4788.7  510.23  4795.4  510.03  4817.1  508.13
  4831.3  507.62  4852.2  505.87  4902.4  503.75  4965.9  502.53  4980.1  500.80
  4981.6  498.88  4983.8  496.18  4984.3  495.38  4989.3  495.38  4989.8  496.18
  4994.3  497.00  5001.1  498.88  5003.7  500.96  5008.9  500.96  5026.5  502.53
  5031.6  500.64  5038.6  501.63  5058.8  502.86  5068.9  504.30  5097.5  506.75
  5102.6  506.61  5119.4  508.35  5168.5  511.02  5173.6  511.56  5176.3  512.20
#Mann=3,-1,0
  4779.2    0.16       0  4983.8    0.07       0  4989.8    0.16       0
Bank Sta=4981.6,5001.1
Exp/Cntr=0.3,0.1

Type RM Length L Ch R = 1,183,0,0,0
BEGIN DESCRIPTION:
UNT 123 in LFCCL Watershed 1.0
END DESCRIPTION:
XS GIS Cut Line= 3
      2831955.40      7086608.23      2832125.90      7086439.98
      2832046.85      7086218.40
#Sta/Elev= 30
  4779.8  511.01  4783.0  511.01  4788.9  510.01  4810.1  508.80  4817.2  507.73
  4845.5  505.22  4905.2  502.44  4937.3  502.33  4965.6  501.62  4979.8  500.18
  4983.4  497.17  4986.9  494.17  4990.9  491.82  4991.4  491.02  4996.4  491.02
  4996.9  491.82  5006.6  497.17  5015.2  501.61  5020.1  502.24  5038.7  501.71
  5045.9  502.28  5095.0  502.01  5100.3  502.62  5120.2  502.09  5141.4  502.25
  5187.4  503.62  5205.1  503.59  5218.3  504.80  5243.8  505.84  5254.6  507.06
#Mann=5,-1,0
  4779.8    0.16       0  4905.2    0.12       0  4990.9    0.07       0
  4996.9    0.12       0  5020.1    0.16       0
Bank Sta=4983.4,5006.6
Exp/Cntr=0.3,0.1

Chan Stop Cuts=-1