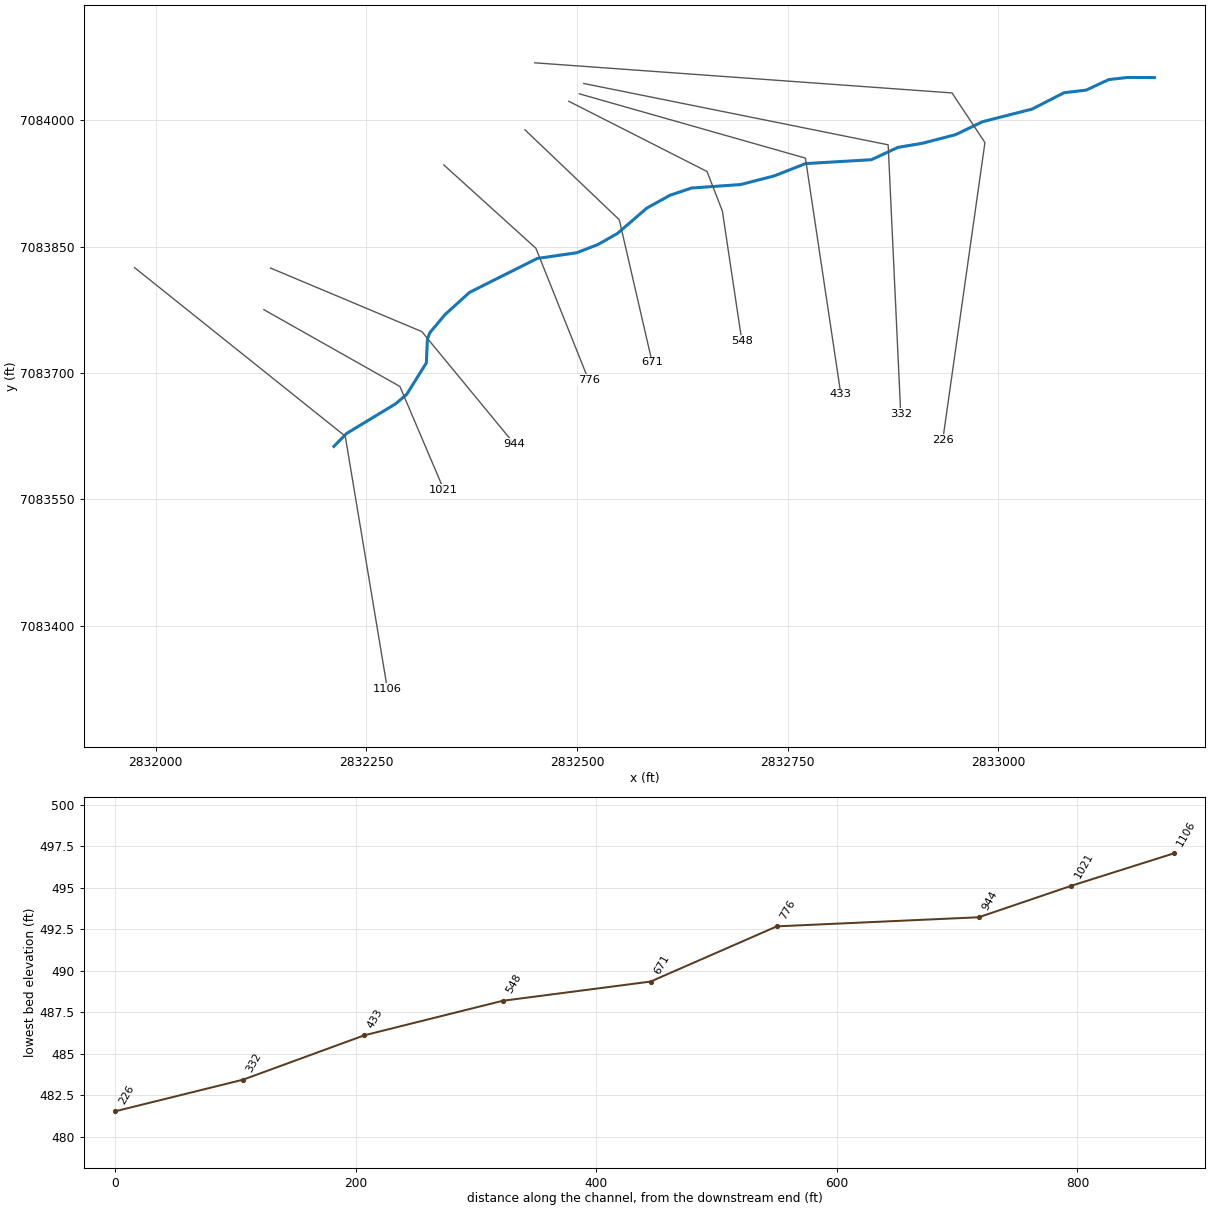
--- UNT 124 in LFCCL Watershed.prj (project) ---

Proj Title=UNT 124 in LFCCL Watershed Base Level Engineering
Current Plan=p01
Default Exp/Contr=0.3,0.1
English Units
Geom File=g01
Flow File=f01
Plan File=p01
BEGIN DESCRIPTION:
UNT 124 in LFCCL Watershed
END DESCRIPTION:

--- UNT 124 in LFCCL Watershed.p01 (plan) ---

Plan Title=Multiple Run
Short Identifier=Multiple
Geom File=g01
Flow File=f01
Subcritical Flow
K Sum by GR= 0
Std Step Tol= 0.01
Critical Tol= 0.01
Num of Std Step Trials= 20
Max Error Tol= 0.3
Flow Tol Ratio= 0.001
Split Flow NTrial= 30
Split Flow Tol= 0.02
Split Flow Ratio= 0.02
Log Output Level= 0
Friction Slope Method= 1
Unsteady Friction Slope Method= 2
Unsteady Bridges Friction Slope Method= 1
Parabolic Critical Depth
Global Vel Dist=  1 , 1 , 1
Global Log Level= 0
CheckData=True
Encroach Param= -1, 0, 0, 0
BEGIN DESCRIPTION:
Multiple Run
END DESCRIPTION:

--- UNT 124 in LFCCL Watershed.f01 (steady flow) ---

Flow Title=Multiple
Number of Profiles=7
Profile Names=10-year,25-year,50-year,1pct_min,100-year,1pct_plu,500-year
River Rch & RM= UNT 124 in LFCCL,Reach-1,1106
     196     241     275     156     312     622     398
Boundary for River Rch & Prof#=UNT 124 in LFCCL,Reach-1,1
Up Type=0
Dn Type=3
Dn Slope=0.005
Boundary for River Rch & Prof#=UNT 124 in LFCCL,Reach-1,2
Up Type=0
Dn Type=3
Dn Slope=0.005
Boundary for River Rch & Prof#=UNT 124 in LFCCL,Reach-1,3
Up Type=0
Dn Type=3
Dn Slope=0.005
Boundary for River Rch & Prof#=UNT 124 in LFCCL,Reach-1,4
Up Type=0
Dn Type=3
Dn Slope=0.005
Boundary for River Rch & Prof#=UNT 124 in LFCCL,Reach-1,5
Up Type=0
Dn Type=3
Dn Slope=0.005
Boundary for River Rch & Prof#=UNT 124 in LFCCL,Reach-1,6
Up Type=0
Dn Type=3
Dn Slope=0.005
Boundary for River Rch & Prof#=UNT 124 in LFCCL,Reach-1,7
Up Type=0
Dn Type=3
Dn Slope=0.005

--- UNT 124 in LFCCL Watershed.g01 (geometry) ---

Geom Title=Existing Conditions

River Reach=UNT 124 in LFCCL,Reach-1
Reach XY= 30
      2832211.42      7083612.84      2832226.67      7083628.28
      2832284.62      7083663.33      2832298.03      7083674.76
      2832321.27      7083712.04      2832322.56      7083740.39
      2832325.39      7083747.79      2832343.33      7083769.25
      2832372.48      7083795.67      2832452.83      7083835.98
      2832499.74      7083842.75      2832524.87      7083852.45
      2832548.23      7083865.72      2832582.94      7083895.73
      2832610.48      7083910.98      2832636.05      7083919.60
      2832694.34      7083923.72      2832734.24      7083933.97
      2832771.47      7083948.59      2832849.55      7083953.21
      2832881.21      7083967.88      2832910.30      7083972.75
      2832949.64      7083983.00      2832981.58      7083998.34
      2833040.34      7084013.30      2833078.37      7084032.74
      2833104.54      7084035.82      2833131.39      7084048.33
      2833153.55      7084050.82      2833185.59      7084050.71

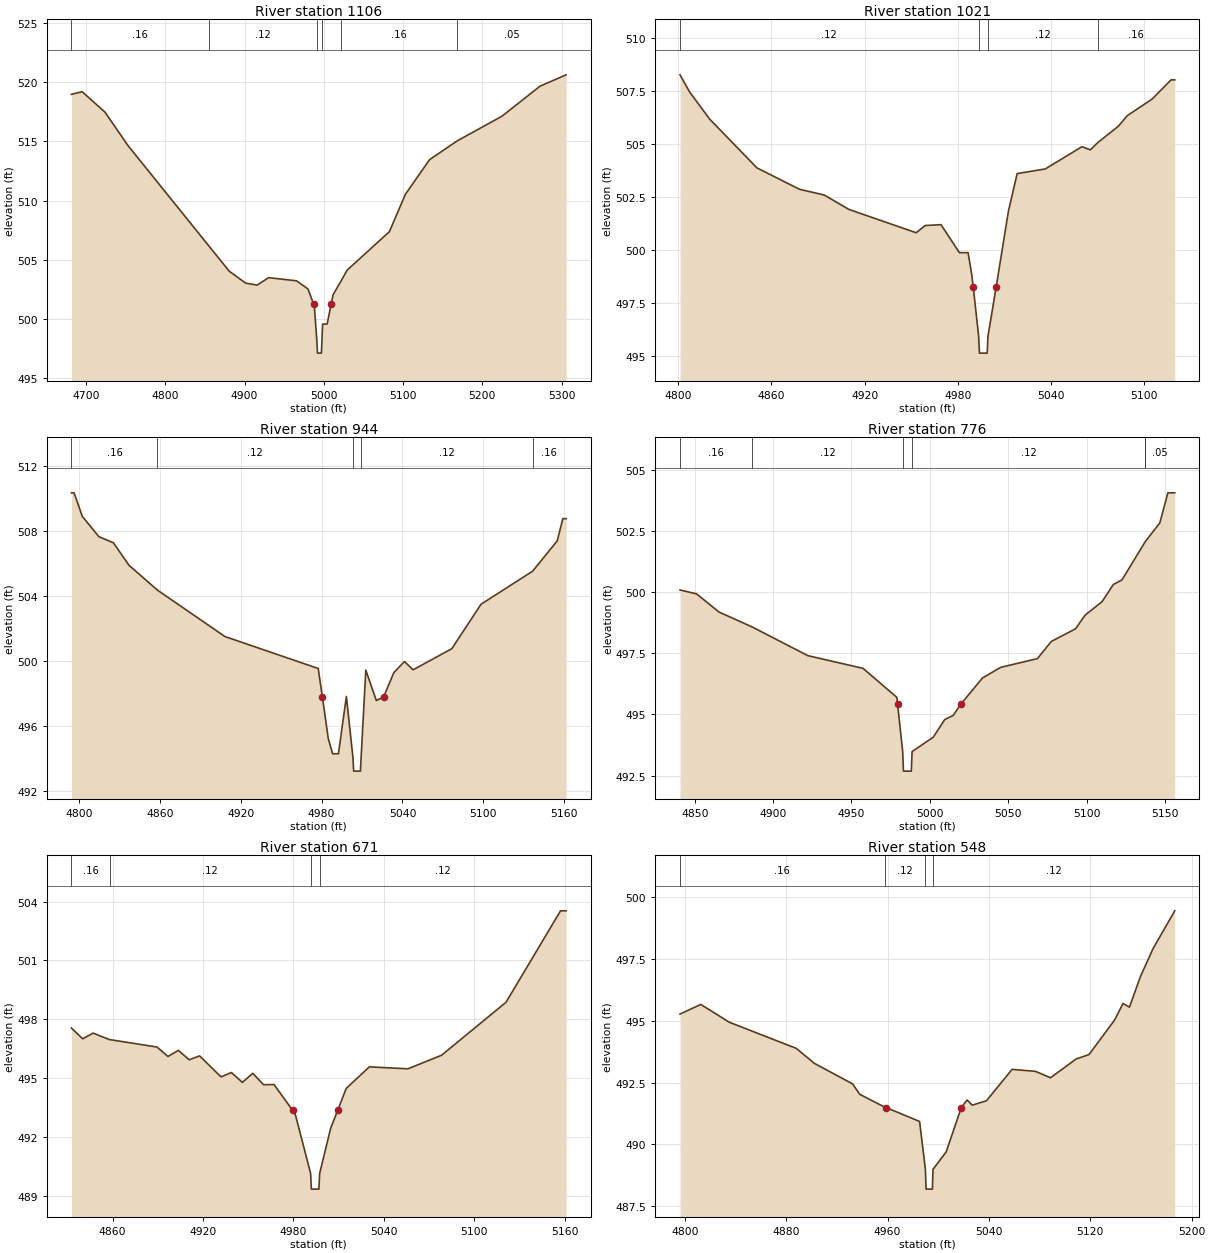
Type RM Length L Ch R = 1,1106,85,85,85
BEGIN DESCRIPTION:
UNT 124 in LFCCL Watershed 2.0
END DESCRIPTION:
XS GIS Cut Line= 3
      2831974.99      7083825.00      2832225.00      7083625.00
      2832275.00      7083325.00
#Sta/Elev= 30
  4681.5  518.99  4695.1  519.21  4723.9  517.48  4752.7  514.67  4854.9  506.16
  4880.8  504.01  4901.6  503.00  4916.0  502.84  4930.4  503.47  4965.6  503.20
  4980.1  502.51  4987.2  501.21  4988.1  501.05  4991.5  497.88  4992.0  497.08
  4997.0  497.08  4997.5  497.88  4998.5  499.54  5004.2  499.54  5009.3  501.21
  5011.8  502.03  5021.9  503.20  5029.5  504.11  5082.8  507.36  5103.0  510.53
  5133.5  513.46  5168.4  515.05  5224.7  517.13  5272.9  519.68  5305.8  520.64
#Mann=6,-1,0
  4681.5    0.16       0  4854.9    0.12       0  4991.5    0.07       0
  4997.5    0.12       0  5021.9    0.16       0  5168.4    0.05       0
Bank Sta=4987.2,5009.3
Exp/Cntr=0.3,0.1

Type RM Length L Ch R = 1,1021,77,77,77
BEGIN DESCRIPTION:
XS3797A
END DESCRIPTION:
XS GIS Cut Line= 3
      2832128.38      7083775.19      2832289.86      7083684.03
      2832341.92      7083561.68
#Sta/Elev= 30
  4801.2  508.26  4807.4  507.45  4820.3  506.17  4850.7  503.87  4878.1  502.86
  4894.0  502.59  4909.9  501.91  4953.2  500.81  4959.0  501.15  4969.2  501.19
  4981.0  499.87  4986.6  499.87  4989.0  498.82  4989.9  498.26  4993.4  495.93
  4993.9  495.13  4998.9  495.13  4999.4  495.93  5004.7  498.26  5012.6  501.84
  5018.2  503.60  5036.3  503.82  5059.9  504.87  5065.3  504.72  5070.0  505.06
  5083.4  505.84  5089.0  506.33  5105.1  507.12  5117.2  508.02  5119.6  508.02
#Mann=4,-1,0
  4801.2    0.12       0  4993.4    0.07       0  4999.4    0.12       0
  5070.0    0.16       0
Bank Sta=4989.9,5004.7
Exp/Cntr=0.3,0.1

Type RM Length L Ch R = 1,944,168,168,168
BEGIN DESCRIPTION:
XS3793A
END DESCRIPTION:
XS GIS Cut Line= 3
      2832136.22      7083824.65      2832315.90      7083749.14
      2832425.30      7083616.29
#Sta/Elev= 30
  4794.4  510.37  4796.4  510.37  4802.5  508.92  4814.8  507.67  4825.6  507.29
  4837.1  505.91  4858.2  504.38  4908.3  501.52  4977.5  499.55  4980.6  497.79
  4985.0  495.22  4988.2  494.30  4992.5  494.30  4998.4  497.83  5003.3  494.03
  5003.8  493.23  5008.8  493.23  5009.3  494.03  5012.8  499.45  5020.6  497.58
  5026.0  497.79  5033.6  499.30  5041.5  499.98  5047.9  499.47  5076.6  500.77
  5098.3  503.51  5136.5  505.54  5154.8  507.41  5159.0  508.78  5161.4  508.78
#Mann=5,-1,0
  4794.4    0.16       0  4858.2    0.12       0  5003.3    0.07       0
  5009.3    0.12       0  5136.5    0.16       0
Bank Sta=4980.6,5026
Exp/Cntr=0.3,0.1

Type RM Length L Ch R = 1,776,105,105,105
BEGIN DESCRIPTION:
XS3794A
END DESCRIPTION:
XS GIS Cut Line= 3
      2832341.98      7083947.02      2832451.32      7083848.09
      2832513.80      7083691.88
#Sta/Elev= 30
  4840.6  500.10  4851.2  499.94  4865.4  499.20  4886.8  498.58  4922.2  497.41
  4957.4  496.89  4979.0  495.70  4979.4  495.44  4982.7  493.48  4983.2  492.68
  4988.2  492.68  4988.7  493.48  5002.2  494.07  5009.5  494.79  5014.9  494.96
  5020.0  495.44  5033.7  496.50  5045.2  496.93  5068.7  497.29  5077.5  497.99
  5093.0  498.51  5099.1  499.07  5109.9  499.62  5117.2  500.33  5122.6  500.51
  5137.4  502.07  5137.5  502.08  5146.8  502.85  5151.9  504.08  5156.3  504.08
#Mann=6,-1,0
  4840.6    0.16       0  4886.8    0.12       0  4982.7    0.07       0
  4988.7    0.12       0  5137.4    0.16       0  5137.5    0.05       0
Bank Sta=4979.4,5020
Exp/Cntr=0.3,0.1

Type RM Length L Ch R = 1,671,123,123,123
BEGIN DESCRIPTION:
XS3795A
END DESCRIPTION:
XS GIS Cut Line= 3
      2832438.32      7083988.70      2832550.28      7083881.95
      2832589.34      7083712.69
#Sta/Elev= 30
  4832.6  497.56  4840.1  497.01  4847.0  497.30  4857.9  496.97  4889.4  496.59
  4896.7  496.11  4903.6  496.42  4910.8  495.94  4917.7  496.14  4931.9  495.07
  4938.8  495.29  4946.1  494.79  4953.0  495.25  4960.2  494.67  4967.1  494.68
  4979.4  493.37  4981.3  493.14  4991.4  490.15  4991.9  489.35  4996.9  489.35
  4997.4  490.15  5004.7  492.45  5009.4  493.37  5015.0  494.48  5030.4  495.58
  5056.0  495.48  5078.3  496.17  5121.1  498.87  5157.3  503.53  5161.0  503.53
#Mann=4,-1,0
  4832.6    0.16       0  4857.9    0.12       0  4991.4    0.07       0
  4997.4    0.12       0
Bank Sta=4979.4,5009.4
Exp/Cntr=0.3,0.1

Type RM Length L Ch R = 1,548,115,115,115
BEGIN DESCRIPTION:
XS3796A
END DESCRIPTION:
XS GIS Cut Line= 4
      2832490.38      7084022.57      2832654.44      7083939.24
      2832672.67      7083892.37      2832695.81      7083738.10
#Sta/Elev= 30
  4796.3  495.28  4812.7  495.67  4835.1  494.95  4888.0  493.89  4902.4  493.28
  4932.5  492.45  4938.1  492.03  4957.8  491.51  4959.1  491.49  4985.3  490.93
  4989.9  488.99  4990.4  488.19  4995.4  488.19  4995.9  488.99  5006.3  489.70
  5018.2  491.49  5022.8  491.80  5026.9  491.59  5038.1  491.77  5058.3  493.04
  5076.7  492.96  5088.6  492.70  5108.8  493.46  5119.0  493.64  5139.2  495.04
  5145.8  495.71  5150.9  495.56  5159.4  496.78  5169.5  497.93  5186.6  499.46
#Mann=4,-1,0
  4796.3    0.16       0  4957.8    0.12       0  4989.9    0.07       0
  4995.9    0.12       0
Bank Sta=4959.1,5018.2
Exp/Cntr=0.3,0.1

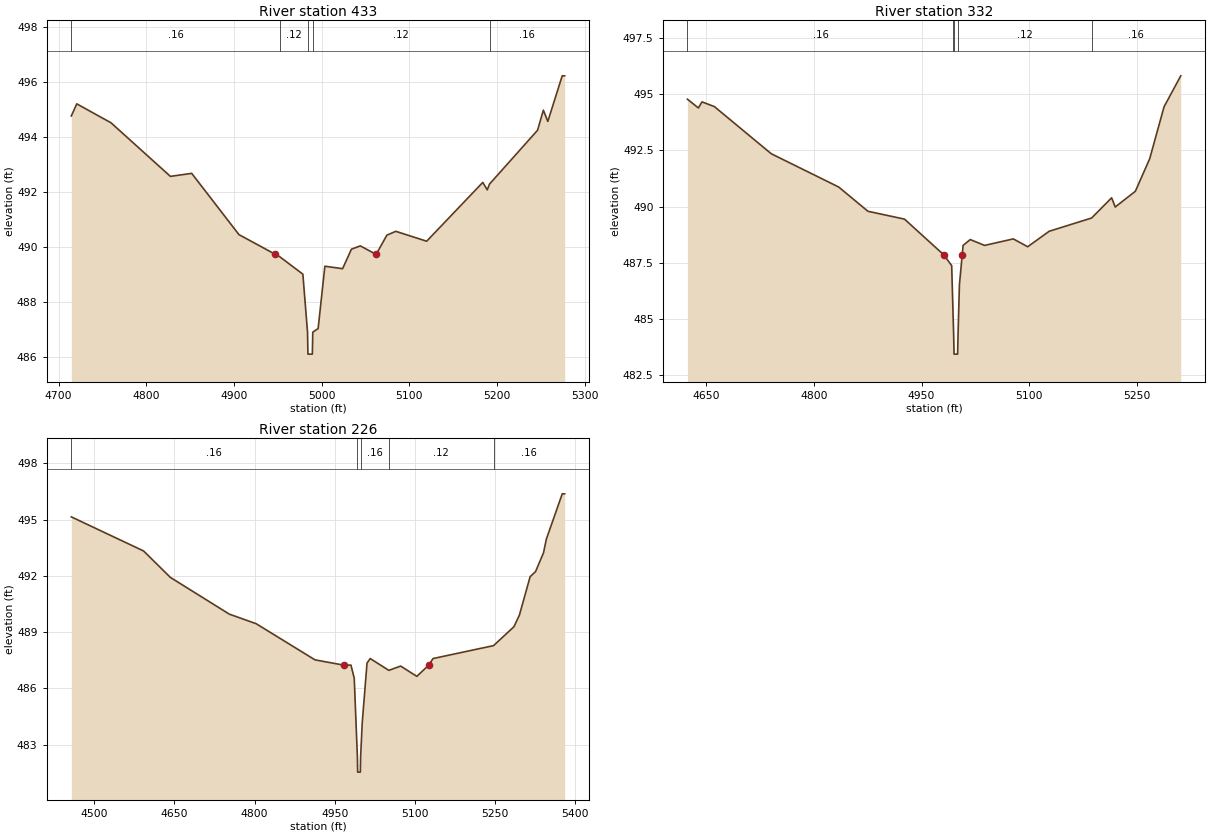
Type RM Length L Ch R = 1,433,101,101,101
BEGIN DESCRIPTION:
Mapping XS 9ecd97f0
END DESCRIPTION:
XS GIS Cut Line= 3
      2832502.97      7084031.39      2832771.29      7083955.10
      2832813.38      7083674.49
#Sta/Elev= 30
  4714.6  494.78  4720.8  495.22  4759.9  494.53  4827.6  492.58  4851.9  492.69
  4905.8  490.46  4947.4  489.74  4952.1  489.66  4978.7  489.02  4984.0  486.91
  4984.5  486.11  4989.5  486.11  4990.0  486.91  4996.1  487.04  5003.8  489.31
  5024.0  489.22  5034.1  489.93  5044.2  490.05  5062.3  489.74  5074.5  490.44
  5084.7  490.58  5119.9  490.22  5183.9  492.36  5189.0  492.09  5191.6  492.30
  5246.4  494.26  5253.0  494.99  5258.1  494.58  5274.5  496.24  5277.3  496.24
#Mann=5,-1,0
  4714.6    0.16       0  4952.1    0.12       0  4984.0    0.07       0
  4990.0    0.12       0  5191.6    0.16       0
Bank Sta=4947.4,5062.3
Exp/Cntr=0.3,0.1

Type RM Length L Ch R = 1,332,106,106,106
BEGIN DESCRIPTION:
Mapping XS 24e819b7
END DESCRIPTION:
XS GIS Cut Line= 3
      2832508.18      7084043.68      2832869.50      7083970.89
      2832884.41      7083651.72
#Sta/Elev= 30
  4623.5  494.78  4638.8  494.39  4643.9  494.66  4661.1  494.45  4740.5  492.35
  4834.5  490.87  4875.3  489.79  4926.3  489.44  4981.1  487.85  4992.1  487.37
  4994.4  484.79  4994.9  484.23  4995.4  483.43  5000.4  483.43  5000.9  484.23
  5002.9  486.52  5006.8  487.85  5008.0  488.27  5018.0  488.53  5038.0  488.27
  5078.1  488.56  5098.1  488.21  5128.1  488.90  5187.3  489.49  5215.2  490.39
  5220.2  489.98  5248.3  490.68  5268.3  492.13  5288.3  494.44  5311.6  495.82
#Mann=5,-1,0
  4623.5    0.16       0  4994.4    0.12       0  4994.9    0.07       0
  5000.9    0.12       0  5187.3    0.16       0
Bank Sta=4981.1,5006.8
Exp/Cntr=0.3,0.1

Type RM Length L Ch R = 1,226,0,0,0
BEGIN DESCRIPTION:
UNT 124 in LFCCL Watershed 1.0
END DESCRIPTION:
XS GIS Cut Line= 4
      2832450.04      7084068.23      2832945.32      7084032.47
      2832984.38      7083973.52      2832934.40      7083621.03
#Sta/Elev= 30
  4457.0  495.15  4592.3  493.33  4642.4  491.92  4752.7  489.96  4802.9  489.45
  4913.1  487.52  4966.7  487.24  4980.3  487.24  4986.5  486.54  4992.4  482.33
  4992.9  481.53  4997.9  481.53  4998.4  482.33  5001.4  484.15  5010.4  487.35
  5016.4  487.59  5051.3  486.96  5073.3  487.19  5103.6  486.64  5126.0  487.24
  5133.9  487.59  5247.2  488.28  5285.4  489.29  5295.5  489.90  5315.7  491.96
  5325.8  492.23  5340.7  493.23  5346.0  493.96  5375.8  496.38  5380.3  496.38
#Mann=5,-1,0
  4457.0    0.16       0  4992.4    0.07       0  4998.4    0.16       0
  5051.3    0.12       0  5247.2    0.16       0
Bank Sta=4966.7,5126
Exp/Cntr=0.3,0.1

Chan Stop Cuts=-1