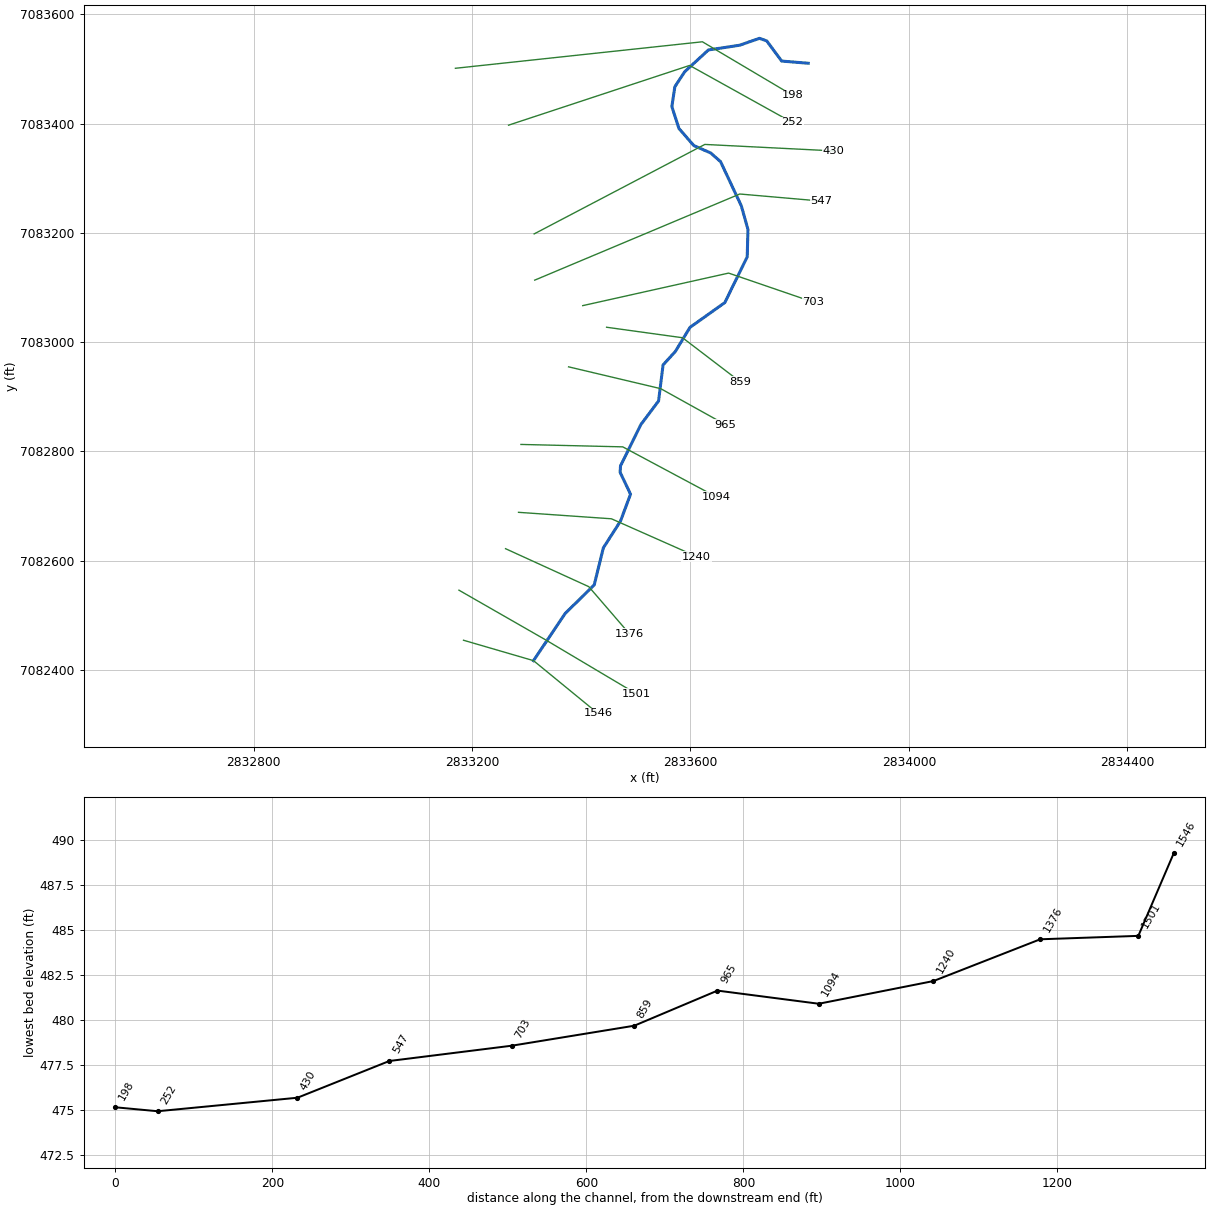
--- UNT 125 in LFCCL Watershed.prj (project) ---

Proj Title=UNT 125 in LFCCL Watershed Base Level Engineering
Current Plan=p01
Default Exp/Contr=0.3,0.1
English Units
Geom File=g01
Flow File=f01
Plan File=p01
BEGIN DESCRIPTION:
UNT 125 in LFCCL Watershed
END DESCRIPTION:

--- UNT 125 in LFCCL Watershed.p01 (plan) ---

Plan Title=Multiple Run
Short Identifier=Multiple
Geom File=g01
Flow File=f01
Subcritical Flow
K Sum by GR= 0
Std Step Tol= 0.01
Critical Tol= 0.01
Num of Std Step Trials= 20
Max Error Tol= 0.3
Flow Tol Ratio= 0.001
Split Flow NTrial= 30
Split Flow Tol= 0.02
Split Flow Ratio= 0.02
Log Output Level= 0
Friction Slope Method= 1
Unsteady Friction Slope Method= 2
Unsteady Bridges Friction Slope Method= 1
Parabolic Critical Depth
Global Vel Dist=  1 , 1 , 1
Global Log Level= 0
CheckData=True
Encroach Param= -1, 0, 0, 0
BEGIN DESCRIPTION:
Multiple Run
END DESCRIPTION:

--- UNT 125 in LFCCL Watershed.f01 (steady flow) ---

Flow Title=Multiple
Number of Profiles=7
Profile Names=10-year,25-year,50-year,1pct_min,100-year,1pct_plu,500-year
River Rch & RM= UNT 125 in LFCCL,Reach-1,1546
     398     517     611     359     717    1430     982
Boundary for River Rch & Prof#=UNT 125 in LFCCL,Reach-1,1
Up Type=0
Dn Type=3
Dn Slope=0.005
Boundary for River Rch & Prof#=UNT 125 in LFCCL,Reach-1,2
Up Type=0
Dn Type=3
Dn Slope=0.005
Boundary for River Rch & Prof#=UNT 125 in LFCCL,Reach-1,3
Up Type=0
Dn Type=3
Dn Slope=0.005
Boundary for River Rch & Prof#=UNT 125 in LFCCL,Reach-1,4
Up Type=0
Dn Type=3
Dn Slope=0.005
Boundary for River Rch & Prof#=UNT 125 in LFCCL,Reach-1,5
Up Type=0
Dn Type=3
Dn Slope=0.005
Boundary for River Rch & Prof#=UNT 125 in LFCCL,Reach-1,6
Up Type=0
Dn Type=3
Dn Slope=0.005
Boundary for River Rch & Prof#=UNT 125 in LFCCL,Reach-1,7
Up Type=0
Dn Type=3
Dn Slope=0.005

--- UNT 125 in LFCCL Watershed.g01 (geometry) ---

Geom Title=Existing Conditions

River Reach=UNT 125 in LFCCL,Reach-1
Reach XY= 30
      2833312.59      7082416.95      2833370.56      7082503.33
      2833423.74      7082555.50      2833440.48      7082623.39
      2833471.86      7082672.43      2833490.26      7082721.70
      2833471.18      7082761.73      2833471.92      7082773.45
      2833509.19      7082849.18      2833541.58      7082892.41
      2833549.83      7082958.37      2833572.17      7082982.85
      2833599.20      7083027.21      2833662.81      7083072.38
      2833703.88      7083156.21      2833705.25      7083206.36
      2833693.08      7083249.64      2833655.08      7083330.53
      2833636.99      7083346.43      2833606.10      7083359.96
      2833578.85      7083391.31      2833565.94      7083431.30
      2833571.36      7083467.62      2833589.41      7083495.12
      2833632.88      7083535.05      2833689.84      7083543.64
      2833726.27      7083556.30      2833739.58      7083551.62
      2833766.97      7083514.65      2833815.59      7083510.71

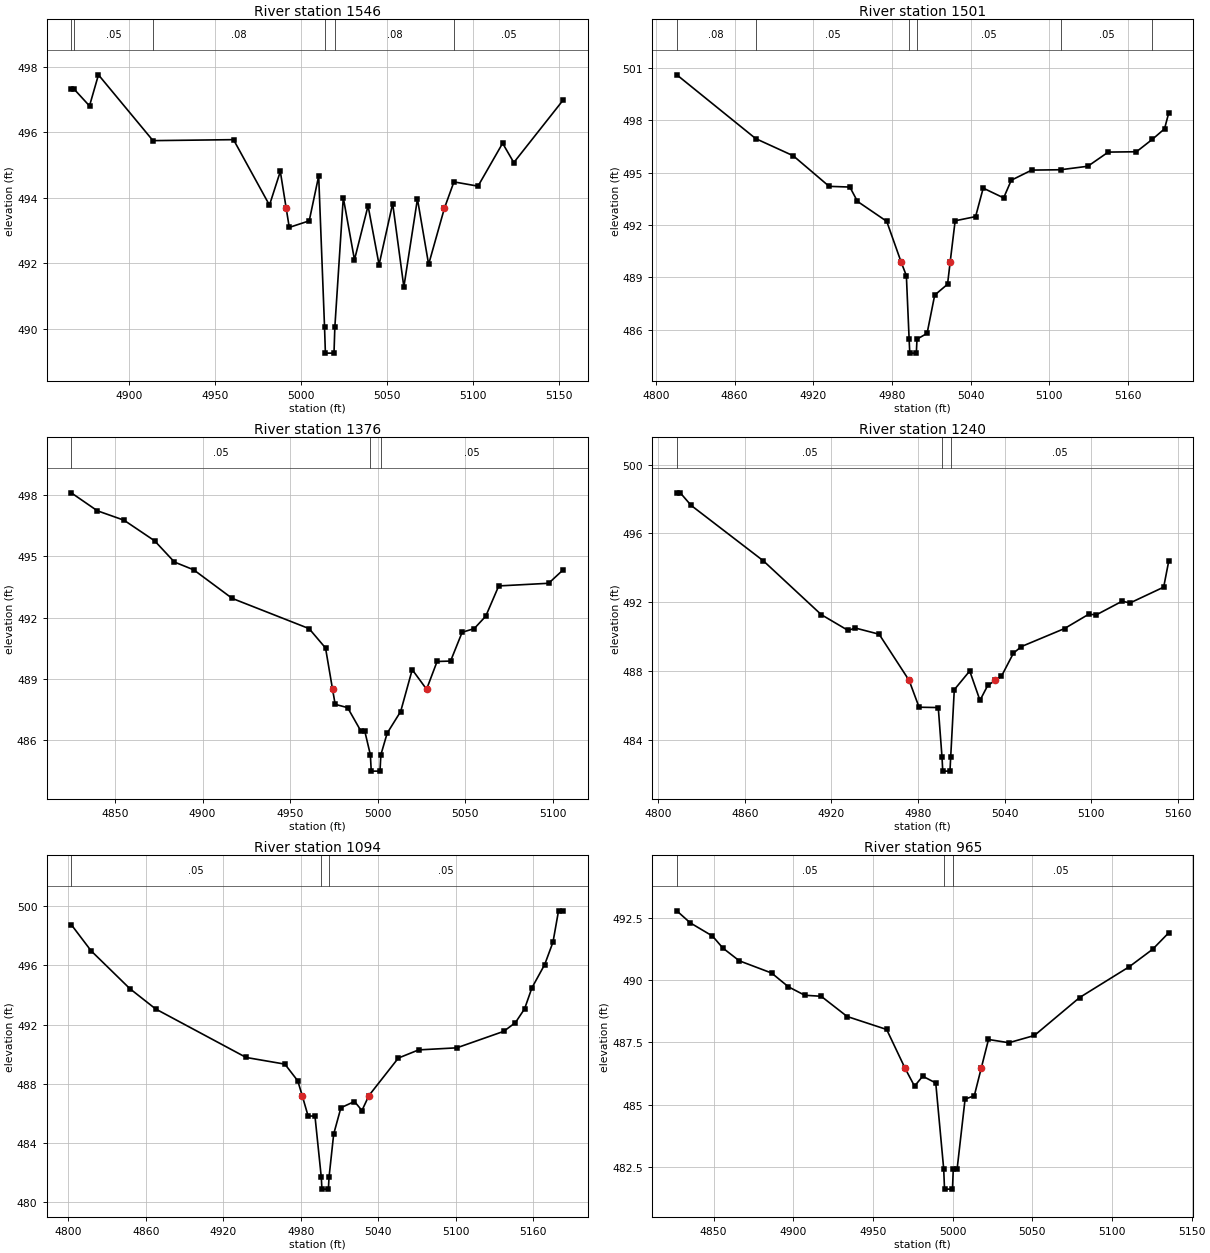
Type RM Length L Ch R = 1,1546,45,45,45
BEGIN DESCRIPTION:
UNT 125 in LFCCL Watershed 2.0
END DESCRIPTION:
XS GIS Cut Line= 3
      2833184.42      7082454.30      2833312.59      7082416.95
      2833430.49      7082320.39
#Sta/Elev= 30
  4866.5  497.31  4868.2  497.31  4877.1  496.80  4882.3  497.75  4914.0  495.74
  4960.8  495.77  4981.7  493.77  4988.0  494.80  4991.4  493.68  4993.2  493.09
  5004.8  493.29  5010.3  494.66  5013.7  490.05  5014.2  489.25  5019.2  489.25
  5019.7  490.05  5024.6  494.00  5031.1  492.10  5039.0  493.75  5045.4  491.95
  5053.3  493.82  5059.8  491.27  5067.7  493.96  5074.2  491.96  5083.4  493.68
  5088.9  494.48  5102.9  494.35  5117.2  495.66  5123.7  495.07  5152.4  496.98
#Mann=6,-1,0
  4866.5    0.08       0  4868.2    0.05       0  4914.0    0.08       0
  5013.7    0.07       0  5019.7    0.08       0  5088.9    0.05       0
Bank Sta=4991.4,5083.4
Exp/Cntr=0.3,0.1

Type RM Length L Ch R = 1,1501,125,125,125
BEGIN DESCRIPTION:
Mapping XS 6c8b4316
END DESCRIPTION:
XS GIS Cut Line= 3
      2833176.07      7082545.98      2833334.75      7082455.00
      2833500.03      7082356.73
#Sta/Elev= 30
  4815.9  500.59  4876.1  496.94  4904.7  495.96  4932.1  494.21  4947.9  494.17
  4953.7  493.35  4976.0  492.21  4987.0  489.88  4991.0  489.10  4993.1  485.47
  4993.6  484.67  4998.6  484.67  4999.1  485.47  5006.8  485.80  5012.6  487.99
  5022.4  488.61  5024.4  489.88  5028.2  492.24  5043.8  492.48  5049.6  494.11
  5065.2  493.55  5071.0  494.56  5086.6  495.14  5108.6  495.16  5129.4  495.36
  5145.0  496.17  5166.5  496.19  5178.6  496.90  5187.9  497.50  5191.1  498.41
#Mann=6,-1,0
  4815.9    0.08       0  4876.1    0.05       0  4993.1    0.07       0
  4999.1    0.05       0  5108.6    0.05       0  5178.6    0.08       0
Bank Sta=4987,5024.4
Exp/Cntr=0.3,0.1

Type RM Length L Ch R = 1,1376,136,136,136
BEGIN DESCRIPTION:
XS3798A
END DESCRIPTION:
XS GIS Cut Line= 3
      2833261.41      7082621.91      2833413.85      7082552.35
      2833487.85      7082466.50
#Sta/Elev= 30
  4825.0  498.11  4839.9  497.23  4855.1  496.77  4872.6  495.76  4883.9  494.72
  4894.9  494.34  4916.9  492.94  4960.8  491.46  4970.2  490.51  4974.2  488.49
  4975.7  487.75  4982.8  487.59  4990.4  486.44  4992.6  486.44  4995.8  485.28
  4996.3  484.48  5001.3  484.48  5001.8  485.28  5005.4  486.34  5013.1  487.40
  5019.7  489.45  5027.9  488.49  5033.9  489.85  5041.6  489.87  5048.2  491.28
  5055.1  491.46  5061.7  492.07  5069.1  493.55  5097.6  493.68  5105.9  494.34
#Mann=3,-1,0
  4825.0    0.05       0  4995.8    0.03       0  5001.8    0.05       0
Bank Sta=4974.2,5027.9
Exp/Cntr=0.3,0.1

Type RM Length L Ch R = 1,1240,146,146,146
BEGIN DESCRIPTION:
XS3799A
END DESCRIPTION:
XS GIS Cut Line= 3
      2833285.16      7082688.49      2833455.28      7082676.65
      2833611.02      7082607.60
#Sta/Elev= 30
  4812.8  498.36  4815.2  498.36  4822.7  497.63  4872.8  494.40  4912.9  491.27
  4931.5  490.35  4936.5  490.49  4953.0  490.13  4973.8  487.44  4980.7  485.88
  4994.0  485.86  4996.6  482.96  4997.1  482.16  5002.1  482.16  5002.6  482.96
  5005.1  486.90  5015.8  487.99  5022.9  486.28  5028.3  487.15  5033.6  487.44
  5037.7  487.67  5046.1  489.03  5051.6  489.41  5081.5  490.46  5098.2  491.29
  5103.6  491.26  5121.4  492.05  5126.9  491.95  5150.2  492.87  5153.7  494.38
#Mann=3,-1,0
  4812.8    0.05       0  4996.6    0.03       0  5002.6    0.05       0
Bank Sta=4973.8,5033.6
Exp/Cntr=0.3,0.1

Type RM Length L Ch R = 1,1094,129,129,129
BEGIN DESCRIPTION:
XS3800A
END DESCRIPTION:
XS GIS Cut Line= 3
      2833289.57      7082812.79      2833476.00      7082808.35
      2833647.64      7082716.61
#Sta/Elev= 30
  4802.3  498.74  4817.7  496.97  4847.7  494.42  4867.7  493.05  4937.8  489.78
  4967.8  489.33  4977.8  488.20  4981.2  487.21  4985.8  485.83  4991.1  485.83
  4996.0  481.70  4996.5  480.90  5001.5  480.90  5002.0  481.70  5005.6  484.61
  5011.2  486.39  5021.7  486.81  5027.5  486.20  5032.9  487.21  5055.7  489.74
  5071.4  490.29  5101.0  490.43  5137.3  491.54  5146.4  492.13  5153.5  493.06
  5159.2  494.48  5169.1  496.05  5175.5  497.56  5179.8  499.67  5183.4  499.67
#Mann=3,-1,0
  4802.3    0.05       0  4996.0    0.03       0  5002.0    0.05       0
Bank Sta=4981.2,5032.9
Exp/Cntr=0.3,0.1

Type RM Length L Ch R = 1,965,106,106,106
BEGIN DESCRIPTION:
XS3803A
END DESCRIPTION:
XS GIS Cut Line= 3
      2833376.85      7082954.85      2833545.55      7082914.89
      2833663.85      7082849.17
#Sta/Elev= 30
  4826.9  492.77  4835.3  492.29  4849.3  491.76  4855.8  491.28  4866.1  490.77
  4886.4  490.28  4896.9  489.73  4907.2  489.39  4917.5  489.35  4933.8  488.54
  4958.6  488.02  4970.2  486.46  4976.1  485.75  4981.2  486.15  4989.4  485.88
  4994.4  482.43  4994.9  481.63  4999.9  481.63  5000.4  482.43  5002.8  482.43
  5007.8  485.23  5013.6  485.37  5017.9  486.46  5022.5  487.62  5035.3  487.49
  5051.3  487.78  5079.7  489.30  5110.8  490.53  5125.5  491.23  5135.6  491.89
#Mann=3,-1,0
  4826.9    0.05       0  4994.4    0.03       0  5000.4    0.05       0
Bank Sta=4970.2,5017.9
Exp/Cntr=0.3,0.1

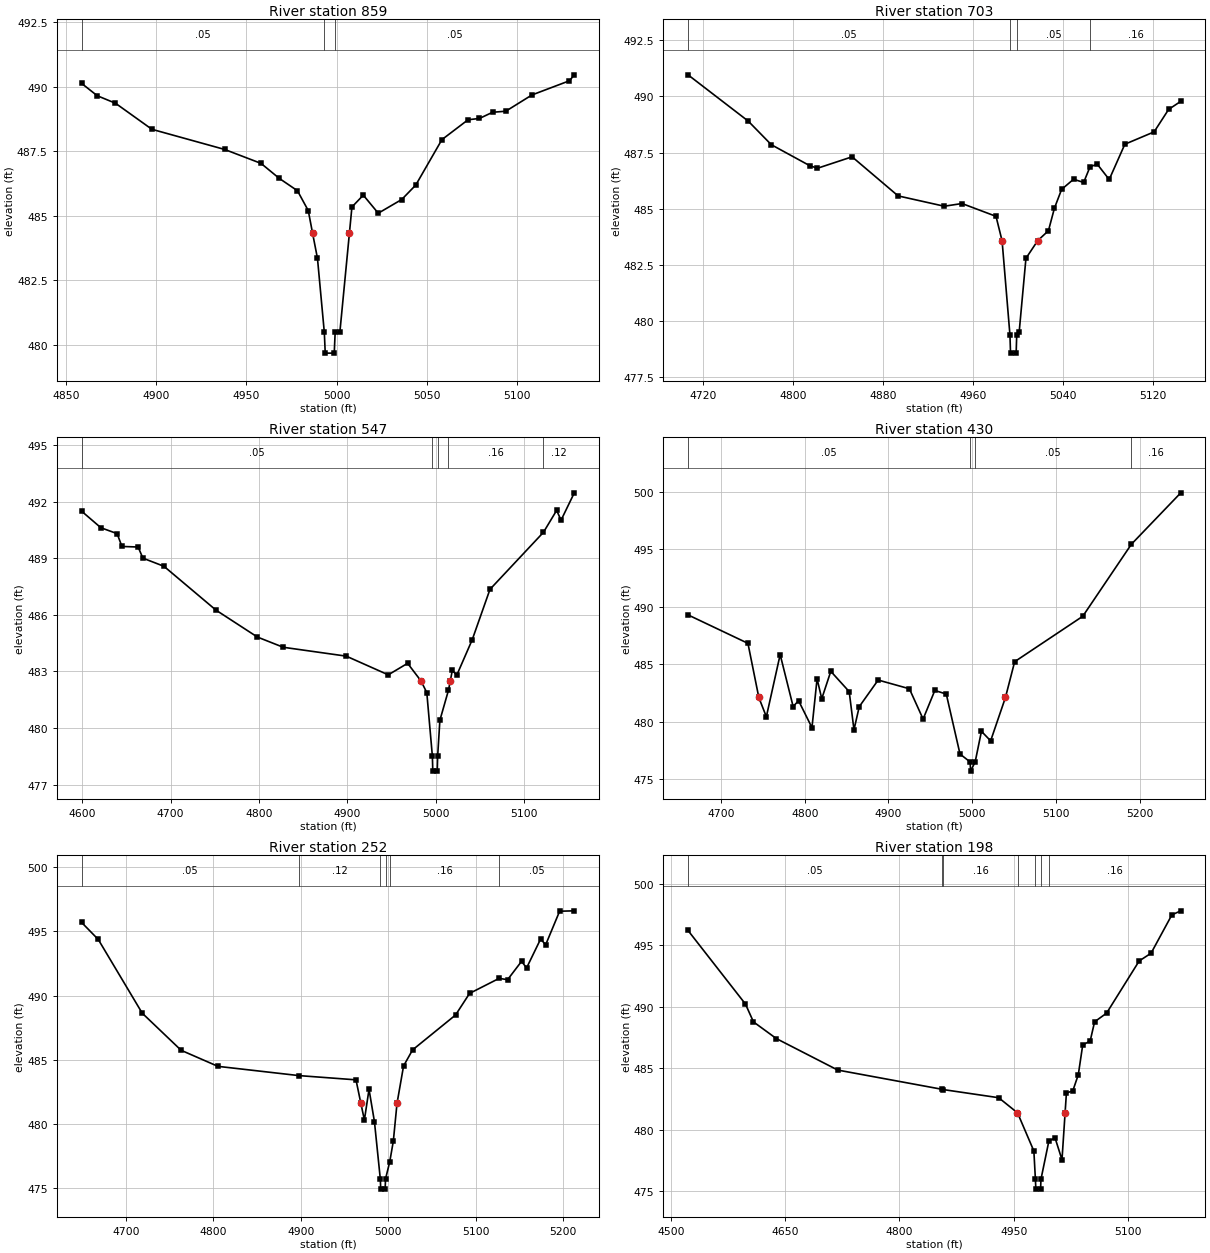
Type RM Length L Ch R = 1,859,156,156,156
BEGIN DESCRIPTION:
XS3802A
END DESCRIPTION:
XS GIS Cut Line= 3
      2833446.41      7083027.35      2833585.50      7083008.12
      2833691.02      7082927.51
#Sta/Elev= 30
  4858.6  490.13  4867.3  489.65  4877.4  489.36  4897.6  488.35  4937.9  487.57
  4958.1  487.03  4968.2  486.45  4978.3  485.97  4984.3  485.20  4986.7  484.32
  4989.4  483.35  4993.2  480.48  4993.7  479.68  4998.7  479.68  4999.2  480.48
  5001.8  480.48  5007.1  484.32  5008.5  485.34  5014.8  485.80  5023.1  485.10
  5036.1  485.63  5043.9  486.19  5058.4  487.95  5072.9  488.72  5079.2  488.77
  5086.5  489.01  5093.8  489.05  5108.3  489.68  5129.1  490.23  5131.8  490.46
#Mann=3,-1,0
  4858.6    0.05       0  4993.2    0.03       0  4999.2    0.05       0
Bank Sta=4986.7,5007.1
Exp/Cntr=0.3,0.1

Type RM Length L Ch R = 1,703,156,156,156
BEGIN DESCRIPTION:
XS3801A
END DESCRIPTION:
XS GIS Cut Line= 3
      2833402.74      7083066.92      2833669.85      7083126.50
      2833825.20      7083073.23
#Sta/Elev= 30
  4706.8  490.96  4760.3  488.90  4780.8  487.85  4814.8  486.92  4821.8  486.80
  4852.6  487.31  4893.5  485.57  4934.5  485.11  4950.3  485.23  4980.5  484.66
  4985.9  483.57  4992.9  479.37  4993.4  478.57  4998.4  478.57  4998.9  479.37
  5001.1  479.52  5007.1  482.79  5017.6  483.58  5027.1  484.02  5032.4  485.02
  5038.8  485.86  5049.4  486.31  5058.4  486.17  5064.1  486.87  5070.5  486.98
  5081.1  486.30  5095.0  487.87  5121.0  488.42  5133.9  489.42  5144.7  489.78
#Mann=4,-1,0
  4706.8    0.05       0  4992.9    0.03       0  4998.9    0.05       0
  5064.1    0.16       0
Bank Sta=4985.9,5017.6
Exp/Cntr=0.3,0.1

Type RM Length L Ch R = 1,547,117,117,117
BEGIN DESCRIPTION:
XS3804A
END DESCRIPTION:
XS GIS Cut Line= 3
      2833314.87      7083113.59      2833690.26      7083271.29
      2833840.02      7083258.27
#Sta/Elev= 30
  4599.2  491.49  4621.1  490.61  4639.4  490.30  4644.9  489.62  4663.2  489.59
  4668.6  489.00  4692.4  488.57  4751.2  486.25  4798.2  484.82  4827.4  484.28
  4898.7  483.81  4946.2  482.82  4968.1  483.43  4983.2  482.50  4989.8  481.88
  4996.1  478.52  4996.6  477.72  5001.6  477.72  5002.1  478.52  5004.6  480.41
  5014.3  482.00  5016.4  482.50  5018.7  483.06  5023.7  482.80  5041.2  484.68
  5061.3  487.35  5121.8  490.37  5136.7  491.53  5141.7  491.01  5156.7  492.46
#Mann=5,-1,0
  4599.2    0.05       0  4996.1    0.03       0  5002.1    0.05       0
  5014.3    0.16       0  5121.8    0.12       0
Bank Sta=4983.2,5016.4
Exp/Cntr=0.3,0.1

Type RM Length L Ch R = 1,430,178,178,178
BEGIN DESCRIPTION:
Mapping XS 332175b1
END DESCRIPTION:
XS GIS Cut Line= 3
      2833313.80      7083198.23      2833626.27      7083362.06
      2833861.95      7083350.23
#Sta/Elev= 30
  4660.5  489.30  4732.1  486.82  4745.1  482.10  4754.1  480.42  4770.6  485.84
  4786.1  481.31  4792.6  481.82  4808.6  479.47  4814.7  483.73  4820.3  481.99
  4831.1  484.38  4853.1  482.61  4858.8  479.28  4865.1  481.30  4887.7  483.62
  4925.0  482.86  4941.4  480.22  4955.4  482.71  4969.1  482.40  4985.5  477.17
  4997.6  476.48  4998.1  475.68  5003.6  476.48  5011.1  479.15  5022.1  478.32
  5039.8  482.10  5050.8  485.22  5132.2  489.18  5190.3  495.46  5249.3  499.94
#Mann=4,-1,0
  4660.5    0.05       0  4997.6    0.03       0  5003.6    0.05       0
  5190.3    0.16       0
Bank Sta=4745.1,5039.8
Exp/Cntr=0.3,0.1

Type RM Length L Ch R = 1,252,54,54,54
BEGIN DESCRIPTION:
Mapping XS 6318f8a8
END DESCRIPTION:
XS GIS Cut Line= 3
      2833266.88      7083397.31      2833598.45      7083506.68
      2833785.92      7083402.53
#Sta/Elev= 30
  4649.4  495.70  4668.5  494.37  4718.8  488.63  4763.3  485.74  4805.4  484.49
  4898.0  483.77  4963.3  483.44  4968.9  481.60  4972.9  480.31  4978.2  482.70
  4984.4  480.18  4991.1  475.73  4991.6  474.93  4996.6  474.93  4997.1  475.73
  5001.9  477.06  5006.0  478.67  5010.2  481.60  5017.7  484.52  5028.0  485.77
  5077.2  488.49  5093.2  490.17  5127.0  491.34  5136.7  491.24  5152.7  492.67
  5158.4  492.15  5174.5  494.41  5180.2  493.95  5196.2  496.57  5213.0  496.60
#Mann=6,-1,0
  4649.4    0.05       0  4898.0    0.12       0  4991.1    0.07       0
  4997.1    0.12       0  5001.9    0.16       0  5127.0    0.05       0
Bank Sta=4968.9,5010.2
Exp/Cntr=0.3,0.1

Type RM Length L Ch R = 1,198,0,0,0
BEGIN DESCRIPTION:
UNT 125 in LFCCL Watershed 1.0
END DESCRIPTION:
XS GIS Cut Line= 3
      2833169.62      7083501.47      2833621.83      7083550.00
      2833786.88      7083452.11
#Sta/Elev= 30
  4522.6  496.20  4598.0  490.21  4608.5  488.76  4638.6  487.40  4719.1  484.84
  4856.4  483.27  4857.8  483.25  4930.3  482.59  4954.6  481.38  4955.8  481.25
  4976.5  478.25  4978.5  475.95  4979.1  475.15  4985.3  475.15  4985.8  475.95
  4996.2  479.07  5004.3  479.32  5013.4  477.54  5017.5  481.38  5019.2  482.97
  5027.6  483.15  5034.8  484.46  5040.6  486.88  5050.4  487.21  5056.2  488.77
  5071.9  489.47  5114.7  493.72  5130.3  494.35  5157.6  497.47  5169.3  497.80
#Mann=7,-1,0
  4522.6    0.05       0  4856.4    0.12       0  4857.8    0.16       0
  4955.8    0.12       0  4978.5    0.07       0  4985.8    0.12       0
  4996.2    0.16       0
Bank Sta=4954.6,5017.5
Exp/Cntr=0.3,0.1

Chan Stop Cuts=-1