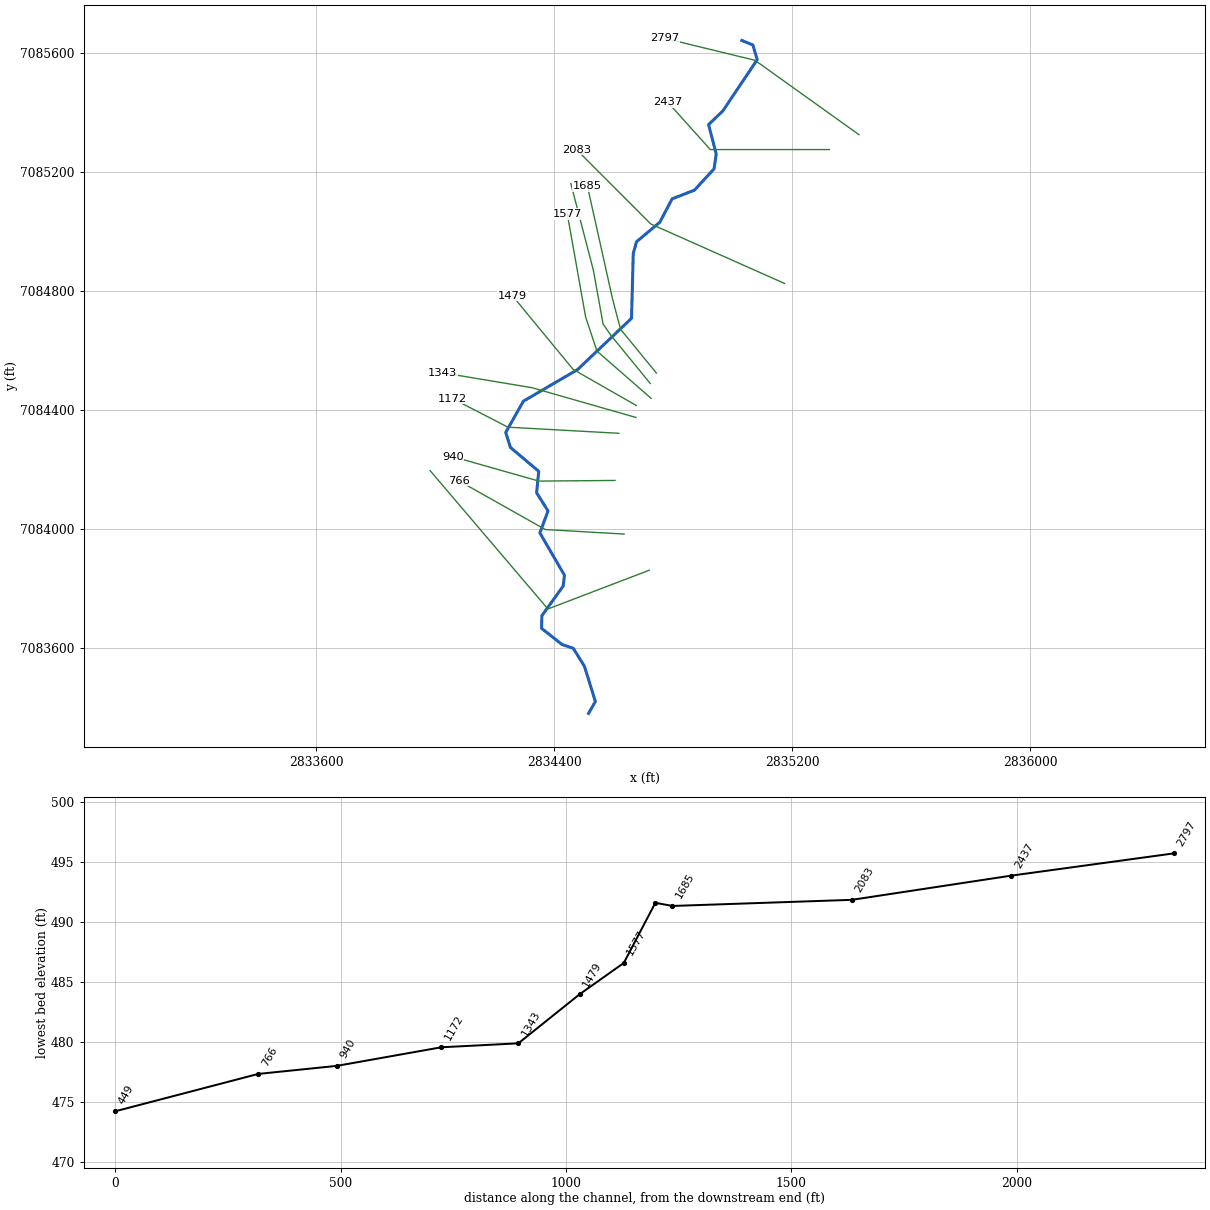
--- UNT 126 in LFCCL Watershed.prj (project) ---

Proj Title=UNT 126 in LFCCL Watershed Base Level Engineering
Current Plan=p01
Default Exp/Contr=0.3,0.1
English Units
Geom File=g01
Flow File=f01
Plan File=p01
BEGIN DESCRIPTION:
UNT 126 in LFCCL Watershed
END DESCRIPTION:

--- UNT 126 in LFCCL Watershed.p01 (plan) ---

Plan Title=Multiple Run
Short Identifier=Multiple
Geom File=g01
Flow File=f01
Subcritical Flow
K Sum by GR= 0
Std Step Tol= 0.01
Critical Tol= 0.01
Num of Std Step Trials= 20
Max Error Tol= 0.3
Flow Tol Ratio= 0.001
Split Flow NTrial= 30
Split Flow Tol= 0.02
Split Flow Ratio= 0.02
Log Output Level= 0
Friction Slope Method= 1
Unsteady Friction Slope Method= 2
Unsteady Bridges Friction Slope Method= 1
Parabolic Critical Depth
Global Vel Dist=  1 , 1 , 1
Global Log Level= 0
CheckData=True
Encroach Param= -1, 0, 0, 0
BEGIN DESCRIPTION:
Multiple Run
END DESCRIPTION:

--- UNT 126 in LFCCL Watershed.f01 (steady flow) ---

Flow Title=Multiple
Number of Profiles=7
Profile Names=10-year,25-year,50-year,1pct_min,100-year,1pct_plu,500-year
River Rch & RM= UNT 126 in LFCCL,Reach-1,2797
     463     605     719     425     848    1691    1173
Boundary for River Rch & Prof#=UNT 126 in LFCCL,Reach-1,1
Up Type=0
Dn Type=3
Dn Slope=0.005
Boundary for River Rch & Prof#=UNT 126 in LFCCL,Reach-1,2
Up Type=0
Dn Type=3
Dn Slope=0.005
Boundary for River Rch & Prof#=UNT 126 in LFCCL,Reach-1,3
Up Type=0
Dn Type=3
Dn Slope=0.005
Boundary for River Rch & Prof#=UNT 126 in LFCCL,Reach-1,4
Up Type=0
Dn Type=3
Dn Slope=0.005
Boundary for River Rch & Prof#=UNT 126 in LFCCL,Reach-1,5
Up Type=0
Dn Type=3
Dn Slope=0.005
Boundary for River Rch & Prof#=UNT 126 in LFCCL,Reach-1,6
Up Type=0
Dn Type=3
Dn Slope=0.005
Boundary for River Rch & Prof#=UNT 126 in LFCCL,Reach-1,7
Up Type=0
Dn Type=3
Dn Slope=0.005

--- UNT 126 in LFCCL Watershed.g01 (geometry) ---

Geom Title=Existing Conditions

River Reach=UNT 126 in LFCCL,Reach-1
Reach XY= 30
      2835031.22      7085641.54      2835067.97      7085626.41
      2835082.80      7085577.12      2834967.15      7085404.75
      2834919.14      7085359.03      2834944.86      7085260.07
      2834937.59      7085210.18      2834871.80      7085138.70
      2834796.72      7085109.59      2834755.06      7085030.81
      2834676.84      7084965.25      2834665.90      7084925.67
      2834660.04      7084708.07      2834478.44      7084535.61
      2834296.47      7084429.62      2834237.13      7084324.81
      2834252.70      7084274.33      2834348.07      7084194.03
      2834340.89      7084121.82      2834379.35      7084060.76
      2834351.86      7083987.11      2834434.49      7083844.87
      2834430.29      7083808.44      2834358.65      7083708.94
      2834357.53      7083666.61      2834425.69      7083612.56
      2834464.43      7083599.11      2834501.88      7083538.64
      2834538.53      7083420.47      2834515.59      7083380.71

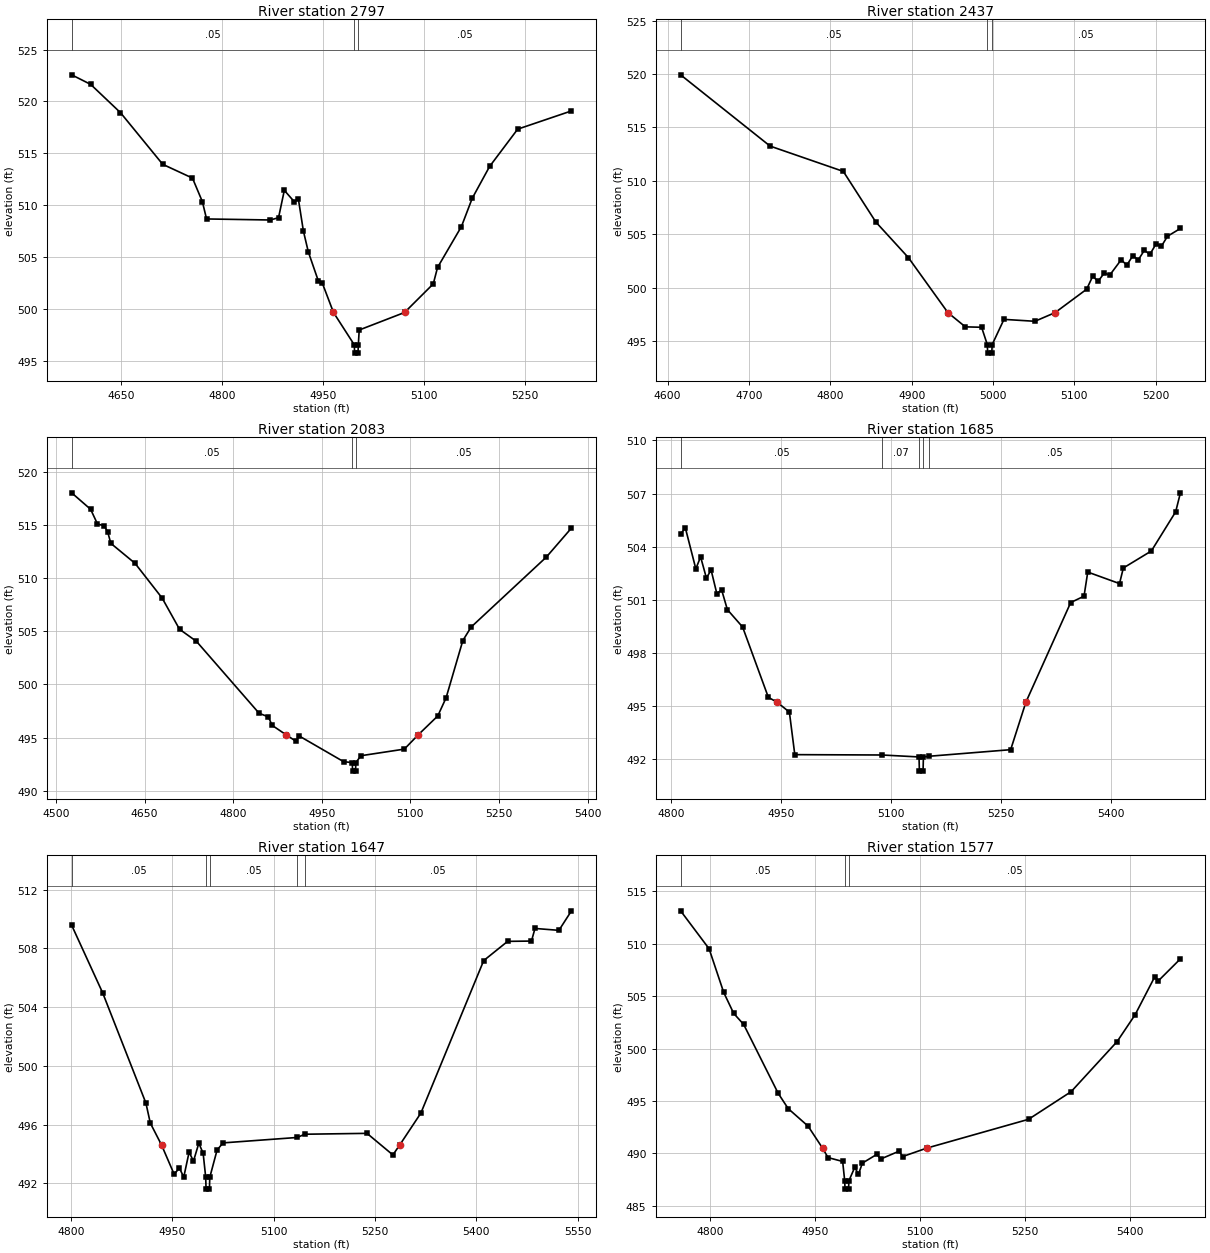
Type RM Length L Ch R = 1,2797,360,360,360
BEGIN DESCRIPTION:
UNT 126 in LFCCL Watershed 7.0
END DESCRIPTION:
XS GIS Cut Line= 3
      2835424.98      7085325.01      2835075.00      7085575.00
      2834771.72      7085648.71
#Sta/Elev= 30
  4576.6  522.56  4604.8  521.64  4649.1  518.91  4711.8  513.93  4756.0  512.60
  4770.7  510.33  4776.9  508.66  4871.5  508.56  4883.8  508.78  4892.4  511.42
  4907.2  510.32  4913.3  510.57  4920.7  507.50  4928.0  505.49  4942.8  502.70
  4948.9  502.46  4965.4  499.64  4996.3  496.52  4996.8  495.72  5001.8  495.72
  5002.3  496.52  5003.6  497.95  5070.9  499.64  5113.6  502.40  5119.9  503.98
  5155.4  507.93  5171.4  510.65  5197.2  513.72  5238.9  517.32  5318.8  519.08
#Mann=3,-1,0
  4576.6    0.05       0  4996.3    0.03       0  5002.3    0.05       0
Bank Sta=4965.4,5070.9
Exp/Cntr=0.3,0.1

Type RM Length L Ch R = 1,2437,354,354,354
BEGIN DESCRIPTION:
UNT 126 in LFCCL Watershed 6.0
END DESCRIPTION:
XS GIS Cut Line= 3
      2835325.02      7085275.00      2834925.00      7085275.00
      2834781.77      7085434.51
#Sta/Elev= 30
  4616.0  519.92  4726.0  513.25  4816.0  510.88  4856.0  506.14  4896.0  502.81
  4944.6  497.66  4966.0  496.33  4986.0  496.29  4993.0  494.67  4993.5  493.87
  4998.5  493.87  4999.0  494.67  5013.5  497.03  5051.5  496.85  5076.3  497.66
  5115.1  499.85  5122.5  501.05  5129.3  500.60  5136.8  501.37  5143.5  501.17
  5157.7  502.62  5164.4  502.09  5171.9  502.99  5178.6  502.60  5186.1  503.50
  5192.8  503.11  5200.3  504.07  5207.0  503.87  5214.5  504.81  5230.4  505.54
#Mann=3,-1,0
  4616.0    0.05       0  4993.0    0.03       0  4999.0    0.05       0
Bank Sta=4944.6,5076.3
Exp/Cntr=0.3,0.1

Type RM Length L Ch R = 1,2083,398,398,398
BEGIN DESCRIPTION:
UNT 126 in LFCCL Watershed 5.0
END DESCRIPTION:
XS GIS Cut Line= 3
      2835174.96      7084825.02      2834725.00      7085025.00
      2834474.97      7085275.03
#Sta/Elev= 30
  4526.6  518.02  4558.7  516.47  4570.3  515.09  4581.3  514.93  4587.4  514.38
  4592.9  513.27  4633.9  511.39  4679.8  508.12  4709.2  505.19  4737.9  504.05
  4843.9  497.29  4859.6  496.95  4865.8  496.16  4889.5  495.27  4906.2  494.66
  4911.6  495.16  4986.9  492.74  5001.6  492.65  5002.1  491.85  5007.1  491.85
  5007.6  492.65  5016.3  493.30  5089.7  493.92  5113.3  495.27  5146.3  497.04
  5160.4  498.75  5188.7  504.13  5202.8  505.40  5330.1  511.98  5372.6  514.71
#Mann=3,-1,0
  4526.6    0.05       0  5001.6    0.03       0  5007.6    0.05       0
Bank Sta=4889.5,5113.3
Exp/Cntr=0.3,0.1

Type RM Length L Ch R = 1,1685,38,38,38
BEGIN DESCRIPTION:
XS3805A
END DESCRIPTION:
XS GIS Cut Line= 4
      2834743.58      7084524.33      2834623.19      7084671.15
      2834596.77      7084770.97      2834511.93      7085151.30
#Sta/Elev= 30
  4812.6  504.72  4819.1  505.06  4833.4  502.75  4839.9  503.43  4847.8  502.24
  4854.3  502.68  4862.1  501.35  4868.6  501.57  4876.5  500.45  4897.3  499.47
  4932.5  495.50  4944.4  495.23  4961.2  494.67  4968.6  492.27  5087.8  492.25
  5138.3  492.14  5138.8  491.34  5143.8  491.34  5144.3  492.14  5152.3  492.18
  5263.5  492.55  5284.3  495.23  5345.5  500.85  5363.7  501.21  5368.8  502.57
  5412.2  501.92  5417.4  502.80  5455.7  503.76  5488.9  505.97  5495.4  507.04
#Mann=5,-1,0
  4812.6    0.05       0  5087.8    0.07       0  5138.3    0.03       0
  5144.3    0.07       0  5152.3    0.05       0
Bank Sta=4944.4,5284.3
Exp/Cntr=0.3,0.1

Type RM Length L Ch R = 1,1647,70,70,70
BEGIN DESCRIPTION:
XS3806A
END DESCRIPTION:
XS GIS Cut Line= 5
      2834723.03      7084489.10      2834590.90      7084650.59
      2834564.47      7084688.76      2834532.17      7084867.87
      2834456.02      7085160.75
#Sta/Elev= 30
  4801.2  509.58  4847.2  504.96  4911.1  497.46  4917.6  496.10  4934.3  494.60
  4952.8  492.62  4960.7  493.03  4967.1  492.42  4975.0  494.12  4981.5  493.51
  4989.4  494.73  4995.8  494.04  4999.6  492.40  5000.1  491.60  5005.1  491.60
  5005.6  492.40  5016.4  494.26  5025.2  494.75  5135.2  495.12  5146.0  495.34
  5238.3  495.40  5276.6  493.93  5286.6  494.60  5318.0  496.78  5411.0  507.17
  5446.4  508.48  5481.7  508.50  5486.9  509.36  5522.3  509.23  5540.9  510.56
#Mann=5,-1,0
  4801.2    0.05       0  4999.6    0.03       0  5005.6    0.05       0
  5135.2    0.07       0  5146.0    0.05       0
Bank Sta=4934.3,5286.6
Exp/Cntr=0.3,0.1

Type RM Length L Ch R = 1,1577,98,98,98
BEGIN DESCRIPTION:
XS3807A
END DESCRIPTION:
XS GIS Cut Line= 4
      2834725.98      7084439.17      2834543.92      7084597.74
      2834505.75      7084712.25      2834444.10      7085058.67
#Sta/Elev= 30
  4757.5  513.14  4798.2  509.52  4819.1  505.35  4833.3  503.36  4847.6  502.30
  4896.9  495.73  4911.2  494.27  4939.6  492.60  4960.3  490.50  4968.1  489.60
  4989.0  489.23  4991.9  487.39  4992.4  486.59  4997.4  486.59  4997.9  487.39
  5006.3  488.67  5011.6  488.00  5017.1  489.07  5037.9  489.91  5043.2  489.46
  5069.6  490.21  5074.8  489.70  5109.0  490.50  5254.5  493.25  5315.4  495.89
  5381.1  500.67  5406.8  503.23  5435.0  506.87  5440.1  506.47  5471.5  508.56
#Mann=3,-1,0
  4757.5    0.05       0  4991.9    0.03       0  4997.9    0.05       0
Bank Sta=4960.3,5109
Exp/Cntr=0.3,0.1

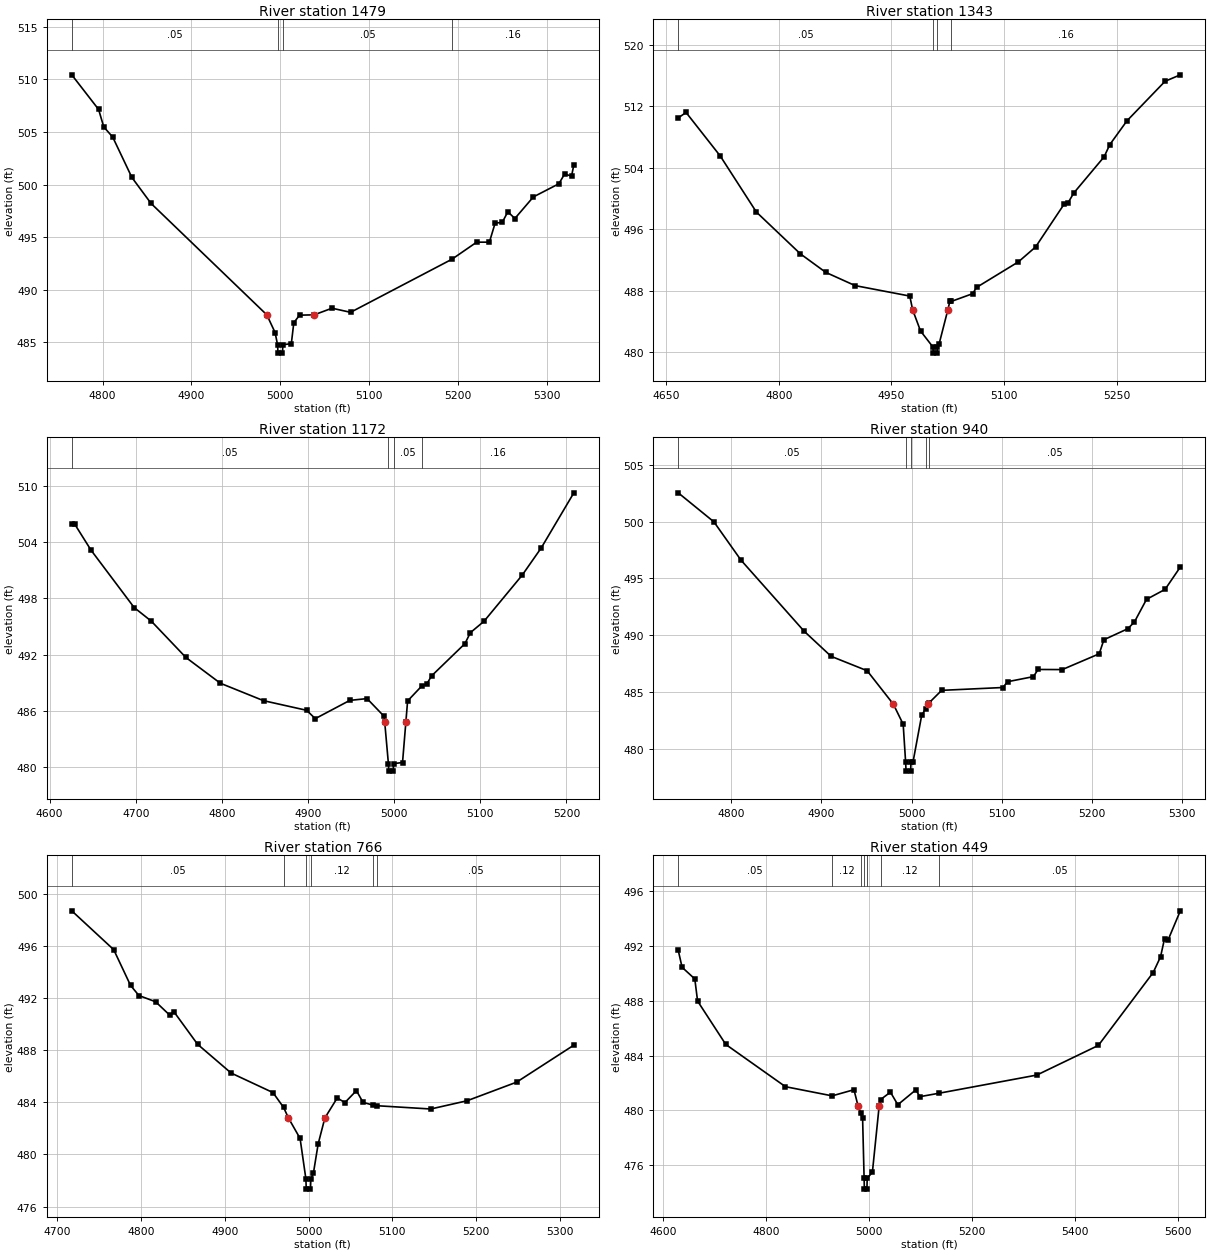
Type RM Length L Ch R = 1,1479,136,136,136
BEGIN DESCRIPTION:
XS3811A
END DESCRIPTION:
XS GIS Cut Line= 3
      2834676.28      7084415.02      2834463.57      7084536.57
      2834259.80      7084783.70
#Sta/Elev= 30
  4765.2  510.44  4795.4  507.15  4801.2  505.49  4811.3  504.52  4832.9  500.68
  4854.5  498.21  4984.8  487.62  4994.1  485.94  4996.9  484.78  4997.4  483.98
  5002.4  483.98  5002.9  484.78  5012.4  484.88  5015.2  486.87  5021.7  487.59
  5038.1  487.62  5058.2  488.25  5079.1  487.86  5193.3  492.91  5221.1  494.53
  5235.4  494.53  5241.9  496.35  5249.8  496.40  5256.2  497.42  5264.1  496.78
  5284.9  498.83  5313.6  500.08  5320.1  501.01  5327.9  500.81  5330.5  501.88
#Mann=4,-1,0
  4765.2    0.05       0  4996.9    0.03       0  5002.9    0.05       0
  5193.3    0.16       0
Bank Sta=4984.8,5038.1
Exp/Cntr=0.3,0.1

Type RM Length L Ch R = 1,1343,171,171,171
BEGIN DESCRIPTION:
UNT 126 in LFCCL Watershed 3.0
END DESCRIPTION:
XS GIS Cut Line= 3
      2834674.95      7084375.01      2834325.00      7084475.00
      2834025.00      7084525.00
#Sta/Elev= 30
  4666.3  510.47  4676.7  511.18  4722.2  505.52  4770.3  498.23  4828.8  492.80
  4862.6  490.39  4901.6  488.67  4974.4  487.31  4978.2  485.53  4988.7  482.77
  5005.2  480.69  5005.7  479.89  5010.7  479.89  5011.2  480.69  5013.4  481.07
  5025.1  485.53  5027.7  486.61  5029.6  486.61  5058.1  487.62  5063.2  488.43
  5119.0  491.76  5141.8  493.69  5179.8  499.26  5184.9  499.41  5192.5  500.69
  5233.0  505.41  5240.6  507.00  5263.4  510.09  5314.1  515.23  5334.4  516.07
#Mann=4,-1,0
  4666.3    0.05       0  5005.2    0.03       0  5011.2    0.05       0
  5029.6    0.16       0
Bank Sta=4978.2,5025.1
Exp/Cntr=0.3,0.1

Type RM Length L Ch R = 1,1172,232,232,232
BEGIN DESCRIPTION:
XS3808A
END DESCRIPTION:
XS GIS Cut Line= 3
      2834617.29      7084321.75      2834244.43      7084342.30
      2834058.24      7084438.30
#Sta/Elev= 30
  4625.7  505.89  4629.3  505.89  4648.0  503.15  4698.1  497.02  4718.1  495.56
  4758.2  491.69  4798.2  488.94  4848.3  487.08  4898.4  486.05  4908.4  485.16
  4948.5  487.11  4968.5  487.30  4988.5  485.39  4989.0  484.82  4993.3  480.36
  4993.8  479.56  4998.8  479.56  4999.3  480.36  5009.7  480.48  5013.6  484.82
  5015.6  487.05  5032.4  488.68  5037.8  488.85  5043.5  489.73  5082.1  493.16
  5088.5  494.34  5104.3  495.55  5148.6  500.47  5170.8  503.39  5208.6  509.26
#Mann=4,-1,0
  4625.7    0.05       0  4993.3    0.03       0  4999.3    0.05       0
  5032.4    0.16       0
Bank Sta=4989,5013.6
Exp/Cntr=0.3,0.1

Type RM Length L Ch R = 1,940,174,174,174
BEGIN DESCRIPTION:
XS3810A
END DESCRIPTION:
XS GIS Cut Line= 3
      2834604.59      7084163.31      2834348.55      7084161.14
      2834058.92      7084243.27
#Sta/Elev= 30
  4741.1  502.54  4780.7  499.98  4810.7  496.61  4880.7  490.35  4910.7  488.13
  4950.7  486.86  4979.8  483.91  4990.7  482.14  4993.4  478.81  4993.9  478.01
  4998.9  478.01  4999.4  478.81  5001.6  478.81  5011.2  482.92  5015.6  483.52
  5018.5  483.91  5019.2  484.01  5033.4  485.13  5101.3  485.38  5106.5  485.89
  5135.2  486.34  5140.4  486.97  5167.2  486.96  5208.2  488.35  5213.4  489.59
  5239.9  490.56  5247.3  491.16  5260.7  493.15  5281.3  494.03  5298.2  496.00
#Mann=5,-1,0
  4741.1    0.05       0  4993.4    0.03       0  4999.4    0.05       0
  5015.6    0.07       0  5019.2    0.05       0
Bank Sta=4979.8,5018.5
Exp/Cntr=0.3,0.1

Type RM Length L Ch R = 1,766,317,317,317
BEGIN DESCRIPTION:
XS3809A
END DESCRIPTION:
XS GIS Cut Line= 3
      2834635.04      7083983.18      2834370.25      7083998.38
      2834078.62      7084162.56
#Sta/Elev= 30
  4717.1  498.70  4767.2  495.72  4787.3  492.98  4797.3  492.20  4817.3  491.72
  4834.2  490.69  4839.2  490.95  4867.4  488.46  4907.5  486.25  4957.5  484.75
  4970.2  483.61  4976.0  482.80  4989.9  481.23  4996.8  478.14  4997.3  477.34
  5002.3  477.34  5002.8  478.14  5005.8  478.56  5011.5  480.81  5019.5  482.80
  5034.3  484.34  5043.4  483.98  5057.2  484.90  5065.1  484.00  5076.9  483.79
  5082.2  483.74  5146.0  483.49  5189.3  484.12  5248.6  485.55  5317.0  488.39
#Mann=6,-1,0
  4717.1    0.05       0  4970.2    0.12       0  4996.8    0.07       0
  5002.8    0.12       0  5076.9    0.07       0  5082.2    0.05       0
Bank Sta=4976,5019.5
Exp/Cntr=0.3,0.1

Type RM Length L Ch R = 1,449,0,0,0
BEGIN DESCRIPTION:
UNT 126 in LFCCL Watershed 1.0
END DESCRIPTION:
XS GIS Cut Line= 3
      2834719.69      7083861.67      2834378.93      7083731.45
      2833982.70      7084196.43
#Sta/Elev= 30
  4628.8  491.69  4636.3  490.45  4661.0  489.60  4666.4  487.98  4721.2  484.81
  4837.2  481.72  4927.9  481.05  4970.3  481.50  4978.2  480.32  4983.3  479.79
  4987.1  479.40  4990.0  475.03  4990.5  474.23  4995.5  474.23  4996.0  475.03
  5006.1  475.46  5019.3  480.32  5022.0  480.78  5041.2  481.32  5055.5  480.40
  5090.6  481.49  5098.3  480.99  5135.3  481.24  5325.6  482.57  5445.3  484.74
  5551.8  490.07  5566.1  491.22  5573.8  492.54  5580.4  492.42  5604.5  494.58
#Mann=7,-1,0
  4628.8    0.05       0  4927.9    0.12       0  4983.3    0.07       0
  4990.0    0.07       0  4996.0    0.07       0  5022.0    0.12       0
  5135.3    0.05       0
Bank Sta=4978.2,5019.3
Exp/Cntr=0.3,0.1

Chan Stop Cuts=-1