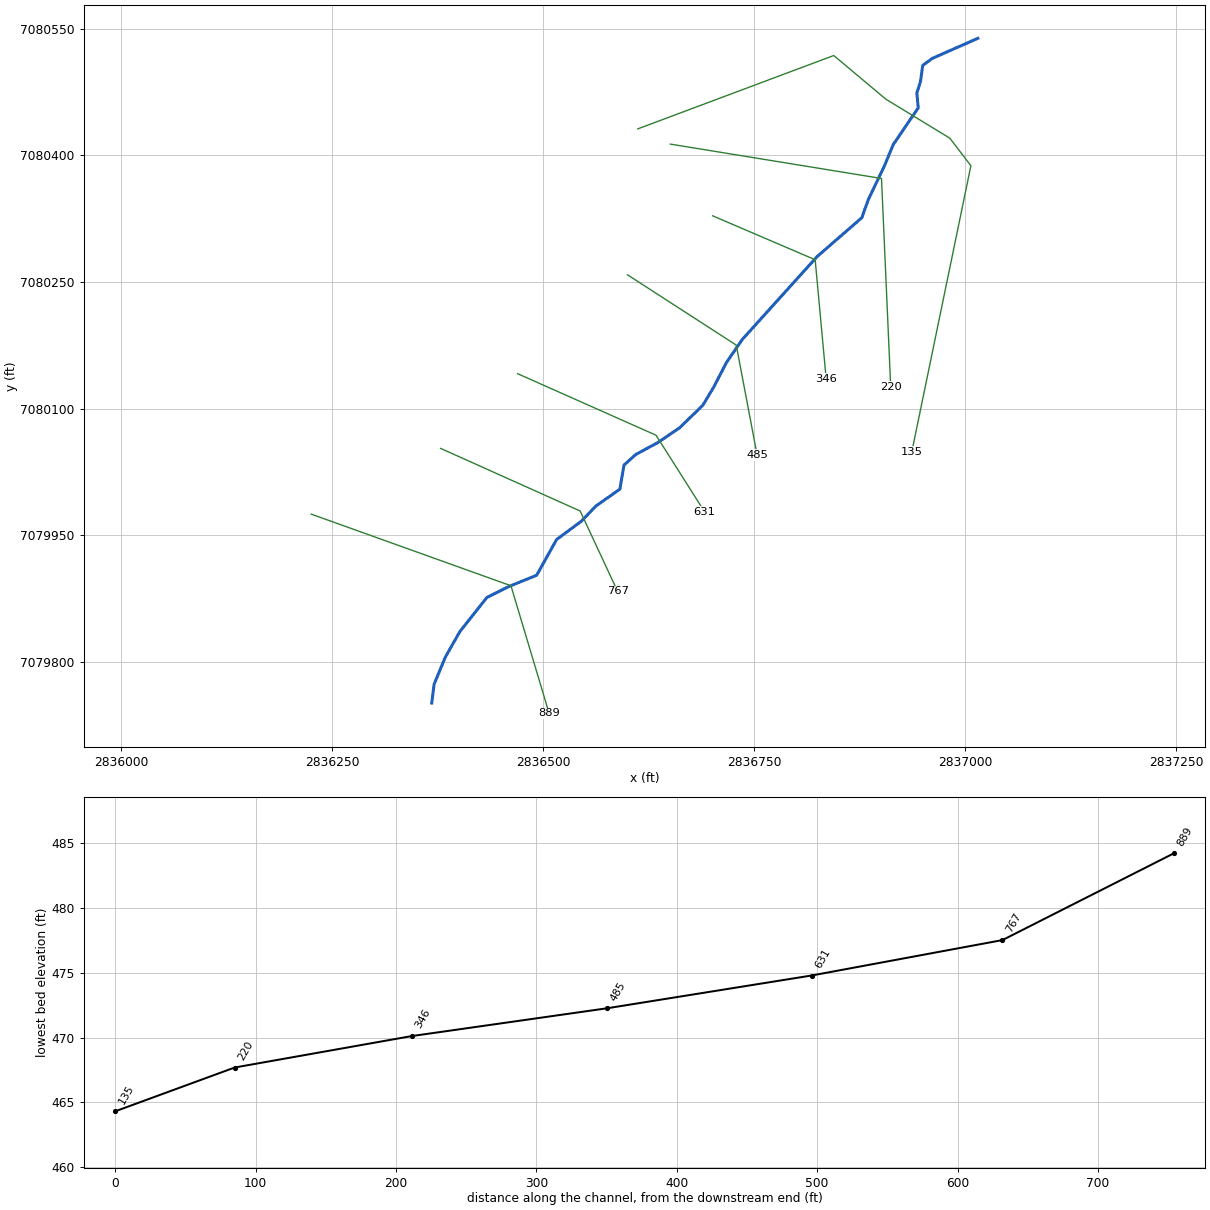
--- UNT 127 in LFCCL Watershed.prj (project) ---

Proj Title=UNT 127 in LFCCL Watershed Base Level Engineering
Current Plan=p01
Default Exp/Contr=0.3,0.1
English Units
Geom File=g01
Flow File=f01
Plan File=p01
Y Axis Title=Elevation
X Axis Title(PF)=Main Channel Distance
X Axis Title(XS)=Station
BEGIN DESCRIPTION:
UNT 127 in LFCCL Watershed
END DESCRIPTION:
DSS Export Rating Curves= 0
DSS Export Rating Curve Sorted= 0
DSS Export Volume Flow Curves= 0
DXF OffsetX= 0
DXF OffsetY= 0
DXF ScaleX= 1
DXF ScaleY= 10

--- UNT 127 in LFCCL Watershed.p01 (plan) ---

Plan Title=Multiple Run
Short Identifier=Multiple
Geom File=g01
Flow File=f01
Subcritical Flow
K Sum by GR= 0
Std Step Tol= 0.01
Critical Tol= 0.01
Num of Std Step Trials= 20
Max Error Tol= 0.3
Flow Tol Ratio= 0.001
Split Flow NTrial= 30
Split Flow Tol= 0.02
Split Flow Ratio= 0.02
Log Output Level= 0
Friction Slope Method= 1
Unsteady Friction Slope Method= 2
Unsteady Bridges Friction Slope Method= 1
Parabolic Critical Depth
Global Vel Dist=  1 , 1 , 1
Global Log Level= 0
CheckData=True
Encroach Param= -1, 0, 0, 0
BEGIN DESCRIPTION:
Multiple Run
END DESCRIPTION:

--- UNT 127 in LFCCL Watershed.f01 (steady flow) ---

Flow Title=Multiple
Number of Profiles=7
Profile Names=10-year,25-year,50-year,1pct_min,100-year,1pct_plu,500-year
River Rch & RM= UNT 127 in LFCCL,Reach-1,889
      71      81      87      47      94     188     109
Boundary for River Rch & Prof#=UNT 127 in LFCCL,Reach-1,1
Up Type=0
Dn Type=3
Dn Slope=0.005
Boundary for River Rch & Prof#=UNT 127 in LFCCL,Reach-1,2
Up Type=0
Dn Type=3
Dn Slope=0.005
Boundary for River Rch & Prof#=UNT 127 in LFCCL,Reach-1,3
Up Type=0
Dn Type=3
Dn Slope=0.005
Boundary for River Rch & Prof#=UNT 127 in LFCCL,Reach-1,4
Up Type=0
Dn Type=3
Dn Slope=0.005
Boundary for River Rch & Prof#=UNT 127 in LFCCL,Reach-1,5
Up Type=0
Dn Type=3
Dn Slope=0.005
Boundary for River Rch & Prof#=UNT 127 in LFCCL,Reach-1,6
Up Type=0
Dn Type=3
Dn Slope=0.005
Boundary for River Rch & Prof#=UNT 127 in LFCCL,Reach-1,7
Up Type=0
Dn Type=3
Dn Slope=0.005

--- UNT 127 in LFCCL Watershed.g01 (geometry) ---

Geom Title=Existing Conditions
Program Version=5.07

River Reach=UNT 127 in LFCCL,Reach-1
Reach XY= 30
      2836367.77      7079751.18      2836370.55       7079773.4
      2836383.75      7079805.34      2836401.11       7079835.9
      2836433.05      7079876.18      2836459.44      7079889.37
      2836492.08      7079902.57      2836515.69      7079944.93
      2836544.86      7079966.45      2836562.22      7079984.51
      2836590.69      7080004.65      2836595.55      7080033.12
      2836609.44      7080045.62      2836635.14      7080059.51
      2836661.18      7080077.04      2836688.95      7080103.95
      2836701.98      7080125.66      2836716.73       7080154.3
      2836735.83      7080182.08      2836824.37      7080280.17
      2836877.32      7080326.18      2836885.14      7080347.88
      2836904.23      7080387.81      2836914.65      7080412.98
      2836944.16      7080456.38      2836942.57      7080474.18
      2836946.91      7080487.63      2836949.52      7080506.73
       2836960.8      7080514.98      2837014.79      7080538.78

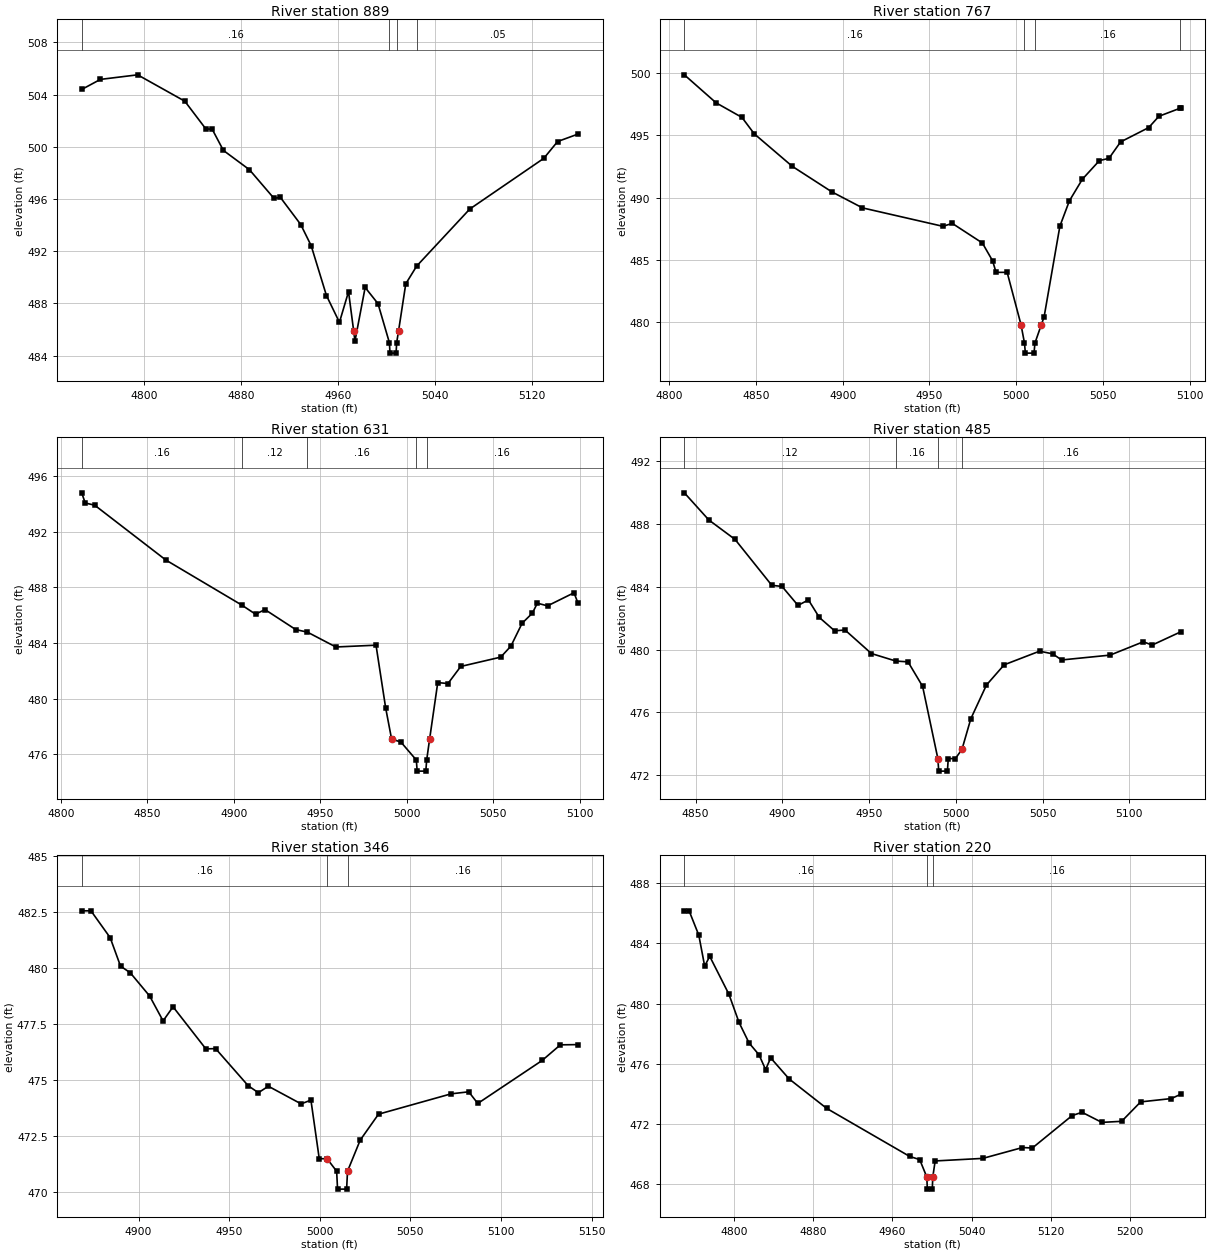
Type RM Length L Ch R = 1 ,889     ,122,122,122
BEGIN DESCRIPTION:
UNT 127 in LFCCL Watershed 1.0
END DESCRIPTION:
XS GIS Cut Line= 3
      2836225.02      7079974.99      2836461.63      7079890.13
      2836506.86      7079738.92
#Sta/Elev= 30
  4748.8  504.39  4764.2  505.16  4794.9  505.51  4833.8  503.49  4851.1  501.37
  4856.4  501.34  4865.6  499.72  4887.1  498.24  4907.3  496.05  4912.6  496.12
  4929.4  494.04    4938  492.42  4950.6   488.6  4961.3  486.55  4968.8   488.9
    4973  485.92  4974.1  485.11  4982.5  489.22  4993.1  487.98  5002.5  484.99
    5003  484.19    5008  484.19  5008.5  484.99  5010.1  485.92    5016   489.5
    5025  490.86  5068.8  495.23  5129.8  499.11  5141.2   500.4    5158  500.97
#Mann= 4 ,-1 , 0
  4748.8     .16       0  5002.5     .07       0  5008.5     .16       0
    5025     .05       0
Bank Sta=4973,5010.1
XS Rating Curve= 0 ,0
Exp/Cntr=0.3,0.1

Type RM Length L Ch R = 1 ,767     ,136,136,136
BEGIN DESCRIPTION:
XS3812A
END DESCRIPTION:
XS GIS Cut Line= 3
      2836378.26      7080052.91      2836543.66      7079978.68
      2836587.91      7079883.67
#Sta/Elev= 30
  4808.7  499.87    4827  497.62  4841.9  496.45    4849  495.13  4870.9  492.52
  4893.7  490.47  4911.4  489.18  4957.7   487.7  4963.2  487.93  4980.5  486.36
  4986.4  484.93  4988.4     484  4994.8     484  5002.8  479.79  5004.8  478.31
  5005.3  477.51  5010.3  477.51  5010.8  478.31  5014.5  479.79  5016.1  480.42
  5025.2  487.71  5030.7  489.75  5038.2  491.49    5048  492.98  5053.5  493.16
  5060.2  494.48  5076.4  495.63  5082.3  496.54  5094.4  497.18  5094.8  497.18
#Mann= 4 ,-1 , 0
  4808.7     .16       0  5004.8     .07       0  5010.8     .16       0
  5094.4     .05       0
Bank Sta=5002.8,5014.5
XS Rating Curve= 0 ,0
Exp/Cntr=0.3,0.1

Type RM Length L Ch R = 1 ,631     ,146,146,146
BEGIN DESCRIPTION:
XS3813A
END DESCRIPTION:
XS GIS Cut Line= 3
      2836469.46      7080141.43       2836633.5      7080068.52
      2836691.05      7079977.73
#Sta/Elev= 30
  4812.1   494.8  4814.1  494.07  4819.6  493.91  4860.7  489.97  4904.6  486.73
  4912.6  486.07  4918.1   486.4  4935.9  484.96  4942.6  484.78  4959.1  483.71
  4982.3  483.84  4987.9  479.31  4991.3  477.09  4996.7  476.87  5005.6  475.58
  5006.1  474.78  5011.1  474.78  5011.6  475.58  5013.3  477.09    5018  481.15
  5023.9  481.08  5031.3  482.31  5054.4  482.98  5060.3  483.77  5066.8  485.42
  5072.7  486.14  5075.6  486.86  5081.5  486.67  5096.8  487.61  5099.1  486.87
#Mann= 5 ,-1 , 0
  4812.1     .16       0  4904.6     .12       0  4942.6     .16       0
  5005.6     .07       0  5011.6     .16       0
Bank Sta=4991.3,5013.3
XS Rating Curve= 0 ,0
Exp/Cntr=0.3,0.1

Type RM Length L Ch R = 1 ,485     ,139,139,139
BEGIN DESCRIPTION:
XS3814A
END DESCRIPTION:
XS GIS Cut Line= 3
      2836599.67      7080258.61      2836728.56      7080175.29
      2836753.29       7080045.1
#Sta/Elev= 30
  4843.5     490  4857.6  488.27  4872.7  487.03  4893.9   484.1  4899.8  484.03
    4909  482.82    4915  483.17  4921.3  482.05  4930.1   481.2  4936.1  481.25
  4951.3  479.75  4965.4  479.27  4972.4  479.22  4980.8  477.66  4989.6  473.05
  4990.1  472.25  4995.1  472.25  4995.6  473.05  4999.7  473.05  5003.5  473.64
  5008.6  475.59  5017.6  477.74  5027.8  479.03  5048.2   479.9  5055.8  479.73
  5060.9  479.34  5088.9  479.65    5108   480.5  5113.1  480.29  5129.5  481.13
#Mann= 4 ,-1 , 0
  4843.5     .12       0  4965.4     .16       0  4989.6     .07       0
  5003.5     .16       0
Bank Sta=4989.6,5003.5
XS Rating Curve= 0 ,0
Exp/Cntr=0.3,0.1

Type RM Length L Ch R = 1 ,346     ,126,126,126
BEGIN DESCRIPTION:
XS3815A
END DESCRIPTION:
XS GIS Cut Line= 3
      2836700.56       7080328.5      2836822.09      7080276.42
      2836835.11      7080135.33
#Sta/Elev= 29
  4868.6  482.55  4873.7  482.55  4884.3  481.35    4890  480.08  4895.4  479.78
  4906.1  478.74  4913.5  477.63    4919  478.26  4937.1  476.38  4942.5  476.39
  4960.5  474.73  4966.1  474.42  4971.6  474.71  4989.7  473.92  4995.1  474.09
  4999.7  471.47    5004  471.47  5009.3  470.91  5009.8  470.11  5014.8  470.11
  5015.3  470.91  5022.3   472.3  5032.4  473.46  5072.5  474.37  5082.2  474.46
  5087.2  473.94  5122.7  475.86  5132.8  476.56  5142.5  476.57
#Mann= 3 , 0 , 0
  4868.6     .16       0    5004     .03       0  5015.3     .16       0
Bank Sta=5004,5015.3
XS Rating Curve= 0 ,0
Exp/Cntr=0.3,0.1

Type RM Length L Ch R = 1 ,220     ,85,85,85
BEGIN DESCRIPTION:
Mapping XS 744e5edd
END DESCRIPTION:
XS GIS Cut Line= 3
      2836650.56      7080413.43      2836900.68      7080372.73
       2836911.6      7080125.58
#Sta/Elev= 30
    4750  486.16  4754.8  486.16  4764.6  484.54  4770.5  482.49  4775.6  483.14
    4795  480.62  4805.2  478.75  4815.3  477.39  4825.4   476.6    4832  475.62
  4837.1   476.4  4855.8     475  4893.6  473.05  4977.4  469.86  4987.5  469.65
  4994.7  468.49  4995.2  467.69  5000.2  467.69  5000.7  468.49  5003.1  469.56
  5051.2  469.73  5091.2  470.45  5101.2  470.42  5141.3  472.57  5151.3  472.79
  5171.3  472.12  5191.3  472.19  5210.5  473.48  5241.4   473.7  5250.8  473.98
#Mann= 3 ,-1 , 0
    4750     .16       0  4994.7     .03       0  5000.7     .16       0
Bank Sta=4994.7,5000.7
XS Rating Curve= 0 ,0
Exp/Cntr=0.3,0.1

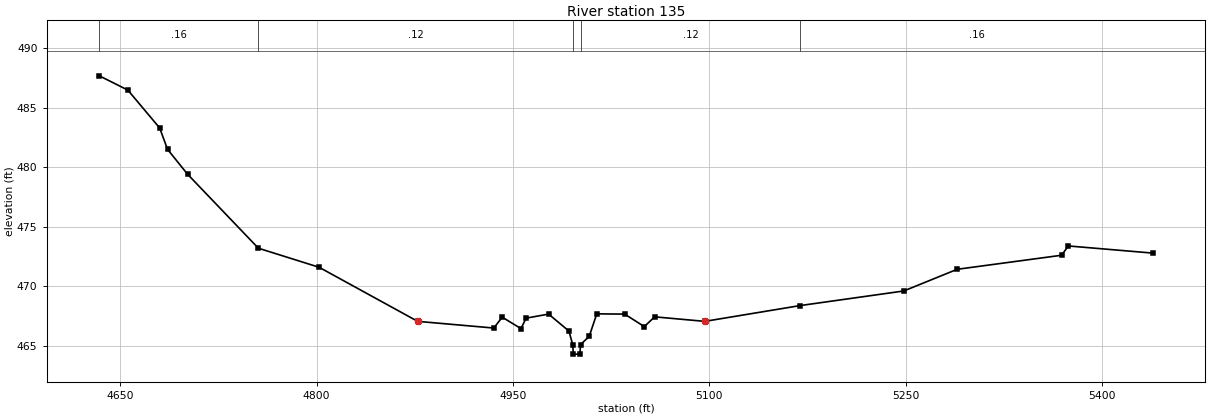
Type RM Length L Ch R = 1 ,135     ,0,0,0
BEGIN DESCRIPTION:
UNT 127 in LFCCL Watershed 0.0
END DESCRIPTION:
XS GIS Cut Line= 6
      2836611.86      7080431.48       2836844.1      7080518.41
      2836905.91      7080466.65       2836981.6      7080420.49
       2837006.6      7080387.85      2836936.56      7080048.68
#Sta/Elev= 30
  4634.1  487.68  4655.9  486.48  4680.2   483.3  4686.2  481.51  4701.5  479.42
  4755.6  473.21    4802  471.61  4877.3  467.07  4935.4  466.51  4941.9  467.42
  4956.2  466.46  4960.1  467.34  4977.3  467.68  4992.8  466.26  4995.7  465.12
  4996.2  464.32  5001.2  464.32  5001.7  465.12  5008.3  465.81  5014.1   467.7
  5035.4  467.68  5050.4  466.63  5058.3  467.45  5096.6  467.07  5169.7   468.4
  5248.6  469.62  5289.4  471.44  5369.2  472.62  5374.3   473.4  5438.8   472.8
#Mann= 5 ,-1 , 0
  4634.1     .16       0  4755.6     .12       0  4995.7     .07       0
  5001.7     .12       0  5169.7     .16       0
Bank Sta=4877.3,5096.6
XS Rating Curve= 0 ,0
Exp/Cntr=0.3,0.1
LCMann Table=0

Chan Stop Cuts=-1
Use User Specified Reach Order=0
Composite Channel Slope=5