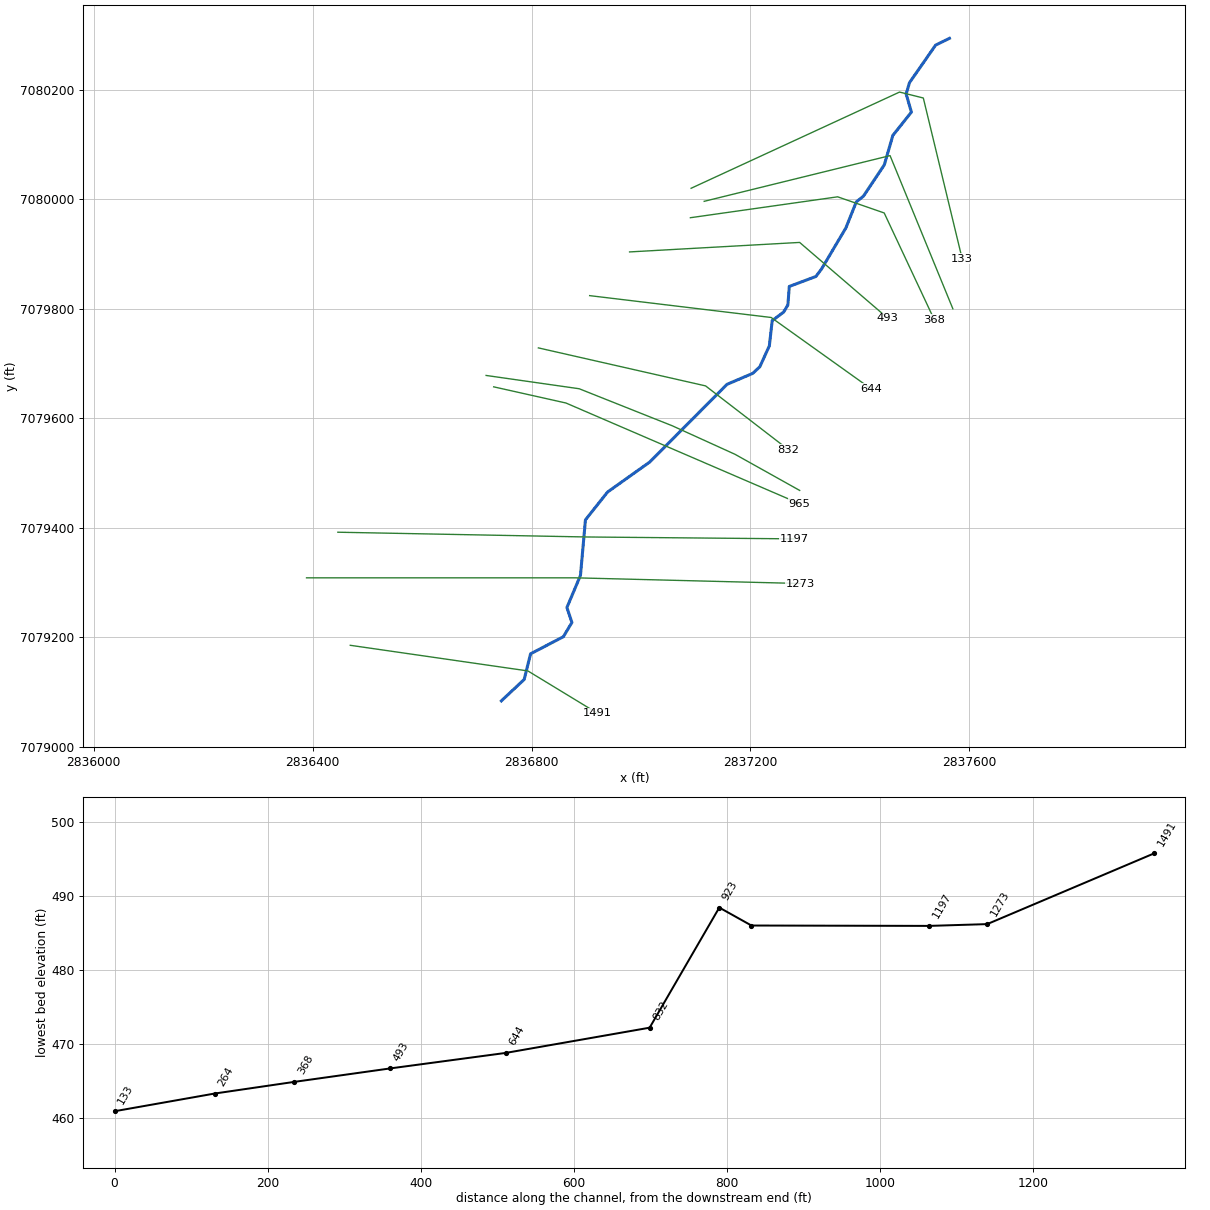
--- UNT 128 in LFCCL Watershed.prj (project) ---

Proj Title=UNT 128 in LFCCL Watershed Base Level Engineering
Current Plan=p01
Default Exp/Contr=0.3,0.1
English Units
Geom File=g01
Flow File=f01
Plan File=p01
BEGIN DESCRIPTION:
UNT 128 in LFCCL Watershed
END DESCRIPTION:

--- UNT 128 in LFCCL Watershed.p01 (plan) ---

Plan Title=Multiple Run
Short Identifier=Multiple
Geom File=g01
Flow File=f01
Subcritical Flow
K Sum by GR= 0
Std Step Tol= 0.01
Critical Tol= 0.01
Num of Std Step Trials= 20
Max Error Tol= 0.3
Flow Tol Ratio= 0.001
Split Flow NTrial= 30
Split Flow Tol= 0.02
Split Flow Ratio= 0.02
Log Output Level= 0
Friction Slope Method= 1
Unsteady Friction Slope Method= 2
Unsteady Bridges Friction Slope Method= 1
Parabolic Critical Depth
Global Vel Dist=  1 , 1 , 1
Global Log Level= 0
CheckData=True
Encroach Param= -1, 0, 0, 0
BEGIN DESCRIPTION:
Multiple Run
END DESCRIPTION:

--- UNT 128 in LFCCL Watershed.f01 (steady flow) ---

Flow Title=Multiple
Number of Profiles=7
Profile Names=10-year,25-year,50-year,1pct_min,100-year,1pct_plu,500-year
River Rch & RM= UNT 128 in LFCCL,Reach-1,1491
     110     129     143      80     159     318     194
Boundary for River Rch & Prof#=UNT 128 in LFCCL,Reach-1,1
Up Type=0
Dn Type=3
Dn Slope=0.005
Boundary for River Rch & Prof#=UNT 128 in LFCCL,Reach-1,2
Up Type=0
Dn Type=3
Dn Slope=0.005
Boundary for River Rch & Prof#=UNT 128 in LFCCL,Reach-1,3
Up Type=0
Dn Type=3
Dn Slope=0.005
Boundary for River Rch & Prof#=UNT 128 in LFCCL,Reach-1,4
Up Type=0
Dn Type=3
Dn Slope=0.005
Boundary for River Rch & Prof#=UNT 128 in LFCCL,Reach-1,5
Up Type=0
Dn Type=3
Dn Slope=0.005
Boundary for River Rch & Prof#=UNT 128 in LFCCL,Reach-1,6
Up Type=0
Dn Type=3
Dn Slope=0.005
Boundary for River Rch & Prof#=UNT 128 in LFCCL,Reach-1,7
Up Type=0
Dn Type=3
Dn Slope=0.005

--- UNT 128 in LFCCL Watershed.g01 (geometry) ---

Geom Title=Existing Conditions

River Reach=UNT 128 in LFCCL,Reach-1
Reach XY= 30
      2836744.91      7079083.46      2836786.58      7079122.52
      2836798.30      7079169.40      2836858.20      7079200.65
      2836873.82      7079226.69      2836864.71      7079254.03
      2836889.45      7079312.63      2836898.56      7079414.19
      2836938.92      7079464.97      2837015.75      7079519.66
      2837157.33      7079661.85      2837204.20      7079681.81
      2837217.22      7079693.96      2837234.58      7079732.16
      2837239.79      7079778.17      2837260.63      7079793.79
      2837268.44      7079806.81      2837271.04      7079840.67
      2837319.65      7079858.89      2837330.07      7079872.78
      2837374.34      7079947.44      2837393.44      7079995.18
      2837406.46      7080005.60      2837444.65      7080062.89
      2837460.28      7080116.71      2837494.13      7080159.24
      2837484.58      7080192.23      2837490.66      7080213.06
      2837538.40      7080281.64      2837563.62      7080294.02

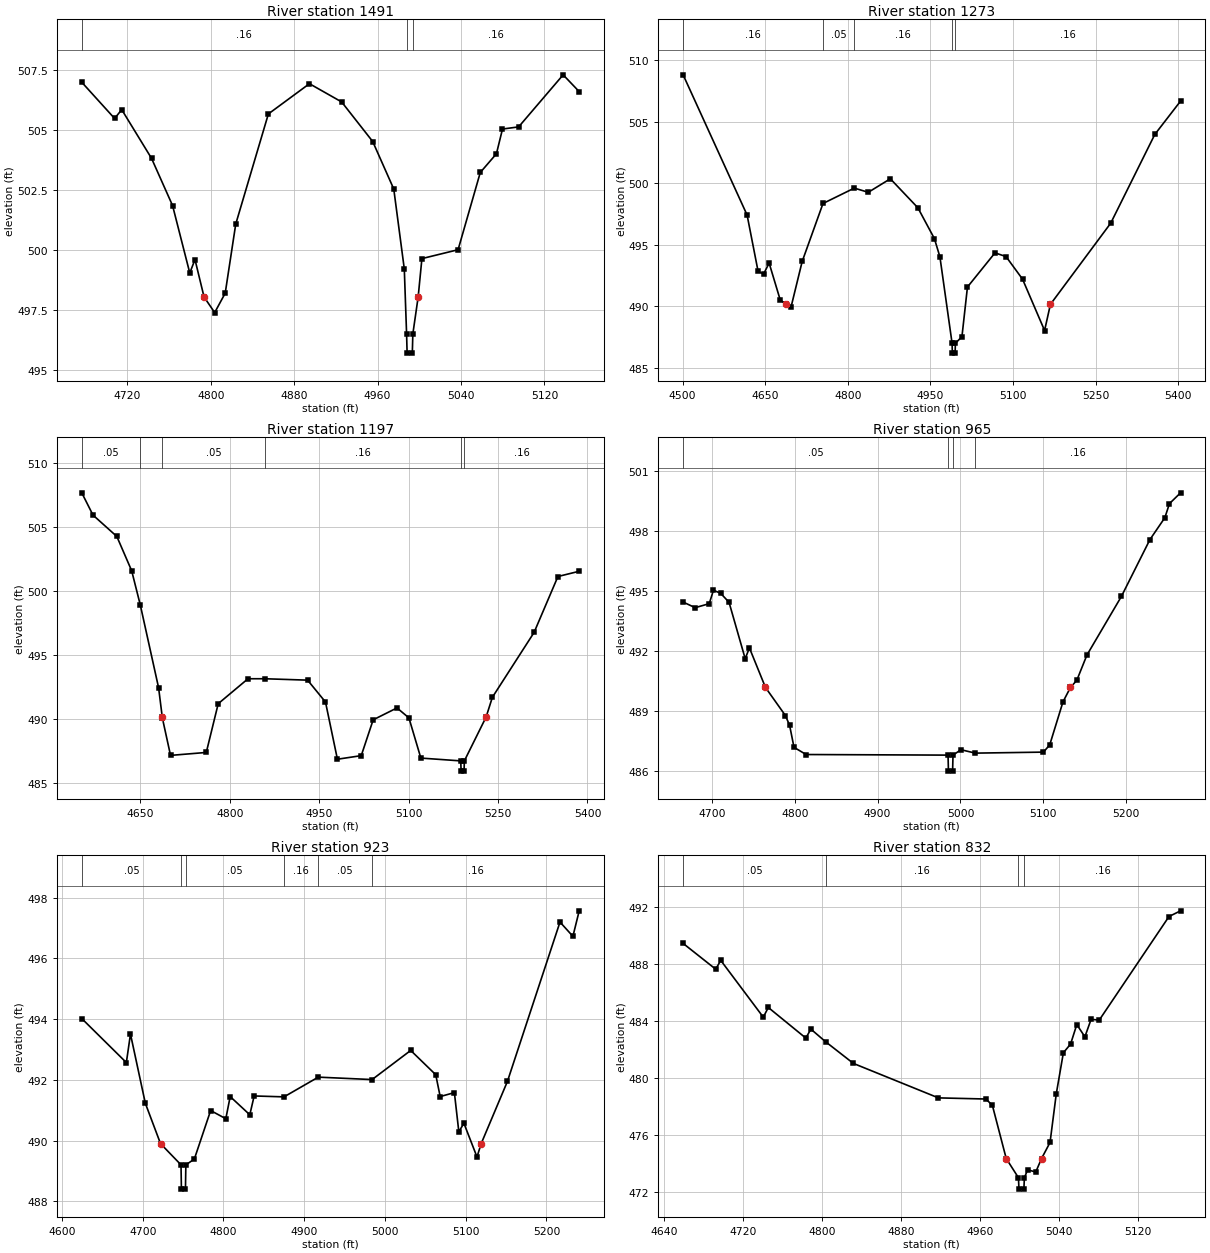
Type RM Length L Ch R = 1,1491,218,218,218
BEGIN DESCRIPTION:
UNT 128 in LFCCL Watershed 2.0
END DESCRIPTION:
XS GIS Cut Line= 3
      2836468.80      7079184.99      2836793.41      7079138.13
      2836920.91      7079060.59
#Sta/Elev= 30
  4676.2  506.99  4707.7  505.48  4714.5  505.85  4743.1  503.82  4763.3  501.85
  4779.8  499.04  4784.8  499.60  4793.5  498.04  4803.7  497.39  4813.8  498.20
  4823.9  501.08  4855.2  505.67  4894.6  506.93  4925.5  506.17  4955.3  504.52
  4975.5  502.54  4985.6  499.21  4987.8  496.50  4988.3  495.70  4993.3  495.70
  4993.8  496.50  4998.9  498.04  5002.5  499.64  5037.2  500.01  5058.5  503.23
  5074.0  504.01  5079.8  505.04  5095.3  505.13  5138.0  507.30  5153.4  506.60
#Mann=3,-1,0
  4676.2    0.16       0  4987.8    0.07       0  4993.8    0.16       0
Bank Sta=4793.5,4998.9
Exp/Cntr=0.3,0.1

Type RM Length L Ch R = 1,1273,76,76,76
BEGIN DESCRIPTION:
XS3819A
END DESCRIPTION:
XS GIS Cut Line= 3
      2836388.93      7079308.26      2836880.22      7079308.26
      2837291.70      7079297.89
#Sta/Elev= 30
  4501.0  508.82  4617.1  497.41  4637.1  492.82  4647.1  492.61  4657.1  493.50
  4677.1  490.52  4687.0  490.14  4697.1  489.96  4717.1  493.63  4754.9  498.35
  4811.7  499.60  4837.1  499.26  4877.1  500.36  4927.1  498.00  4957.1  495.49
  4967.1  494.01  4989.2  486.97  4989.7  486.17  4994.7  486.17  4995.2  486.97
  5007.1  487.51  5017.1  491.55  5067.1  494.33  5087.1  494.03  5117.1  492.19
  5157.1  488.01  5167.7  490.14  5277.2  496.75  5357.2  503.97  5403.9  506.68
#Mann=5,-1,0
  4501.0    0.16       0  4754.9    0.05       0  4811.7    0.16       0
  4989.2    0.07       0  4995.2    0.16       0
Bank Sta=4687,5167.7
Exp/Cntr=0.3,0.1

Type RM Length L Ch R = 1,1197,232,232,232
BEGIN DESCRIPTION:
XS3818A
END DESCRIPTION:
XS GIS Cut Line= 3
      2836446.16      7079391.60      2836899.31      7079382.92
      2837280.66      7079379.45
#Sta/Elev= 30
  4551.5  507.68  4570.3  505.94  4610.3  504.27  4635.2  501.59  4649.8  498.89
  4680.4  492.44  4686.5  490.16  4686.7  490.08  4700.4  487.16  4760.4  487.39
  4780.4  491.20  4830.4  493.15  4858.5  493.15  4930.4  493.04  4960.4  491.33
  4980.4  486.86  5020.4  487.14  5040.4  489.94  5080.4  490.87  5100.4  490.09
  5120.4  486.95  5187.4  486.73  5187.9  485.93  5192.9  485.93  5193.4  486.73
  5229.9  490.16  5240.4  491.70  5310.4  496.77  5350.4  501.14  5386.1  501.55
#Mann=6,-1,0
  4551.5    0.05       0  4649.8    0.16       0  4686.7    0.05       0
  4858.5    0.16       0  5187.4    0.07       0  5193.4    0.16       0
Bank Sta=4686.5,5229.9
Exp/Cntr=0.3,0.1

Type RM Length L Ch R = 1,965,42,42,42
BEGIN DESCRIPTION:
XS3816A
END DESCRIPTION:
XS GIS Cut Line= 3
      2836730.89      7079657.23      2836862.86      7079627.71
      2837289.97      7079443.67
#Sta/Elev= 30
  4665.3  494.43  4679.8  494.15  4696.8  494.35  4701.9  495.02  4710.5  494.87
  4720.7  494.42  4740.2  491.60  4745.3  492.14  4764.7  490.16  4788.7  488.76
  4793.8  488.27  4799.1  487.17  4813.7  486.81  4985.0  486.78  4985.5  485.98
  4990.5  485.98  4991.0  486.78  5000.6  487.05  5017.9  486.88  5100.1  486.93
  5107.7  487.29  5123.7  489.44  5132.7  490.16  5140.4  490.52  5152.6  491.78
  5194.2  494.71  5228.6  497.55  5246.7  498.65  5252.2  499.35  5265.6  499.89
#Mann=4,-1,0
  4665.3    0.05       0  4985.0   0.033       0  4991.0    0.05       0
  5017.9    0.16       0
Bank Sta=4764.7,5132.7
Exp/Cntr=0.3,0.1

Type RM Length L Ch R = 1,923,91,91,91
BEGIN DESCRIPTION:
XS3817A
END DESCRIPTION:
XS GIS Cut Line= 5
      2836717.04      7079678.05      2836887.16      7079653.75
      2837057.30      7079586.04      2837171.88      7079533.96
      2837289.97      7079467.97
#Sta/Elev= 30
  4624.5  494.02  4679.7  492.57  4684.8  493.51  4703.2  491.23  4722.0  489.90
  4747.4  489.20  4747.9  488.40  4752.9  488.40  4753.4  489.20  4763.9  489.39
  4784.1  490.99  4802.9  490.72  4808.3  491.45  4832.6  490.85  4838.0  491.47
  4875.0  491.44  4917.4  492.09  4984.1  492.01  5031.9  492.97  5062.9  492.17
  5068.4  491.45  5086.0  491.58  5091.5  490.29  5097.8  490.57  5114.0  489.46
  5119.2  489.90  5151.7  491.95  5216.8  497.20  5232.8  496.73  5240.6  497.57
#Mann=6,-1,0
  4624.5    0.05       0  4747.4    0.07       0  4753.4    0.05       0
  4875.0    0.16       0  4917.4    0.05       0  4984.1    0.16       0
Bank Sta=4722,5119.2
Exp/Cntr=0.3,0.1

Type RM Length L Ch R = 1,832,188,188,188
BEGIN DESCRIPTION:
XS3820A
END DESCRIPTION:
XS GIS Cut Line= 3
      2836812.56      7079728.39      2837118.06      7079658.96
      2837269.07      7079542.66
#Sta/Elev= 30
  4658.9  489.47  4691.9  487.66  4697.0  488.28  4740.1  484.29  4745.2  484.97
  4783.2  482.82  4788.3  483.45  4803.3  482.56  4831.4  481.04  4917.5  478.62
  4965.7  478.54  4972.2  478.09  4986.2  474.36  4998.6  473.01  4999.1  472.21
  5004.1  472.21  5004.6  473.01  5007.9  473.57  5016.1  473.41  5022.0  474.36
  5030.6  475.49  5036.9  478.90  5044.1  481.79  5051.4  482.40  5057.7  483.77
  5065.9  482.91  5072.2  484.14  5080.4  484.08  5151.1  491.36  5162.8  491.76
#Mann=4,-1,0
  4658.9    0.05       0  4803.3    0.16       0  4998.6    0.07       0
  5004.6    0.16       0
Bank Sta=4986.2,5022
Exp/Cntr=0.3,0.1

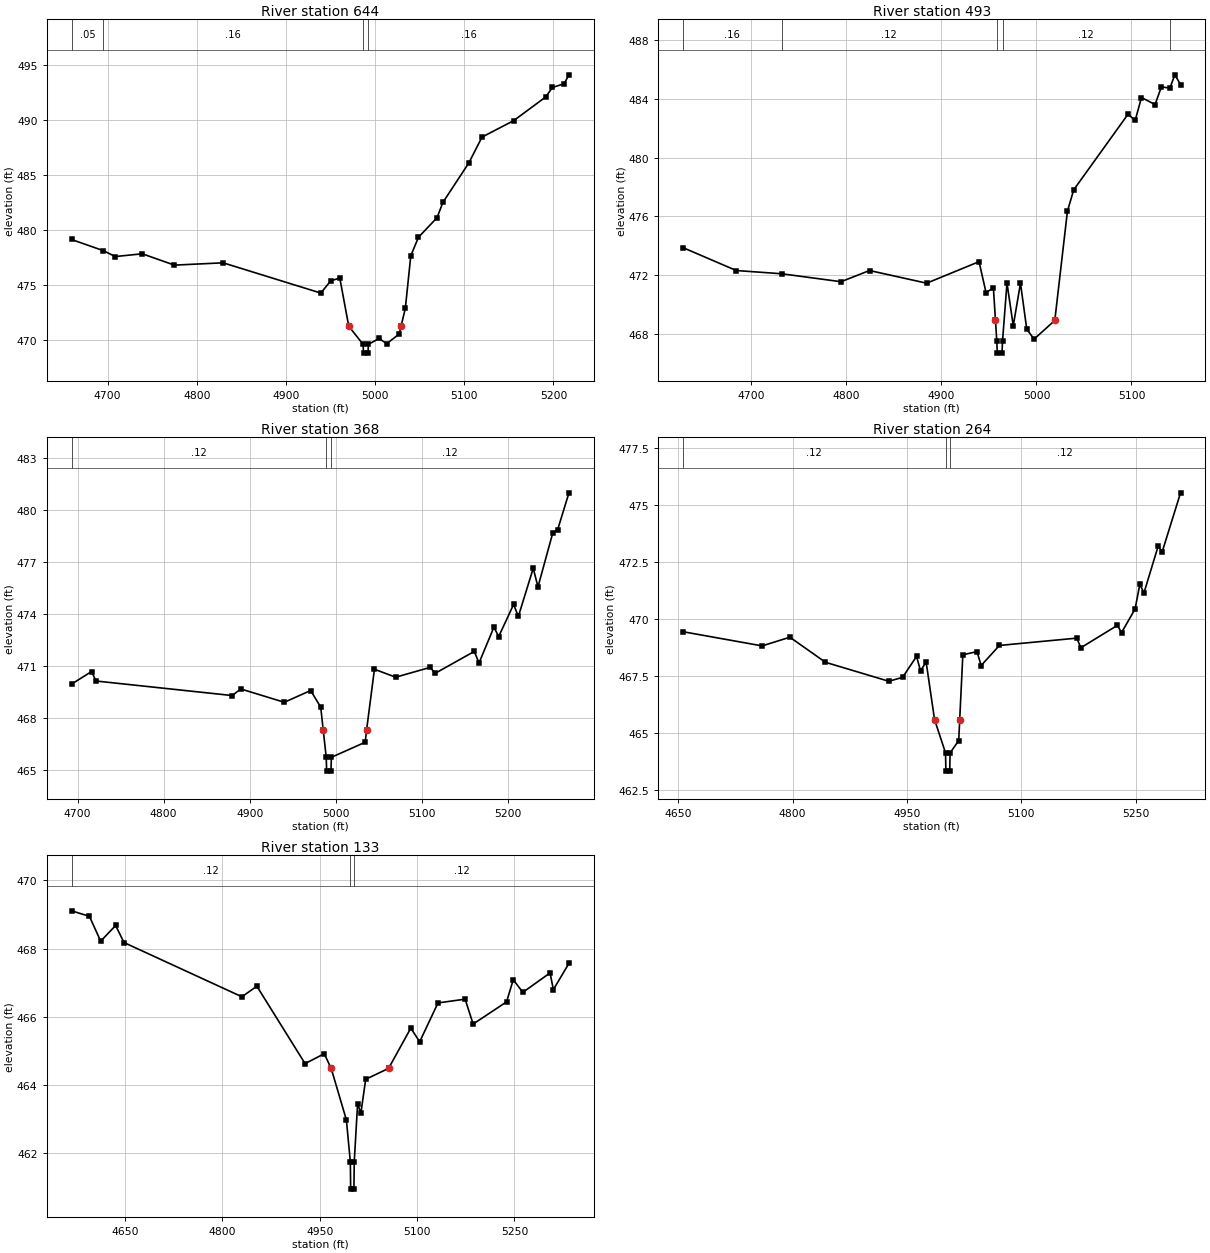
Type RM Length L Ch R = 1,644,151,151,151
BEGIN DESCRIPTION:
XS3821A
END DESCRIPTION:
XS GIS Cut Line= 3
      2836906.25      7079823.89      2837237.86      7079783.96
      2837420.05      7079653.82
#Sta/Elev= 30
  4659.5  479.14  4695.0  478.13  4708.6  477.59  4738.8  477.84  4774.9  476.81
  4829.5  477.02  4939.1  474.27  4950.3  475.39  4960.4  475.63  4970.4  471.26
  4986.5  469.61  4987.0  468.81  4992.0  468.81  4992.5  469.61  5004.4  470.14
  5013.0  469.67  5026.9  470.54  5029.1  471.26  5033.9  472.89  5040.0  477.66
  5048.6  479.34  5069.5  481.13  5076.0  482.51  5105.1  486.10  5119.9  488.45
  5155.5  489.95  5191.2  492.09  5198.9  492.96  5212.0  493.30  5217.4  494.11
#Mann=4,-1,0
  4659.5    0.05       0  4695.0    0.16       0  4986.5    0.07       0
  4992.5    0.16       0
Bank Sta=4970.4,5029.1
Exp/Cntr=0.3,0.1

Type RM Length L Ch R = 1,493,125,125,125
BEGIN DESCRIPTION:
XS3822A
END DESCRIPTION:
XS GIS Cut Line= 3
      2836979.17      7079903.75      2837289.94      7079921.11
      2837450.69      7079782.83
#Sta/Elev= 30
  4628.3  473.88  4684.2  472.33  4731.9  472.11  4794.4  471.57  4824.4  472.33
  4884.5  471.47  4939.6  472.93  4947.0  470.82  4954.7  471.17  4956.9  468.94
  4958.3  467.52  4958.8  466.72  4963.8  466.72  4964.3  467.52  4969.0  471.48
  4975.6  468.58  4983.2  471.47  4989.8  468.35  4997.5  467.67  5019.3  468.94
  5032.6  476.36  5039.2  477.81  5096.3  482.94  5103.9  482.53  5110.5  484.08
  5124.8  483.60  5131.4  484.80  5140.4  484.72  5145.6  485.62  5151.6  484.96
#Mann=5,-1,0
  4628.3    0.16       0  4731.9    0.12       0  4958.3    0.07       0
  4964.3    0.12       0  5140.4    0.16       0
Bank Sta=4956.9,5019.3
Exp/Cntr=0.3,0.1

Type RM Length L Ch R = 1,368,104,104,104
BEGIN DESCRIPTION:
XS3823A
END DESCRIPTION:
XS GIS Cut Line= 4
      2837090.26      7079966.25      2837359.38      7080004.44
      2837444.45      7079974.93      2837536.19      7079779.34
#Sta/Elev= 30
  4693.0  469.94  4716.3  470.67  4721.4  470.12  4879.6  469.28  4889.7  469.66
  4940.2  468.89  4970.8  469.57  4982.5  468.61  4985.4  467.29  4988.9  465.71
  4989.4  464.91  4994.4  464.91  4994.9  465.71  5034.2  466.58  5035.8  467.29
  5044.9  470.80  5069.6  470.34  5109.8  470.91  5115.3  470.56  5160.9  471.83
  5166.4  471.16  5183.7  473.23  5189.3  472.69  5206.6  474.55  5212.1  473.85
  5229.4  476.64  5234.9  475.56  5252.2  478.70  5257.7  478.86  5270.9  481.00
#Mann=3,-1,0
  4693.0    0.12       0  4988.9    0.07       0  4994.9    0.12       0
Bank Sta=4985.4,5035.8
Exp/Cntr=0.3,0.1

Type RM Length L Ch R = 1,264,131,131,131
BEGIN DESCRIPTION:
Mapping XS c265c01c
END DESCRIPTION:
XS GIS Cut Line= 3
      2837115.52      7079996.20      2837455.15      7080079.75
      2837569.91      7079799.82
#Sta/Elev= 30
  4656.5  469.45  4760.1  468.83  4796.5  469.21  4843.2  468.11  4926.2  467.28
  4944.3  467.45  4962.6  468.37  4967.8  467.74  4975.2  468.12  4986.2  465.60
  5000.6  464.14  5001.1  463.34  5006.1  463.34  5006.6  464.14  5017.9  464.68
  5019.2  465.60  5023.3  468.44  5041.9  468.58  5047.3  467.97  5071.3  468.85
  5172.7  469.17  5178.1  468.75  5226.0  469.73  5231.4  469.41  5249.2  470.45
  5255.4  471.53  5260.8  471.15  5279.4  473.20  5284.8  472.96  5308.8  475.54
#Mann=3,-1,0
  4656.5    0.12       0  5000.6    0.07       0  5006.6    0.12       0
Bank Sta=4986.2,5019.2
Exp/Cntr=0.3,0.1

Type RM Length L Ch R = 1,133,0,0,0
BEGIN DESCRIPTION:
UNT 128 in LFCCL Watershed 1.0
END DESCRIPTION:
XS GIS Cut Line= 4
      2837091.63      7080020.06      2837472.51      7080195.85
      2837515.91      7080185.00      2837586.82      7079891.57
#Sta/Elev= 30
  4567.9  469.11  4595.4  468.95  4612.8  468.22  4635.8  468.68  4648.7  468.18
  4830.3  466.59  4853.3  466.90  4927.6  464.63  4957.1  464.92  4967.8  464.49
  4991.2  462.98  4997.3  461.75  4997.8  460.95  5002.8  460.95  5003.3  461.75
  5008.5  463.45  5013.6  463.18  5020.9  464.17  5056.2  464.49  5090.4  465.67
  5104.1  465.27  5132.3  466.41  5174.1  466.52  5186.4  465.79  5237.9  466.44
  5248.2  467.09  5263.0  466.72  5304.9  467.29  5310.0  466.80  5334.0  467.57
#Mann=3,-1,0
  4567.9    0.12       0  4997.3    0.07       0  5003.3    0.12       0
Bank Sta=4967.8,5056.2
Exp/Cntr=0.3,0.1

Chan Stop Cuts=-1