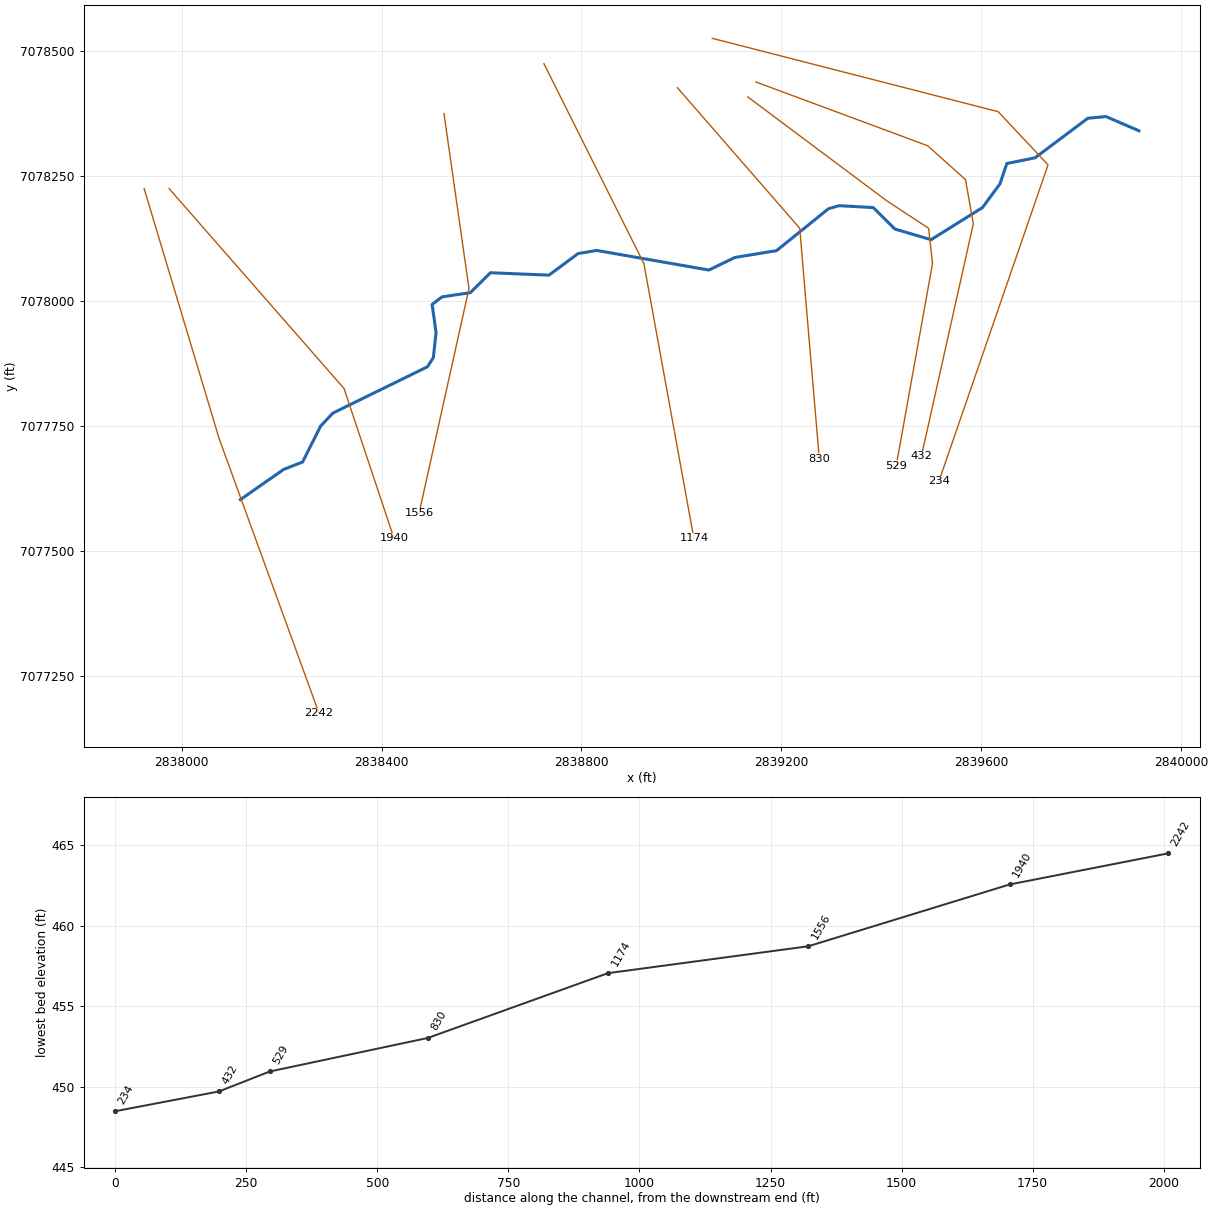
--- UNT 129 in LFCCL Watershed.prj (project) ---

Proj Title=UNT 129 in LFCCL Watershed Base Level Engineering
Current Plan=p01
Default Exp/Contr=0.3,0.1
English Units
Geom File=g01
Flow File=f01
Plan File=p01
BEGIN DESCRIPTION:
UNT 129 in LFCCL Watershed
END DESCRIPTION:

--- UNT 129 in LFCCL Watershed.p01 (plan) ---

Plan Title=Multiple Run
Short Identifier=Multiple
Geom File=g01
Flow File=f01
Subcritical Flow
K Sum by GR= 0
Std Step Tol= 0.01
Critical Tol= 0.01
Num of Std Step Trials= 20
Max Error Tol= 0.3
Flow Tol Ratio= 0.001
Split Flow NTrial= 30
Split Flow Tol= 0.02
Split Flow Ratio= 0.02
Log Output Level= 0
Friction Slope Method= 1
Unsteady Friction Slope Method= 2
Unsteady Bridges Friction Slope Method= 1
Parabolic Critical Depth
Global Vel Dist=  1 , 1 , 1
Global Log Level= 0
CheckData=True
Encroach Param= -1, 0, 0, 0
BEGIN DESCRIPTION:
Multiple Run
END DESCRIPTION:

--- UNT 129 in LFCCL Watershed.f01 (steady flow) ---

Flow Title=Multiple
Number of Profiles=7
Profile Names=10-year,25-year,50-year,1pct_min,100-year,1pct_plu,500-year
River Rch & RM= UNT 129 in LFCCL,Reach-1,2242
     524     694     831     495     987    1969    1386
Boundary for River Rch & Prof#=UNT 129 in LFCCL,Reach-1,1
Up Type=0
Dn Type=3
Dn Slope=0.005
Boundary for River Rch & Prof#=UNT 129 in LFCCL,Reach-1,2
Up Type=0
Dn Type=3
Dn Slope=0.005
Boundary for River Rch & Prof#=UNT 129 in LFCCL,Reach-1,3
Up Type=0
Dn Type=3
Dn Slope=0.005
Boundary for River Rch & Prof#=UNT 129 in LFCCL,Reach-1,4
Up Type=0
Dn Type=3
Dn Slope=0.005
Boundary for River Rch & Prof#=UNT 129 in LFCCL,Reach-1,5
Up Type=0
Dn Type=3
Dn Slope=0.005
Boundary for River Rch & Prof#=UNT 129 in LFCCL,Reach-1,6
Up Type=0
Dn Type=3
Dn Slope=0.005
Boundary for River Rch & Prof#=UNT 129 in LFCCL,Reach-1,7
Up Type=0
Dn Type=3
Dn Slope=0.005

--- UNT 129 in LFCCL Watershed.g01 (geometry) ---

Geom Title=Existing Conditions

River Reach=UNT 129 in LFCCL,Reach-1
Reach XY= 30
      2838117.59      7077602.79      2838204.36      7077663.22
      2838241.99      7077677.94      2838278.12      7077749.79
      2838302.69      7077775.85      2838491.80      7077868.44
      2838503.63      7077886.55      2838509.12      7077936.91
      2838501.25      7077993.22      2838520.98      7078008.36
      2838577.71      7078016.84      2838617.94      7078056.69
      2838735.03      7078051.86      2838793.27      7078095.01
      2838830.48      7078101.31      2839055.00      7078062.08
      2839106.98      7078087.24      2839190.50      7078100.93
      2839294.37      7078184.80      2839315.75      7078190.87
      2839383.87      7078187.04      2839427.18      7078144.15
      2839499.63      7078122.82      2839602.50      7078187.14
      2839637.63      7078234.86      2839651.15      7078275.19
      2839707.63      7078286.68      2839813.20      7078365.80
      2839849.50      7078369.22      2839915.59      7078340.71

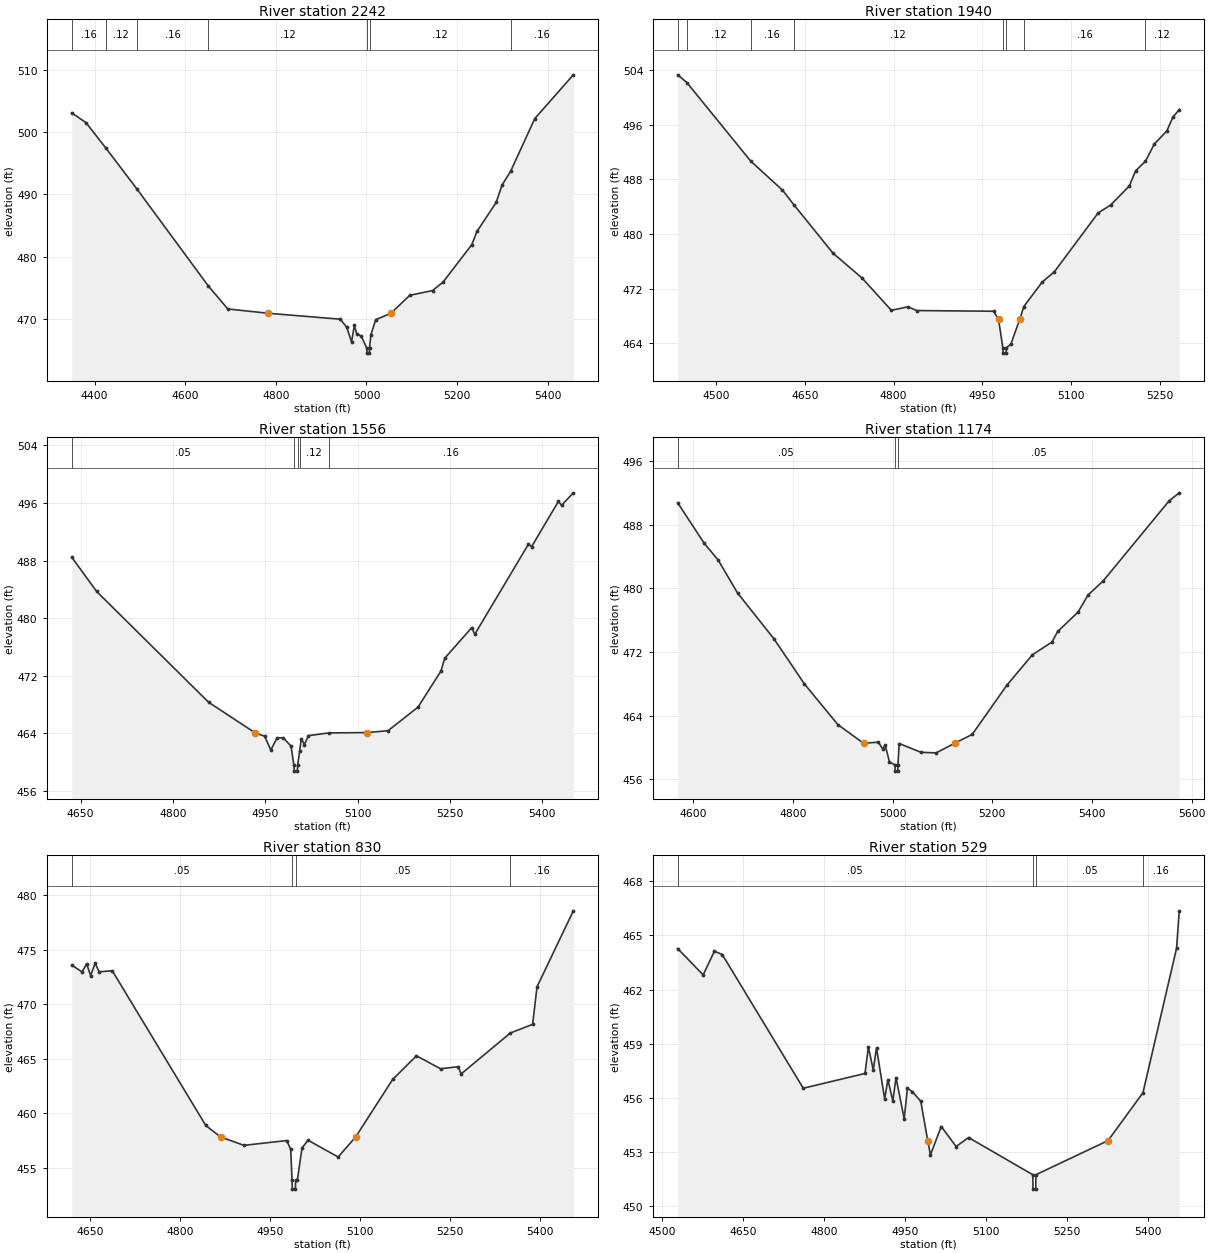
Type RM Length L Ch R = 1,2242,302,302,302
BEGIN DESCRIPTION:
UNT 129 in LFCCL Watershed 5.0
END DESCRIPTION:
XS GIS Cut Line= 3
      2837925.01      7078224.96      2838075.00      7077725.00
      2838275.00      7077175.01
#Sta/Elev= 30
  4349.4  503.10  4380.7  501.55  4424.6  497.46  4492.9  490.91  4650.9  475.28
  4693.9  471.59  4782.7  470.90  4942.5  469.94  4956.5  468.62  4967.1  466.28
  4973.1  468.95  4978.4  467.62  4988.4  467.22  5000.7  465.29  5001.2  464.49
  5006.2  464.49  5006.7  465.29  5009.7  467.46  5020.3  469.85  5054.0  470.90
  5095.5  473.78  5146.0  474.55  5169.3  475.93  5232.5  481.93  5243.8  484.04
  5286.4  488.73  5299.0  491.47  5318.1  493.71  5371.5  502.19  5456.6  509.22
#Mann=7,-1,0
  4349.4    0.16       0  4424.6    0.12       0  4492.9    0.16       0
  4650.9    0.12       0  5000.7    0.07       0  5006.7    0.12       0
  5318.1    0.16       0
Bank Sta=4782.7,5054
Exp/Cntr=0.3,0.1

Type RM Length L Ch R = 1,1940,384,384,384
BEGIN DESCRIPTION:
UNT 129 in LFCCL Watershed 4.0
END DESCRIPTION:
XS GIS Cut Line= 3
      2837974.99      7078225.01      2838325.00      7077825.00
      2838425.01      7077524.96
#Sta/Elev= 30
  4435.2  503.29  4450.7  502.16  4558.8  490.65  4612.2  486.43  4631.3  484.31
  4697.6  477.20  4747.0  473.54  4796.4  468.82  4824.8  469.35  4839.1  468.79
  4969.4  468.69  4977.5  467.51  4984.8  463.36  4985.3  462.56  4990.3  462.56
  4990.8  463.36  4998.3  463.85  5013.3  467.51  5020.2  469.37  5051.1  472.94
  5072.1  474.49  5145.9  483.08  5167.0  484.24  5198.6  487.03  5209.2  489.24
  5225.8  490.64  5240.8  493.16  5261.9  495.07  5272.4  497.12  5283.0  498.21
#Mann=8,-1,0
  4435.2    0.16       0  4450.7    0.12       0  4558.8    0.16       0
  4631.3    0.12       0  4984.8    0.07       0  4990.8    0.12       0
  5020.2    0.16       0  5225.8    0.12       0
Bank Sta=4977.5,5013.3
Exp/Cntr=0.3,0.1

Type RM Length L Ch R = 1,1556,382,382,382
BEGIN DESCRIPTION:
UNT 129 in LFCCL Watershed 3.0
END DESCRIPTION:
XS GIS Cut Line= 3
      2838525.00      7078375.02      2838575.00      7078025.00
      2838475.01      7077575.05
#Sta/Elev= 30
  4635.7  488.46  4676.1  483.70  4858.0  468.29  4932.8  464.08  4948.9  463.57
  4959.0  461.66  4969.1  463.34  4979.2  463.35  4991.8  462.18  4996.5  459.52
  4997.0  458.72  5002.0  458.72  5002.5  459.52  5005.8  461.54  5008.5  463.20
  5013.6  462.42  5020.0  463.65  5052.8  464.03  5114.5  464.08  5149.3  464.34
  5198.0  467.62  5235.1  472.62  5241.5  474.43  5285.1  478.66  5290.2  477.75
  5377.3  490.27  5382.4  489.92  5425.9  496.21  5431.0  495.68  5450.2  497.41
#Mann=5,-1,0
  4635.7    0.05       0  4996.5    0.03       0  5002.5    0.05       0
  5005.8    0.12       0  5052.8    0.16       0
Bank Sta=4932.8,5114.5
Exp/Cntr=0.3,0.1

Type RM Length L Ch R = 1,1174,344,344,344
BEGIN DESCRIPTION:
UNT 129 in LFCCL Watershed 2.0
END DESCRIPTION:
XS GIS Cut Line= 3
      2838725.00      7078475.01      2838925.00      7078075.00
      2839024.99      7077525.04
#Sta/Elev= 30
  4569.0  490.76  4622.1  485.68  4650.1  483.58  4689.2  479.42  4761.9  473.69
  4823.4  467.99  4890.4  462.89  4941.9  460.55  4971.5  460.69  4979.9  459.88
  4985.5  460.28  4993.9  458.18  5004.8  457.85  5005.3  457.05  5010.3  457.05
  5010.8  457.85  5013.4  460.52  5056.9  459.42  5087.4  459.34  5124.5  460.55
  5159.8  461.66  5229.7  467.87  5280.5  471.66  5319.9  473.27  5331.3  474.59
  5372.0  477.02  5392.3  479.18  5422.8  480.96  5554.9  491.01  5575.2  492.01
#Mann=3,-1,0
  4569.0    0.05       0  5004.8    0.03       0  5010.8    0.05       0
Bank Sta=4941.9,5124.5
Exp/Cntr=0.3,0.1

Type RM Length L Ch R = 1,830,301,301,301
BEGIN DESCRIPTION:
XS3824A
END DESCRIPTION:
XS GIS Cut Line= 4
      2838992.10      7078426.83      2839236.89      7078145.59
      2839247.30      7078020.59      2839275.95      7077684.69
#Sta/Elev= 30
  4620.1  473.59  4637.3  472.96  4644.9  473.71  4651.5  472.63  4659.1  473.76
  4665.8  472.97  4687.6  473.07  4843.3  458.87  4867.9  457.81  4906.9  457.04
  4978.2  457.48  4984.8  456.66  4987.0  453.82  4987.5  453.02  4992.5  453.02
  4993.0  453.82  4995.8  453.82  5003.6  456.80  5013.6  457.51  5063.8  455.97
  5092.9  457.81  5154.6  463.09  5194.2  465.26  5234.4  464.07  5263.7  464.26
  5268.7  463.60  5350.5  467.35  5387.7  468.15  5395.0  471.59  5455.5  478.57
#Mann=4,-1,0
  4620.1    0.05       0  4987.0    0.03       0  4993.0    0.05       0
  5350.5    0.16       0
Bank Sta=4867.9,5092.9
Exp/Cntr=0.3,0.1

Type RM Length L Ch R = 1,529,97,97,97
BEGIN DESCRIPTION:
XS3825A
END DESCRIPTION:
XS GIS Cut Line= 5
      2839132.72      7078408.61      2839411.36      7078200.28
      2839494.70      7078145.59      2839502.51      7078075.28
      2839429.89      7077670.68
#Sta/Elev= 30
  4529.1  464.27  4576.3  462.81  4597.1  464.12  4611.7  463.94  4761.8  456.53
  4876.2  457.35  4882.4  458.81  4891.5  457.55  4897.5  458.77  4912.6  455.94
  4918.6  457.01  4927.7  455.83  4933.7  457.12  4948.8  454.84  4954.8  456.52
  4963.9  456.34  4979.5  455.81  4992.4  453.63  4997.4  452.84  5017.5  454.41
  5045.1  453.30  5068.0  453.80  5187.0  451.74  5187.5  450.94  5192.5  450.94
  5193.0  451.74  5326.5  453.63  5391.2  456.28  5453.5  464.29  5458.5  466.36
#Mann=4,-1,0
  4529.1    0.05       0  5187.0    0.03       0  5193.0    0.05       0
  5391.2    0.16       0
Bank Sta=4992.4,5326.5
Exp/Cntr=0.3,0.1

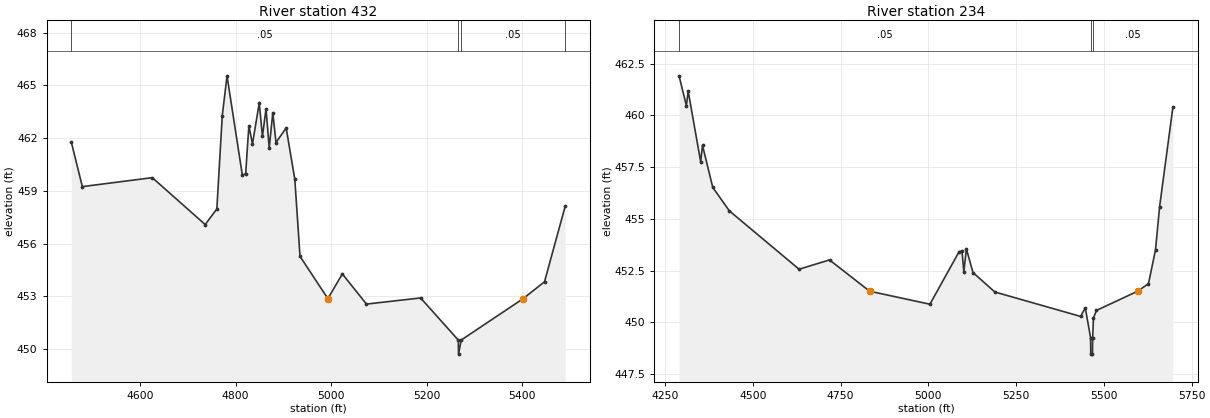
Type RM Length L Ch R = 1,432,198,198,198
BEGIN DESCRIPTION:
XS3826A
END DESCRIPTION:
XS GIS Cut Line= 5
      2839149.24      7078438.33      2839492.96      7078310.74
      2839568.48      7078243.03      2839584.11      7078154.49
      2839480.16      7077689.34
#Sta/Elev= 30
  4455.8  461.77  4478.8  459.24  4625.3  459.75  4736.2  457.08  4760.6  457.97
  4771.9  463.27  4781.9  465.55  4813.9  459.91  4820.9  459.96  4827.7  462.71
  4835.2  461.67  4849.4  464.00  4856.1  462.10  4863.6  463.67  4870.3  461.44
  4877.8  463.45  4884.5  461.75  4905.8  462.58  4923.9  459.66  4934.8  455.27
  4993.2  452.86  5023.5  454.27  5074.0  452.55  5187.4  452.90  5266.4  450.50
  5266.9  449.70  5272.4  450.50  5402.3  452.86  5447.0  453.82  5490.4  458.13
#Mann=4,-1,0
  4455.8    0.05       0  5266.4    0.03       0  5272.4    0.05       0
  5490.4    0.16       0
Bank Sta=4993.2,5402.3
Exp/Cntr=0.3,0.1

Type RM Length L Ch R = 1,234,0,0,0
BEGIN DESCRIPTION:
UNT 129 in LFCCL Watershed 1.0
END DESCRIPTION:
XS GIS Cut Line= 4
      2839061.87      7078525.71      2839633.80      7078378.98
      2839733.66      7078272.62      2839515.22      7077639.17
#Sta/Elev= 30
  4290.2  461.91  4311.1  460.47  4316.2  461.17  4351.8  457.76  4357.0  458.55
  4386.3  456.52  4433.4  455.39  4632.0  452.57  4718.7  453.02  4832.8  451.51
  5004.6  450.88  5087.5  453.41  5095.9  453.46  5101.2  452.46  5108.6  453.55
  5127.2  452.41  5189.6  451.47  5433.9  450.29  5447.1  450.71  5462.1  449.27
  5462.6  448.47  5467.6  448.47  5468.1  449.27  5470.4  450.22  5478.9  450.58
  5596.3  451.51  5627.0  451.87  5647.1  453.51  5658.7  455.59  5696.6  460.40
#Mann=3,-1,0
  4290.2    0.05       0  5462.1    0.03       0  5468.1    0.05       0
Bank Sta=4832.8,5596.3
Exp/Cntr=0.3,0.1

Chan Stop Cuts=-1