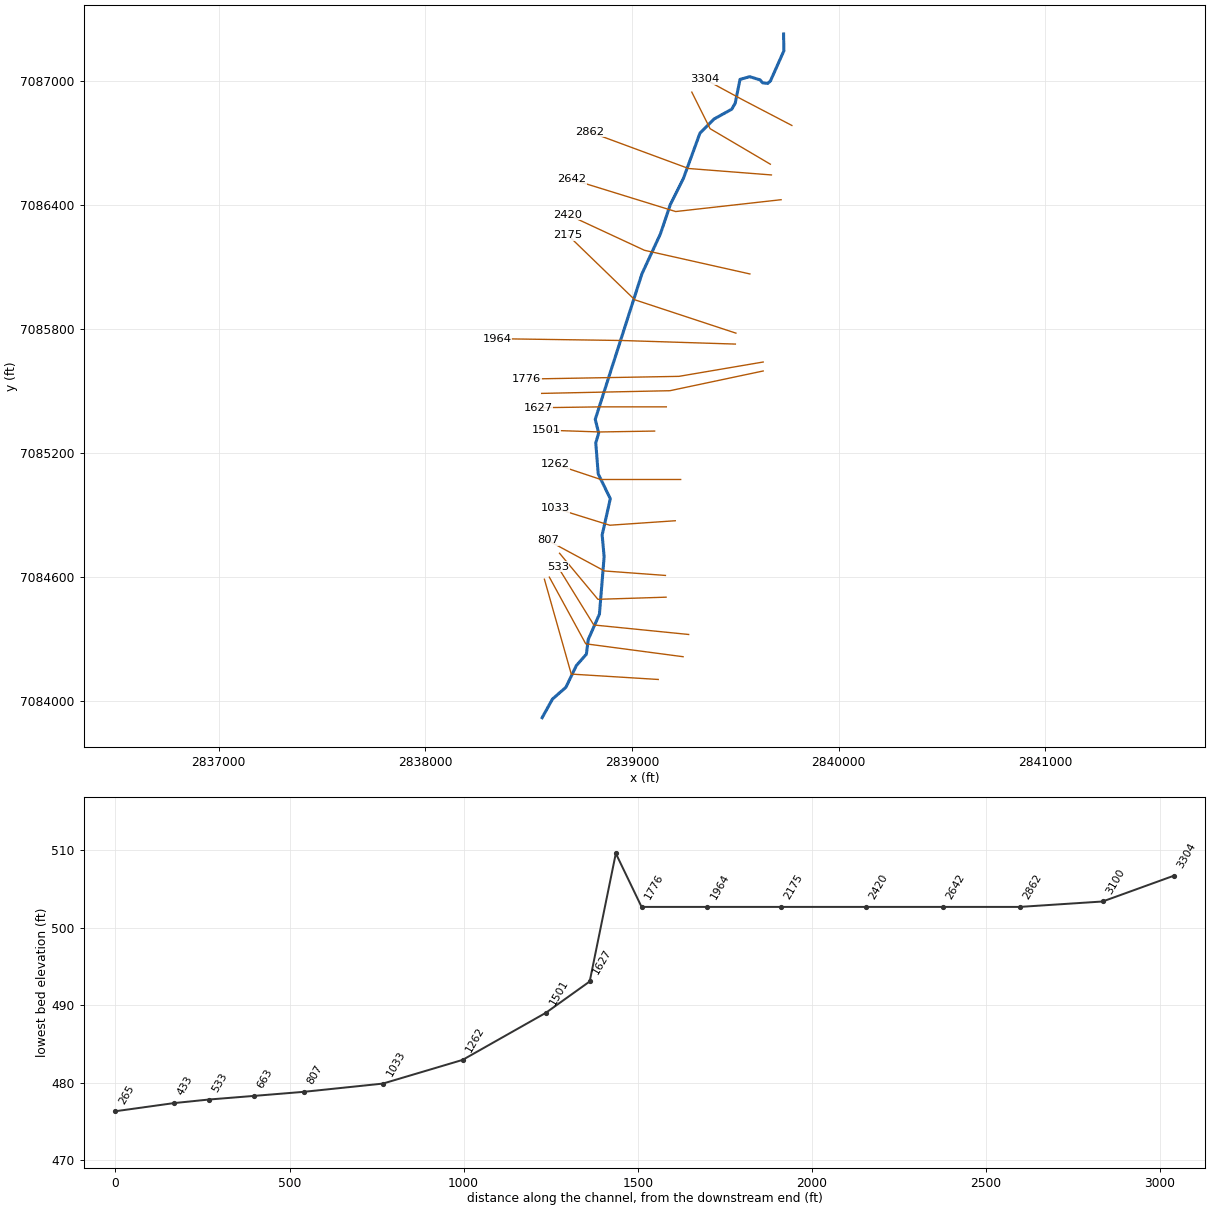
--- UNT 131 in LFCCL Watershed.prj (project) ---

Proj Title=UNT 131 in LFCCL Watershed Base Level Engineering
Current Plan=p01
Default Exp/Contr=0.3,0.1
English Units
Geom File=g01
Flow File=f01
Plan File=p01
BEGIN DESCRIPTION:
UNT 131 in LFCCL Watershed
END DESCRIPTION:

--- UNT 131 in LFCCL Watershed.p01 (plan) ---

Plan Title=Multiple Run
Short Identifier=Multiple
Geom File=g01
Flow File=f01
Subcritical Flow
K Sum by GR= 0
Std Step Tol= 0.01
Critical Tol= 0.01
Num of Std Step Trials= 20
Max Error Tol= 0.3
Flow Tol Ratio= 0.001
Split Flow NTrial= 30
Split Flow Tol= 0.02
Split Flow Ratio= 0.02
Log Output Level= 0
Friction Slope Method= 1
Unsteady Friction Slope Method= 2
Unsteady Bridges Friction Slope Method= 1
Parabolic Critical Depth
Global Vel Dist=  1 , 1 , 1
Global Log Level= 0
CheckData=True
Encroach Param= -1, 0, 0, 0
BEGIN DESCRIPTION:
Multiple Run
END DESCRIPTION:

--- UNT 131 in LFCCL Watershed.f01 (steady flow) ---

Flow Title=Multiple
Number of Profiles=7
Profile Names=10-year,25-year,50-year,1pct_min,100-year,1pct_plu,500-year
River Rch & RM= UNT 131 in LFCCL,Reach-1,3304
     438     570     674     396     791    1578    1084
Boundary for River Rch & Prof#=UNT 131 in LFCCL,Reach-1,1
Up Type=0
Dn Type=3
Dn Slope=0.005
Boundary for River Rch & Prof#=UNT 131 in LFCCL,Reach-1,2
Up Type=0
Dn Type=3
Dn Slope=0.005
Boundary for River Rch & Prof#=UNT 131 in LFCCL,Reach-1,3
Up Type=0
Dn Type=3
Dn Slope=0.005
Boundary for River Rch & Prof#=UNT 131 in LFCCL,Reach-1,4
Up Type=0
Dn Type=3
Dn Slope=0.005
Boundary for River Rch & Prof#=UNT 131 in LFCCL,Reach-1,5
Up Type=0
Dn Type=3
Dn Slope=0.005
Boundary for River Rch & Prof#=UNT 131 in LFCCL,Reach-1,6
Up Type=0
Dn Type=3
Dn Slope=0.005
Boundary for River Rch & Prof#=UNT 131 in LFCCL,Reach-1,7
Up Type=0
Dn Type=3
Dn Slope=0.005

--- UNT 131 in LFCCL Watershed.g01 (geometry) ---

Geom Title=Existing Conditions

River Reach=UNT 131 in LFCCL,Reach-1
Reach XY= 30
      2839734.18      7087229.77      2839735.59      7087148.17
      2839670.48      7087002.34      2839657.46      7086990.62
      2839632.72      7086993.23      2839621.00      7087007.55
      2839570.22      7087023.17      2839523.35      7087010.15
      2839499.91      7086894.27      2839482.98      7086865.62
      2839398.35      7086818.75      2839329.34      7086749.74
      2839249.91      7086532.29      2839186.11      7086404.68
      2839138.07      7086262.29      2839048.73      7086069.34
      2838822.60      7085364.60      2838839.29      7085298.69
      2838825.27      7085250.78      2838836.99      7085100.85
      2838895.54      7084980.65      2838856.18      7084805.43
      2838865.61      7084699.22      2838842.90      7084421.82
      2838788.84      7084299.36      2838779.73      7084228.14
      2838731.43      7084173.28      2838680.59      7084067.95
      2838615.58      7084010.86      2838565.59      7083920.71

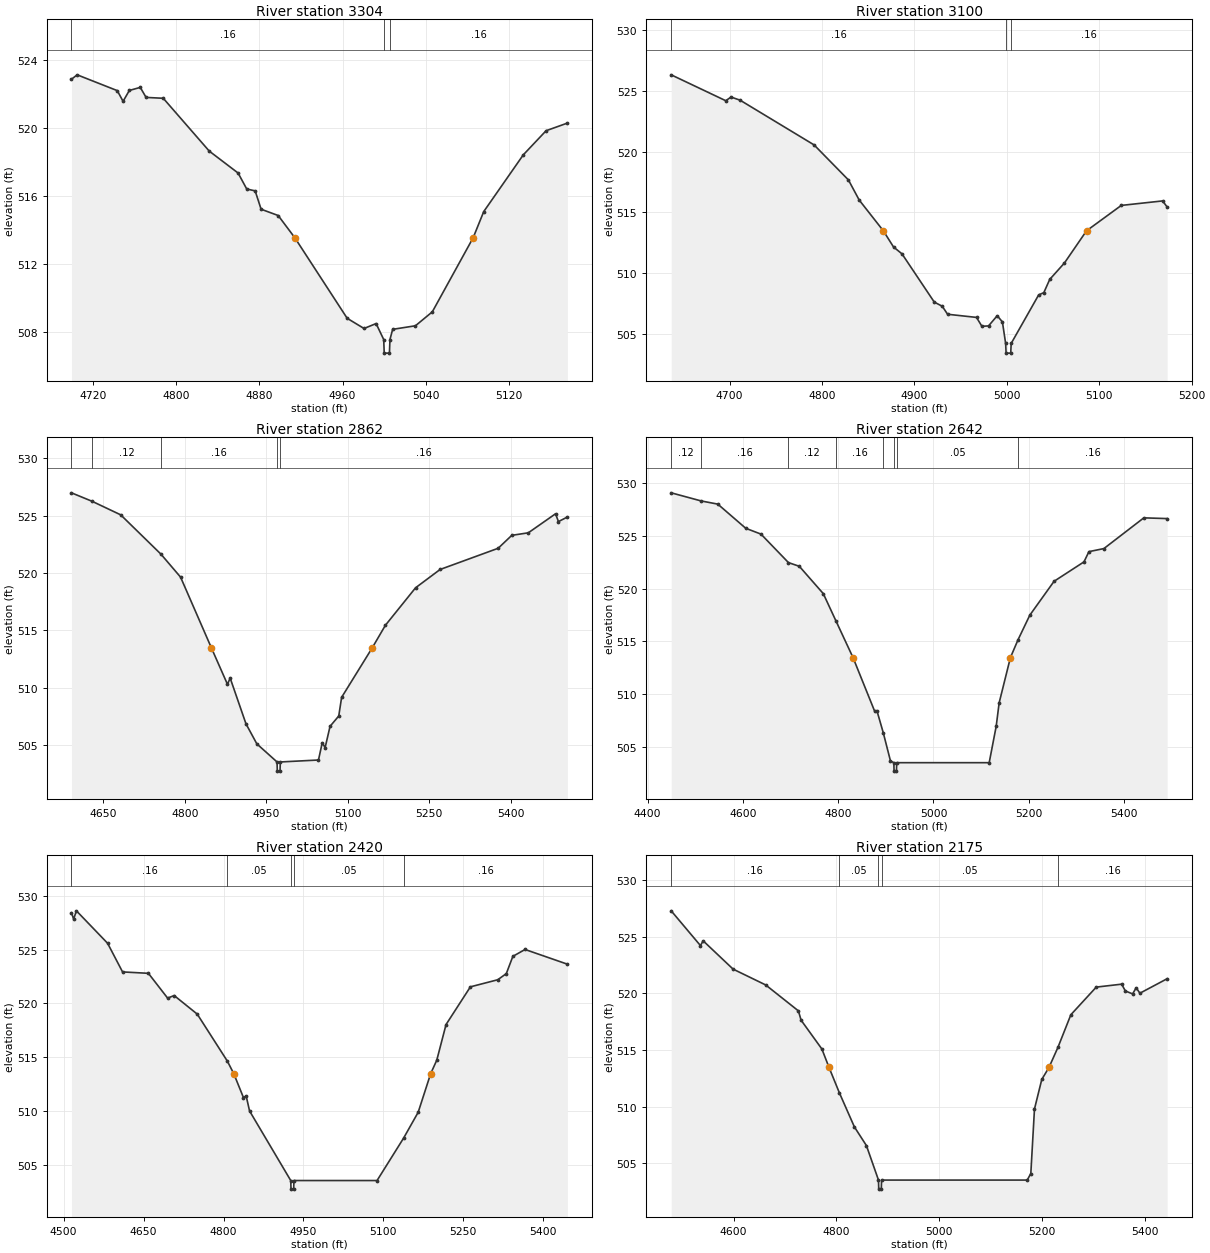
Type RM Length L Ch R = 1,3304,204,204,204
BEGIN DESCRIPTION:
UNT 131 in LFCCL Watershed 3.0
END DESCRIPTION:
XS GIS Cut Line= 3
      2839774.30      7086787.19      2839534.70      7086912.20
      2839353.44      7087010.60
#Sta/Elev= 30
  4699.5  522.85  4705.0  523.11  4743.5  522.18  4749.1  521.55  4755.1  522.19
  4765.6  522.37  4771.2  521.78  4787.7  521.73  4831.9  518.62  4859.6  517.33
  4867.9  516.39  4876.0  516.28  4881.7  515.20  4898.1  514.83  4914.0  513.53
  4964.4  508.78  4980.6  508.18  4992.2  508.47  4999.5  507.53  5000.0  506.73
  5005.0  506.73  5005.5  507.53  5008.1  508.13  5030.0  508.34  5046.2  509.16
  5085.5  513.53  5095.6  515.06  5133.6  518.40  5155.5  519.82  5176.0  520.27
#Mann=3,-1,0
  4699.5    0.16       0  4999.5    0.07       0  5005.5    0.16       0
Bank Sta=4914,5085.5
Exp/Cntr=0.3,0.1

Type RM Length L Ch R = 1,3100,238,238,238
BEGIN DESCRIPTION:
XS3827A
END DESCRIPTION:
XS GIS Cut Line= 3
      2839670.16      7086599.67      2839378.45      7086771.57
      2839289.94      7086948.59
#Sta/Elev= 30
  4636.9  526.32  4695.9  524.19  4701.7  524.49  4711.5  524.23  4791.5  520.55
  4828.6  517.67  4840.3  516.01  4866.4  513.48  4877.4  512.15  4886.6  511.58
  4921.5  507.61  4930.1  507.27  4935.9  506.61  4967.2  506.35  4973.0  505.62
  4980.2  505.65  4989.6  506.49  4995.2  505.98  4998.7  504.21  4999.2  503.41
  5004.2  503.41  5004.7  504.21  5034.4  508.20  5040.0  508.39  5046.4  509.48
  5062.3  510.83  5086.2  513.48  5123.8  515.57  5168.5  515.94  5173.4  515.44
#Mann=3,-1,0
  4636.9    0.16       0  4998.7    0.07       0  5004.7    0.16       0
Bank Sta=4866.4,5086.2
Exp/Cntr=0.3,0.1

Type RM Length L Ch R = 1,2862,220,220,220
BEGIN DESCRIPTION:
XS3828A
END DESCRIPTION:
XS GIS Cut Line= 3
      2839675.31      7086547.61      2839274.29      7086578.86
      2838795.11      7086755.95
#Sta/Elev= 30
  4591.2  527.00  4629.2  526.26  4681.8  525.08  4755.9  521.65  4792.1  519.64
  4848.9  513.46  4878.4  510.29  4883.4  510.83  4912.5  506.84  4932.5  505.09
  4969.7  503.51  4970.2  502.71  4975.2  502.71  4975.7  503.51  5046.0  503.68
  5052.9  505.19  5058.2  504.76  5067.3  506.62  5083.3  507.52  5088.6  509.15
  5144.8  513.46  5169.2  515.44  5224.7  518.71  5269.9  520.31  5376.8  522.16
  5401.9  523.29  5432.3  523.51  5482.4  525.17  5487.8  524.49  5504.3  524.89
#Mann=5,-1,0
  4591.2    0.16       0  4629.2    0.12       0  4755.9    0.16       0
  4969.7    0.07       0  4975.7    0.16       0
Bank Sta=4848.9,5144.8
Exp/Cntr=0.3,0.1

Type RM Length L Ch R = 1,2642,222,222,222
BEGIN DESCRIPTION:
XS3829A
END DESCRIPTION:
XS GIS Cut Line= 3
      2839722.23      7086427.82      2839211.79      7086370.53
      2838708.27      7086526.25
#Sta/Elev= 30
  4449.7  529.07  4512.7  528.30  4547.5  528.00  4606.2  525.71  4638.1  525.16
  4695.8  522.46  4718.6  522.11  4768.9  519.52  4795.2  516.96  4831.3  513.46
  4876.5  508.40  4881.5  508.42  4894.7  506.35  4909.8  503.68  4916.9  503.51
  4917.4  502.71  4922.4  502.71  4922.9  503.51  5117.0  503.51  5131.7  506.96
  5137.9  509.18  5161.5  513.46  5177.4  515.14  5202.2  517.48  5253.1  520.69
  5315.9  522.53  5326.3  523.50  5357.7  523.79  5441.5  526.70  5490.4  526.63
#Mann=8,-1,0
  4449.7    0.12       0  4512.7    0.16       0  4695.8    0.12       0
  4795.2    0.16       0  4894.7    0.05       0  4916.9   0.033       0
  4922.9    0.05       0  5177.4    0.16       0
Bank Sta=4831.3,5161.5
Exp/Cntr=0.3,0.1

Type RM Length L Ch R = 1,2420,245,245,245
BEGIN DESCRIPTION:
XS3830A
END DESCRIPTION:
XS GIS Cut Line= 3
      2839571.16      7086068.45      2839060.75      7086183.03
      2838690.95      7086354.90
#Sta/Elev= 30
  4514.6  528.45  4518.7  527.86  4523.9  528.63  4582.4  525.61  4610.5  522.94
  4659.0  522.81  4695.1  520.50  4707.4  520.74  4750.7  519.01  4807.1  514.64
  4819.3  513.46  4837.4  511.24  4842.5  511.39  4848.9  509.99  4926.2  503.51
  4926.7  502.71  4931.7  502.71  4932.2  503.51  5088.2  503.51  5138.0  507.46
  5165.4  509.87  5188.8  513.46  5200.3  514.72  5217.7  518.04  5263.4  521.55
  5314.7  522.21  5330.8  522.78  5343.1  524.39  5366.0  525.03  5445.5  523.66
#Mann=5,-1,0
  4514.6    0.16       0  4807.1    0.05       0  4926.2   0.033       0
  4932.2    0.05       0  5138.0    0.16       0
Bank Sta=4819.3,5188.8
Exp/Cntr=0.3,0.1

Type RM Length L Ch R = 1,2175,211,211,211
BEGIN DESCRIPTION:
XS3831A
END DESCRIPTION:
XS GIS Cut Line= 3
      2839503.45      7085781.99      2839013.87      7085943.45
      2838690.94      7086255.95
#Sta/Elev= 30
  4478.6  527.30  4535.5  524.23  4540.8  524.65  4599.0  522.15  4662.5  520.75
  4726.1  518.46  4731.3  517.64  4771.8  515.09  4785.7  513.46  4806.0  511.20
  4835.0  508.21  4858.4  506.56  4881.9  503.51  4882.4  502.71  4887.4  502.71
  4887.9  503.51  5171.3  503.51  5178.3  504.09  5185.4  509.79  5199.6  512.40
  5213.6  513.46  5231.0  515.23  5256.2  518.12  5305.6  520.56  5355.0  520.82
  5362.2  520.22  5376.3  519.96  5383.3  520.50  5390.5  520.02  5443.5  521.30
#Mann=5,-1,0
  4478.6    0.16       0  4806.0    0.05       0  4881.9   0.033       0
  4887.9    0.05       0  5231.0    0.16       0
Bank Sta=4785.7,5213.6
Exp/Cntr=0.3,0.1

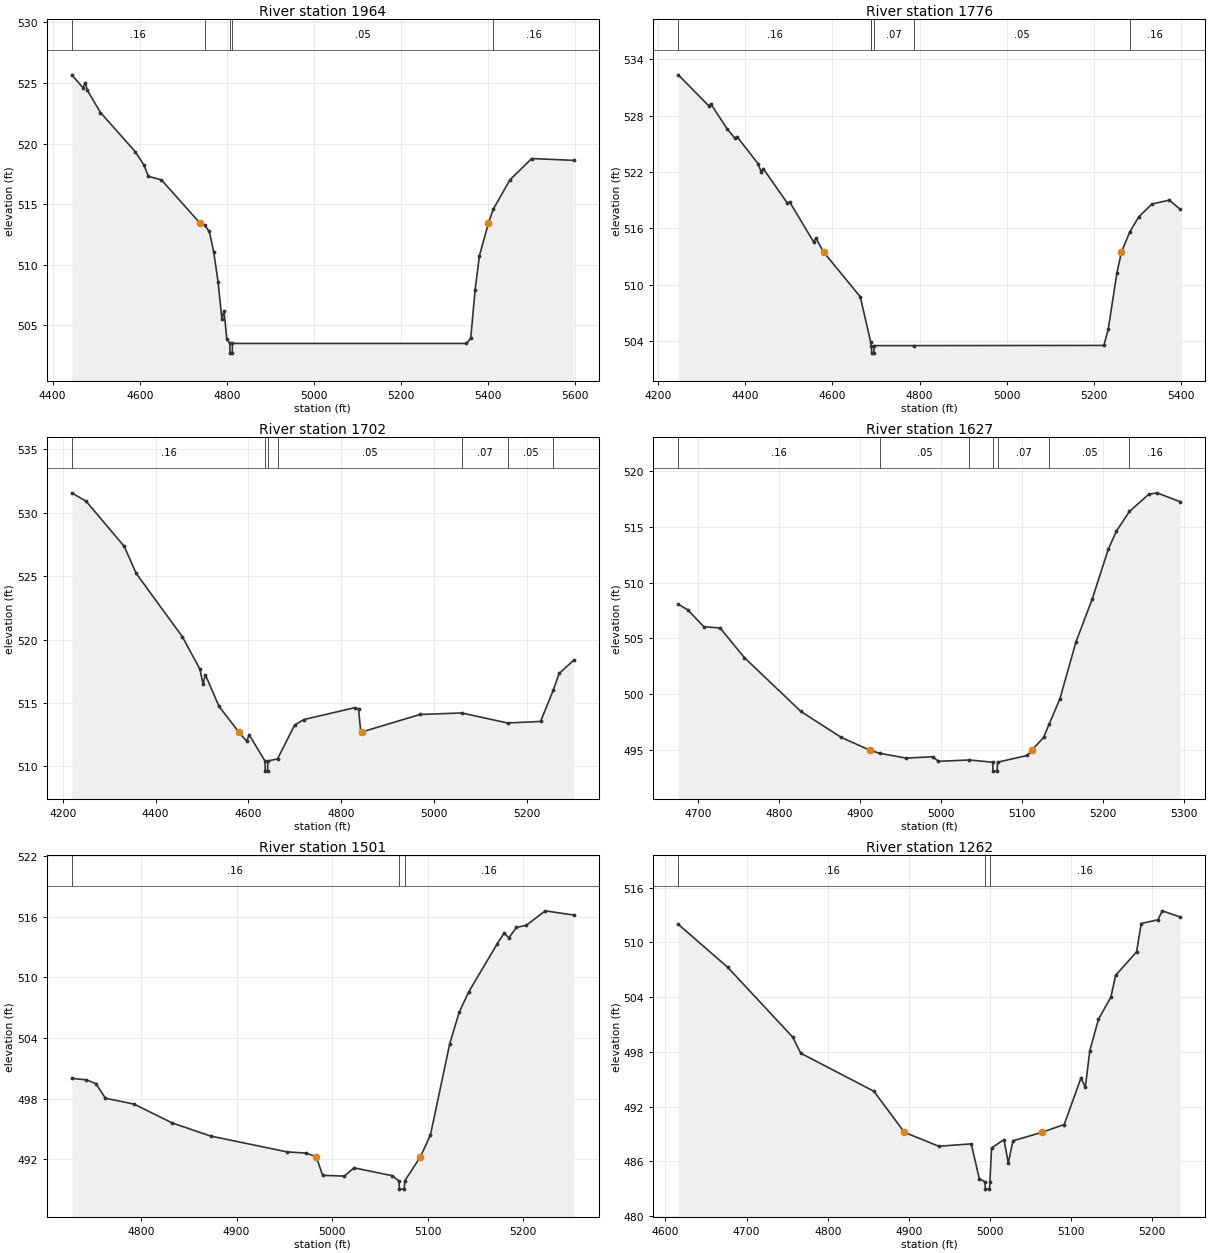
Type RM Length L Ch R = 1,1964,188,188,188
BEGIN DESCRIPTION:
XS3832A
END DESCRIPTION:
XS GIS Cut Line= 3
      2839500.85      7085729.04      2838949.63      7085746.40
      2838348.19      7085755.05
#Sta/Elev= 30
  4444.0  525.68  4469.8  524.61  4474.8  525.04  4479.9  524.40  4509.9  522.57
  4589.9  519.33  4609.9  518.22  4619.9  517.30  4650.0  517.01  4737.9  513.46
  4749.1  513.26  4760.0  512.75  4770.0  511.05  4780.0  508.58  4788.7  505.54
  4793.7  506.19  4800.0  503.87  4807.0  503.51  4807.5  502.71  4812.5  502.71
  4813.0  503.51  5350.2  503.51  5360.2  503.93  5370.2  507.91  5380.2  510.75
  5401.0  513.46  5411.8  514.58  5450.2  517.01  5500.2  518.77  5597.0  518.62
#Mann=5,-1,0
  4444.0    0.16       0  4749.1    0.05       0  4807.0   0.033       0
  4813.0    0.05       0  5411.8    0.16       0
Bank Sta=4737.9,5401
Exp/Cntr=0.3,0.1

Type RM Length L Ch R = 1,1776,74,74,74
BEGIN DESCRIPTION:
XS3834A
END DESCRIPTION:
XS GIS Cut Line= 3
      2839635.36      7085642.22      2839227.41      7085572.79
      2838489.74      7085559.77
#Sta/Elev= 30
  4246.2  532.33  4315.8  529.05  4320.8  529.25  4358.1  526.59  4376.0  525.60
  4381.1  525.75  4429.2  522.88  4436.2  522.03  4441.3  522.34  4496.5  518.67
  4501.5  518.82  4556.7  514.55  4561.8  514.96  4579.7  513.46  4663.7  508.71
  4687.6  503.89  4689.4  503.51  4689.9  502.71  4694.9  502.71  4695.4  503.51
  4786.6  503.51  5222.5  503.53  5232.5  505.26  5252.5  511.28  5262.8  513.46
  5281.8  515.61  5302.5  517.21  5332.5  518.58  5372.5  518.99  5397.8  518.01
#Mann=6,-1,0
  4246.2    0.16       0  4687.6    0.07       0  4689.4   0.033       0
  4695.4    0.07       0  4786.6    0.05       0  5281.8    0.16       0
Bank Sta=4579.7,5262.8
Exp/Cntr=0.3,0.1

Type RM Length L Ch R = 1,1702,75,75,75
BEGIN DESCRIPTION:
XS3833A
END DESCRIPTION:
XS GIS Cut Line= 3
      2839635.41      7085598.83      2839184.01      7085503.34
      2838563.34      7085490.32
#Sta/Elev= 30
  4219.5  531.58  4250.6  530.91  4332.4  527.36  4358.4  525.22  4457.8  520.23
  4495.9  517.65  4502.4  516.48  4507.5  517.22  4536.8  514.74  4579.4  512.71
  4596.7  511.97  4601.8  512.49  4636.0  510.42  4636.5  509.62  4641.5  509.62
  4642.0  510.42  4663.1  510.59  4699.9  513.26  4719.9  513.69  4829.9  514.63
  4837.6  514.53  4842.6  512.64  4845.0  512.71  4970.0  514.09  5059.6  514.21
  5158.7  513.42  5230.0  513.54  5257.7  516.04  5270.0  517.33  5301.7  518.38
#Mann=7,-1,0
  4219.5    0.16       0  4636.0    0.03       0  4642.0    0.16       0
  4663.1    0.05       0  5059.6    0.07       0  5158.7    0.05       0
  5257.7    0.16       0
Bank Sta=4579.4,4845
Exp/Cntr=0.3,0.1

Type RM Length L Ch R = 1,1627,126,126,126
BEGIN DESCRIPTION:
XS3840A
END DESCRIPTION:
XS GIS Cut Line= 3
      2839166.70      7085425.22      2838854.15      7085425.22
      2838546.03      7085420.88
#Sta/Elev= 30
  4675.3  508.05  4687.0  507.56  4707.0  506.03  4727.0  505.93  4757.0  503.27
  4827.0  498.43  4877.0  496.10  4912.1  494.96  4924.2  494.68  4957.0  494.25
  4989.9  494.37  4997.0  493.96  5035.0  494.08  5064.0  493.88  5064.5  493.08
  5069.5  493.08  5070.0  493.88  5107.0  494.49  5112.4  494.96  5127.0  496.10
  5134.0  497.33  5147.0  499.54  5167.0  504.67  5187.0  508.50  5207.0  512.99
  5217.0  514.62  5233.1  516.38  5257.0  517.92  5267.0  518.05  5296.0  517.25
#Mann=7,-1,0
  4675.3    0.16       0  4924.2    0.05       0  5035.0    0.07       0
  5064.0    0.03       0  5070.0    0.07       0  5134.0    0.05       0
  5233.1    0.16       0
Bank Sta=4912.1,5112.4
Exp/Cntr=0.3,0.1

Type RM Length L Ch R = 1,1501,239,239,239
BEGIN DESCRIPTION:
XS3839A
END DESCRIPTION:
XS GIS Cut Line= 3
      2839110.20      7085308.03      2838845.47      7085303.69
      2838585.08      7085312.37
#Sta/Elev= 30
  4727.6  500.00  4742.8  499.86  4752.8  499.48  4762.8  498.04  4792.8  497.45
  4832.8  495.58  4872.8  494.29  4952.8  492.72  4972.8  492.60  4983.3  492.24
  4990.1  490.40  5012.8  490.32  5022.9  491.14  5062.9  490.36  5069.9  489.83
  5070.4  489.03  5075.4  489.03  5075.9  489.83  5092.4  492.24  5102.9  494.41
  5122.9  503.37  5132.9  506.54  5142.9  508.57  5172.9  513.36  5179.9  514.40
  5184.9  513.92  5192.9  514.97  5203.0  515.16  5223.0  516.60  5252.9  516.18
#Mann=3,-1,0
  4727.6    0.16       0  5069.9    0.07       0  5075.9    0.16       0
Bank Sta=4983.3,5092.4
Exp/Cntr=0.3,0.1

Type RM Length L Ch R = 1,1262,229,229,229
BEGIN DESCRIPTION:
XS3838A
END DESCRIPTION:
XS GIS Cut Line= 3
      2839236.12      7085073.65      2838849.81      7085073.65
      2838629.25      7085147.17
#Sta/Elev= 30
  4615.7  511.98  4676.8  507.25  4756.8  499.61  4766.8  497.84  4856.8  493.68
  4894.4  489.18  4936.8  487.65  4976.8  487.91  4986.8  484.09  4993.8  483.75
  4994.3  482.95  4999.3  482.95  4999.8  483.75  5001.9  487.46  5017.2  488.38
  5022.5  485.81  5028.2  488.24  5064.1  489.18  5091.4  490.03  5112.1  495.14
  5117.4  494.12  5123.0  498.14  5133.6  501.56  5149.0  504.01  5154.7  506.37
  5180.6  508.96  5186.3  512.06  5207.0  512.47  5212.2  513.45  5234.5  512.77
#Mann=3,-1,0
  4615.7    0.16       0  4993.8    0.07       0  4999.8    0.16       0
Bank Sta=4894.4,5064.1
Exp/Cntr=0.3,0.1

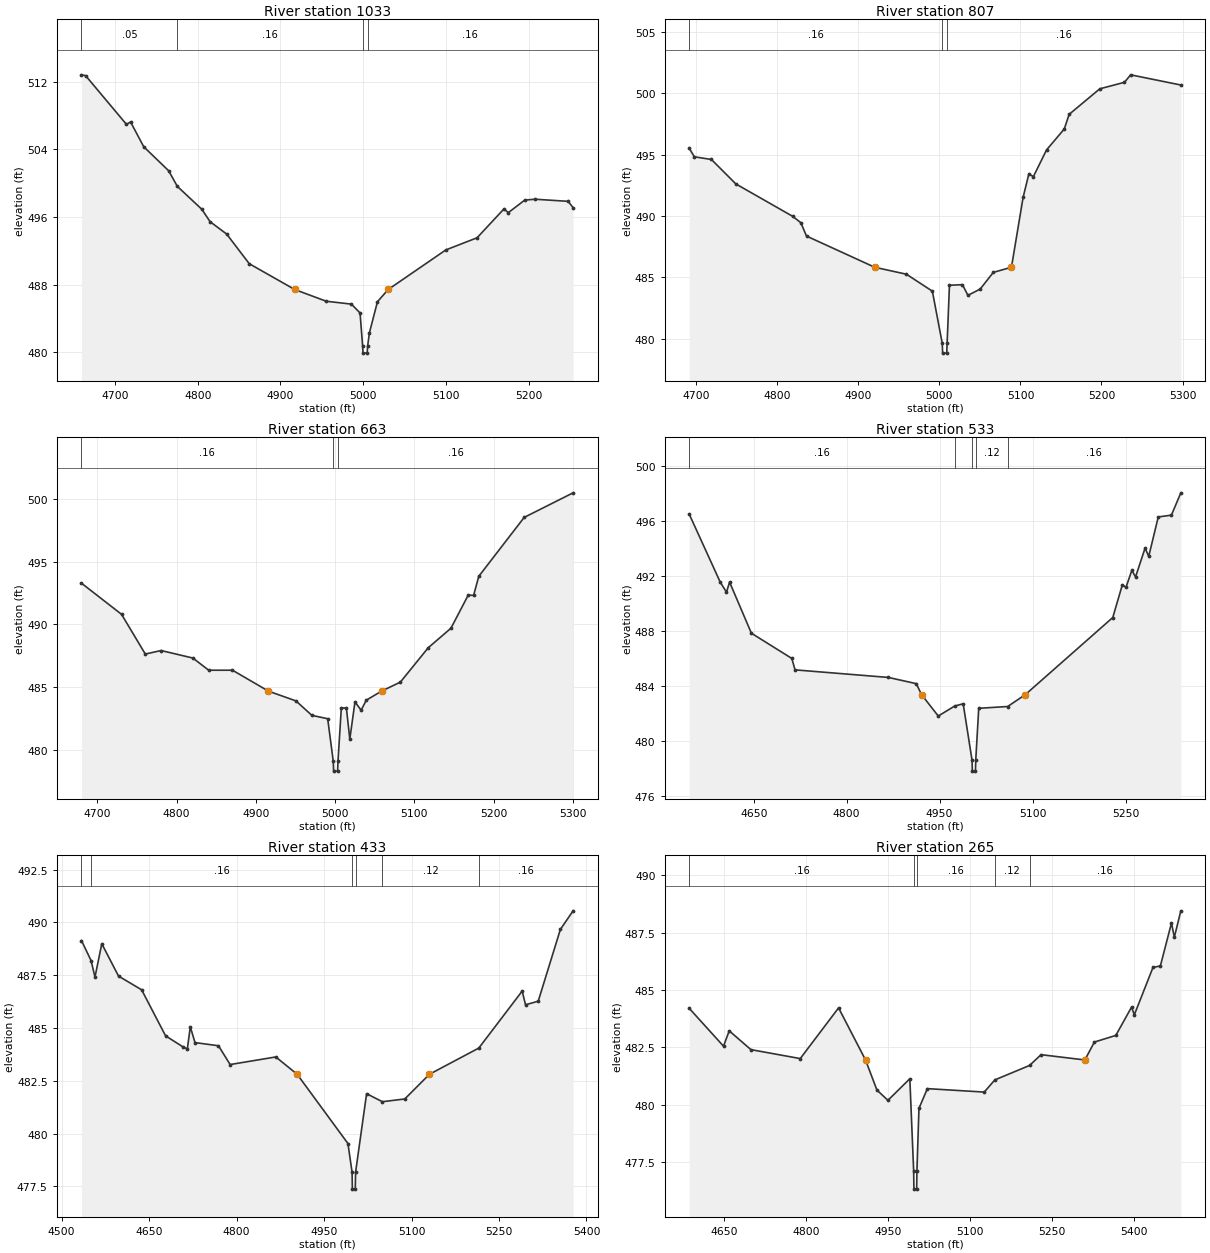
Type RM Length L Ch R = 1,1033,226,226,226
BEGIN DESCRIPTION:
XS3837A
END DESCRIPTION:
XS GIS Cut Line= 3
      2839210.02      7084874.00      2838893.21      7084852.30
      2838629.27      7084934.51
#Sta/Elev= 30
  4659.6  512.82  4664.6  512.72  4713.9  506.96  4718.9  507.24  4734.8  504.31
  4764.9  501.47  4775.4  499.62  4805.0  496.91  4815.0  495.44  4835.0  493.98
  4862.3  490.47  4917.2  487.42  4955.3  486.03  4985.7  485.69  4996.2  484.64
  4999.3  480.69  4999.8  479.89  5004.8  479.89  5005.3  480.69  5007.5  482.30
  5017.2  485.97  5030.2  487.42  5099.8  492.10  5137.6  493.54  5170.1  496.96
  5175.3  496.51  5195.2  498.00  5207.9  498.10  5247.6  497.85  5253.6  497.10
#Mann=4,-1,0
  4659.6    0.05       0  4775.4    0.16       0  4999.3    0.07       0
  5005.3    0.16       0
Bank Sta=4917.2,5030.2
Exp/Cntr=0.3,0.1

Type RM Length L Ch R = 1,807,144,144,144
BEGIN DESCRIPTION:
XS3836A
END DESCRIPTION:
XS GIS Cut Line= 3
      2839162.31      7084609.24      2838867.17      7084630.95
      2838593.78      7084778.49
#Sta/Elev= 30
  4691.3  495.53  4697.6  494.83  4718.7  494.61  4748.8  492.62  4818.9  489.98
  4829.0  489.46  4836.0  488.37  4920.1  485.83  4959.3  485.26  4991.3  483.88
  5003.5  479.63  5004.0  478.83  5009.0  478.83  5009.5  479.63  5012.4  484.36
  5028.4  484.41  5035.2  483.54  5050.3  484.05  5066.5  485.41  5088.9  485.83
  5103.3  491.53  5110.3  493.42  5116.0  493.22  5132.2  495.39  5154.1  497.10
  5160.1  498.29  5197.9  500.37  5228.3  500.90  5236.0  501.51  5297.9  500.68
#Mann=3,-1,0
  4691.3    0.16       0  5003.5    0.07       0  5009.5    0.16       0
Bank Sta=4920.1,5088.9
Exp/Cntr=0.3,0.1

Type RM Length L Ch R = 1,663,130,130,130
BEGIN DESCRIPTION:
XS3835A
END DESCRIPTION:
XS GIS Cut Line= 3
      2839165.43      7084504.07      2838835.57      7084493.65
      2838649.89      7084716.64
#Sta/Elev= 30
  4680.0  493.29  4730.5  490.81  4760.5  487.64  4780.5  487.92  4820.5  487.32
  4840.5  486.35  4870.5  486.35  4915.9  484.68  4950.6  483.90  4970.6  482.75
  4990.6  482.48  4997.6  479.10  4998.1  478.30  5003.1  478.30  5003.6  479.10
  5007.8  483.34  5014.2  483.34  5018.5  480.85  5025.0  483.82  5032.8  483.16
  5039.3  483.96  5058.5  484.68  5082.3  485.40  5117.4  488.14  5146.1  489.70
  5167.9  492.34  5174.7  492.32  5181.2  493.84  5238.5  498.54  5300.2  500.50
#Mann=3,-1,0
  4680.0    0.16       0  4997.6    0.07       0  5003.6    0.16       0
Bank Sta=4915.9,5058.5
Exp/Cntr=0.3,0.1

Type RM Length L Ch R = 1,533,100,100,100
BEGIN DESCRIPTION:
Mapping XS f05b6be9
END DESCRIPTION:
XS GIS Cut Line= 3
      2839274.81      7084323.51      2838815.61      7084369.52
      2838641.28      7084651.71
#Sta/Elev= 30
  4546.0  496.48  4596.1  491.54  4606.1  490.82  4611.1  491.55  4646.3  487.84
  4711.5  486.01  4716.7  485.18  4867.4  484.63  4912.3  484.18  4920.9  483.38
  4947.8  481.83  4974.2  482.55  4988.0  482.72  5002.3  478.63  5002.8  477.83
  5007.8  477.83  5008.3  478.63  5013.1  482.39  5059.8  482.52  5088.2  483.38
  5229.4  488.98  5244.8  491.35  5250.7  491.17  5260.2  492.41  5266.1  491.92
  5281.5  494.02  5287.4  493.42  5302.8  496.28  5324.0  496.41  5339.2  498.03
#Mann=5,-1,0
  4546.0    0.16       0  4974.2    0.12       0  5002.3    0.07       0
  5008.3    0.12       0  5059.8    0.16       0
Bank Sta=4920.9,5088.2
Exp/Cntr=0.3,0.1

Type RM Length L Ch R = 1,433,168,168,168
BEGIN DESCRIPTION:
Mapping XS ae18d3c8
END DESCRIPTION:
XS GIS Cut Line= 3
      2839247.91      7084215.87      2838776.54      7084278.37
      2838600.56      7084601.01
#Sta/Elev= 30
  4534.1  489.14  4550.6  488.19  4557.2  487.41  4568.9  488.99  4597.6  487.46
  4637.2  486.81  4678.3  484.63  4708.5  484.10  4715.6  484.01  4720.7  485.06
  4728.7  484.31  4769.0  484.16  4789.0  483.27  4867.3  483.63  4903.9  482.81
  4991.0  479.53  4998.1  478.17  4998.6  477.37  5003.6  477.37  5004.1  478.17
  5023.0  481.89  5050.0  481.51  5088.5  481.64  5130.8  482.81  5215.4  484.05
  5289.8  486.75  5295.5  486.10  5317.3  486.27  5355.3  489.67  5377.1  490.55
#Mann=6,-1,0
  4534.1    0.12       0  4550.6    0.16       0  4998.1    0.07       0
  5004.1    0.16       0  5050.0    0.12       0  5215.4    0.16       0
Bank Sta=4903.9,5130.8
Exp/Cntr=0.3,0.1

Type RM Length L Ch R = 1,265,0,0,0
BEGIN DESCRIPTION:
UNT 131 in LFCCL Watershed 1.0
END DESCRIPTION:
XS GIS Cut Line= 3
      2839127.59      7084105.77      2838706.58      7084131.81
      2838576.63      7084590.96
#Sta/Elev= 30
  4587.0  484.20  4649.7  482.55  4660.1  483.22  4699.8  482.40  4790.0  482.01
  4860.1  484.22  4909.4  481.95  4930.2  480.64  4950.3  480.19  4990.4  481.13
  4997.4  477.12  4997.9  476.32  5002.9  476.32  5003.4  477.12  5007.1  479.84
  5022.5  480.70  5126.5  480.55  5145.8  481.08  5209.3  481.71  5230.4  482.18
  5310.5  481.95  5327.9  482.73  5367.1  483.02  5395.8  484.25  5401.0  483.92
  5435.0  485.98  5448.6  486.05  5468.9  487.92  5474.1  487.30  5486.0  488.45
#Mann=5,-1,0
  4587.0    0.16       0  4997.4    0.07       0  5003.4    0.16       0
  5145.8    0.12       0  5209.3    0.16       0
Bank Sta=4909.4,5310.5
Exp/Cntr=0.3,0.1

Chan Stop Cuts=-1