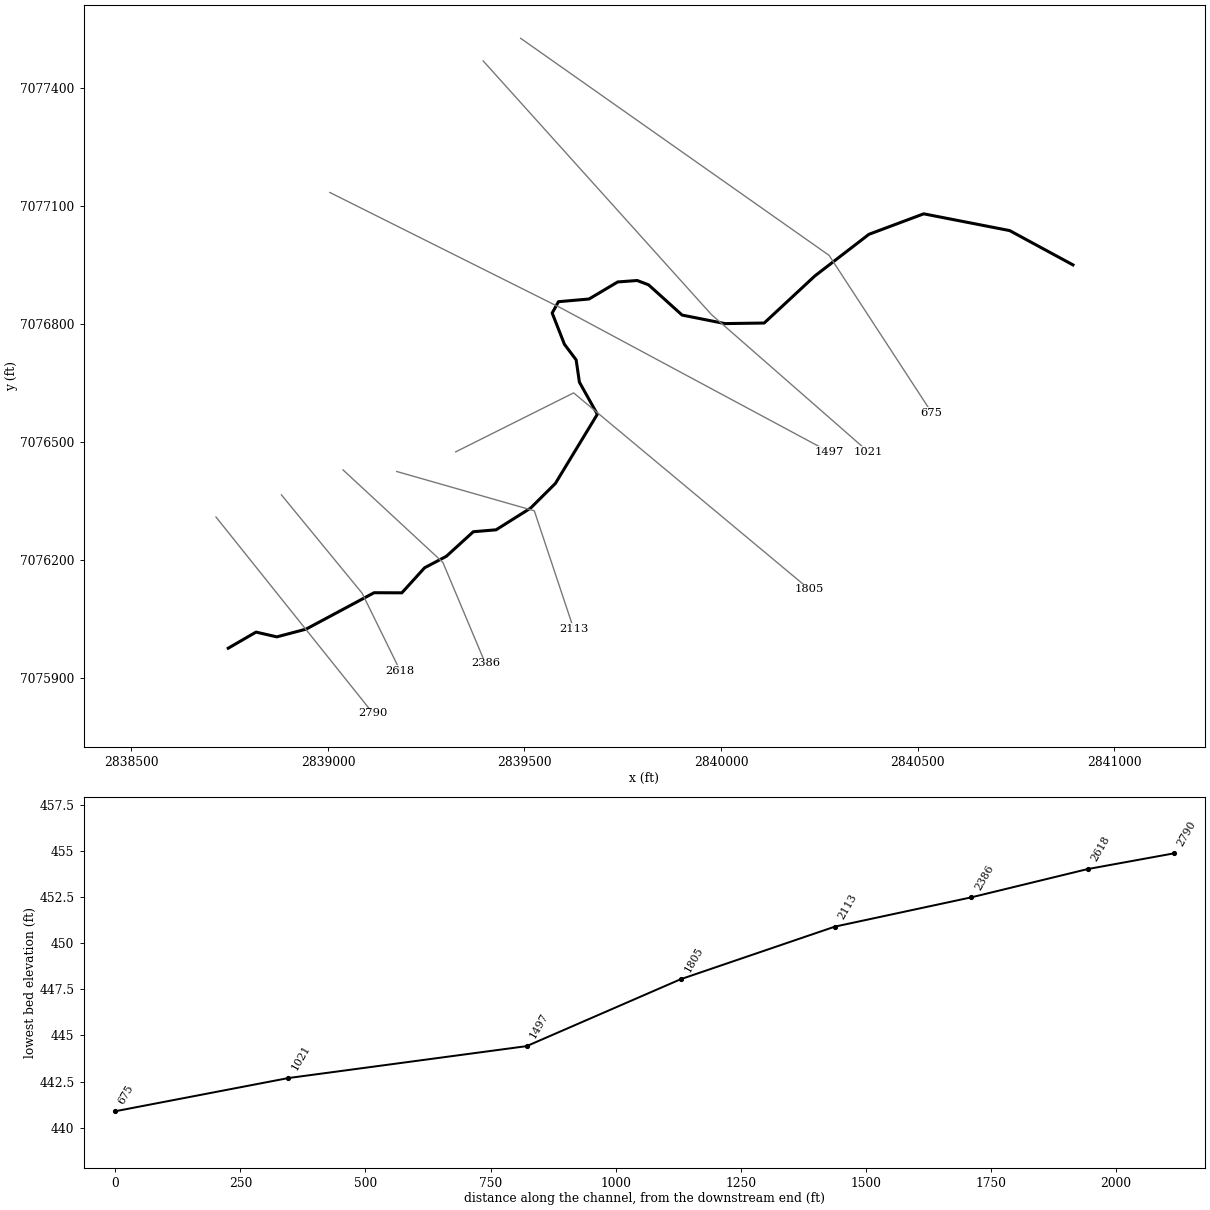
--- UNT 132 in LFCCL Watershed.prj (project) ---

Proj Title=UNT 132 in LFCCL Watershed Base Level Engineering
Current Plan=p01
Default Exp/Contr=0.3,0.1
English Units
Geom File=g01
Flow File=f01
Plan File=p01
BEGIN DESCRIPTION:
UNT 132 in LFCCL Watershed
END DESCRIPTION:

--- UNT 132 in LFCCL Watershed.p01 (plan) ---

Plan Title=Multiple Run
Short Identifier=Multiple
Geom File=g01
Flow File=f01
Subcritical Flow
K Sum by GR= 0
Std Step Tol= 0.01
Critical Tol= 0.01
Num of Std Step Trials= 20
Max Error Tol= 0.3
Flow Tol Ratio= 0.001
Split Flow NTrial= 30
Split Flow Tol= 0.02
Split Flow Ratio= 0.02
Log Output Level= 0
Friction Slope Method= 1
Unsteady Friction Slope Method= 2
Unsteady Bridges Friction Slope Method= 1
Parabolic Critical Depth
Global Vel Dist=  1 , 1 , 1
Global Log Level= 0
CheckData=True
Encroach Param= -1, 0, 0, 0
BEGIN DESCRIPTION:
Multiple Run
END DESCRIPTION:

--- UNT 132 in LFCCL Watershed.f01 (steady flow) ---

Flow Title=Multiple
Number of Profiles=7
Profile Names=10-year,25-year,50-year,1pct_min,100-year,1pct_plu,500-year
River Rch & RM= UNT 132 in LFCCL,Reach-1,2790
     605     809     975     584    1166    2326    1659
Boundary for River Rch & Prof#=UNT 132 in LFCCL,Reach-1,1
Up Type=0
Dn Type=3
Dn Slope=0.005
Boundary for River Rch & Prof#=UNT 132 in LFCCL,Reach-1,2
Up Type=0
Dn Type=3
Dn Slope=0.005
Boundary for River Rch & Prof#=UNT 132 in LFCCL,Reach-1,3
Up Type=0
Dn Type=3
Dn Slope=0.005
Boundary for River Rch & Prof#=UNT 132 in LFCCL,Reach-1,4
Up Type=0
Dn Type=3
Dn Slope=0.005
Boundary for River Rch & Prof#=UNT 132 in LFCCL,Reach-1,5
Up Type=0
Dn Type=3
Dn Slope=0.005
Boundary for River Rch & Prof#=UNT 132 in LFCCL,Reach-1,6
Up Type=0
Dn Type=3
Dn Slope=0.005
Boundary for River Rch & Prof#=UNT 132 in LFCCL,Reach-1,7
Up Type=0
Dn Type=3
Dn Slope=0.005

--- UNT 132 in LFCCL Watershed.g01 (geometry) ---

Geom Title=Existing Conditions

River Reach=UNT 132 in LFCCL,Reach-1
Reach XY= 30
      2838746.16      7075975.38      2838816.92      7076016.39
      2838869.85      7076004.25      2838944.25      7076023.92
      2839117.27      7076116.57      2839187.99      7076116.31
      2839245.83      7076180.05      2839301.16      7076209.25
      2839369.79      7076271.76      2839427.76      7076276.67
      2839515.27      7076331.67      2839578.59      7076394.60
      2839685.37      7076570.69      2839639.71      7076652.39
      2839631.44      7076708.99      2839601.69      7076748.59
      2839570.46      7076828.22      2839586.40      7076857.08
      2839664.19      7076863.91      2839737.19      7076907.33
      2839786.75      7076910.99      2839815.73      7076899.99
      2839900.99      7076823.03      2840010.31      7076801.36
      2840109.91      7076802.79      2840238.96      7076922.72
      2840376.48      7077028.56      2840515.78      7077080.66
      2840734.47      7077038.02      2840895.59      7076950.71

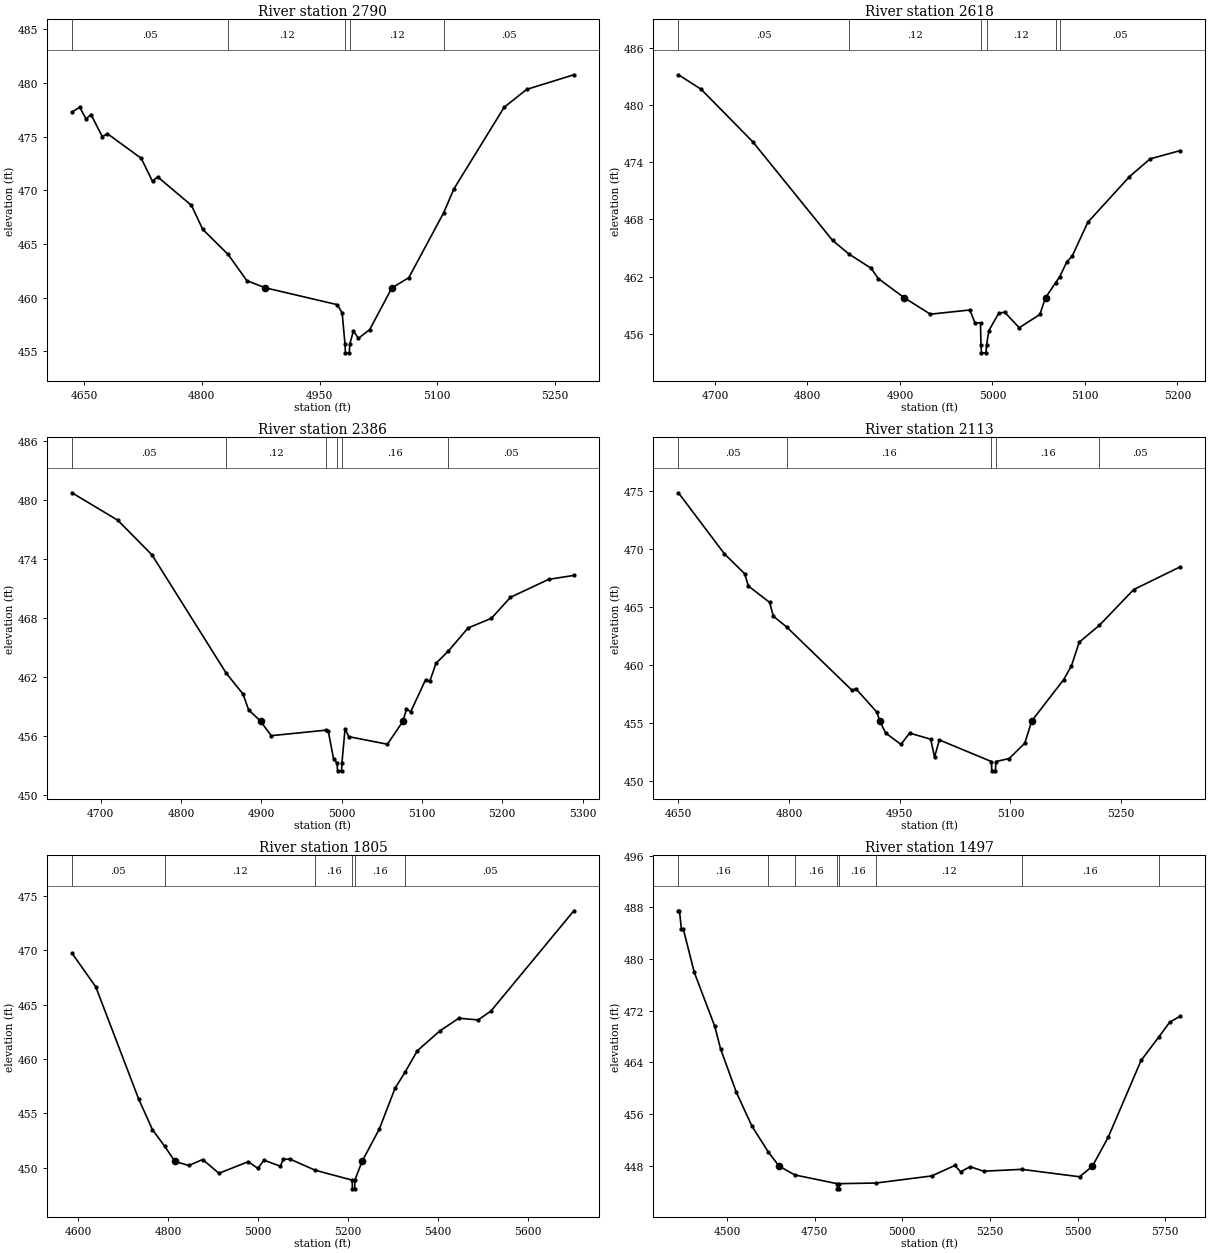
Type RM Length L Ch R = 1,2790,172,172,172
BEGIN DESCRIPTION:
UNT 132 in LFCCL Watershed 6.0
END DESCRIPTION:
XS GIS Cut Line= 3
      2838715.01      7076309.17      2838914.98      7076059.21
      2839114.69      7075809.57
#Sta/Elev= 30
  4634.4  477.29  4644.3  477.75  4652.3  476.66  4658.7  477.07  4673.1  475.00
  4679.5  475.29  4722.7  472.99  4737.1  470.84  4743.5  471.27  4786.7  468.61
  4801.1  466.37  4833.5  464.03  4857.4  461.59  4880.8  460.93  4972.4  459.36
  4978.8  458.61  4982.5  455.67  4983.0  454.87  4988.0  454.87  4988.5  455.67
  4993.2  456.90  4999.6  456.22  5014.0  457.04  5042.3  460.93  5063.7  461.86
  5108.2  467.91  5121.3  470.14  5185.3  477.74  5214.1  479.41  5274.2  480.77
#Mann=5,-1,0
  4634.4    0.05       0  4833.5    0.12       0  4982.5    0.07       0
  4988.5    0.12       0  5108.2    0.05       0
Bank Sta=4880.8,5042.3
Exp/Cntr=0.3,0.1

Type RM Length L Ch R = 1,2618,232,232,232
BEGIN DESCRIPTION:
XS3841A
END DESCRIPTION:
XS GIS Cut Line= 3
      2838881.50      7076365.52      2839086.91      7076115.29
      2839183.39      7075918.62
#Sta/Elev= 30
  4660.4  483.15  4685.0  481.63  4741.0  476.11  4827.1  465.80  4845.1  464.35
  4868.7  462.89  4876.6  461.80  4904.5  459.80  4932.8  458.07  4975.6  458.51
  4981.1  457.16  4987.1  457.16  4987.6  454.82  4988.1  454.02  4993.1  454.02
  4993.6  454.82  4996.2  456.36  5006.7  458.15  5013.1  458.29  5029.0  456.65
  5051.3  458.04  5057.4  459.80  5068.3  461.36  5072.7  461.98  5080.6  463.58
  5086.1  464.12  5103.1  467.69  5148.0  472.46  5170.5  474.34  5203.2  475.21
#Mann=6,-1,0
  4660.4    0.05       0  4845.1    0.12       0  4987.6    0.07       0
  4993.6    0.12       0  5068.3    0.16       0  5072.7    0.05       0
Bank Sta=4904.5,5057.4
Exp/Cntr=0.3,0.1

Type RM Length L Ch R = 1,2386,273,273,273
BEGIN DESCRIPTION:
XS3842A
END DESCRIPTION:
XS GIS Cut Line= 3
      2839038.33      7076429.06      2839292.35      7076193.73
      2839400.34      7075936.77
#Sta/Elev= 30
  4664.2  480.72  4721.3  477.93  4763.9  474.41  4856.5  462.38  4877.2  460.29
  4884.1  458.70  4899.1  457.52  4912.4  456.06  4980.5  456.62  4983.3  456.54
  4990.1  453.66  4994.4  453.29  4994.9  452.49  4999.9  452.49  5000.4  453.29
  5004.3  456.76  5008.9  455.96  5057.0  455.19  5076.4  457.52  5080.7  458.74
  5086.1  458.50  5104.5  461.73  5109.9  461.61  5117.6  463.41  5132.9  464.65
  5157.4  466.99  5186.6  467.98  5210.3  470.11  5257.8  471.93  5289.2  472.33
#Mann=6,-1,0
  4664.2    0.05       0  4856.5    0.12       0  4980.5    0.16       0
  4994.4    0.07       0  5000.4    0.16       0  5132.9    0.05       0
Bank Sta=4899.1,5076.4
Exp/Cntr=0.3,0.1

Type RM Length L Ch R = 1,2113,308,308,308
BEGIN DESCRIPTION:
UNT 132 in LFCCL Watershed 5.0
END DESCRIPTION:
XS GIS Cut Line= 3
      2839175.03      7076424.99      2839525.00      7076325.00
      2839625.00      7076025.00
#Sta/Elev= 30
  4650.1  474.83  4712.5  469.57  4739.8  467.87  4745.0  466.80  4773.6  465.40
  4778.8  464.21  4796.6  463.29  4885.4  457.83  4890.6  457.97  4919.2  455.94
  4922.9  455.20  4930.9  454.16  4951.7  453.17  4963.4  454.15  4992.0  453.62
  4997.2  452.08  5003.7  453.56  5074.3  451.70  5074.8  450.90  5079.8  450.90
  5080.3  451.70  5098.4  451.96  5119.5  453.28  5129.0  455.20  5172.2  458.75
  5182.7  459.93  5193.3  461.97  5220.7  463.43  5267.1  466.50  5330.3  468.46
#Mann=5,-1,0
  4650.1    0.05       0  4796.6    0.16       0  5074.3    0.07       0
  5080.3    0.16       0  5220.7    0.05       0
Bank Sta=4922.9,5129
Exp/Cntr=0.3,0.1

Type RM Length L Ch R = 1,1805,308,308,308
BEGIN DESCRIPTION:
UNT 132 in LFCCL Watershed 4.0
END DESCRIPTION:
XS GIS Cut Line= 3
      2839325.00      7076475.00      2839625.00      7076625.00
      2840224.97      7076125.02
#Sta/Elev= 30
  4586.2  469.75  4639.3  466.64  4734.3  456.35  4765.1  453.51  4792.7  451.95
  4815.4  450.57  4846.1  450.20  4876.9  450.75  4913.2  449.48  4978.2  450.55
  4999.7  449.94  5013.4  450.69  5049.8  450.13  5056.3  450.76  5070.7  450.80
  5126.8  449.77  5209.5  448.85  5210.0  448.05  5215.0  448.05  5215.5  448.85
  5231.4  450.57  5269.8  453.55  5305.0  457.32  5327.0  458.78  5354.4  460.76
  5403.9  462.57  5446.8  463.76  5489.8  463.60  5518.4  464.43  5702.6  473.65
#Mann=6,-1,0
  4586.2    0.05       0  4792.7    0.12       0  5126.8    0.16       0
  5209.5    0.07       0  5215.5    0.16       0  5327.0    0.05       0
Bank Sta=4815.4,5231.4
Exp/Cntr=0.3,0.1

Type RM Length L Ch R = 1,1497,476,476,476
BEGIN DESCRIPTION:
UNT 132 in LFCCL Watershed 3.0
END DESCRIPTION:
XS GIS Cut Line= 3
      2839004.73      7077135.00      2839594.90      7076839.91
      2840274.96      7076475.02
#Sta/Elev= 30
  4361.5  487.49  4364.4  487.49  4370.0  484.67  4375.6  484.64  4406.5  477.99
  4465.1  469.60  4481.8  466.10  4526.6  459.39  4571.3  454.12  4617.6  450.15
  4649.1  447.92  4693.6  446.57  4814.2  445.22  4814.7  444.42  4819.7  444.42
  4820.2  445.22  4924.9  445.32  5084.2  446.42  5150.0  448.04  5166.2  447.06
  5193.8  447.85  5232.0  447.15  5340.5  447.44  5505.7  446.29  5542.4  447.92
  5587.7  452.45  5681.1  464.30  5731.0  467.89  5763.1  470.25  5793.1  471.16
#Mann=8,-1,0
  4361.5    0.16       0  4617.6    0.12       0  4693.6    0.16       0
  4814.2    0.07       0  4820.2    0.16       0  4924.9    0.12       0
  5340.5    0.16       0  5731.0    0.05       0
Bank Sta=4649.1,5542.4
Exp/Cntr=0.3,0.1

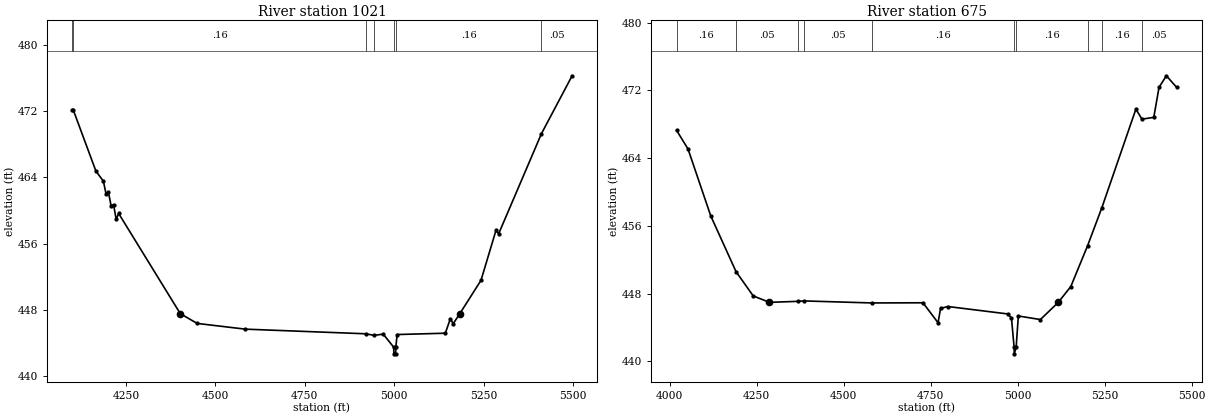
Type RM Length L Ch R = 1,1021,346,346,346
BEGIN DESCRIPTION:
UNT 132 in LFCCL Watershed 2.0
END DESCRIPTION:
XS GIS Cut Line= 3
      2839394.90      7077469.72      2839975.00      7076825.00
      2840375.00      7076475.00
#Sta/Elev= 30
  4098.9  472.13  4103.2  472.08  4166.1  464.75  4187.0  463.53  4194.5  461.99
  4201.2  462.19  4208.7  460.54  4215.4  460.71  4222.9  458.91  4229.6  459.64
  4402.1  447.54  4449.3  446.36  4583.9  445.67  4920.8  445.11  4943.9  444.92
  4969.5  445.07  4998.8  443.49  4999.3  442.69  5004.3  442.69  5004.8  443.49
  5008.4  445.02  5143.2  445.18  5157.4  446.95  5165.0  446.31  5183.7  447.54
  5242.9  451.56  5285.1  457.63  5292.2  457.17  5411.9  469.26  5497.7  476.25
#Mann=7,-1,0
  4098.9    0.05       0  4103.2    0.16       0  4920.8    0.12       0
  4943.9    0.16       0  4998.8    0.07       0  5004.8    0.16       0
  5411.9    0.05       0
Bank Sta=4402.1,5183.7
Exp/Cntr=0.3,0.1

Type RM Length L Ch R = 1,675,0,0,0
BEGIN DESCRIPTION:
UNT 132 in LFCCL Watershed 1.0
END DESCRIPTION:
XS GIS Cut Line= 3
      2839490.31      7077527.19      2840275.00      7076975.00
      2840536.14      7076574.76
#Sta/Elev= 30
  4019.8  467.30  4052.9  465.08  4118.2  457.18  4190.8  450.60  4240.2  447.73
  4287.0  446.97  4368.3  447.09  4385.5  447.14  4581.4  446.90  4728.0  446.92
  4771.4  444.56  4778.5  446.25  4799.4  446.48  4971.9  445.60  4982.3  445.12
  4989.8  441.69  4990.3  440.89  4995.8  441.69  5002.0  445.36  5065.3  444.94
  5116.8  446.97  5152.8  448.84  5201.0  453.66  5242.2  458.17  5339.8  469.79
  5357.2  468.61  5391.2  468.82  5406.3  472.37  5427.4  473.73  5457.2  472.35
#Mann=10,-1,0
  4019.8    0.16       0  4190.8    0.05       0  4368.3    0.16       0
  4385.5    0.05       0  4581.4    0.16       0  4989.8    0.07       0
  4995.8    0.16       0  5201.0    0.12       0  5242.2    0.16       0
  5357.2    0.05       0
Bank Sta=4287,5116.8
Exp/Cntr=0.3,0.1

Chan Stop Cuts=-1