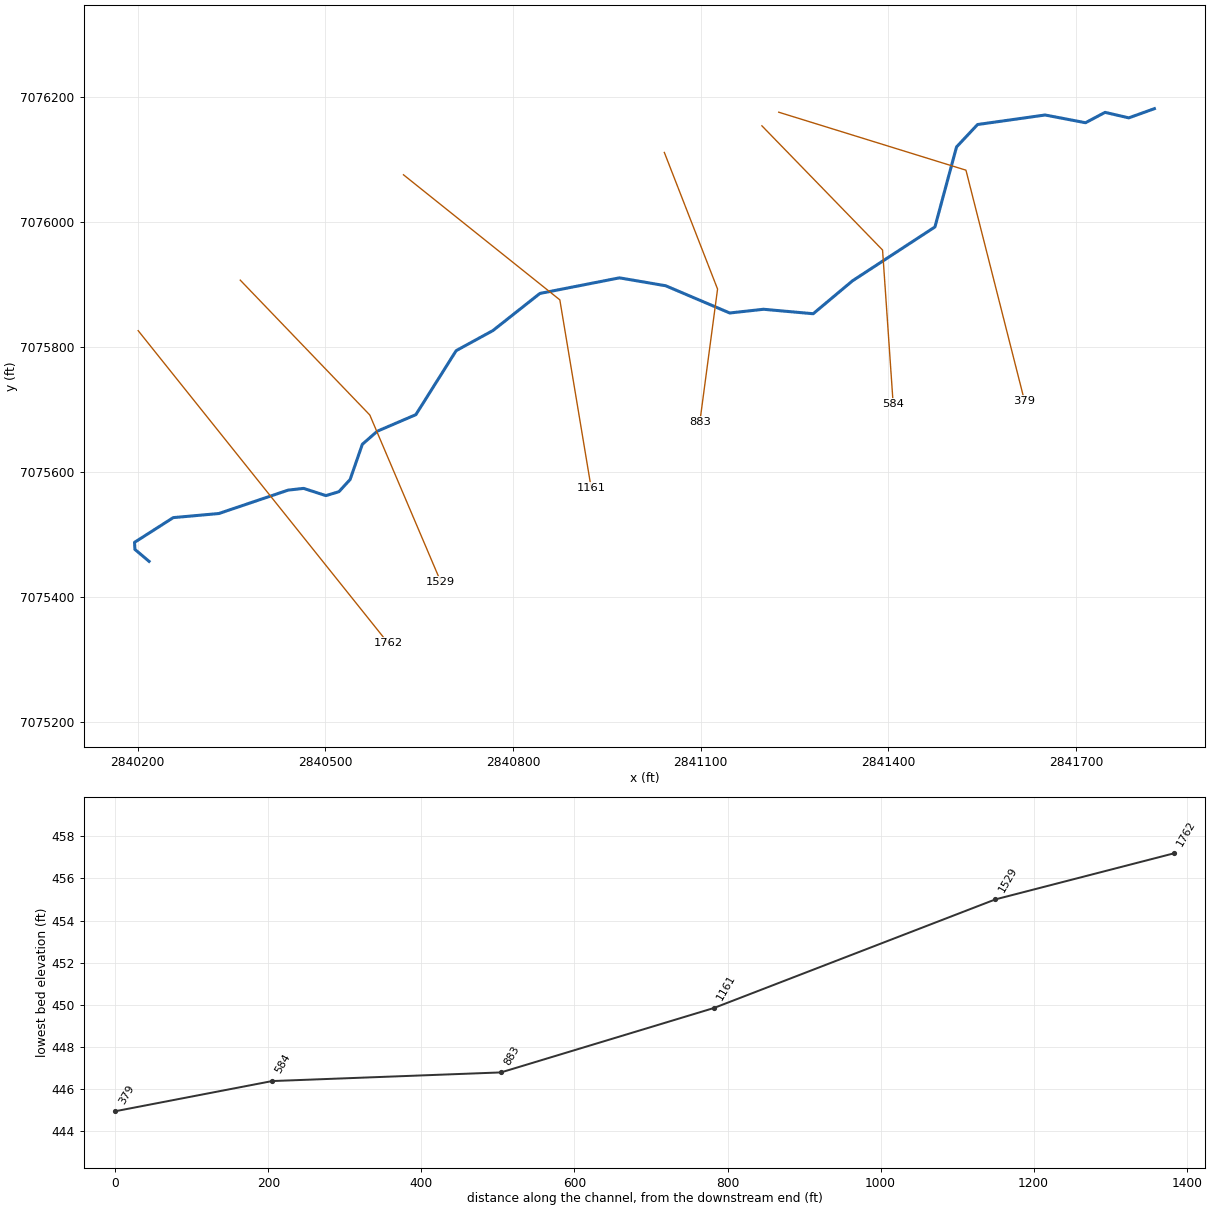
--- UNT 133 in LFCCL Watershed.prj (project) ---

Proj Title=UNT 133 in LFCCL Watershed Base Level Engineering
Current Plan=p01
Default Exp/Contr=0.3,0.1
English Units
Geom File=g01
Flow File=f01
Plan File=p01
BEGIN DESCRIPTION:
UNT 133 in LFCCL Watershed
END DESCRIPTION:

--- UNT 133 in LFCCL Watershed.p01 (plan) ---

Plan Title=Multiple Run
Short Identifier=Multiple
Geom File=g01
Flow File=f01
Subcritical Flow
K Sum by GR= 0
Std Step Tol= 0.01
Critical Tol= 0.01
Num of Std Step Trials= 20
Max Error Tol= 0.3
Flow Tol Ratio= 0.001
Split Flow NTrial= 30
Split Flow Tol= 0.02
Split Flow Ratio= 0.02
Log Output Level= 0
Friction Slope Method= 1
Unsteady Friction Slope Method= 2
Unsteady Bridges Friction Slope Method= 1
Parabolic Critical Depth
Global Vel Dist=  1 , 1 , 1
Global Log Level= 0
CheckData=True
Encroach Param= -1, 0, 0, 0
BEGIN DESCRIPTION:
Multiple Run
END DESCRIPTION:

--- UNT 133 in LFCCL Watershed.f01 (steady flow) ---

Flow Title=Multiple
Number of Profiles=7
Profile Names=10-year,25-year,50-year,1pct_min,100-year,1pct_plu,500-year
River Rch & RM= UNT 133 in LFCCL,Reach-1,1762
     330     422     493     287     573    1144     770
Boundary for River Rch & Prof#=UNT 133 in LFCCL,Reach-1,1
Up Type=0
Dn Type=3
Dn Slope=0.005
Boundary for River Rch & Prof#=UNT 133 in LFCCL,Reach-1,2
Up Type=0
Dn Type=3
Dn Slope=0.005
Boundary for River Rch & Prof#=UNT 133 in LFCCL,Reach-1,3
Up Type=0
Dn Type=3
Dn Slope=0.005
Boundary for River Rch & Prof#=UNT 133 in LFCCL,Reach-1,4
Up Type=0
Dn Type=3
Dn Slope=0.005
Boundary for River Rch & Prof#=UNT 133 in LFCCL,Reach-1,5
Up Type=0
Dn Type=3
Dn Slope=0.005
Boundary for River Rch & Prof#=UNT 133 in LFCCL,Reach-1,6
Up Type=0
Dn Type=3
Dn Slope=0.005
Boundary for River Rch & Prof#=UNT 133 in LFCCL,Reach-1,7
Up Type=0
Dn Type=3
Dn Slope=0.005

--- UNT 133 in LFCCL Watershed.g01 (geometry) ---

Geom Title=Existing Conditions

River Reach=UNT 133 in LFCCL,Reach-1
Reach XY= 30
      2840218.29      7075456.93      2840195.64      7075476.05
      2840195.05      7075487.30      2840256.95      7075526.86
      2840329.87      7075533.42      2840440.52      7075570.79
      2840465.29      7075573.60      2840500.98      7075562.06
      2840521.87      7075568.34      2840539.74      7075587.89
      2840559.24      7075644.07      2840583.05      7075664.94
      2840644.81      7075691.45      2840709.25      7075793.78
      2840768.08      7075825.97      2840843.13      7075885.27
      2840970.24      7075910.20      2841044.26      7075897.55
      2841146.60      7075854.01      2841200.56      7075859.97
      2841280.05      7075852.83      2841342.80      7075905.37
      2841474.70      7075991.59      2841509.23      7076119.50
      2841542.83      7076155.31      2841650.81      7076170.56
      2841715.43      7076158.18      2841746.69      7076174.78
      2841784.58      7076165.96      2841825.59      7076180.71

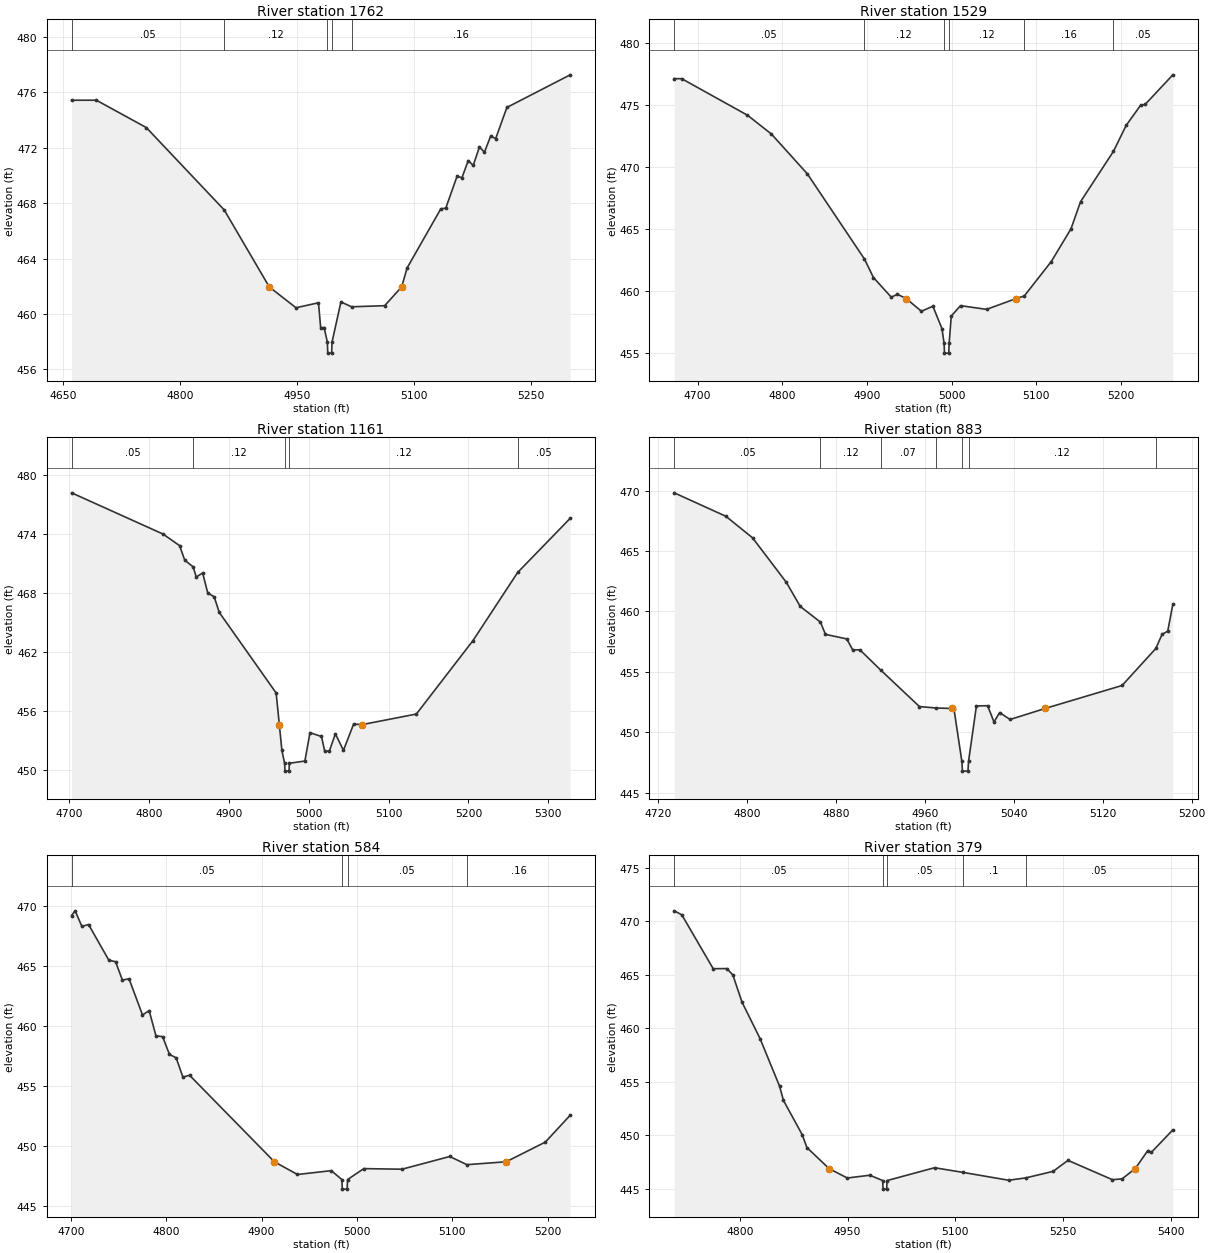
Type RM Length L Ch R = 1,1762,233,233,233
BEGIN DESCRIPTION:
UNT 133 in LFCCL Watershed 3.0
END DESCRIPTION:
XS GIS Cut Line= 3
      2840200.89      7075825.75      2840400.91      7075575.72
      2840600.44      7075326.31
#Sta/Elev= 30
  4661.2  475.41  4693.0  475.41  4757.0  473.44  4857.0  467.50  4914.8  461.95
  4949.1  460.45  4977.9  460.81  4980.7  459.02  4985.1  459.02  4989.3  457.98
  4989.8  457.18  4994.8  457.18  4995.3  457.98  5006.7  460.87  5020.3  460.52
  5062.8  460.60  5084.6  461.95  5091.6  463.32  5134.8  467.58  5141.2  467.63
  5155.6  469.92  5162.0  469.83  5170.0  471.06  5176.4  470.71  5184.4  472.04
  5190.8  471.66  5198.8  472.83  5205.2  472.64  5219.6  474.89  5300.8  477.24
#Mann=5,-1,0
  4661.2    0.05       0  4857.0    0.12       0  4989.3    0.07       0
  4995.3    0.12       0  5020.3    0.16       0
Bank Sta=4914.8,5084.6
Exp/Cntr=0.3,0.1

Type RM Length L Ch R = 1,1529,368,368,368
BEGIN DESCRIPTION:
XS3843A
END DESCRIPTION:
XS GIS Cut Line= 3
      2840364.10      7075906.50      2840571.20      7075690.90
      2840684.65      7075424.29
#Sta/Elev= 30
  4672.4  477.14  4681.2  477.14  4758.9  474.19  4787.2  472.67  4829.6  469.46
  4896.9  462.60  4907.6  461.10  4928.7  459.51  4935.9  459.75  4946.3  459.40
  4964.2  458.38  4977.8  458.78  4988.5  456.98  4991.0  455.80  4991.5  455.00
  4996.5  455.00  4997.0  455.80  4999.5  457.99  5010.4  458.83  5041.2  458.53
  5076.0  459.40  5085.7  459.61  5117.6  462.39  5140.8  465.02  5152.1  467.21
  5191.0  471.28  5206.0  473.37  5223.0  474.99  5228.4  475.06  5261.1  477.45
#Mann=6,-1,0
  4672.4    0.05       0  4896.9    0.12       0  4991.0    0.07       0
  4997.0    0.12       0  5085.7    0.16       0  5191.0    0.05       0
Bank Sta=4946.3,5076
Exp/Cntr=0.3,0.1

Type RM Length L Ch R = 1,1161,278,278,278
BEGIN DESCRIPTION:
UNT 133 in LFCCL Watershed 2.0
END DESCRIPTION:
XS GIS Cut Line= 3
      2840625.01      7076074.99      2840875.00      7075875.00
      2840925.00      7075574.98
#Sta/Elev= 30
  4703.1  478.22  4817.5  474.02  4838.3  472.84  4844.8  471.35  4855.2  470.68
  4859.2  469.64  4867.2  470.05  4873.6  468.00  4881.6  467.63  4888.0  466.03
  4959.2  457.82  4963.2  454.60  4966.4  451.97  4969.8  450.65  4970.3  449.85
  4975.3  449.85  4975.8  450.65  4995.2  450.88  5001.6  453.77  5016.0  453.38
  5020.0  451.89  5025.8  451.89  5033.4  453.65  5043.5  451.97  5056.2  454.64
  5067.3  454.60  5134.8  455.67  5205.7  463.16  5261.6  470.10  5327.4  475.62
#Mann=5,-1,0
  4703.1    0.05       0  4855.2    0.12       0  4969.8    0.07       0
  4975.8    0.12       0  5261.6    0.05       0
Bank Sta=4963.2,5067.3
Exp/Cntr=0.3,0.1

Type RM Length L Ch R = 1,883,299,299,299
BEGIN DESCRIPTION:
XS3845A
END DESCRIPTION:
XS GIS Cut Line= 3
      2841042.07      7076110.67      2841127.16      7075892.29
      2841098.82      7075679.74
#Sta/Elev= 30
  4734.2  469.81  4780.7  467.87  4804.7  466.09  4835.1  462.41  4847.6  460.42
  4865.8  459.12  4870.3  458.11  4889.5  457.73  4894.8  456.83  4901.3  456.83
  4920.0  455.16  4954.9  452.14  4969.7  452.02  4984.4  451.98  4986.0  451.94
  4993.1  447.60  4993.6  446.80  4998.6  446.80  4999.1  447.60  5006.2  452.19
  5016.3  452.21  5022.0  450.86  5027.1  451.64  5036.5  451.07  5068.0  451.98
  5137.3  453.88  5167.7  456.94  5173.3  458.11  5178.4  458.37  5183.0  460.59
#Mann=7,-1,0
  4734.2    0.05       0  4865.8    0.12       0  4920.0    0.07       0
  4969.7    0.12       0  4993.1    0.07       0  4999.1    0.12       0
  5167.7    0.16       0
Bank Sta=4984.4,5068
Exp/Cntr=0.3,0.1

Type RM Length L Ch R = 1,584,205,205,205
BEGIN DESCRIPTION:
XS3844A
END DESCRIPTION:
XS GIS Cut Line= 3
      2841198.06      7076153.26      2841390.95      7075954.70
      2841407.90      7075708.91
#Sta/Elev= 30
  4700.6  469.20  4704.3  469.59  4711.4  468.29  4718.4  468.45  4739.7  465.47
  4746.7  465.35  4753.9  463.82  4760.9  463.92  4775.0  460.91  4782.0  461.27
  4789.1  459.17  4796.1  459.10  4803.3  457.62  4810.3  457.34  4817.4  455.73
  4824.4  455.88  4913.4  448.67  4937.6  447.61  4973.1  447.93  4984.2  447.19
  4984.7  446.39  4989.7  446.39  4990.2  447.19  5007.2  448.10  5047.3  448.05
  5097.4  449.11  5115.4  448.43  5156.6  448.67  5197.7  450.31  5223.8  452.55
#Mann=4,-1,0
  4700.6    0.05       0  4984.2    0.03       0  4990.2    0.05       0
  5115.4    0.16       0
Bank Sta=4913.4,5156.6
Exp/Cntr=0.3,0.1

Type RM Length L Ch R = 1,379,0,0,0
BEGIN DESCRIPTION:
UNT 133 in LFCCL Watershed 1.0
END DESCRIPTION:
XS GIS Cut Line= 3
      2841224.97      7076175.01      2841524.27      7076082.34
      2841617.89      7075713.56
#Sta/Elev= 30
  4708.9  470.98  4719.4  470.61  4763.1  465.57  4782.2  465.58  4790.5  464.98
  4803.1  462.46  4828.3  459.04  4855.5  454.58  4860.9  453.25  4886.9  450.06
  4893.5  448.85  4924.4  446.88  4949.7  446.00  4981.1  446.26  4999.0  445.76
  4999.5  444.96  5004.5  444.96  5005.0  445.76  5071.1  446.96  5110.3  446.53
  5174.2  445.79  5198.0  446.01  5236.1  446.62  5256.8  447.65  5318.7  445.84
  5332.1  445.92  5350.4  446.88  5367.9  448.57  5373.0  448.41  5402.7  450.50
#Mann=5,-1,0
  4708.9    0.05       0  4999.0    0.03       0  5005.0    0.05       0
  5110.3     0.1       0  5198.0    0.05       0
Bank Sta=4924.4,5350.4
Exp/Cntr=0.3,0.1

Chan Stop Cuts=-1