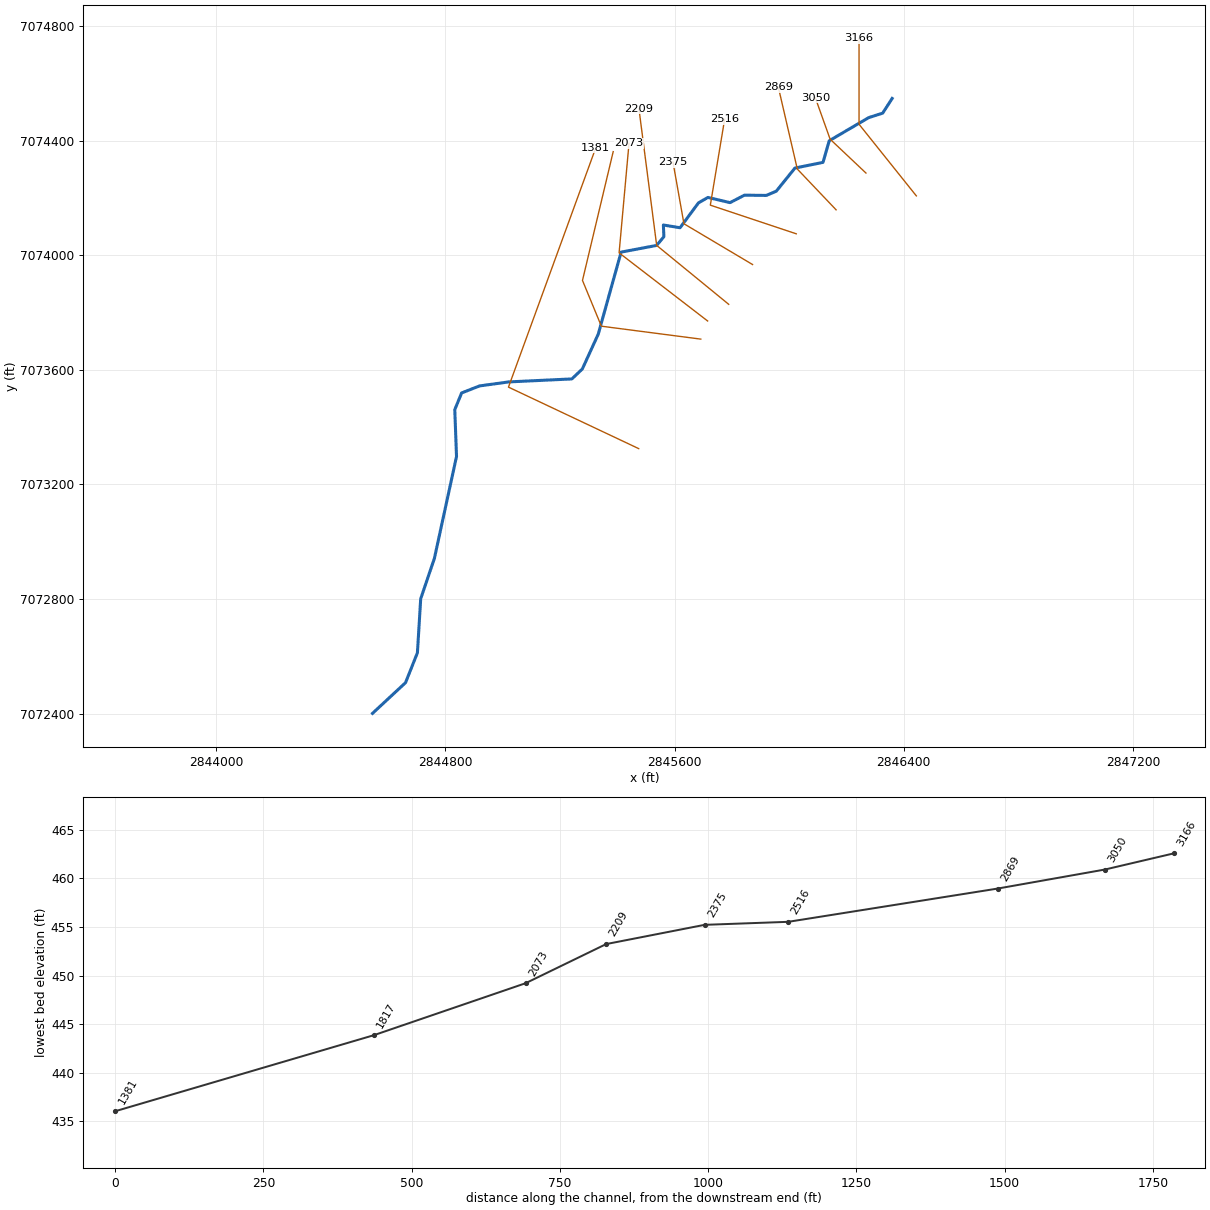
--- UNT 134 in LFCCL Watershed.prj (project) ---

Proj Title=UNT 134 in LFCCL Watershed Base Level Engineering
Current Plan=p01
Default Exp/Contr=0.3,0.1
English Units
Geom File=g01
Flow File=f01
Plan File=p01
BEGIN DESCRIPTION:
UNT 134 in LFCCL Watershed
END DESCRIPTION:

--- UNT 134 in LFCCL Watershed.p01 (plan) ---

Plan Title=Multiple Run
Short Identifier=Multiple
Geom File=g01
Flow File=f01
Subcritical Flow
K Sum by GR= 0
Std Step Tol= 0.01
Critical Tol= 0.01
Num of Std Step Trials= 20
Max Error Tol= 0.3
Flow Tol Ratio= 0.001
Split Flow NTrial= 30
Split Flow Tol= 0.02
Split Flow Ratio= 0.02
Log Output Level= 0
Friction Slope Method= 1
Unsteady Friction Slope Method= 2
Unsteady Bridges Friction Slope Method= 1
Parabolic Critical Depth
Global Vel Dist=  1 , 1 , 1
Global Log Level= 0
CheckData=True
Encroach Param= -1, 0, 0, 0
BEGIN DESCRIPTION:
Multiple Run
END DESCRIPTION:

--- UNT 134 in LFCCL Watershed.f01 (steady flow) ---

Flow Title=Multiple
Number of Profiles=7
Profile Names=10-year,25-year,50-year,1pct_min,100-year,1pct_plu,500-year
River Rch & RM= UNT 134 in LFCCL,Reach-1,3166
     483     638     762     453     904    1804    1267
Boundary for River Rch & Prof#=UNT 134 in LFCCL,Reach-1,1
Up Type=0
Dn Type=3
Dn Slope=0.005
Boundary for River Rch & Prof#=UNT 134 in LFCCL,Reach-1,2
Up Type=0
Dn Type=3
Dn Slope=0.005
Boundary for River Rch & Prof#=UNT 134 in LFCCL,Reach-1,3
Up Type=0
Dn Type=3
Dn Slope=0.005
Boundary for River Rch & Prof#=UNT 134 in LFCCL,Reach-1,4
Up Type=0
Dn Type=3
Dn Slope=0.005
Boundary for River Rch & Prof#=UNT 134 in LFCCL,Reach-1,5
Up Type=0
Dn Type=3
Dn Slope=0.005
Boundary for River Rch & Prof#=UNT 134 in LFCCL,Reach-1,6
Up Type=0
Dn Type=3
Dn Slope=0.005
Boundary for River Rch & Prof#=UNT 134 in LFCCL,Reach-1,7
Up Type=0
Dn Type=3
Dn Slope=0.005

--- UNT 134 in LFCCL Watershed.g01 (geometry) ---

Geom Title=Existing Conditions

River Reach=UNT 134 in LFCCL,Reach-1
Reach XY= 30
      2846359.87      7074547.64      2846326.75      7074496.29
      2846278.14      7074480.67      2846140.12      7074399.94
      2846118.42      7074324.42      2846020.33      7074304.45
      2845955.22      7074223.72      2845920.50      7074208.97
      2845844.11      7074209.84      2845793.76      7074183.79
      2845716.51      7074202.02      2845683.52      7074182.93
      2845619.28      7074096.12      2845561.12      7074105.67
      2845562.86      7074064.87      2845537.69      7074034.49
      2845413.55      7074011.05      2845333.69      7073724.59
      2845278.14      7073603.06      2845241.68      7073568.34
      2845021.19      7073557.93      2844919.28      7073543.86
      2844856.78      7073519.38      2844832.83      7073461.05
      2844838.90      7073297.51      2844761.64      7072941.61
      2844713.90      7072800.98      2844702.35      7072612.05
      2844660.86      7072507.79      2844545.59      7072400.71

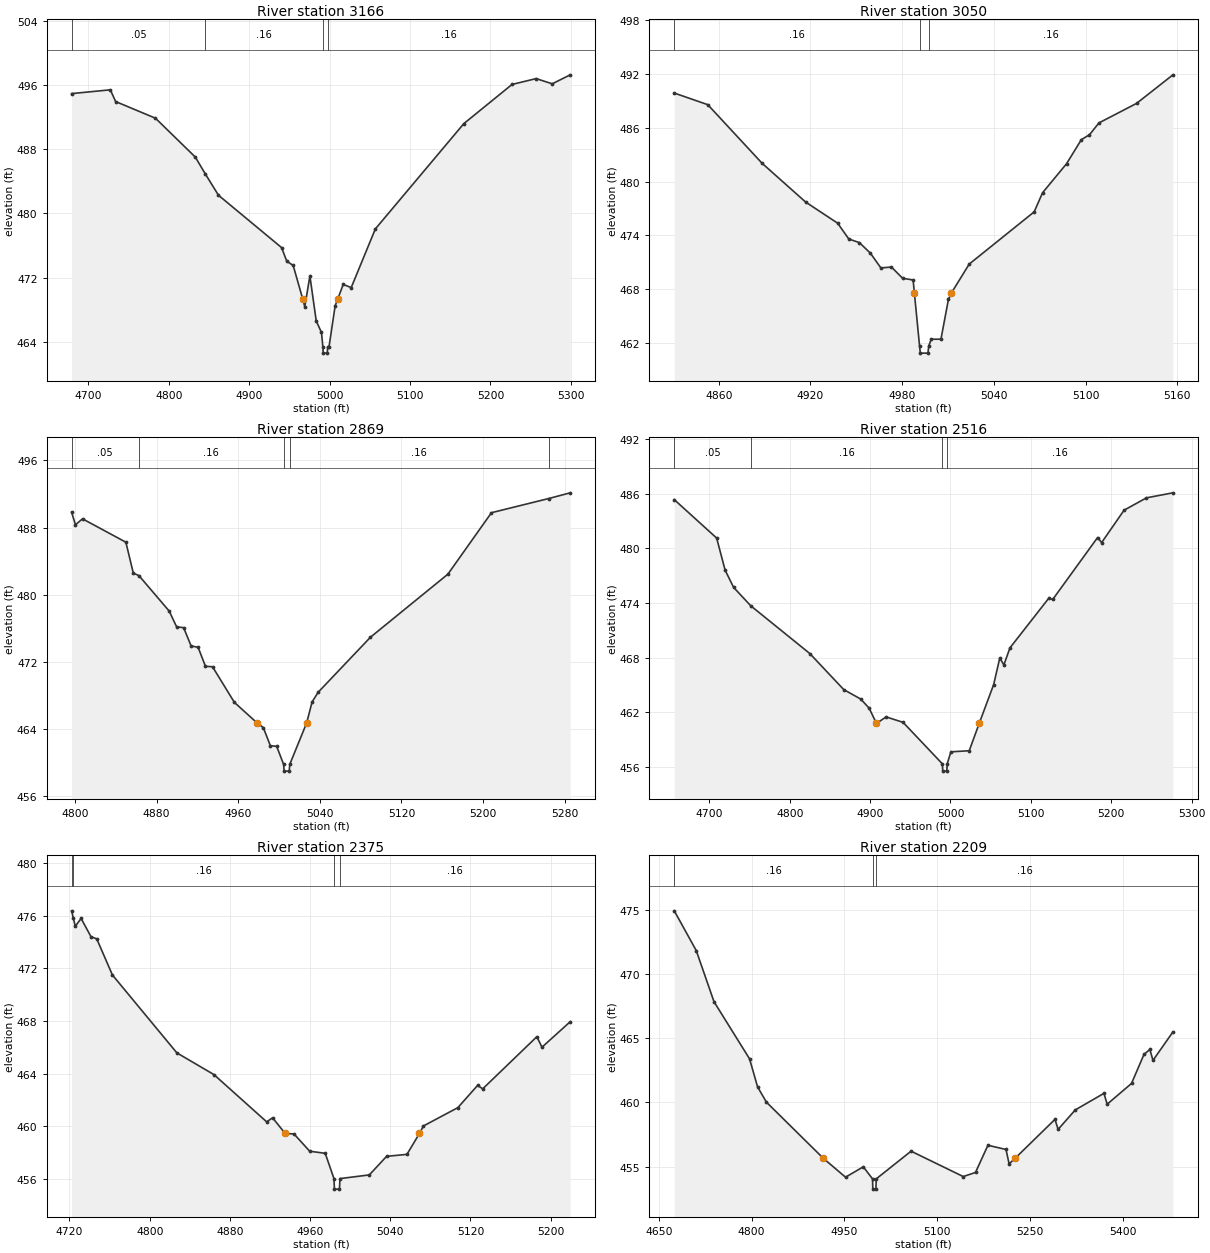
Type RM Length L Ch R = 1,3166,116,116,116
BEGIN DESCRIPTION:
UNT 134 in LFCCL Watershed 3.0
END DESCRIPTION:
XS GIS Cut Line= 3
      2846444.20      7074207.36      2846244.18      7074457.38
      2846244.18      7074757.39
#Sta/Elev= 30
  4679.0  494.94  4727.2  495.41  4733.7  493.95  4783.3  491.87  4832.9  487.02
  4845.3  484.92  4861.7  482.26  4940.2  475.73  4946.6  474.04  4954.6  473.50
  4966.6  469.28  4969.0  468.35  4975.4  472.19  4983.3  466.57  4989.8  465.15
  4991.5  463.37  4992.0  462.57  4997.0  462.57  4997.5  463.37  4999.2  463.37
  5006.8  468.47  5009.9  469.28  5016.8  471.13  5026.8  470.75  5056.8  478.06
  5166.8  491.19  5226.8  496.08  5256.8  496.81  5276.8  496.16  5299.2  497.28
#Mann=4,-1,0
  4679.0    0.05       0  4845.3    0.16       0  4991.5    0.07       0
  4997.5    0.16       0
Bank Sta=4966.6,5009.9
Exp/Cntr=0.3,0.1

Type RM Length L Ch R = 1,3050,181,181,181
BEGIN DESCRIPTION:
XS3850A
END DESCRIPTION:
XS GIS Cut Line= 3
      2846268.29      7074287.14      2846143.26      7074405.21
      2846091.36      7074550.55
#Sta/Elev= 30
  4830.9  489.85  4852.8  488.56  4888.4  482.03  4916.8  477.73  4937.8  475.37
  4945.1  473.61  4952.0  473.21  4959.2  472.04  4966.1  470.39  4973.0  470.49
  4980.3  469.24  4987.2  469.05  4988.0  467.62  4991.4  461.71  4991.9  460.91
  4996.9  460.91  4997.4  461.71  4999.1  462.46  5005.4  462.46  5010.3  466.90
  5012.3  467.62  5023.9  470.82  5066.4  476.63  5071.9  478.76  5087.6  481.99
  5097.3  484.67  5102.6  485.21  5108.8  486.53  5133.4  488.70  5157.2  491.88
#Mann=3,-1,0
  4830.9    0.16       0  4991.4    0.07       0  4997.4    0.16       0
Bank Sta=4988,5012.3
Exp/Cntr=0.3,0.1

Type RM Length L Ch R = 1,2869,353,353,353
BEGIN DESCRIPTION:
XS3848A
END DESCRIPTION:
XS GIS Cut Line= 3
      2846164.08      7074158.71      2846028.68      7074301.05
      2845962.71      7074585.76
#Sta/Elev= 30
  4796.7  489.83  4800.5  488.33  4807.4  489.04  4849.9  486.25  4857.2  482.55
  4862.6  482.28  4892.4  478.03  4899.6  476.16  4906.5  476.06  4913.8  473.89
  4920.7  473.71  4927.9  471.45  4934.8  471.40  4956.3  467.14  4978.4  464.71
  4984.6  464.14  4991.5  461.98  4997.7  461.91  5004.5  459.75  5005.0  458.95
  5010.0  458.95  5010.5  459.75  5027.1  464.71  5032.4  467.20  5038.3  468.35
  5089.6  474.92  5165.5  482.44  5208.2  489.77  5264.3  491.46  5285.4  492.14
#Mann=5,-1,0
  4796.7    0.05       0  4862.6    0.16       0  5004.5    0.07       0
  5010.5    0.16       0  5264.3    0.05       0
Bank Sta=4978.4,5027.1
Exp/Cntr=0.3,0.1

Type RM Length L Ch R = 1,2516,141,141,141
BEGIN DESCRIPTION:
UNT 134 in LFCCL Watershed 2.0
END DESCRIPTION:
XS GIS Cut Line= 3
      2846024.98      7074075.01      2845725.00      7074175.00
      2845774.99      7074474.96
#Sta/Elev= 30
  4656.4  485.36  4709.1  481.14  4719.6  477.62  4730.2  475.72  4751.5  473.70
  4825.0  468.45  4867.2  464.49  4888.3  463.45  4898.8  462.45  4907.9  460.77
  4919.9  461.49  4941.0  460.89  4989.9  456.33  4990.4  455.53  4995.4  455.53
  4995.9  456.33  5000.5  457.65  5023.3  457.77  5035.7  460.77  5053.7  465.04
  5061.3  467.96  5066.4  467.20  5074.0  469.08  5122.1  474.51  5127.2  474.40
  5183.0  481.20  5188.0  480.64  5215.9  484.20  5243.8  485.56  5276.7  486.11
#Mann=4,-1,0
  4656.4    0.05       0  4751.5    0.16       0  4989.9    0.07       0
  4995.9    0.16       0
Bank Sta=4907.9,5035.7
Exp/Cntr=0.3,0.1

Type RM Length L Ch R = 1,2375,166,166,166
BEGIN DESCRIPTION:
XS3849A
END DESCRIPTION:
XS GIS Cut Line= 3
      2845872.47      7073967.69      2845632.85      7074110.07
      2845594.65      7074325.38
#Sta/Elev= 30
  4722.1  476.36  4723.7  475.85  4725.8  475.19  4731.6  475.78  4741.4  474.40
  4747.2  474.23  4762.8  471.49  4827.1  465.57  4864.1  463.92  4916.7  460.33
  4922.6  460.64  4935.1  459.45  4944.0  459.41  4959.6  458.10  4975.1  457.94
  4983.8  456.02  4984.3  455.22  4989.3  455.22  4989.8  456.02  5019.1  456.30
  5036.3  457.71  5056.6  457.86  5069.1  459.45  5073.1  460.02  5107.4  461.41
  5127.1  463.10  5132.2  462.84  5186.2  466.80  5191.3  466.00  5219.5  467.94
#Mann=4,-1,0
  4722.1    0.05       0  4723.7    0.16       0  4983.8    0.07       0
  4989.8    0.16       0
Bank Sta=4935.1,5069.1
Exp/Cntr=0.3,0.1

Type RM Length L Ch R = 1,2209,136,136,136
BEGIN DESCRIPTION:
XS3847A
END DESCRIPTION:
XS GIS Cut Line= 3
      2845789.09      7073828.83      2845537.69      7074034.49
      2845475.78      7074511.39
#Sta/Elev= 30
  4675.2  474.94  4710.7  471.84  4739.4  467.85  4796.8  463.40  4809.8  461.21
  4824.1  460.02  4916.1  455.64  4951.9  454.17  4980.6  454.98  4995.5  454.04
  4996.0  453.24  5001.0  453.24  5001.5  454.04  5057.8  456.20  5142.1  454.22
  5161.9  454.54  5182.0  456.66  5211.2  456.33  5216.2  455.21  5225.8  455.64
  5290.3  458.68  5295.4  457.90  5323.2  459.42  5369.5  460.71  5374.6  459.86
  5414.0  461.48  5434.1  463.74  5443.6  464.13  5448.7  463.28  5480.9  465.50
#Mann=3,-1,0
  4675.2    0.16       0  4995.5    0.07       0  5001.5    0.16       0
Bank Sta=4916.1,5225.8
Exp/Cntr=0.3,0.1

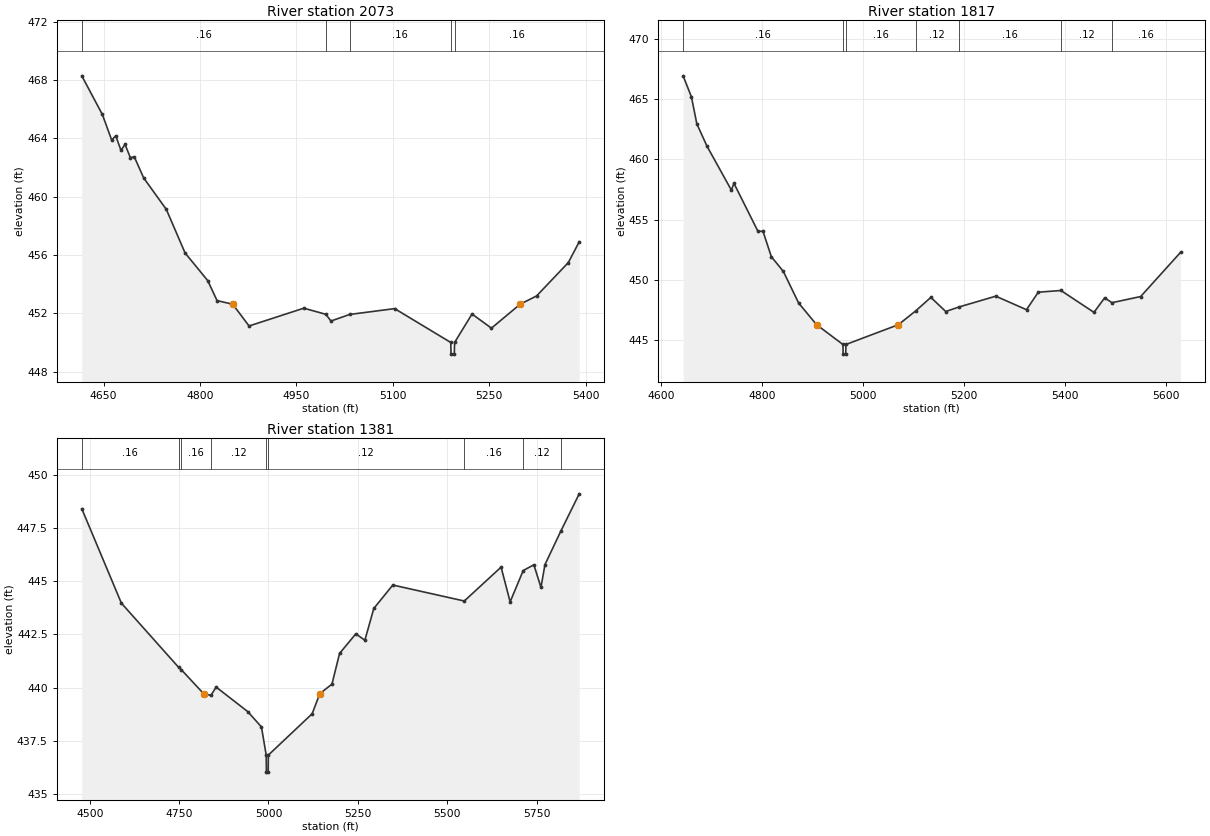
Type RM Length L Ch R = 1,2073,256,256,256
BEGIN DESCRIPTION:
Mapping XS 53b31df1
END DESCRIPTION:
XS GIS Cut Line= 3
      2845715.54      7073770.65      2845406.51      7074008.49
      2845441.14      7074391.07
#Sta/Elev= 30
  4616.0  468.29  4648.0  465.64  4662.5  463.89  4668.8  464.18  4677.0  463.18
  4683.3  463.59  4691.5  462.69  4697.8  462.73  4712.3  461.29  4747.6  459.13
  4776.7  456.15  4812.0  454.25  4826.5  452.88  4850.9  452.63  4876.3  451.14
  4961.5  452.36  4995.8  451.94  5003.8  451.48  5032.9  451.93  5102.9  452.33
  5190.2  450.01  5190.7  449.21  5195.7  449.21  5196.2  450.01  5223.3  451.96
  5253.5  450.99  5298.1  452.63  5323.8  453.20  5373.2  455.49  5390.1  456.91
#Mann=5,-1,0
  4616.0    0.16       0  4995.8    0.12       0  5032.9    0.16       0
  5190.2    0.07       0  5196.2    0.16       0
Bank Sta=4850.9,5298.1
Exp/Cntr=0.3,0.1

Type RM Length L Ch R = 1,1817,436,436,436
BEGIN DESCRIPTION:
XS3846A
END DESCRIPTION:
XS GIS Cut Line= 4
      2845691.86      7073707.30      2845344.65      7073752.43
      2845278.68      7073912.16      2845385.91      7074361.81
#Sta/Elev= 30
  4643.0  466.91  4659.5  465.16  4670.1  462.94  4690.3  461.08  4738.6  457.44
  4743.6  458.01  4791.1  454.04  4801.2  454.03  4817.7  451.93  4841.5  450.71
  4871.8  448.09  4907.3  446.30  4959.5  444.66  4960.0  443.86  4965.0  443.86
  4965.5  444.66  5069.4  446.30  5103.6  447.44  5133.7  448.56  5163.1  447.39
  5189.0  447.76  5262.2  448.66  5323.1  447.54  5346.4  448.99  5391.3  449.13
  5456.7  447.32  5477.9  448.52  5492.4  448.12  5549.2  448.63  5628.2  452.29
#Mann=7,-1,0
  4643.0    0.16       0  4959.5    0.07       0  4965.5    0.16       0
  5103.6    0.12       0  5189.0    0.16       0  5391.3    0.12       0
  5492.4    0.16       0
Bank Sta=4907.3,5069.4
Exp/Cntr=0.3,0.1

Type RM Length L Ch R = 1,1381,0,0,0
BEGIN DESCRIPTION:
UNT 134 in LFCCL Watershed 1.0
END DESCRIPTION:
XS GIS Cut Line= 3
      2845475.01      7073325.00      2845020.30      7073539.71
      2845325.01      7074375.02
#Sta/Elev= 30
  4477.5  448.40  4588.3  443.97  4748.9  440.95  4756.4  440.84  4818.5  439.72
  4838.8  439.64  4853.5  440.03  4942.0  438.88  4980.3  438.16  4993.6  436.84
  4994.1  436.04  4999.1  436.04  4999.6  436.84  5122.2  438.78  5143.5  439.72
  5177.6  440.17  5198.9  441.61  5244.4  442.53  5269.7  442.23  5294.7  443.72
  5347.9  444.82  5547.9  444.07  5650.9  445.66  5676.2  444.03  5712.8  445.50
  5742.6  445.77  5762.5  444.71  5773.7  445.78  5817.8  447.34  5869.5  449.10
#Mann=9,-1,0
  4477.5    0.16       0  4748.9    0.12       0  4756.4    0.16       0
  4838.8    0.12       0  4993.6    0.07       0  4999.6    0.12       0
  5547.9    0.16       0  5712.8    0.12       0  5817.8    0.16       0
Bank Sta=4818.5,5143.5
Exp/Cntr=0.3,0.1

Chan Stop Cuts=-1