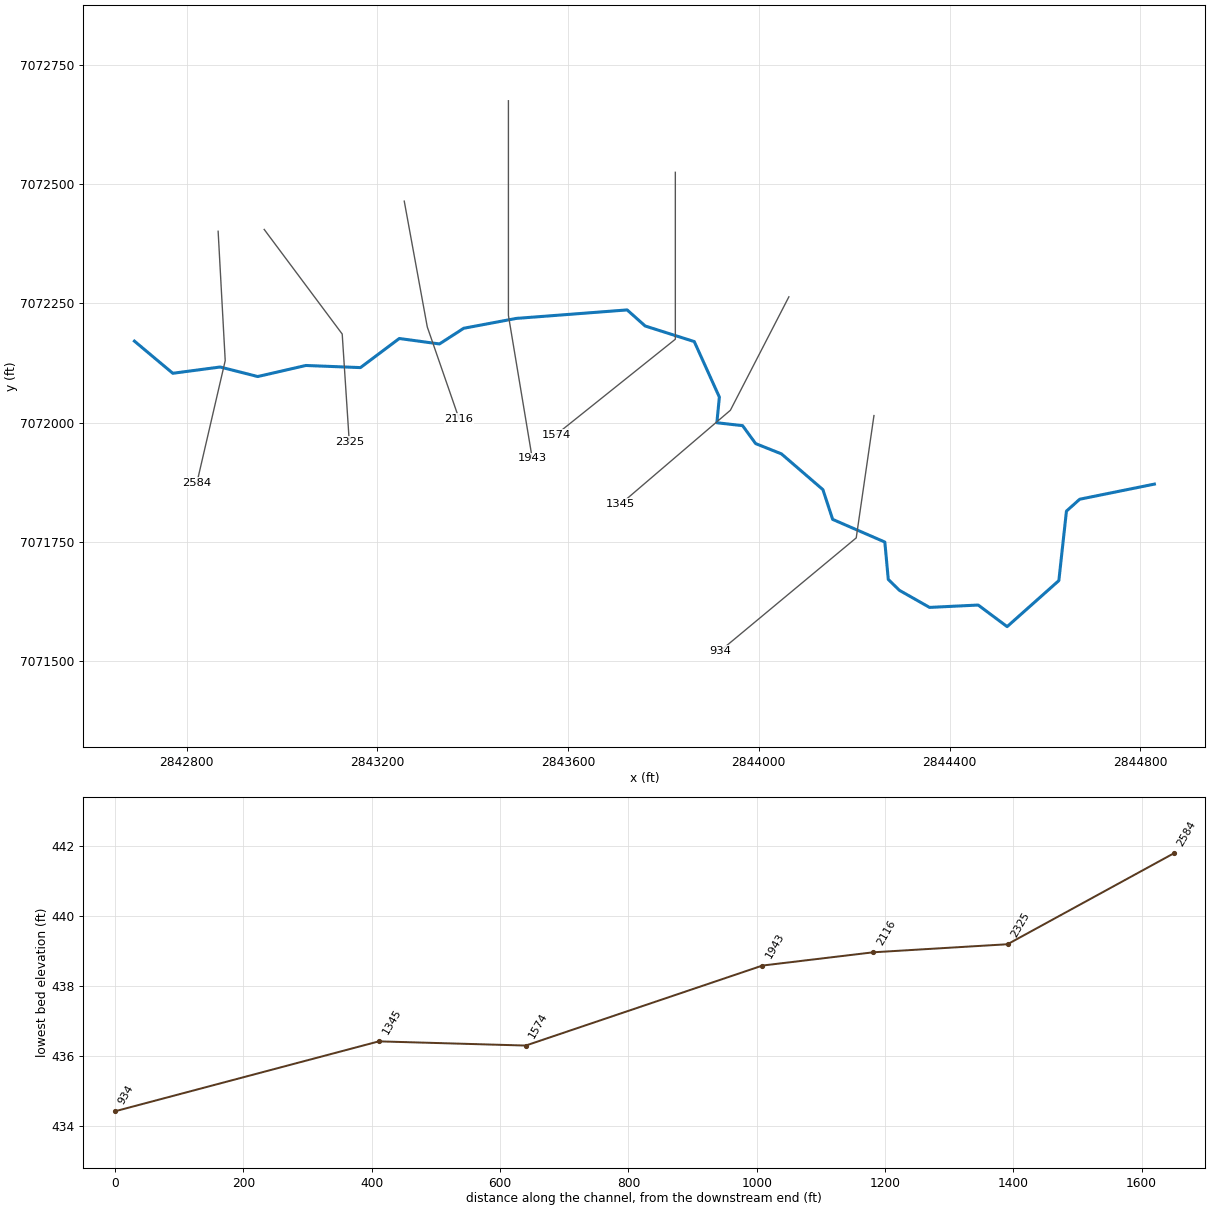
--- UNT 135 in LFCCL Watershed.prj (project) ---

Proj Title=UNT 135 in LFCCL Watershed Base Level Engineering
Current Plan=p01
Default Exp/Contr=0.3,0.1
English Units
Geom File=g01
Flow File=f01
Plan File=p01
BEGIN DESCRIPTION:
UNT 135 in LFCCL Watershed
END DESCRIPTION:

--- UNT 135 in LFCCL Watershed.p01 (plan) ---

Plan Title=Multiple Run
Short Identifier=Multiple
Geom File=g01
Flow File=f01
Subcritical Flow
K Sum by GR= 0
Std Step Tol= 0.01
Critical Tol= 0.01
Num of Std Step Trials= 20
Max Error Tol= 0.3
Flow Tol Ratio= 0.001
Split Flow NTrial= 30
Split Flow Tol= 0.02
Split Flow Ratio= 0.02
Log Output Level= 0
Friction Slope Method= 1
Unsteady Friction Slope Method= 2
Unsteady Bridges Friction Slope Method= 1
Parabolic Critical Depth
Global Vel Dist=  1 , 1 , 1
Global Log Level= 0
CheckData=True
Encroach Param= -1, 0, 0, 0
BEGIN DESCRIPTION:
Multiple Run
END DESCRIPTION:

--- UNT 135 in LFCCL Watershed.f01 (steady flow) ---

Flow Title=Multiple
Number of Profiles=7
Profile Names=10-year,25-year,50-year,1pct_min,100-year,1pct_plu,500-year
River Rch & RM= UNT 135 in LFCCL,Reach-1,2584
     449     586     695     410     818    1632    1127
Boundary for River Rch & Prof#=UNT 135 in LFCCL,Reach-1,1
Up Type=0
Dn Type=3
Dn Slope=0.005
Boundary for River Rch & Prof#=UNT 135 in LFCCL,Reach-1,2
Up Type=0
Dn Type=3
Dn Slope=0.005
Boundary for River Rch & Prof#=UNT 135 in LFCCL,Reach-1,3
Up Type=0
Dn Type=3
Dn Slope=0.005
Boundary for River Rch & Prof#=UNT 135 in LFCCL,Reach-1,4
Up Type=0
Dn Type=3
Dn Slope=0.005
Boundary for River Rch & Prof#=UNT 135 in LFCCL,Reach-1,5
Up Type=0
Dn Type=3
Dn Slope=0.005
Boundary for River Rch & Prof#=UNT 135 in LFCCL,Reach-1,6
Up Type=0
Dn Type=3
Dn Slope=0.005
Boundary for River Rch & Prof#=UNT 135 in LFCCL,Reach-1,7
Up Type=0
Dn Type=3
Dn Slope=0.005

--- UNT 135 in LFCCL Watershed.g01 (geometry) ---

Geom Title=Existing Conditions

River Reach=UNT 135 in LFCCL,Reach-1
Reach XY= 30
      2842690.78      7072171.04      2842771.27      7072103.60
      2842870.56      7072116.75      2842949.36      7072096.79
      2843050.26      7072119.96      2843164.78      7072115.51
      2843246.22      7072176.54      2843330.37      7072165.10
      2843381.30      7072197.98      2843491.44      7072218.66
      2843724.00      7072236.46      2843761.73      7072202.77
      2843864.71      7072170.07      2843917.35      7072053.62
      2843912.08      7071999.88      2843966.06      7071993.76
      2843993.33      7071956.22      2844047.51      7071934.61
      2844134.44      7071859.63      2844154.92      7071797.23
      2844264.30      7071749.74      2844271.51      7071671.36
      2844294.89      7071648.48      2844358.07      7071612.66
      2844460.05      7071617.64      2844520.74      7071572.37
      2844629.19      7071668.88      2844645.11      7071814.63
      2844672.96      7071839.51      2844829.57      7071871.23

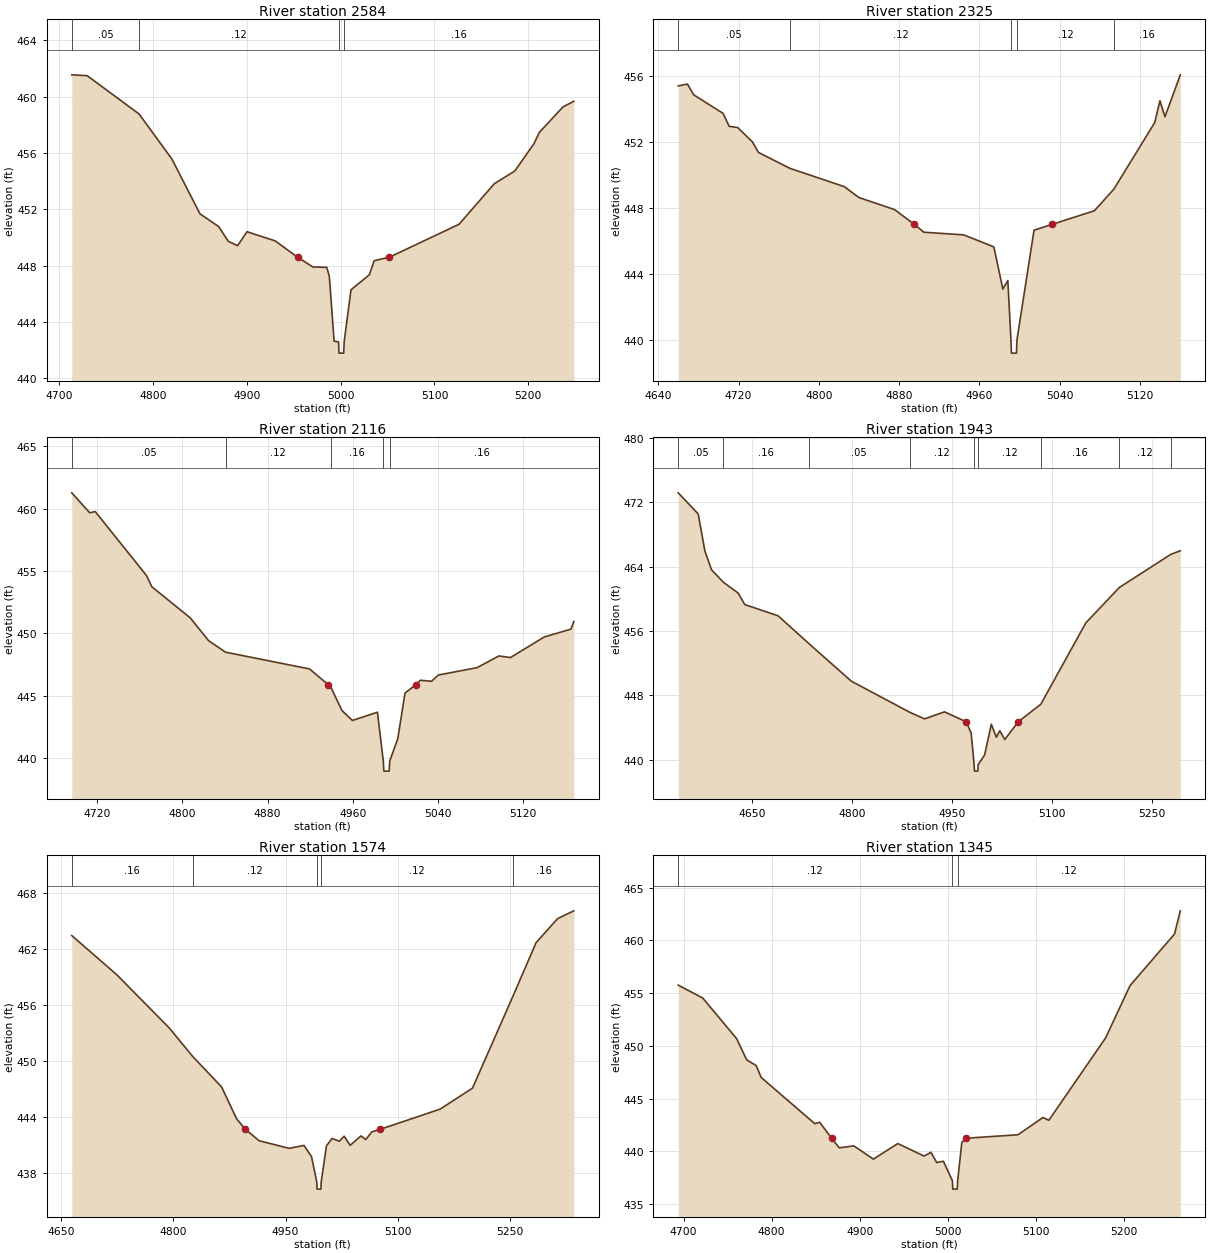
Type RM Length L Ch R = 1,2584,259,259,259
BEGIN DESCRIPTION:
UNT 135 in LFCCL Watershed 4.0
END DESCRIPTION:
XS GIS Cut Line= 3
      2842866.31      7072401.41      2842881.18      7072130.13
      2842821.72      7071873.72
#Sta/Elev= 30
  4713.6  461.56  4730.0  461.50  4785.3  458.78  4820.2  455.59  4850.2  451.69
  4870.2  450.78  4880.3  449.74  4890.3  449.43  4900.3  450.42  4930.3  449.77
  4954.2  448.61  4970.4  447.92  4985.3  447.89  4988.0  447.25  4993.1  442.64
  4997.8  442.60  4998.3  441.80  5003.3  441.80  5003.8  442.60  5011.1  446.30
  5030.6  447.36  5035.8  448.36  5052.0  448.61  5126.2  450.95  5163.8  453.83
  5185.6  454.73  5206.1  456.68  5211.6  457.46  5236.9  459.28  5248.5  459.68
#Mann=4,-1,0
  4713.6    0.05       0  4785.3    0.12       0  4997.8    0.07       0
  5003.8    0.16       0
Bank Sta=4954.2,5052
Exp/Cntr=0.3,0.1

Type RM Length L Ch R = 1,2325,209,209,209
BEGIN DESCRIPTION:
XS3851A
END DESCRIPTION:
XS GIS Cut Line= 3
      2842962.92      7072405.20      2843126.48      7072185.88
      2843141.32      7071959.56
#Sta/Elev= 30
  4659.9  455.38  4669.1  455.49  4675.3  454.84  4704.5  453.72  4710.7  452.93
  4719.1  452.86  4733.7  452.00  4739.9  451.35  4771.1  450.39  4825.4  449.28
  4840.0  448.62  4875.5  447.89  4895.2  447.00  4904.7  446.52  4944.4  446.36
  4974.5  445.63  4983.4  443.08  4988.4  443.59  4991.5  440.00  4992.0  439.20
  4997.0  439.20  4997.5  440.00  5014.5  446.64  5032.7  447.00  5074.7  447.82
  5094.1  449.13  5134.8  453.16  5140.0  454.48  5145.0  453.51  5160.3  456.05
#Mann=5,-1,0
  4659.9    0.05       0  4771.1    0.12       0  4991.5    0.07       0
  4997.5    0.12       0  5094.1    0.16       0
Bank Sta=4895.2,5032.7
Exp/Cntr=0.3,0.1

Type RM Length L Ch R = 1,2116,173,173,173
BEGIN DESCRIPTION:
XS3852A
END DESCRIPTION:
XS GIS Cut Line= 3
      2843256.57      7072464.59      2843304.88      7072200.75
      2843371.34      7072008.75
#Sta/Elev= 30
  4696.1  461.27  4713.0  459.67  4718.1  459.77  4766.2  454.65  4771.3  453.74
  4807.5  451.24  4824.5  449.43  4840.5  448.50  4919.3  447.16  4937.0  445.89
  4939.6  445.65  4949.8  443.82  4959.6  443.03  4983.1  443.69  4988.6  439.77
  4989.1  438.97  4994.1  438.97  4994.6  439.77  5002.2  441.57  5009.0  445.23
  5019.2  445.89  5023.3  446.25  5033.9  446.17  5040.2  446.67  5076.6  447.26
  5097.2  448.20  5108.0  448.07  5139.7  449.72  5164.8  450.35  5167.5  450.96
#Mann=5,-1,0
  4696.1    0.05       0  4840.5    0.12       0  4939.6    0.16       0
  4988.6    0.07       0  4994.6    0.16       0
Bank Sta=4937,5019.2
Exp/Cntr=0.3,0.1

Type RM Length L Ch R = 1,1943,369,369,369
BEGIN DESCRIPTION:
UNT 135 in LFCCL Watershed 3.0
END DESCRIPTION:
XS GIS Cut Line= 3
      2843475.00      7072675.05      2843475.00      7072225.00
      2843525.00      7071924.99
#Sta/Elev= 30
  4538.9  473.15  4568.9  470.53  4578.9  465.94  4588.9  463.59  4606.7  462.05
  4628.9  460.70  4638.9  459.27  4688.9  457.88  4734.7  454.46  4798.9  449.76
  4886.9  445.89  4908.9  445.08  4938.9  445.95  4971.4  444.72  4978.9  443.33
  4983.4  439.39  4983.9  438.59  4988.9  438.59  4989.4  439.39  4999.1  440.59
  5009.2  444.41  5016.8  442.80  5021.9  443.60  5029.5  442.52  5049.7  444.72
  5083.5  446.89  5151.2  457.00  5201.6  461.40  5278.7  465.50  5293.1  465.96
#Mann=9,-1,0
  4538.9    0.05       0  4606.7    0.16       0  4734.7    0.05       0
  4886.9    0.12       0  4983.4    0.07       0  4989.4    0.12       0
  5083.5    0.16       0  5201.6    0.12       0  5278.7    0.16       0
Bank Sta=4971.4,5049.7
Exp/Cntr=0.3,0.1

Type RM Length L Ch R = 1,1574,229,229,229
BEGIN DESCRIPTION:
UNT 135 in LFCCL Watershed 2.0
END DESCRIPTION:
XS GIS Cut Line= 3
      2843825.00      7072525.03      2843825.00      7072175.00
      2843574.99      7071974.99
#Sta/Elev= 30
  4664.7  463.47  4724.7  459.28  4794.7  453.58  4826.3  450.50  4864.7  447.25
  4884.7  443.84  4896.5  442.71  4914.7  441.49  4954.7  440.67  4974.7  440.98
  4984.7  439.79  4991.7  437.10  4992.2  436.30  4997.2  436.30  4997.7  437.10
  5004.7  440.94  5012.2  441.73  5021.9  441.43  5028.3  441.97  5036.3  440.99
  5050.7  442.00  5057.2  441.61  5065.2  442.43  5076.5  442.71  5156.4  444.87
  5199.6  447.12  5254.0  457.04  5284.5  462.71  5313.3  465.29  5334.9  466.12
#Mann=5,-1,0
  4664.7    0.16       0  4826.3    0.12       0  4991.7    0.07       0
  4997.7    0.12       0  5254.0    0.16       0
Bank Sta=4896.5,5076.5
Exp/Cntr=0.3,0.1

Type RM Length L Ch R = 1,1345,411,411,411
BEGIN DESCRIPTION:
XS3853A
END DESCRIPTION:
XS GIS Cut Line= 3
      2844063.10      7072263.95      2843940.43      7072026.06
      2843710.54      7071829.54
#Sta/Elev= 30
  4694.0  455.75  4721.8  454.53  4760.3  450.68  4771.7  448.67  4782.6  448.12
  4788.2  447.00  4849.1  442.62  4854.7  442.75  4868.1  441.24  4876.9  440.33
  4893.4  440.52  4915.6  439.26  4943.4  440.74  4973.2  439.55  4980.9  439.91
  4987.5  438.94  4995.1  439.06  5005.3  437.22  5005.8  436.42  5010.8  436.42
  5011.3  437.22  5016.0  440.84  5020.5  441.24  5079.7  441.57  5108.2  443.21
  5114.8  442.94  5179.3  450.75  5207.0  455.70  5257.5  460.59  5264.1  462.79
#Mann=3,-1,0
  4694.0    0.12       0  5005.3    0.07       0  5011.3    0.12       0
Bank Sta=4868.1,5020.5
Exp/Cntr=0.3,0.1

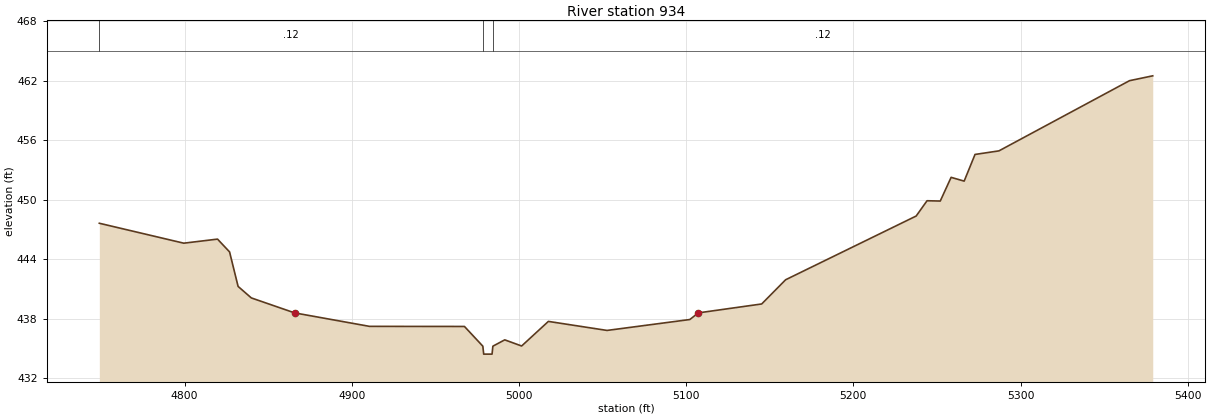
Type RM Length L Ch R = 1,934,0,0,0
BEGIN DESCRIPTION:
UNT 135 in LFCCL Watershed 1.0
END DESCRIPTION:
XS GIS Cut Line= 3
      2844241.49      7072014.95      2844204.32      7071758.46
      2843919.06      7071521.36
#Sta/Elev= 30
  4749.0  447.62  4799.5  445.61  4819.7  446.02  4826.9  444.73  4832.0  441.25
  4839.9  440.09  4865.8  438.58  4910.6  437.22  4967.4  437.21  4978.4  435.22
  4978.9  434.42  4983.9  434.42  4984.4  435.22  4991.5  435.86  5001.6  435.24
  5017.6  437.72  5052.7  436.81  5102.2  437.91  5107.3  438.58  5145.2  439.48
  5159.5  441.92  5237.6  448.35  5244.1  449.89  5252.0  449.86  5258.5  452.25
  5266.3  451.87  5272.8  454.56  5287.1  454.92  5365.2  462.00  5379.1  462.49
#Mann=3,-1,0
  4749.0    0.12       0  4978.4    0.07       0  4984.4    0.12       0
Bank Sta=4865.8,5107.3
Exp/Cntr=0.3,0.1

Chan Stop Cuts=-1