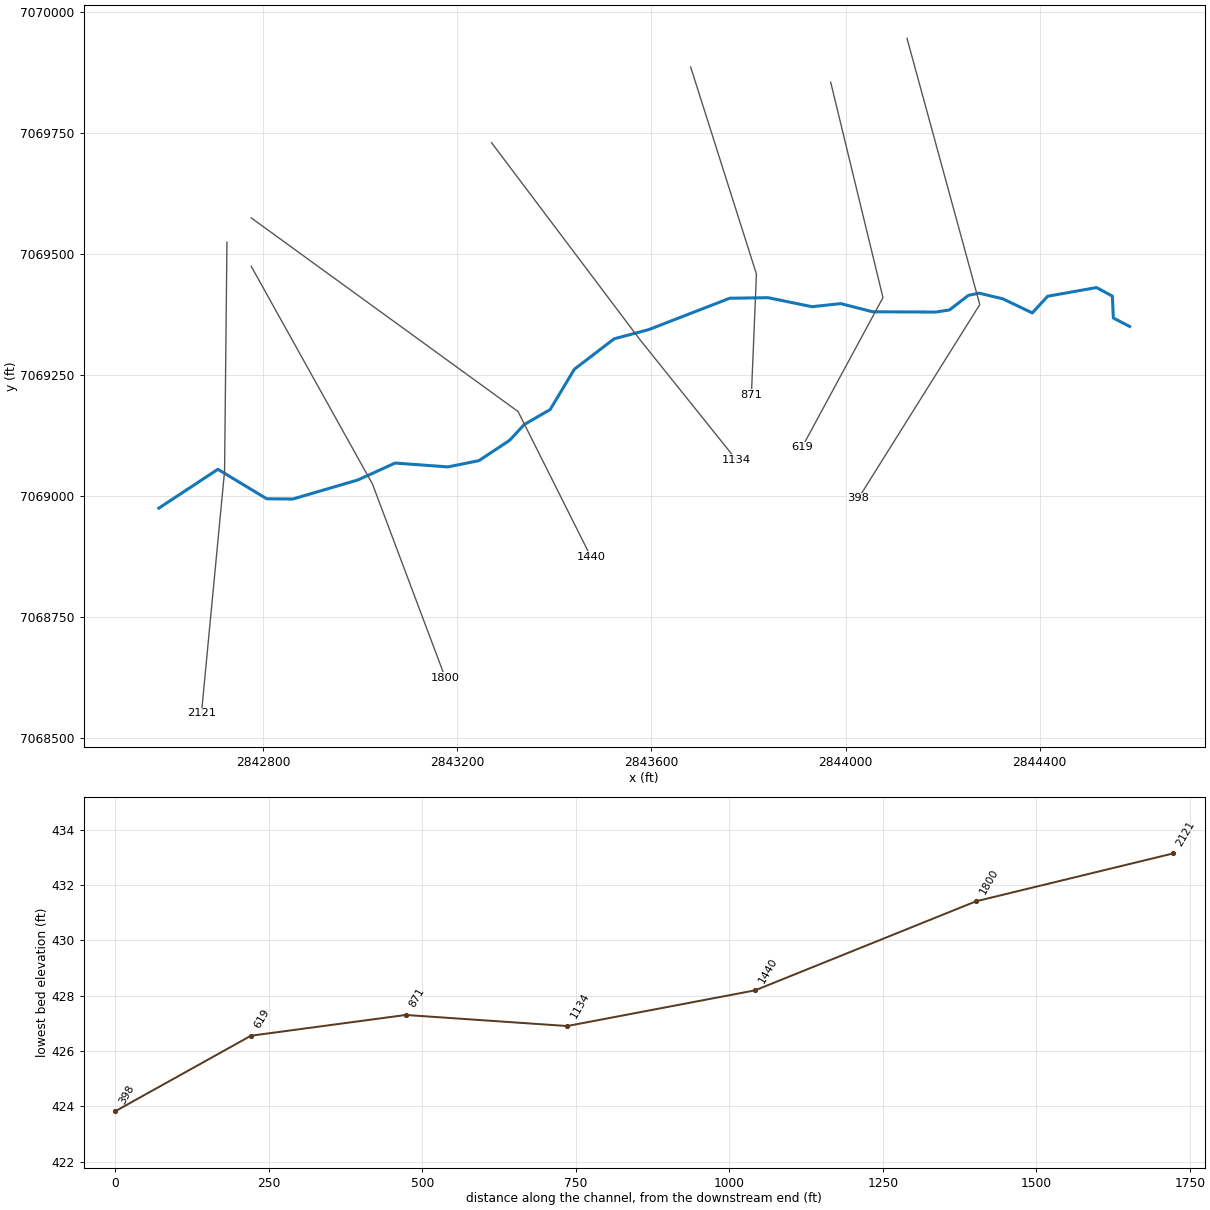
--- UNT 136 in LFCCL Watershed.prj (project) ---

Proj Title=UNT 136 in LFCCL Watershed Base Level Engineering
Current Plan=p01
Default Exp/Contr=0.3,0.1
English Units
Geom File=g01
Flow File=f01
Plan File=p01
BEGIN DESCRIPTION:
UNT 136 in LFCCL Watershed
END DESCRIPTION:

--- UNT 136 in LFCCL Watershed.p01 (plan) ---

Plan Title=Multiple Run
Short Identifier=Multiple
Geom File=g01
Flow File=f01
Subcritical Flow
K Sum by GR= 0
Std Step Tol= 0.01
Critical Tol= 0.01
Num of Std Step Trials= 20
Max Error Tol= 0.3
Flow Tol Ratio= 0.001
Split Flow NTrial= 30
Split Flow Tol= 0.02
Split Flow Ratio= 0.02
Log Output Level= 0
Friction Slope Method= 1
Unsteady Friction Slope Method= 2
Unsteady Bridges Friction Slope Method= 1
Parabolic Critical Depth
Global Vel Dist=  1 , 1 , 1
Global Log Level= 0
CheckData=True
Encroach Param= -1, 0, 0, 0
BEGIN DESCRIPTION:
Multiple Run
END DESCRIPTION:

--- UNT 136 in LFCCL Watershed.f01 (steady flow) ---

Flow Title=Multiple
Number of Profiles=7
Profile Names=10-year,25-year,50-year,1pct_min,100-year,1pct_plu,500-year
River Rch & RM= UNT 136 in LFCCL,Reach-1,2121
     834    1134    1381     834    1664    3320    2411
River Rch & RM= UNT 136 in LFCCL,Reach-1,1800
     932    1274    1557     943    1882    3755    2744
Boundary for River Rch & Prof#=UNT 136 in LFCCL,Reach-1,1
Up Type=0
Dn Type=3
Dn Slope=0.005
Boundary for River Rch & Prof#=UNT 136 in LFCCL,Reach-1,2
Up Type=0
Dn Type=3
Dn Slope=0.005
Boundary for River Rch & Prof#=UNT 136 in LFCCL,Reach-1,3
Up Type=0
Dn Type=3
Dn Slope=0.005
Boundary for River Rch & Prof#=UNT 136 in LFCCL,Reach-1,4
Up Type=0
Dn Type=3
Dn Slope=0.005
Boundary for River Rch & Prof#=UNT 136 in LFCCL,Reach-1,5
Up Type=0
Dn Type=3
Dn Slope=0.005
Boundary for River Rch & Prof#=UNT 136 in LFCCL,Reach-1,6
Up Type=0
Dn Type=3
Dn Slope=0.005
Boundary for River Rch & Prof#=UNT 136 in LFCCL,Reach-1,7
Up Type=0
Dn Type=3
Dn Slope=0.005

--- UNT 136 in LFCCL Watershed.g01 (geometry) ---

Geom Title=Existing Conditions

River Reach=UNT 136 in LFCCL,Reach-1
Reach XY= 30
      2842584.72      7068975.43      2842706.36      7069055.64
      2842806.98      7068994.73      2842860.61      7068994.22
      2842994.44      7069033.48      2843071.59      7069068.54
      2843180.52      7069060.60      2843244.43      7069073.53
      2843308.01      7069115.78      2843337.44      7069147.88
      2843391.17      7069179.04      2843441.02      7069262.31
      2843523.13      7069325.22      2843594.18      7069344.11
      2843761.33      7069409.00      2843840.27      7069410.10
      2843930.95      7069391.49      2843990.08      7069397.88
      2844055.69      7069381.06      2844185.72      7069380.43
      2844214.00      7069384.69      2844253.39      7069414.99
      2844275.23      7069419.49      2844324.40      7069407.71
      2844384.90      7069378.62      2844416.58      7069413.11
      2844517.37      7069431.04      2844549.94      7069413.39
      2844552.01      7069368.10      2844585.55      7069350.72

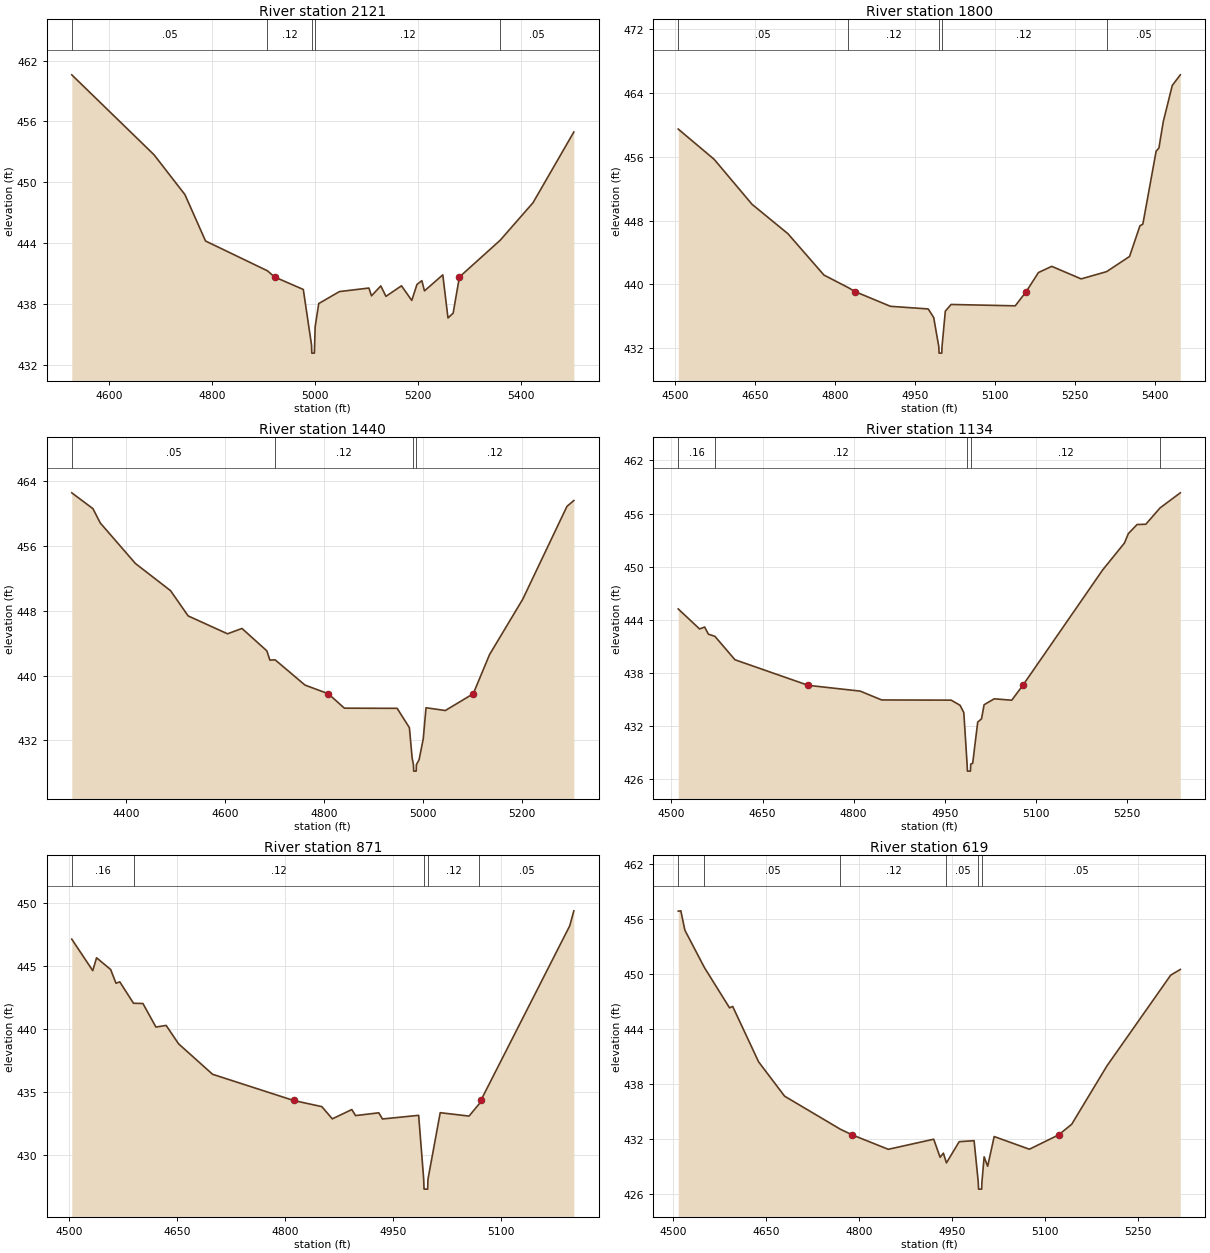
Type RM Length L Ch R = 1,2121,321,321,321
BEGIN DESCRIPTION:
UNT 136 in LFCCL Watershed 5.0
END DESCRIPTION:
XS GIS Cut Line= 3
      2842725.00      7069524.97      2842720.10      7069052.00
      2842672.43      7068551.46
#Sta/Elev= 30
  4527.0  460.59  4687.0  452.70  4747.0  448.77  4787.0  444.20  4907.3  441.26
  4921.2  440.65  4977.0  439.42  4993.0  433.94  4993.5  433.14  4998.5  433.14
  4999.0  433.94  5000.0  435.73  5007.0  438.03  5047.2  439.21  5104.5  439.56
  5109.5  438.79  5127.6  439.77  5137.6  438.74  5167.8  439.78  5187.8  438.34
  5197.9  439.91  5207.4  440.29  5212.5  439.28  5248.1  440.86  5258.2  436.61
  5268.2  437.08  5280.4  440.65  5359.6  444.27  5423.4  447.97  5502.8  454.95
#Mann=5,-1,0
  4527.0    0.05       0  4907.3    0.12       0  4993.0    0.07       0
  4999.0    0.12       0  5359.6    0.05       0
Bank Sta=4921.2,5280.4
Exp/Cntr=0.3,0.1

Type RM Length L Ch R = 1,1800,360,360,360
BEGIN DESCRIPTION:
UNT 136 in LFCCL Watershed 4.0
END DESCRIPTION:
XS GIS Cut Line= 3
      2842775.00      7069475.01      2843025.00      7069025.00
      2843175.00      7068624.99
#Sta/Elev= 30
  4505.4  459.45  4572.9  455.66  4643.8  450.04  4711.3  446.35  4778.8  441.18
  4824.4  439.61  4837.2  439.11  4903.5  437.27  4974.4  436.94  4984.7  435.87
  4994.3  432.21  4994.8  431.41  4999.8  431.41  5000.3  432.21  5006.5  436.66
  5017.3  437.50  5137.7  437.33  5158.3  439.11  5181.3  441.50  5206.2  442.27
  5261.4  440.70  5309.2  441.61  5352.2  443.51  5371.7  447.35  5377.1  447.55
  5402.0  456.67  5407.3  457.09  5415.4  460.37  5432.3  464.91  5447.4  466.24
#Mann=5,-1,0
  4505.4    0.05       0  4824.4    0.12       0  4994.3    0.07       0
  5000.3    0.12       0  5309.2    0.05       0
Bank Sta=4837.2,5158.3
Exp/Cntr=0.3,0.1

Type RM Length L Ch R = 1,1440,306,306,306
BEGIN DESCRIPTION:
UNT 136 in LFCCL Watershed 3.0
END DESCRIPTION:
XS GIS Cut Line= 3
      2842774.96      7069575.03      2843325.00      7069175.00
      2843474.99      7068875.03
#Sta/Elev= 30
  4290.2  462.58  4333.1  460.62  4347.8  458.86  4418.9  453.85  4490.0  450.49
  4525.6  447.37  4605.2  445.16  4634.5  445.82  4684.8  443.05  4690.9  441.91
  4701.6  441.94  4762.0  438.82  4809.1  437.75  4841.6  435.97  4948.3  435.95
  4973.1  433.56  4978.7  429.78  4981.3  428.99  4981.8  428.19  4986.8  428.19
  4987.3  428.99  4992.7  429.61  5001.1  432.18  5006.7  436.02  5045.8  435.68
  5102.2  437.75  5135.2  442.59  5202.3  449.43  5291.8  460.91  5305.7  461.63
#Mann=4,-1,0
  4290.2    0.05       0  4701.6    0.12       0  4981.3    0.07       0
  4987.3    0.12       0
Bank Sta=4809.1,5102.2
Exp/Cntr=0.3,0.1

Type RM Length L Ch R = 1,1134,263,263,263
BEGIN DESCRIPTION:
UNT 136 in LFCCL Watershed 2.0
END DESCRIPTION:
XS GIS Cut Line= 3
      2843270.45      7069730.20      2843575.00      7069325.00
      2843774.97      7069075.04
#Sta/Elev= 30
  4511.1  445.22  4546.3  442.96  4554.6  443.18  4560.8  442.37  4571.5  442.13
  4604.6  439.48  4725.3  436.59  4810.8  435.94  4846.2  434.94  4960.7  434.92
  4975.3  434.34  4981.5  433.51  4986.9  427.70  4987.4  426.90  4992.4  426.90
  4992.9  427.70  4996.1  427.78  5004.4  432.44  5010.7  432.81  5014.9  434.40
  5031.6  435.07  5060.4  434.91  5078.7  436.59  5210.1  449.62  5246.1  452.67
  5252.5  453.73  5266.9  454.76  5281.3  454.79  5304.8  456.64  5338.1  458.34
#Mann=5,-1,0
  4511.1    0.16       0  4571.5    0.12       0  4986.9    0.07       0
  4992.9    0.12       0  5304.8    0.05       0
Bank Sta=4725.3,5078.7
Exp/Cntr=0.3,0.1

Type RM Length L Ch R = 1,871,252,252,252
BEGIN DESCRIPTION:
XS3855A
END DESCRIPTION:
XS GIS Cut Line= 3
      2843680.76      7069886.61      2843816.35      7069458.96
      2843805.95      7069209.31
#Sta/Elev= 30
  4503.4  447.15  4532.6  444.65  4537.9  445.67  4557.5  444.74  4564.9  443.65
  4570.2  443.76  4589.3  442.06  4602.4  442.04  4620.5  440.17  4634.7  440.30
  4652.0  438.84  4699.3  436.42  4812.0  434.34  4851.3  433.85  4865.9  432.88
  4893.0  433.62  4898.2  433.14  4930.5  433.36  4935.7  432.87  4986.0  433.16
  4993.0  428.10  4993.5  427.30  4998.5  427.30  4999.0  428.10  5016.0  433.37
  5056.1  433.10  5070.2  434.07  5072.5  434.34  5196.2  448.21  5201.9  449.40
#Mann=5,-1,0
  4503.4    0.16       0  4589.3    0.12       0  4993.0    0.07       0
  4999.0    0.12       0  5070.2    0.05       0
Bank Sta=4812,5072.5
Exp/Cntr=0.3,0.1

Type RM Length L Ch R = 1,619,221,221,221
BEGIN DESCRIPTION:
XS3854A
END DESCRIPTION:
XS GIS Cut Line= 3
      2843969.33      7069855.37      2844077.13      7069410.28
      2843910.25      7069100.87
#Sta/Elev= 30
  4508.6  456.84  4512.8  456.88  4519.3  454.77  4550.8  450.70  4591.3  446.31
  4596.4  446.46  4638.2  440.42  4680.1  436.68  4770.2  433.07  4789.2  432.46
  4847.3  430.89  4920.5  431.99  4930.8  430.02  4936.1  430.47  4941.0  429.41
  4961.6  431.72  4985.6  431.83  4992.3  427.35  4992.8  426.55  4997.8  426.55
  4998.3  427.35  5001.8  430.07  5007.5  429.04  5018.0  432.28  5074.8  430.90
  5121.9  432.46  5143.0  433.62  5199.8  439.98  5302.6  449.87  5318.1  450.49
#Mann=6,-1,0
  4508.6    0.16       0  4550.8    0.05       0  4770.2    0.12       0
  4941.0    0.05       0  4992.3    0.03       0  4998.3    0.05       0
Bank Sta=4789.2,5121.9
Exp/Cntr=0.3,0.1

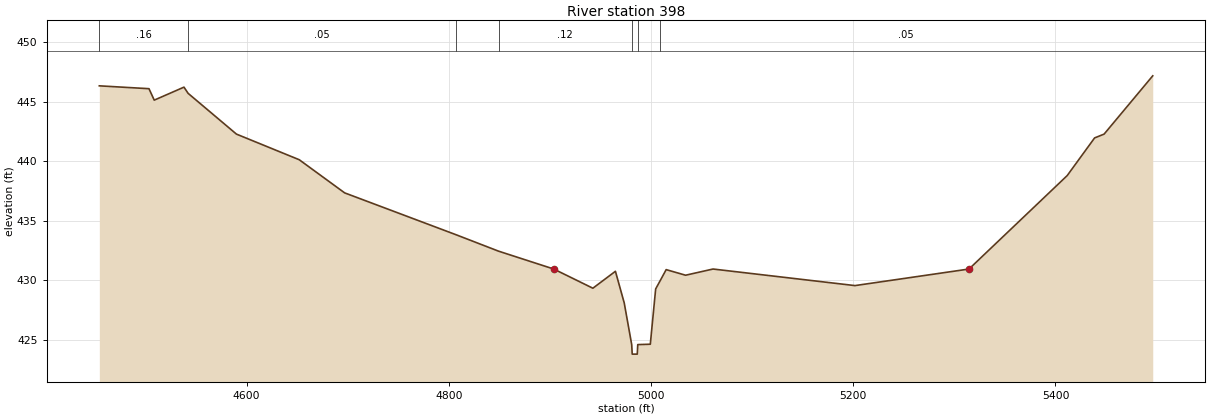
Type RM Length L Ch R = 1,398,0,0,0
BEGIN DESCRIPTION:
UNT 136 in LFCCL Watershed 1.0
END DESCRIPTION:
XS GIS Cut Line= 3
      2844126.67      7069945.85      2844276.66      7069395.86
      2844026.65      7068995.84
#Sta/Elev= 30
  4454.4  446.33  4503.5  446.09  4508.7  445.13  4538.1  446.22  4542.2  445.70
  4590.0  442.28  4652.1  440.13  4697.0  437.35  4807.1  433.84  4849.2  432.46
  4903.8  430.96  4942.5  429.35  4964.8  430.77  4973.5  428.12  4980.9  424.62
  4981.4  423.82  4986.4  423.82  4986.9  424.62  4999.3  424.65  5004.6  429.29
  5008.6  429.91  5015.0  430.91  5034.2  430.44  5061.3  430.96  5201.7  429.57
  5314.5  430.96  5411.6  438.80  5438.7  441.96  5448.1  442.28  5496.2  447.17
#Mann=7,-1,0
  4454.4    0.16       0  4542.2    0.05       0  4807.1    0.07       0
  4849.2    0.12       0  4980.9    0.07       0  4986.9    0.12       0
  5008.6    0.05       0
Bank Sta=4903.8,5314.5
Exp/Cntr=0.3,0.1

Chan Stop Cuts=-1