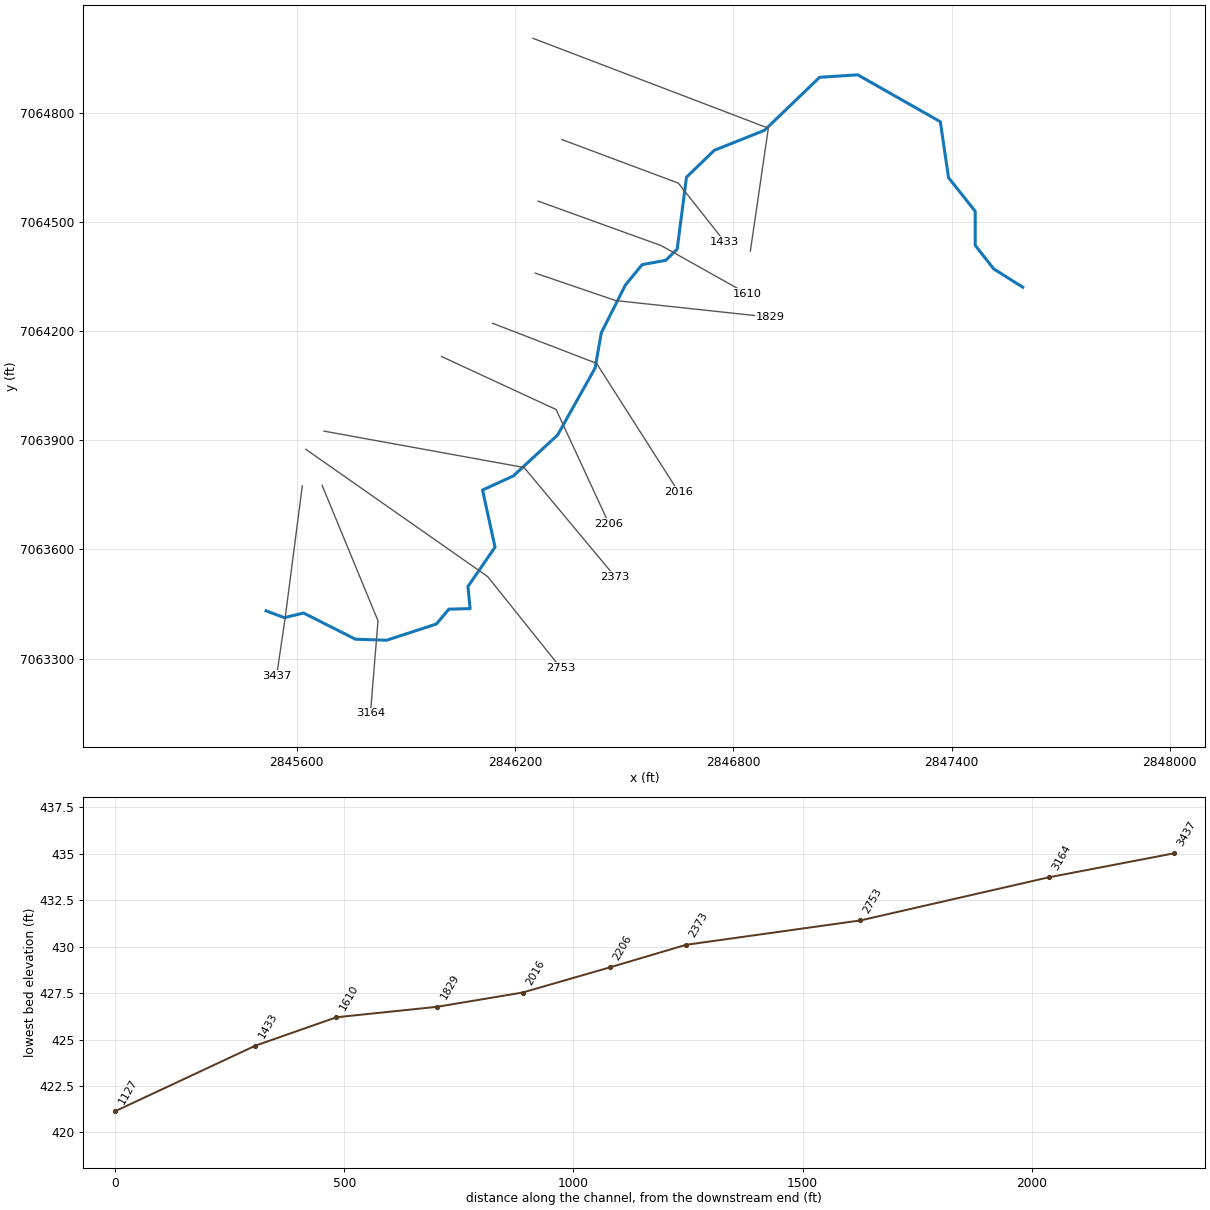
--- UNT 137 in LFCCL Watershed.prj (project) ---

Proj Title=UNT 137 in LFCCL Watershed Base Level Engineering
Current Plan=p01
Default Exp/Contr=0.3,0.1
English Units
Geom File=g01
Flow File=f01
Plan File=p01
BEGIN DESCRIPTION:
UNT 137 in LFCCL Watershed
END DESCRIPTION:

--- UNT 137 in LFCCL Watershed.p01 (plan) ---

Plan Title=Multiple Run
Short Identifier=Multiple
Geom File=g01
Flow File=f01
Subcritical Flow
K Sum by GR= 0
Std Step Tol= 0.01
Critical Tol= 0.01
Num of Std Step Trials= 20
Max Error Tol= 0.3
Flow Tol Ratio= 0.001
Split Flow NTrial= 30
Split Flow Tol= 0.02
Split Flow Ratio= 0.02
Log Output Level= 0
Friction Slope Method= 1
Unsteady Friction Slope Method= 2
Unsteady Bridges Friction Slope Method= 1
Parabolic Critical Depth
Global Vel Dist=  1 , 1 , 1
Global Log Level= 0
CheckData=True
Encroach Param= -1, 0, 0, 0
BEGIN DESCRIPTION:
Multiple Run
END DESCRIPTION:

--- UNT 137 in LFCCL Watershed.f01 (steady flow) ---

Flow Title=Multiple
Number of Profiles=7
Profile Names=10-year,25-year,50-year,1pct_min,100-year,1pct_plu,500-year
River Rch & RM= UNT 137 in LFCCL,Reach-1,3437
     416     540     638     375     747    1491    1022
Boundary for River Rch & Prof#=UNT 137 in LFCCL,Reach-1,1
Up Type=0
Dn Type=3
Dn Slope=0.005
Boundary for River Rch & Prof#=UNT 137 in LFCCL,Reach-1,2
Up Type=0
Dn Type=3
Dn Slope=0.005
Boundary for River Rch & Prof#=UNT 137 in LFCCL,Reach-1,3
Up Type=0
Dn Type=3
Dn Slope=0.005
Boundary for River Rch & Prof#=UNT 137 in LFCCL,Reach-1,4
Up Type=0
Dn Type=3
Dn Slope=0.005
Boundary for River Rch & Prof#=UNT 137 in LFCCL,Reach-1,5
Up Type=0
Dn Type=3
Dn Slope=0.005
Boundary for River Rch & Prof#=UNT 137 in LFCCL,Reach-1,6
Up Type=0
Dn Type=3
Dn Slope=0.005
Boundary for River Rch & Prof#=UNT 137 in LFCCL,Reach-1,7
Up Type=0
Dn Type=3
Dn Slope=0.005

--- UNT 137 in LFCCL Watershed.g01 (geometry) ---

Geom Title=Existing Conditions

River Reach=UNT 137 in LFCCL,Reach-1
Reach XY= 30
      2845515.81      7063431.02      2845565.89      7063412.25
      2845618.72      7063425.07      2845761.40      7063353.07
      2845847.17      7063350.27      2845983.92      7063394.78
      2846018.30      7063435.73      2846076.55      7063437.04
      2846070.62      7063498.04      2846145.08      7063606.06
      2846110.76      7063763.14      2846195.15      7063801.62
      2846317.11      7063914.36      2846420.10      7064098.27
      2846437.14      7064195.07      2846503.64      7064326.91
      2846549.44      7064382.67      2846614.31      7064394.45
      2846645.73      7064425.32      2846671.30      7064622.95
      2846747.93      7064696.92      2846885.74      7064751.83
      2847037.20      7064897.53      2847142.02      7064904.37
      2847369.16      7064775.42      2847391.64      7064621.63
      2847464.98      7064529.36      2847464.99      7064435.78
      2847515.61      7064371.13      2847595.59      7064320.71

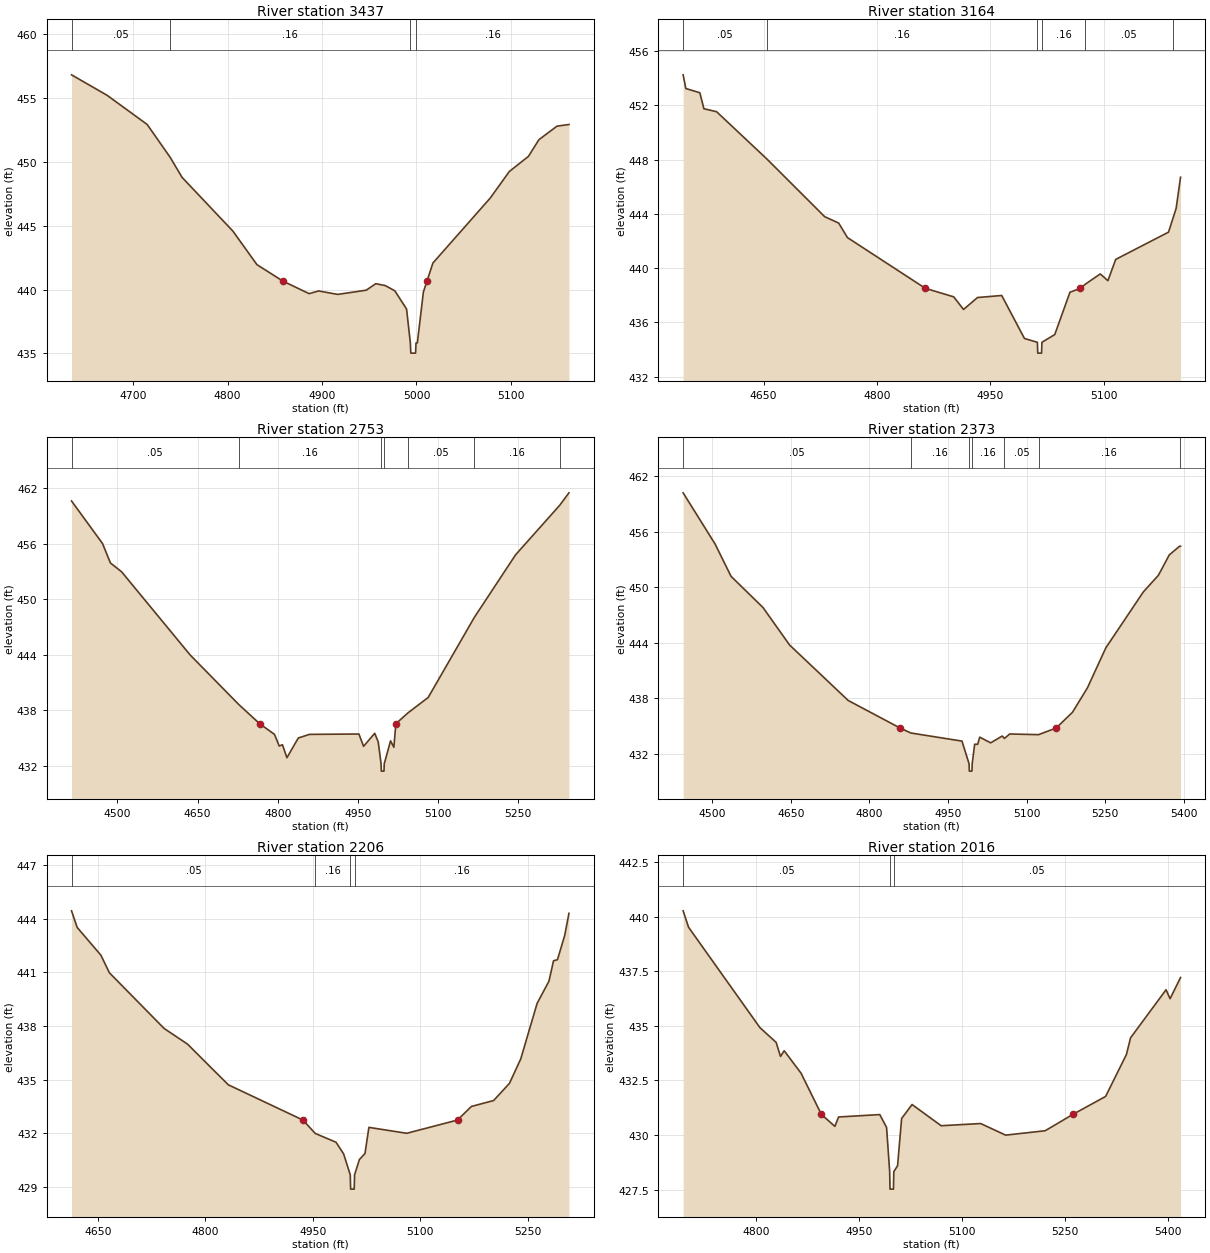
Type RM Length L Ch R = 1,3437,273,273,273
BEGIN DESCRIPTION:
UNT 137 in LFCCL Watershed 4.0
END DESCRIPTION:
XS GIS Cut Line= 3
      2845615.26      7063774.42      2845568.19      7063411.41
      2845544.76      7063252.58
#Sta/Elev= 30
  4634.8  456.82  4672.6  455.21  4714.9  452.93  4739.2  450.36  4751.8  448.79
  4805.6  444.58  4831.1  441.95  4858.6  440.66  4886.3  439.68  4896.4  439.89
  4916.6  439.62  4946.8  439.95  4956.9  440.46  4967.0  440.31  4977.1  439.90
  4989.5  438.47  4993.5  435.82  4994.0  435.02  4999.0  435.02  4999.5  435.82
  5000.9  435.82  5007.3  439.81  5011.1  440.66  5017.4  442.08  5078.1  447.17
  5098.3  449.25  5118.5  450.43  5129.6  451.74  5148.8  452.80  5161.4  452.93
#Mann=4,-1,0
  4634.8    0.05       0  4739.2    0.16       0  4993.5    0.07       0
  4999.5    0.16       0
Bank Sta=4858.6,5011.1
Exp/Cntr=0.3,0.1

Type RM Length L Ch R = 1,3164,411,411,411
BEGIN DESCRIPTION:
XS3856A
END DESCRIPTION:
XS GIS Cut Line= 3
      2845669.76      7063775.98      2845823.40      7063403.60
      2845802.63      7063149.18
#Sta/Elev= 30
  4543.6  454.25  4547.2  453.24  4565.7  452.93  4571.1  451.75  4587.9  451.53
  4654.5  448.04  4730.9  443.79  4749.4  443.32  4761.0  442.25  4864.0  438.51
  4901.6  437.88  4914.6  436.95  4933.1  437.83  4965.1  437.98  4995.2  434.81
  5012.3  434.53  5012.8  433.73  5017.8  433.73  5018.3  434.53  5035.3  435.10
  5055.4  438.22  5069.2  438.51  5075.9  438.82  5095.5  439.57  5105.6  439.07
  5115.9  440.64  5185.8  442.65  5191.9  443.71  5195.9  444.41  5201.7  446.70
#Mann=6,-1,0
  4543.6    0.05       0  4654.5    0.16       0  5012.3    0.07       0
  5018.3    0.16       0  5075.9    0.05       0  5191.9    0.16       0
Bank Sta=4864,5069.2
Exp/Cntr=0.3,0.1

Type RM Length L Ch R = 1,2753,380,380,380
BEGIN DESCRIPTION:
UNT 137 in LFCCL Watershed 3.0
END DESCRIPTION:
XS GIS Cut Line= 3
      2845624.97      7063875.02      2846125.00      7063525.00
      2846324.99      7063275.01
#Sta/Elev= 30
  4414.3  460.60  4472.3  456.00  4487.1  453.90  4508.1  452.94  4636.2  443.96
  4727.3  438.60  4766.3  436.53  4794.0  435.38  4802.8  434.12  4808.9  434.26
  4817.2  432.86  4838.5  434.99  4859.4  435.38  4951.9  435.42  4960.6  434.09
  4981.5  435.50  4988.0  434.57  4993.3  432.21  4993.8  431.41  4998.8  431.41
  4999.3  432.21  5011.1  434.68  5017.3  433.99  5021.0  436.53  5043.8  437.71
  5081.5  439.37  5167.8  448.02  5244.8  454.77  5327.6  460.14  5344.8  461.48
#Mann=7,-1,0
  4414.3    0.05       0  4727.3    0.16       0  4993.3    0.07       0
  4999.3    0.16       0  5043.8    0.05       0  5167.8    0.16       0
  5327.6    0.05       0
Bank Sta=4766.3,5021
Exp/Cntr=0.3,0.1

Type RM Length L Ch R = 1,2373,167,167,167
BEGIN DESCRIPTION:
UNT 137 in LFCCL Watershed 2.0
END DESCRIPTION:
XS GIS Cut Line= 3
      2845675.01      7063925.00      2846225.00      7063825.00
      2846474.99      7063525.02
#Sta/Elev= 30
  4444.5  460.23  4505.5  454.69  4536.0  451.19  4597.0  447.81  4647.8  443.75
  4759.6  437.75  4858.5  434.77  4879.0  434.23  4976.8  433.35  4990.3  430.90
  4990.8  430.10  4995.8  430.10  4996.3  430.90  5001.0  433.01  5006.8  433.01
  5010.7  433.78  5031.5  433.16  5053.6  433.90  5057.8  433.64  5067.9  434.12
  5123.0  434.05  5156.7  434.77  5187.7  436.47  5216.3  439.12  5251.5  443.46
  5323.1  449.51  5351.7  451.30  5372.5  453.51  5392.2  454.45  5394.0  454.45
#Mann=7,-1,0
  4444.5    0.05       0  4879.0    0.16       0  4990.3    0.07       0
  4996.3    0.16       0  5057.8    0.05       0  5123.0    0.16       0
  5392.2    0.05       0
Bank Sta=4858.5,5156.7
Exp/Cntr=0.3,0.1

Type RM Length L Ch R = 1,2206,190,190,190
BEGIN DESCRIPTION:
XS3857A
END DESCRIPTION:
XS GIS Cut Line= 3
      2845997.83      7064130.18      2846312.98      7063984.33
      2846458.62      7063669.66
#Sta/Elev= 30
  4613.3  444.43  4621.2  443.50  4654.3  441.95  4666.1  440.97  4742.4  437.86
  4775.2  436.98  4832.0  434.71  4936.1  432.74  4953.4  431.99  4982.3  431.50
  4992.9  430.85  5002.2  429.68  5002.7  428.88  5007.7  428.88  5008.2  429.68
  5014.9  430.53  5022.7  430.87  5028.2  432.33  5081.0  432.00  5151.8  432.74
  5171.2  433.50  5202.2  433.83  5224.3  434.79  5240.0  436.15  5262.9  439.26
  5279.4  440.50  5285.8  441.64  5291.3  441.70  5301.4  443.06  5307.3  444.29
#Mann=4,-1,0
  4613.3    0.05       0  4953.4    0.16       0  5002.2    0.07       0
  5008.2    0.16       0
Bank Sta=4936.1,5151.8
Exp/Cntr=0.3,0.1

Type RM Length L Ch R = 1,2016,187,187,187
BEGIN DESCRIPTION:
XS3861A
END DESCRIPTION:
XS GIS Cut Line= 3
      2846138.54      7064221.29      2846424.10      7064111.33
      2846649.03      7063758.53
#Sta/Elev= 30
  4694.0  440.26  4701.9  439.51  4805.8  434.92  4829.5  434.24  4835.8  433.60
  4841.2  433.86  4865.8  432.83  4895.3  430.95  4915.0  430.40  4920.4  430.83
  4980.4  430.94  4990.3  430.35  4994.8  428.33  4995.3  427.53  5000.3  427.53
  5000.8  428.33  5006.3  428.60  5012.2  430.76  5027.4  431.40  5069.8  430.43
  5127.3  430.53  5163.7  430.00  5221.2  430.20  5261.7  430.95  5309.3  431.77
  5339.6  433.69  5345.6  434.45  5397.3  436.65  5403.2  436.24  5418.4  437.21
#Mann=3,-1,0
  4694.0    0.05       0  4994.8    0.03       0  5000.8    0.05       0
Bank Sta=4895.3,5261.7
Exp/Cntr=0.3,0.1

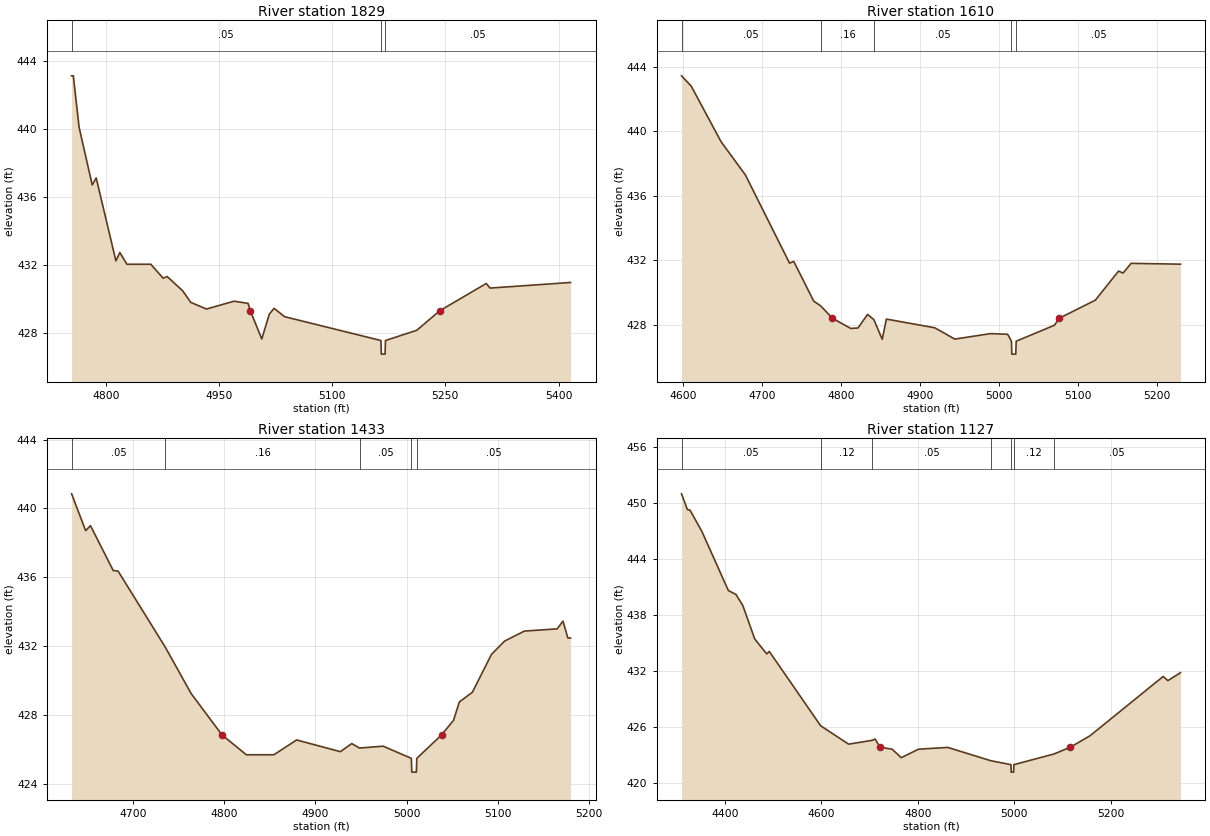
Type RM Length L Ch R = 1,1829,219,219,219
BEGIN DESCRIPTION:
XS3860A
END DESCRIPTION:
XS GIS Cut Line= 3
      2846255.66      7064359.34      2846477.05      7064283.81
      2846901.88      7064238.14
#Sta/Elev= 30
  4754.7  443.11  4757.0  443.11  4764.6  440.09  4782.0  436.70  4787.3  437.11
  4813.4  432.24  4818.6  432.73  4828.0  432.04  4859.7  432.04  4876.0  431.22
  4881.3  431.32  4901.9  430.48  4912.6  429.80  4933.4  429.41  4970.0  429.87
  4988.6  429.74  4991.5  429.31  5006.7  427.65  5016.7  429.11  5023.0  429.45
  5036.9  428.96  5164.6  427.56  5165.1  426.76  5170.1  426.76  5170.6  427.56
  5212.1  428.16  5242.6  429.31  5304.2  430.91  5309.2  430.64  5415.9  430.97
#Mann=3,-1,0
  4754.7    0.05       0  5164.6    0.03       0  5170.6    0.05       0
Bank Sta=4991.5,5242.6
Exp/Cntr=0.3,0.1

Type RM Length L Ch R = 1,1610,177,177,177
BEGIN DESCRIPTION:
XS3859A
END DESCRIPTION:
XS GIS Cut Line= 3
      2846263.48      7064557.25      2846602.05      7064434.85
      2846839.05      7064302.02
#Sta/Elev= 30
  4598.0  443.43  4610.2  442.80  4648.1  439.35  4678.8  437.30  4734.8  431.83
  4740.1  431.94  4765.4  429.48  4774.4  429.18  4789.1  428.42  4812.3  427.79
  4821.4  427.82  4833.6  428.66  4841.6  428.33  4852.1  427.12  4857.4  428.37
  4918.7  427.83  4944.0  427.13  4989.2  427.47  5010.9  427.43  5015.7  427.00
  5016.2  426.20  5021.2  426.20  5021.7  427.00  5070.2  427.99  5076.2  428.42
  5121.9  429.54  5151.3  431.34  5157.0  431.22  5167.2  431.82  5229.7  431.77
#Mann=5,-1,0
  4598.0    0.05       0  4774.4    0.16       0  4841.6    0.05       0
  5015.7    0.03       0  5021.7    0.05       0
Bank Sta=4789.1,5076.2
Exp/Cntr=0.3,0.1

Type RM Length L Ch R = 1,1433,306,306,306
BEGIN DESCRIPTION:
XS3858A
END DESCRIPTION:
XS GIS Cut Line= 3
      2846328.61      7064726.51      2846648.92      7064606.72
      2846776.54      7064445.24
#Sta/Elev= 30
  4632.3  440.85  4647.7  438.71  4653.0  439.00  4678.0  436.39  4683.3  436.36
  4735.1  431.94  4763.5  429.24  4797.5  426.83  4824.1  425.68  4854.4  425.68
  4879.3  426.54  4927.4  425.86  4939.9  426.33  4948.4  426.07  4974.3  426.18
  5005.3  425.47  5005.8  424.67  5010.8  424.67  5011.3  425.47  5038.4  426.83
  5051.6  427.68  5058.0  428.75  5072.4  429.32  5093.2  431.51  5107.7  432.29
  5129.4  432.87  5165.4  433.00  5171.8  433.45  5177.1  432.47  5180.1  432.47
#Mann=5,-1,0
  4632.3    0.05       0  4735.1    0.16       0  4948.4    0.05       0
  5005.3    0.03       0  5011.3    0.05       0
Bank Sta=4797.5,5038.4
Exp/Cntr=0.3,0.1

Type RM Length L Ch R = 1,1127,0,0,0
BEGIN DESCRIPTION:
UNT 137 in LFCCL Watershed 1.0
END DESCRIPTION:
XS GIS Cut Line= 3
      2846249.50      7065004.68      2846896.32      7064757.76
      2846846.89      7064419.59
#Sta/Elev= 30
  4310.4  450.98  4322.6  449.29  4327.9  449.24  4352.7  446.94  4407.5  440.61
  4423.3  440.19  4437.5  439.00  4462.2  435.41  4487.0  433.82  4492.3  434.08
  4598.8  426.11  4656.7  424.14  4705.8  424.55  4711.5  424.69  4722.0  423.81
  4746.9  423.60  4765.8  422.69  4801.7  423.60  4862.2  423.79  4951.0  422.37
  4993.2  421.94  4993.7  421.14  4998.7  421.14  4999.2  421.94  5082.1  423.08
  5116.1  423.81  5157.1  425.04  5308.7  431.40  5318.4  430.95  5344.5  431.80
#Mann=7,-1,0
  4310.4    0.05       0  4598.8    0.12       0  4705.8    0.05       0
  4951.0    0.12       0  4993.2    0.07       0  4999.2    0.12       0
  5082.1    0.05       0
Bank Sta=4722,5116.1
Exp/Cntr=0.3,0.1

Chan Stop Cuts=-1