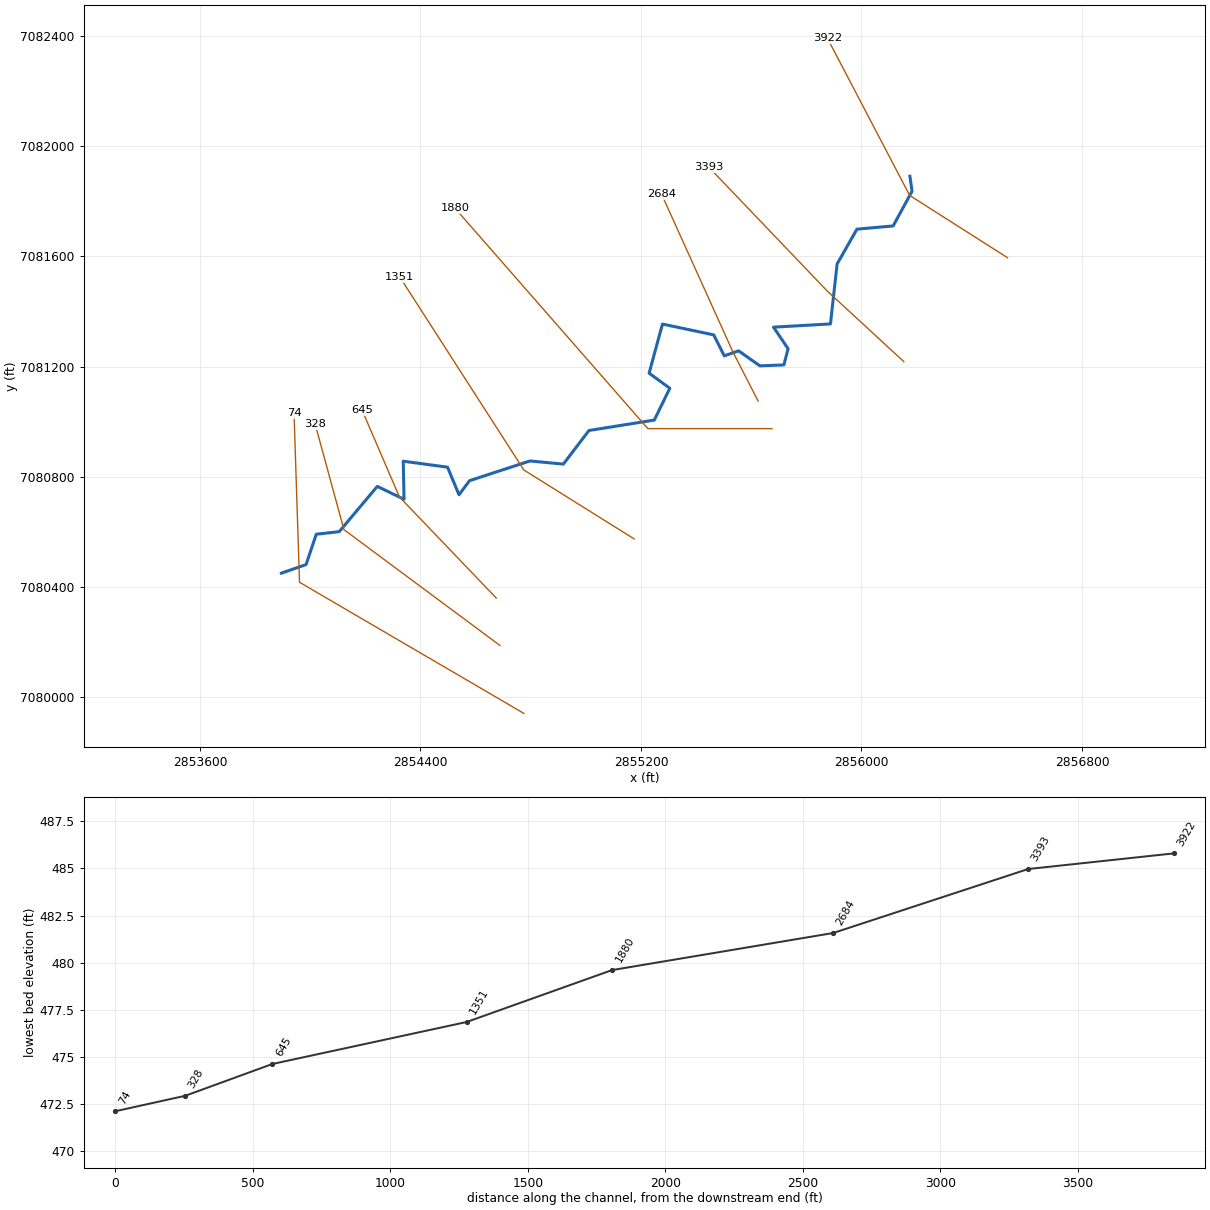
--- UNT 138 in LFCCL Watershed.prj (project) ---

Proj Title=UNT 138 in LFCCL Watershed Base Level Engineering
Current Plan=p01
Default Exp/Contr=0.3,0.1
English Units
Geom File=g01
Flow File=f01
Plan File=p01
BEGIN DESCRIPTION:
UNT 138 in LFCCL Watershed
END DESCRIPTION:

--- UNT 138 in LFCCL Watershed.p01 (plan) ---

Plan Title=Multiple Run
Short Identifier=Multiple
Geom File=g01
Flow File=f01
Subcritical Flow
K Sum by GR= 0
Std Step Tol= 0.01
Critical Tol= 0.01
Num of Std Step Trials= 20
Max Error Tol= 0.3
Flow Tol Ratio= 0.001
Split Flow NTrial= 30
Split Flow Tol= 0.02
Split Flow Ratio= 0.02
Log Output Level= 0
Friction Slope Method= 1
Unsteady Friction Slope Method= 2
Unsteady Bridges Friction Slope Method= 1
Parabolic Critical Depth
Global Vel Dist=  1 , 1 , 1
Global Log Level= 0
CheckData=True
Encroach Param= -1, 0, 0, 0
BEGIN DESCRIPTION:
Multiple Run
END DESCRIPTION:

--- UNT 138 in LFCCL Watershed.f01 (steady flow) ---

Flow Title=Multiple
Number of Profiles=7
Profile Names=10-year,25-year,50-year,1pct_min,100-year,1pct_plu,500-year
River Rch & RM= UNT 138 in LFCCL,Reach-1,3922
    1097    1526    1888    1159    2313    4615    3462
River Rch & RM= UNT 138 in LFCCL,Reach-1,3393
    1106    1531    1886    1153    2300    4590    3412
Boundary for River Rch & Prof#=UNT 138 in LFCCL,Reach-1,1
Up Type=0
Dn Type=3
Dn Slope=0.005
Boundary for River Rch & Prof#=UNT 138 in LFCCL,Reach-1,2
Up Type=0
Dn Type=3
Dn Slope=0.005
Boundary for River Rch & Prof#=UNT 138 in LFCCL,Reach-1,3
Up Type=0
Dn Type=3
Dn Slope=0.005
Boundary for River Rch & Prof#=UNT 138 in LFCCL,Reach-1,4
Up Type=0
Dn Type=3
Dn Slope=0.005
Boundary for River Rch & Prof#=UNT 138 in LFCCL,Reach-1,5
Up Type=0
Dn Type=3
Dn Slope=0.005
Boundary for River Rch & Prof#=UNT 138 in LFCCL,Reach-1,6
Up Type=0
Dn Type=3
Dn Slope=0.005
Boundary for River Rch & Prof#=UNT 138 in LFCCL,Reach-1,7
Up Type=0
Dn Type=3
Dn Slope=0.005

--- UNT 138 in LFCCL Watershed.g01 (geometry) ---

Geom Title=Existing Conditions

River Reach=UNT 138 in LFCCL,Reach-1
Reach XY= 30
      2856175.59      7081890.71      2856183.53      7081836.50
      2856114.98      7081710.49      2855983.61      7081698.69
      2855911.65      7081572.70      2855887.50      7081354.87
      2855680.80      7081343.19      2855733.77      7081264.81
      2855718.46      7081206.09      2855631.36      7081202.84
      2855554.28      7081257.18      2855502.20      7081239.08
      2855463.87      7081315.21      2855277.93      7081354.36
      2855229.56      7081176.23      2855304.66      7081121.52
      2855248.31      7081006.03      2855011.25      7080968.27
      2854918.41      7080846.33      2854796.96      7080857.69
      2854578.03      7080786.15      2854539.74      7080734.99
      2854498.21      7080835.10      2854337.43      7080856.87
      2854340.39      7080718.67      2854243.30      7080765.54
      2854105.20      7080601.24      2854021.83      7080591.86
      2853984.80      7080481.74      2853895.59      7080450.71

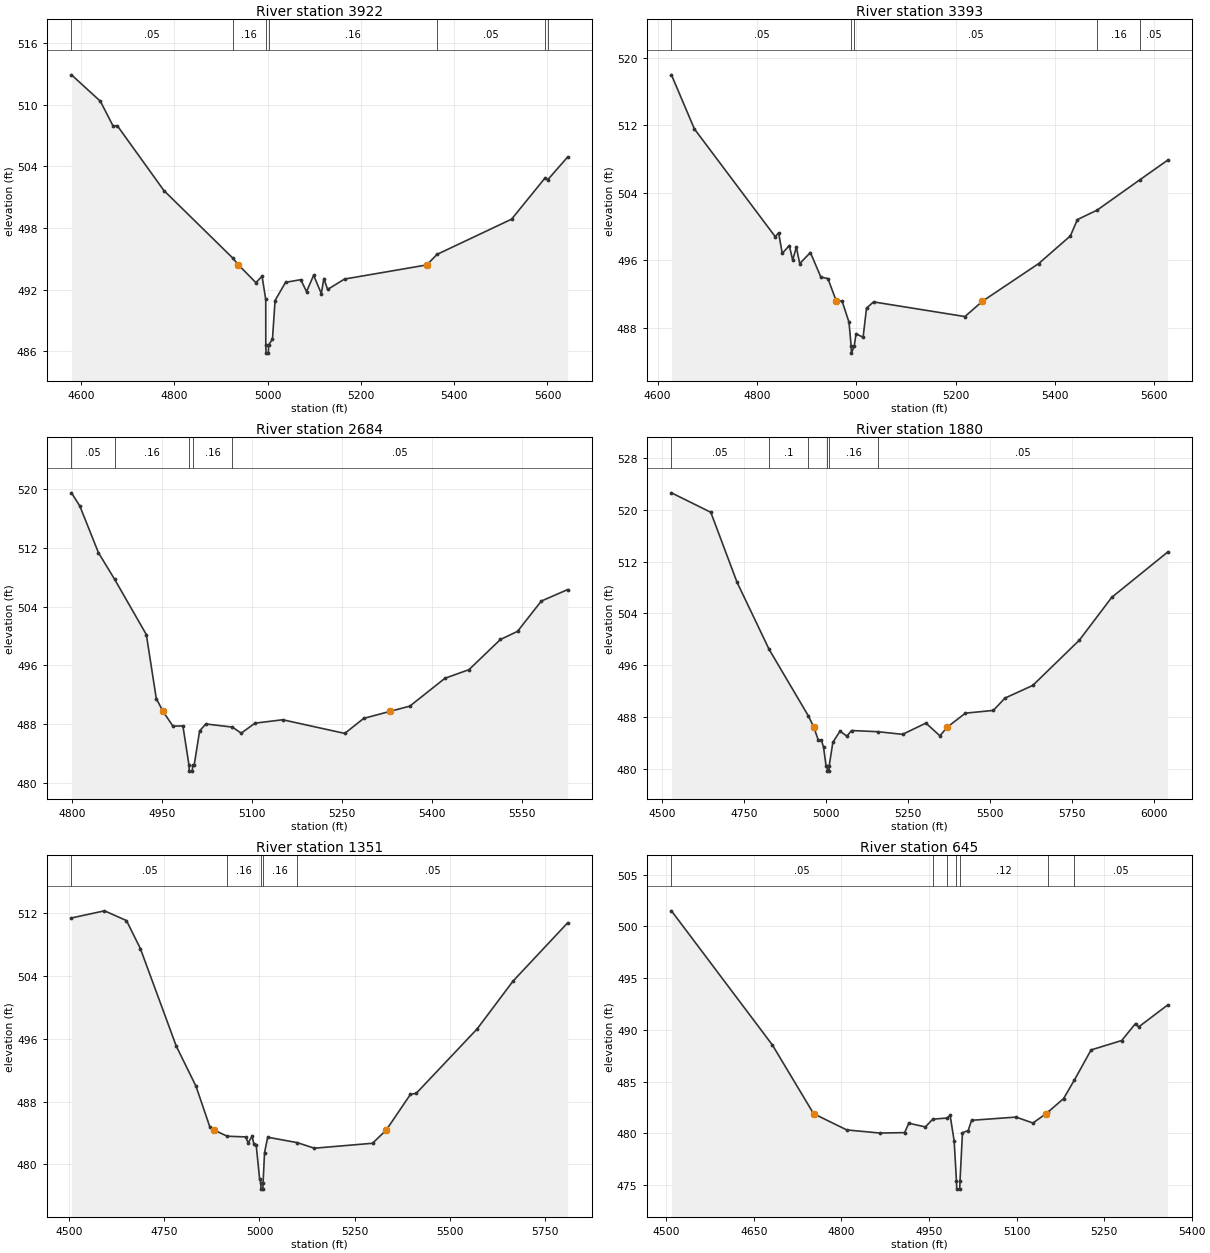
Type RM Length L Ch R = 1,3922,529,529,529
BEGIN DESCRIPTION:
UNT 138 in LFCCL Watershed 6.0
END DESCRIPTION:
XS GIS Cut Line= 3
      2856529.79      7081595.20      2856174.89      7081821.10
      2855876.63      7082391.08
#Sta/Elev= 30
  4579.3  512.93  4641.2  510.36  4668.3  507.96  4677.6  507.97  4777.5  501.65
  4924.7  495.09  4937.4  494.40  4974.8  492.67  4988.0  493.30  4995.9  491.03
  4996.0  486.60  4996.5  485.80  5001.5  485.80  5002.0  486.60  5010.3  487.15
  5015.9  490.93  5038.3  492.70  5070.9  492.96  5083.4  491.80  5098.6  493.39
  5115.0  491.61  5120.6  493.07  5128.6  492.01  5164.8  493.02  5341.4  494.40
  5363.0  495.42  5523.1  498.86  5595.1  502.89  5601.0  502.72  5643.3  504.92
#Mann=7,-1,0
  4579.3    0.05       0  4924.7    0.16       0  4996.0    0.07       0
  5002.0    0.16       0  5363.0    0.05       0  5595.1    0.07       0
  5601.0    0.05       0
Bank Sta=4937.4,5341.4
Exp/Cntr=0.3,0.1

Type RM Length L Ch R = 1,3393,709,709,709
BEGIN DESCRIPTION:
UNT 138 in LFCCL Watershed 5.0
END DESCRIPTION:
XS GIS Cut Line= 3
      2856153.55      7081218.29      2855875.00      7081475.00
      2855446.47      7081923.34
#Sta/Elev= 30
  4627.9  518.00  4674.1  511.58  4836.9  498.79  4843.7  499.25  4851.0  496.81
  4865.2  497.74  4872.0  496.01  4879.4  497.55  4886.2  495.60  4907.7  496.91
  4928.7  494.00  4942.9  493.82  4960.0  491.12  4971.3  491.18  4985.4  488.64
  4989.8  485.77  4990.3  484.97  4995.8  485.77  4999.6  487.26  5013.8  486.86
  5020.7  490.31  5034.8  491.05  5218.8  489.31  5253.9  491.12  5367.3  495.60
  5431.1  498.88  5445.3  500.82  5484.9  501.94  5570.7  505.53  5626.9  507.87
#Mann=5,-1,0
  4627.9    0.05       0  4989.8    0.03       0  4995.8    0.05       0
  5484.9    0.16       0  5570.7    0.05       0
Bank Sta=4960,5253.9
Exp/Cntr=0.3,0.1

Type RM Length L Ch R = 1,2684,804,804,804
BEGIN DESCRIPTION:
UNT 138 in LFCCL Watershed 4.0
END DESCRIPTION:
XS GIS Cut Line= 3
      2855625.01      7081074.99      2855533.00      7081254.37
      2855275.02      7081824.96
#Sta/Elev= 30
  4798.4  519.50  4812.3  517.71  4843.4  511.34  4870.5  507.70  4923.3  500.18
  4939.9  491.46  4951.2  489.70  4967.7  487.70  4984.3  487.73  4994.5  482.37
  4995.0  481.57  5000.0  481.57  5000.5  482.37  5003.1  482.37  5012.2  487.06
  5022.6  488.00  5066.8  487.57  5081.6  486.75  5104.7  488.11  5150.9  488.57
  5254.3  486.71  5286.0  488.76  5329.2  489.70  5362.9  490.43  5421.6  494.23
  5461.6  495.40  5514.0  499.51  5542.6  500.62  5582.3  504.75  5626.2  506.31
#Mann=5,-1,0
  4798.4    0.05       0  4870.5    0.16       0  4994.5    0.07       0
  5000.5    0.16       0  5066.8    0.05       0
Bank Sta=4951.2,5329.2
Exp/Cntr=0.3,0.1

Type RM Length L Ch R = 1,1880,529,529,529
BEGIN DESCRIPTION:
UNT 138 in LFCCL Watershed 3.0
END DESCRIPTION:
XS GIS Cut Line= 3
      2855674.99      7080975.00      2855225.00      7080975.00
      2854525.00      7081775.00
#Sta/Elev= 30
  4529.7  522.65  4649.7  519.64  4729.7  508.82  4827.7  498.42  4947.5  488.12
  4963.6  486.42  4977.2  484.44  4986.8  484.44  4993.5  483.30  5001.0  480.46
  5004.7  480.40  5005.2  479.60  5010.2  479.60  5010.7  480.40  5021.9  484.06
  5043.8  485.79  5064.6  485.01  5078.9  485.88  5159.4  485.70  5234.5  485.29
  5305.7  487.03  5348.4  485.06  5371.0  486.42  5426.3  488.57  5511.2  488.99
  5546.8  490.90  5631.3  492.85  5773.6  499.86  5872.3  506.48  6042.7  513.48
#Mann=6,-1,0
  4529.7    0.05       0  4827.7     0.1       0  4947.5    0.16       0
  5004.7    0.07       0  5010.7    0.16       0  5159.4    0.05       0
Bank Sta=4963.6,5371
Exp/Cntr=0.3,0.1

Type RM Length L Ch R = 1,1351,706,706,706
BEGIN DESCRIPTION:
UNT 138 in LFCCL Watershed 2.0
END DESCRIPTION:
XS GIS Cut Line= 3
      2855175.04      7080574.98      2854775.00      7080825.00
      2854325.01      7081524.99
#Sta/Elev= 30
  4505.9  511.43  4592.6  512.34  4650.4  511.10  4687.0  507.52  4781.3  495.08
  4833.2  489.96  4869.7  484.75  4880.8  484.37  4915.2  483.59  4964.1  483.50
  4970.0  482.73  4980.6  483.59  4985.2  482.58  4991.2  482.51  5000.4  478.11
  5003.4  477.64  5003.9  476.84  5008.9  476.84  5009.4  477.64  5013.3  481.51
  5021.6  483.46  5099.4  482.77  5144.1  482.06  5297.0  482.69  5333.0  484.37
  5396.7  488.93  5411.9  489.06  5572.0  497.28  5666.2  503.37  5809.8  510.81
#Mann=5,-1,0
  4505.9    0.05       0  4915.2    0.16       0  5003.4    0.07       0
  5009.4    0.16       0  5099.4    0.05       0
Bank Sta=4880.8,5333
Exp/Cntr=0.3,0.1

Type RM Length L Ch R = 1,645,317,317,317
BEGIN DESCRIPTION:
XS3862A
END DESCRIPTION:
XS GIS Cut Line= 3
      2854674.96      7080360.20      2854323.42      7080727.36
      2854188.55      7081041.19
#Sta/Elev= 30
  4508.9  501.50  4681.9  488.53  4752.4  481.90  4809.2  480.33  4865.8  480.03
  4908.3  480.07  4915.5  480.98  4943.8  480.62  4956.6  481.37  4980.9  481.48
  4986.3  481.73  4993.2  479.25  4997.1  475.41  4997.6  474.61  5002.7  474.61
  5003.2  475.41  5007.4  480.06  5017.2  480.27  5023.0  481.26  5099.1  481.57
  5128.1  481.00  5150.6  481.90  5154.0  482.06  5180.6  483.36  5199.2  485.16
  5227.7  488.06  5280.2  488.97  5303.8  490.61  5309.2  490.28  5358.8  492.40
#Mann=7,-1,0
  4508.9    0.05       0  4956.6    0.16       0  4980.9    0.12       0
  4997.1    0.07       0  5003.2    0.12       0  5154.0    0.16       0
  5199.2    0.05       0
Bank Sta=4752.4,5150.6
Exp/Cntr=0.3,0.1

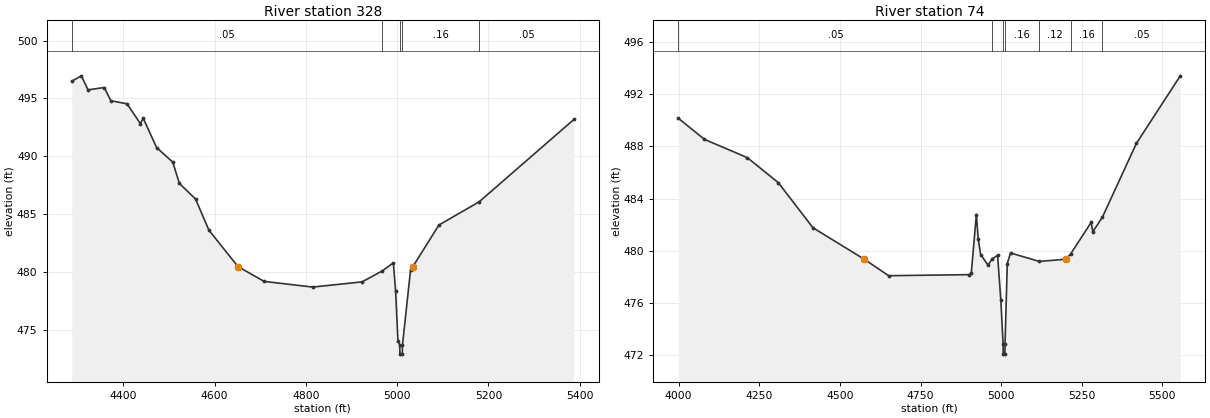
Type RM Length L Ch R = 1,328,254,254,254
BEGIN DESCRIPTION:
Mapping XS da33a4d6
END DESCRIPTION:
XS GIS Cut Line= 3
      2854688.19      7080188.45      2854122.21      7080608.59
      2854018.11      7080990.27
#Sta/Elev= 30
  4286.8  496.48  4307.8  496.95  4322.4  495.74  4357.9  495.94  4372.5  494.80
  4408.0  494.53  4437.2  492.82  4443.4  493.29  4472.7  490.76  4508.1  489.50
  4522.7  487.66  4558.2  486.31  4587.4  483.62  4651.1  480.48  4708.4  479.20
  4814.8  478.71  4923.3  479.16  4967.6  480.11  4991.7  480.80  4996.6  478.39
  5001.8  474.03  5005.6  473.72  5006.1  472.92  5011.2  472.92  5011.7  473.72
  5029.4  480.19  5034.5  480.48  5091.6  484.07  5179.7  486.07  5387.3  493.18
#Mann=5,-1,0
  4286.8    0.05       0  4967.6    0.16       0  5005.6    0.07       0
  5011.7    0.16       0  5179.7    0.05       0
Bank Sta=4651.1,5034.5
Exp/Cntr=0.3,0.1

Type RM Length L Ch R = 1,74,0,0,0
BEGIN DESCRIPTION:
UNT 138 in LFCCL Watershed 1.0
END DESCRIPTION:
XS GIS Cut Line= 3
      2854775.03      7079941.90      2853961.13      7080417.60
      2853941.18      7081031.15
#Sta/Elev= 30
  3998.9  490.15  4080.1  488.53  4213.2  487.13  4309.0  485.22  4416.5  481.77
  4575.5  479.36  4651.2  478.10  4901.7  478.18  4907.5  478.31  4923.2  482.78
  4929.0  480.90  4936.5  479.72  4959.0  478.92  4973.2  479.40  4989.0  479.66
  4999.1  476.21  5006.0  472.90  5006.5  472.10  5011.6  472.10  5012.1  472.90
  5019.1  479.03  5029.1  479.84  5118.2  479.19  5200.5  479.36  5216.0  479.78
  5279.1  482.18  5284.2  481.46  5313.8  482.57  5419.3  488.22  5555.5  493.39
#Mann=7,-1,0
  3998.9    0.05       0  4973.2    0.16       0  5006.0    0.07       0
  5012.1    0.16       0  5118.2    0.12       0  5216.0    0.16       0
  5313.8    0.05       0
Bank Sta=4575.5,5200.5
Exp/Cntr=0.3,0.1

Chan Stop Cuts=-1