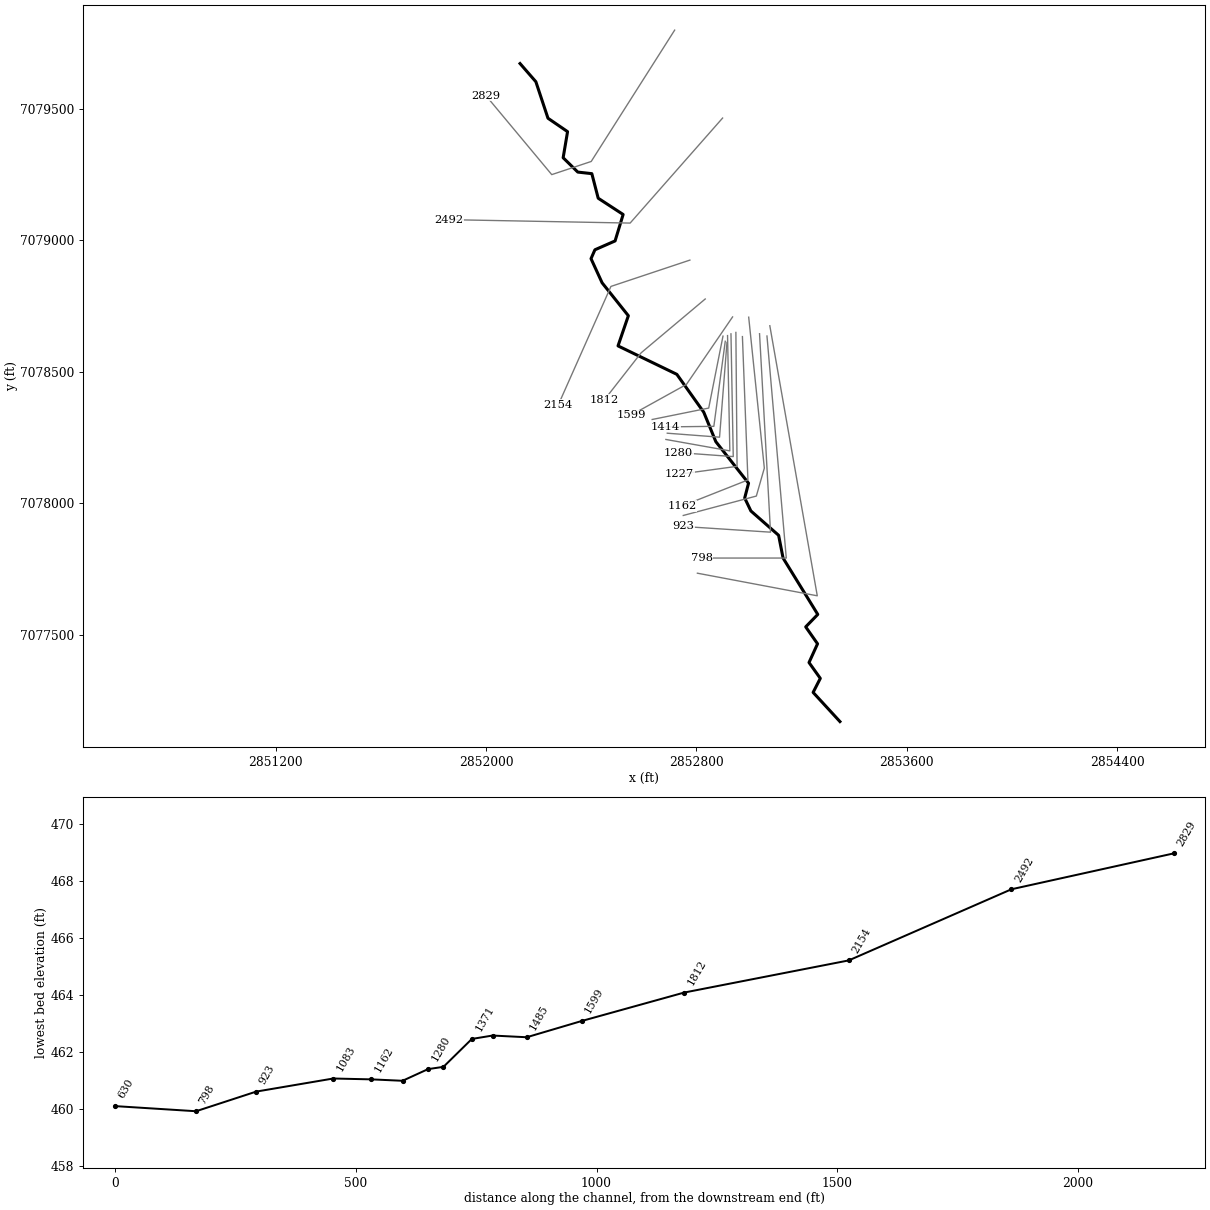
--- UNT 140 in LFCCL Watershed.prj (project) ---

Proj Title=UNT 140 in LFCCL Watershed Base Level Engineering
Current Plan=p01
Default Exp/Contr=0.3,0.1
English Units
Geom File=g01
Flow File=f01
Plan File=p01
Y Axis Title=Elevation
X Axis Title(PF)=Main Channel Distance
X Axis Title(XS)=Station
BEGIN DESCRIPTION:
UNT 140 in LFCCL Watershed
END DESCRIPTION:
DSS Export Rating Curves= 0
DSS Export Rating Curve Sorted= 0
DSS Export Volume Flow Curves= 0
DXF OffsetX= 0
DXF OffsetY= 0
DXF ScaleX= 1
DXF ScaleY= 10

--- UNT 140 in LFCCL Watershed.p01 (plan) ---

Plan Title=Multiple Run
Short Identifier=Multiple
Geom File=g01
Flow File=f01
Subcritical Flow
K Sum by GR= 0
Std Step Tol= 0.01
Critical Tol= 0.01
Num of Std Step Trials= 20
Max Error Tol= 0.3
Flow Tol Ratio= 0.001
Split Flow NTrial= 30
Split Flow Tol= 0.02
Split Flow Ratio= 0.02
Log Output Level= 0
Friction Slope Method= 1
Unsteady Friction Slope Method= 2
Unsteady Bridges Friction Slope Method= 1
Parabolic Critical Depth
Global Vel Dist=  1 , 1 , 1
Global Log Level= 0
CheckData=True
Encroach Param= -1, 0, 0, 0
BEGIN DESCRIPTION:
Multiple Run
END DESCRIPTION:

--- UNT 140 in LFCCL Watershed.f01 (steady flow) ---

Flow Title=Multiple
Number of Profiles=7
Profile Names=10-year,25-year,50-year,1pct_min,100-year,1pct_plu,500-year
River Rch & RM= UNT 140 in LFCCL,Reach-1,2829
     809    1090    1320     792    1581    3154    2262
River Rch & RM= UNT 140 in LFCCL,Reach-1,2492
     850    1146    1387     833    1662    3315    2377
Boundary for River Rch & Prof#=UNT 140 in LFCCL,Reach-1,1
Up Type=0
Dn Type=3
Dn Slope=0.005
Boundary for River Rch & Prof#=UNT 140 in LFCCL,Reach-1,2
Up Type=0
Dn Type=3
Dn Slope=0.005
Boundary for River Rch & Prof#=UNT 140 in LFCCL,Reach-1,3
Up Type=0
Dn Type=3
Dn Slope=0.005
Boundary for River Rch & Prof#=UNT 140 in LFCCL,Reach-1,4
Up Type=0
Dn Type=3
Dn Slope=0.005
Boundary for River Rch & Prof#=UNT 140 in LFCCL,Reach-1,5
Up Type=0
Dn Type=3
Dn Slope=0.005
Boundary for River Rch & Prof#=UNT 140 in LFCCL,Reach-1,6
Up Type=0
Dn Type=3
Dn Slope=0.005
Boundary for River Rch & Prof#=UNT 140 in LFCCL,Reach-1,7
Up Type=0
Dn Type=3
Dn Slope=0.005

--- UNT 140 in LFCCL Watershed.g01 (geometry) ---

Geom Title=Existing Conditions
Program Version=5.07

River Reach=UNT 140 in LFCCL,Reach-1
Reach XY= 30
      2852129.44       7079672.3      2852189.62      7079603.13
      2852235.66      7079464.33      2852310.09      7079413.34
      2852293.35      7079314.15      2852348.99      7079259.63
      2852402.38      7079253.69       2852426.6      7079160.25
      2852521.37      7079098.48      2852490.79      7078997.95
      2852414.08      7078964.25      2852399.31      7078930.52
      2852441.47      7078838.66      2852541.22      7078713.57
      2852501.92       7078598.9      2852725.57      7078490.75
       2852827.8      7078346.91      2852873.82      7078234.69
      2852998.12      7078076.89      2852983.48      7078020.63
      2853007.02      7077971.41      2853112.46      7077878.84
      2853129.36      7077792.39       2853261.3      7077578.06
       2853215.4      7077530.71      2853260.42      7077466.42
        2853228.      7077395.17      2853270.92      7077334.95
      2853243.62      7077281.63      2853345.59      7077170.71

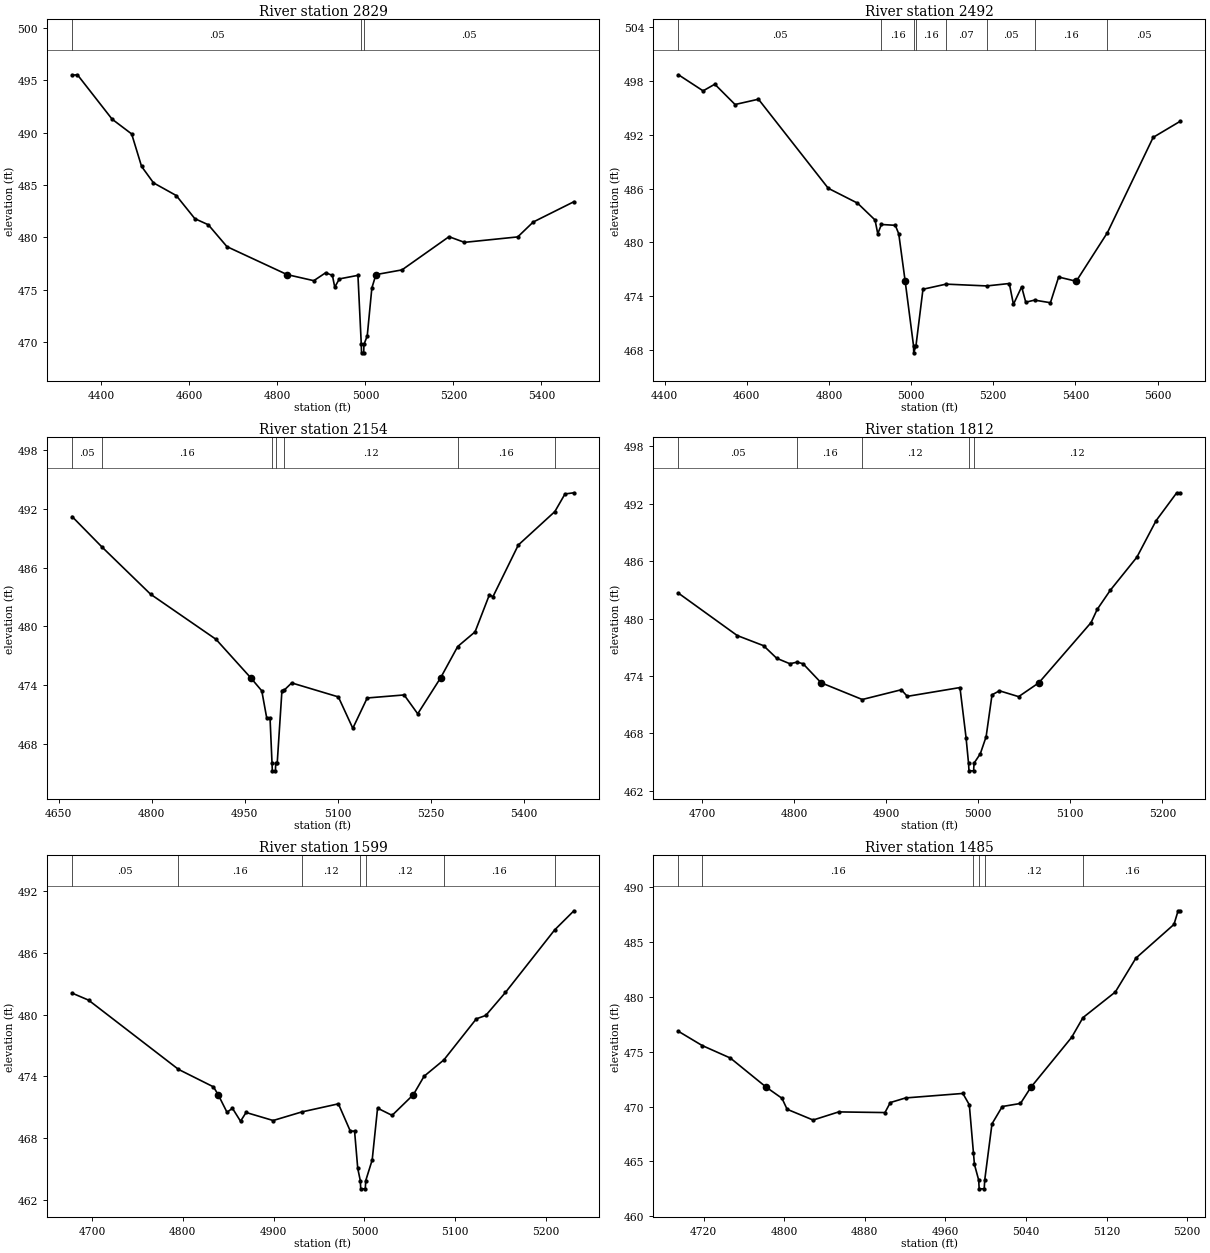
Type RM Length L Ch R = 1 ,2829    ,337,337,337
BEGIN DESCRIPTION:
UNT 140 in LFCCL Watershed 3.0
END DESCRIPTION:
XS GIS Cut Line= 4
      2852717.22      7079799.29        2852400.        7079300.
        2852250.        7079250.      2851999.98      7079550.03
#Sta/Elev= 30
  4333.6  495.48  4345.8  495.52  4424.6  491.28    4469  489.87  4491.5  486.77
  4518.6   485.2  4570.3  483.99  4612.6  481.78  4643.1   481.2  4685.5  479.11
  4822.2  476.44  4882.8  475.86  4909.9  476.62  4925.1  476.36  4930.4  475.24
  4940.9  476.03  4983.1  476.37  4990.7  469.77  4991.2  468.97  4996.2  468.97
  4996.7  469.77  5004.2  470.58  5014.7  475.16    5024  476.44  5083.2  476.89
    5190  480.06  5225.1  479.52  5346.2  480.04  5381.3  481.46  5473.8   483.4
#Mann= 3 ,-1 , 0
  4333.6     .05       0  4990.7     .03       0  4996.7     .05       0
Bank Sta=4822.2,5024
XS Rating Curve= 0 ,0
Exp/Cntr=0.3,0.1

Type RM Length L Ch R = 1 ,2492    ,338,338,338
BEGIN DESCRIPTION:
Mapping XS 9f2f1b11
END DESCRIPTION:
XS GIS Cut Line= 3
      2852899.49      7079465.07      2852547.96      7079065.79
      2851858.96      7079078.79
#Sta/Elev= 30
    4434  498.67  4493.9  496.88  4522.4  497.62  4571.7  495.36  4628.6  495.95
  4798.5  486.03  4869.6  484.38  4912.3   482.5  4918.9  480.97  4927.8     482
  4961.6  481.91    4970  480.96  4985.6  475.68  5005.9  468.51  5006.4  467.71
  5011.9  468.51  5028.9  474.79  5085.1  475.36  5184.2  475.16    5239  475.43
    5249  473.11    5269  475.06    5279  473.35  5300.5  473.58    5339  473.29
    5359  476.15  5401.9  475.68  5477.8   481.1    5589   491.7  5655.1   493.5
#Mann= 8 ,-1 , 0
    4434     .05       0  4927.8     .16       0  5005.9     .07       0
  5011.9     .16       0  5085.1     .07       0  5184.2     .05       0
  5300.5     .16       0  5477.8     .05       0
Bank Sta=4985.6,5401.9
XS Rating Curve= 0 ,0
Exp/Cntr=0.3,0.1

Type RM Length L Ch R = 1 ,2154    ,342,342,342
BEGIN DESCRIPTION:
UNT 140 in LFCCL Watershed 2.0
END DESCRIPTION:
XS GIS Cut Line= 3
      2852775.04      7078925.01        2852475.        7078825.
        2852275.      7078375.01
#Sta/Elev= 30
  4671.7  491.21  4719.5  488.12  4798.2  483.27  4903.6  478.66  4959.8  474.71
  4977.4  473.39  4985.3  470.64  4990.7  470.64  4993.9  466.01  4994.4  465.21
  4999.4  465.21  4999.9  466.01  5002.3  466.03  5009.9  473.42    5014  473.49
  5025.6   474.2  5100.8  472.77  5124.1  469.56  5147.3  472.66  5206.8  472.97
  5228.7  471.04  5265.5  474.71  5293.1  477.92  5321.1  479.42  5344.3  483.23
  5349.8     483  5390.8   488.3  5449.7  491.72    5466  493.52  5480.4  493.64
#Mann= 7 ,-1 , 0
  4671.7     .05       0  4719.5     .16       0  4993.9     .07       0
  4999.9     .16       0    5014     .12       0  5293.1     .16       0
  5449.7     .05       0
Bank Sta=4959.8,5265.5
XS Rating Curve= 0 ,0
Exp/Cntr=0.3,0.1

Type RM Length L Ch R = 1 ,1812    ,213,213,213
BEGIN DESCRIPTION:
XS3865A
END DESCRIPTION:
XS GIS Cut Line= 3
      2852833.42      7078777.22       2852589.8      7078572.58
      2852450.09      7078393.88
#Sta/Elev= 30
  4674.5  482.66  4738.3  478.23  4766.9  477.17  4781.2  475.85  4795.5  475.28
  4803.4  475.45  4809.8  475.28  4829.4  473.29  4874.1  471.54  4916.5  472.56
    4923  471.87  4980.2  472.79  4986.8  467.56  4989.5  464.88    4990  464.08
    4995  464.08  4995.5  464.88  5002.3  465.87  5008.6  467.65    5015  472.03
  5023.1  472.45  5043.9  471.84  5065.9  473.29  5122.6  479.59  5129.2  480.96
  5143.4  482.96  5172.3  486.42  5193.1  490.23  5215.6  493.16  5219.5  493.16
#Mann= 5 ,-1 , 0
  4674.5     .05       0  4803.4     .16       0  4874.1     .12       0
  4989.5     .07       0  4995.5     .12       0
Bank Sta=4829.4,5065.9
XS Rating Curve= 0 ,0
Exp/Cntr=0.3,0.1

Type RM Length L Ch R = 1 ,1599    ,114,114,114
BEGIN DESCRIPTION:
XS3864A
END DESCRIPTION:
XS GIS Cut Line= 3
      2852937.41        7078709.      2852761.99      7078452.37
      2852550.77      7078335.39
#Sta/Elev= 30
  4678.2   482.1  4696.3  481.42  4795.3  474.69  4833.8  472.99    4839  472.23
  4848.7  470.52  4854.7  470.91  4863.6  469.65  4869.7   470.5  4899.5  469.72
  4930.9  470.55  4971.3  471.34  4984.4  468.69  4989.1  468.69  4992.6  465.06
  4995.4  463.88  4995.9  463.08  5000.9  463.08  5001.4  463.88  5008.5  465.89
  5014.4  470.92  5030.4  470.22  5053.8  472.23  5065.6  474.02  5087.4  475.61
  5123.1   479.6  5133.5  479.93  5155.2  482.17  5209.3  488.24  5230.5   490.1
#Mann= 7 ,-1 , 0
  4678.2     .05       0  4795.3     .16       0  4930.9     .12       0
  4995.4     .07       0  5001.4     .12       0  5087.4     .16       0
  5209.3     .12       0
Bank Sta=4839,5053.8
XS Rating Curve= 0 ,0
Exp/Cntr=0.3,0.1

Type RM Length L Ch R = 1 ,1485    ,71,71,71
BEGIN DESCRIPTION:
Mapping XS ecbe5ce5
END DESCRIPTION:
XS GIS Cut Line= 3
      2852900.93      7078636.02      2852846.67      7078362.55
      2852631.82      7078319.14
#Sta/Elev= 30
  4695.1  476.84  4718.6  475.55  4746.6  474.41  4782.3  471.75  4797.8  470.75
  4802.9  469.75  4828.7  468.77  4854.1  469.51    4900  469.45  4905.3  470.36
  4920.4  470.78  4977.3  471.19  4983.7  470.16  4987.8  465.79  4988.8  464.73
    4993  463.31  4993.5  462.51  4998.5  462.51    4999  463.31  5006.2  468.42
  5016.4     470  5034.5  470.28  5044.8  471.75  5085.3   476.3  5096.5  478.09
  5128.6  480.42    5149   483.5  5186.8  486.57  5190.9  487.81  5193.1  487.81
#Mann= 6 ,-1 , 0
  4695.1     .05       0  4718.6     .16       0  4987.8     .12       0
    4993     .07       0    4999     .12       0  5096.5     .16       0
Bank Sta=4782.3,5044.8
XS Rating Curve= 0 ,0
Exp/Cntr=0.3,0.1

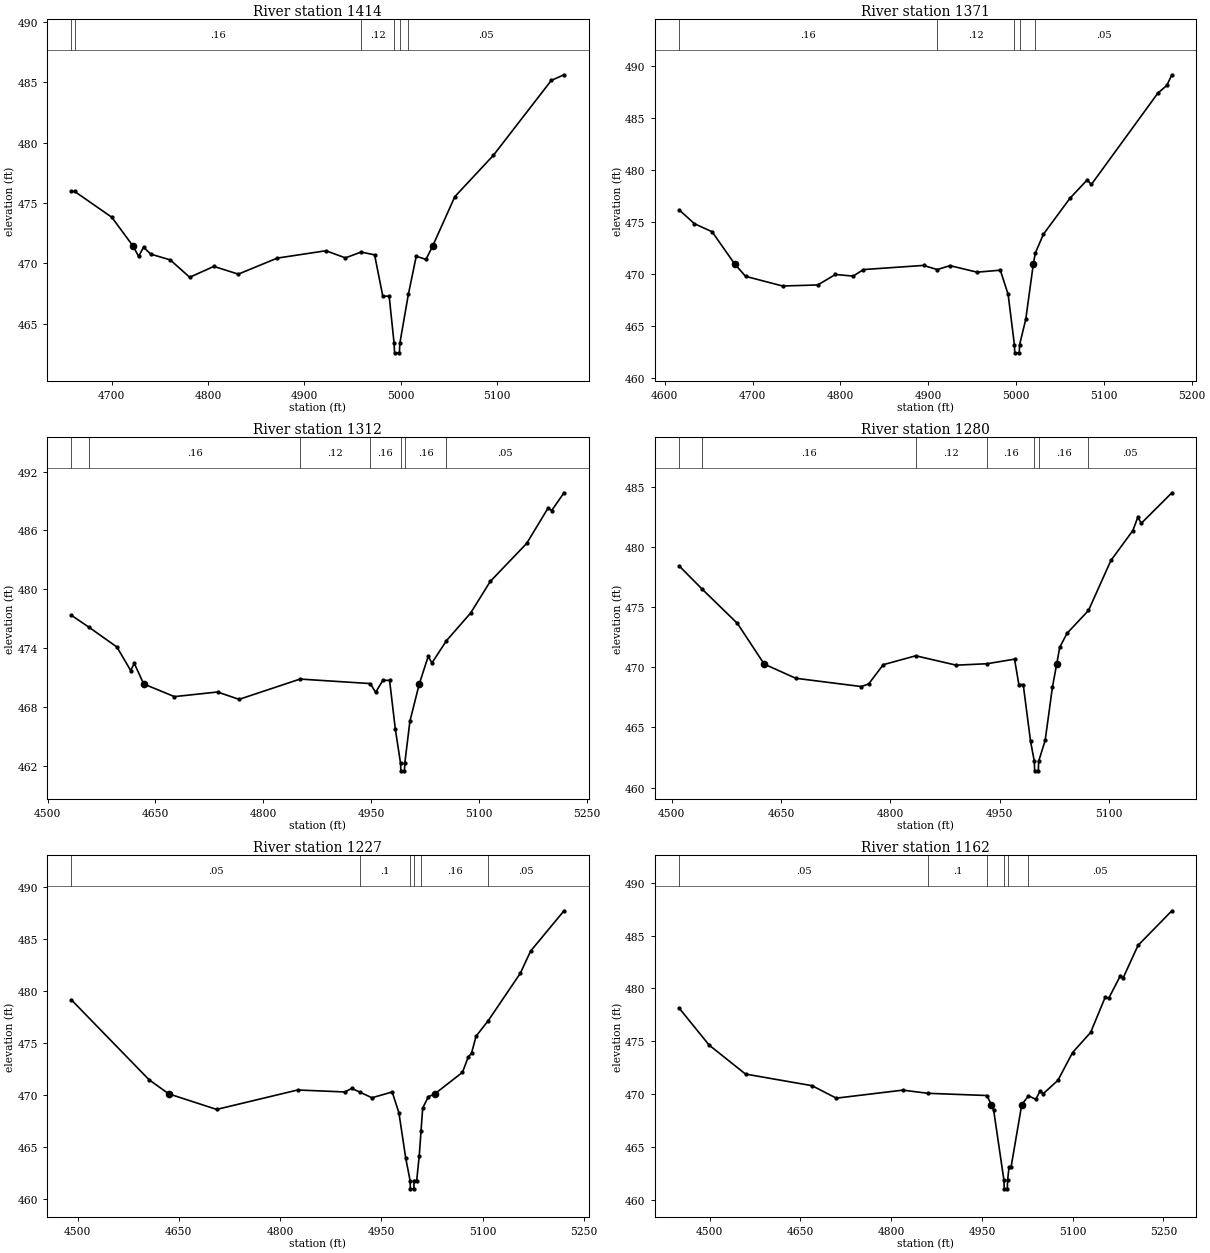
Type RM Length L Ch R = 1 ,1414    ,43,43,43
BEGIN DESCRIPTION:
Mapping XS 7457c1b2
END DESCRIPTION:
XS GIS Cut Line= 3
      2852909.61      7078616.47       2852866.2       7078293.1
      2852681.79      7078290.93
#Sta/Elev= 30
  4658.5  475.96  4661.8  475.96  4700.3  473.82  4722.5  471.41  4728.1  470.57
  4733.2  471.33  4740.7  470.76  4760.9  470.28  4781.1  468.84  4806.1  469.74
  4831.5   469.1  4871.9  470.43  4922.3  471.04  4942.5  470.45  4958.8  470.93
  4972.8   470.7  4981.3  467.27  4987.9  467.27    4993  463.37  4993.5  462.57
  4998.5  462.57    4999  463.37  5007.8  467.42    5016  470.59    5026  470.32
  5032.9  471.41    5056  475.53    5096  478.96    5156  485.17  5169.2  485.64
#Mann= 6 ,-1 , 0
  4658.5     .05       0  4661.8     .16       0  4958.8     .12       0
    4993     .07       0    4999     .12       0  5007.8     .05       0
Bank Sta=4722.5,5032.9
XS Rating Curve= 0 ,0
Exp/Cntr=0.3,0.1

Type RM Length L Ch R = 1 ,1371    ,59,59,59
BEGIN DESCRIPTION:
Mapping XS 1b60d9b7
END DESCRIPTION:
XS GIS Cut Line= 3
      2852916.12      7078612.16       2852887.9      7078251.87
      2852689.17      7078266.99
#Sta/Elev= 30
  4616.7  476.19  4633.9  474.87    4654   474.1  4679.6  471.01  4692.1  469.81
  4734.2  468.88  4774.3  468.98  4794.4  469.99  4814.5  469.83  4826.3  470.46
  4894.7  470.86  4910.3  470.46  4924.8  470.84  4955.6  470.21  4982.1   470.4
    4991  468.07  4998.1  463.25  4998.6  462.45  5003.6  462.45  5004.1  463.25
  5011.1  465.69  5019.7  471.01    5022  472.06  5031.1  473.85  5061.2   477.3
  5080.8  479.07  5085.8  478.65  5161.5  487.44  5171.6  488.17  5177.4   489.2
#Mann= 5 ,-1 , 0
  4616.7     .16       0  4910.3     .12       0  4998.1     .07       0
  5004.1     .12       0    5022     .05       0
Bank Sta=4679.6,5019.7
XS Rating Curve= 0 ,0
Exp/Cntr=0.3,0.1

Type RM Length L Ch R = 1 ,1312    ,32,32,32
BEGIN DESCRIPTION:
Mapping XS 847e043f
END DESCRIPTION:
XS GIS Cut Line= 3
      2852918.29      7078638.15      2852926.97      7078199.79
      2852683.96      7078243.18
#Sta/Elev= 30
  4533.2  477.33  4557.9   476.1  4596.4   474.1  4615.6   471.7  4620.6  472.43
  4633.7  470.33  4676.4  469.04  4736.4  469.51  4766.4  468.76  4851.3  470.83
    4949  470.37  4956.4  469.47  4966.4   470.7  4975.8   470.7  4983.8  465.72
    4991  462.27  4991.5  461.47  4996.5  461.47    4997  462.27  5004.1  466.54
  5017.1  470.33  5029.6  473.15  5034.7  472.47  5054.9  474.74  5088.5  477.56
  5115.9  480.79  5166.6  484.67  5196.2  488.26  5201.3  488.02  5218.5  489.83
#Mann= 7 ,-1 , 0
  4533.2     .05       0  4557.9     .16       0  4851.3     .12       0
    4949     .16       0    4991     .07       0    4997     .16       0
  5054.9     .05       0
Bank Sta=4633.7,5017.1
XS Rating Curve= 0 ,0
Exp/Cntr=0.3,0.1

Type RM Length L Ch R = 1 ,1280    ,53,53,53
BEGIN DESCRIPTION:
Mapping XS 6294d332
END DESCRIPTION:
XS GIS Cut Line= 3
      2852931.31      7078644.69      2852939.99      7078178.09
      2852731.62      7078193.28
#Sta/Elev= 30
  4510.7  478.42  4541.6  476.53  4590.4  473.65  4627.1  470.27  4670.4  469.09
  4760.4   468.4  4770.4  468.62  4790.4  470.22    4835  470.96  4890.5  470.18
  4932.8   470.3  4970.5  470.68  4976.4  468.57  4982.4  468.57  4992.4  463.87
  4997.6  462.19  4998.1  461.39  5003.1  461.39  5003.6  462.19  5012.5  463.92
  5022.5  468.36  5028.3  470.27  5032.5  471.67  5042.5  472.83  5071.9  474.73
  5102.7  478.89  5132.8  481.38  5139.5  482.47  5144.5  481.99  5186.3  484.52
#Mann= 7 ,-1 , 0
  4510.7     .05       0  4541.6     .16       0    4835     .12       0
  4932.8     .16       0  4997.6     .07       0  5003.6     .16       0
  5071.9     .05       0
Bank Sta=4627.1,5028.3
XS Rating Curve= 0 ,0
Exp/Cntr=0.3,0.1

Type RM Length L Ch R = 1 ,1227    ,65,65,65
BEGIN DESCRIPTION:
XS3863A
END DESCRIPTION:
XS GIS Cut Line= 3
        2852950.      7078650.03      2852954.48      7078141.05
        2852736.      7078111.24
#Sta/Elev= 30
    4491  479.15    4606  471.47    4635  470.12    4706  468.62    4826  470.49
    4896   470.3    4906  470.64    4918  470.29    4936  469.74    4966   470.3
    4976  468.28    4986  463.95  4992.5  461.78    4993  460.98    4998  460.98
  4998.5  461.78  5002.3  461.78  5006.1  464.17  5008.7  466.52  5011.2  468.77
  5019.7  469.84  5029.2  470.12  5070.1  472.19  5078.4  473.62  5083.5  474.03
  5090.3  475.67  5108.4  477.17  5155.8  481.72    5171  483.85  5220.5  487.73
#Mann= 6 ,-1 , 0
    4491     .05       0    4918      .1       0  4992.5     .07       0
  4998.5      .1       0  5008.7     .16       0  5108.4     .05       0
Bank Sta=4635,5029.2
XS Rating Curve= 0 ,0
Exp/Cntr=0.3,0.1

Type RM Length L Ch R = 1 ,1162    ,79,79,79
BEGIN DESCRIPTION:
Mapping XS eef1e12c
END DESCRIPTION:
XS GIS Cut Line= 3
      2852974.83      7078634.28      2852995.76      7078089.25
      2852745.76      7077990.29
#Sta/Elev= 30
  4449.8  478.11  4499.1  474.63  4559.2  471.89  4669.2  470.79  4709.3  469.61
  4819.3  470.37  4860.5  470.07  4958.3  469.86  4965.7  468.99  4969.5  468.46
  4986.5  461.83    4987  461.03    4992  461.03  4992.5  461.83  4994.9  463.11
  4998.3  463.11  5015.9  468.99    5027  469.83  5039.1   469.5    5046  470.26
  5051.4  470.03  5075.7   471.3    5100  473.93  5129.8  475.83  5154.1  479.19
  5159.5  479.04  5178.4  481.13  5183.8  481.02  5208.2  484.07  5264.1  487.34
#Mann= 6 ,-1 , 0
  4449.8     .05       0  4860.5      .1       0  4958.3     .16       0
  4986.5     .07       0  4992.5     .16       0    5027     .05       0
Bank Sta=4965.7,5015.9
XS Rating Curve= 0 ,0
Exp/Cntr=0.3,0.1

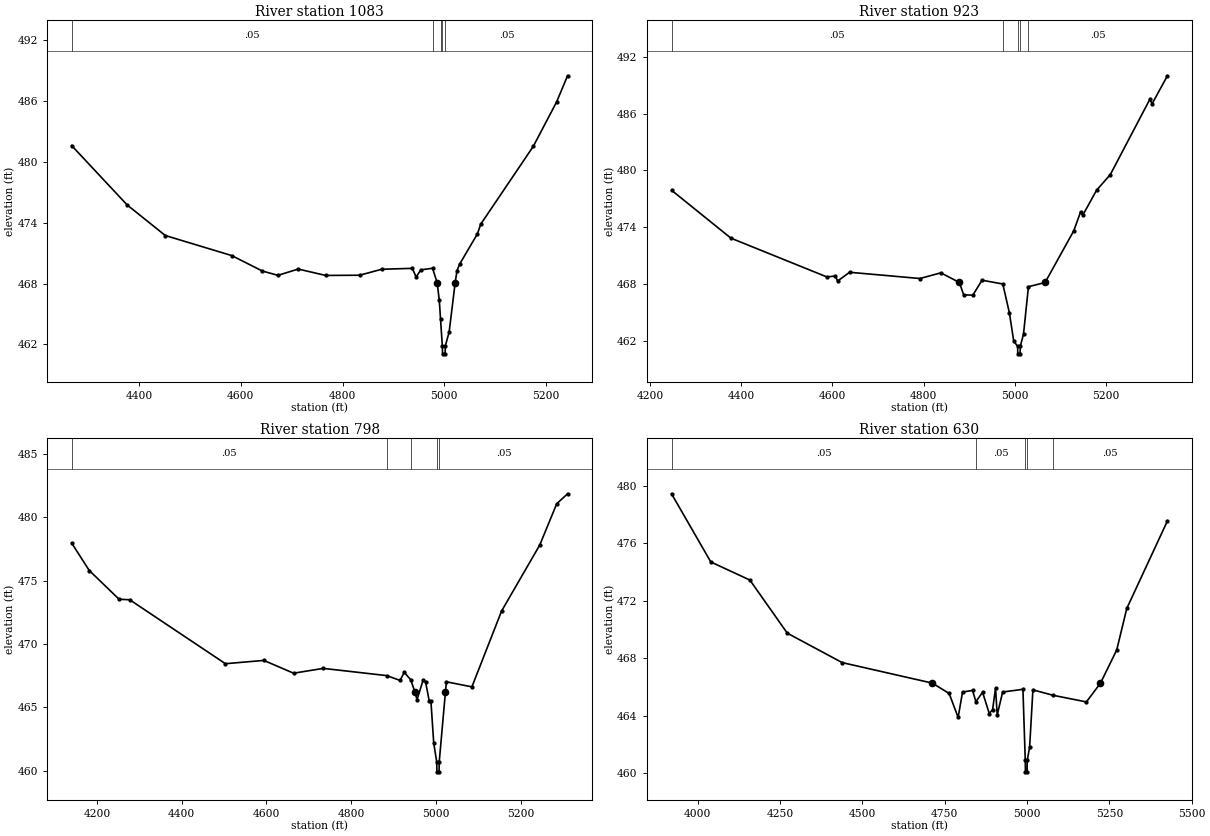
Type RM Length L Ch R = 1 ,1083    ,160,160,160
BEGIN DESCRIPTION:
Mapping XS ba1838a7
END DESCRIPTION:
XS GIS Cut Line= 4
       2852998.7      7078708.07      2853058.15      7078134.37
      2853027.77      7078028.03      2852749.97      7077954.24
#Sta/Elev= 30
  4267.4  481.62  4376.5  475.76  4451.5  472.74  4582.1  470.76  4642.5  469.23
  4672.9  468.81  4712.8  469.43  4766.6   468.8  4833.5  468.82  4876.9  469.41
  4937.1   469.5  4944.5  468.64  4953.7  469.35  4976.8  469.51  4985.8   468.1
    4990  466.39  4992.5   464.5    4996  461.86  4996.5  461.06  5001.5  461.06
    5002  461.86  5009.4   463.2  5021.3   468.1  5024.9  469.28  5030.1  469.92
  5065.1  472.91  5071.4  473.85  5174.9  481.55  5220.6  485.92  5242.2  488.51
#Mann= 5 ,-1 , 0
  4267.4     .05       0  4976.8     .16       0  4992.5     .05       0
    4996     .03       0    5002     .05       0
Bank Sta=4985.8,5021.3
XS Rating Curve= 0 ,0
Exp/Cntr=0.3,0.1

Type RM Length L Ch R = 1 ,923     ,125,125,125
BEGIN DESCRIPTION:
Mapping XS ffbc2484
END DESCRIPTION:
XS GIS Cut Line= 3
      2853039.94      7078645.14      2853081.69      7077890.73
      2852749.87      7077912.42
#Sta/Elev= 30
  4247.1  477.91  4377.4  472.84  4587.8  468.74  4606.5  468.83  4611.5   468.3
  4637.8  469.23  4792.1  468.57  4838.1  469.17  4878.7  468.15  4888.2  466.84
  4908.3  466.81  4928.3  468.39    4974  467.99  4988.4  464.94    4998  461.94
  5006.4   461.4  5006.9   460.6  5011.9   460.6  5012.4   461.4  5019.4  462.68
  5030.2   467.7  5066.8  468.15  5129.6  473.61  5144.7  475.62  5149.7  475.29
  5179.7  477.91  5209.8  479.56  5296.5  487.52  5301.6  487.06  5335.2  490.02
#Mann= 5 ,-1 , 0
  4247.1     .05       0    4974     .07       0  5006.4     .07       0
  5012.4     .07       0  5030.2     .05       0
Bank Sta=4878.7,5066.8
XS Rating Curve= 0 ,0
Exp/Cntr=0.3,0.1

Type RM Length L Ch R = 1 ,798     ,168,168,168
BEGIN DESCRIPTION:
Mapping XS 30d2673d
END DESCRIPTION:
XS GIS Cut Line= 3
      2853068.15      7078636.46       2853141.6      7077792.37
      2852819.37      7077792.37
#Sta/Elev= 30
  4140.5  477.98  4182.1  475.81  4252.4  473.54  4277.4   473.5  4503.1  468.45
  4593.7  468.71  4663.9   467.7  4733.9  468.08  4883.6  467.51  4914.9  467.13
  4924.9  467.77  4940.2  467.18  4949.9  466.22    4955  465.61  4969.7  467.19
  4975.1  467.02  4983.9  465.48  4987.8  465.48  4994.4  462.17  5001.4  460.71
  5001.9  459.91  5006.9  459.91  5007.4  460.71    5022  466.22  5024.4  467.02
  5084.4  466.62  5154.4  472.61  5244.4  477.82  5284.4  481.08    5310  481.87
#Mann= 5 ,-1 , 0
  4140.5     .05       0  4883.6     .07       0  4940.2     .05       0
  5001.4     .03       0  5007.4     .05       0
Bank Sta=4949.9,5022
XS Rating Curve= 0 ,0
Exp/Cntr=0.3,0.1

Type RM Length L Ch R = 1 ,630     ,0,0,0
BEGIN DESCRIPTION:
Mapping XS 42893b8f
END DESCRIPTION:
XS GIS Cut Line= 3
        2853079.      7078675.52      2853259.42      7077648.85
      2852803.66      7077734.79
#Sta/Elev= 30
  3920.2  479.46  4039.5  474.71  4158.2  473.45  4271.8  469.75  4438.5   467.7
  4712.5  466.27  4763.4  465.55  4790.7  463.88  4804.1  465.65  4834.5  465.76
  4844.6  464.98    4865  465.63  4885.3  464.15  4895.4  464.43  4904.3  465.93
  4909.4  464.05  4925.9  465.65  4987.5  465.84  4994.6  460.89  4995.1  460.09
  5000.1  460.09  5000.6  460.89  5007.8   461.8  5017.8   465.8  5079.6  465.42
  5180.2  464.96  5223.1  466.27  5272.4  468.58  5302.9  471.47  5426.4  477.57
#Mann= 5 ,-1 , 0
  3920.2     .05       0  4844.6     .05       0  4994.6     .05       0
  5000.6     .05       0  5079.6     .05       0
Bank Sta=4712.5,5223.1
XS Rating Curve= 0 ,0
Exp/Cntr=0.3,0.1
LCMann Table=0

Chan Stop Cuts=-1
Use User Specified Reach Order=0
Composite Channel Slope=5