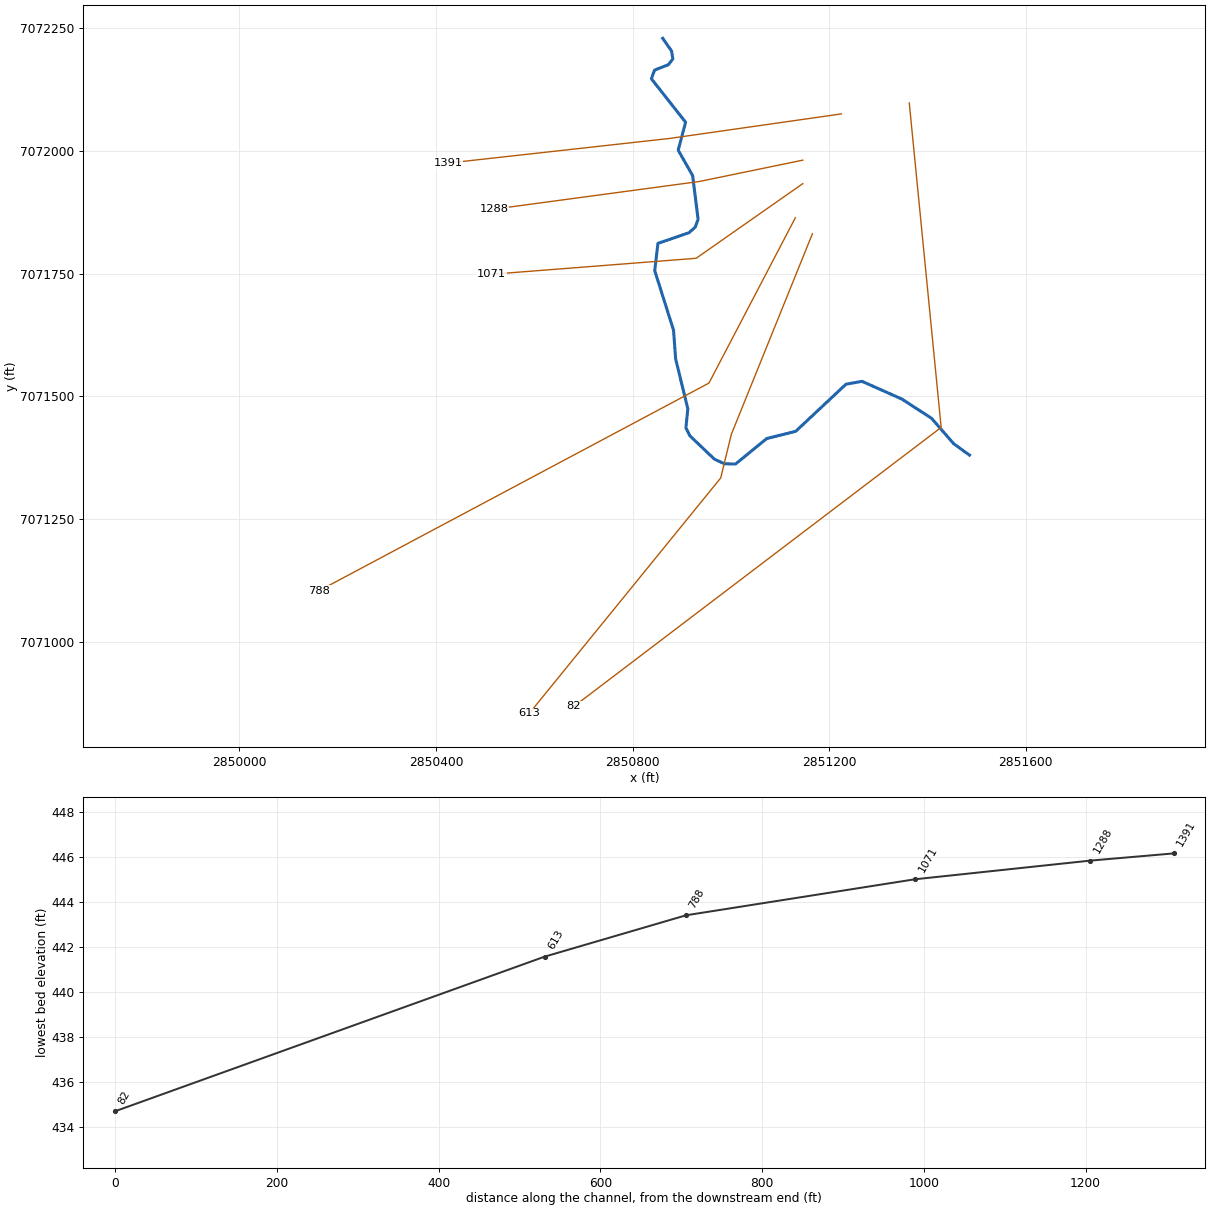
--- UNT 141 in LFCCL Watershed.prj (project) ---

Proj Title=UNT 141 in LFCCL Watershed Base Level Engineering
Current Plan=p01
Default Exp/Contr=0.3,0.1
English Units
Geom File=g01
Flow File=f01
Plan File=p01
BEGIN DESCRIPTION:
UNT 141 in LFCCL Watershed
END DESCRIPTION:

--- UNT 141 in LFCCL Watershed.p01 (plan) ---

Plan Title=Multiple Run
Short Identifier=Multiple
Geom File=g01
Flow File=f01
Subcritical Flow
K Sum by GR= 0
Std Step Tol= 0.01
Critical Tol= 0.01
Num of Std Step Trials= 20
Max Error Tol= 0.3
Flow Tol Ratio= 0.001
Split Flow NTrial= 30
Split Flow Tol= 0.02
Split Flow Ratio= 0.02
Log Output Level= 0
Friction Slope Method= 1
Unsteady Friction Slope Method= 2
Unsteady Bridges Friction Slope Method= 1
Parabolic Critical Depth
Global Vel Dist=  1 , 1 , 1
Global Log Level= 0
CheckData=True
Encroach Param= -1, 0, 0, 0
BEGIN DESCRIPTION:
Multiple Run
END DESCRIPTION:

--- UNT 141 in LFCCL Watershed.f01 (steady flow) ---

Flow Title=Multiple
Number of Profiles=7
Profile Names=10-year,25-year,50-year,1pct_min,100-year,1pct_plu,500-year
River Rch & RM= UNT 141 in LFCCL,Reach-1,1391
     807    1088    1316     789    1575    3142    2250
Boundary for River Rch & Prof#=UNT 141 in LFCCL,Reach-1,1
Up Type=0
Dn Type=3
Dn Slope=0.005
Boundary for River Rch & Prof#=UNT 141 in LFCCL,Reach-1,2
Up Type=0
Dn Type=3
Dn Slope=0.005
Boundary for River Rch & Prof#=UNT 141 in LFCCL,Reach-1,3
Up Type=0
Dn Type=3
Dn Slope=0.005
Boundary for River Rch & Prof#=UNT 141 in LFCCL,Reach-1,4
Up Type=0
Dn Type=3
Dn Slope=0.005
Boundary for River Rch & Prof#=UNT 141 in LFCCL,Reach-1,5
Up Type=0
Dn Type=3
Dn Slope=0.005
Boundary for River Rch & Prof#=UNT 141 in LFCCL,Reach-1,6
Up Type=0
Dn Type=3
Dn Slope=0.005
Boundary for River Rch & Prof#=UNT 141 in LFCCL,Reach-1,7
Up Type=0
Dn Type=3
Dn Slope=0.005

--- UNT 141 in LFCCL Watershed.g01 (geometry) ---

Geom Title=Existing Conditions

River Reach=UNT 141 in LFCCL,Reach-1
Reach XY= 30
      2850861.36      7072228.75      2850879.49      7072202.86
      2850881.98      7072186.88      2850872.91      7072175.11
      2850844.73      7072164.03      2850838.37      7072146.42
      2850908.00      7072058.03      2850892.90      7072001.11
      2850922.31      7071949.43      2850933.39      7071860.35
      2850927.61      7071844.65      2850914.89      7071833.21
      2850851.65      7071811.59      2850845.16      7071756.11
      2850883.43      7071634.81      2850887.67      7071576.56
      2850912.48      7071475.07      2850908.59      7071436.21
      2850916.58      7071420.14      2850966.50      7071372.50
      2850986.85      7071363.09      2851009.57      7071362.62
      2851073.13      7071414.51      2851131.96      7071429.10
      2851234.42      7071525.10      2851267.03      7071530.81
      2851347.87      7071494.85      2851408.29      7071455.73
      2851453.26      7071404.07      2851485.59      7071380.71

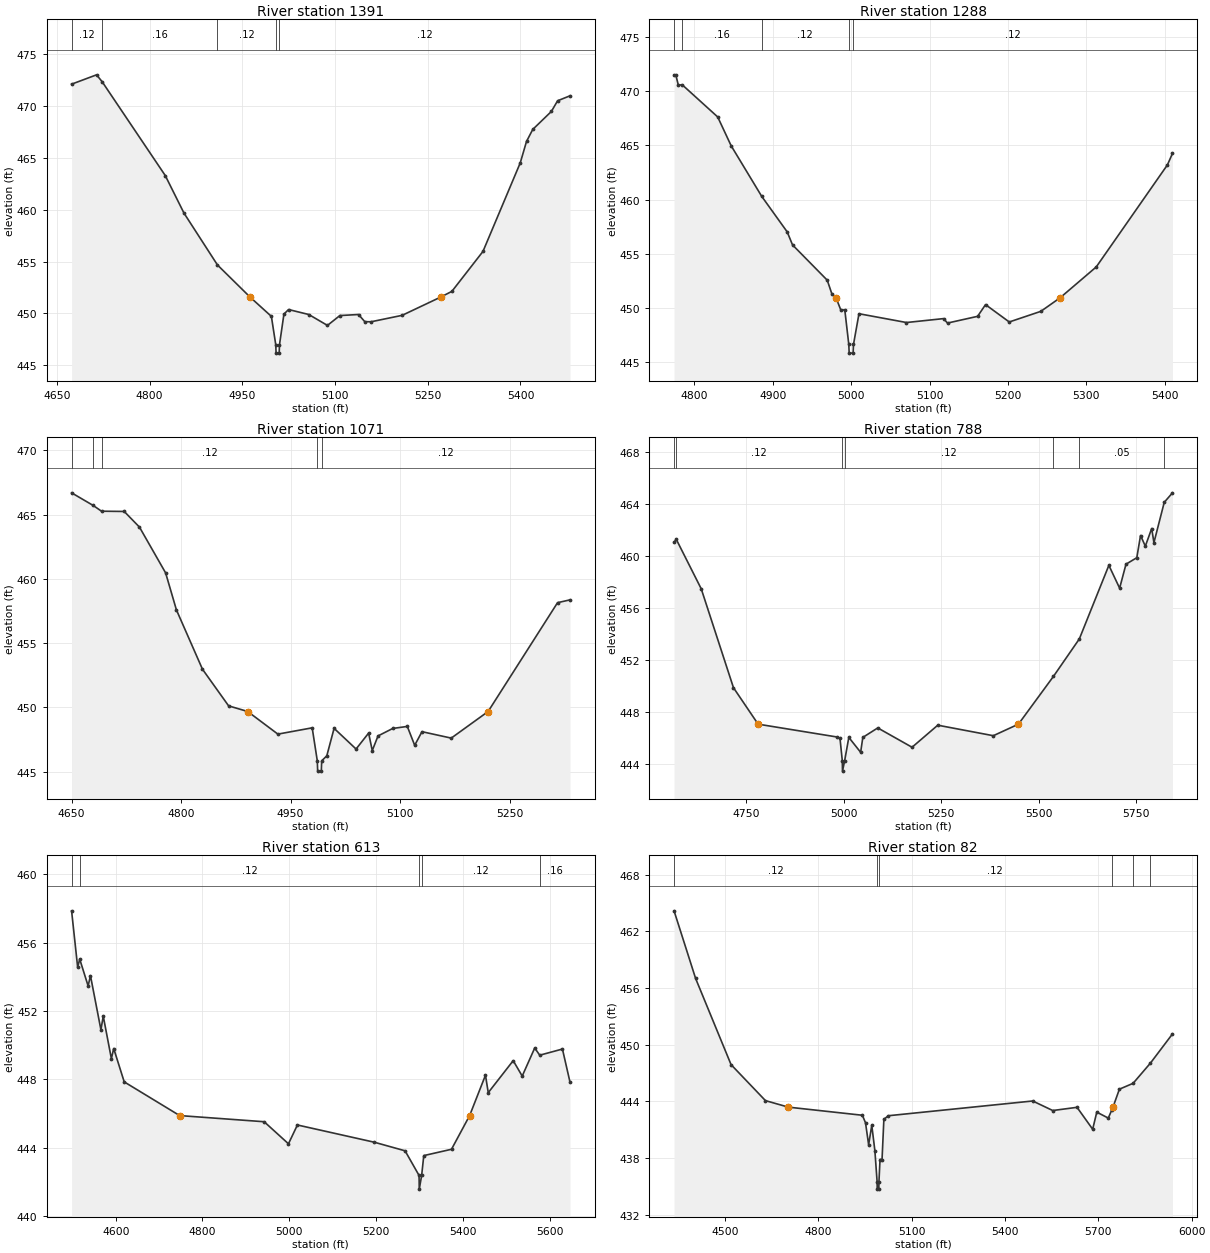
Type RM Length L Ch R = 1,1391,103,103,103
BEGIN DESCRIPTION:
UNT 141 in LFCCL Watershed 2.0
END DESCRIPTION:
XS GIS Cut Line= 3
      2851225.00      7072075.00      2850875.00      7072025.00
      2850425.02      7071975.00
#Sta/Elev= 30
  4673.9  472.09  4714.3  472.99  4723.4  472.32  4825.4  463.29  4855.7  459.67
  4909.9  454.67  4962.6  451.58  4997.1  449.72  5004.2  446.98  5004.7  446.18
  5009.7  446.18  5010.2  446.98  5017.4  449.94  5024.9  450.38  5057.6  449.90
  5087.8  448.85  5107.9  449.80  5138.1  449.90  5148.2  449.21  5158.3  449.20
  5208.6  449.82  5271.0  451.58  5289.1  452.13  5339.4  455.98  5399.7  464.51
  5409.8  466.57  5419.9  467.73  5450.0  469.46  5460.1  470.49  5480.2  470.97
#Mann=5,-1,0
  4673.9    0.12       0  4723.4    0.16       0  4909.9    0.12       0
  5004.2    0.07       0  5010.2    0.12       0
Bank Sta=4962.6,5271
Exp/Cntr=0.3,0.1

Type RM Length L Ch R = 1,1288,217,217,217
BEGIN DESCRIPTION:
XS3868A
END DESCRIPTION:
XS GIS Cut Line= 3
      2851146.43      7071980.88      2850935.95      7071937.48
      2850518.53      7071881.25
#Sta/Elev= 30
  4774.0  471.50  4776.2  471.50  4779.5  470.54  4784.3  470.59  4829.7  467.62
  4846.9  464.96  4885.9  460.30  4918.4  457.03  4925.2  455.83  4969.5  452.58
  4975.5  451.30  4980.7  450.96  4986.8  449.84  4991.9  449.84  4997.0  446.66
  4997.5  445.86  5002.5  445.86  5003.0  446.66  5010.0  449.49  5070.6  448.68
  5117.9  449.04  5123.0  448.63  5161.4  449.25  5171.5  450.33  5201.8  448.73
  5242.1  449.71  5266.7  450.96  5312.8  453.80  5403.6  463.20  5410.1  464.26
#Mann=5,-1,0
  4774.0    0.12       0  4784.3    0.16       0  4885.9    0.12       0
  4997.0    0.07       0  5003.0    0.12       0
Bank Sta=4980.7,5266.7
Exp/Cntr=0.3,0.1

Type RM Length L Ch R = 1,1071,283,283,283
BEGIN DESCRIPTION:
XS3867A
END DESCRIPTION:
XS GIS Cut Line= 3
      2851146.47      7071933.15      2850929.44      7071781.23
      2850512.83      7071748.68
#Sta/Elev= 30
  4650.1  466.69  4679.6  465.71  4691.1  465.26  4722.2  465.24  4743.1  464.02
  4778.9  460.46  4793.7  457.58  4829.4  452.96  4865.2  450.11  4891.4  449.67
  4932.7  447.91  4979.7  448.40  4986.7  445.83  4987.2  445.03  4992.2  445.03
  4992.7  445.83  4999.7  446.22  5009.7  448.36  5039.8  446.75  5057.0  447.99
  5062.0  446.63  5069.9  447.77  5090.0  448.35  5110.0  448.51  5120.1  447.04
  5130.1  448.10  5170.2  447.60  5220.7  449.67  5315.8  458.14  5332.9  458.36
#Mann=5,-1,0
  4650.1    0.12       0  4679.6    0.16       0  4691.1    0.12       0
  4986.7    0.07       0  4992.7    0.12       0
Bank Sta=4891.4,5220.7
Exp/Cntr=0.3,0.1

Type RM Length L Ch R = 1,788,175,175,175
BEGIN DESCRIPTION:
XS3866A
END DESCRIPTION:
XS GIS Cut Line= 3
      2851131.26      7071863.68      2850955.49      7071527.32
      2850162.73      7071105.11
#Sta/Elev= 30
  4565.4  461.06  4571.0  461.30  4635.1  457.48  4717.7  449.86  4780.9  447.05
  4983.4  446.06  4990.8  445.95  4996.7  444.23  4997.2  443.43  5002.7  444.23
  5013.4  446.03  5043.7  444.88  5049.3  446.03  5087.6  446.76  5175.5  445.27
  5241.4  446.97  5383.8  446.16  5448.2  447.05  5537.9  450.73  5604.3  453.62
  5680.0  459.29  5707.6  457.53  5723.9  459.38  5751.6  459.88  5761.2  461.59
  5773.5  460.77  5789.8  462.13  5795.5  461.04  5822.0  464.15  5843.1  464.88
#Mann=7,-1,0
  4565.4    0.16       0  4571.0    0.12       0  4996.7    0.07       0
  5002.7    0.12       0  5537.9    0.16       0  5604.3    0.05       0
  5822.0    0.16       0
Bank Sta=4780.9,5448.2
Exp/Cntr=0.3,0.1

Type RM Length L Ch R = 1,613,531,531,531
BEGIN DESCRIPTION:
XS3869A
END DESCRIPTION:
XS GIS Cut Line= 4
      2851165.98      7071831.11      2851001.06      7071423.16
      2850979.36      7071334.18      2850589.91      7070855.25
#Sta/Elev= 30
  4498.3  457.86  4512.3  454.56  4517.0  455.04  4536.4  453.47  4541.8  454.07
  4565.9  450.91  4571.3  451.70  4590.0  449.22  4595.4  449.81  4619.6  447.86
  4747.4  445.89  4942.2  445.53  4998.2  444.24  5018.8  445.34  5196.4  444.33
  5267.0  443.83  5299.2  442.39  5299.7  441.59  5305.2  442.39  5310.1  443.55
  5374.0  443.92  5415.8  445.89  5452.3  448.25  5458.7  447.23  5516.2  449.10
  5537.0  448.20  5565.8  449.84  5577.4  449.42  5629.7  449.78  5647.2  447.84
#Mann=5,-1,0
  4498.3    0.16       0  4517.0    0.12       0  5299.2    0.07       0
  5305.2    0.12       0  5577.4    0.16       0
Bank Sta=4747.4,5415.8
Exp/Cntr=0.3,0.1

Type RM Length L Ch R = 1,82,0,0,0
BEGIN DESCRIPTION:
UNT 141 in LFCCL Watershed 1.0
END DESCRIPTION:
XS GIS Cut Line= 3
      2851363.05      7072097.31      2851427.96      7071437.10
      2850680.74      7070869.42
#Sta/Elev= 30
  4336.6  464.18  4405.9  457.02  4519.8  447.90  4630.3  444.09  4703.8  443.40
  4941.8  442.54  4951.9  441.74  4961.9  439.42  4972.0  441.48  4982.0  438.79
  4989.1  435.52  4989.6  434.72  4994.6  434.72  4995.1  435.52  4998.5  437.85
  5005.0  437.85  5010.9  442.11  5025.4  442.49  5489.2  444.05  5553.6  443.04
  5631.6  443.38  5681.9  441.06  5695.1  442.87  5732.1  442.24  5742.8  443.06
  5747.2  443.40  5767.8  445.30  5811.8  445.92  5867.5  448.06  5938.4  451.15
#Mann=6,-1,0
  4336.6    0.12       0  4989.1    0.07       0  4995.1    0.12       0
  5742.8    0.16       0  5811.8    0.12       0  5867.5    0.16       0
Bank Sta=4703.8,5747.2
Exp/Cntr=0.3,0.1

Chan Stop Cuts=-1