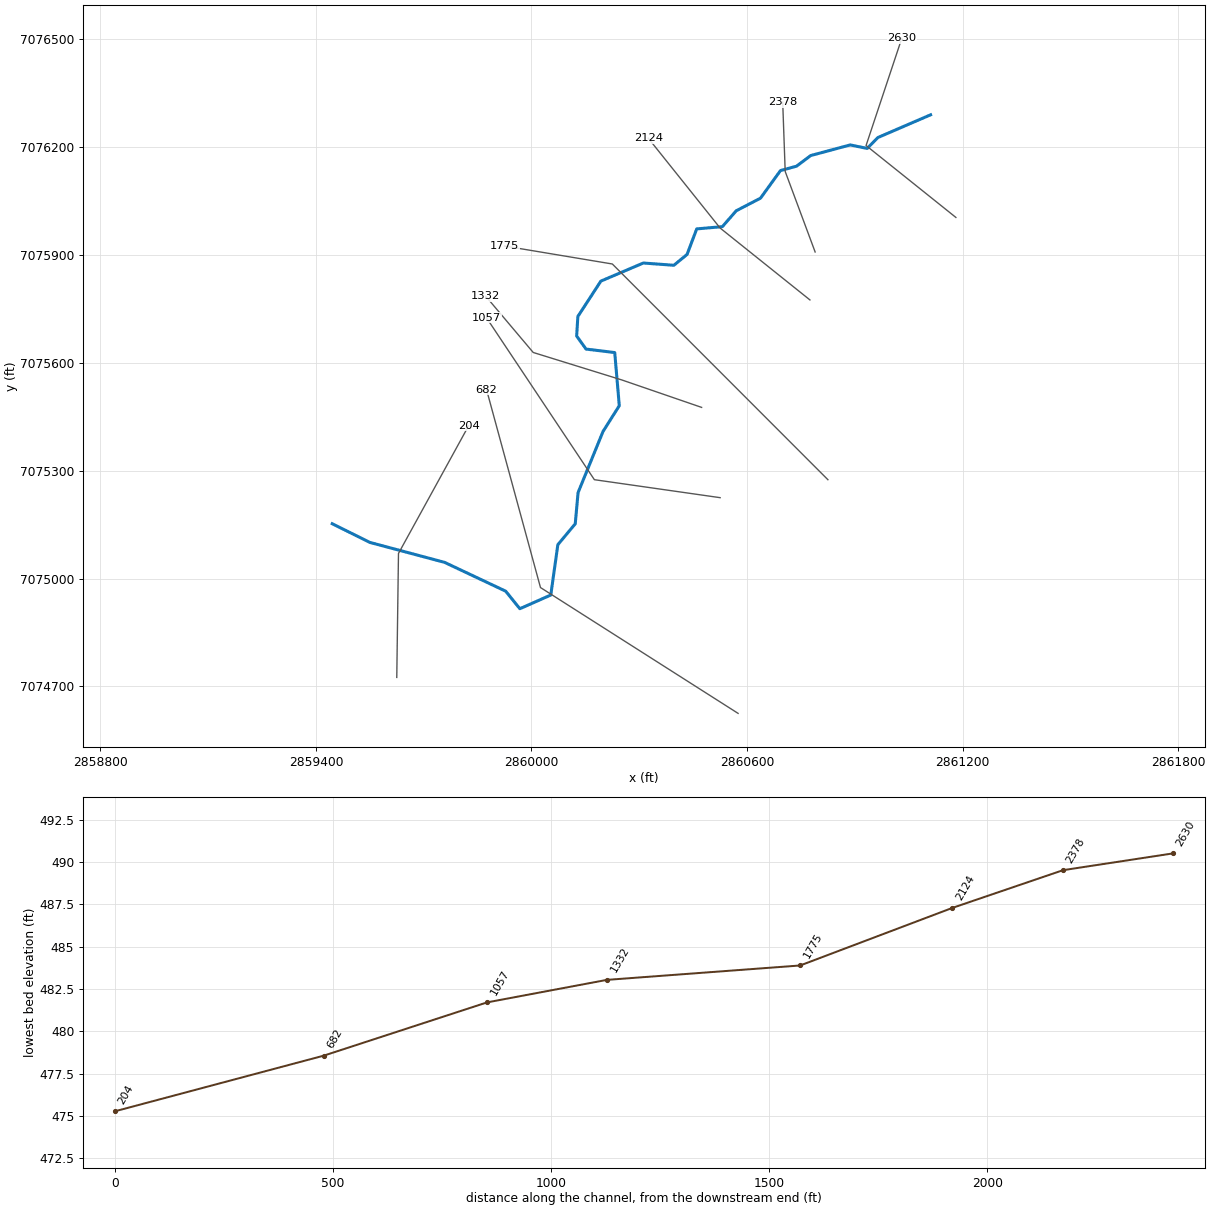
--- UNT 142 in LFCCL Watershed.prj (project) ---

Proj Title=UNT 142 in LFCCL Watershed Base Level Engineering
Current Plan=p01
Default Exp/Contr=0.3,0.1
English Units
Geom File=g01
Flow File=f01
Plan File=p01
BEGIN DESCRIPTION:
UNT 142 in LFCCL Watershed
END DESCRIPTION:

--- UNT 142 in LFCCL Watershed.p01 (plan) ---

Plan Title=Multiple Run
Short Identifier=Multiple
Geom File=g01
Flow File=f01
Subcritical Flow
K Sum by GR= 0
Std Step Tol= 0.01
Critical Tol= 0.01
Num of Std Step Trials= 20
Max Error Tol= 0.3
Flow Tol Ratio= 0.001
Split Flow NTrial= 30
Split Flow Tol= 0.02
Split Flow Ratio= 0.02
Log Output Level= 0
Friction Slope Method= 1
Unsteady Friction Slope Method= 2
Unsteady Bridges Friction Slope Method= 1
Parabolic Critical Depth
Global Vel Dist=  1 , 1 , 1
Global Log Level= 0
CheckData=True
Encroach Param= -1, 0, 0, 0
BEGIN DESCRIPTION:
Multiple Run
END DESCRIPTION:

--- UNT 142 in LFCCL Watershed.f01 (steady flow) ---

Flow Title=Multiple
Number of Profiles=7
Profile Names=10-year,25-year,50-year,1pct_min,100-year,1pct_plu,500-year
River Rch & RM= UNT 142 in LFCCL,Reach-1,2630
     731     986    1195     718    1433    2860    2057
Boundary for River Rch & Prof#=UNT 142 in LFCCL,Reach-1,1
Up Type=0
Dn Type=3
Dn Slope=0.005
Boundary for River Rch & Prof#=UNT 142 in LFCCL,Reach-1,2
Up Type=0
Dn Type=3
Dn Slope=0.005
Boundary for River Rch & Prof#=UNT 142 in LFCCL,Reach-1,3
Up Type=0
Dn Type=3
Dn Slope=0.005
Boundary for River Rch & Prof#=UNT 142 in LFCCL,Reach-1,4
Up Type=0
Dn Type=3
Dn Slope=0.005
Boundary for River Rch & Prof#=UNT 142 in LFCCL,Reach-1,5
Up Type=0
Dn Type=3
Dn Slope=0.005
Boundary for River Rch & Prof#=UNT 142 in LFCCL,Reach-1,6
Up Type=0
Dn Type=3
Dn Slope=0.005
Boundary for River Rch & Prof#=UNT 142 in LFCCL,Reach-1,7
Up Type=0
Dn Type=3
Dn Slope=0.005

--- UNT 142 in LFCCL Watershed.g01 (geometry) ---

Geom Title=Existing Conditions

River Reach=UNT 142 in LFCCL,Reach-1
Reach XY= 30
      2861110.89      7076289.97      2860964.02      7076226.72
      2860934.45      7076196.44      2860887.19      7076206.18
      2860777.26      7076176.69      2860737.65      7076147.04
      2860693.09      7076134.91      2860637.38      7076058.04
      2860569.93      7076023.06      2860531.27      7075978.89
      2860459.87      7075972.62      2860433.01      7075901.53
      2860396.25      7075871.40      2860311.33      7075877.73
      2860193.06      7075827.35      2860129.04      7075729.00
      2860125.66      7075674.57      2860151.89      7075638.30
      2860231.65      7075628.68      2860244.38      7075480.81
      2860199.15      7075409.24      2860129.61      7075239.04
      2860121.77      7075152.24      2860073.33      7075094.18
      2860053.68      7074954.15      2859967.60      7074916.09
      2859928.11      7074964.88      2859758.39      7075044.91
      2859550.00      7075100.59      2859445.29      7075152.52

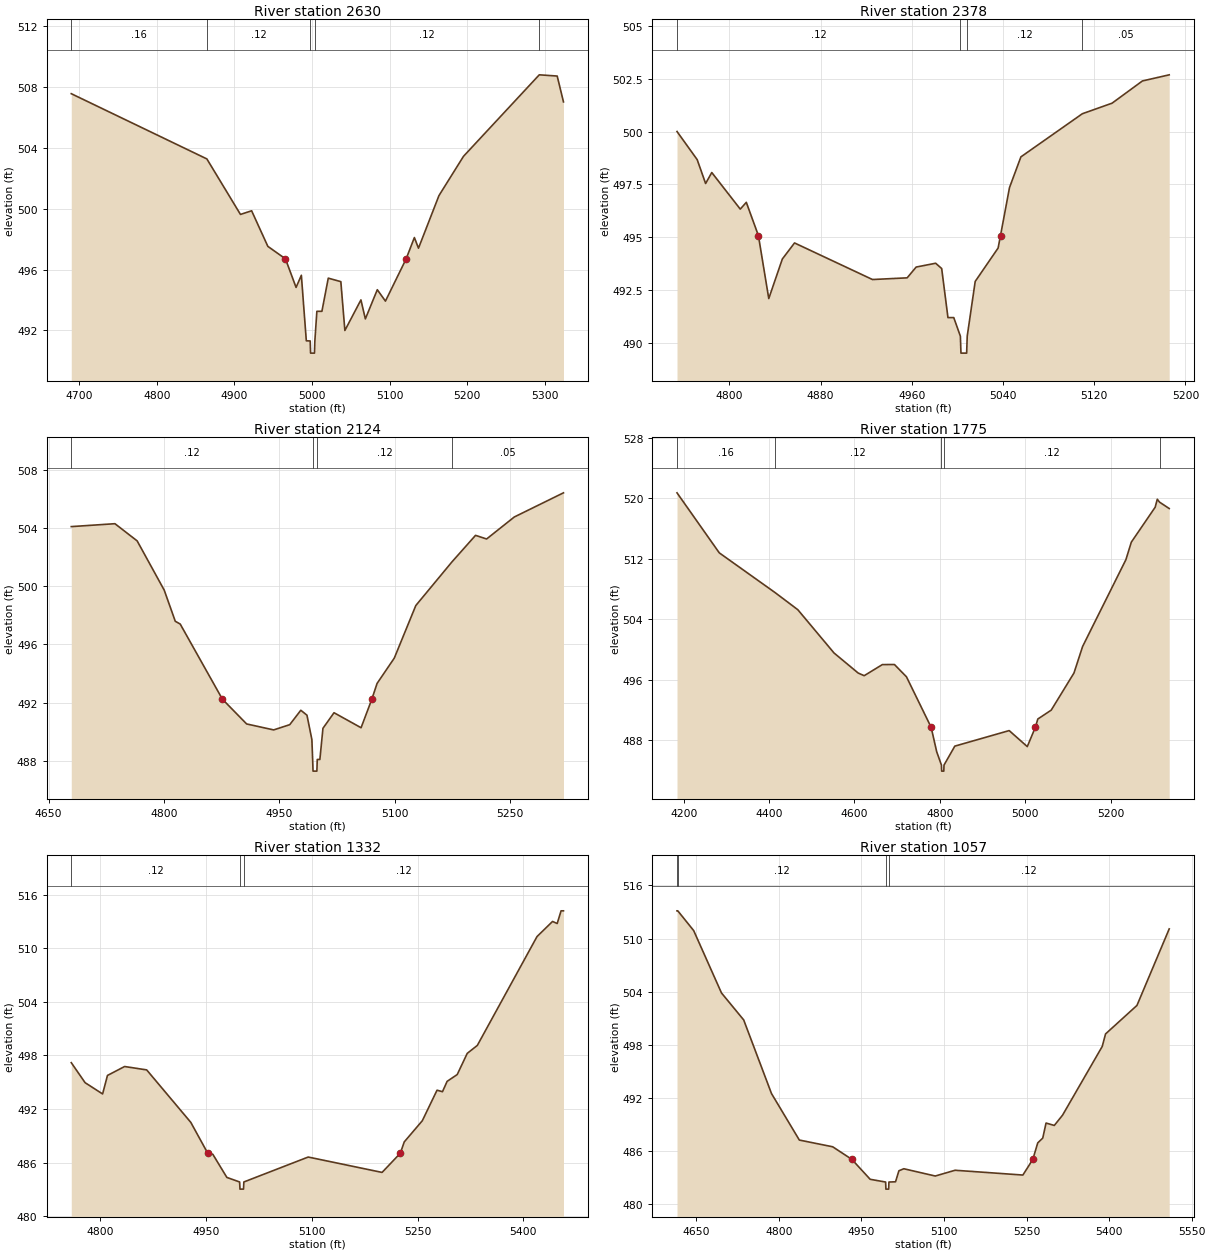
Type RM Length L Ch R = 1,2630,252,252,252
BEGIN DESCRIPTION:
UNT 142 in LFCCL Watershed 6.0
END DESCRIPTION:
XS GIS Cut Line= 3
      2861181.28      7076004.49      2860931.25      7076204.51
      2861030.64      7076502.69
#Sta/Elev= 30
  4689.6  507.57  4864.4  503.28  4907.7  499.63  4922.1  499.87  4943.0  497.53
  4965.7  496.71  4979.4  494.83  4986.2  495.63  4992.6  491.32  4997.6  491.31
  4998.1  490.51  5003.1  490.51  5003.6  491.31  5006.2  493.26  5012.7  493.26
  5020.9  495.44  5037.1  495.21  5042.3  492.00  5063.0  494.01  5068.7  492.76
  5084.1  494.68  5094.6  493.93  5121.3  496.71  5131.9  498.11  5137.2  497.41
  5163.6  500.87  5195.2  503.45  5292.9  508.81  5316.0  508.73  5324.1  507.03
#Mann=5,-1,0
  4689.6    0.16       0  4864.4    0.12       0  4997.6    0.07       0
  5003.6    0.12       0  5292.9    0.05       0
Bank Sta=4965.7,5121.3
Exp/Cntr=0.3,0.1

Type RM Length L Ch R = 1,2378,254,254,254
BEGIN DESCRIPTION:
XS3870A
END DESCRIPTION:
XS GIS Cut Line= 3
      2860789.49      7075908.38      2860706.15      7076132.35
      2860699.21      7076325.05
#Sta/Elev= 30
  4754.0  500.00  4771.7  498.67  4779.1  497.54  4784.5  498.06  4809.5  496.33
  4814.8  496.65  4825.4  495.08  4834.5  492.10  4846.4  493.97  4857.1  494.73
  4925.5  493.00  4955.9  493.08  4963.8  493.59  4980.9  493.77  4986.2  493.52
  4991.7  491.20  4996.8  491.20  5002.6  490.32  5003.1  489.52  5008.1  489.52
  5008.6  490.32  5015.6  492.91  5035.7  494.49  5037.8  495.08  5045.7  497.35
  5055.7  498.80  5109.6  500.84  5135.7  501.34  5162.3  502.39  5185.8  502.68
#Mann=4,-1,0
  4754.0    0.12       0  5002.6    0.07       0  5008.6    0.12       0
  5109.6    0.05       0
Bank Sta=4825.4,5037.8
Exp/Cntr=0.3,0.1

Type RM Length L Ch R = 1,2124,349,349,349
BEGIN DESCRIPTION:
UNT 142 in LFCCL Watershed 5.0
END DESCRIPTION:
XS GIS Cut Line= 3
      2860775.02      7075774.99      2860525.00      7075975.00
      2860325.02      7076224.98
#Sta/Elev= 30
  4679.4  504.08  4736.2  504.28  4765.1  503.10  4800.3  499.72  4814.7  497.58
  4821.1  497.39  4876.0  492.23  4907.5  490.53  4942.7  490.12  4963.6  490.48
  4978.0  491.47  4986.0  491.13  4992.4  489.46  4993.4  488.09  4993.9  487.29
  4998.9  487.29  4999.4  488.09  5002.8  488.09  5006.8  490.23  5021.2  491.30
  5056.4  490.27  5070.4  492.23  5077.2  493.31  5099.6  495.05  5127.6  498.66
  5174.5  501.65  5205.3  503.48  5219.7  503.23  5255.7  504.74  5319.7  506.40
#Mann=4,-1,0
  4679.4    0.12       0  4993.4    0.07       0  4999.4    0.12       0
  5174.5    0.05       0
Bank Sta=4876,5070.4
Exp/Cntr=0.3,0.1

Type RM Length L Ch R = 1,1775,443,443,443
BEGIN DESCRIPTION:
UNT 142 in LFCCL Watershed 4.0
END DESCRIPTION:
XS GIS Cut Line= 3
      2860825.03      7075274.97      2860225.00      7075875.00
      2859925.01      7075925.00
#Sta/Elev= 30
  4184.4  520.75  4283.4  512.80  4414.0  507.54  4467.3  505.27  4552.1  499.54
  4608.7  496.88  4622.8  496.53  4665.3  498.00  4693.6  498.01  4721.8  496.38
  4779.6  489.69  4792.6  486.45  4803.7  484.69  4804.2  483.89  4809.2  483.89
  4809.7  484.69  4835.0  487.20  4962.3  489.26  5004.7  487.14  5023.6  489.69
  5029.4  490.79  5060.8  491.97  5114.1  496.89  5134.3  500.40  5235.7  511.90
  5248.4  514.22  5304.2  518.84  5309.2  519.90  5314.4  519.52  5337.1  518.67
#Mann=5,-1,0
  4184.4    0.16       0  4414.0    0.12       0  4803.7    0.07       0
  4809.7    0.12       0  5314.4    0.16       0
Bank Sta=4779.6,5023.6
Exp/Cntr=0.3,0.1

Type RM Length L Ch R = 1,1332,275,275,275
BEGIN DESCRIPTION:
XS3871A
END DESCRIPTION:
XS GIS Cut Line= 4
      2860473.54      7075476.10      2860251.29      7075552.49
      2860004.76      7075628.88      2859872.82      7075785.13
#Sta/Elev= 30
  4759.2  497.19  4778.8  494.95  4803.6  493.69  4810.5  495.76  4834.8  496.76
  4866.1  496.38  4928.6  490.51  4952.6  487.06  4959.8  486.94  4979.7  484.35
  4997.8  483.84  4998.3  483.04  5003.3  483.04  5003.8  483.84  5095.0  486.63
  5199.7  484.91  5225.6  487.06  5231.1  488.32  5256.7  490.69  5277.6  494.11
  5285.3  493.94  5291.9  495.10  5306.2  495.86  5320.4  498.23  5334.7  499.12
  5419.3  511.30  5441.3  512.99  5447.9  512.76  5453.4  514.18  5456.8  514.18
#Mann=3,-1,0
  4759.2    0.12       0  4997.8    0.07       0  5003.8    0.12       0
Bank Sta=4952.6,5225.6
Exp/Cntr=0.3,0.1

Type RM Length L Ch R = 1,1057,375,375,375
BEGIN DESCRIPTION:
UNT 142 in LFCCL Watershed 3.0
END DESCRIPTION:
XS GIS Cut Line= 3
      2860525.02      7075225.00      2860175.00      7075275.00
      2859875.00      7075724.99
#Sta/Elev= 30
  4614.8  513.13  4616.2  513.13  4645.1  510.90  4695.6  503.86  4736.0  500.81
  4786.5  492.50  4837.1  487.25  4897.7  486.49  4932.5  485.07  4965.8  482.82
  4993.9  482.51  4994.4  481.71  4999.4  481.71  4999.9  482.51  5011.9  482.54
  5018.0  483.78  5027.0  484.01  5084.1  483.19  5120.1  483.84  5243.3  483.30
  5261.4  485.07  5270.3  486.93  5279.4  487.47  5285.4  489.17  5300.4  488.90
  5315.4  490.06  5387.5  497.82  5393.5  499.23  5450.6  502.45  5509.2  511.09
#Mann=4,-1,0
  4614.8    0.16       0  4616.2    0.12       0  4993.9    0.07       0
  4999.9    0.12       0
Bank Sta=4932.5,5261.4
Exp/Cntr=0.3,0.1

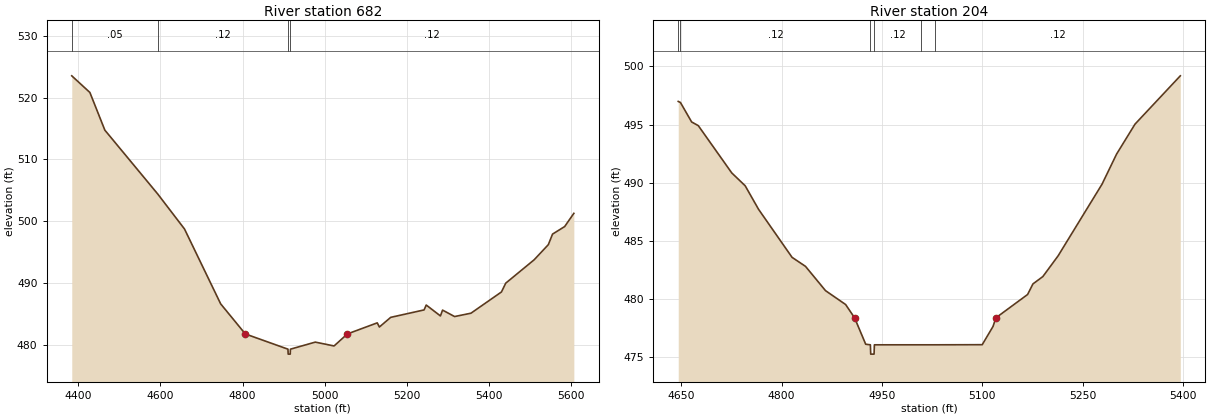
Type RM Length L Ch R = 1,682,478,478,478
BEGIN DESCRIPTION:
UNT 142 in LFCCL Watershed 2.0
END DESCRIPTION:
XS GIS Cut Line= 3
      2860575.03      7074624.98      2860025.00      7074975.00
      2859875.01      7075524.96
#Sta/Elev= 30
  4384.2  523.51  4428.3  520.82  4464.7  514.74  4593.1  504.45  4658.6  498.77
  4746.6  486.68  4806.6  481.82  4910.4  479.36  4910.9  478.56  4915.9  478.56
  4916.4  479.36  4976.9  480.50  5022.6  479.88  5055.0  481.82  5127.7  483.61
  5132.9  482.94  5160.5  484.50  5241.7  485.70  5246.9  486.49  5281.5  484.73
  5286.7  485.67  5316.0  484.63  5355.8  485.17  5430.0  488.60  5440.4  490.02
  5509.5  493.79  5544.1  496.24  5554.4  497.95  5583.8  499.16  5606.2  501.30
#Mann=4,-1,0
  4384.2    0.05       0  4593.1    0.12       0  4910.4    0.07       0
  4916.4    0.12       0
Bank Sta=4806.6,5055
Exp/Cntr=0.3,0.1

Type RM Length L Ch R = 1,204,0,0,0
BEGIN DESCRIPTION:
UNT 142 in LFCCL Watershed 1.0
END DESCRIPTION:
XS GIS Cut Line= 3
      2859625.00      7074724.96      2859629.76      7075069.85
      2859825.00      7075425.00
#Sta/Elev= 30
  4645.7  496.98  4649.0  496.89  4665.7  495.22  4675.7  494.90  4725.7  490.84
  4745.7  489.74  4765.8  487.71  4815.8  483.59  4835.8  482.82  4865.8  480.73
  4895.8  479.54  4909.2  478.40  4925.8  476.13  4932.8  476.08  4933.3  475.28
  4938.3  475.28  4938.8  476.08  5008.9  476.08  5028.8  476.08  5099.9  476.09
  5116.0  477.65  5120.4  478.40  5167.7  480.40  5175.7  481.31  5190.5  481.94
  5213.3  483.72  5278.9  489.87  5300.7  492.46  5328.2  495.03  5395.9  499.18
#Mann=6,-1,0
  4645.7    0.05       0  4649.0    0.12       0  4932.8    0.07       0
  4938.8    0.12       0  5008.9    0.07       0  5028.8    0.12       0
Bank Sta=4909.2,5120.4
Exp/Cntr=0.3,0.1

Chan Stop Cuts=-1