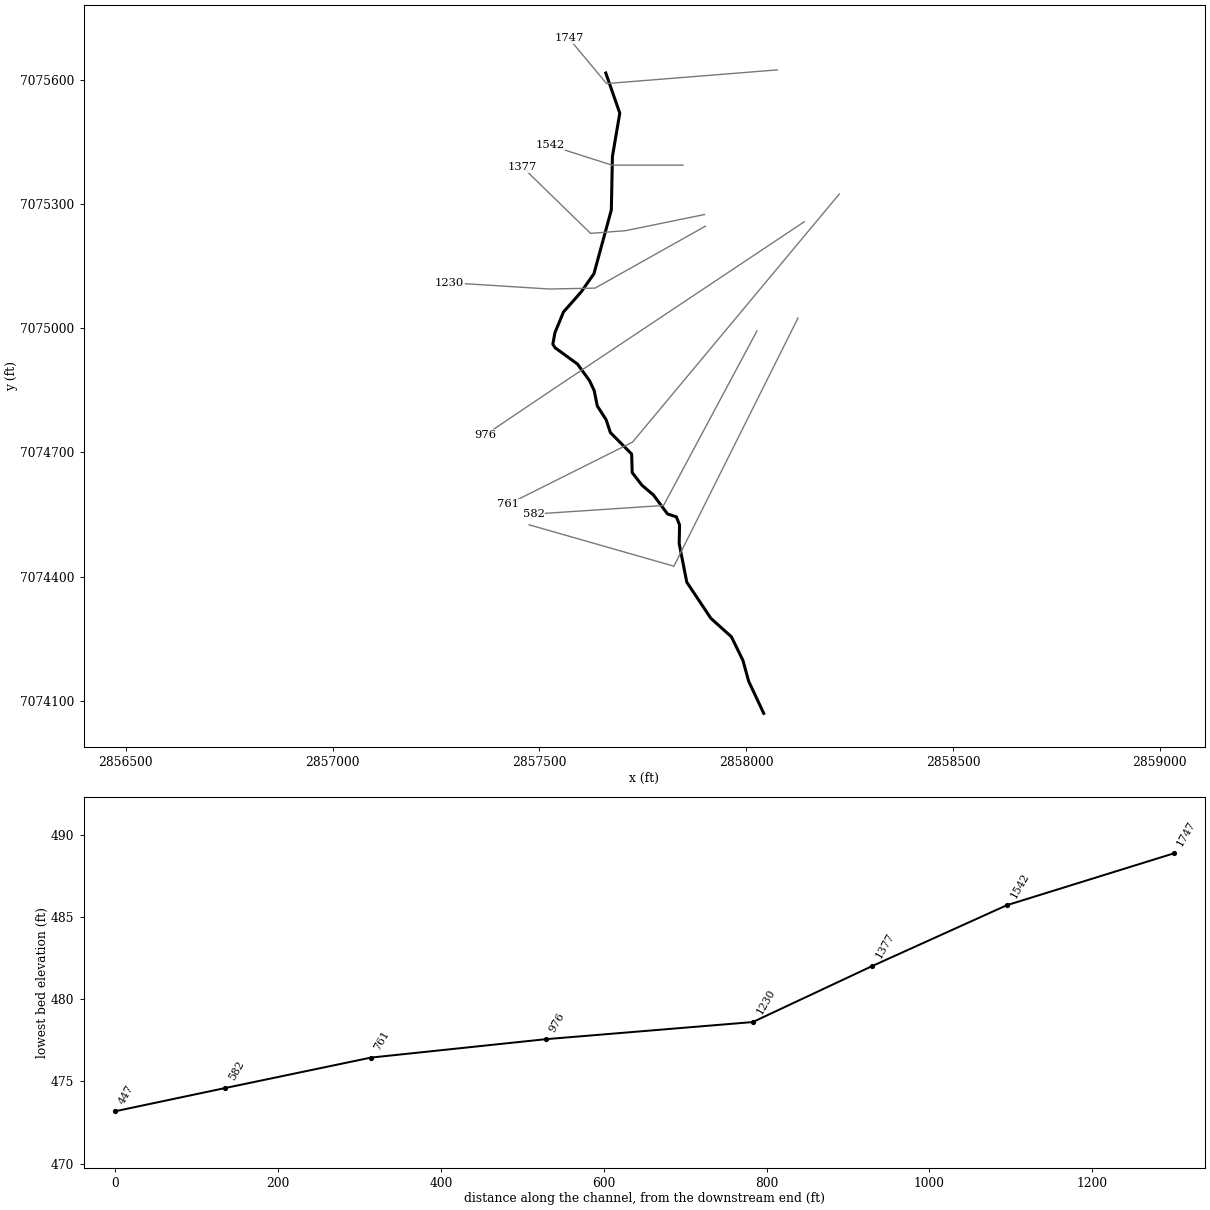
--- UNT 144 in LFCCL Watershed.prj (project) ---

Proj Title=UNT 144 in LFCCL Watershed Base Level Engineering
Current Plan=p01
Default Exp/Contr=0.3,0.1
English Units
Geom File=g01
Flow File=f01
Plan File=p01
BEGIN DESCRIPTION:
UNT 144 in LFCCL Watershed
END DESCRIPTION:

--- UNT 144 in LFCCL Watershed.p01 (plan) ---

Plan Title=Multiple Run
Short Identifier=Multiple
Geom File=g01
Flow File=f01
Subcritical Flow
K Sum by GR= 0
Std Step Tol= 0.01
Critical Tol= 0.01
Num of Std Step Trials= 20
Max Error Tol= 0.3
Flow Tol Ratio= 0.001
Split Flow NTrial= 30
Split Flow Tol= 0.02
Split Flow Ratio= 0.02
Log Output Level= 0
Friction Slope Method= 1
Unsteady Friction Slope Method= 2
Unsteady Bridges Friction Slope Method= 1
Parabolic Critical Depth
Global Vel Dist=  1 , 1 , 1
Global Log Level= 0
CheckData=True
Encroach Param= -1, 0, 0, 0
BEGIN DESCRIPTION:
Multiple Run
END DESCRIPTION:

--- UNT 144 in LFCCL Watershed.f01 (steady flow) ---

Flow Title=Multiple
Number of Profiles=7
Profile Names=10-year,25-year,50-year,1pct_min,100-year,1pct_plu,500-year
River Rch & RM= UNT 144 in LFCCL,Reach-1,1747
     335     430     504     294     588    1172     794
Boundary for River Rch & Prof#=UNT 144 in LFCCL,Reach-1,1
Up Type=0
Dn Type=3
Dn Slope=0.005
Boundary for River Rch & Prof#=UNT 144 in LFCCL,Reach-1,2
Up Type=0
Dn Type=3
Dn Slope=0.005
Boundary for River Rch & Prof#=UNT 144 in LFCCL,Reach-1,3
Up Type=0
Dn Type=3
Dn Slope=0.005
Boundary for River Rch & Prof#=UNT 144 in LFCCL,Reach-1,4
Up Type=0
Dn Type=3
Dn Slope=0.005
Boundary for River Rch & Prof#=UNT 144 in LFCCL,Reach-1,5
Up Type=0
Dn Type=3
Dn Slope=0.005
Boundary for River Rch & Prof#=UNT 144 in LFCCL,Reach-1,6
Up Type=0
Dn Type=3
Dn Slope=0.005
Boundary for River Rch & Prof#=UNT 144 in LFCCL,Reach-1,7
Up Type=0
Dn Type=3
Dn Slope=0.005

--- UNT 144 in LFCCL Watershed.g01 (geometry) ---

Geom Title=Existing Conditions

River Reach=UNT 144 in LFCCL,Reach-1
Reach XY= 30
      2857660.26      7075617.45      2857694.14      7075520.45
      2857676.38      7075415.88      2857673.67      7075286.34
      2857631.72      7075132.31      2857600.68      7075088.02
      2857558.00      7075039.59      2857537.29      7074989.44
      2857532.24      7074961.66      2857537.74      7074953.12
      2857591.76      7074913.78      2857620.98      7074873.59
      2857632.31      7074849.37      2857639.75      7074812.43
      2857661.23      7074778.87      2857671.43      7074747.99
      2857722.78      7074696.24      2857724.17      7074651.24
      2857747.78      7074620.68      2857775.56      7074597.07
      2857809.57      7074551.28      2857830.84      7074544.33
      2857838.65      7074524.80      2857837.78      7074479.66
      2857856.11      7074386.35      2857914.47      7074298.81
      2857963.94      7074254.41      2857991.85      7074197.33
      2858005.81      7074146.58      2858042.18      7074069.11

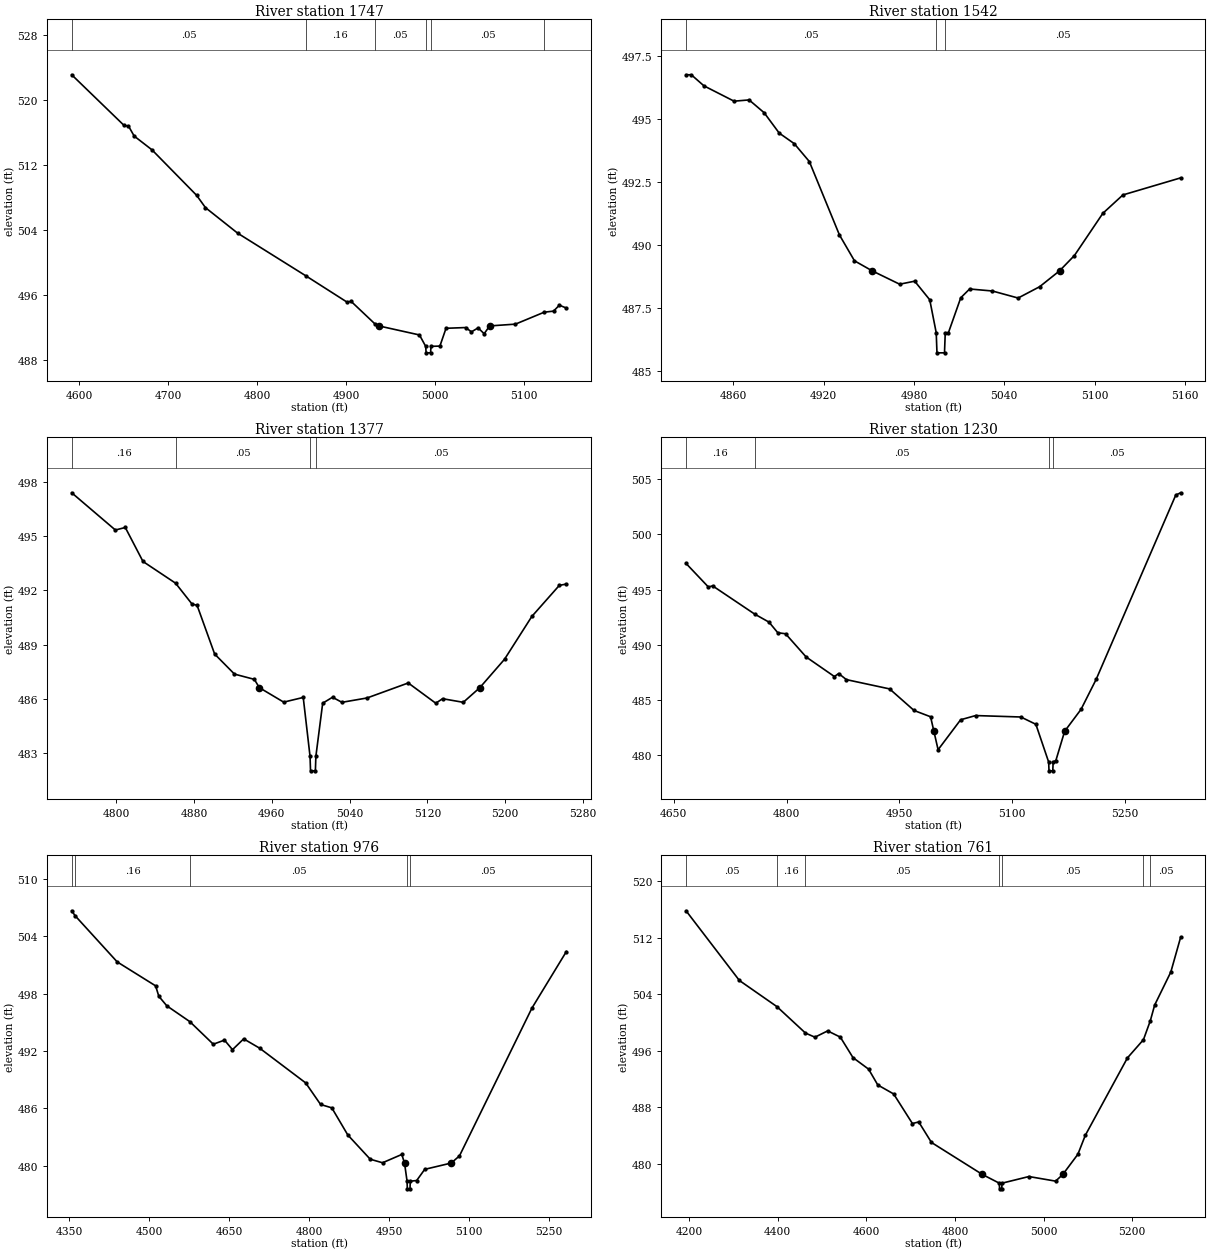
Type RM Length L Ch R = 1,1747,205,205,205
BEGIN DESCRIPTION:
UNT 144 in LFCCL Watershed 5.0
END DESCRIPTION:
XS GIS Cut Line= 3
      2858075.04      7075625.00      2857662.09      7075591.91
      2857571.01      7075701.28
#Sta/Elev= 30
  4591.4  523.06  4650.3  516.83  4655.3  516.75  4661.7  515.52  4681.7  513.83
  4731.9  508.24  4741.9  506.72  4778.1  503.58  4854.6  498.35  4900.9  495.12
  4905.9  495.18  4932.4  492.44  4937.0  492.17  4982.7  491.06  4989.7  489.66
  4990.2  488.86  4995.2  488.86  4995.7  489.66  5005.7  489.69  5012.6  491.88
  5034.7  491.97  5041.2  491.44  5048.7  491.93  5055.5  491.21  5061.7  492.17
  5090.7  492.39  5123.1  493.86  5133.6  493.99  5140.1  494.72  5148.0  494.37
#Mann=6,-1,0
  4591.4    0.05       0  4854.6    0.16       0  4932.4    0.05       0
  4989.7    0.03       0  4995.7    0.05       0  5123.1    0.16       0
Bank Sta=4937,5061.7
Exp/Cntr=0.3,0.1

Type RM Length L Ch R = 1,1542,165,165,165
BEGIN DESCRIPTION:
XS3872A
END DESCRIPTION:
XS GIS Cut Line= 3
      2857846.94      7075394.65      2857675.52      7075394.65
      2857525.77      7075442.39
#Sta/Elev= 30
  4828.6  496.77  4832.1  496.77  4840.5  496.33  4860.5  495.72  4870.5  495.77
  4880.5  495.26  4890.5  494.45  4900.5  494.03  4910.5  493.32  4930.5  490.40
  4940.5  489.37  4952.3  488.97  4970.5  488.44  4980.5  488.56  4990.5  487.82
  4994.8  486.51  4995.3  485.71  5000.3  485.71  5000.8  486.51  5002.9  486.51
  5011.1  487.90  5017.0  488.25  5032.1  488.17  5049.2  487.89  5063.5  488.34
  5076.7  488.97  5086.6  489.58  5105.5  491.26  5118.8  491.99  5157.2  492.67
#Mann=3,-1,0
  4828.6    0.05       0  4994.8    0.03       0  5000.8    0.05       0
Bank Sta=4952.3,5076.7
Exp/Cntr=0.3,0.1

Type RM Length L Ch R = 1,1377,147,147,147
BEGIN DESCRIPTION:
XS3873A
END DESCRIPTION:
XS GIS Cut Line= 4
      2857899.00      7075275.28      2857708.07      7075236.23
      2857623.43      7075229.72      2857459.41      7075389.42
#Sta/Elev= 30
  4754.2  497.40  4799.1  495.34  4809.3  495.48  4827.5  493.60  4861.0  492.40
  4878.0  491.24  4883.1  491.18  4901.2  488.48  4921.6  487.37  4942.0  487.08
  4947.2  486.62  4972.2  485.82  4992.3  486.08  4999.3  482.82  4999.8  482.02
  5004.8  482.02  5005.3  482.82  5012.3  485.76  5022.4  486.09  5032.1  485.81
  5057.9  486.05  5100.3  486.88  5128.6  485.76  5135.6  486.01  5156.9  485.81
  5173.9  486.62  5199.3  488.19  5227.4  490.56  5255.7  492.28  5262.9  492.35
#Mann=4,-1,0
  4754.2    0.16       0  4861.0    0.05       0  4999.3    0.03       0
  5005.3    0.05       0
Bank Sta=4947.2,5173.9
Exp/Cntr=0.3,0.1

Type RM Length L Ch R = 1,1230,254,254,254
BEGIN DESCRIPTION:
XS3874A
END DESCRIPTION:
XS GIS Cut Line= 4
      2857901.25      7075247.10      2857634.28      7075097.34
      2857523.61      7075095.17      2857282.69      7075110.36
#Sta/Elev= 30
  4666.2  497.37  4695.9  495.24  4701.6  495.34  4757.7  492.78  4776.6  492.06
  4788.3  491.10  4798.6  491.01  4826.0  488.91  4863.6  487.14  4869.3  487.41
  4879.6  486.86  4937.1  486.02  4969.6  484.07  4991.6  483.50  4996.0  482.19
  5001.6  480.52  5031.6  483.23  5051.6  483.61  5111.7  483.48  5131.7  482.82
  5148.7  479.41  5149.2  478.61  5154.2  478.61  5154.7  479.41  5158.3  479.54
  5170.0  482.19  5191.8  484.17  5211.9  486.88  5317.9  503.56  5324.4  503.76
#Mann=4,-1,0
  4666.2    0.16       0  4757.7    0.05       0  5148.7    0.03       0
  5154.7    0.05       0
Bank Sta=4996,5170
Exp/Cntr=0.3,0.1

Type RM Length L Ch R = 1,976,215,215,215
BEGIN DESCRIPTION:
UNT 144 in LFCCL Watershed 3.0
END DESCRIPTION:
XS GIS Cut Line= 3
      2858140.20      7075257.82      2857540.19      7074857.81
      2857368.67      7074742.32
#Sta/Elev= 30
  4354.8  506.68  4361.2  506.16  4440.1  501.33  4512.2  498.82  4518.2  497.73
  4533.2  496.73  4576.5  495.07  4620.4  492.71  4641.4  493.14  4656.4  492.14
  4677.4  493.27  4707.5  492.29  4793.7  488.66  4821.7  486.40  4842.7  486.05
  4872.7  483.21  4914.8  480.67  4937.9  480.30  4974.0  481.17  4979.1  480.27
  4983.9  478.37  4984.4  477.57  4989.4  477.57  4989.9  478.37  5001.9  478.44
  5017.0  479.61  5066.7  480.27  5082.2  481.02  5218.0  496.48  5282.7  502.41
#Mann=5,-1,0
  4354.8    0.05       0  4361.2    0.16       0  4576.5    0.05       0
  4983.9    0.03       0  4989.9    0.05       0
Bank Sta=4979.1,5066.7
Exp/Cntr=0.3,0.1

Type RM Length L Ch R = 1,761,179,179,179
BEGIN DESCRIPTION:
UNT 144 in LFCCL Watershed 2.0
END DESCRIPTION:
XS GIS Cut Line= 3
      2858224.99      7075324.99      2857725.00      7074725.00
      2857425.02      7074575.01
#Sta/Elev= 30
  4193.1  515.78  4313.5  505.92  4398.3  502.22  4462.7  498.48  4484.0  497.90
  4512.7  498.79  4541.3  497.91  4569.9  495.01  4605.1  493.38  4625.9  491.14
  4661.7  489.87  4704.0  485.69  4718.3  485.91  4747.0  483.01  4862.0  478.48
  4900.2  477.25  4900.7  476.45  4905.7  476.45  4906.2  477.25  4966.9  478.19
  5027.2  477.54  5043.4  478.48  5077.5  481.34  5094.3  484.03  5189.3  494.97
  5225.5  497.55  5241.0  500.23  5250.8  502.45  5287.2  507.11  5309.5  512.06
#Mann=7,-1,0
  4193.1    0.05       0  4398.3    0.16       0  4462.7    0.05       0
  4900.2    0.03       0  4906.2    0.05       0  5225.5    0.08       0
  5241.0    0.05       0
Bank Sta=4862,5043.4
Exp/Cntr=0.3,0.1

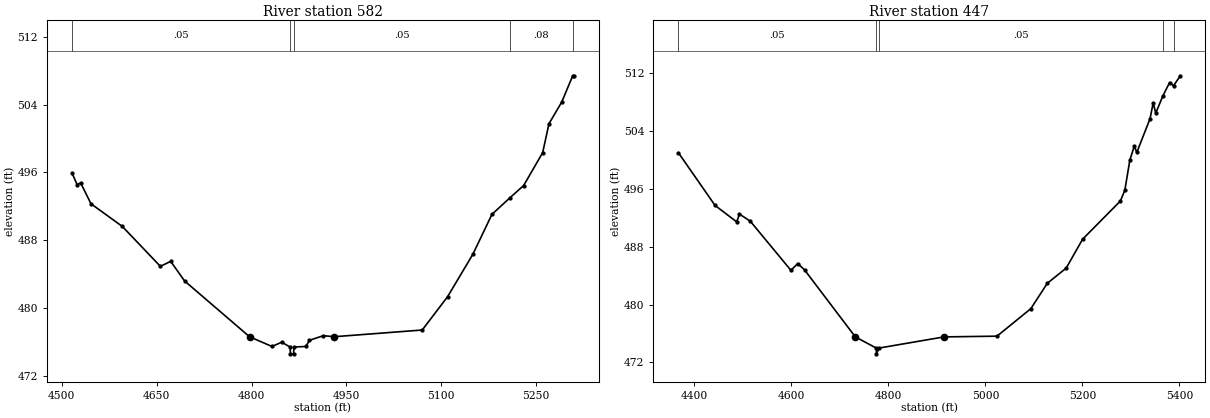
Type RM Length L Ch R = 1,582,135,135,135
BEGIN DESCRIPTION:
Mapping XS fe86065f
END DESCRIPTION:
XS GIS Cut Line= 3
      2858025.72      7074993.69      2857800.00      7074571.77
      2857485.79      7074550.94
#Sta/Elev= 30
  4516.1  495.94  4524.3  494.56  4529.9  494.76  4546.2  492.30  4595.7  489.63
  4655.9  484.92  4672.2  485.51  4694.1  483.20  4796.8  476.62  4832.2  475.47
  4847.7  475.97  4861.0  475.40  4861.5  474.60  4866.5  474.60  4867.0  475.40
  4885.9  475.47  4891.6  476.20  4913.5  476.74  4930.7  476.62  5069.8  477.41
  5109.9  481.34  5149.9  486.35  5180.0  491.05  5208.6  493.02  5230.1  494.45
  5260.2  498.33  5270.2  501.75  5290.2  504.28  5307.7  507.40  5309.5  507.40
#Mann=5,-1,0
  4516.1    0.05       0  4861.0    0.03       0  4867.0    0.05       0
  5208.6    0.08       0  5307.7    0.05       0
Bank Sta=4796.8,4930.7
Exp/Cntr=0.3,0.1

Type RM Length L Ch R = 1,447,0,0,0
BEGIN DESCRIPTION:
UNT 144 in LFCCL Watershed 1.0
END DESCRIPTION:
XS GIS Cut Line= 3
      2858125.02      7075025.03      2857825.00      7074425.00
      2857474.96      7074525.01
#Sta/Elev= 30
  4366.9  500.96  4442.4  493.69  4487.1  491.41  4492.7  492.49  4515.1  491.51
  4598.9  484.72  4612.9  485.66  4626.9  484.79  4731.7  475.53  4774.8  473.99
  4775.3  473.19  4780.8  473.99  4914.6  475.53  5023.8  475.63  5093.7  479.44
  5127.5  482.93  5166.5  485.03  5200.3  489.02  5278.3  494.30  5287.4  495.79
  5297.8  499.97  5306.9  501.87  5312.1  501.01  5339.4  505.67  5345.9  507.86
  5351.1  506.42  5365.4  508.75  5379.7  510.66  5388.0  510.23  5401.8  511.59
#Mann=5,-1,0
  4366.9    0.05       0  4774.8    0.03       0  4780.8    0.05       0
  5365.4    0.08       0  5388.0    0.05       0
Bank Sta=4731.7,4914.6
Exp/Cntr=0.3,0.1

Chan Stop Cuts=-1