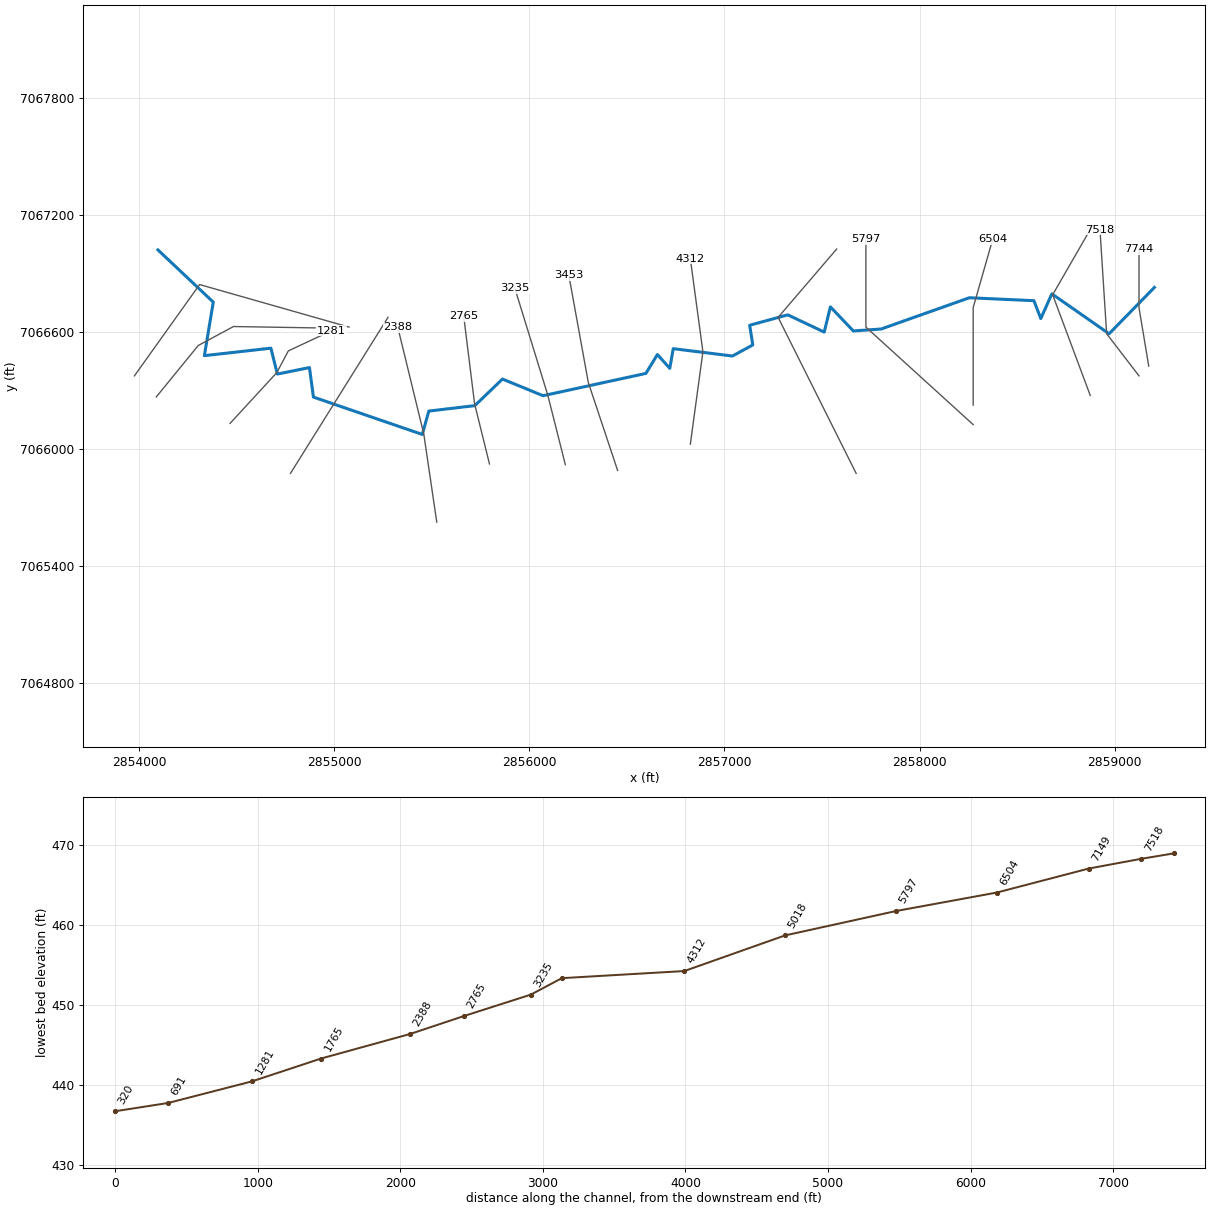
--- UNT 145 in LFCCL Watershed.prj (project) ---

Proj Title=UNT 145 in LFCCL Watershed Base Level Engineering
Current Plan=p01
Default Exp/Contr=0.3,0.1
English Units
Geom File=g01
Flow File=f01
Plan File=p01
BEGIN DESCRIPTION:
UNT 145 in LFCCL Watershed
END DESCRIPTION:

--- UNT 145 in LFCCL Watershed.p01 (plan) ---

Plan Title=Multiple Run
Short Identifier=Multiple
Geom File=g01
Flow File=f01
Subcritical Flow
K Sum by GR= 0
Std Step Tol= 0.01
Critical Tol= 0.01
Num of Std Step Trials= 20
Max Error Tol= 0.3
Flow Tol Ratio= 0.001
Split Flow NTrial= 30
Split Flow Tol= 0.02
Split Flow Ratio= 0.02
Log Output Level= 0
Friction Slope Method= 1
Unsteady Friction Slope Method= 2
Unsteady Bridges Friction Slope Method= 1
Parabolic Critical Depth
Global Vel Dist=  1 , 1 , 1
Global Log Level= 0
CheckData=True
Encroach Param= -1, 0, 0, 0
BEGIN DESCRIPTION:
Multiple Run
END DESCRIPTION:

--- UNT 145 in LFCCL Watershed.f01 (steady flow) ---

Flow Title=Multiple
Number of Profiles=7
Profile Names=10-year,25-year,50-year,1pct_min,100-year,1pct_plu,500-year
River Rch & RM= UNT 145 in LFCCL,Reach-1,7744
     759    1018    1228     734    1465    2923    2080
River Rch & RM= UNT 145 in LFCCL,Reach-1,5797
    1026    1400    1708    1032    2059    4108    2985
Boundary for River Rch & Prof#=UNT 145 in LFCCL,Reach-1,1
Up Type=0
Dn Type=3
Dn Slope=0.005
Boundary for River Rch & Prof#=UNT 145 in LFCCL,Reach-1,2
Up Type=0
Dn Type=3
Dn Slope=0.005
Boundary for River Rch & Prof#=UNT 145 in LFCCL,Reach-1,3
Up Type=0
Dn Type=3
Dn Slope=0.005
Boundary for River Rch & Prof#=UNT 145 in LFCCL,Reach-1,4
Up Type=0
Dn Type=3
Dn Slope=0.005
Boundary for River Rch & Prof#=UNT 145 in LFCCL,Reach-1,5
Up Type=0
Dn Type=3
Dn Slope=0.005
Boundary for River Rch & Prof#=UNT 145 in LFCCL,Reach-1,6
Up Type=0
Dn Type=3
Dn Slope=0.005
Boundary for River Rch & Prof#=UNT 145 in LFCCL,Reach-1,7
Up Type=0
Dn Type=3
Dn Slope=0.005

--- UNT 145 in LFCCL Watershed.g01 (geometry) ---

Geom Title=Existing Conditions

River Reach=UNT 145 in LFCCL,Reach-1
Reach XY= 30
      2859204.09      7066828.45      2858971.76      7066590.79
      2858678.34      7066795.43      2858621.61      7066668.63
      2858586.57      7066760.40      2858255.40      7066775.41
      2857803.26      7066615.25      2857660.62      7066605.24
      2857542.99      7066728.70      2857511.29      7066599.40
      2857324.43      7066687.82      2857129.23      7066634.43
      2857145.08      7066533.49      2857040.81      7066476.77
      2856737.16      7066514.31      2856719.64      7066413.37
      2856656.24      7066484.28      2856597.01      7066387.51
      2856069.80      7066273.22      2855861.85      7066358.61
      2855720.01      7066222.25      2855484.24      7066194.44
      2855450.82      7066074.65      2854892.80      7066266.13
      2854872.34      7066417.53      2854707.84      7066384.13
      2854674.66      7066516.95      2854333.65      7066478.54
      2854379.26      7066753.10      2854095.59      7067020.71

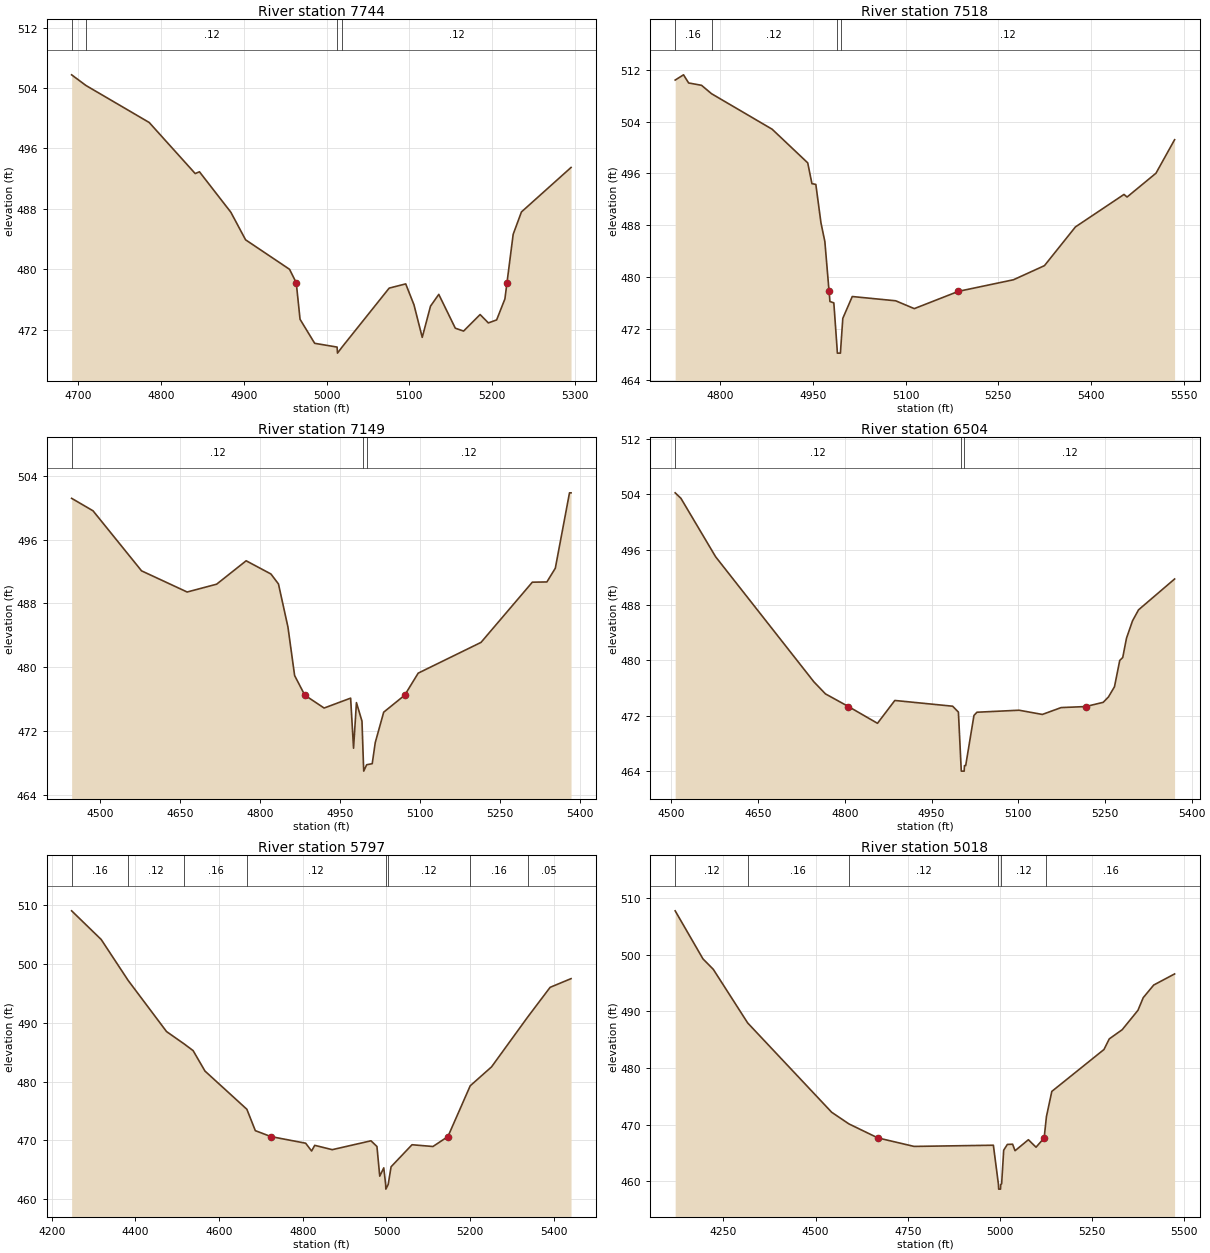
Type RM Length L Ch R = 1,7744,226,226,226
BEGIN DESCRIPTION:
UNT 145 in LFCCL Watershed 12.0
END DESCRIPTION:
XS GIS Cut Line= 3
      2859175.00      7066425.01      2859125.00      7066725.00
      2859125.00      7067024.97
#Sta/Elev= 30
  4691.7  505.75  4709.0  504.34  4785.5  499.44  4841.2  492.67  4846.3  492.91
  4884.3  487.55  4902.1  483.90  4955.3  479.99  4963.4  478.21  4968.0  473.37
  4985.7  470.19  5012.8  469.69  5013.3  468.89  5018.8  469.69  5075.8  477.50
  5095.8  478.06  5105.8  475.29  5115.8  470.98  5125.8  475.11  5135.8  476.67
  5155.8  472.19  5165.8  471.81  5185.8  474.00  5195.8  472.89  5205.8  473.29
  5215.8  476.07  5218.3  478.21  5225.8  484.63  5235.8  487.59  5295.8  493.48
#Mann=4,-1,0
  4691.7    0.16       0  4709.0    0.12       0  5012.8    0.07       0
  5018.8    0.12       0
Bank Sta=4963.4,5218.3
Exp/Cntr=0.3,0.1

Type RM Length L Ch R = 1,7518,369,369,369
BEGIN DESCRIPTION:
UNT 145 in LFCCL Watershed 11.0
END DESCRIPTION:
XS GIS Cut Line= 3
      2859124.99      7066375.01      2858959.11      7066591.08
      2858925.00      7067124.99
#Sta/Elev= 30
  4727.6  510.43  4741.1  511.24  4749.4  509.98  4770.2  509.62  4786.4  508.32
  4884.4  502.83  4941.9  497.63  4948.7  494.42  4955.0  494.30  4963.3  488.36
  4969.6  485.46  4976.4  477.77  4977.8  476.20  4984.1  475.99  4989.3  469.02
  4989.8  468.22  4994.8  468.22  4995.3  469.02  4998.6  473.59  5013.9  476.97
  5084.1  476.31  5114.2  475.10  5185.5  477.77  5274.5  479.56  5324.6  481.74
  5374.7  487.73  5453.2  492.75  5458.2  492.35  5504.9  496.03  5535.0  501.21
#Mann=4,-1,0
  4727.6    0.16       0  4786.4    0.12       0  4989.3    0.07       0
  4995.3    0.12       0
Bank Sta=4976.4,5185.5
Exp/Cntr=0.3,0.1

Type RM Length L Ch R = 1,7149,645,645,645
BEGIN DESCRIPTION:
UNT 145 in LFCCL Watershed 10.0
END DESCRIPTION:
XS GIS Cut Line= 3
      2858875.01      7066274.98      2858682.38      7066790.86
      2858875.02      7067125.04
#Sta/Elev= 30
  4446.5  501.16  4486.6  499.60  4577.6  492.08  4663.1  489.43  4718.4  490.41
  4773.7  493.34  4820.1  491.69  4834.3  490.44  4852.1  485.04  4864.6  478.97
  4883.7  476.51  4919.9  474.90  4969.6  476.14  4975.1  469.87  4980.5  475.58
  4990.9  473.26  4993.7  467.80  4994.2  467.00  4999.7  467.80  5010.1  467.93
  5015.8  470.58  5031.6  474.38  5071.0  476.51  5096.3  479.27  5214.1  483.12
  5310.3  490.66  5337.6  490.69  5353.4  492.41  5380.0  501.85  5382.9  501.85
#Mann=3,-1,0
  4446.5    0.12       0  4993.7    0.07       0  4999.7    0.12       0
Bank Sta=4883.7,5071
Exp/Cntr=0.3,0.1

Type RM Length L Ch R = 1,6504,707,707,707
BEGIN DESCRIPTION:
UNT 145 in LFCCL Watershed 9.0
END DESCRIPTION:
XS GIS Cut Line= 3
      2858275.00      7066225.03      2858275.00      7066725.00
      2858375.01      7067075.02
#Sta/Elev= 30
  4506.5  504.21  4516.5  503.41  4576.5  494.97  4746.5  476.90  4766.5  475.16
  4806.3  473.33  4856.5  470.91  4886.5  474.21  4986.5  473.38  4996.5  472.53
  5001.0  464.80  5001.5  464.00  5006.5  464.00  5007.0  464.80  5009.1  464.80
  5023.4  472.04  5028.6  472.51  5101.4  472.80  5141.7  472.19  5174.2  473.18
  5216.8  473.33  5247.0  473.94  5256.1  474.72  5266.5  476.19  5275.6  479.99
  5280.8  480.42  5287.3  483.21  5297.7  485.71  5308.1  487.30  5370.5  491.76
#Mann=3,-1,0
  4506.5    0.12       0  5001.0    0.07       0  5007.0    0.12       0
Bank Sta=4806.3,5216.8
Exp/Cntr=0.3,0.1

Type RM Length L Ch R = 1,5797,779,779,779
BEGIN DESCRIPTION:
UNT 145 in LFCCL Watershed 8.0
END DESCRIPTION:
XS GIS Cut Line= 3
      2858275.02      7066124.98      2857725.00      7066625.00
      2857725.00      7067074.97
#Sta/Elev= 30
  4247.8  509.09  4318.4  504.21  4383.0  497.22  4474.5  488.53  4516.3  486.44
  4538.1  485.28  4566.4  481.80  4666.5  475.29  4686.7  471.65  4723.9  470.64
  4807.0  469.51  4821.2  468.18  4828.6  469.15  4870.5  468.41  4963.1  469.92
  4977.3  468.95  4984.0  463.90  4993.6  465.31  4998.1  462.49  4998.6  461.69
  5004.2  462.49  5011.1  465.50  5061.1  469.25  5111.1  468.95  5146.9  470.64
  5200.2  479.29  5251.1  482.51  5337.2  490.97  5391.1  496.06  5441.1  497.54
#Mann=8,-1,0
  4247.8    0.16       0  4383.0    0.12       0  4516.3    0.16       0
  4666.5    0.12       0  4998.1    0.07       0  5004.2    0.12       0
  5200.2    0.16       0  5337.2    0.05       0
Bank Sta=4723.9,5146.9
Exp/Cntr=0.3,0.1

Type RM Length L Ch R = 1,5018,706,706,706
BEGIN DESCRIPTION:
UNT 145 in LFCCL Watershed 7.0
END DESCRIPTION:
XS GIS Cut Line= 3
      2857674.98      7065875.04      2857275.00      7066675.00
      2857575.03      7067025.03
#Sta/Elev= 30
  4118.9  507.71  4194.3  499.24  4222.3  497.40  4315.7  487.94  4543.7  472.19
  4590.7  470.13  4669.0  467.67  4767.3  466.17  4982.5  466.38  4996.3  459.44
  4996.8  458.64  5001.9  458.64  5002.4  459.44  5004.9  459.57  5010.5  465.51
  5020.4  466.52  5034.7  466.56  5041.3  465.41  5077.5  467.35  5098.3  466.03
  5120.3  467.67  5126.5  471.43  5141.1  475.87  5282.7  483.26  5297.0  485.13
  5332.1  486.75  5374.9  490.17  5389.2  492.40  5417.7  494.63  5474.3  496.58
#Mann=6,-1,0
  4118.9    0.12       0  4315.7    0.16       0  4590.7    0.12       0
  4996.3    0.07       0  5002.4    0.12       0  5126.5    0.16       0
Bank Sta=4669,5120.3
Exp/Cntr=0.3,0.1

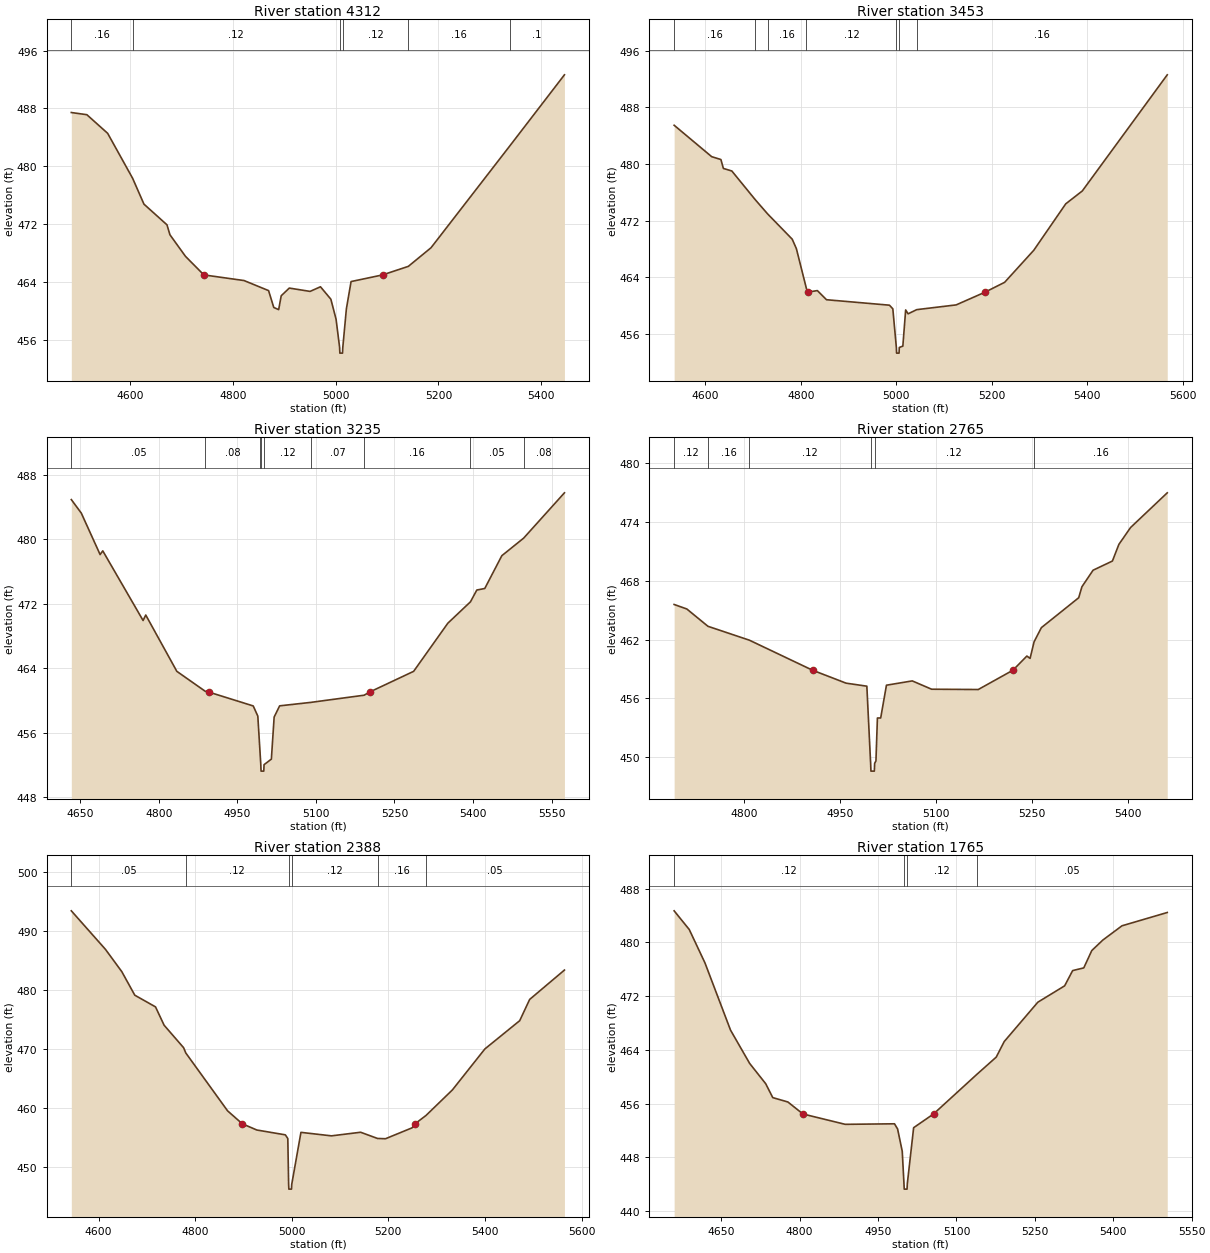
Type RM Length L Ch R = 1,4312,859,859,859
BEGIN DESCRIPTION:
UNT 145 in LFCCL Watershed 6.0
END DESCRIPTION:
XS GIS Cut Line= 3
      2856825.01      7066025.05      2856889.43      7066498.20
      2856824.99      7066975.05
#Sta/Elev= 30
  4486.2  487.44  4516.4  487.14  4556.8  484.57  4605.4  478.35  4627.4  474.78
  4672.2  471.92  4677.9  470.55  4708.2  467.56  4743.9  465.00  4822.0  464.22
  4869.7  462.83  4879.8  460.50  4889.3  460.20  4894.3  462.12  4910.0  463.18
  4950.4  462.72  4970.6  463.36  4990.8  461.64  5000.9  458.88  5007.8  454.99
  5008.3  454.19  5013.5  454.19  5014.0  454.99  5021.0  460.33  5030.1  464.08
  5091.4  465.00  5141.4  466.18  5185.5  468.75  5338.2  482.78  5444.9  492.65
#Mann=6,-1,0
  4486.2    0.16       0  4605.4    0.12       0  5007.8    0.07       0
  5014.0    0.12       0  5141.4    0.16       0  5338.2     0.1       0
Bank Sta=4743.9,5091.4
Exp/Cntr=0.3,0.1

Type RM Length L Ch R = 1,3453,218,218,218
BEGIN DESCRIPTION:
UNT 145 in LFCCL Watershed 5.0
END DESCRIPTION:
XS GIS Cut Line= 3
      2856452.07      7065890.31      2856302.08      7066340.28
      2856202.11      7066890.16
#Sta/Elev= 30
  4534.5  485.48  4613.2  481.04  4632.5  480.64  4637.7  479.38  4655.4  479.02
  4704.9  474.93  4730.5  472.95  4781.9  469.39  4790.6  468.06  4811.7  462.41
  4815.2  461.92  4834.6  462.13  4853.8  460.84  4985.6  460.07  4992.7  459.56
  5000.1  454.10  5000.6  453.30  5005.8  453.30  5006.3  454.10  5013.7  454.29
  5019.6  459.40  5024.7  458.85  5042.8  459.44  5125.4  460.11  5186.3  461.92
  5227.0  463.30  5288.0  467.82  5355.0  474.38  5389.7  476.20  5567.7  492.60
#Mann=7,-1,0
  4534.5    0.16       0  4704.9    0.08       0  4730.5    0.16       0
  4811.7    0.12       0  5000.1    0.07       0  5006.3    0.12       0
  5042.8    0.16       0
Bank Sta=4815.2,5186.3
Exp/Cntr=0.3,0.1

Type RM Length L Ch R = 1,3235,470,470,470
BEGIN DESCRIPTION:
UNT 145 in LFCCL Watershed 4.0
END DESCRIPTION:
XS GIS Cut Line= 3
      2856184.16      7065919.55      2856093.89      7066277.18
      2855925.00      7066824.99
#Sta/Elev= 30
  4632.6  484.93  4651.7  483.25  4687.6  478.11  4692.7  478.57  4769.7  469.93
  4774.8  470.61  4834.2  463.62  4888.6  461.14  4894.7  461.06  4980.1  459.33
  4988.9  458.07  4993.1  453.63  4994.6  452.04  4995.1  451.24  5000.3  451.24
  5000.8  452.04  5014.8  452.73  5020.1  457.95  5030.6  459.34  5090.3  459.77
  5192.0  460.66  5202.8  461.06  5286.6  463.62  5351.9  469.59  5395.2  472.25
  5407.3  473.71  5422.5  473.90  5455.1  477.97  5496.8  480.15  5574.7  485.77
#Mann=9,-1,0
  4632.6    0.05       0  4888.6    0.08       0  4993.1    0.12       0
  4994.6    0.07       0  5000.8    0.12       0  5090.3    0.07       0
  5192.0    0.16       0  5395.2    0.05       0  5496.8    0.08       0
Bank Sta=4894.7,5202.8
Exp/Cntr=0.3,0.1

Type RM Length L Ch R = 1,2765,377,377,377
BEGIN DESCRIPTION:
XS3875A
END DESCRIPTION:
XS GIS Cut Line= 3
      2855795.28      7065923.00      2855718.89      7066232.04
      2855663.33      7066679.97
#Sta/Elev= 30
  4691.2  465.59  4711.0  465.13  4744.0  463.36  4808.7  461.94  4907.3  458.87
  4959.6  457.55  4992.0  457.24  4997.9  449.36  4998.4  448.56  5003.7  448.56
  5004.2  449.36  5006.2  449.60  5008.5  453.99  5013.6  453.99  5022.6  457.34
  5062.9  457.78  5093.1  456.93  5165.9  456.90  5220.0  458.87  5241.8  460.32
  5246.8  460.08  5253.0  461.77  5264.4  463.22  5322.7  466.28  5327.7  467.40
  5345.1  469.09  5375.3  470.03  5385.4  471.73  5403.6  473.45  5460.9  477.00
#Mann=6,-1,0
  4691.2    0.12       0  4744.0    0.16       0  4808.7    0.12       0
  4997.9    0.07       0  5004.2    0.12       0  5253.0    0.16       0
Bank Sta=4907.3,5220
Exp/Cntr=0.3,0.1

Type RM Length L Ch R = 1,2388,623,623,623
BEGIN DESCRIPTION:
UNT 145 in LFCCL Watershed 3.0
END DESCRIPTION:
XS GIS Cut Line= 3
      2855525.00      7065624.97      2855458.58      7066076.41
      2855325.00      7066624.99
#Sta/Elev= 30
  4543.7  493.49  4614.5  486.95  4648.3  483.17  4675.1  479.19  4718.0  477.21
  4735.8  474.10  4776.2  470.29  4780.7  469.40  4867.2  459.59  4897.7  457.39
  4927.8  456.34  4986.8  455.52  4991.9  454.89  4993.6  447.12  4994.1  446.32
  4999.5  446.32  5000.0  447.12  5019.1  455.94  5082.3  455.35  5142.6  455.96
  5177.6  454.91  5194.1  454.86  5249.2  456.71  5255.2  457.39  5277.8  458.79
  5332.6  463.13  5399.9  470.08  5472.0  474.87  5492.6  478.47  5564.6  483.45
#Mann=6,-1,0
  4543.7    0.05       0  4780.7    0.12       0  4993.6    0.07       0
  5000.0    0.12       0  5177.6    0.16       0  5277.8    0.05       0
Bank Sta=4897.7,5255.2
Exp/Cntr=0.3,0.1

Type RM Length L Ch R = 1,1765,484,484,484
BEGIN DESCRIPTION:
UNT 145 in LFCCL Watershed 2.0
END DESCRIPTION:
XS GIS Cut Line= 3
      2854774.97      7065874.96      2855025.00      7066275.00
      2855274.98      7066674.96
#Sta/Elev= 30
  4559.9  484.71  4588.8  481.93  4618.9  476.95  4667.8  466.94  4704.4  461.98
  4735.1  458.96  4748.6  456.89  4777.5  456.24  4806.4  454.45  4887.2  452.91
  4981.5  452.99  4987.4  452.22  4996.3  448.90  4999.6  444.06  5000.1  443.26
  5005.5  443.26  5006.0  444.06  5018.1  452.41  5056.1  454.45  5139.3  460.37
  5176.1  462.92  5191.4  465.24  5255.7  471.10  5307.0  473.54  5322.3  475.81
  5343.6  476.21  5358.9  478.79  5380.1  480.36  5416.7  482.48  5503.3  484.46
#Mann=4,-1,0
  4559.9    0.12       0  4999.6    0.07       0  5006.0    0.12       0
  5139.3    0.05       0
Bank Sta=4806.4,5056.1
Exp/Cntr=0.3,0.1

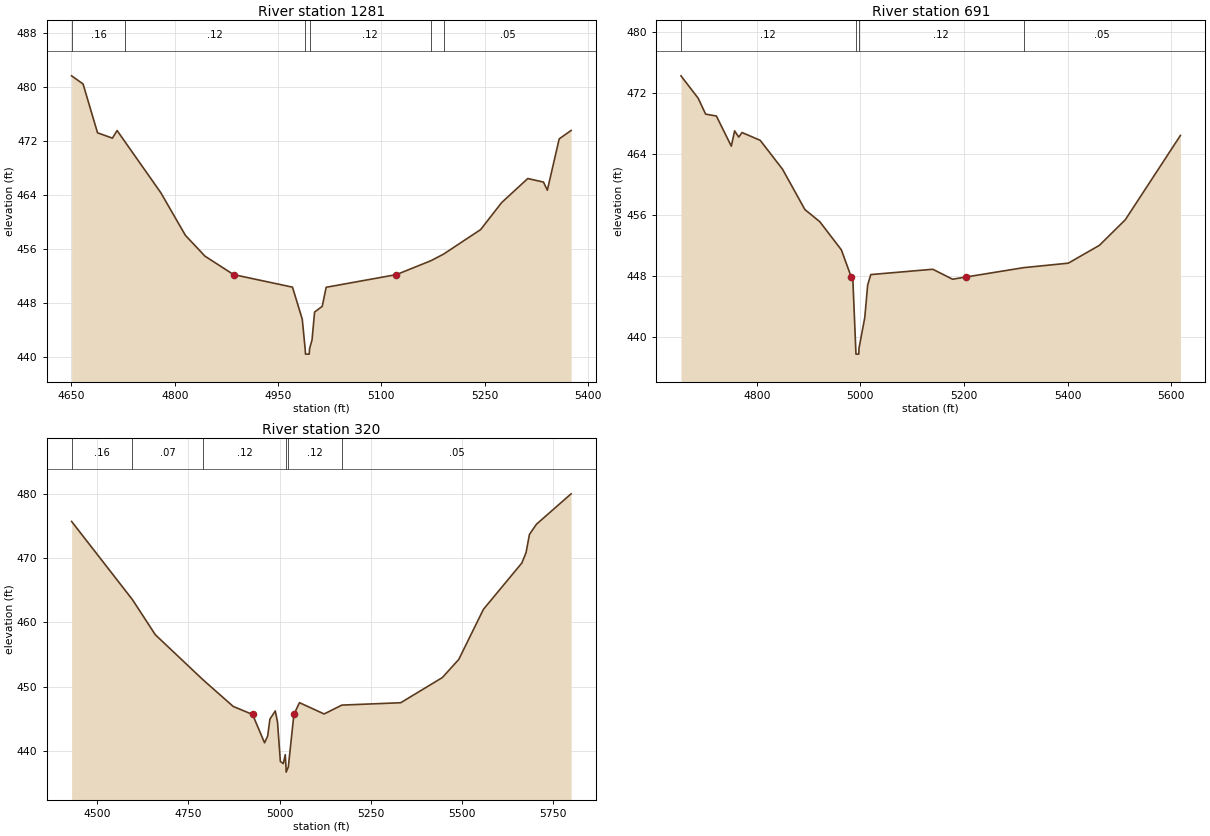
Type RM Length L Ch R = 1,1281,590,590,590
BEGIN DESCRIPTION:
XS3876A
END DESCRIPTION:
XS GIS Cut Line= 4
      2854465.42      7066131.35      2854705.00      7066391.76
      2854764.03      7066502.87      2854986.26      7066607.04
#Sta/Elev= 30
  4650.3  481.63  4666.9  480.42  4687.9  473.19  4709.5  472.40  4716.3  473.53
  4728.2  471.80  4779.8  464.31  4815.5  458.00  4843.9  454.92  4885.4  452.19
  4970.9  450.33  4985.1  445.59  4989.3  441.21  4989.8  440.41  4995.2  440.41
  4995.7  441.21  4999.3  442.52  5003.0  446.64  5014.1  447.49  5019.8  450.31
  5121.9  452.19  5172.2  454.26  5190.2  455.22  5244.0  458.85  5274.6  462.86
  5312.5  466.42  5335.3  465.89  5340.9  464.69  5358.1  472.29  5375.4  473.54
#Mann=6,-1,0
  4650.3    0.16       0  4728.2    0.12       0  4989.3    0.07       0
  4995.7    0.12       0  5172.2     0.1       0  5190.2    0.05       0
Bank Sta=4885.4,5121.9
Exp/Cntr=0.3,0.1

Type RM Length L Ch R = 1,691,371,371,371
BEGIN DESCRIPTION:
XS3877A
END DESCRIPTION:
XS GIS Cut Line= 4
      2854086.93      7066266.75      2854302.22      7066530.65
      2854482.78      7066627.87      2854901.47      7066620.95
#Sta/Elev= 30
  4653.6  474.26  4686.9  471.31  4701.2  469.23  4722.0  468.98  4750.8  465.02
  4757.2  467.03  4765.1  466.21  4771.6  466.81  4806.7  465.78  4849.8  461.98
  4892.9  456.69  4921.6  455.10  4963.3  451.40  4982.4  447.83  4985.6  447.30
  4991.0  438.50  4991.5  437.70  4996.9  437.70  4997.4  438.50  5008.5  442.50
  5014.1  446.78  5020.1  448.15  5139.9  448.85  5178.0  447.54  5203.9  447.83
  5315.2  449.06  5401.5  449.65  5461.5  451.99  5511.5  455.35  5618.0  466.43
#Mann=4,-1,0
  4653.6    0.12       0  4991.0    0.07       0  4997.4    0.12       0
  5315.2    0.05       0
Bank Sta=4982.4,5203.9
Exp/Cntr=0.3,0.1

Type RM Length L Ch R = 1,320,0,0,0
BEGIN DESCRIPTION:
UNT 145 in LFCCL Watershed 1.0
END DESCRIPTION:
XS GIS Cut Line= 3
      2853975.00      7066375.01      2854309.17      7066843.15
      2855075.03      7066624.99
#Sta/Elev= 30
  4429.2  475.75  4596.2  463.56  4659.0  458.09  4790.3  451.05  4872.9  446.91
  4926.0  445.66  4958.9  441.24  4967.5  442.30  4973.7  444.94  4988.4  446.21
  4994.5  444.49  5002.4  438.33  5010.4  438.00  5015.8  439.39  5017.8  437.47
  5018.3  436.67  5024.2  437.47  5039.5  445.66  5054.8  447.50  5122.5  445.74
  5171.3  447.12  5332.8  447.49  5447.1  451.41  5492.2  454.24  5559.9  462.05
  5665.5  469.28  5677.0  470.90  5686.3  473.73  5705.7  475.33  5800.7  480.06
#Mann=6,-1,0
  4429.2    0.16       0  4596.2    0.07       0  4790.3    0.12       0
  5017.8    0.07       0  5024.2    0.12       0  5171.3    0.05       0
Bank Sta=4926,5039.5
Exp/Cntr=0.3,0.1

Chan Stop Cuts=-1