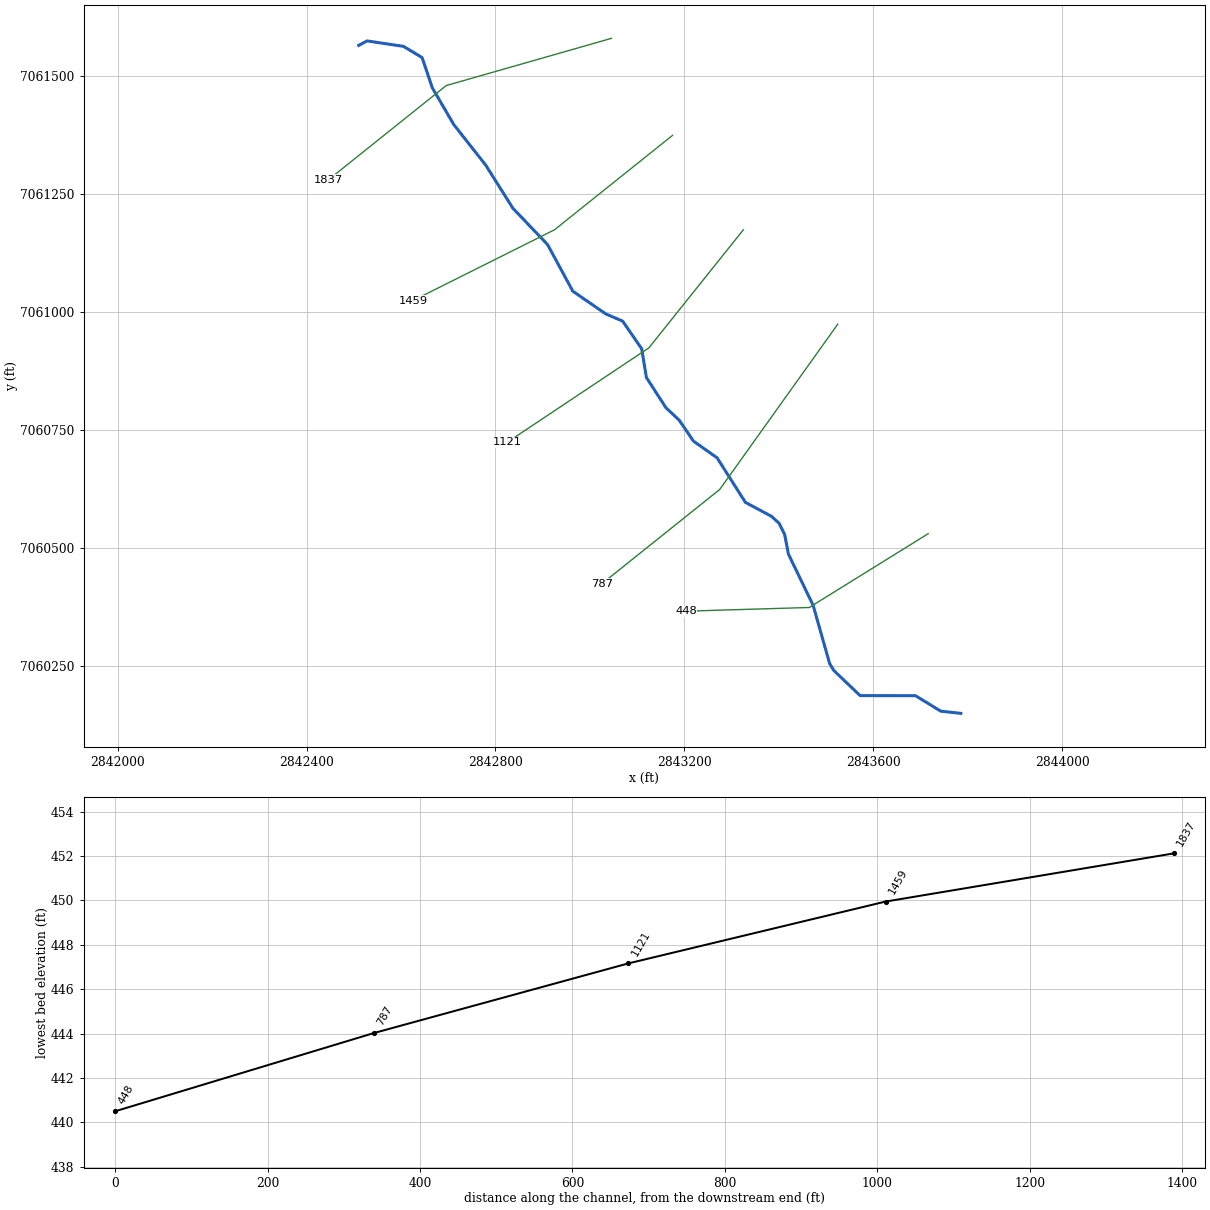
--- UNT 148 in LFCCL Watershed.prj (project) ---

Proj Title=UNT 148 in LFCCL Watershed Base Level Engineering
Current Plan=p01
Default Exp/Contr=0.3,0.1
English Units
Geom File=g01
Flow File=f01
Plan File=p01
BEGIN DESCRIPTION:
UNT 148 in LFCCL Watershed
END DESCRIPTION:

--- UNT 148 in LFCCL Watershed.p01 (plan) ---

Plan Title=Multiple Run
Short Identifier=Multiple
Geom File=g01
Flow File=f01
Subcritical Flow
K Sum by GR= 0
Std Step Tol= 0.01
Critical Tol= 0.01
Num of Std Step Trials= 20
Max Error Tol= 0.3
Flow Tol Ratio= 0.001
Split Flow NTrial= 30
Split Flow Tol= 0.02
Split Flow Ratio= 0.02
Log Output Level= 0
Friction Slope Method= 1
Unsteady Friction Slope Method= 2
Unsteady Bridges Friction Slope Method= 1
Parabolic Critical Depth
Global Vel Dist=  1 , 1 , 1
Global Log Level= 0
CheckData=True
Encroach Param= -1, 0, 0, 0
BEGIN DESCRIPTION:
Multiple Run
END DESCRIPTION:

--- UNT 148 in LFCCL Watershed.f01 (steady flow) ---

Flow Title=Multiple
Number of Profiles=7
Profile Names=10-year,25-year,50-year,1pct_min,100-year,1pct_plu,500-year
River Rch & RM= UNT 148 in LFCCL,Reach-1,1837
     562     742     886     525    1048    2090    1460
Boundary for River Rch & Prof#=UNT 148 in LFCCL,Reach-1,1
Up Type=0
Dn Type=3
Dn Slope=0.005
Boundary for River Rch & Prof#=UNT 148 in LFCCL,Reach-1,2
Up Type=0
Dn Type=3
Dn Slope=0.005
Boundary for River Rch & Prof#=UNT 148 in LFCCL,Reach-1,3
Up Type=0
Dn Type=3
Dn Slope=0.005
Boundary for River Rch & Prof#=UNT 148 in LFCCL,Reach-1,4
Up Type=0
Dn Type=3
Dn Slope=0.005
Boundary for River Rch & Prof#=UNT 148 in LFCCL,Reach-1,5
Up Type=0
Dn Type=3
Dn Slope=0.005
Boundary for River Rch & Prof#=UNT 148 in LFCCL,Reach-1,6
Up Type=0
Dn Type=3
Dn Slope=0.005
Boundary for River Rch & Prof#=UNT 148 in LFCCL,Reach-1,7
Up Type=0
Dn Type=3
Dn Slope=0.005

--- UNT 148 in LFCCL Watershed.g01 (geometry) ---

Geom Title=Existing Conditions

River Reach=UNT 148 in LFCCL,Reach-1
Reach XY= 30
      2842510.33      7061565.60      2842527.95      7061575.09
      2842605.17      7061563.56      2842644.57      7061539.79
      2842666.11      7061475.98      2842711.33      7061398.35
      2842779.35      7061311.89      2842836.84      7061220.69
      2842910.47      7061143.48      2842963.80      7061044.93
      2843033.55      7060996.86      2843069.34      7060981.53
      2843109.71      7060923.07      2843119.61      7060862.36
      2843160.86      7060798.37      2843189.16      7060771.75
      2843219.06      7060727.62      2843269.45      7060691.92
      2843329.35      7060597.69      2843384.65      7060568.07
      2843400.73      7060553.36      2843412.57      7060529.63
      2843420.49      7060488.06      2843472.85      7060379.57
      2843507.70      7060256.52      2843516.61      7060241.59
      2843572.27      7060188.37      2843689.66      7060188.18
      2843743.23      7060155.35      2843785.59      7060150.71

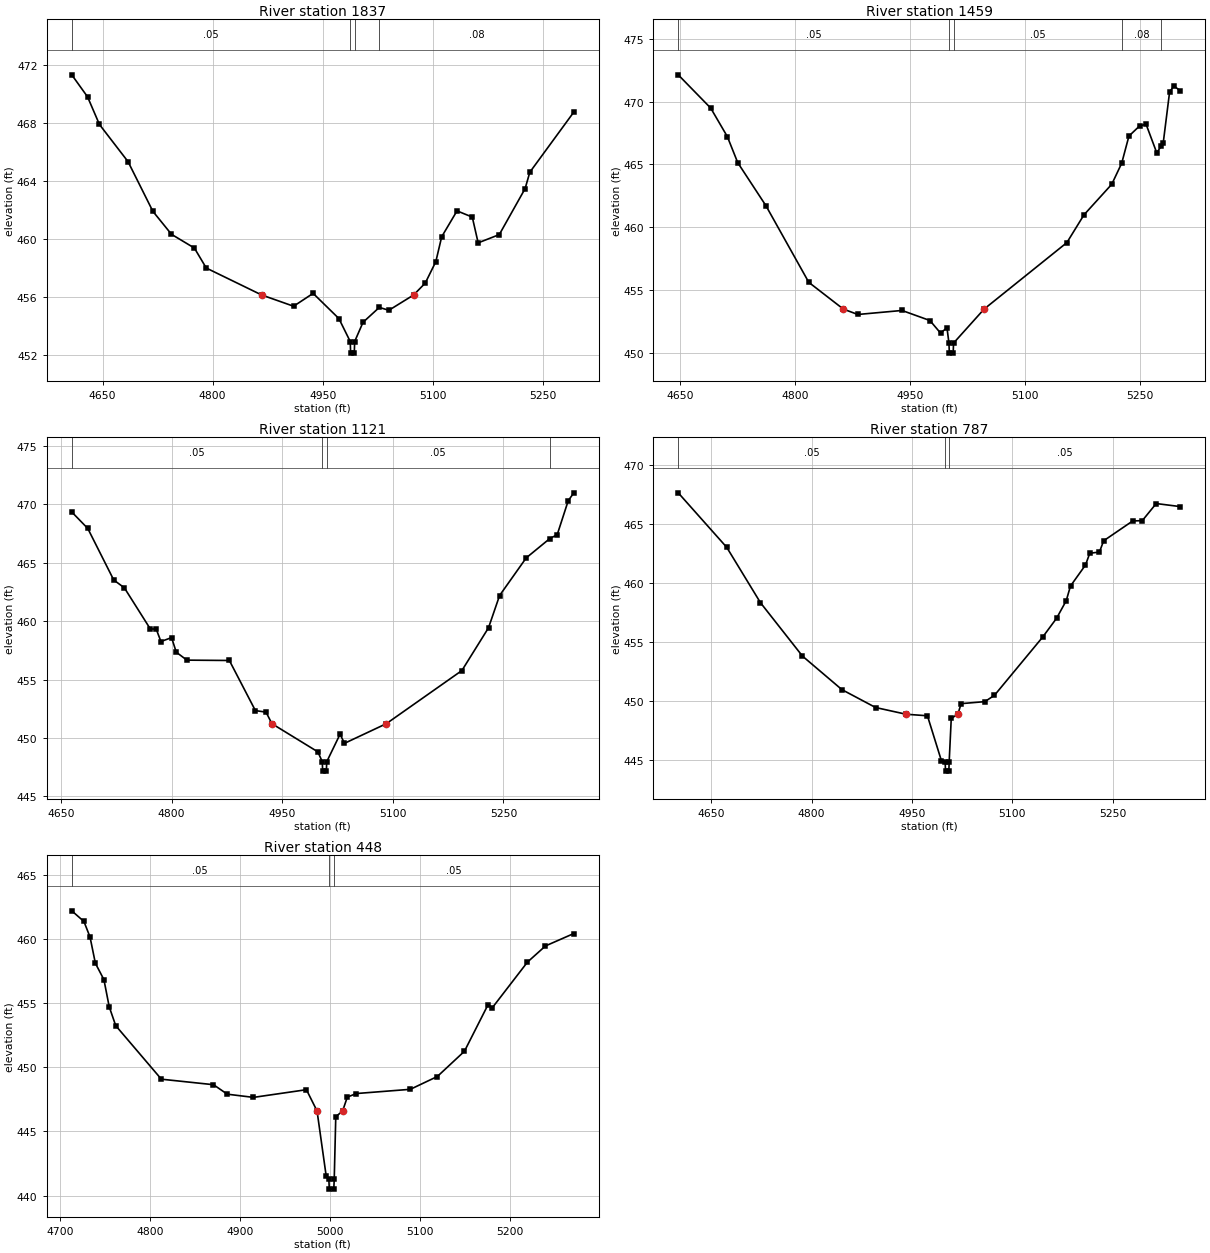
Type RM Length L Ch R = 1,1837,378,378,378
BEGIN DESCRIPTION:
UNT 148 in LFCCL Watershed 5.0
END DESCRIPTION:
XS GIS Cut Line= 3
      2843045.66      7061580.55      2842695.64      7061480.54
      2842445.63      7061280.53
#Sta/Elev= 30
  4608.0  471.35  4629.5  469.83  4645.7  467.92  4684.7  465.35  4718.5  461.92
  4743.9  460.33  4775.1  459.38  4791.3  458.00  4866.7  456.14  4910.3  455.36
  4936.9  456.25  4972.0  454.51  4987.5  452.92  4988.0  452.12  4993.0  452.12
  4993.5  452.92  5004.9  454.25  5027.1  455.28  5040.1  455.08  5073.9  456.14
  5089.7  456.96  5104.1  458.44  5112.1  460.16  5133.0  461.95  5153.8  461.52
  5161.8  459.74  5190.6  460.31  5225.8  463.49  5232.2  464.62  5292.2  468.78
#Mann=4,-1,0
  4608.0    0.05       0  4987.5    0.03       0  4993.5    0.05       0
  5027.1    0.08       0
Bank Sta=4866.7,5073.9
Exp/Cntr=0.3,0.1

Type RM Length L Ch R = 1,1459,338,338,338
BEGIN DESCRIPTION:
UNT 148 in LFCCL Watershed 4.0
END DESCRIPTION:
XS GIS Cut Line= 3
      2843175.02      7061375.01      2842925.00      7061175.00
      2842624.99      7061025.00
#Sta/Elev= 30
  4647.2  472.13  4689.6  469.48  4711.3  467.21  4724.9  465.13  4761.7  461.70
  4817.7  455.59  4862.8  453.46  4881.7  453.03  4939.4  453.35  4975.8  452.55
  4989.7  451.55  4998.1  451.97  5000.7  450.75  5001.2  449.95  5006.2  449.95
  5006.7  450.75  5046.6  453.46  5154.7  458.76  5177.0  460.97  5213.3  463.41
  5226.3  465.09  5235.7  467.25  5249.7  468.06  5258.1  468.19  5272.0  465.92
  5278.2  466.47  5280.4  466.66  5288.8  470.76  5294.4  471.24  5302.8  470.86
#Mann=5,-1,0
  4647.2    0.05       0  5000.7    0.03       0  5006.7    0.05       0
  5226.3    0.08       0  5278.2    0.16       0
Bank Sta=4862.8,5046.6
Exp/Cntr=0.3,0.1

Type RM Length L Ch R = 1,1121,334,334,334
BEGIN DESCRIPTION:
UNT 148 in LFCCL Watershed 3.0
END DESCRIPTION:
XS GIS Cut Line= 3
      2843325.03      7061175.03      2843125.00      7060925.00
      2842824.96      7060724.97
#Sta/Elev= 30
  4664.7  469.34  4686.4  467.93  4721.6  463.52  4736.0  462.85  4771.2  459.33
  4779.2  459.32  4785.6  458.25  4800.0  458.59  4806.4  457.34  4820.8  456.66
  4878.4  456.63  4913.7  452.34  4928.1  452.21  4936.1  451.22  4998.4  448.81
  5004.4  447.96  5004.9  447.16  5009.9  447.16  5010.4  447.96  5028.5  450.32
  5034.5  449.54  5091.2  451.22  5193.7  455.77  5229.8  459.43  5244.8  462.19
  5280.9  465.41  5313.0  467.07  5322.9  467.39  5337.9  470.31  5345.5  470.98
#Mann=4,-1,0
  4664.7    0.05       0  5004.4    0.03       0  5010.4    0.05       0
  5313.0    0.08       0
Bank Sta=4936.1,5091.2
Exp/Cntr=0.3,0.1

Type RM Length L Ch R = 1,787,339,339,339
BEGIN DESCRIPTION:
UNT 148 in LFCCL Watershed 2.0
END DESCRIPTION:
XS GIS Cut Line= 3
      2843525.01      7060975.02      2843275.00      7060625.00
      2843025.00      7060425.00
#Sta/Elev= 30
  4600.8  467.65  4673.3  463.02  4723.7  458.32  4786.4  453.79  4845.4  450.94
  4895.8  449.42  4941.3  448.85  4973.2  448.72  4994.1  444.90  4999.7  444.82
  5000.2  444.02  5005.2  444.02  5005.7  444.82  5008.8  448.50  5018.6  448.85
  5023.6  449.75  5059.0  449.92  5073.4  450.46  5145.4  455.40  5166.2  457.00
  5180.6  458.49  5187.0  459.74  5209.4  461.52  5215.8  462.52  5230.2  462.62
  5236.6  463.58  5279.9  465.26  5294.3  465.29  5315.1  466.74  5351.1  466.48
#Mann=3,-1,0
  4600.8    0.05       0  4999.7    0.03       0  5005.7    0.05       0
Bank Sta=4941.3,5018.6
Exp/Cntr=0.3,0.1

Type RM Length L Ch R = 1,448,0,0,0
BEGIN DESCRIPTION:
UNT 148 in LFCCL Watershed 1.0
END DESCRIPTION:
XS GIS Cut Line= 3
      2843716.48      7060531.23      2843464.58      7060375.00
      2843203.51      7060367.18
#Sta/Elev= 30
  4713.1  462.22  4726.6  461.39  4733.4  460.17  4739.3  458.13  4748.8  456.85
  4754.7  454.73  4761.9  453.26  4812.6  449.08  4870.5  448.65  4885.8  447.91
  4914.9  447.66  4973.7  448.26  4985.5  446.60  4995.7  441.50  4998.6  441.30
  4999.1  440.50  5004.1  440.50  5004.6  441.30  5006.3  446.15  5013.9  446.60
  5019.1  447.68  5029.1  447.96  5089.1  448.29  5119.1  449.29  5149.2  451.26
  5175.3  454.88  5180.3  454.67  5219.2  458.22  5239.2  459.48  5270.7  460.45
#Mann=3,-1,0
  4713.1    0.05       0  4998.6    0.03       0  5004.6    0.05       0
Bank Sta=4985.5,5013.9
Exp/Cntr=0.3,0.1

Chan Stop Cuts=-1