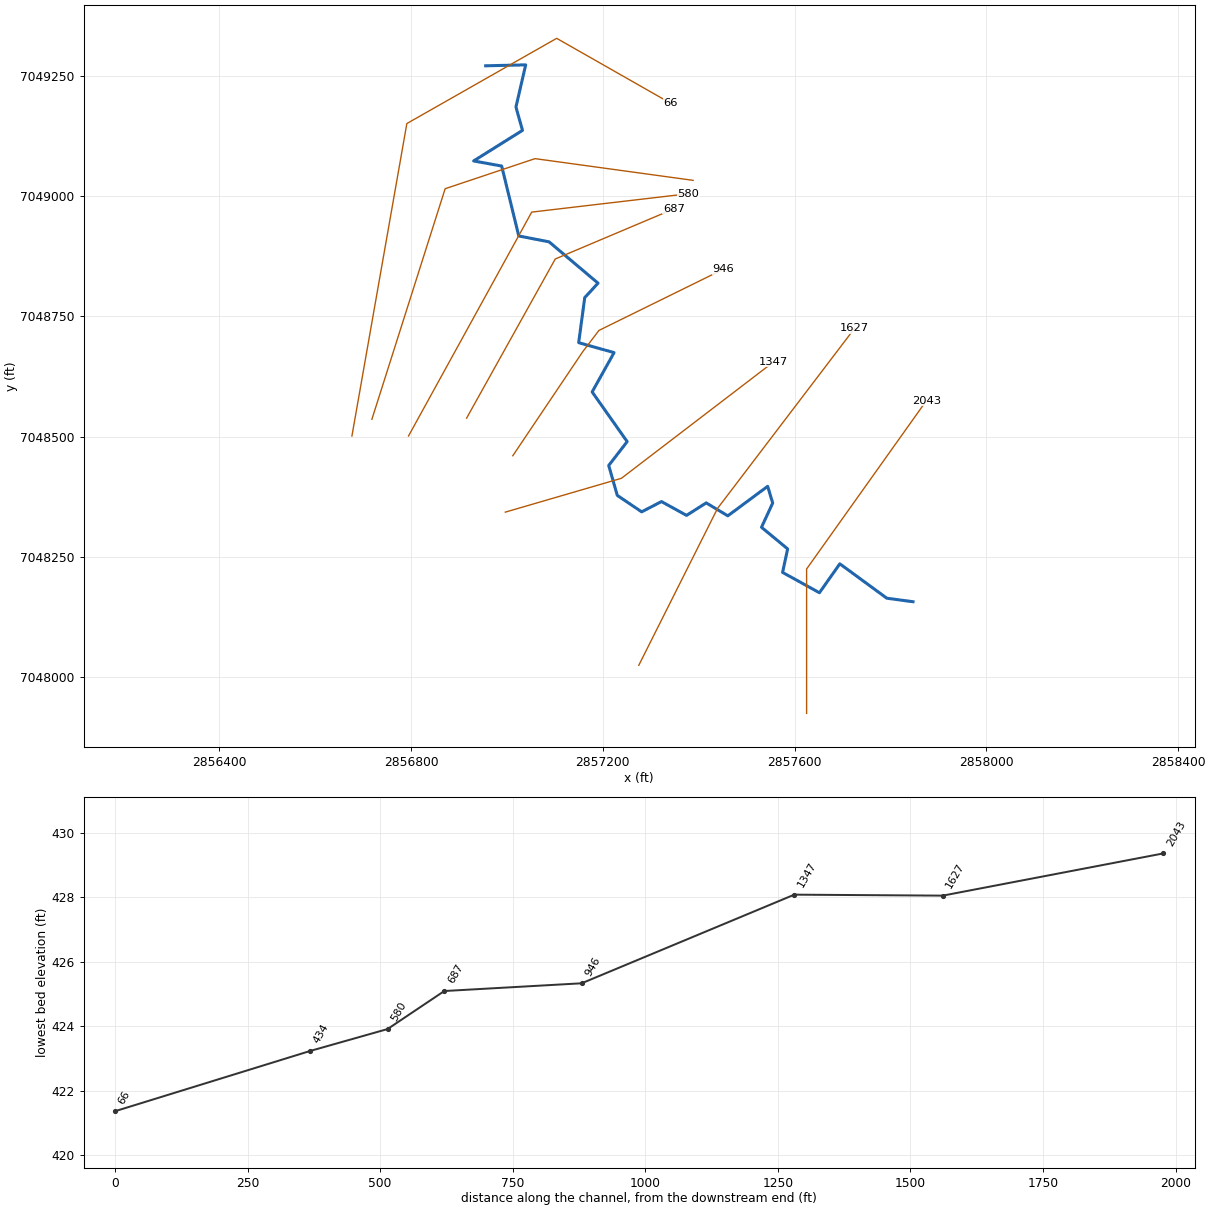
--- UNT 150 in LFCCL Watershed.prj (project) ---

Proj Title=UNT 150 in LFCCL Watershed Base Level Engineering
Current Plan=p01
Default Exp/Contr=0.3,0.1
English Units
Geom File=g01
Flow File=f01
Plan File=p01
BEGIN DESCRIPTION:
UNT 150 in LFCCL Watershed
END DESCRIPTION:

--- UNT 150 in LFCCL Watershed.p01 (plan) ---

Plan Title=Multiple Run
Short Identifier=Multiple
Geom File=g01
Flow File=f01
Subcritical Flow
K Sum by GR= 0
Std Step Tol= 0.01
Critical Tol= 0.01
Num of Std Step Trials= 20
Max Error Tol= 0.3
Flow Tol Ratio= 0.001
Split Flow NTrial= 30
Split Flow Tol= 0.02
Split Flow Ratio= 0.02
Log Output Level= 0
Friction Slope Method= 1
Unsteady Friction Slope Method= 2
Unsteady Bridges Friction Slope Method= 1
Parabolic Critical Depth
Global Vel Dist=  1 , 1 , 1
Global Log Level= 0
CheckData=True
Encroach Param= -1, 0, 0, 0
BEGIN DESCRIPTION:
Multiple Run
END DESCRIPTION:

--- UNT 150 in LFCCL Watershed.f01 (steady flow) ---

Flow Title=Multiple
Number of Profiles=7
Profile Names=10-year,25-year,50-year,1pct_min,100-year,1pct_plu,500-year
River Rch & RM= UNT 150 in LFCCL,Reach-1,2043
     422     554     659     390     779    1553    1088
Boundary for River Rch & Prof#=UNT 150 in LFCCL,Reach-1,1
Up Type=0
Dn Type=3
Dn Slope=0.005
Boundary for River Rch & Prof#=UNT 150 in LFCCL,Reach-1,2
Up Type=0
Dn Type=3
Dn Slope=0.005
Boundary for River Rch & Prof#=UNT 150 in LFCCL,Reach-1,3
Up Type=0
Dn Type=3
Dn Slope=0.005
Boundary for River Rch & Prof#=UNT 150 in LFCCL,Reach-1,4
Up Type=0
Dn Type=3
Dn Slope=0.005
Boundary for River Rch & Prof#=UNT 150 in LFCCL,Reach-1,5
Up Type=0
Dn Type=3
Dn Slope=0.005
Boundary for River Rch & Prof#=UNT 150 in LFCCL,Reach-1,6
Up Type=0
Dn Type=3
Dn Slope=0.005
Boundary for River Rch & Prof#=UNT 150 in LFCCL,Reach-1,7
Up Type=0
Dn Type=3
Dn Slope=0.005

--- UNT 150 in LFCCL Watershed.g01 (geometry) ---

Geom Title=Existing Conditions

River Reach=UNT 150 in LFCCL,Reach-1
Reach XY= 30
      2857846.87      7048156.99      2857792.30      7048164.29
      2857694.30      7048235.77      2857651.73      7048175.68
      2857574.87      7048217.93      2857585.44      7048266.80
      2857530.92      7048311.70      2857554.28      7048362.10
      2857543.80      7048396.83      2857460.69      7048335.50
      2857415.61      7048362.36      2857374.56      7048336.41
      2857322.31      7048365.10      2857280.98      7048343.78
      2857230.20      7048377.88      2857212.28      7048440.15
      2857250.72      7048489.69      2857177.69      7048592.94
      2857223.42      7048674.65      2857149.58      7048695.29
      2857162.21      7048788.90      2857189.98      7048818.98
      2857087.85      7048904.87      2857024.65      7048917.05
      2856988.98      7049062.39      2856930.50      7049072.96
      2857032.40      7049136.51      2857018.75      7049185.09
      2857039.08      7049272.62      2856955.59      7049270.71

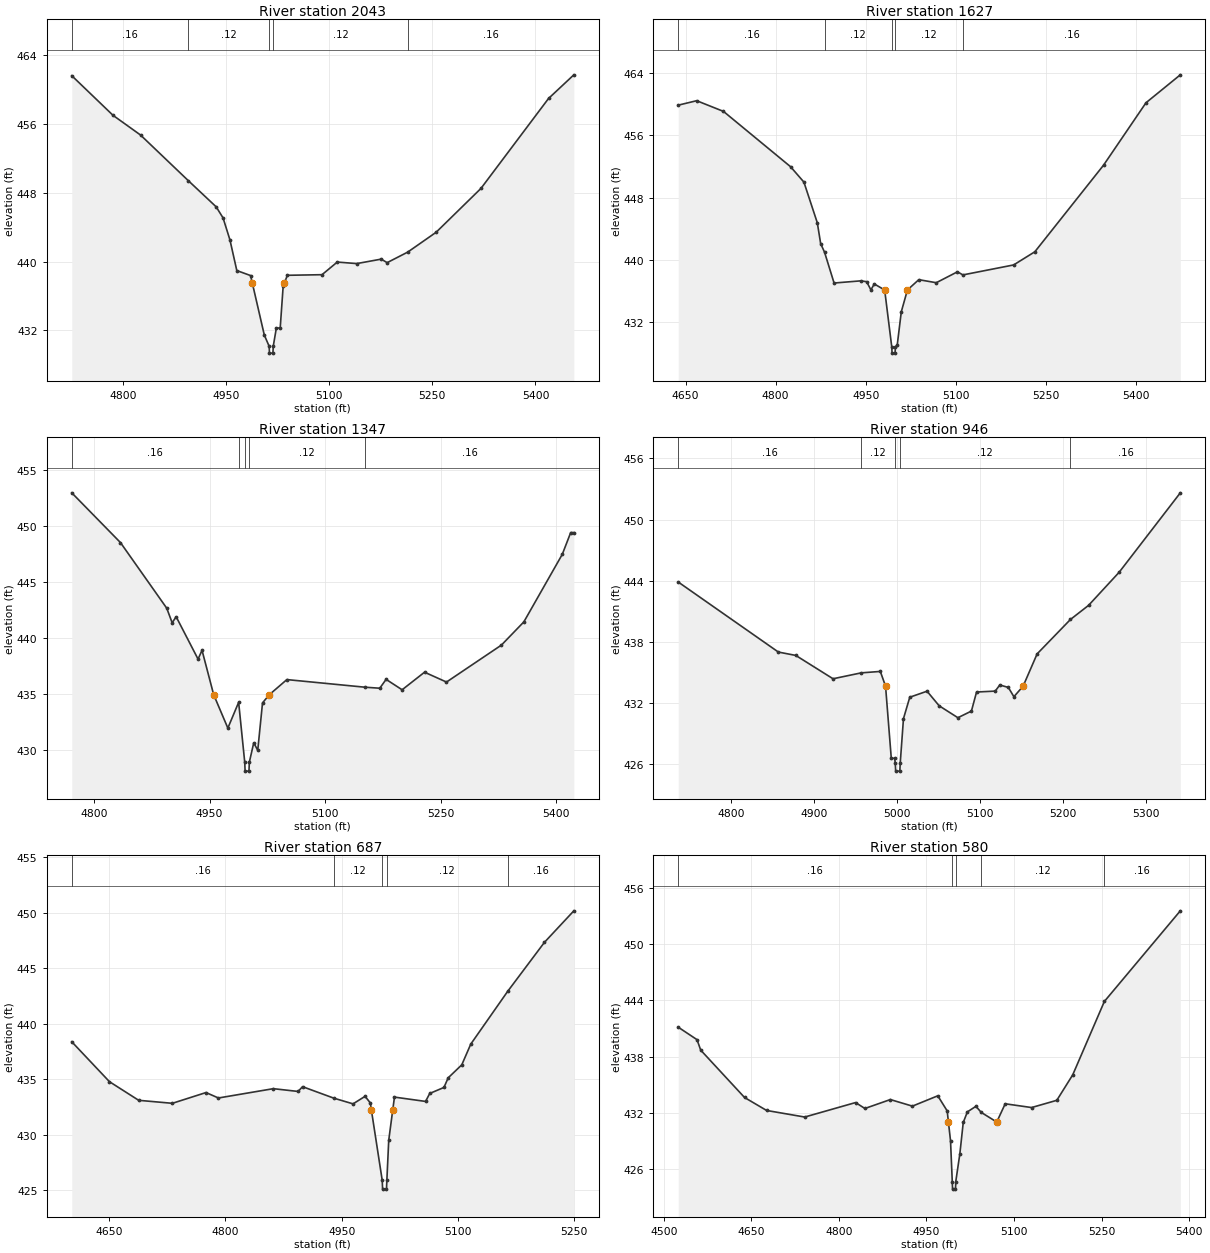
Type RM Length L Ch R = 1,2043,416,416,416
BEGIN DESCRIPTION:
UNT 150 in LFCCL Watershed 3.0
END DESCRIPTION:
XS GIS Cut Line= 3
      2857625.00      7047924.97      2857625.00      7048225.00
      2857874.97      7048574.96
#Sta/Elev= 30
  4725.7  461.62  4785.7  457.01  4825.7  454.72  4895.1  449.42  4935.7  446.37
  4945.7  445.08  4955.7  442.53  4965.7  438.96  4985.7  438.38  4988.3  437.49
  5005.7  431.46  5012.7  430.16  5013.2  429.36  5018.2  429.36  5018.7  430.16
  5023.2  432.28  5028.8  432.28  5033.1  437.14  5034.8  437.49  5039.2  438.41
  5089.6  438.48  5111.8  439.95  5140.0  439.77  5175.7  440.29  5184.3  439.88
  5214.3  441.11  5255.5  443.41  5320.7  448.51  5419.0  458.97  5455.8  461.72
#Mann=5,-1,0
  4725.7    0.16       0  4895.1    0.12       0  5012.7    0.07       0
  5018.7    0.12       0  5214.3    0.16       0
Bank Sta=4988.3,5034.8
Exp/Cntr=0.3,0.1

Type RM Length L Ch R = 1,1627,280,280,280
BEGIN DESCRIPTION:
UNT 150 in LFCCL Watershed 2.0
END DESCRIPTION:
XS GIS Cut Line= 3
      2857274.99      7048024.97      2857439.27      7048350.99
      2857724.98      7048724.97
#Sta/Elev= 30
  4637.8  459.85  4668.5  460.42  4713.1  459.05  4824.7  451.96  4847.0  449.98
  4869.3  444.76  4874.9  442.08  4881.3  441.00  4897.2  437.04  4941.8  437.32
  4951.4  437.21  4958.5  436.16  4964.1  436.92  4981.4  436.15  4993.2  428.85
  4993.7  428.05  4998.7  428.05  4999.2  428.85  5002.3  429.07  5009.1  433.36
  5019.3  436.15  5038.2  437.47  5067.3  437.08  5102.6  438.48  5111.6  438.08
  5196.1  439.36  5231.4  441.05  5345.7  452.15  5416.4  460.16  5473.5  463.74
#Mann=5,-1,0
  4637.8    0.16       0  4881.3    0.12       0  4993.2    0.07       0
  4999.2    0.12       0  5111.6    0.16       0
Bank Sta=4981.4,5019.3
Exp/Cntr=0.3,0.1

Type RM Length L Ch R = 1,1347,401,401,401
BEGIN DESCRIPTION:
XS3880A
END DESCRIPTION:
XS GIS Cut Line= 3
      2856996.55      7048343.17      2857238.75      7048413.49
      2857556.47      7048655.68
#Sta/Elev= 30
  4771.1  452.92  4834.3  448.48  4894.4  442.62  4901.4  441.32  4906.6  441.86
  4935.0  438.08  4940.2  438.86  4955.3  434.90  4973.7  431.92  4987.7  434.22
  4995.6  428.88  4996.1  428.08  5001.1  428.08  5001.6  428.88  5007.3  430.61
  5012.5  429.94  5018.7  434.17  5027.5  434.90  5050.3  436.25  5151.7  435.57
  5170.9  435.48  5179.1  436.27  5199.9  435.34  5229.0  436.91  5257.5  436.03
  5328.8  439.33  5357.9  441.40  5407.8  447.43  5418.7  449.37  5422.8  449.37
#Mann=5,-1,0
  4771.1    0.16       0  4987.7    0.12       0  4995.6    0.07       0
  5001.6    0.12       0  5151.7    0.16       0
Bank Sta=4955.3,5027.5
Exp/Cntr=0.3,0.1

Type RM Length L Ch R = 1,946,259,259,259
BEGIN DESCRIPTION:
XS3879A
END DESCRIPTION:
XS GIS Cut Line= 4
      2857012.18      7048460.35      2857158.02      7048676.51
      2857191.87      7048720.78      2857451.13      7048847.81
#Sta/Elev= 30
  4736.0  443.88  4856.7  437.01  4877.7  436.68  4922.6  434.39  4956.6  434.97
  4979.6  435.11  4985.9  433.66  4992.8  426.59  4996.8  426.59  4997.6  426.13
  4998.1  425.33  5003.1  425.33  5003.6  426.13  5007.5  430.48  5015.1  432.58
  5035.9  433.17  5050.5  431.74  5073.1  430.57  5089.4  431.22  5095.6  433.09
  5118.1  433.18  5123.6  433.78  5133.9  433.54  5140.6  432.63  5151.7  433.66
  5168.6  436.83  5208.8  440.21  5230.6  441.59  5267.6  444.85  5341.2  452.63
#Mann=5,-1,0
  4736.0    0.16       0  4956.6    0.12       0  4997.6    0.07       0
  5003.6    0.12       0  5208.8    0.16       0
Bank Sta=4985.9,5151.7
Exp/Cntr=0.3,0.1

Type RM Length L Ch R = 1,687,107,107,107
BEGIN DESCRIPTION:
XS3878A
END DESCRIPTION:
XS GIS Cut Line= 3
      2856915.81      7048538.45      2857100.73      7048869.22
      2857348.14      7048973.39
#Sta/Elev= 30
  4602.0  438.38  4650.6  434.78  4688.3  433.10  4731.7  432.83  4775.1  433.80
  4791.1  433.31  4861.9  434.15  4893.8  433.90  4899.6  434.33  4940.1  433.29
  4964.7  432.78  4980.2  433.46  4987.0  432.86  4988.3  432.24  5002.3  425.89
  5002.8  425.09  5007.8  425.09  5008.3  425.89  5010.7  429.49  5015.9  432.24
  5018.1  433.39  5058.2  433.00  5063.6  433.72  5081.9  434.26  5087.4  435.13
  5104.9  436.30  5116.5  438.17  5164.0  442.92  5211.5  447.35  5249.4  450.19
#Mann=5,-1,0
  4602.0    0.16       0  4940.1    0.12       0  5002.3    0.07       0
  5008.3    0.12       0  5164.0    0.16       0
Bank Sta=4988.3,5015.9
Exp/Cntr=0.3,0.1

Type RM Length L Ch R = 1,580,146,146,146
BEGIN DESCRIPTION:
Mapping XS b3a6aa5f
END DESCRIPTION:
XS GIS Cut Line= 3
      2856794.65      7048501.34      2857051.62      7048966.66
      2857378.03      7049004.85
#Sta/Elev= 30
  4524.8  441.14  4557.0  439.81  4563.3  438.70  4638.4  433.66  4676.2  432.28
  4741.5  431.58  4828.6  433.12  4844.6  432.49  4888.2  433.44  4926.0  432.74
  4969.5  433.84  4985.6  432.23  4987.7  431.05  4991.3  429.06  4994.3  424.71
  4994.8  423.91  4999.8  423.91  5000.3  424.71  5007.3  427.67  5013.1  431.00
  5020.2  432.13  5034.8  432.72  5044.0  432.07  5070.5  431.05  5085.0  432.99
  5130.2  432.59  5173.4  433.36  5200.7  436.07  5254.9  443.88  5385.0  453.52
#Mann=5,-1,0
  4524.8    0.16       0  4994.3    0.07       0  5000.3    0.16       0
  5044.0    0.12       0  5254.9    0.16       0
Bank Sta=4987.7,5070.5
Exp/Cntr=0.3,0.1

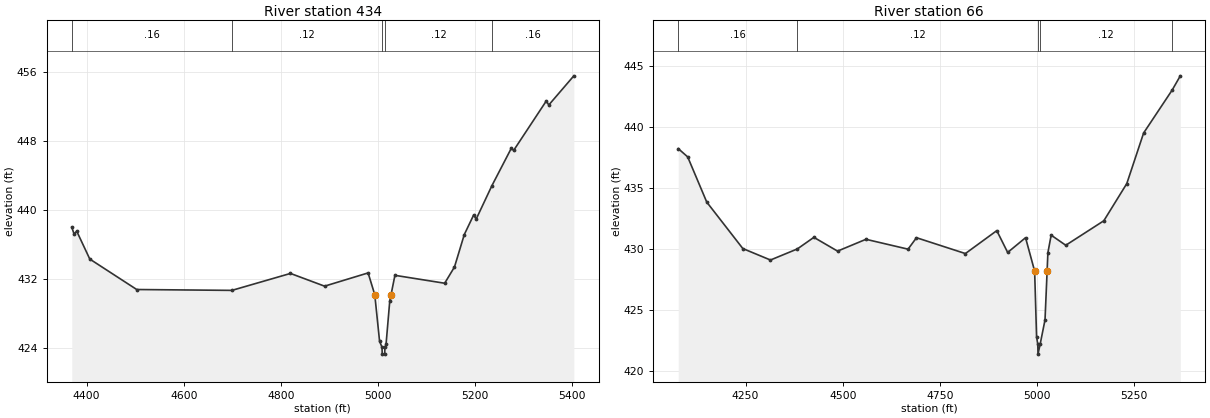
Type RM Length L Ch R = 1,434,368,368,368
BEGIN DESCRIPTION:
Mapping XS b3701d47
END DESCRIPTION:
XS GIS Cut Line= 4
      2856718.29      7048536.11      2856871.06      7049015.27
      2857058.56      7049077.77      2857388.42      7049032.63
#Sta/Elev= 30
  4369.6  437.97  4374.5  437.18  4379.7  437.53  4406.7  434.28  4503.3  430.74
  4699.2  430.64  4819.8  432.61  4890.0  431.13  4979.6  432.67  4993.3  430.14
  5003.2  424.73  5008.2  424.03  5008.7  423.23  5013.7  423.23  5014.2  424.03
  5016.5  424.35  5024.2  429.43  5026.8  430.14  5034.8  432.39  5137.2  431.47
  5157.4  433.36  5177.6  437.13  5197.0  439.42  5202.0  438.92  5234.6  442.83
  5274.2  447.14  5279.3  446.92  5346.4  452.66  5351.5  452.19  5403.1  455.58
#Mann=5,-1,0
  4369.6    0.16       0  4699.2    0.12       0  5008.2    0.07       0
  5014.2    0.12       0  5234.6    0.16       0
Bank Sta=4993.3,5026.8
Exp/Cntr=0.3,0.1

Type RM Length L Ch R = 1,66,0,0,0
BEGIN DESCRIPTION:
UNT 150 in LFCCL Watershed 1.0
END DESCRIPTION:
XS GIS Cut Line= 4
      2856676.61      7048501.34      2856791.20      7049150.68
      2857103.70      7049327.77      2857341.36      7049192.95
#Sta/Elev= 30
  4076.7  438.22  4101.0  437.54  4150.1  433.83  4242.9  430.02  4314.0  429.08
  4383.2  429.99  4425.7  430.94  4486.6  429.81  4559.7  430.78  4668.0  429.97
  4689.7  430.91  4815.5  429.61  4896.3  431.49  4924.3  429.70  4970.3  430.91
  4993.7  428.17  4998.7  422.77  5001.8  422.16  5002.3  421.36  5007.8  422.16
  5020.4  424.17  5025.8  428.17  5027.8  429.68  5036.2  431.12  5073.8  430.29
  5171.7  432.30  5230.8  435.35  5274.1  439.50  5347.7  443.03  5368.5  444.19
#Mann=5,-1,0
  4076.7    0.16       0  4383.2    0.12       0  5001.8    0.07       0
  5007.8    0.12       0  5347.7    0.16       0
Bank Sta=4993.7,5025.8
Exp/Cntr=0.3,0.1

Chan Stop Cuts=-1