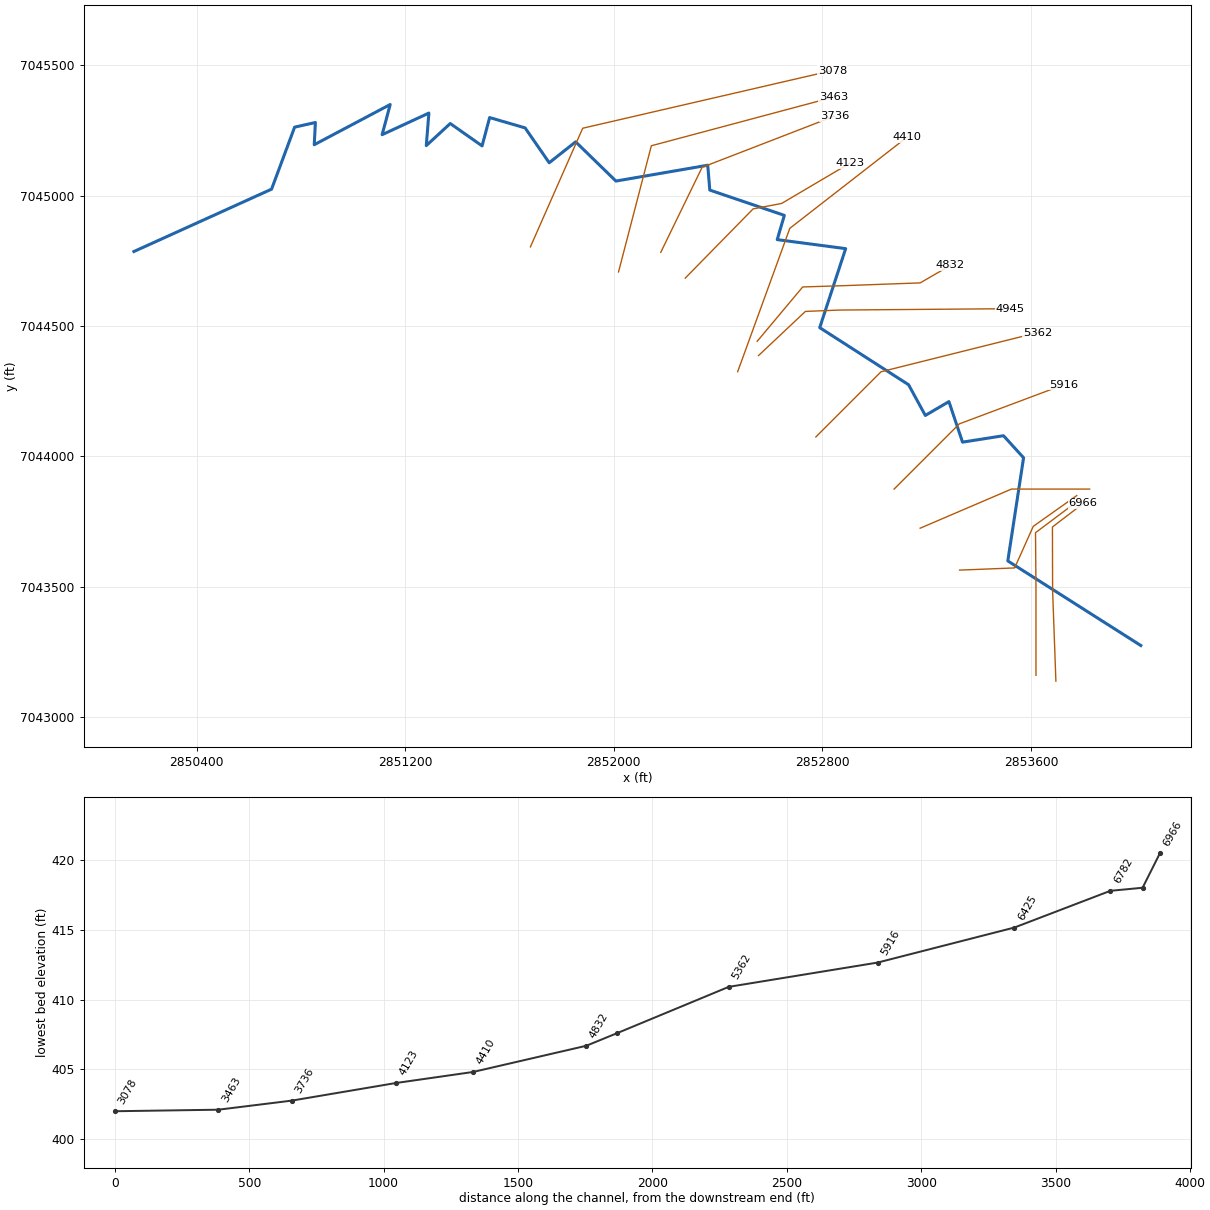
--- UNT 151 in LFCCL Watershed.prj (project) ---

Proj Title=UNT 151 in LFCCL Watershed Base Level Engineering
Current Plan=p01
Default Exp/Contr=0.3,0.1
English Units
Geom File=g01
Flow File=f01
Plan File=p01
BEGIN DESCRIPTION:
UNT 151 in LFCCL Watershed
END DESCRIPTION:

--- UNT 151 in LFCCL Watershed.p01 (plan) ---

Plan Title=Multiple Run
Short Identifier=Multiple
Geom File=g01
Flow File=f01
Subcritical Flow
K Sum by GR= 0
Std Step Tol= 0.01
Critical Tol= 0.01
Num of Std Step Trials= 20
Max Error Tol= 0.3
Flow Tol Ratio= 0.001
Split Flow NTrial= 30
Split Flow Tol= 0.02
Split Flow Ratio= 0.02
Log Output Level= 0
Friction Slope Method= 1
Unsteady Friction Slope Method= 2
Unsteady Bridges Friction Slope Method= 1
Parabolic Critical Depth
Global Vel Dist=  1 , 1 , 1
Global Log Level= 0
CheckData=True
Encroach Param= -1, 0, 0, 0
BEGIN DESCRIPTION:
Multiple Run
END DESCRIPTION:

--- UNT 151 in LFCCL Watershed.f01 (steady flow) ---

Flow Title=Multiple
Number of Profiles=7
Profile Names=10-year,25-year,50-year,1pct_min,100-year,1pct_plu,500-year
River Rch & RM= UNT 151 in LFCCL,Reach-1,6966
     599     805     974     586    1169    2332    1686
River Rch & RM= UNT 151 in LFCCL,Reach-1,4832
     736     998    1214     734    1464    2921    2133
Boundary for River Rch & Prof#=UNT 151 in LFCCL,Reach-1,1
Up Type=0
Dn Type=3
Dn Slope=0.005
Boundary for River Rch & Prof#=UNT 151 in LFCCL,Reach-1,2
Up Type=0
Dn Type=3
Dn Slope=0.005
Boundary for River Rch & Prof#=UNT 151 in LFCCL,Reach-1,3
Up Type=0
Dn Type=3
Dn Slope=0.005
Boundary for River Rch & Prof#=UNT 151 in LFCCL,Reach-1,4
Up Type=0
Dn Type=3
Dn Slope=0.005
Boundary for River Rch & Prof#=UNT 151 in LFCCL,Reach-1,5
Up Type=0
Dn Type=3
Dn Slope=0.005
Boundary for River Rch & Prof#=UNT 151 in LFCCL,Reach-1,6
Up Type=0
Dn Type=3
Dn Slope=0.005
Boundary for River Rch & Prof#=UNT 151 in LFCCL,Reach-1,7
Up Type=0
Dn Type=3
Dn Slope=0.005

--- UNT 151 in LFCCL Watershed.g01 (geometry) ---

Geom Title=Existing Conditions

River Reach=UNT 151 in LFCCL,Reach-1
Reach XY= 30
      2854021.12      7043275.00      2853511.05      7043599.48
      2853571.51      7043995.18      2853494.49      7044079.66
      2853337.42      7044055.02      2853285.19      7044210.45
      2853194.74      7044157.36      2853130.53      7044275.14
      2852789.68      7044494.12      2852889.19      7044797.16
      2852626.71      7044831.71      2852654.02      7044924.78
      2852368.13      7045021.74      2852360.33      7045117.04
      2852008.13      7045056.29      2851853.76      7045206.76
      2851752.33      7045126.51      2851659.82      7045260.26
      2851523.84      7045299.83      2851494.86      7045191.16
      2851372.82      7045276.98      2851280.87      7045192.27
      2851290.90      7045317.10      2851111.45      7045234.07
      2851142.66      7045349.98      2850851.20      7045195.62
      2850855.66      7045280.88      2850775.97      7045263.05
      2850687.62      7045025.25      2850159.57      7044786.05

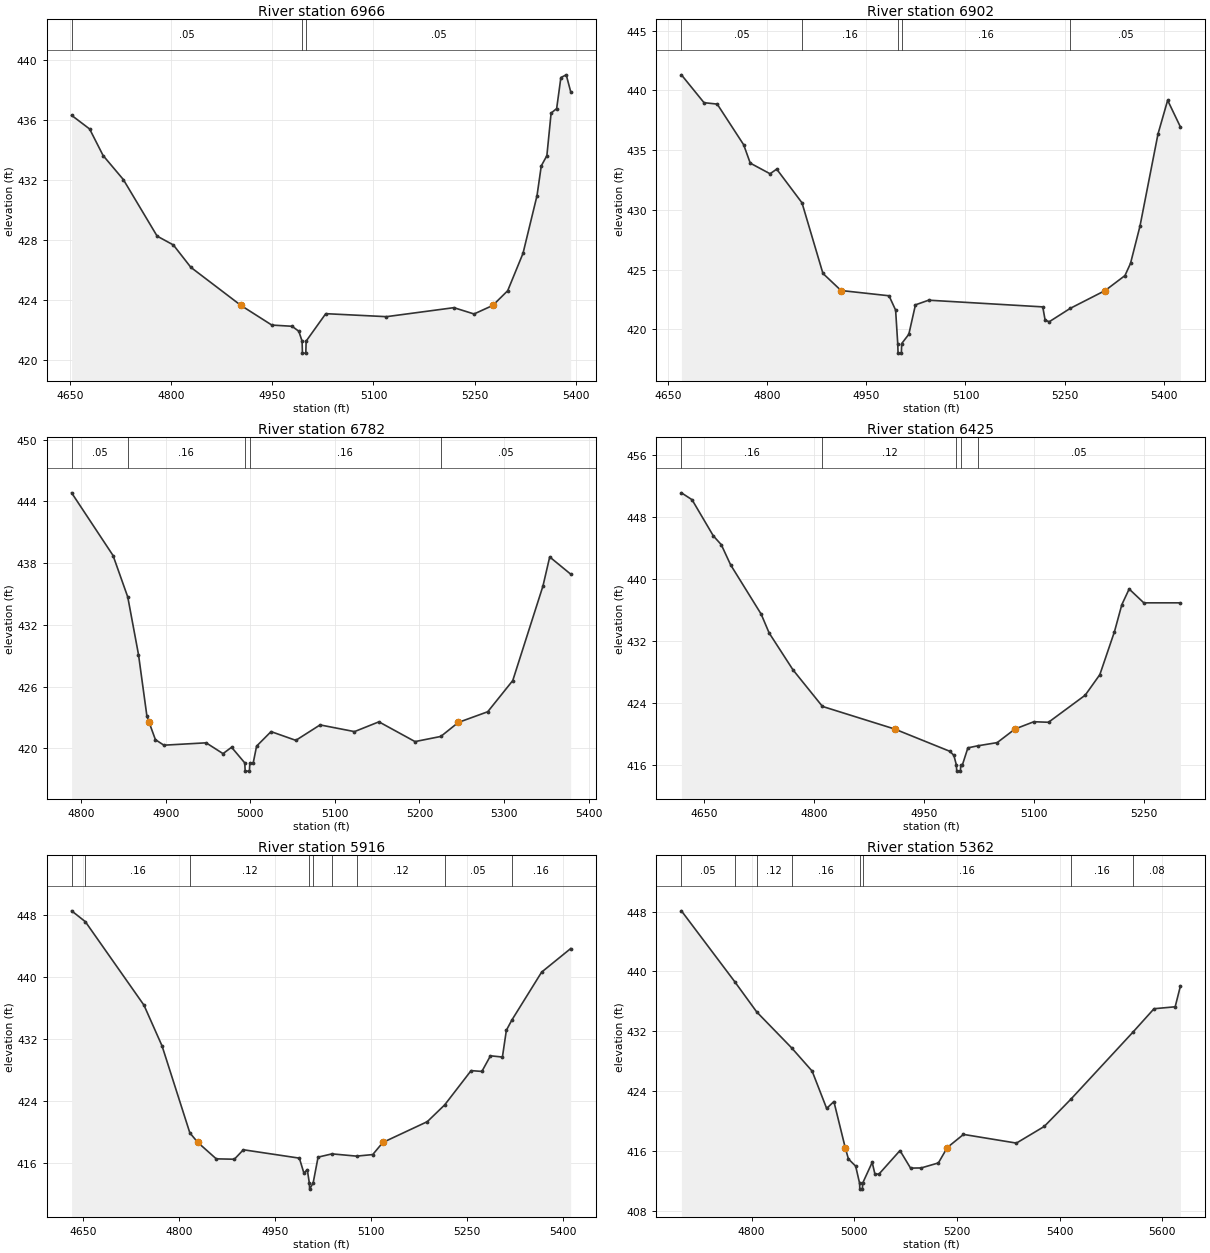
Type RM Length L Ch R = 1,6966,64,64,64
BEGIN DESCRIPTION:
UNT 151 in LFCCL Watershed 7.0
END DESCRIPTION:
XS GIS Cut Line= 4
      2853695.43      7043138.31      2853682.85      7043485.68
      2853682.18      7043729.64      2853800.27      7043819.75
#Sta/Elev= 30
  4652.4  436.33  4679.1  435.42  4699.1  433.65  4729.1  432.05  4779.2  428.28
  4803.3  427.69  4829.2  426.20  4903.5  423.66  4949.3  422.35  4979.3  422.27
  4989.3  421.94  4994.2  421.28  4994.7  420.48  4999.7  420.48  5000.2  421.28
  5029.3  423.11  5119.3  422.91  5219.3  423.51  5249.2  423.09  5277.0  423.66
  5299.1  424.64  5321.8  427.13  5342.6  430.98  5348.9  432.96  5357.2  433.64
  5363.5  436.48  5371.7  436.78  5378.0  438.85  5385.9  439.03  5392.5  437.91
#Mann=3,-1,0
  4652.4    0.05       0  4994.2    0.04       0  5000.2    0.05       0
Bank Sta=4903.5,5277
Exp/Cntr=0.3,0.1

Type RM Length L Ch R = 1,6902,120,120,120
BEGIN DESCRIPTION:
Mapping XS a8a91b48
END DESCRIPTION:
XS GIS Cut Line= 4
      2853619.04      7043160.80      2853619.04      7043492.44
      2853617.31      7043707.72      2853784.00      7043832.74
#Sta/Elev= 30
  4670.1  441.31  4704.3  438.98  4724.3  438.86  4764.3  435.46  4774.3  433.92
  4804.3  433.03  4814.3  433.42  4852.6  430.60  4884.3  424.69  4911.7  423.26
  4984.3  422.82  4994.3  421.62  4997.5  418.82  4998.0  418.02  5003.0  418.02
  5003.5  418.82  5014.3  419.60  5024.3  422.06  5044.3  422.45  5217.0  421.89
  5220.6  420.77  5226.9  420.65  5258.7  421.77  5311.5  423.26  5341.4  424.51
  5349.8  425.53  5364.1  428.64  5391.4  436.36  5406.0  439.18  5425.4  436.94
#Mann=5,-1,0
  4670.1    0.05       0  4852.6    0.16       0  4997.5    0.07       0
  5003.5    0.16       0  5258.7    0.05       0
Bank Sta=4911.7,5311.5
Exp/Cntr=0.3,0.1

Type RM Length L Ch R = 1,6782,357,357,357
BEGIN DESCRIPTION:
XS3885A
END DESCRIPTION:
XS GIS Cut Line= 4
      2853326.00      7043564.22      2853537.23      7043572.60
      2853608.63      7043732.03      2853775.27      7043850.07
#Sta/Elev= 30
  4788.6  444.84  4837.6  438.75  4855.0  434.72  4867.7  429.13  4877.7  423.12
  4880.3  422.53  4887.7  420.86  4897.7  420.32  4947.7  420.55  4967.7  419.50
  4977.8  420.12  4993.4  418.60  4993.9  417.80  4998.9  417.80  4999.4  418.60
  5003.4  418.60  5007.4  420.23  5024.5  421.64  5053.8  420.79  5082.5  422.29
  5123.2  421.64  5152.1  422.59  5194.8  420.67  5225.3  421.17  5246.0  422.53
  5280.8  423.57  5310.4  426.60  5346.1  435.78  5354.1  438.61  5378.9  436.94
#Mann=5,-1,0
  4788.6    0.05       0  4855.0    0.16       0  4993.4    0.07       0
  4999.4    0.16       0  5225.3    0.05       0
Bank Sta=4880.3,5246
Exp/Cntr=0.3,0.1

Type RM Length L Ch R = 1,6425,509,509,509
BEGIN DESCRIPTION:
UNT 151 in LFCCL Watershed 6.0
END DESCRIPTION:
XS GIS Cut Line= 3
      2853175.01      7043725.00      2853525.00      7043875.00
      2853825.02      7043875.00
#Sta/Elev= 30
  4619.5  451.17  4634.0  450.28  4663.0  445.61  4673.9  444.46  4686.6  441.86
  4728.3  435.48  4739.2  433.04  4771.8  428.26  4811.9  423.54  4910.3  420.62
  4985.8  417.73  4991.2  417.20  4994.6  415.97  4995.1  415.17  5000.1  415.17
  5000.6  415.97  5002.8  415.97  5010.3  418.18  5023.5  418.44  5050.3  418.86
  5074.6  420.62  5100.3  421.56  5120.3  421.49  5170.3  424.99  5190.3  427.65
  5210.3  433.22  5220.3  436.70  5230.3  438.73  5250.3  436.94  5300.3  436.94
#Mann=5,-1,0
  4619.5    0.16       0  4811.9    0.12       0  4994.6    0.07       0
  5000.6    0.12       0  5023.5    0.05       0
Bank Sta=4910.3,5074.6
Exp/Cntr=0.3,0.1

Type RM Length L Ch R = 1,5916,554,554,554
BEGIN DESCRIPTION:
UNT 151 in LFCCL Watershed 5.0
END DESCRIPTION:
XS GIS Cut Line= 3
      2853074.98      7043874.98      2853325.00      7044125.00
      2853725.02      7044275.01
#Sta/Elev= 30
  4631.9  448.50  4653.4  447.10  4745.1  436.35  4773.4  431.10  4816.9  419.90
  4829.4  418.67  4858.2  416.56  4886.5  416.51  4900.6  417.73  4988.2  416.65
  4995.3  414.73  5000.6  415.17  5003.8  413.46  5004.3  412.66  5009.8  413.46
  5017.5  416.78  5039.3  417.20  5077.7  416.91  5103.0  417.11  5118.8  418.67
  5188.4  421.35  5215.6  423.51  5256.9  427.92  5273.8  427.82  5287.2  429.83
  5305.9  429.67  5312.1  433.12  5320.5  434.41  5367.3  440.61  5412.7  443.64
#Mann=9,-1,0
  4631.9    0.05       0  4653.4    0.16       0  4816.9    0.12       0
  5003.8    0.07       0  5009.8    0.12       0  5039.3    0.16       0
  5077.7    0.12       0  5215.6    0.05       0  5320.5    0.16       0
Bank Sta=4829.4,5118.8
Exp/Cntr=0.3,0.1

Type RM Length L Ch R = 1,5362,417,417,417
BEGIN DESCRIPTION:
UNT 151 in LFCCL Watershed 4.0
END DESCRIPTION:
XS GIS Cut Line= 3
      2852774.99      7044074.99      2853025.00      7044325.00
      2853624.97      7044474.99
#Sta/Elev= 30
  4663.2  448.10  4767.1  438.63  4809.9  434.59  4878.2  429.77  4917.8  426.69
  4946.1  421.70  4960.2  422.62  4982.2  416.48  4988.5  414.95  5002.6  413.99
  5010.2  411.72  5010.7  410.92  5015.7  410.92  5016.2  411.72  5034.8  414.50
  5040.0  412.96  5047.7  412.91  5088.9  416.07  5109.5  413.73  5130.2  413.75
  5163.7  414.42  5181.1  416.48  5212.6  418.23  5315.7  417.07  5369.8  419.29
  5422.1  422.96  5542.2  431.86  5583.7  435.02  5624.9  435.28  5635.2  438.08
#Mann=8,-1,0
  4663.2    0.05       0  4767.1    0.16       0  4809.9    0.12       0
  4878.2    0.16       0  5010.2    0.07       0  5016.2    0.16       0
  5422.1    0.16       0  5542.2    0.08       0
Bank Sta=4982.2,5181.1
Exp/Cntr=0.3,0.1

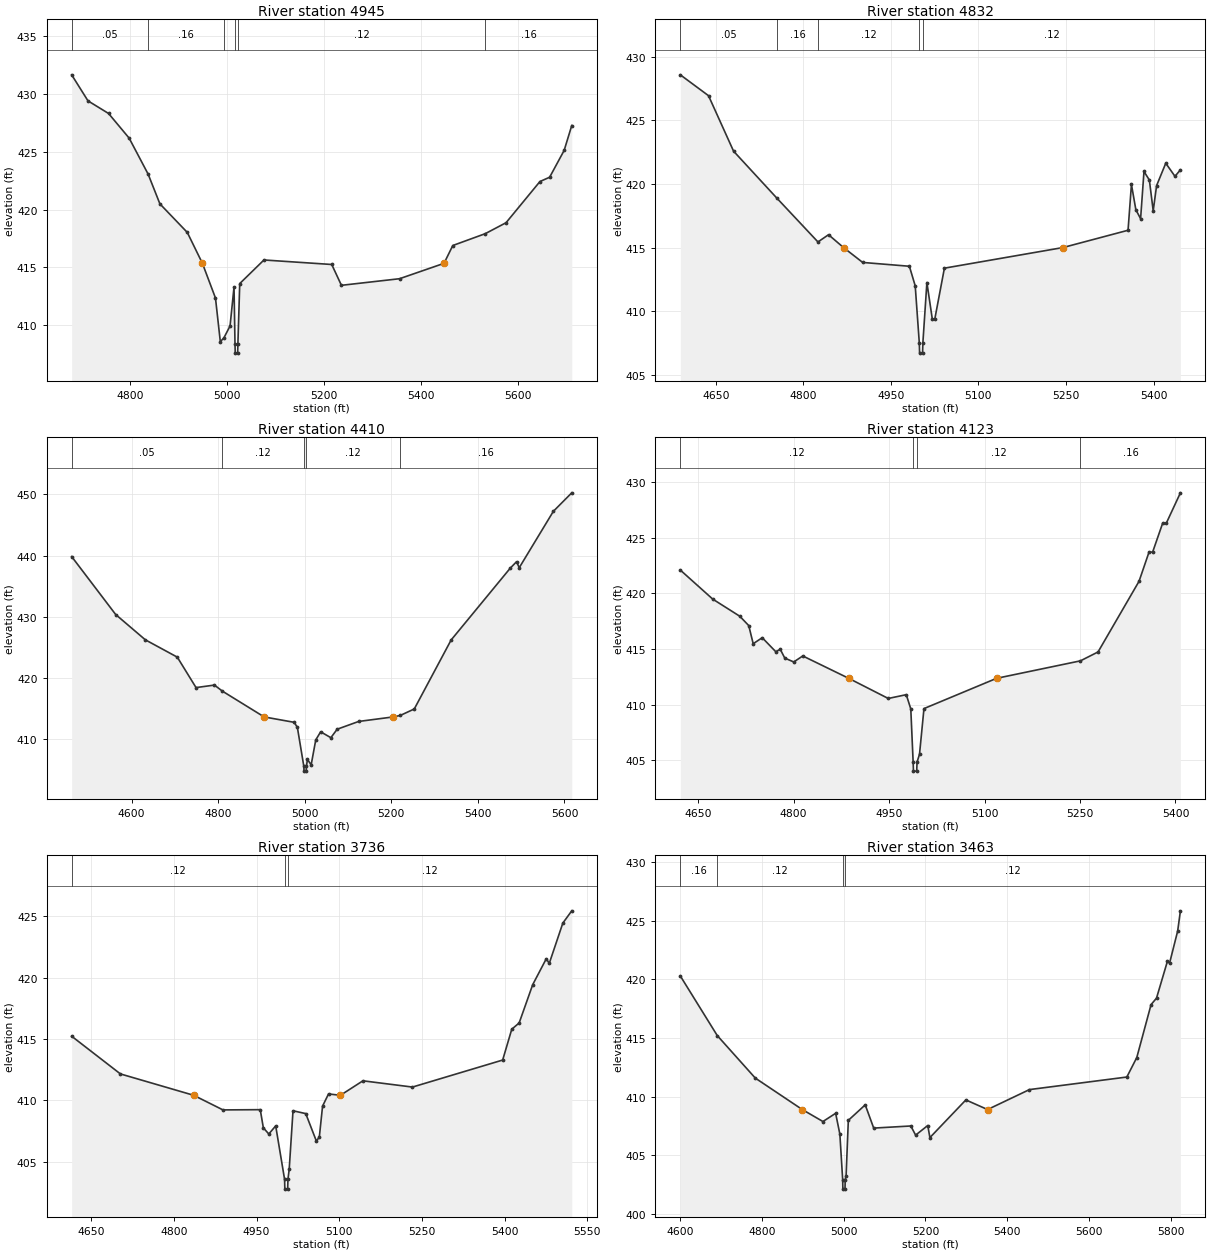
Type RM Length L Ch R = 1,4945,113,113,113
BEGIN DESCRIPTION:
XS3884A
END DESCRIPTION:
XS GIS Cut Line= 4
      2852555.18      7044387.14      2852734.86      7044556.41
      2852867.67      7044561.62      2853520.68      7044566.82
#Sta/Elev= 30
  4679.2  431.64  4712.9  429.39  4755.4  428.30  4797.9  426.17  4837.1  423.06
  4861.4  420.49  4918.0  418.02  4949.2  415.35  4976.2  412.35  4986.2  408.58
  4993.6  408.91  5006.3  409.94  5014.5  413.30  5016.5  408.39  5017.0  407.59
  5022.0  407.59  5022.5  408.39  5026.3  413.60  5076.3  415.64  5216.3  415.25
  5236.3  413.45  5356.3  414.02  5448.2  415.35  5466.3  416.89  5533.2  417.91
  5576.3  418.86  5646.3  422.42  5666.3  422.79  5696.3  425.11  5712.0  427.26
#Mann=6,-1,0
  4679.2    0.05       0  4837.1    0.16       0  4993.6    0.12       0
  5016.5    0.07       0  5022.5    0.12       0  5533.2    0.16       0
Bank Sta=4949.2,5448.2
Exp/Cntr=0.3,0.1

Type RM Length L Ch R = 1,4832,422,422,422
BEGIN DESCRIPTION:
XS3883A
END DESCRIPTION:
XS GIS Cut Line= 5
      2852549.95      7044441.80      2852724.45      7044650.16
      2852888.51      7044655.37      2853174.97      7044665.78
      2853291.10      7044732.89
#Sta/Elev= 30
  4589.4  428.58  4637.7  426.94  4680.6  422.58  4754.9  418.88  4825.2  415.44
  4843.3  416.01  4869.0  415.00  4901.8  413.83  4981.8  413.53  4991.8  411.99
  4998.8  407.50  4999.3  406.70  5004.4  406.70  5004.9  407.50  5011.8  412.25
  5021.1  409.37  5025.3  409.37  5041.8  413.38  5244.9  415.00  5356.4  416.36
  5362.2  419.96  5369.8  417.97  5377.9  417.27  5383.7  420.98  5392.9  420.31
  5399.5  417.89  5405.3  419.87  5421.0  421.63  5436.8  420.60  5446.1  421.11
#Mann=5,-1,0
  4589.4    0.05       0  4754.9    0.16       0  4825.2    0.12       0
  4998.8    0.07       0  5004.9    0.12       0
Bank Sta=4869,5244.9
Exp/Cntr=0.3,0.1

Type RM Length L Ch R = 1,4410,287,287,287
BEGIN DESCRIPTION:
UNT 151 in LFCCL Watershed 2.0
END DESCRIPTION:
XS GIS Cut Line= 3
      2852475.01      7044325.03      2852675.00      7044875.00
      2853125.01      7045225.01
#Sta/Elev= 30
  4461.5  439.85  4563.2  430.39  4631.7  426.26  4705.5  423.43  4748.8  418.46
  4791.3  418.87  4809.7  417.88  4906.2  413.67  4975.5  412.79  4982.9  411.97
  4997.8  405.62  4998.3  404.82  5003.4  404.82  5003.9  405.62  5006.1  406.72
  5014.8  405.86  5025.4  409.92  5036.7  411.24  5060.3  410.28  5074.8  411.66
  5124.5  412.93  5204.3  413.67  5220.6  413.91  5253.0  414.97  5338.1  426.23
  5474.7  437.96  5489.2  439.01  5495.5  438.04  5574.3  447.24  5616.8  450.26
#Mann=5,-1,0
  4461.5    0.05       0  4809.7    0.12       0  4997.8    0.07       0
  5003.9    0.12       0  5220.6    0.16       0
Bank Sta=4906.2,5204.3
Exp/Cntr=0.3,0.1

Type RM Length L Ch R = 1,4123,387,387,387
BEGIN DESCRIPTION:
XS3882A
END DESCRIPTION:
XS GIS Cut Line= 4
      2852273.94      7044684.03      2852534.34      7044949.64
      2852643.72      7044970.47      2852904.16      7045124.13
#Sta/Elev= 30
  4622.1  422.10  4673.0  419.49  4715.5  417.95  4729.6  417.11  4736.6  415.48
  4750.8  416.02  4772.1  414.76  4779.1  414.98  4786.2  414.19  4800.3  413.84
  4814.5  414.38  4886.7  412.37  4948.8  410.56  4977.1  410.90  4984.2  409.62
  4987.9  404.83  4988.4  404.03  4993.5  404.03  4994.0  404.83  4997.9  405.55
  5004.9  409.65  5119.0  412.37  5250.7  413.94  5278.4  414.74  5342.8  421.09
  5358.4  423.70  5364.2  423.72  5379.9  426.31  5385.7  426.32  5407.8  429.04
#Mann=4,-1,0
  4622.1    0.12       0  4987.9    0.07       0  4994.0    0.12       0
  5250.7    0.16       0
Bank Sta=4886.7,5119
Exp/Cntr=0.3,0.1

Type RM Length L Ch R = 1,3736,273,273,273
BEGIN DESCRIPTION:
XS3881A
END DESCRIPTION:
XS GIS Cut Line= 3
      2852180.18      7044782.99      2852338.66      7045108.98
      2852846.44      7045305.36
#Sta/Elev= 30
  4614.8  415.22  4703.2  412.15  4836.1  410.41  4889.2  409.22  4956.8  409.24
  4962.4  407.76  4972.3  407.26  4984.8  407.92  5000.9  403.57  5001.4  402.77
  5006.5  402.77  5007.0  403.57  5009.3  404.39  5016.2  409.15  5039.3  408.92
  5058.5  406.69  5063.9  407.00  5069.8  409.53  5080.6  410.52  5102.2  410.41
  5143.0  411.59  5232.8  411.08  5396.4  413.28  5412.9  415.79  5426.3  416.30
  5450.9  419.42  5475.5  421.53  5480.9  421.15  5505.5  424.43  5521.7  425.43
#Mann=3,-1,0
  4614.8    0.12       0  5000.9    0.07       0  5007.0    0.12       0
Bank Sta=4836.1,5102.2
Exp/Cntr=0.3,0.1

Type RM Length L Ch R = 1,3463,385,385,385
BEGIN DESCRIPTION:
Mapping XS 1126965d
END DESCRIPTION:
XS GIS Cut Line= 3
      2852018.14      7044707.74      2852144.00      7045191.66
      2852841.43      7045377.93
#Sta/Elev= 30
  4601.1  420.28  4691.4  415.20  4784.3  411.58  4899.1  408.90  4949.6  407.88
  4980.6  408.58  4990.9  406.81  4997.8  402.92  4998.3  402.12  5003.5  402.12
  5004.0  402.92  5006.1  403.21  5011.6  407.98  5052.9  409.30  5073.6  407.32
  5164.3  407.50  5176.0  406.72  5205.7  407.54  5210.9  406.51  5298.8  409.72
  5351.8  408.90  5454.1  410.60  5692.1  411.67  5716.4  413.33  5751.3  417.84
  5764.6  418.39  5791.4  421.55  5796.5  421.37  5816.3  424.11  5823.0  425.83
#Mann=4,-1,0
  4601.1    0.16       0  4691.4    0.12       0  4997.8    0.07       0
  5004.0    0.12       0
Bank Sta=4899.1,5351.8
Exp/Cntr=0.3,0.1

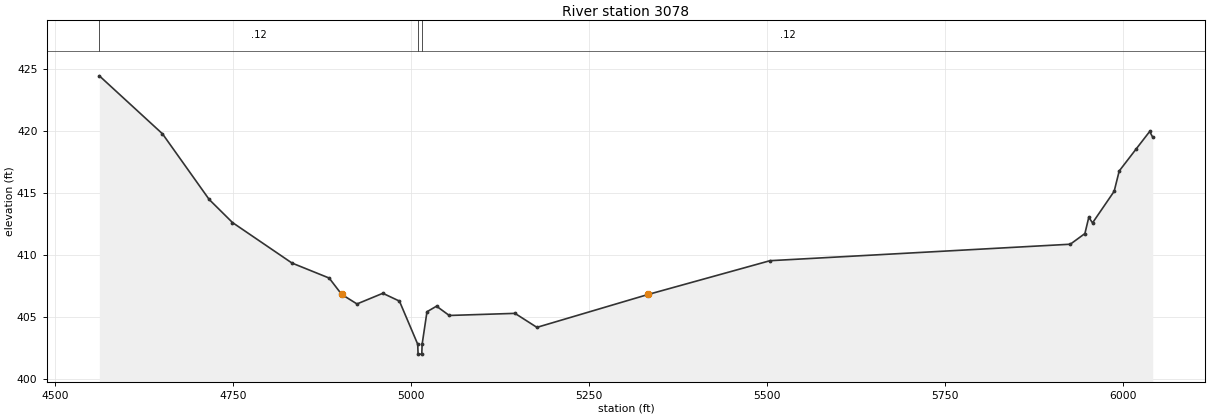
Type RM Length L Ch R = 1,3078,0,0,0
BEGIN DESCRIPTION:
UNT 151 in LFCCL Watershed 1.0
END DESCRIPTION:
XS GIS Cut Line= 3
      2851680.19      7044803.84      2851880.76      7045258.93
      2852837.81      7045480.14
#Sta/Elev= 30
  4562.0  424.47  4650.7  419.79  4716.3  414.49  4749.0  412.63  4832.6  409.36
  4884.8  408.15  4902.4  406.83  4923.9  406.06  4960.2  406.92  4983.5  406.29
  5009.2  402.81  5009.7  402.01  5014.9  402.01  5015.4  402.81  5022.2  405.43
  5035.6  405.88  5053.5  405.13  5145.8  405.30  5176.6  404.17  5333.1  406.83
  5504.0  409.55  5925.8  410.88  5946.3  411.74  5951.8  413.06  5957.0  412.60
  5987.4  415.15  5994.5  416.79  6018.2  418.56  6037.3  419.98  6041.6  419.51
#Mann=3,-1,0
  4562.0    0.12       0  5009.2    0.07       0  5015.4    0.12       0
Bank Sta=4902.4,5333.1
Exp/Cntr=0.3,0.1

Chan Stop Cuts=-1