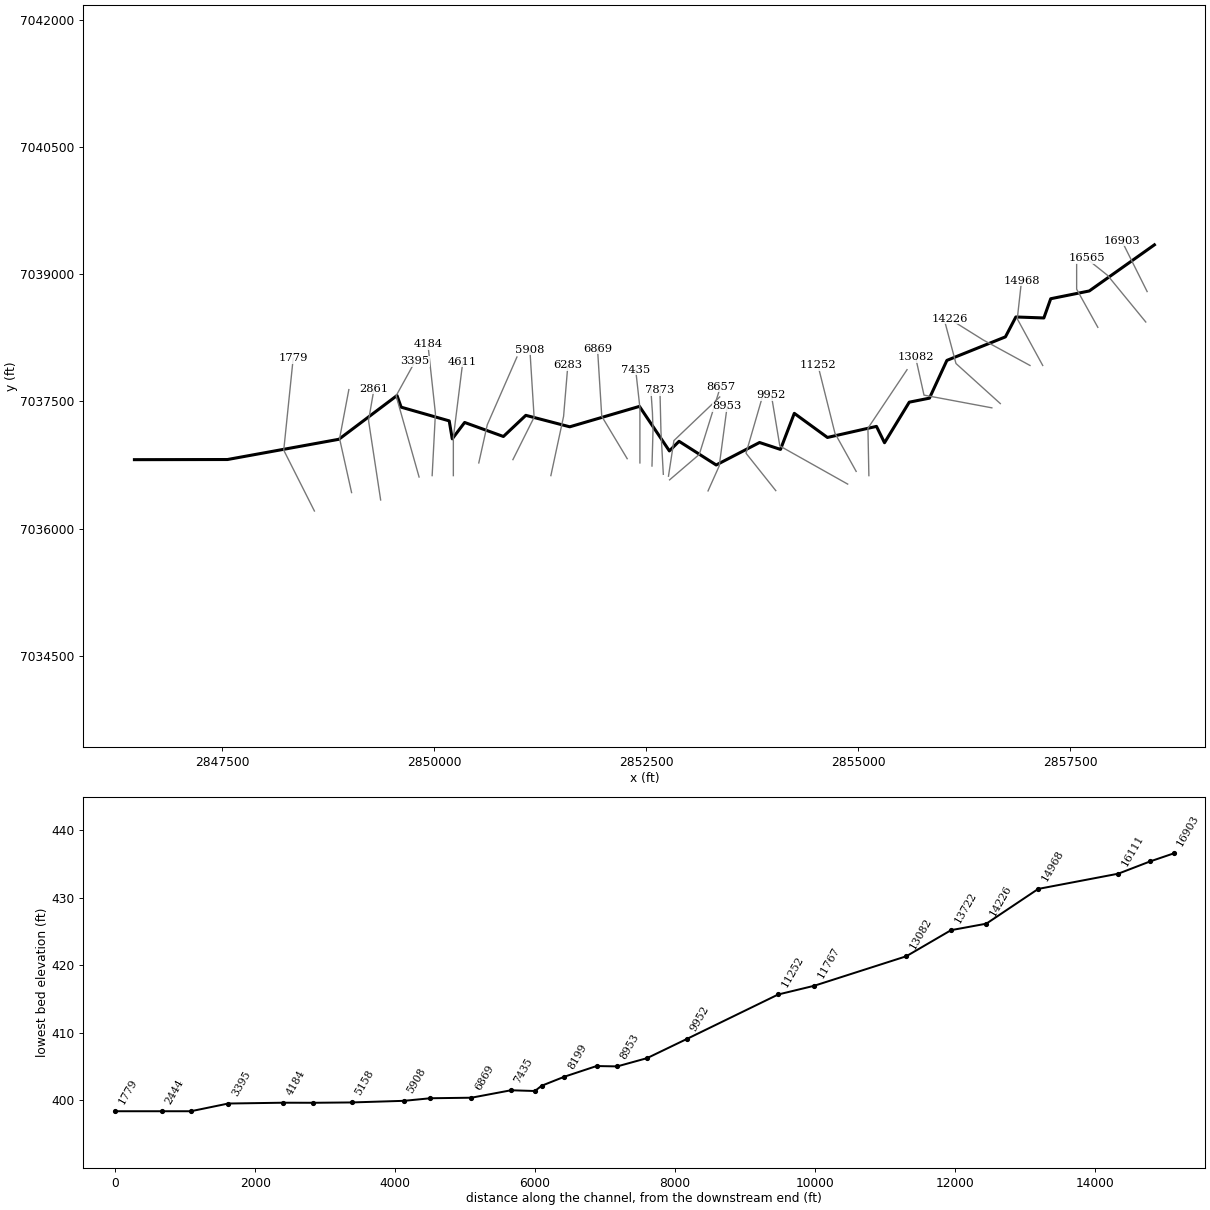
--- UNT 154 in LFCCL Watershed.prj (project) ---

Proj Title=UNT 154 in LFCCL Watershed Base Level Engineering
Current Plan=p01
Default Exp/Contr=0.3,0.1
English Units
Geom File=g01
Flow File=f01
Plan File=p01
BEGIN DESCRIPTION:
UNT 154 in LFCCL Watershed
END DESCRIPTION:

--- UNT 154 in LFCCL Watershed.p01 (plan) ---

Plan Title=Multiple Run
Short Identifier=Multiple
Geom File=g01
Flow File=f01
Subcritical Flow
K Sum by GR= 0
Std Step Tol= 0.01
Critical Tol= 0.01
Num of Std Step Trials= 20
Max Error Tol= 0.3
Flow Tol Ratio= 0.001
Split Flow NTrial= 30
Split Flow Tol= 0.02
Split Flow Ratio= 0.02
Log Output Level= 0
Friction Slope Method= 1
Unsteady Friction Slope Method= 2
Unsteady Bridges Friction Slope Method= 1
Parabolic Critical Depth
Global Vel Dist=  1 , 1 , 1
Global Log Level= 0
CheckData=True
Encroach Param= -1, 0, 0, 0
BEGIN DESCRIPTION:
Multiple Run
END DESCRIPTION:

--- UNT 154 in LFCCL Watershed.f01 (steady flow) ---

Flow Title=Multiple
Number of Profiles=7
Profile Names=10-year,25-year,50-year,1pct_min,100-year,1pct_plu,500-year
River Rch & RM= UNT 154 in LFCCL,Reach-1,16903
     485     643     769     458     913    1822    1290
River Rch & RM= UNT 154 in LFCCL,Reach-1,16565
     825    1122    1365     825    1646    3285    2399
River Rch & RM= UNT 154 in LFCCL,Reach-1,8953
    1048    1439    1764    1072    2139    4267    3152
River Rch & RM= UNT 154 in LFCCL,Reach-1,2444
    1114    1531    1876    1140    2275    4540    3353
Boundary for River Rch & Prof#=UNT 154 in LFCCL,Reach-1,1
Up Type=0
Dn Type=3
Dn Slope=0.005
Boundary for River Rch & Prof#=UNT 154 in LFCCL,Reach-1,2
Up Type=0
Dn Type=3
Dn Slope=0.005
Boundary for River Rch & Prof#=UNT 154 in LFCCL,Reach-1,3
Up Type=0
Dn Type=3
Dn Slope=0.005
Boundary for River Rch & Prof#=UNT 154 in LFCCL,Reach-1,4
Up Type=0
Dn Type=3
Dn Slope=0.005
Boundary for River Rch & Prof#=UNT 154 in LFCCL,Reach-1,5
Up Type=0
Dn Type=3
Dn Slope=0.005
Boundary for River Rch & Prof#=UNT 154 in LFCCL,Reach-1,6
Up Type=0
Dn Type=3
Dn Slope=0.005
Boundary for River Rch & Prof#=UNT 154 in LFCCL,Reach-1,7
Up Type=0
Dn Type=3
Dn Slope=0.005

--- UNT 154 in LFCCL Watershed.g01 (geometry) ---

Geom Title=Existing Conditions

River Reach=UNT 154 in LFCCL,Reach-1
Reach XY= 30
      2858492.10      7039348.65      2857724.00      7038804.13
      2857269.20      7038712.50      2857188.48      7038485.59
      2856857.96      7038497.22      2856735.19      7038262.47
      2856044.95      7037984.83      2855839.27      7037539.27
      2855601.21      7037491.77      2855309.38      7037013.12
      2855214.53      7037206.22      2854636.34      7037075.31
      2854245.67      7037359.94      2854082.77      7036934.22
      2853835.71      7037015.81      2853324.52      7036750.58
      2852886.65      7037030.10      2852772.39      7036916.61
      2852419.50      7037442.06      2851597.90      7037201.10
      2851079.45      7037336.35      2850815.17      7037086.84
      2850358.12      7037252.40      2850211.99      7037058.86
      2850176.24      7037271.06      2849609.59      7037432.73
      2849560.62      7037570.31      2848875.12      7037053.86
      2847561.70      7036815.06      2846464.13      7036813.33

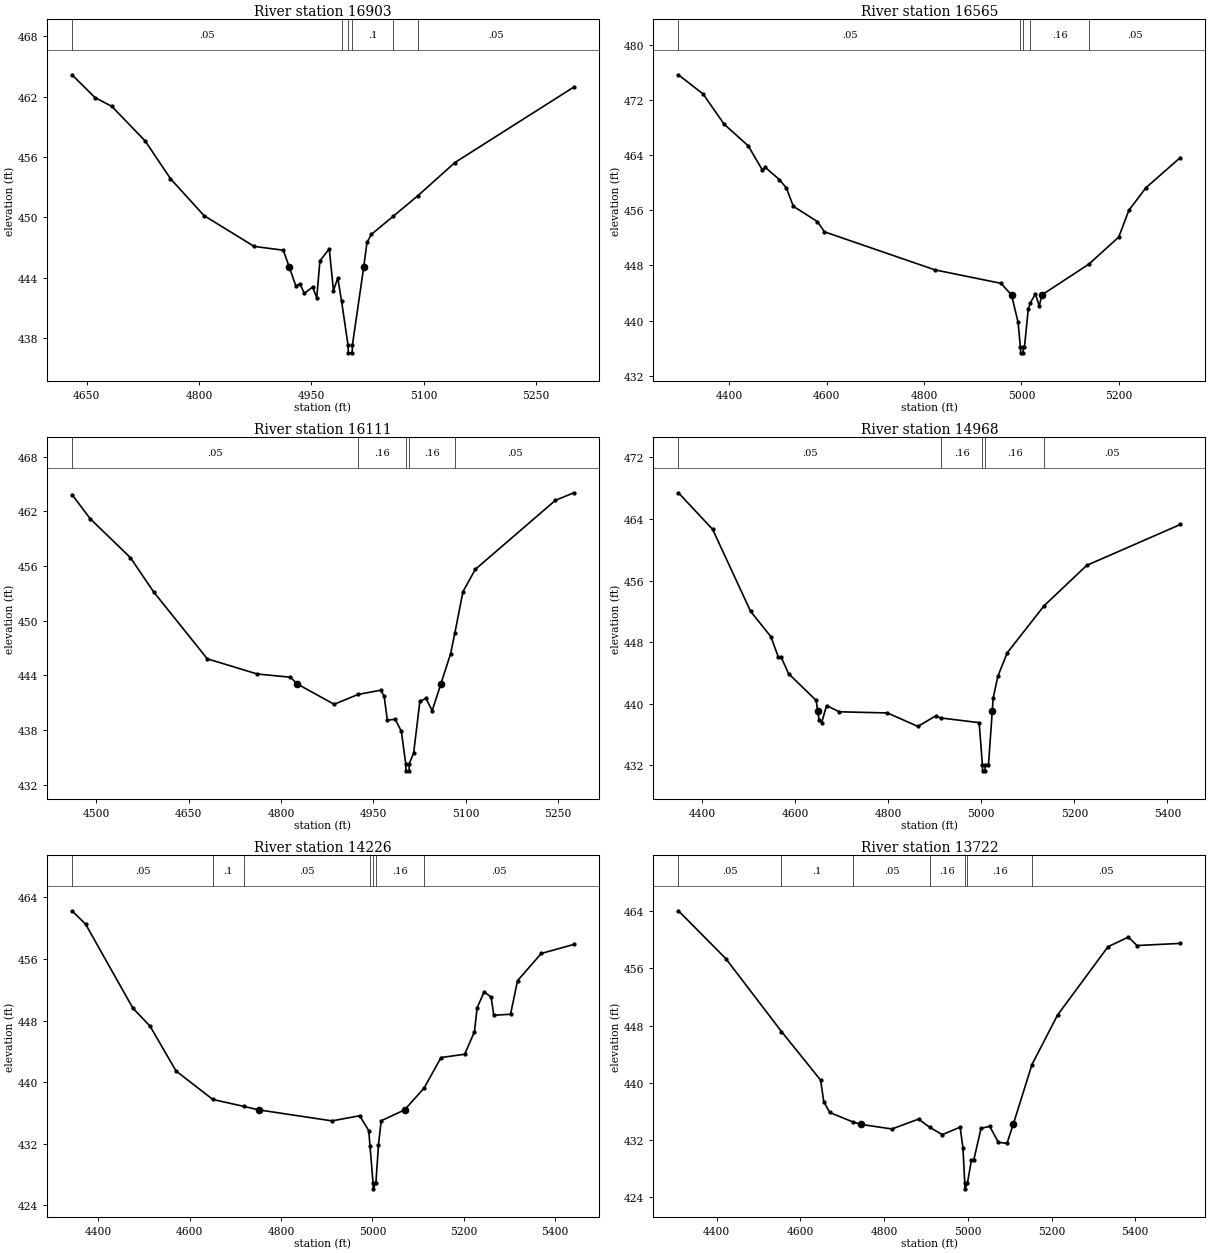
Type RM Length L Ch R = 1,16903,338,338,338
BEGIN DESCRIPTION:
UNT 154 in LFCCL Watershed 25.0
END DESCRIPTION:
XS GIS Cut Line= 3
      2858406.23      7038797.18      2858256.25      7039097.14
      2858106.24      7039397.16
#Sta/Elev= 30
  4630.1  464.17  4661.0  461.90  4683.4  461.03  4728.1  457.58  4761.8  453.84
  4806.5  450.18  4873.6  447.11  4912.6  446.73  4920.4  445.08  4929.3  443.19
  4934.9  443.38  4940.7  442.44  4951.7  443.07  4957.3  442.02  4961.5  445.67
  4974.0  446.87  4979.6  442.72  4985.4  443.97  4990.5  441.65  4999.0  437.33
  4999.5  436.53  5004.5  436.53  5005.0  437.33  5020.1  445.08  5024.4  447.50
  5030.2  448.30  5059.4  450.10  5092.6  452.16  5142.0  455.45  5300.9  462.95
#Mann=6,-1,0
  4630.1    0.05       0  4990.5     0.1       0  4999.0    0.07       0
  5005.0     0.1       0  5059.4    0.16       0  5092.6    0.05       0
Bank Sta=4920.4,5020.1
Exp/Cntr=0.3,0.1

Type RM Length L Ch R = 1,16565,454,454,454
BEGIN DESCRIPTION:
UNT 154 in LFCCL Watershed 24.0
END DESCRIPTION:
XS GIS Cut Line= 3
      2858390.08      7038438.05      2857940.10      7038988.02
      2857690.07      7039188.05
#Sta/Elev= 30
  4295.6  475.62  4346.5  472.82  4389.5  468.46  4439.0  465.33  4467.8  461.84
  4474.2  462.19  4502.9  460.44  4517.3  459.23  4531.6  456.57  4581.2  454.35
  4595.5  452.87  4822.4  447.36  4958.0  445.41  4979.7  443.73  4993.2  439.77
  4998.0  436.14  4998.5  435.34  5003.5  435.34  5004.0  436.14  5006.2  436.14
  5014.2  441.72  5018.7  442.60  5028.7  443.88  5036.7  442.14  5042.1  443.73
  5138.6  448.19  5199.9  452.11  5220.7  455.99  5256.0  459.27  5326.4  463.63
#Mann=5,-1,0
  4295.6    0.05       0  4998.0    0.03       0  5004.0    0.05       0
  5018.7    0.16       0  5138.6    0.05       0
Bank Sta=4979.7,5042.1
Exp/Cntr=0.3,0.1

Type RM Length L Ch R = 1,16111,1143,1143,1143
BEGIN DESCRIPTION:
UNT 154 in LFCCL Watershed 23.0
END DESCRIPTION:
XS GIS Cut Line= 3
      2857825.01      7038374.97      2857575.00      7038825.00
      2857575.00      7039124.99
#Sta/Elev= 30
  4460.5  463.84  4490.3  461.17  4555.5  456.91  4593.2  453.15  4680.2  445.82
  4761.4  444.15  4815.2  443.80  4826.3  443.06  4886.1  440.83  4925.5  441.92
  4961.6  442.37  4967.3  441.73  4972.5  439.09  4985.3  439.18  4995.3  437.86
  5002.3  434.33  5002.8  433.53  5007.8  433.53  5008.3  434.33  5015.3  435.52
  5025.3  441.16  5035.3  441.47  5045.3  440.12  5059.4  443.06  5075.3  446.40
  5082.2  448.68  5095.3  453.19  5115.3  455.63  5245.3  463.20  5275.3  464.03
#Mann=5,-1,0
  4460.5    0.05       0  4925.5    0.16       0  5002.3    0.07       0
  5008.3    0.16       0  5082.2    0.05       0
Bank Sta=4826.3,5059.4
Exp/Cntr=0.3,0.1

Type RM Length L Ch R = 1,14968,742,742,742
BEGIN DESCRIPTION:
UNT 154 in LFCCL Watershed 22.0
END DESCRIPTION:
XS GIS Cut Line= 3
      2857175.02      7037924.96      2856875.00      7038475.00
      2856925.00      7038924.99
#Sta/Elev= 30
  4348.6  467.40  4422.2  462.65  4503.8  452.00  4547.5  448.70  4563.6  446.04
  4569.3  446.08  4585.5  443.90  4644.8  440.43  4648.0  439.09  4651.0  437.87
  4656.7  437.55  4667.1  439.76  4694.6  438.95  4798.1  438.80  4863.6  437.05
  4901.6  438.41  4913.7  438.14  4995.3  437.54  5002.3  432.08  5002.8  431.28
  5007.9  431.28  5008.4  432.08  5015.4  432.08  5023.6  439.09  5025.5  440.75
  5035.5  443.55  5055.6  446.61  5135.2  452.74  5226.7  457.97  5427.9  463.28
#Mann=5,-1,0
  4348.6    0.05       0  4913.7    0.16       0  5002.3    0.07       0
  5008.4    0.16       0  5135.2    0.05       0
Bank Sta=4648,5023.6
Exp/Cntr=0.3,0.1

Type RM Length L Ch R = 1,14226,504,504,504
BEGIN DESCRIPTION:
UNT 154 in LFCCL Watershed 21.0
END DESCRIPTION:
XS GIS Cut Line= 3
      2857025.02      7037924.99      2856475.00      7038225.00
      2856075.02      7038474.99
#Sta/Elev= 30
  4342.6  462.27  4372.5  460.53  4476.0  449.61  4513.5  447.28  4570.4  441.45
  4650.9  437.75  4718.3  436.86  4751.1  436.40  4911.7  434.97  4972.1  435.64
  4992.1  433.70  4994.7  431.74  5001.4  426.94  5001.9  426.14  5007.7  426.94
  5013.3  431.84  5019.2  434.98  5070.4  436.40  5113.2  439.24  5150.1  443.20
  5202.0  443.63  5223.3  446.55  5229.1  449.65  5244.5  451.74  5259.8  451.05
  5265.7  448.69  5302.3  448.83  5317.6  453.19  5369.5  456.72  5440.8  457.90
#Mann=7,-1,0
  4342.6    0.05       0  4650.9     0.1       0  4718.3    0.05       0
  4994.7    0.16       0  5001.4    0.07       0  5007.7    0.16       0
  5113.2    0.05       0
Bank Sta=4751.1,5070.4
Exp/Cntr=0.3,0.1

Type RM Length L Ch R = 1,13722,640,640,640
BEGIN DESCRIPTION:
UNT 154 in LFCCL Watershed 20.0
END DESCRIPTION:
XS GIS Cut Line= 3
      2856674.99      7037475.01      2856152.00      7037948.06
      2856025.01      7038424.96
#Sta/Elev= 30
  4308.9  464.06  4422.1  457.37  4555.0  447.18  4648.5  440.38  4656.0  437.38
  4670.2  435.86  4726.1  434.52  4746.1  434.18  4818.9  433.55  4882.4  434.93
  4909.1  433.78  4939.2  432.76  4981.7  433.80  4988.5  430.90  4992.8  425.98
  4993.3  425.18  4999.1  425.98  5008.7  429.16  5014.1  429.16  5031.6  433.63
  5052.3  433.93  5073.0  431.68  5093.7  431.55  5108.5  434.18  5153.3  442.56
  5214.4  449.48  5334.8  459.03  5383.5  460.38  5404.2  459.20  5507.6  459.50
#Mann=7,-1,0
  4308.9    0.05       0  4555.0     0.1       0  4726.1    0.05       0
  4909.1    0.16       0  4992.8    0.07       0  4999.1    0.16       0
  5153.3    0.05       0
Bank Sta=4746.1,5108.5
Exp/Cntr=0.3,0.1

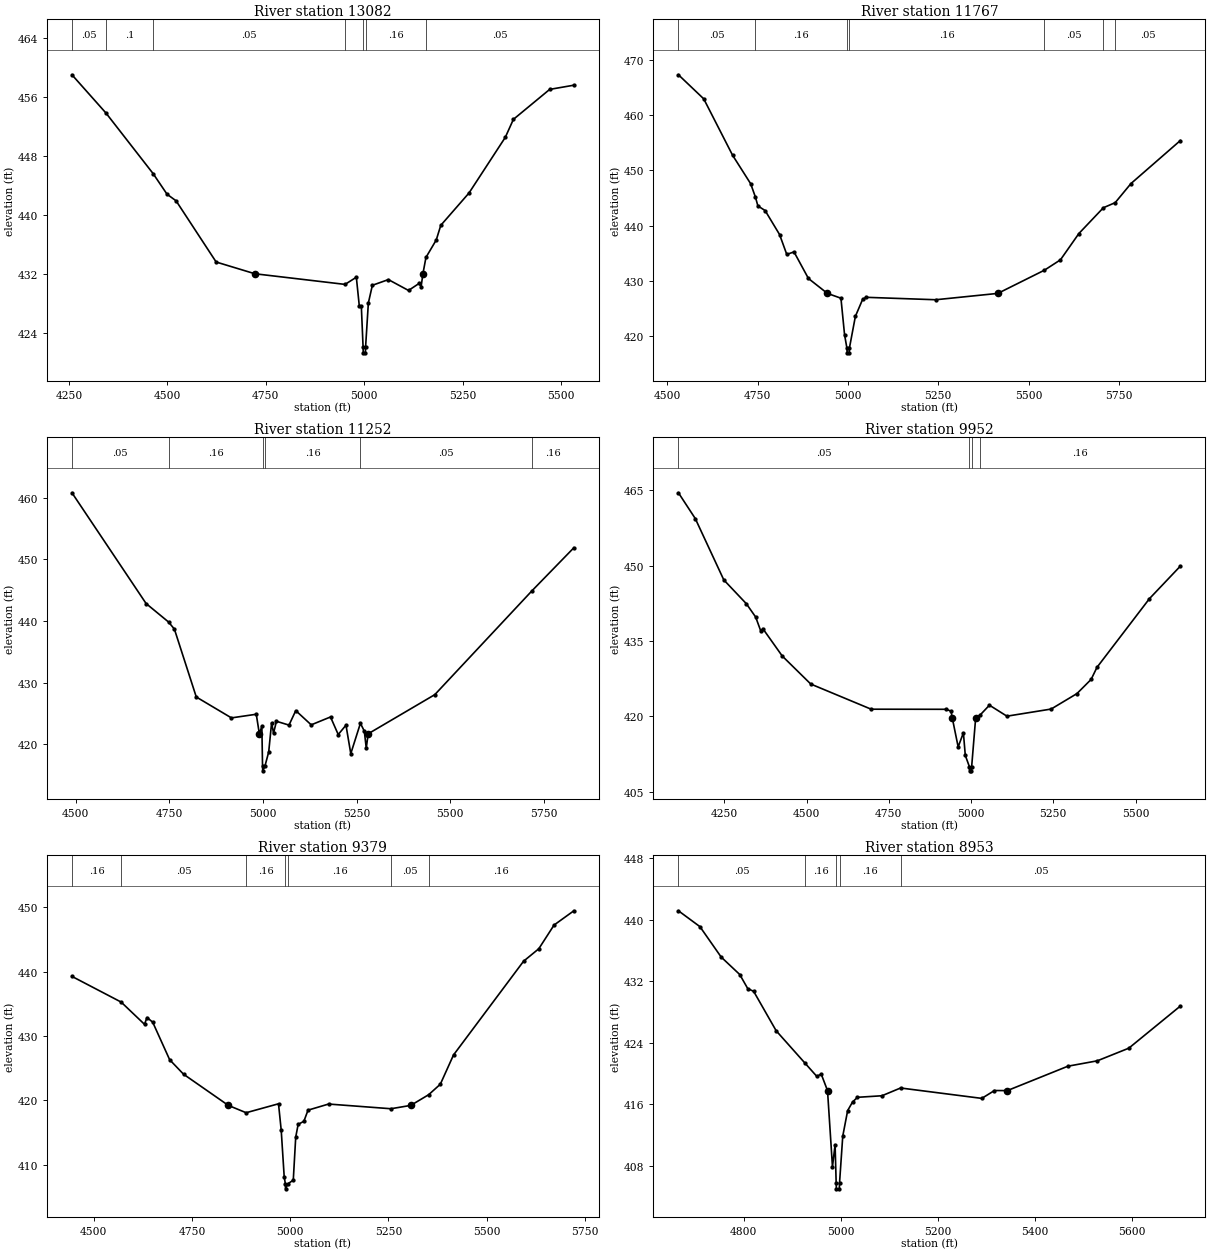
Type RM Length L Ch R = 1,13082,1315,1315,1315
BEGIN DESCRIPTION:
UNT 154 in LFCCL Watershed 19.0
END DESCRIPTION:
XS GIS Cut Line= 3
      2856575.01      7037425.00      2855775.00      7037575.00
      2855675.01      7038024.97
#Sta/Elev= 30
  4257.9  458.98  4344.3  453.80  4464.0  445.60  4499.5  442.80  4522.4  441.91
  4624.2  433.62  4722.6  432.03  4951.6  430.59  4980.3  431.56  4987.9  427.62
  4993.0  427.60  4997.4  422.12  4997.9  421.32  5003.3  421.32  5003.8  422.12
  5010.8  428.07  5021.0  430.47  5061.7  431.24  5112.8  429.77  5139.7  430.72
  5144.8  430.27  5149.4  432.03  5157.1  434.24  5183.3  436.61  5194.8  438.59
  5266.5  442.97  5358.7  450.51  5379.2  452.94  5471.4  457.00  5532.8  457.57
#Mann=7,-1,0
  4257.9    0.05       0  4344.3     0.1       0  4464.0    0.05       0
  4951.6    0.16       0  4997.4    0.07       0  5003.8    0.16       0
  5157.1    0.05       0
Bank Sta=4722.6,5149.4
Exp/Cntr=0.3,0.1

Type RM Length L Ch R = 1,11767,515,515,515
BEGIN DESCRIPTION:
UNT 154 in LFCCL Watershed 18.0
END DESCRIPTION:
XS GIS Cut Line= 3
      2855125.00      7036624.96      2855113.81      7037184.18
      2855575.03      7037875.04
#Sta/Elev= 30
  4530.4  467.34  4600.5  462.98  4680.5  452.75  4730.5  447.60  4743.8  445.15
  4750.5  443.58  4770.5  442.74  4810.5  438.40  4830.5  434.79  4850.5  435.25
  4890.5  430.43  4943.0  427.73  4980.5  426.86  4990.5  420.26  4997.2  417.76
  4997.7  416.96  5003.3  416.96  5003.8  417.76  5020.5  423.57  5040.5  426.64
  5050.5  427.02  5243.0  426.58  5415.0  427.73  5544.2  431.94  5588.4  433.81
  5639.5  438.58  5707.3  443.25  5740.0  444.17  5783.7  447.63  5920.4  455.42
#Mann=7,-1,0
  4530.4    0.05       0  4743.8    0.16       0  4997.2    0.07       0
  5003.8    0.16       0  5544.2    0.05       0  5707.3    0.16       0
  5740.0    0.05       0
Bank Sta=4943,5415
Exp/Cntr=0.3,0.1

Type RM Length L Ch R = 1,11252,1300,1300,1300
BEGIN DESCRIPTION:
UNT 154 in LFCCL Watershed 17.0
END DESCRIPTION:
XS GIS Cut Line= 3
      2854975.00      7036674.99      2854725.00      7037125.00
      2854525.00      7037924.99
#Sta/Elev= 30
  4490.3  460.78  4688.2  442.81  4748.0  439.82  4763.7  438.66  4822.1  427.65
  4915.9  424.26  4982.2  424.85  4990.4  421.68  4997.1  422.90  4998.9  416.47
  4999.4  415.67  5005.5  416.47  5015.4  418.75  5023.1  423.47  5028.3  421.78
  5036.0  423.71  5069.5  423.09  5087.6  425.44  5128.8  423.13  5180.3  424.41
  5200.9  421.56  5221.6  423.08  5234.4  418.46  5260.1  423.38  5270.5  422.12
  5275.7  419.35  5280.8  421.68  5458.6  428.03  5717.8  444.87  5829.7  451.86
#Mann=6,-1,0
  4490.3    0.05       0  4748.0    0.16       0  4998.9    0.07       0
  5005.5    0.16       0  5260.1    0.05       0  5717.8    0.16       0
Bank Sta=4990.4,5280.8
Exp/Cntr=0.3,0.1

Type RM Length L Ch R = 1,9952,573,573,573
BEGIN DESCRIPTION:
UNT 154 in LFCCL Watershed 15.0
END DESCRIPTION:
XS GIS Cut Line= 3
      2854874.97      7036525.02      2854075.00      7036975.00
      2853975.00      7037574.98
#Sta/Elev= 30
  4110.1  464.52  4161.4  459.38  4248.1  447.16  4316.6  442.42  4345.0  439.76
  4360.9  436.91  4366.6  437.47  4425.9  431.99  4512.6  426.41  4696.2  421.40
  4924.7  421.38  4939.0  421.00  4942.8  419.66  4960.7  413.89  4976.6  416.69
  4982.4  412.20  4995.0  409.92  4995.5  409.12  5001.2  409.12  5001.7  409.92
  5013.9  419.66  5027.0  420.21  5055.8  422.20  5109.0  420.01  5243.4  421.43
  5321.9  424.51  5365.0  427.34  5382.8  429.74  5542.4  443.43  5636.2  449.90
#Mann=4,-1,0
  4110.1    0.05       0  4995.0    0.03       0  5001.7    0.05       0
  5027.0    0.16       0
Bank Sta=4942.8,5013.9
Exp/Cntr=0.3,0.1

Type RM Length L Ch R = 1,9379,426,426,426
BEGIN DESCRIPTION:
UNT 154 in LFCCL Watershed 14.0
END DESCRIPTION:
XS GIS Cut Line= 3
      2854027.00      7036448.07      2853676.31      7036889.04
      2853875.01      7037575.02
#Sta/Elev= 30
  4444.6  439.28  4569.8  435.29  4629.3  431.83  4635.6  432.89  4650.1  432.17
  4693.3  426.33  4728.6  424.08  4842.7  419.23  4888.0  418.09  4970.4  419.48
  4977.3  415.36  4984.9  408.11  4987.8  407.06  4988.3  406.26  4994.6  407.06
  5008.0  407.61  5014.2  414.30  5020.4  416.28  5035.0  416.76  5045.5  418.49
  5097.9  419.44  5256.6  418.71  5307.0  419.23  5352.6  420.89  5382.3  422.52
  5415.9  427.07  5594.2  441.64  5633.0  443.58  5671.8  447.26  5722.2  449.48
#Mann=7,-1,0
  4444.6    0.16       0  4569.8    0.05       0  4888.0    0.16       0
  4987.8    0.07       0  4994.6    0.16       0  5256.6    0.05       0
  5352.6    0.16       0
Bank Sta=4842.7,5307
Exp/Cntr=0.3,0.1

Type RM Length L Ch R = 1,8953,296,296,296
BEGIN DESCRIPTION:
XS3886A
END DESCRIPTION:
XS GIS Cut Line= 3
      2853228.39      7036444.59      2853360.33      7036739.73
      2853454.09      7037444.63
#Sta/Elev= 30
  4665.6  441.16  4709.9  439.10  4753.7  435.15  4792.0  432.88  4808.4  431.06
  4820.7  430.69  4867.1  425.57  4925.9  421.41  4950.8  419.65  4959.9  419.95
  4972.9  417.80  4983.1  407.91  4988.5  410.78  4990.7  405.84  4991.2  405.04
  4997.2  405.04  4997.7  405.84  5004.3  411.89  5014.4  415.21  5024.5  416.32
  5034.6  416.93  5085.0  417.13  5123.5  418.14  5290.8  416.79  5317.0  417.81
  5343.4  417.80  5468.3  420.97  5528.9  421.67  5593.8  423.31  5700.0  428.78
#Mann=5,-1,0
  4665.6    0.05       0  4925.9    0.16       0  4990.7    0.07       0
  4997.7    0.16       0  5123.5    0.05       0
Bank Sta=4972.9,5343.4
Exp/Cntr=0.3,0.1

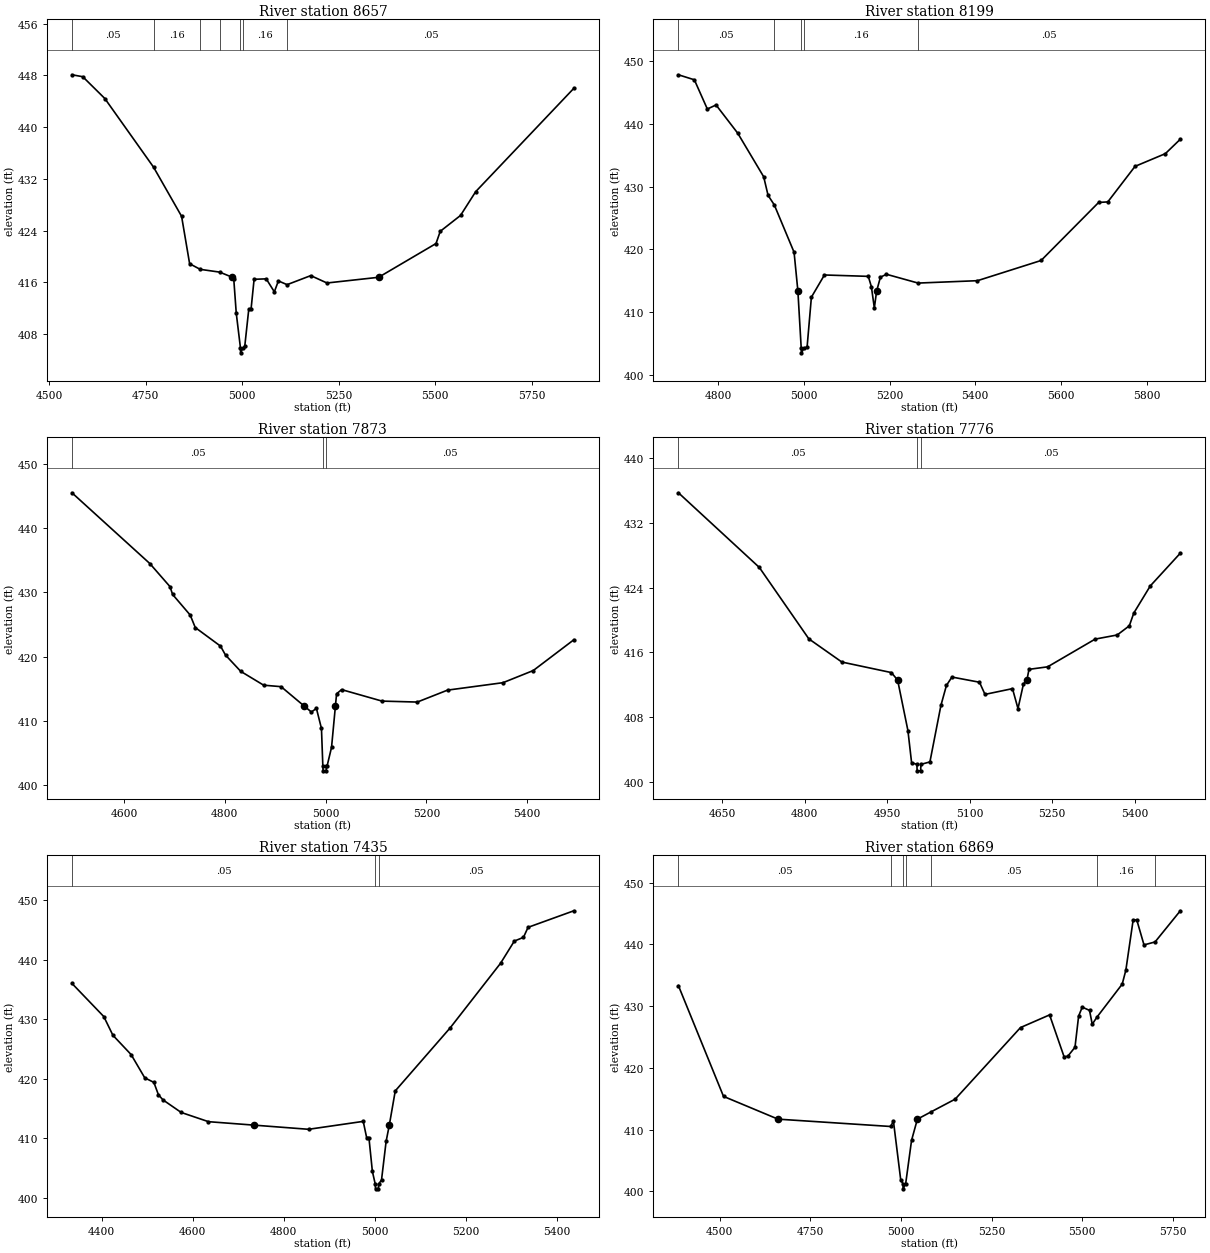
Type RM Length L Ch R = 1,8657,458,458,458
BEGIN DESCRIPTION:
UNT 154 in LFCCL Watershed 13.0
END DESCRIPTION:
XS GIS Cut Line= 3
      2852774.97      7036574.97      2853125.00      7036875.00
      2853375.01      7037675.03
#Sta/Elev= 30
  4559.3  448.08  4587.3  447.78  4644.4  444.41  4770.6  433.79  4843.1  426.20
  4863.9  418.87  4891.2  418.00  4941.7  417.57  4974.6  416.77  4978.1  416.55
  4984.6  411.23  4995.4  405.89  4995.9  405.09  5002.5  405.89  5006.6  406.09
  5017.0  411.83  5022.9  411.83  5030.8  416.46  5062.2  416.53  5083.2  414.52
  5093.7  416.21  5116.2  415.63  5177.5  417.03  5219.4  415.89  5353.1  416.77
  5501.7  421.99  5512.7  423.88  5565.1  426.33  5604.4  430.01  5858.5  445.99
#Mann=7,-1,0
  4559.3    0.05       0  4770.6    0.16       0  4891.2    0.05       0
  4941.7    0.16       0  4995.4    0.07       0  5002.5    0.16       0
  5116.2    0.05       0
Bank Sta=4974.6,5353.1
Exp/Cntr=0.3,0.1

Type RM Length L Ch R = 1,8199,326,326,326
BEGIN DESCRIPTION:
UNT 154 in LFCCL Watershed 12.0
END DESCRIPTION:
XS GIS Cut Line= 3
      2852761.81      7036618.24      2852826.05      7037038.34
      2853366.12      7037553.27
#Sta/Elev= 30
  4707.2  447.84  4744.4  447.04  4774.7  442.38  4795.0  443.03  4845.6  438.53
  4906.2  431.58  4916.4  428.62  4931.0  427.09  4977.1  419.55  4986.0  413.36
  4993.7  404.32  4994.3  403.52  5000.8  404.32  5007.4  404.38  5017.5  412.39
  5047.9  415.93  5150.3  415.71  5157.5  414.06  5164.4  410.67  5169.7  413.36
  5178.6  415.58  5192.7  416.04  5266.5  414.64  5405.0  415.02  5553.5  418.24
  5687.8  427.49  5709.2  427.58  5772.7  433.24  5843.5  435.27  5878.4  437.57
#Mann=5,-1,0
  4707.2    0.05       0  4931.0    0.16       0  4993.7    0.07       0
  5000.8    0.16       0  5266.5    0.05       0
Bank Sta=4986,5169.7
Exp/Cntr=0.3,0.1

Type RM Length L Ch R = 1,7873,97,97,97
BEGIN DESCRIPTION:
XS3887A
END DESCRIPTION:
XS GIS Cut Line= 3
      2852701.05      7036640.75      2852673.27      7037142.51
      2852661.12      7037635.53
#Sta/Elev= 30
  4496.7  445.52  4651.2  434.49  4691.2  430.89  4696.4  429.67  4731.3  426.46
  4741.3  424.52  4791.4  421.62  4801.4  420.22  4831.5  417.69  4877.0  415.53
  4911.6  415.30  4957.1  412.30  4971.7  411.35  4981.7  411.91  4991.7  408.78
  4994.4  402.98  4995.0  402.18  5001.0  402.18  5001.5  402.98  5003.0  402.98
  5011.7  405.85  5019.4  412.30  5021.7  414.19  5031.7  414.84  5111.8  413.05
  5181.8  412.90  5241.8  414.76  5351.8  415.92  5411.8  417.81  5492.4  422.61
#Mann=3,-1,0
  4496.7    0.05       0  4994.4    0.04       0  5001.5    0.05       0
Bank Sta=4957.1,5019.4
Exp/Cntr=0.3,0.1

Type RM Length L Ch R = 1,7776,341,341,341
BEGIN DESCRIPTION:
XS3888A
END DESCRIPTION:
XS GIS Cut Line= 4
      2852567.36      7036737.98      2852579.52      7037163.34
      2852572.57      7037369.94      2852553.48      7037649.44
#Sta/Elev= 30
  4570.5  435.70  4717.6  426.49  4807.6  417.68  4867.6  414.82  4957.7  413.52
  4969.0  412.59  4987.7  406.37  4994.4  402.40  5004.0  402.20  5004.5  401.40
  5010.8  401.40  5011.4  402.20  5027.7  402.50  5047.7  409.47  5057.7  411.93
  5067.7  412.97  5117.8  412.33  5127.8  410.83  5177.8  411.54  5187.8  409.08
  5197.8  412.13  5204.0  412.59  5207.8  413.92  5241.7  414.23  5328.1  417.65
  5368.2  418.16  5390.2  419.29  5398.3  420.86  5428.3  424.21  5482.9  428.25
#Mann=3,-1,0
  4570.5    0.05       0  5004.0    0.03       0  5011.4    0.05       0
Bank Sta=4969,5204
Exp/Cntr=0.3,0.1

Type RM Length L Ch R = 1,7435,566,566,566
BEGIN DESCRIPTION:
UNT 154 in LFCCL Watershed 11.0
END DESCRIPTION:
XS GIS Cut Line= 3
      2852425.00      7036774.97      2852425.00      7037425.00
      2852375.00      7037875.01
#Sta/Elev= 30
  4334.8  436.01  4404.8  430.44  4424.8  427.30  4464.8  424.06  4494.8  420.15
  4514.8  419.39  4524.8  417.31  4534.8  416.45  4574.8  414.34  4634.8  412.79
  4734.7  412.21  4854.8  411.51  4974.8  412.84  4982.3  410.12  4987.3  410.12
  4994.9  404.44  5001.2  402.31  5001.8  401.51  5008.1  401.51  5008.6  402.31
  5015.0  403.00  5025.1  409.48  5032.1  412.21  5045.2  417.96  5165.9  428.55
  5276.6  439.40  5306.8  443.12  5326.9  443.75  5337.0  445.43  5437.6  448.21
#Mann=3,-1,0
  4334.8    0.05       0  5001.2    0.03       0  5008.6    0.05       0
Bank Sta=4734.7,5032.1
Exp/Cntr=0.3,0.1

Type RM Length L Ch R = 1,6869,586,586,586
BEGIN DESCRIPTION:
UNT 154 in LFCCL Watershed 10.0
END DESCRIPTION:
XS GIS Cut Line= 3
      2852275.01      7036824.99      2851975.00      7037325.00
      2851925.00      7038125.03
#Sta/Elev= 30
  4385.9  433.33  4510.3  415.39  4660.7  411.70  4971.9  410.51  4979.0  411.44
  4999.1  401.92  5005.4  401.21  5005.9  400.41  5012.8  401.21  5029.1  408.26
  5045.2  411.70  5083.3  412.89  5149.4  414.94  5329.7  426.54  5409.9  428.59
  5449.9  421.81  5460.0  421.88  5480.0  423.35  5490.0  428.39  5500.0  429.85
  5520.1  429.32  5527.6  427.08  5540.6  428.23  5610.3  433.58  5620.3  435.83
  5640.3  443.90  5650.3  444.01  5670.4  439.93  5700.9  440.41  5770.6  445.46
#Mann=7,-1,0
  4385.9    0.05       0  4971.9    0.16       0  5005.4    0.07       0
  5012.8    0.16       0  5083.3    0.05       0  5540.6    0.16       0
  5700.9    0.05       0
Bank Sta=4660.7,5045.2
Exp/Cntr=0.3,0.1

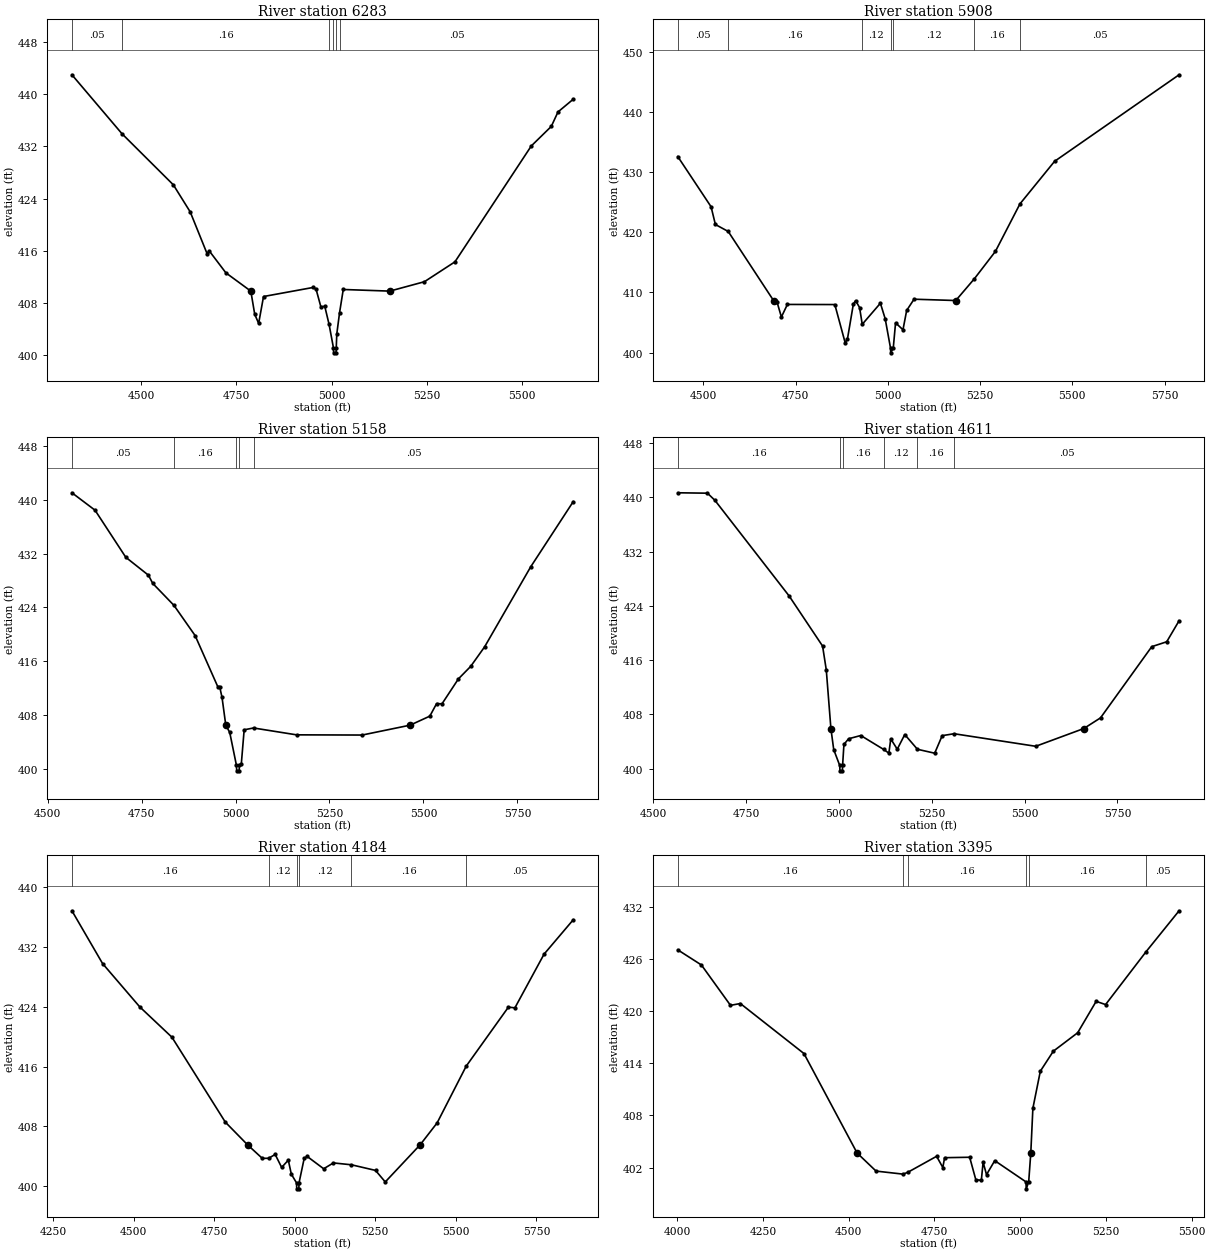
Type RM Length L Ch R = 1,6283,375,375,375
BEGIN DESCRIPTION:
UNT 154 in LFCCL Watershed 9.0
END DESCRIPTION:
XS GIS Cut Line= 3
      2851375.01      7036625.03      2851525.00      7037325.00
      2851575.00      7037924.96
#Sta/Elev= 30
  4317.5  442.99  4449.0  433.95  4584.2  426.10  4628.5  421.95  4672.9  415.53
  4678.0  416.01  4722.3  412.60  4787.8  409.80  4798.1  406.23  4808.4  404.85
  4821.2  408.97  4951.5  410.36  4959.2  410.12  4972.0  407.38  4982.2  407.47
  4993.5  404.70  5004.9  401.13  5005.5  400.33  5011.8  400.33  5012.4  401.13
  5013.8  403.23  5021.1  406.50  5030.8  410.05  5153.1  409.80  5244.1  411.24
  5324.4  414.29  5525.1  432.07  5577.7  435.07  5595.3  437.29  5635.4  439.24
#Mann=6,-1,0
  4317.5    0.05       0  4449.0    0.16       0  4993.5    0.12       0
  5004.9    0.07       0  5012.4    0.12       0  5021.1    0.05       0
Bank Sta=4787.8,5153.1
Exp/Cntr=0.3,0.1

Type RM Length L Ch R = 1,5908,750,750,750
BEGIN DESCRIPTION:
UNT 154 in LFCCL Watershed 8.0
END DESCRIPTION:
XS GIS Cut Line= 3
      2850927.36      7036813.75      2851177.38      7037313.80
      2851127.50      7038111.87
#Sta/Elev= 30
  4430.5  432.56  4520.8  424.22  4532.5  421.27  4567.3  420.11  4690.1  408.64
  4699.7  408.36  4711.4  405.90  4727.6  407.99  4856.2  407.97  4884.2  401.63
  4890.3  402.21  4906.5  408.08  4912.6  408.62  4923.3  407.47  4930.5  404.69
  4979.7  408.19  4992.7  405.61  5007.1  400.75  5007.6  399.95  5014.6  400.75
  5020.8  404.94  5040.9  403.78  5050.9  406.99  5070.9  408.86  5184.0  408.64
  5234.7  412.28  5291.4  416.80  5357.9  424.69  5451.7  431.76  5789.2  446.14
#Mann=7,-1,0
  4430.5    0.05       0  4567.3    0.16       0  4930.5    0.12       0
  5007.1    0.07       0  5014.6    0.12       0  5234.7    0.16       0
  5357.9    0.05       0
Bank Sta=4690.1,5184
Exp/Cntr=0.3,0.1

Type RM Length L Ch R = 1,5158,547,547,547
BEGIN DESCRIPTION:
UNT 154 in LFCCL Watershed 7.0
END DESCRIPTION:
XS GIS Cut Line= 3
      2850525.00      7036775.01      2850625.00      7037225.00
      2850975.01      7038025.02
#Sta/Elev= 30
  4564.5  441.04  4626.0  438.45  4707.9  431.45  4768.1  428.79  4779.6  427.57
  4836.1  424.30  4892.3  419.82  4952.5  412.24  4957.6  412.24  4964.0  410.62
  4974.0  406.49  4984.5  405.42  5002.4  400.51  5003.0  399.71  5009.5  399.71
  5010.2  400.51  5015.2  400.66  5022.9  405.81  5047.8  406.08  5162.3  405.06
  5336.9  405.03  5464.6  406.50  5517.0  407.84  5535.0  409.70  5549.4  409.67
  5593.1  413.38  5625.8  415.24  5662.8  418.14  5785.2  430.01  5898.7  439.73
#Mann=5,-1,0
  4564.5    0.05       0  4836.1    0.16       0  5002.4    0.07       0
  5010.2    0.16       0  5047.8    0.05       0
Bank Sta=4974,5464.6
Exp/Cntr=0.3,0.1

Type RM Length L Ch R = 1,4611,427,427,427
BEGIN DESCRIPTION:
UNT 154 in LFCCL Watershed 6.0
END DESCRIPTION:
XS GIS Cut Line= 3
      2850225.00      7036624.96      2850225.00      7037075.00
      2850336.46      7037968.03
#Sta/Elev= 30
  4566.1  440.66  4646.1  440.60  4666.1  439.55  4866.1  425.44  4956.1  418.06
  4966.1  414.53  4978.5  405.90  4986.1  402.79  5002.2  400.46  5002.9  399.66
  5009.4  399.66  5010.0  400.46  5013.6  403.56  5026.2  404.39  5059.0  404.87
  5120.4  402.82  5134.6  402.27  5139.7  404.37  5157.2  402.85  5177.4  405.01
  5211.5  402.84  5258.0  402.26  5278.2  404.85  5310.3  405.13  5530.1  403.28
  5659.6  405.90  5704.5  407.47  5842.5  417.97  5882.8  418.69  5916.1  421.79
#Mann=6,-1,0
  4566.1    0.16       0  5002.2    0.07       0  5010.0    0.16       0
  5120.4    0.12       0  5211.5    0.16       0  5310.3    0.05       0
Bank Sta=4978.5,5659.6
Exp/Cntr=0.3,0.1

Type RM Length L Ch R = 1,4184,789,789,789
BEGIN DESCRIPTION:
UNT 154 in LFCCL Watershed 5.0
END DESCRIPTION:
XS GIS Cut Line= 3
      2849975.00      7036625.03      2850013.55      7037358.66
      2849925.00      7038175.03
#Sta/Elev= 30
  4308.6  436.79  4403.8  429.74  4518.9  423.97  4619.0  419.91  4784.6  408.58
  4853.6  405.55  4899.4  403.74  4918.9  403.75  4939.4  404.26  4959.5  402.53
  4980.1  403.50  4989.5  401.63  5005.6  400.47  5006.3  399.67  5012.8  399.67
  5013.4  400.47  5029.6  403.77  5038.9  403.99  5089.9  402.35  5120.0  403.13
  5176.2  402.88  5250.8  402.13  5281.0  400.59  5389.3  405.55  5441.9  408.47
  5532.2  416.05  5663.2  423.93  5683.3  423.83  5773.8  431.00  5864.4  435.59
#Mann=6,-1,0
  4308.6    0.16       0  4918.9    0.12       0  5005.6    0.07       0
  5013.4    0.12       0  5176.2    0.16       0  5532.2    0.05       0
Bank Sta=4853.6,5389.3
Exp/Cntr=0.3,0.1

Type RM Length L Ch R = 1,3395,534,534,534
BEGIN DESCRIPTION:
UNT 154 in LFCCL Watershed 4.0
END DESCRIPTION:
XS GIS Cut Line= 3
      2849820.85      7036608.62      2849550.00      7037566.99
      2849774.98      7037974.96
#Sta/Elev= 30
  4001.6  427.02  4070.6  425.28  4155.4  420.64  4184.1  420.85  4369.6  415.10
  4524.5  403.67  4579.8  401.59  4658.7  401.24  4672.8  401.46  4756.4  403.29
  4774.5  402.00  4779.7  403.13  4852.8  403.18  4870.7  400.60  4886.8  400.53
  4892.0  402.61  4901.9  401.18  4925.9  402.79  5017.0  400.35  5017.7  399.55
  5024.9  400.35  5031.0  403.67  5037.1  408.81  5058.8  413.07  5096.7  415.37
  5167.7  417.49  5221.6  421.10  5249.1  420.73  5367.4  426.82  5463.4  431.51
#Mann=6,-1,0
  4001.6    0.16       0  4658.7    0.12       0  4672.8    0.16       0
  5017.0    0.07       0  5024.9    0.16       0  5367.4    0.05       0
Bank Sta=4524.5,5031
Exp/Cntr=0.3,0.1

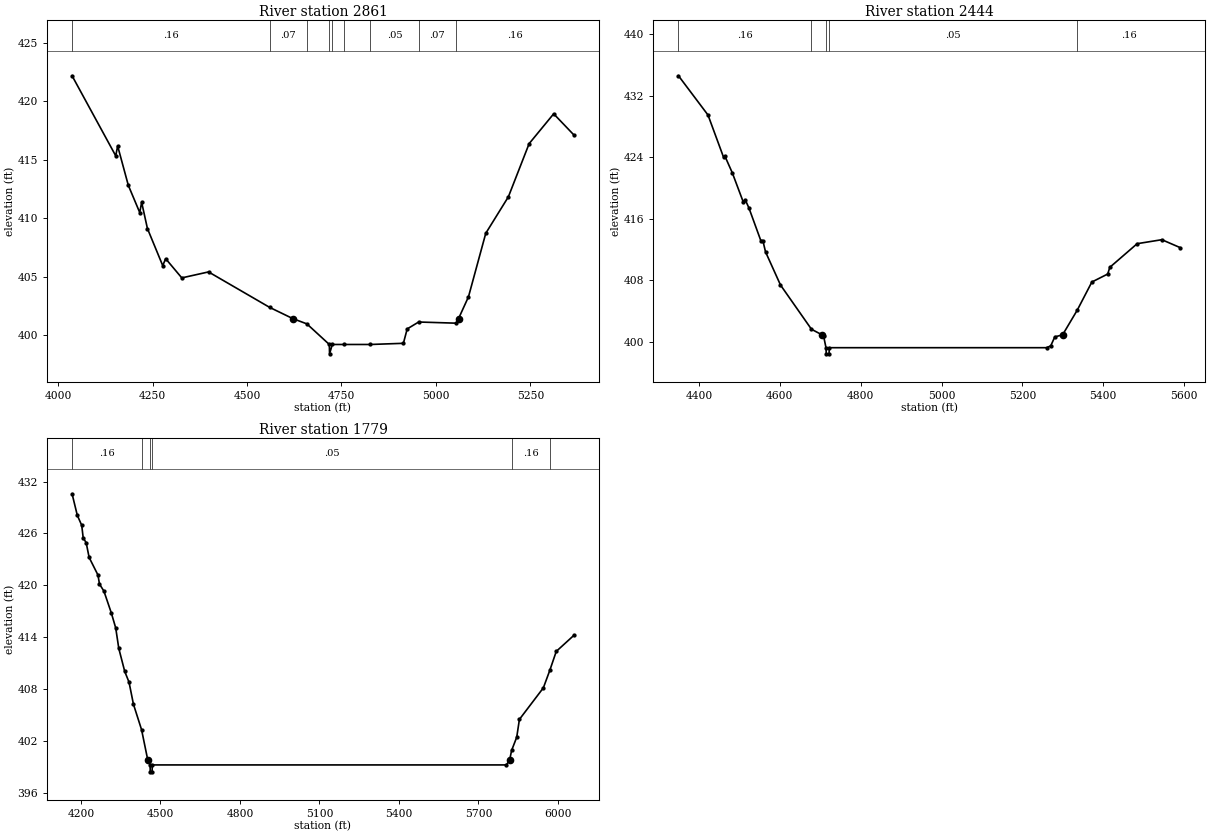
Type RM Length L Ch R = 1,2861,417,417,417
BEGIN DESCRIPTION:
UNT 154 in LFCCL Watershed 3.0
END DESCRIPTION:
XS GIS Cut Line= 3
      2849367.72      7036337.78      2849225.00      7037275.00
      2849289.56      7037650.16
#Sta/Elev= 30
  4036.7  422.17  4152.3  415.33  4157.4  416.17  4185.6  412.81  4215.9  410.48
  4220.9  411.36  4236.2  409.12  4276.7  405.95  4284.5  406.54  4327.2  404.90
  4398.0  405.41  4559.8  402.38  4621.2  401.42  4658.4  400.97  4717.8  399.21
  4718.4  398.41  4725.7  399.21  4757.0  399.21  4826.6  399.21  4913.9  399.31
  4924.0  400.54  4954.3  401.13  5053.6  401.03  5059.9  401.42  5086.2  403.28
  5132.0  408.71  5191.9  411.83  5246.8  416.37  5311.8  418.92  5365.4  417.11
#Mann=9,-1,0
  4036.7    0.16       0  4559.8    0.07       0  4658.4    0.12       0
  4717.8    0.07       0  4725.7    0.12       0  4757.0    0.07       0
  4826.6    0.05       0  4954.3    0.07       0  5053.6    0.16       0
Bank Sta=4621.2,5059.9
Exp/Cntr=0.3,0.1

Type RM Length L Ch R = 1,2444,665,665,665
BEGIN DESCRIPTION:
UNT 154 in LFCCL Watershed 2.0
END DESCRIPTION:
XS GIS Cut Line= 3
      2849025.00      7036424.98      2848883.34      7037061.78
      2848992.70      7037639.86
#Sta/Elev= 30
  4349.7  434.61  4422.7  429.50  4461.1  424.01  4464.8  424.11  4482.9  421.96
  4509.7  418.20  4514.8  418.46  4523.9  417.40  4553.2  413.16  4558.3  413.15
  4564.9  411.69  4601.9  407.37  4678.5  401.61  4704.8  400.88  4708.3  400.77
  4714.4  399.21  4715.1  398.41  4721.9  398.41  4722.6  399.21  5259.8  399.21
  5270.0  399.45  5280.1  400.62  5299.3  400.88  5335.5  404.09  5371.7  407.76
  5410.9  408.80  5416.0  409.67  5483.7  412.75  5544.7  413.27  5590.4  412.23
#Mann=5,-1,0
  4349.7    0.16       0  4678.5    0.05       0  4714.4   0.033       0
  4722.6    0.05       0  5335.5    0.16       0
Bank Sta=4704.8,5299.3
Exp/Cntr=0.3,0.1

Type RM Length L Ch R = 1,1779,0,0,0
BEGIN DESCRIPTION:
UNT 154 in LFCCL Watershed 1.0
END DESCRIPTION:
XS GIS Cut Line= 3
      2848586.47      7036207.60      2848225.00      7036925.00
      2848336.46      7038009.66
#Sta/Elev= 30
  4166.5  430.59  4186.2  428.10  4202.9  426.94  4208.5  425.48  4219.6  424.94
  4230.9  423.22  4264.3  421.18  4269.9  420.14  4286.6  419.33  4314.5  416.81
  4331.2  415.06  4342.8  412.69  4365.2  410.03  4381.4  408.79  4398.1  406.23
  4428.8  403.28  4452.2  399.77  4460.9  399.21  4461.6  398.41  4468.5  398.41
  4469.2  399.21  5805.3  399.21  5817.6  399.77  5825.0  400.88  5844.4  402.42
  5854.5  404.48  5944.9  408.13  5969.5  410.18  5993.6  412.35  6060.2  414.21
#Mann=6,-1,0
  4166.5    0.16       0  4428.8    0.05       0  4460.9   0.033       0
  4469.2    0.05       0  5825.0    0.16       0  5969.5    0.12       0
Bank Sta=4452.2,5817.6
Exp/Cntr=0.3,0.1

Chan Stop Cuts=-1