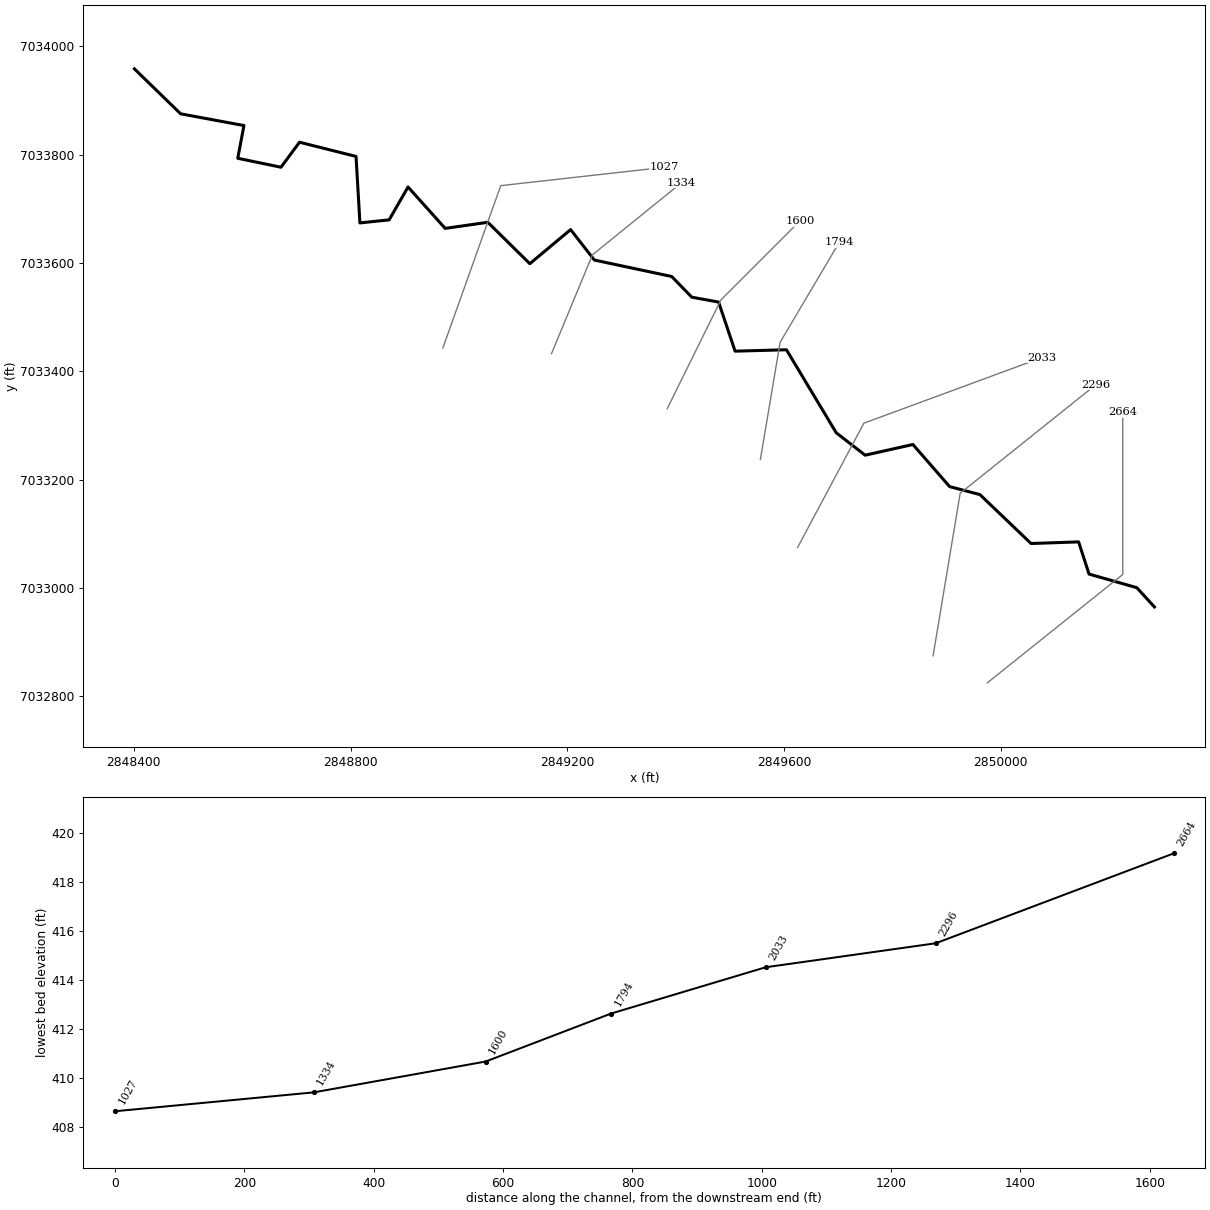
--- UNT 156 in LFCCL Watershed.prj (project) ---

Proj Title=UNT 156 in LFCCL Watershed Base Level Engineering
Current Plan=p01
Default Exp/Contr=0.3,0.1
English Units
Geom File=g01
Flow File=f01
Plan File=p01
BEGIN DESCRIPTION:
UNT 156 in LFCCL Watershed
END DESCRIPTION:

--- UNT 156 in LFCCL Watershed.p01 (plan) ---

Plan Title=Multiple Run
Short Identifier=Multiple
Geom File=g01
Flow File=f01
Subcritical Flow
K Sum by GR= 0
Std Step Tol= 0.01
Critical Tol= 0.01
Num of Std Step Trials= 20
Max Error Tol= 0.3
Flow Tol Ratio= 0.001
Split Flow NTrial= 30
Split Flow Tol= 0.02
Split Flow Ratio= 0.02
Log Output Level= 0
Friction Slope Method= 1
Unsteady Friction Slope Method= 2
Unsteady Bridges Friction Slope Method= 1
Parabolic Critical Depth
Global Vel Dist=  1 , 1 , 1
Global Log Level= 0
CheckData=True
Encroach Param= -1, 0, 0, 0
BEGIN DESCRIPTION:
Multiple Run
END DESCRIPTION:

--- UNT 156 in LFCCL Watershed.f01 (steady flow) ---

Flow Title=Multiple
Number of Profiles=7
Profile Names=10-year,25-year,50-year,1pct_min,100-year,1pct_plu,500-year
River Rch & RM= UNT 156 in LFCCL,Reach-1,2664
     232     293     340     197     393     784     524
Boundary for River Rch & Prof#=UNT 156 in LFCCL,Reach-1,1
Up Type=0
Dn Type=3
Dn Slope=0.005
Boundary for River Rch & Prof#=UNT 156 in LFCCL,Reach-1,2
Up Type=0
Dn Type=3
Dn Slope=0.005
Boundary for River Rch & Prof#=UNT 156 in LFCCL,Reach-1,3
Up Type=0
Dn Type=3
Dn Slope=0.005
Boundary for River Rch & Prof#=UNT 156 in LFCCL,Reach-1,4
Up Type=0
Dn Type=3
Dn Slope=0.005
Boundary for River Rch & Prof#=UNT 156 in LFCCL,Reach-1,5
Up Type=0
Dn Type=3
Dn Slope=0.005
Boundary for River Rch & Prof#=UNT 156 in LFCCL,Reach-1,6
Up Type=0
Dn Type=3
Dn Slope=0.005
Boundary for River Rch & Prof#=UNT 156 in LFCCL,Reach-1,7
Up Type=0
Dn Type=3
Dn Slope=0.005

--- UNT 156 in LFCCL Watershed.g01 (geometry) ---

Geom Title=Existing Conditions

River Reach=UNT 156 in LFCCL,Reach-1
Reach XY= 30
      2850283.44      7032965.13      2850251.01      7033000.62
      2850162.81      7033025.79      2850143.55      7033085.18
      2850055.73      7033082.19      2849961.43      7033172.46
      2849905.45      7033187.22      2849837.78      7033264.92
      2849749.63      7033245.18      2849696.31      7033286.46
      2849604.35      7033439.75      2849509.59      7033437.16
      2849479.15      7033527.75      2849429.70      7033536.74
      2849392.62      7033574.95      2849249.89      7033605.29
      2849206.06      7033661.48      2849130.77      7033598.55
      2849053.23      7033674.97      2848974.56      7033663.73
      2848906.01      7033740.15      2848871.17      7033679.46
      2848817.23      7033673.84      2848810.04      7033796.53
      2848705.76      7033822.75      2848671.57      7033776.59
      2848591.79      7033793.11      2848603.19      7033853.52
      2848486.37      7033875.17      2848401.07      7033958.15

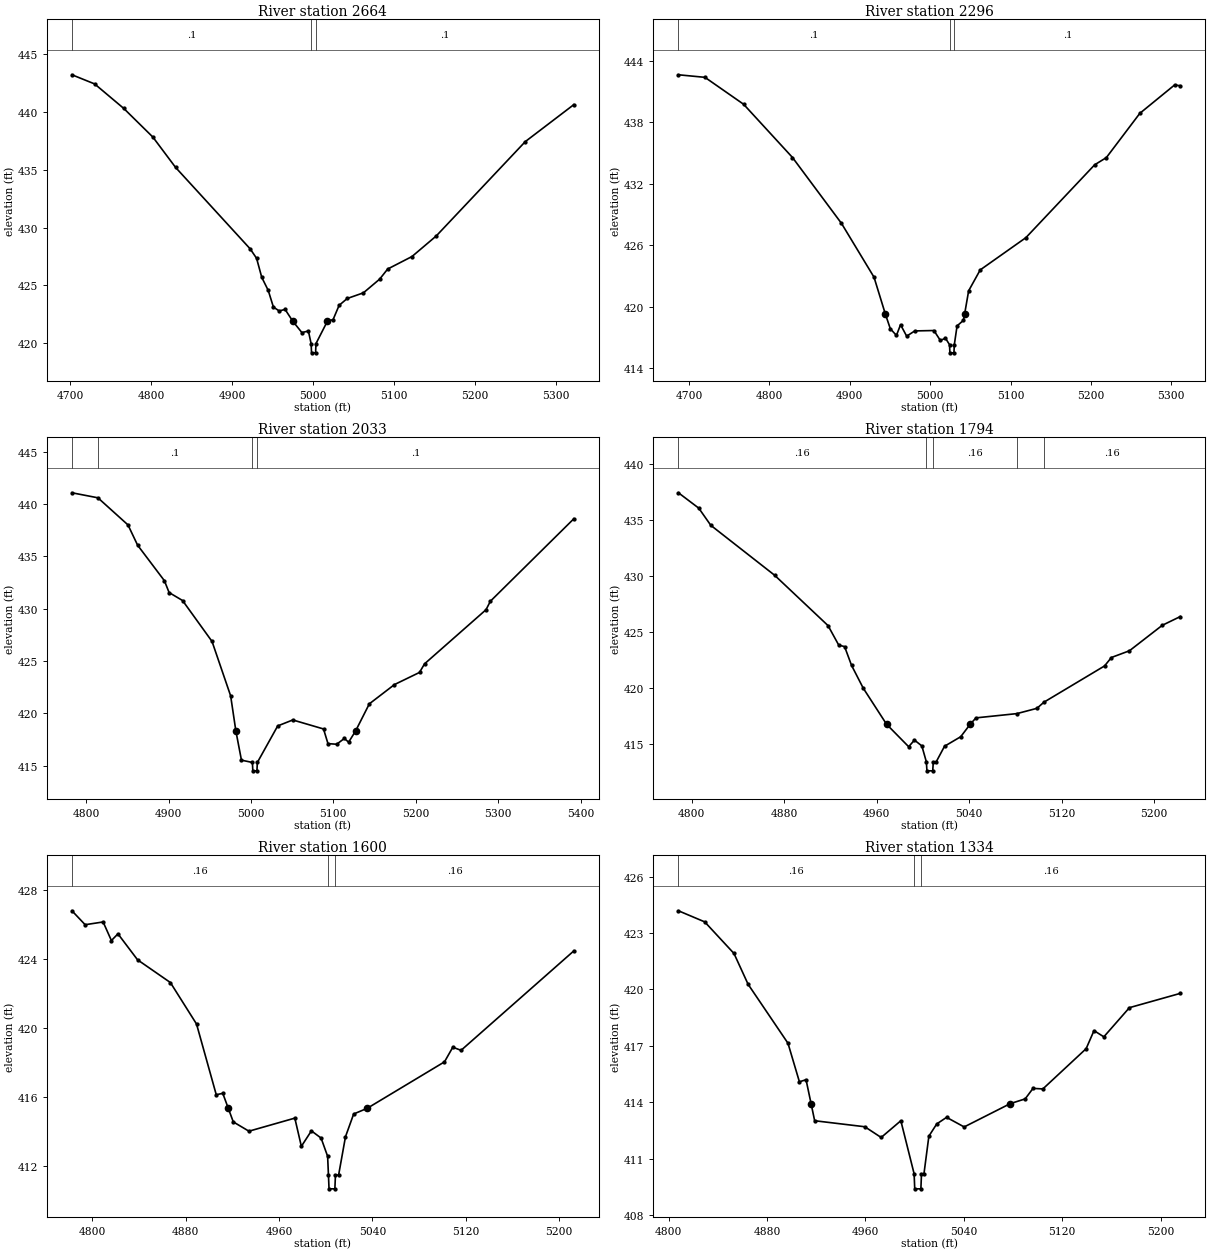
Type RM Length L Ch R = 1,2664,368,368,368
BEGIN DESCRIPTION:
UNT 156 in LFCCL Watershed 4.0
END DESCRIPTION:
XS GIS Cut Line= 3
      2849975.03      7032825.02      2850225.00      7033025.00
      2850225.00      7033324.98
#Sta/Elev= 30
  4702.4  443.21  4730.4  442.42  4766.4  440.30  4802.4  437.82  4830.4  435.20
  4922.5  428.16  4930.5  427.34  4936.9  425.69  4944.9  424.56  4951.3  423.12
  4958.5  422.78  4965.7  422.92  4975.1  421.91  4986.5  420.91  4994.5  421.05
  4997.9  419.96  4998.4  419.16  5003.4  419.16  5003.9  419.96  5018.1  421.91
  5025.0  422.03  5032.5  423.27  5042.5  423.86  5062.5  424.35  5082.5  425.53
  5092.5  426.41  5122.5  427.49  5152.5  429.27  5262.5  437.43  5322.5  440.63
#Mann=3,-1,0
  4702.4     0.1       0  4997.9    0.07       0  5003.9     0.1       0
Bank Sta=4975.1,5018.1
Exp/Cntr=0.3,0.1

Type RM Length L Ch R = 1,2296,263,263,263
BEGIN DESCRIPTION:
UNT 156 in LFCCL Watershed 3.0
END DESCRIPTION:
XS GIS Cut Line= 3
      2849875.00      7032874.99      2849925.00      7033175.00
      2850175.00      7033375.00
#Sta/Elev= 30
  4686.9  442.65  4719.9  442.40  4768.0  439.77  4828.8  434.57  4889.7  428.14
  4930.2  422.88  4944.3  419.28  4950.5  417.84  4958.1  417.19  4963.2  418.24
  4970.8  417.12  4980.9  417.63  5004.7  417.67  5012.7  416.70  5019.1  416.92
  5024.1  416.29  5024.6  415.49  5029.6  415.49  5030.1  416.29  5033.5  418.12
  5041.5  418.67  5042.9  419.28  5047.9  421.55  5062.3  423.59  5119.1  426.74
  5204.7  433.86  5219.2  434.56  5260.8  438.88  5304.0  441.65  5311.2  441.58
#Mann=3,-1,0
  4686.9     0.1       0  5024.1    0.07       0  5030.1     0.1       0
Bank Sta=4944.3,5042.9
Exp/Cntr=0.3,0.1

Type RM Length L Ch R = 1,2033,239,239,239
BEGIN DESCRIPTION:
UNT 156 in LFCCL Watershed 2.0
END DESCRIPTION:
XS GIS Cut Line= 3
      2849625.02      7033075.03      2849747.24      7033304.22
      2850075.04      7033425.02
#Sta/Elev= 30
  4782.8  441.07  4814.3  440.59  4850.8  438.00  4862.5  436.06  4895.0  432.67
  4900.7  431.54  4917.0  430.78  4952.8  426.87  4975.4  421.67  4981.7  418.33
  4988.5  415.53  5001.8  415.31  5002.3  414.51  5007.3  414.51  5007.8  415.31
  5032.5  418.80  5050.8  419.37  5088.1  418.51  5093.5  417.11  5104.1  417.05
  5113.3  417.60  5118.6  417.25  5127.1  418.33  5143.7  420.91  5174.2  422.75
  5204.6  423.91  5210.7  424.73  5285.3  429.90  5290.6  430.71  5391.9  438.59
#Mann=4,-1,0
  4782.8    0.16       0  4814.3     0.1       0  5001.8    0.07       0
  5007.8     0.1       0
Bank Sta=4981.7,5127.1
Exp/Cntr=0.3,0.1

Type RM Length L Ch R = 1,1794,194,194,194
BEGIN DESCRIPTION:
XS3891A
END DESCRIPTION:
XS GIS Cut Line= 3
      2849556.27      7033237.40      2849592.72      7033453.53
      2849702.10      7033638.42
#Sta/Elev= 30
  4788.5  437.40  4806.1  436.03  4816.5  434.50  4871.7  430.05  4917.9  425.56
  4927.1  423.83  4932.2  423.69  4938.2  422.02  4948.3  419.99  4968.5  416.77
  4987.6  414.77  4992.6  415.36  4999.0  414.84  5002.9  413.42  5003.4  412.62
  5008.4  412.62  5008.9  413.42  5011.4  413.42  5018.6  414.81  5032.6  415.66
  5040.8  416.77  5045.8  417.34  5081.2  417.72  5098.5  418.19  5104.6  418.74
  5157.0  421.97  5162.9  422.72  5178.5  423.32  5206.9  425.59  5222.5  426.37
#Mann=5,-1,0
  4788.5    0.16       0  5002.9    0.07       0  5008.9    0.16       0
  5081.2     0.1       0  5104.6    0.16       0
Bank Sta=4968.5,5040.8
Exp/Cntr=0.3,0.1

Type RM Length L Ch R = 1,1600,266,266,266
BEGIN DESCRIPTION:
XS3890A
END DESCRIPTION:
XS GIS Cut Line= 3
      2849384.37      7033331.09      2849483.35      7033531.65
      2849629.18      7033677.49
#Sta/Elev= 30
  4782.7  426.82  4794.0  426.01  4809.4  426.17  4816.5  425.09  4822.1  425.48
  4838.9  423.97  4867.0  422.65  4889.4  420.24  4906.3  416.13  4911.9  416.21
  4916.6  415.34  4920.9  414.55  4934.3  414.01  4973.6  414.77  4979.2  413.13
  4987.8  414.03  4996.1  413.61  5001.7  412.55  5002.4  411.46  5002.9  410.66
  5007.9  410.66  5008.4  411.46  5011.1  411.46  5017.0  413.69  5024.0  415.01
  5035.6  415.34  5101.8  418.04  5108.9  418.89  5116.0  418.71  5212.6  424.49
#Mann=3,-1,0
  4782.7    0.16       0  5002.4    0.07       0  5008.4    0.16       0
Bank Sta=4916.6,5035.6
Exp/Cntr=0.3,0.1

Type RM Length L Ch R = 1,1334,307,307,307
BEGIN DESCRIPTION:
XS3889A
END DESCRIPTION:
XS GIS Cut Line= 3
      2849170.83      7033432.66      2849246.37      7033614.98
      2849410.25      7033747.65
#Sta/Elev= 30
  4807.9  424.18  4829.3  423.59  4853.1  421.91  4864.6  420.27  4897.0  417.14
  4906.3  415.09  4911.7  415.20  4915.8  413.93  4918.7  413.02  4959.5  412.70
  4972.8  412.13  4988.8  413.02  4999.6  410.20  5000.1  409.40  5005.1  409.40
  5005.6  410.20  5007.6  410.20  5011.6  412.20  5018.0  412.85  5026.0  413.20
  5040.3  412.69  5077.8  413.93  5089.9  414.18  5096.3  414.74  5104.3  414.71
  5139.5  416.85  5145.9  417.81  5153.9  417.48  5174.7  419.03  5216.1  419.79
#Mann=3,-1,0
  4807.9    0.16       0  4999.6    0.07       0  5005.6    0.16       0
Bank Sta=4915.8,5077.8
Exp/Cntr=0.3,0.1

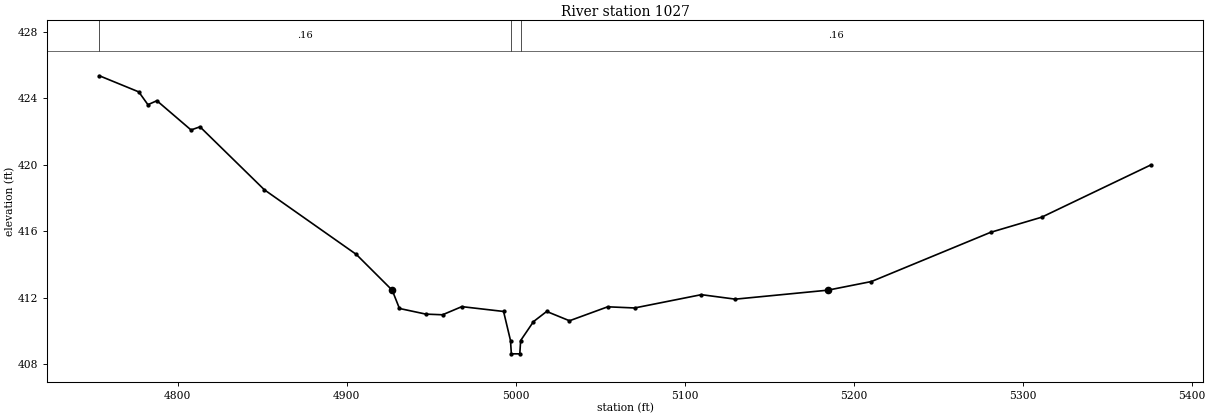
Type RM Length L Ch R = 1,1027,0,0,0
BEGIN DESCRIPTION:
UNT 156 in LFCCL Watershed 1.0
END DESCRIPTION:
XS GIS Cut Line= 3
      2848970.32      7033443.08      2849077.10      7033742.59
      2849379.13      7033776.44
#Sta/Elev= 30
  4753.8  425.36  4777.1  424.39  4782.5  423.62  4787.8  423.86  4808.0  422.10
  4813.3  422.29  4851.4  418.50  4905.8  414.61  4927.0  412.46  4931.3  411.36
  4946.9  411.02  4956.8  410.98  4968.2  411.47  4992.9  411.18  4997.0  409.43
  4997.5  408.63  5002.5  408.63  5003.0  409.43  5010.6  410.57  5018.4  411.18
  5031.9  410.62  5054.5  411.46  5070.4  411.39  5109.9  412.19  5130.0  411.92
  5184.7  412.46  5210.5  412.98  5281.0  415.94  5311.2  416.85  5375.7  419.99
#Mann=3,-1,0
  4753.8    0.16       0  4997.0    0.07       0  5003.0    0.16       0
Bank Sta=4927,5184.7
Exp/Cntr=0.3,0.1

Chan Stop Cuts=-1