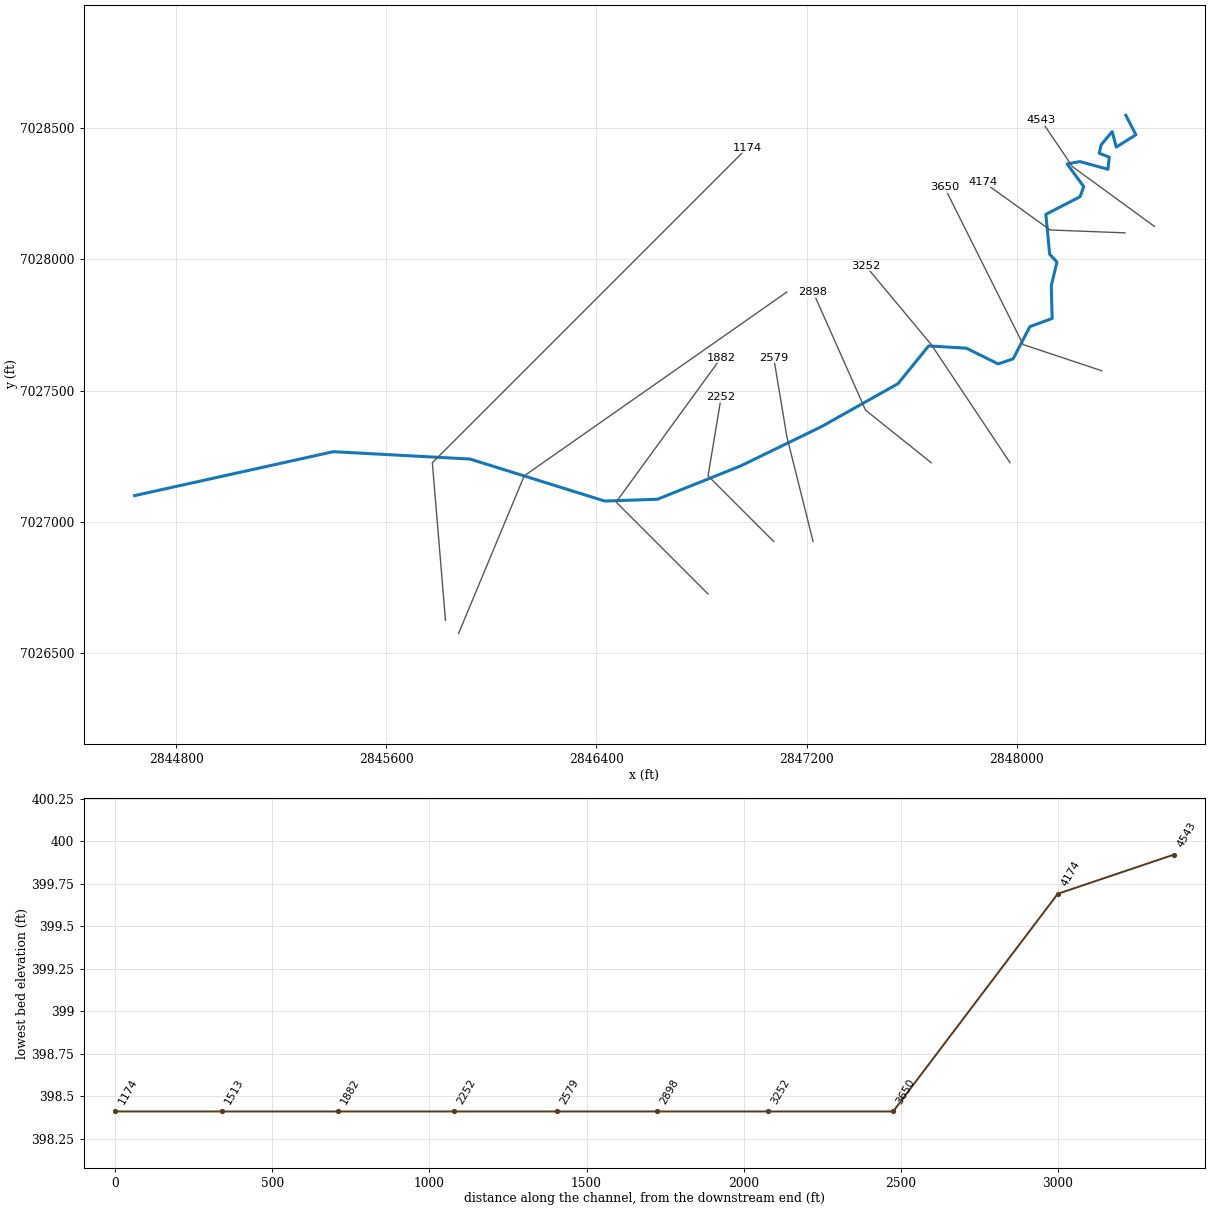
--- UNT 157 in LFCCL Watershed.prj (project) ---

Proj Title=UNT 157 in LFCCL Watershed Base Level Engineering
Current Plan=p01
Default Exp/Contr=0.3,0.1
English Units
Geom File=g01
Flow File=f01
Plan File=p01
BEGIN DESCRIPTION:
UNT 157 in LFCCL Watershed
END DESCRIPTION:

--- UNT 157 in LFCCL Watershed.p01 (plan) ---

Plan Title=Multiple Run
Short Identifier=Multiple
Geom File=g01
Flow File=f01
Subcritical Flow
K Sum by GR= 0
Std Step Tol= 0.01
Critical Tol= 0.01
Num of Std Step Trials= 20
Max Error Tol= 0.3
Flow Tol Ratio= 0.001
Split Flow NTrial= 30
Split Flow Tol= 0.02
Split Flow Ratio= 0.02
Log Output Level= 0
Friction Slope Method= 1
Unsteady Friction Slope Method= 2
Unsteady Bridges Friction Slope Method= 1
Parabolic Critical Depth
Global Vel Dist=  1 , 1 , 1
Global Log Level= 0
CheckData=True
Encroach Param= -1, 0, 0, 0
BEGIN DESCRIPTION:
Multiple Run
END DESCRIPTION:

--- UNT 157 in LFCCL Watershed.f01 (steady flow) ---

Flow Title=Multiple
Number of Profiles=7
Profile Names=10-year,25-year,50-year,1pct_min,100-year,1pct_plu,500-year
River Rch & RM= UNT 157 in LFCCL,Reach-1,4543
     375     490     580     343     684    1365     950
River Rch & RM= UNT 157 in LFCCL,Reach-1,4174
     545     724     867     517    1031    2056    1458
Boundary for River Rch & Prof#=UNT 157 in LFCCL,Reach-1,1
Up Type=0
Dn Type=3
Dn Slope=0.005
Boundary for River Rch & Prof#=UNT 157 in LFCCL,Reach-1,2
Up Type=0
Dn Type=3
Dn Slope=0.005
Boundary for River Rch & Prof#=UNT 157 in LFCCL,Reach-1,3
Up Type=0
Dn Type=3
Dn Slope=0.005
Boundary for River Rch & Prof#=UNT 157 in LFCCL,Reach-1,4
Up Type=0
Dn Type=3
Dn Slope=0.005
Boundary for River Rch & Prof#=UNT 157 in LFCCL,Reach-1,5
Up Type=0
Dn Type=3
Dn Slope=0.005
Boundary for River Rch & Prof#=UNT 157 in LFCCL,Reach-1,6
Up Type=0
Dn Type=3
Dn Slope=0.005
Boundary for River Rch & Prof#=UNT 157 in LFCCL,Reach-1,7
Up Type=0
Dn Type=3
Dn Slope=0.005

--- UNT 157 in LFCCL Watershed.g01 (geometry) ---

Geom Title=Existing Conditions

River Reach=UNT 157 in LFCCL,Reach-1
Reach XY= 30
      2848416.06      7028548.38      2848454.42      7028474.05
      2848379.61      7028427.06      2848364.27      7028486.04
      2848322.07      7028435.69      2848314.88      7028403.56
      2848353.24      7028388.70      2848347.97      7028342.66
      2848241.51      7028371.91      2848192.60      7028362.80
      2848255.90      7028276.49      2848241.99      7028238.13
      2848111.56      7028170.99      2848125.95      7028018.98
      2848153.76      7027989.25      2848132.18      7027899.58
      2848135.54      7027774.43      2848050.66      7027743.26
      2847986.88      7027620.50      2847929.82      7027601.32
      2847808.50      7027661.26      2847665.12      7027669.89
      2847548.43      7027526.06      2847255.52      7027361.62
      2846948.92      7027212.60      2846632.04      7027085.85
      2846431.63      7027079.00      2845918.14      7027239.03
      2845397.65      7027267.01      2844640.75      7027099.66

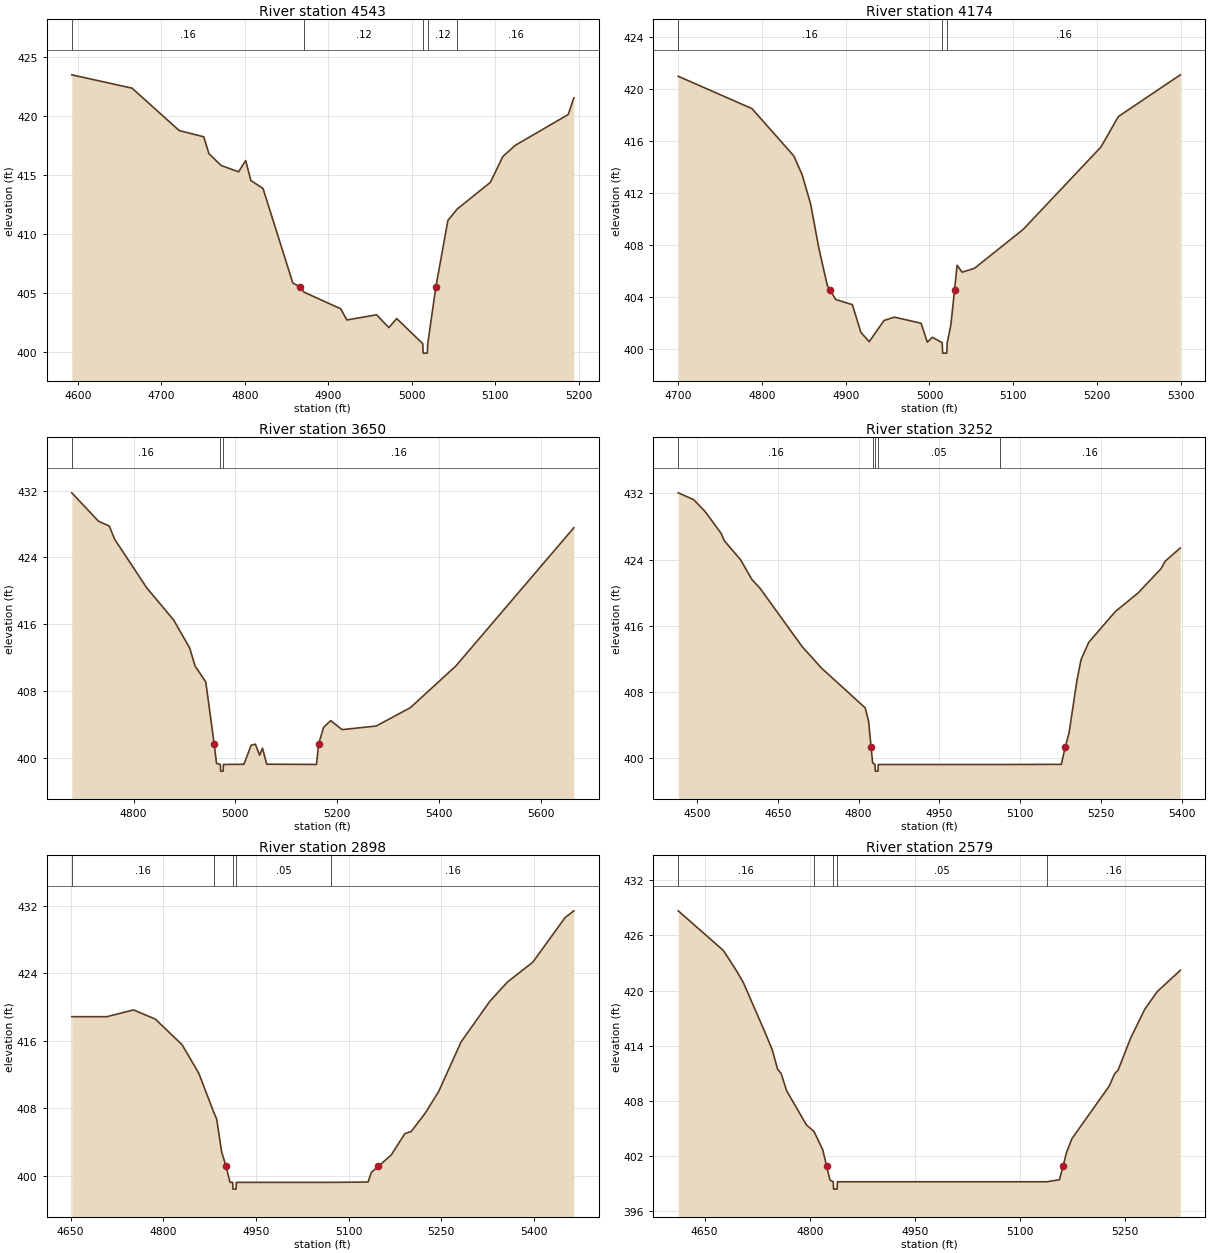
Type RM Length L Ch R = 1,4543,369,369,369
BEGIN DESCRIPTION:
UNT 157 in LFCCL Watershed 10.0
END DESCRIPTION:
XS GIS Cut Line= 3
      2848525.01      7028125.00      2848212.79      7028352.81
      2848092.49      7028530.52
#Sta/Elev= 30
  4592.9  423.50  4665.1  422.37  4721.5  418.78  4750.9  418.25  4757.1  416.82
  4771.7  415.82  4792.6  415.28  4801.1  416.24  4807.3  414.55  4821.9  413.87
  4857.5  405.87  4866.2  405.52  4871.1  405.08  4914.8  403.68  4922.3  402.73
  4957.9  403.17  4972.5  402.08  4981.9  402.85  5013.1  400.72  5013.6  399.92
  5018.6  399.92  5019.1  400.72  5028.8  405.52  5043.2  411.16  5054.4  412.13
  5094.1  414.39  5109.0  416.58  5124.0  417.53  5187.3  420.14  5194.0  421.55
#Mann=5,-1,0
  4592.9    0.16       0  4871.1    0.12       0  5013.1    0.07       0
  5019.1    0.12       0  5054.4    0.16       0
Bank Sta=4866.2,5028.8
Exp/Cntr=0.3,0.1

Type RM Length L Ch R = 1,4174,524,524,524
BEGIN DESCRIPTION:
XS3892A
END DESCRIPTION:
XS GIS Cut Line= 3
      2848412.99      7028100.45      2848127.75      7028111.42
      2847872.62      7028295.23
#Sta/Elev= 30
  4699.8  421.00  4787.9  418.51  4837.9  414.87  4847.9  413.41  4857.9  411.19
  4867.9  407.74  4877.9  404.91  4880.9  404.58  4887.9  403.82  4907.9  403.42
  4918.0  401.29  4928.0  400.57  4945.6  402.20  4958.0  402.46  4990.0  401.99
  4997.4  400.53  5003.5  400.91  5015.2  400.49  5015.7  399.69  5020.7  399.69
  5021.2  400.49  5025.6  401.88  5030.0  404.58  5033.0  406.45  5039.1  405.92
  5053.8  406.22  5111.9  409.21  5204.8  415.55  5225.7  417.90  5299.7  421.11
#Mann=3,-1,0
  4699.8    0.16       0  5015.2    0.07       0  5021.2    0.16       0
Bank Sta=4880.9,5030
Exp/Cntr=0.3,0.1

Type RM Length L Ch R = 1,3650,398,398,398
BEGIN DESCRIPTION:
UNT 157 in LFCCL Watershed 8.0
END DESCRIPTION:
XS GIS Cut Line= 3
      2848324.96      7027575.01      2848025.00      7027675.00
      2847725.00      7028275.00
#Sta/Elev= 30
  4678.4  431.74  4731.1  428.33  4752.1  427.77  4762.7  426.18  4825.9  420.35
  4878.6  416.52  4910.3  413.15  4920.8  411.00  4941.9  409.08  4958.3  401.68
  4963.0  399.33  4970.5  399.21  4971.0  398.41  4976.0  398.41  4976.5  399.21
  5016.9  399.23  5030.9  401.50  5039.3  401.64  5047.7  400.32  5053.3  401.16
  5061.7  399.24  5159.5  399.21  5163.7  401.68  5173.5  403.66  5187.4  404.46
  5209.8  403.38  5276.9  403.81  5344.0  406.01  5433.4  411.00  5665.4  427.56
#Mann=3,-1,0
  4678.4    0.16       0  4970.5    0.07       0  4976.5    0.16       0
Bank Sta=4958.3,5163.7
Exp/Cntr=0.3,0.1

Type RM Length L Ch R = 1,3252,354,354,354
BEGIN DESCRIPTION:
UNT 157 in LFCCL Watershed 7.0
END DESCRIPTION:
XS GIS Cut Line= 3
      2847975.01      7027224.99      2847675.00      7027675.00
      2847424.97      7027975.03
#Sta/Elev= 30
  4465.5  432.08  4494.1  431.26  4515.1  429.84  4545.1  427.17  4551.1  426.28
  4581.2  423.98  4602.2  421.59  4617.2  420.54  4695.4  413.47  4731.4  410.87
  4812.5  406.05  4818.6  404.44  4823.2  401.33  4826.2  399.40  4830.6  399.21
  4831.1  398.41  4836.1  398.41  4836.6  399.21  5061.8  399.21  5176.2  399.23
  5183.4  401.33  5190.5  403.02  5204.9  409.29  5212.7  411.89  5227.0  413.99
  5276.4  417.72  5318.8  419.98  5361.1  422.90  5368.9  423.81  5396.9  425.41
#Mann=5,-1,0
  4465.5    0.16       0  4826.2    0.05       0  4830.6   0.033       0
  4836.6    0.05       0  5061.8    0.16       0
Bank Sta=4823.2,5183.4
Exp/Cntr=0.3,0.1

Type RM Length L Ch R = 1,2898,319,319,319
BEGIN DESCRIPTION:
UNT 157 in LFCCL Watershed 6.0
END DESCRIPTION:
XS GIS Cut Line= 3
      2847675.02      7027224.98      2847425.00      7027425.00
      2847225.01      7027874.98
#Sta/Elev= 30
  4652.0  418.84  4708.9  418.84  4752.1  419.64  4787.3  418.55  4830.5  415.52
  4857.7  412.12  4881.5  407.57  4886.5  406.72  4894.5  402.85  4901.7  401.11
  4908.1  399.22  4912.4  399.21  4912.9  398.41  4917.9  398.41  4918.4  399.21
  5071.7  399.21  5131.5  399.25  5137.0  400.40  5148.2  401.11  5169.2  402.47
  5191.0  404.98  5201.3  405.24  5223.9  407.39  5245.8  409.97  5282.0  415.84
  5328.5  420.65  5357.2  422.95  5398.3  425.30  5450.3  430.57  5464.6  431.38
#Mann=5,-1,0
  4652.0    0.16       0  4881.5    0.05       0  4912.4   0.033       0
  4918.4    0.05       0  5071.7    0.16       0
Bank Sta=4901.7,5148.2
Exp/Cntr=0.3,0.1

Type RM Length L Ch R = 1,2579,327,327,327
BEGIN DESCRIPTION:
UNT 157 in LFCCL Watershed 5.0
END DESCRIPTION:
XS GIS Cut Line= 3
      2847225.01      7026924.96      2847125.00      7027325.00
      2847075.00      7027625.01
#Sta/Elev= 30
  4612.3  428.68  4676.8  424.36  4694.8  422.24  4705.1  420.90  4736.0  415.49
  4746.3  413.60  4754.1  411.46  4759.2  410.98  4767.0  409.10  4795.3  405.39
  4806.1  404.68  4818.5  402.69  4824.2  400.88  4828.8  399.39  4833.5  399.21
  4834.0  398.41  4839.0  398.41  4839.5  399.21  5138.5  399.21  5156.4  399.44
  5161.3  400.88  5166.6  402.44  5174.2  403.91  5227.4  409.62  5235.0  410.96
  5240.1  411.37  5257.8  414.81  5278.1  417.98  5295.8  419.89  5328.8  422.21
#Mann=5,-1,0
  4612.3    0.16       0  4806.1    0.05       0  4833.5   0.033       0
  4839.5    0.05       0  5138.5    0.16       0
Bank Sta=4824.2,5161.3
Exp/Cntr=0.3,0.1

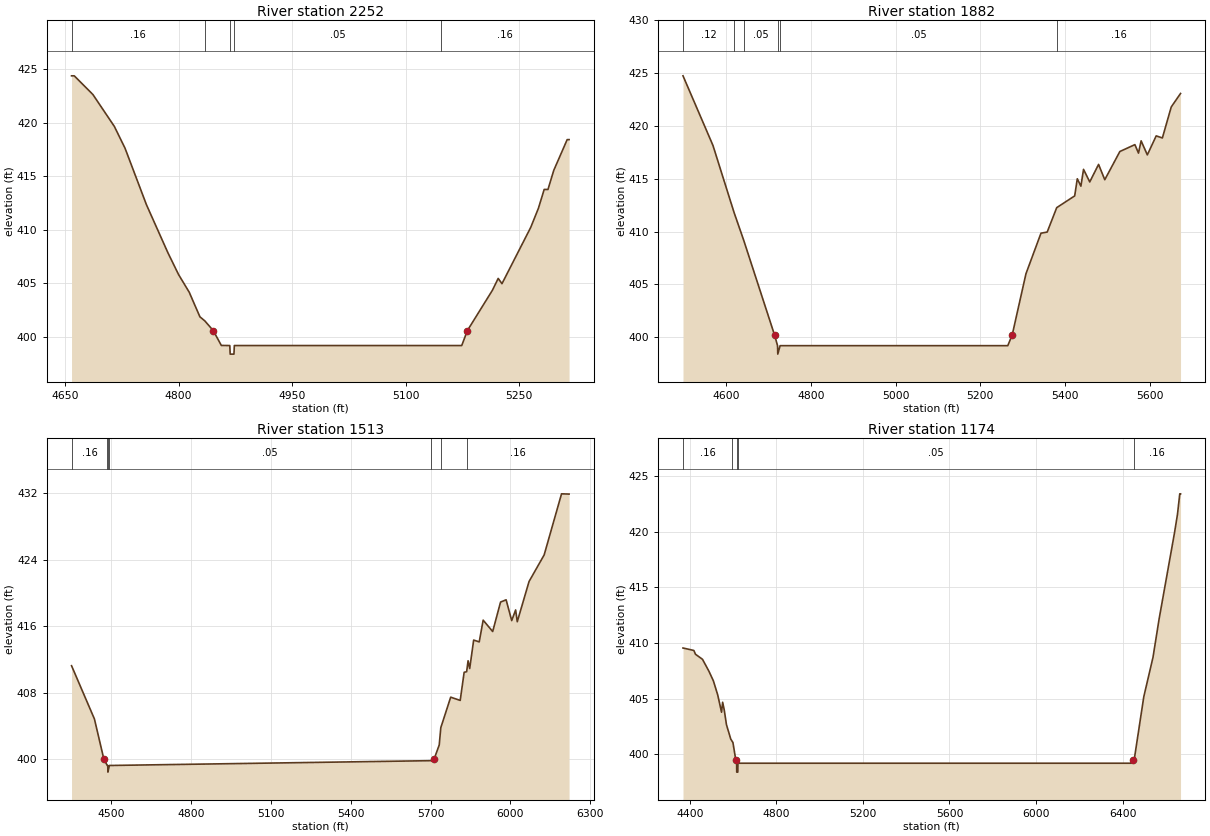
Type RM Length L Ch R = 1,2252,370,370,370
BEGIN DESCRIPTION:
UNT 157 in LFCCL Watershed 4.0
END DESCRIPTION:
XS GIS Cut Line= 3
      2847075.03      7026924.97      2846825.00      7027175.00
      2846875.00      7027474.97
#Sta/Elev= 30
  4658.5  424.37  4662.1  424.37  4686.8  422.62  4715.1  419.65  4729.2  417.62
  4757.5  412.35  4785.8  407.88  4800.0  405.83  4814.1  404.18  4828.2  401.89
  4834.7  401.51  4845.8  400.61  4856.5  399.22  4867.7  399.21  4868.2  398.41
  4873.2  398.41  4873.7  399.21  5146.6  399.21  5174.3  399.21  5181.8  400.61
  5214.8  404.36  5222.5  405.47  5227.5  404.98  5265.5  410.23  5275.7  412.02
  5283.3  413.77  5288.3  413.77  5296.0  415.56  5313.7  418.42  5316.2  418.42
#Mann=5,-1,0
  4658.5    0.16       0  4834.7    0.05       0  4867.7   0.033       0
  4873.7    0.05       0  5146.6    0.16       0
Bank Sta=4845.8,5181.8
Exp/Cntr=0.3,0.1

Type RM Length L Ch R = 1,1882,369,369,369
BEGIN DESCRIPTION:
UNT 157 in LFCCL Watershed 3.0
END DESCRIPTION:
XS GIS Cut Line= 3
      2846824.99      7026725.01      2846475.00      7027075.00
      2846874.98      7027624.98
#Sta/Elev= 30
  4498.1  424.74  4568.8  418.16  4618.6  411.82  4641.4  409.19  4714.2  400.23
  4721.4  399.21  4721.9  398.41  4727.4  399.21  5265.1  399.21  5275.6  400.23
  5308.0  406.01  5343.5  409.85  5358.2  409.96  5380.7  412.27  5423.1  413.38
  5429.3  415.00  5437.8  414.30  5444.0  415.89  5458.7  414.70  5479.5  416.36
  5494.2  414.91  5529.8  417.58  5565.3  418.23  5573.8  417.43  5580.0  418.59
  5594.7  417.26  5615.6  419.06  5630.2  418.86  5651.1  421.79  5673.1  423.07
#Mann=6,-1,0
  4498.1    0.12       0  4618.6    0.16       0  4641.4    0.05       0
  4721.4   0.033       0  4727.4    0.05       0  5380.7    0.16       0
Bank Sta=4714.2,5275.6
Exp/Cntr=0.3,0.1

Type RM Length L Ch R = 1,1513,339,339,339
BEGIN DESCRIPTION:
UNT 157 in LFCCL Watershed 2.0
END DESCRIPTION:
XS GIS Cut Line= 3
      2845875.00      7026575.01      2846125.00      7027175.00
      2847124.96      7027874.97
#Sta/Elev= 30
  4350.0  411.23  4436.1  404.81  4471.6  399.96  4484.4  399.21  4486.2  399.21
  4486.7  398.41  4492.2  399.21  5700.1  399.79  5712.9  399.96  5732.4  401.68
  5738.4  403.77  5775.5  407.44  5811.3  407.05  5826.1  410.44  5835.5  410.51
  5840.9  411.83  5847.0  410.89  5861.9  414.32  5882.8  414.10  5897.6  416.72
  5933.4  415.35  5963.0  418.90  5983.9  419.17  6004.9  416.67  6019.7  417.95
  6025.8  416.53  6070.2  421.38  6126.9  424.58  6192.3  431.94  6220.6  431.91
#Mann=7,-1,0
  4350.0    0.16       0  4484.4    0.05       0  4486.2   0.033       0
  4492.2    0.05       0  5700.1    0.16       0  5738.4    0.05       0
  5835.5    0.16       0
Bank Sta=4471.6,5712.9
Exp/Cntr=0.3,0.1

Type RM Length L Ch R = 1,1174,0,0,0
BEGIN DESCRIPTION:
UNT 157 in LFCCL Watershed 1.0
END DESCRIPTION:
XS GIS Cut Line= 3
      2845825.00      7026625.04      2845775.00      7027225.00
      2846975.00      7028425.00
#Sta/Elev= 30
  4368.8  409.56  4418.9  409.34  4426.5  409.00  4459.1  408.54  4489.2  407.45
  4509.2  406.61  4529.3  405.34  4546.9  403.79  4551.9  404.69  4559.4  403.99
  4569.5  402.68  4589.5  401.38  4595.9  401.18  4599.6  401.06  4612.7  399.51
  4616.6  399.21  4617.1  398.41  4622.1  398.41  4622.6  399.21  6441.6  399.21
  6449.2  399.52  6451.1  399.59  6455.8  399.78  6498.2  405.19  6540.6  408.72
  6568.9  412.17  6639.6  419.86  6653.8  421.57  6664.4  423.41  6667.9  423.41
#Mann=5,-1,0
  4368.8    0.16       0  4595.9    0.05       0  4616.6   0.033       0
  4622.6    0.05       0  6451.1    0.16       0
Bank Sta=4612.7,6449.2
Exp/Cntr=0.3,0.1

Chan Stop Cuts=-1