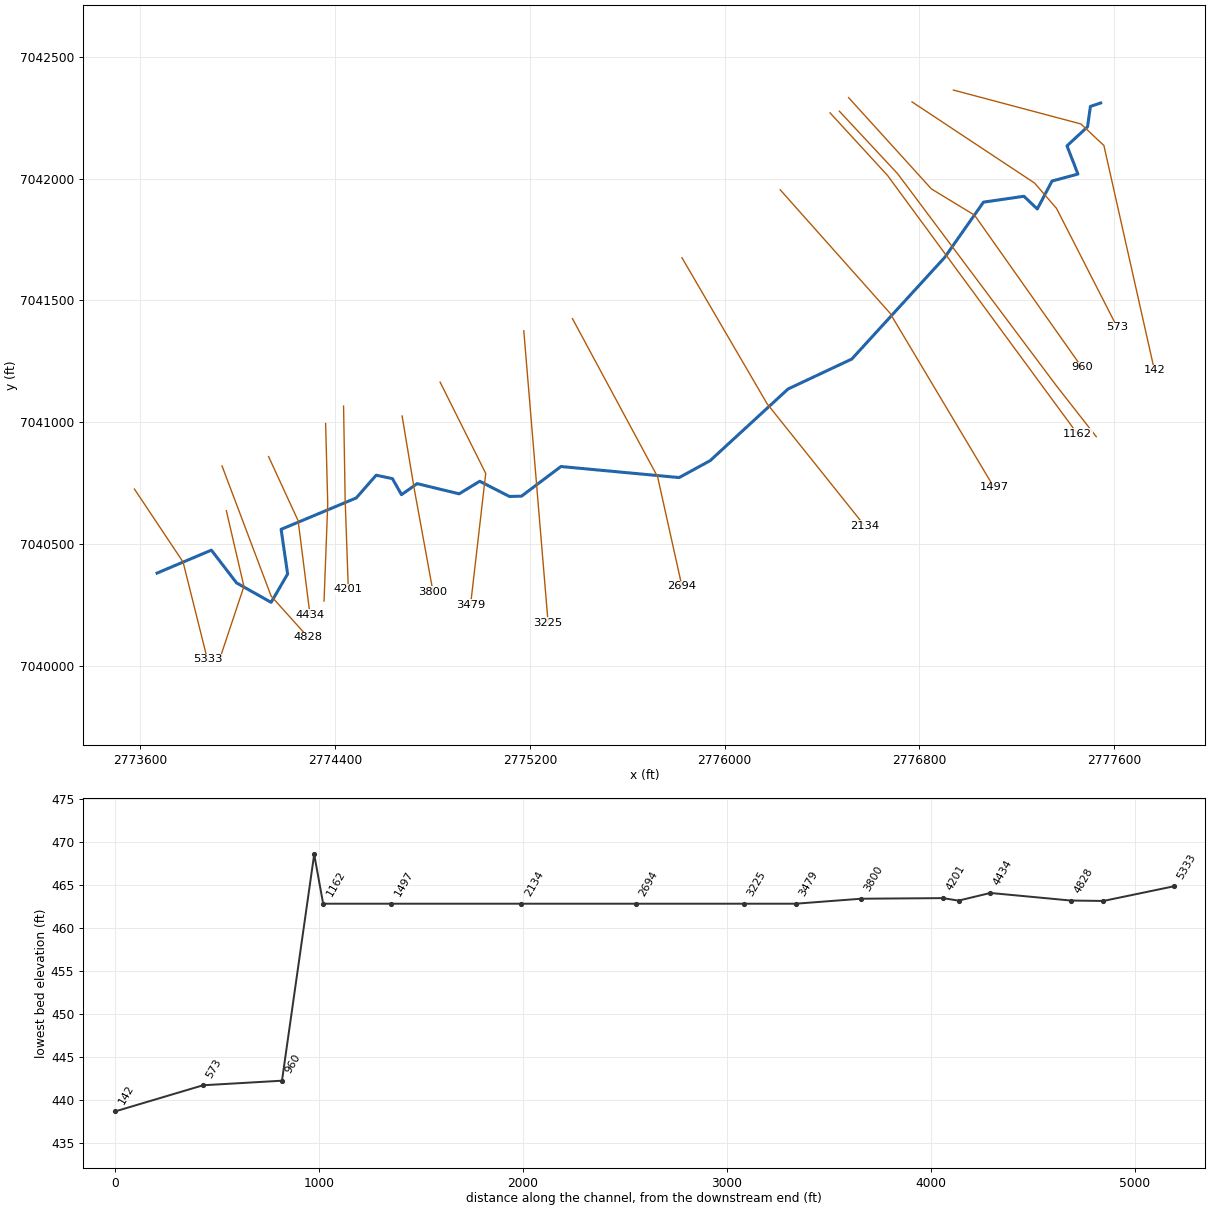
--- UNT 160 in LFCCL Watershed.prj (project) ---

Proj Title=UNT 160 in LFCCL Watershed Base Level Engineering
Current Plan=p01
Default Exp/Contr=0.3,0.1
English Units
Geom File=g01
Flow File=f01
Plan File=p01
BEGIN DESCRIPTION:
UNT 160 in LFCCL Watershed
END DESCRIPTION:

--- UNT 160 in LFCCL Watershed.p01 (plan) ---

Plan Title=Multiple Run
Short Identifier=Multiple
Geom File=g01
Flow File=f01
Subcritical Flow
K Sum by GR= 0
Std Step Tol= 0.01
Critical Tol= 0.01
Num of Std Step Trials= 20
Max Error Tol= 0.3
Flow Tol Ratio= 0.001
Split Flow NTrial= 30
Split Flow Tol= 0.02
Split Flow Ratio= 0.02
Log Output Level= 0
Friction Slope Method= 1
Unsteady Friction Slope Method= 2
Unsteady Bridges Friction Slope Method= 1
Parabolic Critical Depth
Global Vel Dist=  1 , 1 , 1
Global Log Level= 0
CheckData=True
Encroach Param= -1, 0, 0, 0
BEGIN DESCRIPTION:
Multiple Run
END DESCRIPTION:

--- UNT 160 in LFCCL Watershed.f01 (steady flow) ---

Flow Title=Multiple
Number of Profiles=7
Profile Names=10-year,25-year,50-year,1pct_min,100-year,1pct_plu,500-year
River Rch & RM= UNT 160 in LFCCL,Reach-1,5333
     517     689     828     495     987    1970    1405
River Rch & RM= UNT 160 in LFCCL,Reach-1,4988
     589     788     949     568    1133    2262    1620
Boundary for River Rch & Prof#=UNT 160 in LFCCL,Reach-1,1
Up Type=0
Dn Type=3
Dn Slope=0.005
Boundary for River Rch & Prof#=UNT 160 in LFCCL,Reach-1,2
Up Type=0
Dn Type=3
Dn Slope=0.005
Boundary for River Rch & Prof#=UNT 160 in LFCCL,Reach-1,3
Up Type=0
Dn Type=3
Dn Slope=0.005
Boundary for River Rch & Prof#=UNT 160 in LFCCL,Reach-1,4
Up Type=0
Dn Type=3
Dn Slope=0.005
Boundary for River Rch & Prof#=UNT 160 in LFCCL,Reach-1,5
Up Type=0
Dn Type=3
Dn Slope=0.005
Boundary for River Rch & Prof#=UNT 160 in LFCCL,Reach-1,6
Up Type=0
Dn Type=3
Dn Slope=0.005
Boundary for River Rch & Prof#=UNT 160 in LFCCL,Reach-1,7
Up Type=0
Dn Type=3
Dn Slope=0.005

--- UNT 160 in LFCCL Watershed.g01 (geometry) ---

Geom Title=Existing Conditions

River Reach=UNT 160 in LFCCL,Reach-1
Reach XY= 30
      2773667.93      7040379.61      2773891.29      7040473.94
      2773994.52      7040339.56      2774136.90      7040259.47
      2774204.53      7040376.05      2774177.84      7040559.37
      2774486.63      7040688.40      2774568.50      7040781.84
      2774635.24      7040767.60      2774672.62      7040701.75
      2774736.69      7040747.13      2774909.33      7040705.31
      2774993.87      7040756.92      2775115.78      7040694.63
      2775165.62      7040695.52      2775327.58      7040817.43
      2775813.46      7040772.05      2775940.71      7040841.46
      2776261.07      7041136.02      2776522.70      7041258.82
      2776904.88      7041676.70      2777063.97      7041903.41
      2777230.16      7041927.54      2777285.11      7041875.37
      2777345.71      7041990.11      2777452.14      7042018.79
      2777407.16      7042134.65      2777491.65      7042212.91
      2777503.32      7042296.68      2777545.59      7042310.71

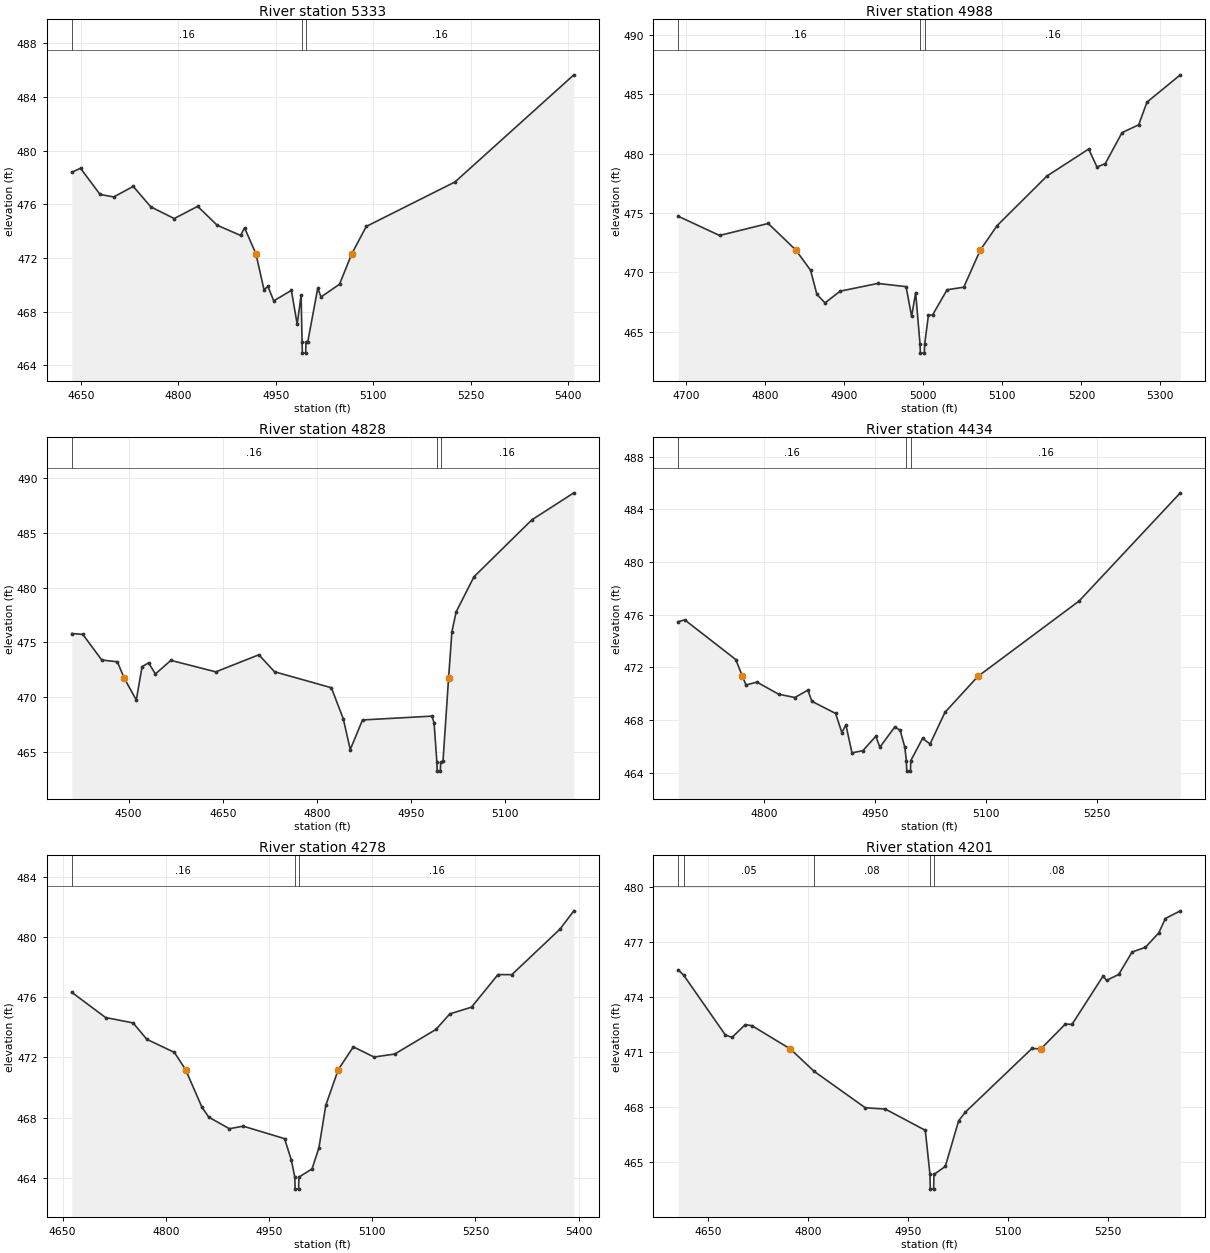
Type RM Length L Ch R = 1,5333,345,345,345
BEGIN DESCRIPTION:
UNT 160 in LFCCL Watershed 9.0
END DESCRIPTION:
XS GIS Cut Line= 3
      2773575.02      7040724.97      2773775.00      7040425.00
      2773874.99      7040025.03
#Sta/Elev= 30
  4635.9  478.39  4649.4  478.69  4679.4  476.74  4700.5  476.55  4730.5  477.34
  4757.6  475.81  4793.6  474.94  4829.7  475.85  4859.7  474.44  4895.8  473.68
  4901.8  474.25  4919.3  472.32  4931.8  469.63  4937.8  469.88  4946.8  468.80
  4973.9  469.58  4982.9  467.05  4988.9  469.23  4990.4  465.70  4990.9  464.90
  4995.9  464.90  4996.4  465.70  4999.0  465.70  5014.5  469.74  5019.6  469.09
  5048.0  470.04  5067.0  472.32  5089.2  474.35  5225.8  477.67  5408.7  485.66
#Mann=3,-1,0
  4635.9    0.16       0  4990.4    0.07       0  4996.4    0.16       0
Bank Sta=4919.3,5067
Exp/Cntr=0.3,0.1

Type RM Length L Ch R = 1,4988,160,160,160
BEGIN DESCRIPTION:
UNT 160 in LFCCL Watershed 8.0
END DESCRIPTION:
XS GIS Cut Line= 3
      2773952.75      7040635.95      2774025.00      7040325.00
      2773924.99      7040024.97
#Sta/Elev= 30
  4689.7  474.73  4742.0  473.11  4803.6  474.12  4838.6  471.88  4857.2  470.18
  4865.2  468.15  4875.5  467.43  4894.7  468.42  4942.4  469.07  4978.1  468.80
  4985.1  466.29  4990.2  468.30  4995.7  464.00  4996.2  463.20  5001.2  463.20
  5001.7  464.00  5006.4  466.41  5011.6  466.41  5030.0  468.54  5051.1  468.75
  5072.0  471.88  5093.3  473.94  5156.5  478.12  5209.2  480.39  5219.8  478.87
  5230.3  479.17  5251.4  481.77  5272.5  482.43  5283.0  484.34  5325.2  486.64
#Mann=3,-1,0
  4689.7    0.16       0  4995.7    0.07       0  5001.7    0.16       0
Bank Sta=4838.6,5072
Exp/Cntr=0.3,0.1

Type RM Length L Ch R = 1,4828,394,394,394
BEGIN DESCRIPTION:
XS3893A
END DESCRIPTION:
XS GIS Cut Line= 3
      2773935.03      7040819.75      2774136.77      7040285.28
      2774289.52      7040115.17
#Sta/Elev= 30
  4409.5  475.81  4427.1  475.73  4457.3  473.39  4482.1  473.23  4493.3  471.71
  4512.3  469.74  4521.5  472.78  4531.8  473.13  4542.8  472.12  4567.4  473.36
  4639.0  472.31  4707.6  473.87  4732.5  472.32  4823.1  470.86  4842.1  468.02
  4853.2  465.22  4872.7  467.92  4983.2  468.27  4986.7  467.68  4991.2  464.05
  4991.7  463.25  4996.7  463.25  4997.2  464.05  5000.9  464.13  5009.8  471.71
  5015.1  475.96  5021.9  477.79  5050.3  480.99  5142.4  486.18  5209.4  488.65
#Mann=3,-1,0
  4409.5    0.16       0  4991.2    0.07       0  4997.2    0.16       0
Bank Sta=4493.3,5009.8
Exp/Cntr=0.3,0.1

Type RM Length L Ch R = 1,4434,156,156,156
BEGIN DESCRIPTION:
XS3894A
END DESCRIPTION:
XS GIS Cut Line= 3
      2774126.34      7040858.23      2774247.88      7040594.31
      2774296.43      7040209.42
#Sta/Elev= 30
  4684.5  475.48  4693.4  475.61  4762.3  472.60  4771.3  471.32  4776.1  470.67
  4790.8  470.89  4820.2  469.97  4842.2  469.72  4859.6  470.28  4865.2  469.43
  4897.2  468.51  4905.6  467.06  4911.1  467.64  4919.3  465.52  4934.0  465.68
  4951.5  466.78  4957.0  465.95  4977.2  467.49  4984.4  467.23  4990.7  465.94
  4992.8  464.93  4993.3  464.13  4998.3  464.13  4998.8  464.93  5014.7  466.62
  5024.8  466.19  5044.9  468.59  5089.4  471.32  5226.3  477.05  5363.0  485.26
#Mann=3,-1,0
  4684.5    0.16       0  4992.8    0.07       0  4998.8    0.16       0
Bank Sta=4771.3,5089.4
Exp/Cntr=0.3,0.1

Type RM Length L Ch R = 1,4278,77,77,77
BEGIN DESCRIPTION:
XS3895A
END DESCRIPTION:
XS GIS Cut Line= 3
      2774360.73      7040994.05      2774369.41      7040664.19
      2774354.22      7040264.85
#Sta/Elev= 30
  4663.4  476.34  4712.5  474.66  4752.5  474.30  4772.5  473.21  4812.5  472.34
  4828.7  471.20  4852.5  468.70  4862.5  468.03  4892.5  467.26  4912.5  467.43
  4972.6  466.60  4982.6  465.15  4987.5  464.04  4988.0  463.24  4993.0  463.24
  4993.5  464.04  5012.6  464.59  5022.6  466.00  5032.6  468.83  5050.7  471.20
  5072.6  472.71  5102.6  472.03  5132.7  472.23  5192.7  473.87  5212.7  474.90
  5244.3  475.35  5282.8  477.52  5302.8  477.51  5372.8  480.54  5393.0  481.76
#Mann=3,-1,0
  4663.4    0.16       0  4987.5    0.07       0  4993.5    0.16       0
Bank Sta=4828.7,5050.7
Exp/Cntr=0.3,0.1

Type RM Length L Ch R = 1,4201,401,401,401
BEGIN DESCRIPTION:
XS3896A
END DESCRIPTION:
XS GIS Cut Line= 3
      2774434.51      7041065.63      2774441.02      7040679.38
      2774454.04      7040312.61
#Sta/Elev= 30
  4605.7  475.50  4614.0  475.20  4676.3  471.95  4686.3  471.81  4706.3  472.51
  4716.3  472.45  4773.9  471.18  4809.6  469.96  4886.4  467.97  4916.4  467.90
  4976.4  466.74  4983.4  464.33  4983.9  463.53  4988.9  463.53  4989.4  464.33
  5006.4  464.77  5026.4  467.26  5036.4  467.73  5136.5  471.21  5149.7  471.18
  5186.5  472.54  5196.5  472.52  5243.3  475.17  5248.3  474.92  5266.6  475.25
  5286.6  476.47  5306.6  476.73  5326.6  477.51  5336.6  478.30  5359.0  478.72
#Mann=5,-1,0
  4605.7    0.08       0  4614.0    0.05       0  4809.6    0.08       0
  4983.4    0.07       0  4989.4    0.08       0
Bank Sta=4773.9,5149.7
Exp/Cntr=0.3,0.1

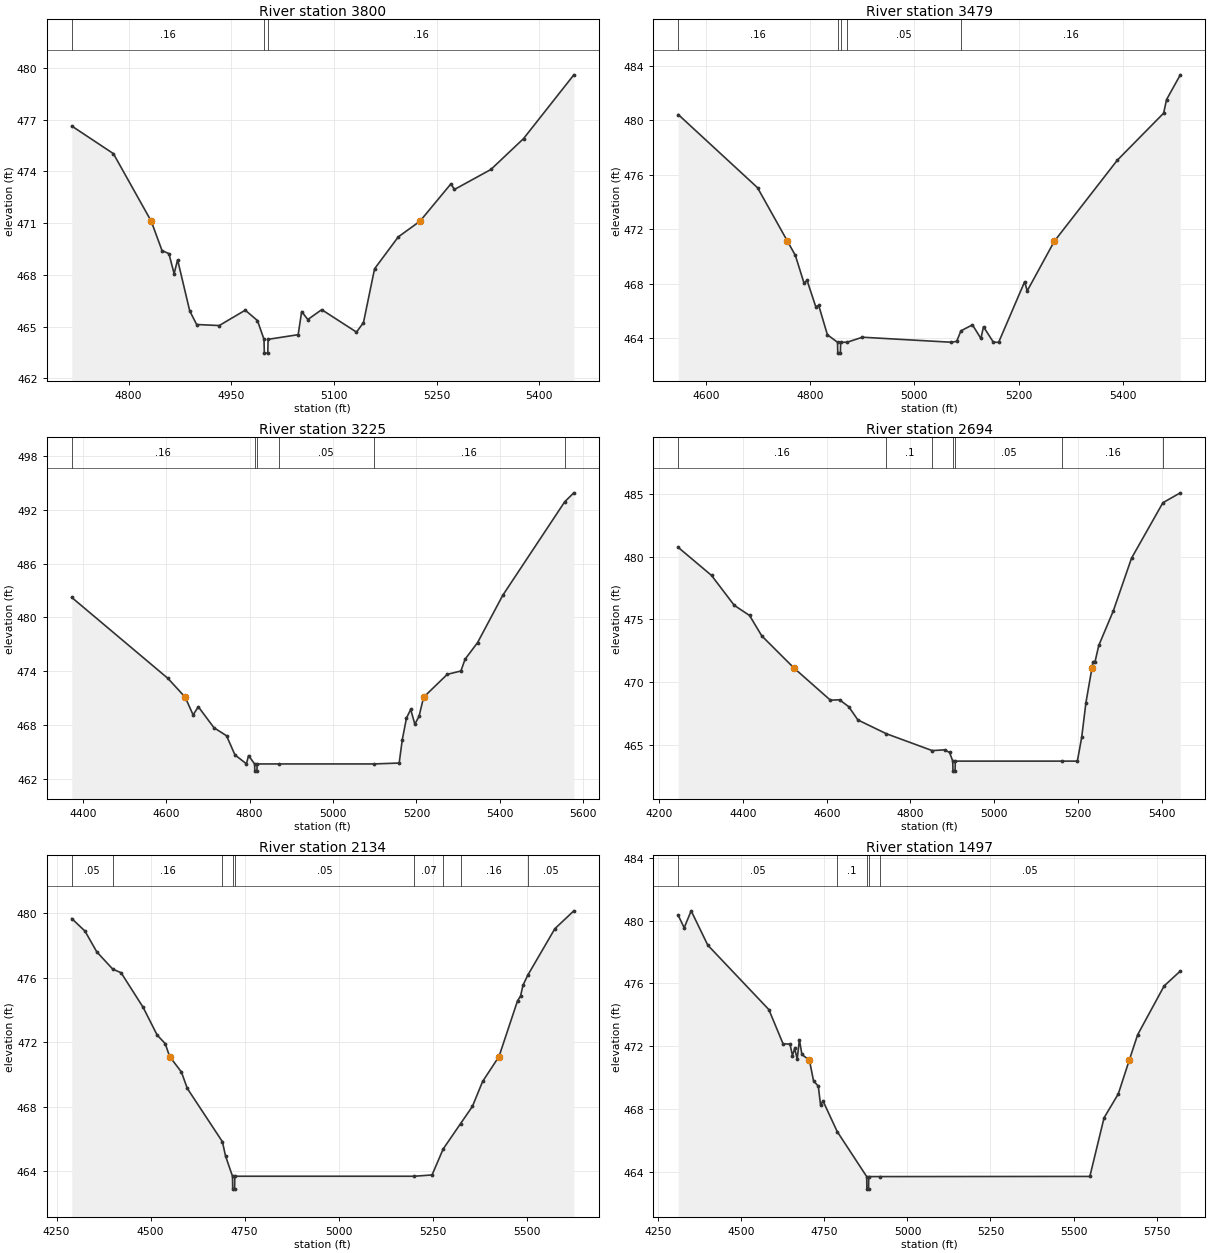
Type RM Length L Ch R = 1,3800,321,321,321
BEGIN DESCRIPTION:
UNT 160 in LFCCL Watershed 5.0
END DESCRIPTION:
XS GIS Cut Line= 3
      2774675.01      7041024.96      2774725.00      7040725.00
      2774802.13      7040302.68
#Sta/Elev= 30
  4716.9  476.63  4777.7  475.03  4833.0  471.11  4848.7  469.41  4858.8  469.23
  4866.4  468.07  4871.5  468.87  4889.2  465.91  4899.3  465.12  4932.3  465.06
  4970.3  465.95  4988.1  465.35  4997.7  464.26  4998.2  463.46  5003.2  463.46
  5003.7  464.26  5047.6  464.53  5052.7  465.87  5061.7  465.41  5082.0  465.98
  5132.8  464.68  5143.0  465.23  5159.2  468.35  5193.8  470.20  5225.5  471.11
  5270.8  473.28  5275.8  472.95  5329.1  474.11  5376.8  475.90  5450.3  479.60
#Mann=3,-1,0
  4716.9    0.16       0  4997.7    0.07       0  5003.7    0.16       0
Bank Sta=4833,5225.5
Exp/Cntr=0.3,0.1

Type RM Length L Ch R = 1,3479,254,254,254
BEGIN DESCRIPTION:
XS3902A
END DESCRIPTION:
XS GIS Cut Line= 3
      2774831.11      7041164.23      2775018.63      7040789.19
      2774956.27      7040248.78
#Sta/Elev= 30
  4546.9  480.43  4699.0  475.05  4756.5  471.11  4771.6  470.07  4788.4  468.01
  4794.0  468.24  4810.8  466.29  4816.4  466.39  4833.1  464.23  4852.5  463.68
  4853.0  462.88  4858.0  462.88  4858.5  463.68  4870.8  463.68  4900.2  464.05
  5071.1  463.68  5081.2  463.75  5089.3  464.52  5111.4  464.96  5127.6  463.96
  5132.6  464.82  5151.6  463.68  5161.7  463.68  5211.5  468.13  5216.5  467.46
  5268.5  471.11  5389.3  477.07  5478.2  480.53  5483.8  481.53  5510.2  483.35
#Mann=5,-1,0
  4546.9    0.16       0  4852.5   0.033       0  4858.5    0.16       0
  4870.8    0.05       0  5089.3    0.16       0
Bank Sta=4756.5,5268.5
Exp/Cntr=0.3,0.1

Type RM Length L Ch R = 1,3225,531,531,531
BEGIN DESCRIPTION:
UNT 160 in LFCCL Watershed 4.0
END DESCRIPTION:
XS GIS Cut Line= 3
      2775175.00      7041374.96      2775225.00      7040775.00
      2775275.00      7040175.02
#Sta/Elev= 30
  4373.4  482.22  4604.2  473.20  4645.4  471.11  4664.4  469.14  4676.9  470.05
  4714.5  467.71  4744.6  466.82  4764.7  464.69  4792.3  463.69  4797.3  464.61
  4811.9  463.68  4812.4  462.88  4817.4  462.88  4817.9  463.68  4869.9  463.68
  5097.8  463.68  5158.6  463.78  5166.1  466.39  5176.1  468.79  5186.2  469.75
  5196.2  468.11  5206.2  468.98  5217.2  471.11  5274.0  473.66  5306.6  474.03
  5316.6  475.34  5346.7  477.20  5406.9  482.45  5555.7  492.88  5577.5  493.87
#Mann=6,-1,0
  4373.4    0.16       0  4811.9   0.033       0  4817.9    0.16       0
  4869.9    0.05       0  5097.8    0.16       0  5555.7    0.05       0
Bank Sta=4645.4,5217.2
Exp/Cntr=0.3,0.1

Type RM Length L Ch R = 1,2694,560,560,560
BEGIN DESCRIPTION:
UNT 160 in LFCCL Watershed 3.0
END DESCRIPTION:
XS GIS Cut Line= 3
      2775375.02      7041424.96      2775725.00      7040775.00
      2775825.01      7040324.98
#Sta/Elev= 30
  4245.4  480.76  4324.9  478.52  4379.2  476.13  4415.7  475.32  4444.9  473.69
  4522.2  471.11  4608.8  468.55  4630.7  468.58  4652.6  468.03  4674.5  466.97
  4742.4  465.87  4852.1  464.52  4881.4  464.58  4893.5  464.37  4901.1  463.68
  4901.6  462.88  4906.6  462.88  4907.1  463.68  5163.2  463.68  5198.7  463.68
  5209.0  465.57  5219.2  468.36  5233.5  471.11  5235.9  471.62  5241.0  471.64
  5249.9  472.93  5284.5  475.68  5328.1  479.90  5403.0  484.33  5444.6  485.12
#Mann=7,-1,0
  4245.4    0.16       0  4742.4     0.1       0  4852.1    0.05       0
  4901.1   0.033       0  4907.1    0.05       0  5163.2    0.16       0
  5403.0    0.05       0
Bank Sta=4522.2,5233.5
Exp/Cntr=0.3,0.1

Type RM Length L Ch R = 1,2134,637,637,637
BEGIN DESCRIPTION:
UNT 160 in LFCCL Watershed 2.0
END DESCRIPTION:
XS GIS Cut Line= 3
      2775824.99      7041675.02      2776175.00      7041075.00
      2776575.03      7040574.96
#Sta/Elev= 30
  4290.3  479.67  4325.5  478.89  4356.9  477.60  4399.4  476.53  4421.4  476.31
  4480.1  474.16  4517.3  472.44  4538.8  471.91  4550.5  471.11  4581.8  470.15
  4597.5  469.13  4690.9  465.82  4699.2  464.93  4717.7  463.68  4718.2  462.88
  4723.3  462.88  4723.8  463.68  5201.2  463.68  5248.3  463.76  5277.8  465.37
  5324.2  466.95  5355.5  468.01  5382.7  469.56  5426.3  471.11  5475.6  474.57
  5483.6  474.86  5490.0  475.53  5502.9  476.16  5574.8  479.04  5625.3  480.15
#Mann=9,-1,0
  4290.3    0.05       0  4399.4    0.16       0  4690.9    0.05       0
  4717.7   0.033       0  4723.8    0.05       0  5201.2    0.07       0
  5277.8    0.05       0  5324.2    0.16       0  5502.9    0.05       0
Bank Sta=4550.5,5426.3
Exp/Cntr=0.3,0.1

Type RM Length L Ch R = 1,1497,335,335,335
BEGIN DESCRIPTION:
XS3897A
END DESCRIPTION:
XS GIS Cut Line= 3
      2776228.73      7041954.09      2776680.09      7041447.18
      2777107.16      7040731.91
#Sta/Elev= 30
  4309.8  480.34  4327.7  479.55  4348.7  480.63  4398.8  478.44  4582.7  474.33
  4625.4  472.15  4646.3  472.13  4653.8  471.40  4660.5  471.86  4668.0  471.18
  4674.7  472.41  4682.2  471.47  4704.8  471.10  4717.3  469.78  4731.6  469.45
  4738.3  468.25  4745.8  468.50  4788.5  466.55  4877.3  463.68  4877.8  462.88
  4882.9  462.88  4883.4  463.68  4916.8  463.68  5549.2  463.69  5592.0  467.43
  5634.8  468.95  5667.8  471.10  5693.2  472.73  5772.9  475.84  5821.6  476.79
#Mann=5,-1,0
  4309.8    0.05       0  4788.5     0.1       0  4877.3   0.033       0
  4883.4     0.1       0  4916.8    0.05       0
Bank Sta=4704.8,5667.8
Exp/Cntr=0.3,0.1

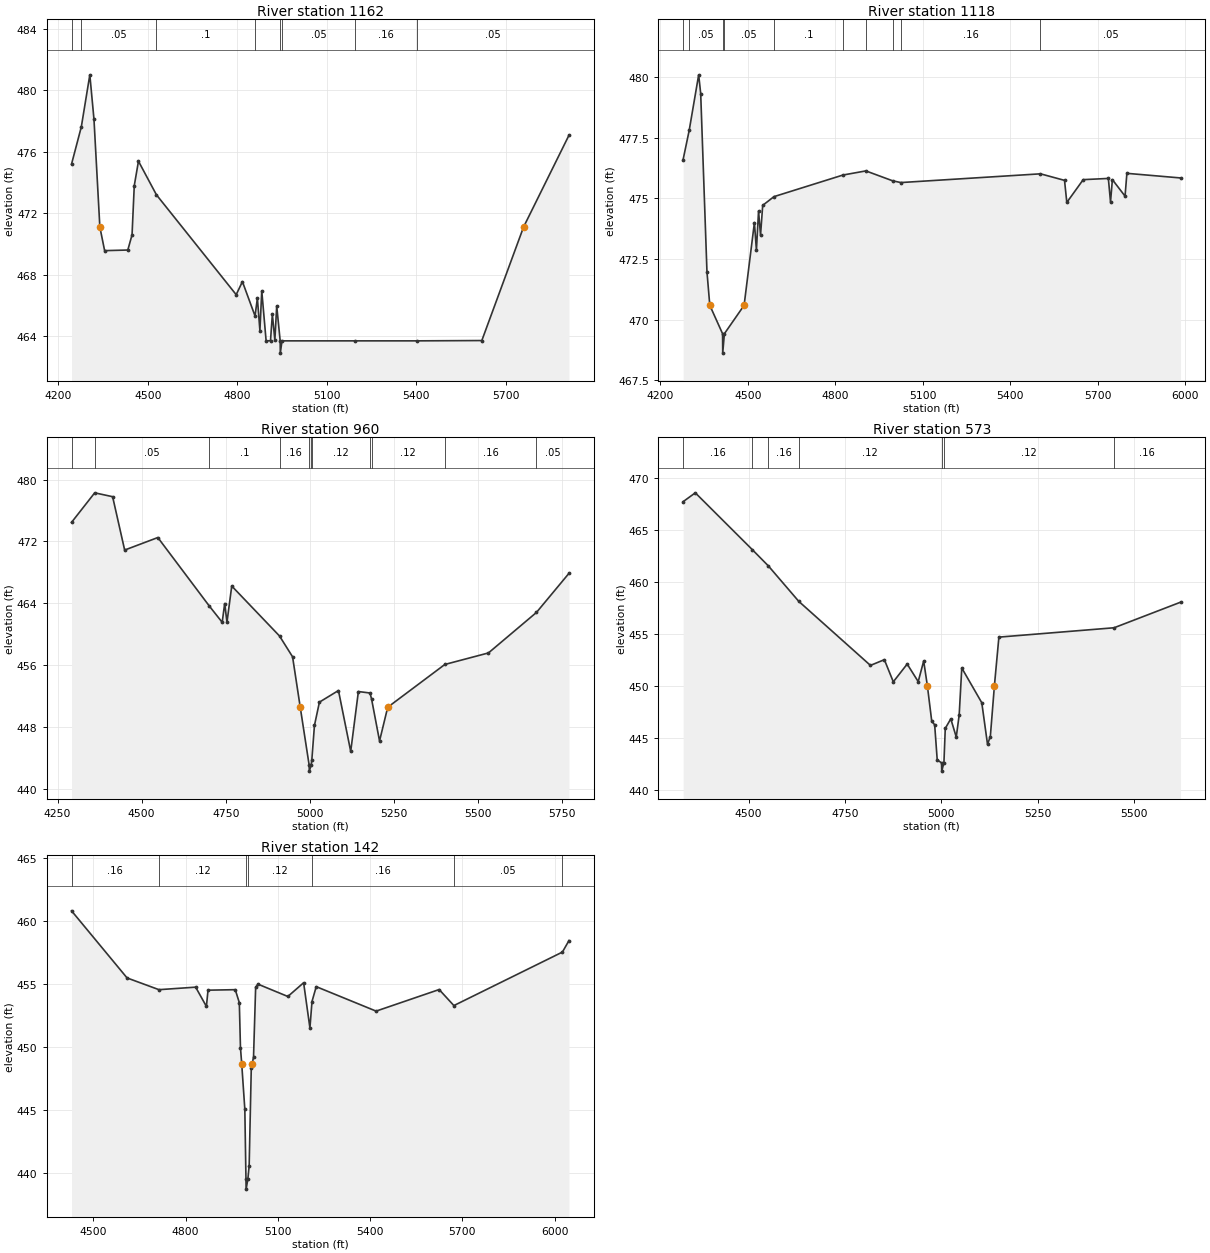
Type RM Length L Ch R = 1,1162,44,44,44
BEGIN DESCRIPTION:
XS3898A
END DESCRIPTION:
XS GIS Cut Line= 3
      2776433.53      7042270.13      2776669.67      7042013.15
      2777450.44      7040951.30
#Sta/Elev= 30
  4244.7  475.20  4277.5  477.63  4306.0  481.02  4319.9  478.12  4339.6  471.10
  4355.6  469.56  4433.3  469.60  4447.5  470.59  4454.9  473.79  4469.0  475.39
  4529.2  473.20  4796.5  466.69  4817.4  467.54  4859.7  465.30  4867.5  466.46
  4876.0  464.35  4882.2  466.94  4896.8  463.68  4911.5  463.69  4917.7  465.41
  4926.1  463.73  4932.3  465.96  4943.9  463.68  4944.4  462.88  4950.0  463.68
  5195.8  463.68  5402.6  463.68  5619.7  463.70  5759.6  471.10  5911.7  477.08
#Mann=8,-1,0
  4244.7    0.16       0  4277.5    0.05       0  4529.2     0.1       0
  4859.7    0.05       0  4943.9   0.033       0  4950.0    0.05       0
  5195.8    0.16       0  5402.6    0.05       0
Bank Sta=4339.6,5759.6
Exp/Cntr=0.3,0.1

Type RM Length L Ch R = 1,1118,158,158,158
BEGIN DESCRIPTION:
XS3899A
END DESCRIPTION:
XS GIS Cut Line= 4
      2776471.78      7042277.00      2776711.34      7042020.09
      2777364.11      7041148.57      2777527.31      7040940.23
#Sta/Elev= 30
  4278.6  476.60  4299.4  477.80  4331.9  480.09  4338.8  479.32  4360.3  471.97
  4370.0  470.59  4413.8  469.42  4414.3  468.62  4420.0  469.42  4487.6  470.59
  4522.9  474.00  4529.8  472.86  4537.1  474.48  4543.9  473.48  4551.3  474.71
  4590.0  475.07  4826.4  475.96  4904.9  476.13  4997.1  475.72  5025.0  475.65
  5503.4  476.01  5585.8  475.74  5593.6  474.83  5649.8  475.77  5736.0  475.82
  5743.4  474.85  5749.8  475.77  5793.2  475.09  5799.5  476.03  5983.4  475.84
#Mann=10,-1,0
  4278.6    0.16       0  4299.4    0.05       0  4413.8    0.07       0
  4420.0    0.05       0  4590.0     0.1       0  4826.4    0.16       0
  4904.9    0.05       0  4997.1    0.12       0  5025.0    0.16       0
  5503.4    0.05       0
Bank Sta=4370,4487.6
Exp/Cntr=0.3,0.1

Type RM Length L Ch R = 1,960,387,387,387
BEGIN DESCRIPTION:
XS3900A
END DESCRIPTION:
XS GIS Cut Line= 4
      2776509.96      7042332.58      2776850.22      7041957.59
      2777027.31      7041849.95      2777468.28      7041224.95
#Sta/Elev= 30
  4291.6  474.46  4360.5  478.28  4413.7  477.78  4449.5  470.88  4548.1  472.50
  4701.0  463.65  4739.4  461.54  4746.8  463.97  4753.6  461.55  4767.8  466.23
  4909.8  459.77  4948.6  457.08  4971.4  450.56  4997.8  443.10  4998.3  442.30
  5004.0  443.10  5005.7  443.68  5013.6  448.20  5028.4  451.22  5085.0  452.72
  5121.4  444.85  5144.2  452.59  5178.8  452.40  5183.5  451.60  5207.1  446.20
  5231.4  450.56  5401.2  456.09  5530.8  457.58  5673.6  462.82  5770.1  467.87
#Mann=11,-1,0
  4291.6    0.16       0  4360.5    0.05       0  4701.0     0.1       0
  4909.8    0.16       0  4997.8    0.07       0  5004.0    0.16       0
  5005.7    0.12       0  5178.8    0.16       0  5183.5    0.12       0
  5401.2    0.16       0  5673.6    0.05       0
Bank Sta=4971.4,5231.4
Exp/Cntr=0.3,0.1

Type RM Length L Ch R = 1,573,431,431,431
BEGIN DESCRIPTION:
XS3901A
END DESCRIPTION:
XS GIS Cut Line= 4
      2776770.37      7042315.23      2777273.84      7041981.90
      2777364.11      7041877.73      2777613.62      7041389.11
#Sta/Elev= 30
  4330.1  467.69  4361.7  468.54  4509.4  463.08  4551.2  461.51  4630.1  458.10
  4816.0  451.94  4852.1  452.49  4875.3  450.36  4911.3  452.07  4939.9  450.38
  4954.1  452.36  4963.6  450.00  4975.0  446.57  4982.6  446.23  4989.2  442.85
  5000.4  442.57  5000.9  441.77  5006.6  442.57  5010.1  445.88  5024.4  446.80
  5038.6  445.05  5046.2  447.17  5052.9  451.69  5104.8  448.35  5119.7  444.35
  5127.0  445.10  5137.6  450.00  5149.2  454.66  5448.0  455.56  5620.4  458.02
#Mann=7,-1,0
  4330.1    0.16       0  4509.4    0.12       0  4551.2    0.16       0
  4630.1    0.12       0  5000.4    0.07       0  5006.6    0.12       0
  5448.0    0.16       0
Bank Sta=4963.6,5137.6
Exp/Cntr=0.3,0.1

Type RM Length L Ch R = 1,142,0,0,0
BEGIN DESCRIPTION:
UNT 160 in LFCCL Watershed 1.0
END DESCRIPTION:
XS GIS Cut Line= 4
      2776940.51      7042363.84      2777464.66      7042224.51
      2777558.84      7042136.10      2777766.42      7041213.18
#Sta/Elev= 30
  4429.2  460.79  4609.8  455.47  4713.5  454.54  4832.8  454.74  4867.8  453.21
  4873.0  454.50  4961.6  454.54  4974.8  453.51  4978.5  449.95  4982.6  448.66
  4992.7  445.06  4996.4  439.53  4996.9  438.73  5002.6  439.53  5006.8  440.58
  5013.7  448.34  5016.4  448.66  5021.0  449.19  5027.9  454.73  5035.2  454.98
  5132.6  454.00  5183.9  455.09  5204.4  451.50  5211.1  453.60  5224.9  454.78
  5419.6  452.84  5624.6  454.55  5672.5  453.28  6025.4  457.52  6046.7  458.43
#Mann=7,-1,0
  4429.2    0.16       0  4713.5    0.12       0  4996.4    0.07       0
  5002.6    0.12       0  5211.1    0.16       0  5672.5    0.05       0
  6025.4    0.16       0
Bank Sta=4982.6,5016.4
Exp/Cntr=0.3,0.1

Chan Stop Cuts=-1