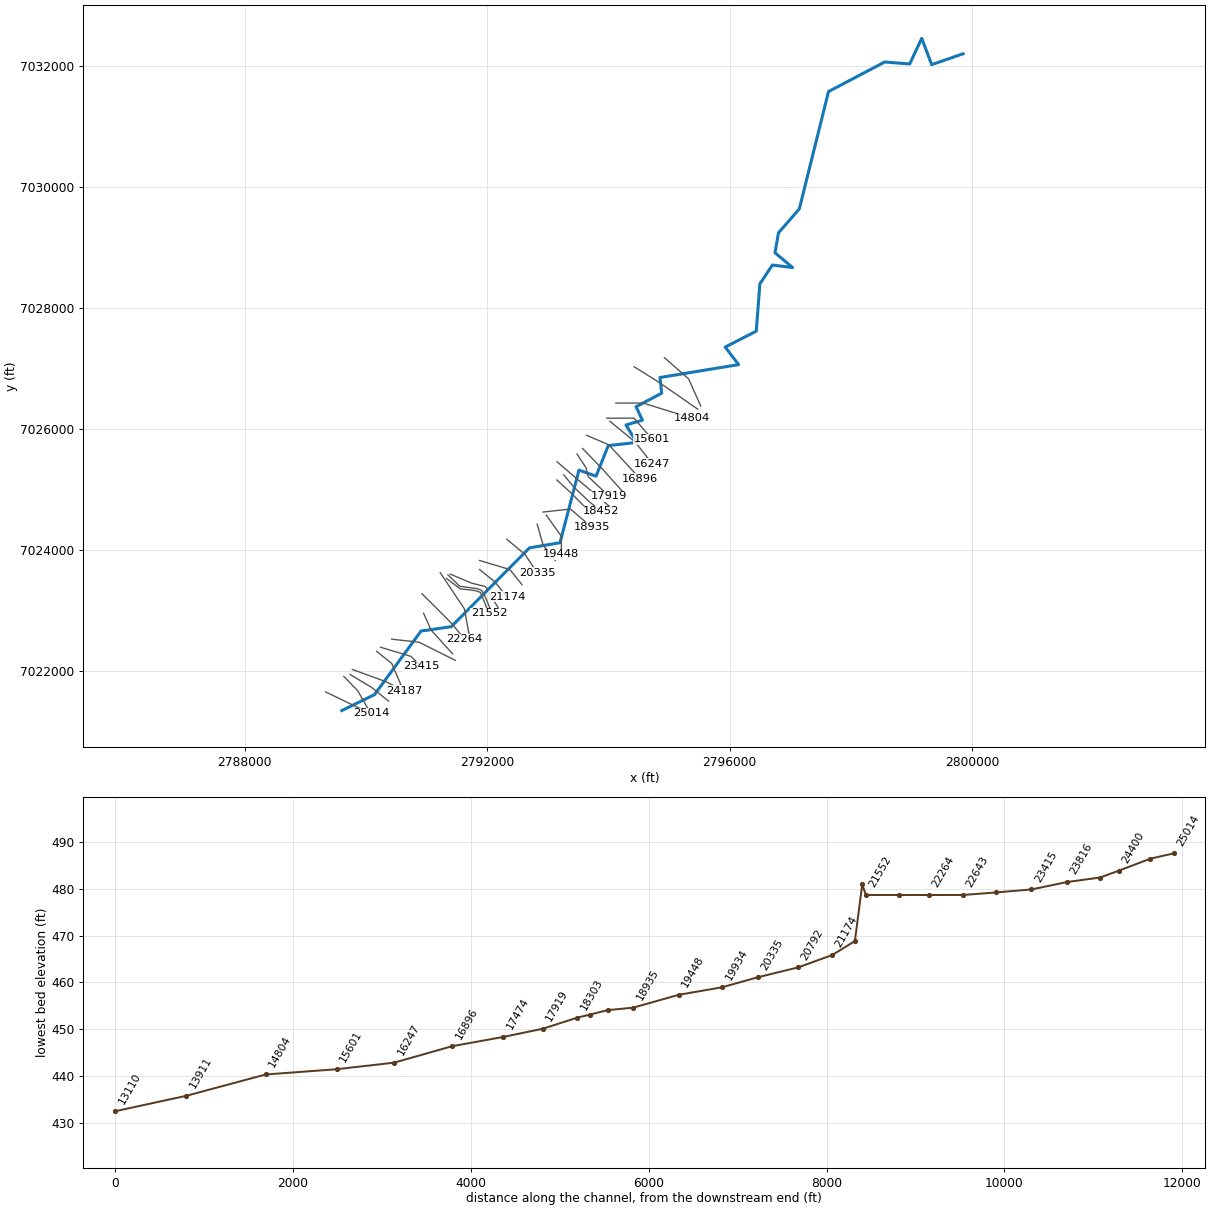
--- UNT 161 in LFCCL Watershed.prj (project) ---

Proj Title=UNT 161 in LFCCL Watershed Base Level Engineering
Current Plan=p01
Default Exp/Contr=0.3,0.1
English Units
Geom File=g01
Flow File=f01
Plan File=p01
BEGIN DESCRIPTION:
UNT 161 in LFCCL Watershed
END DESCRIPTION:

--- UNT 161 in LFCCL Watershed.p01 (plan) ---

Plan Title=Multiple Run
Short Identifier=Multiple
Geom File=g01
Flow File=f01
Subcritical Flow
K Sum by GR= 0
Std Step Tol= 0.01
Critical Tol= 0.01
Num of Std Step Trials= 20
Max Error Tol= 0.3
Flow Tol Ratio= 0.001
Split Flow NTrial= 30
Split Flow Tol= 0.02
Split Flow Ratio= 0.02
Log Output Level= 0
Friction Slope Method= 1
Unsteady Friction Slope Method= 2
Unsteady Bridges Friction Slope Method= 1
Parabolic Critical Depth
Global Vel Dist=  1 , 1 , 1
Global Log Level= 0
CheckData=True
Encroach Param= -1, 0, 0, 0
BEGIN DESCRIPTION:
Multiple Run
END DESCRIPTION:

--- UNT 161 in LFCCL Watershed.f01 (steady flow) ---

Flow Title=Multiple
Number of Profiles=7
Profile Names=10-year,25-year,50-year,1pct_min,100-year,1pct_plu,500-year
River Rch & RM= UNT 161 in LFCCL,Reach-1,25014
     515     682     816     486     969    1933    1368
River Rch & RM= UNT 161 in LFCCL,Reach-1,18935
     717     967    1170     704    1404    2801    2024
River Rch & RM= UNT 161 in LFCCL,Reach-1,9736
     964    1318    1611     977    1948    3888    2857
River Rch & RM= UNT 161 in LFCCL,Reach-1,8659
    1216    1681    2069    1262    2519    5026    3742
Boundary for River Rch & Prof#=UNT 161 in LFCCL,Reach-1,1
Up Type=0
Dn Type=3
Dn Slope=0.005
Boundary for River Rch & Prof#=UNT 161 in LFCCL,Reach-1,2
Up Type=0
Dn Type=3
Dn Slope=0.005
Boundary for River Rch & Prof#=UNT 161 in LFCCL,Reach-1,3
Up Type=0
Dn Type=3
Dn Slope=0.005
Boundary for River Rch & Prof#=UNT 161 in LFCCL,Reach-1,4
Up Type=0
Dn Type=3
Dn Slope=0.005
Boundary for River Rch & Prof#=UNT 161 in LFCCL,Reach-1,5
Up Type=0
Dn Type=3
Dn Slope=0.005
Boundary for River Rch & Prof#=UNT 161 in LFCCL,Reach-1,6
Up Type=0
Dn Type=3
Dn Slope=0.005
Boundary for River Rch & Prof#=UNT 161 in LFCCL,Reach-1,7
Up Type=0
Dn Type=3
Dn Slope=0.005

--- UNT 161 in LFCCL Watershed.g01 (geometry) ---

Geom Title=Existing Conditions

River Reach=UNT 161 in LFCCL,Reach-1
Reach XY= 30
      2789600.59      7021345.71      2790140.21      7021609.28
      2790908.31      7022658.95      2791407.98      7022732.04
      2792698.71      7024033.37      2793202.04      7024118.47
      2793515.67      7025317.73      2793797.39      7025217.16
      2793999.92      7025722.77      2794468.31      7025774.35
      2794291.07      7026063.05      2794563.16      7026141.95
      2794457.16      7026364.54      2794881.36      7026588.33
      2794852.63      7026847.10      2796149.91      7027059.76
      2795929.49      7027349.84      2796441.16      7027612.18
      2796501.72      7028395.29      2796708.58      7028704.61
      2797042.24      7028662.28      2796751.44      7028907.47
      2796808.05      7029235.47      2797152.52      7029632.47
      2797634.70      7031570.17      2798562.86      7032058.70
      2798973.92      7032025.50      2799172.89      7032448.91
      2799336.80      7032014.07      2799855.71      7032194.31

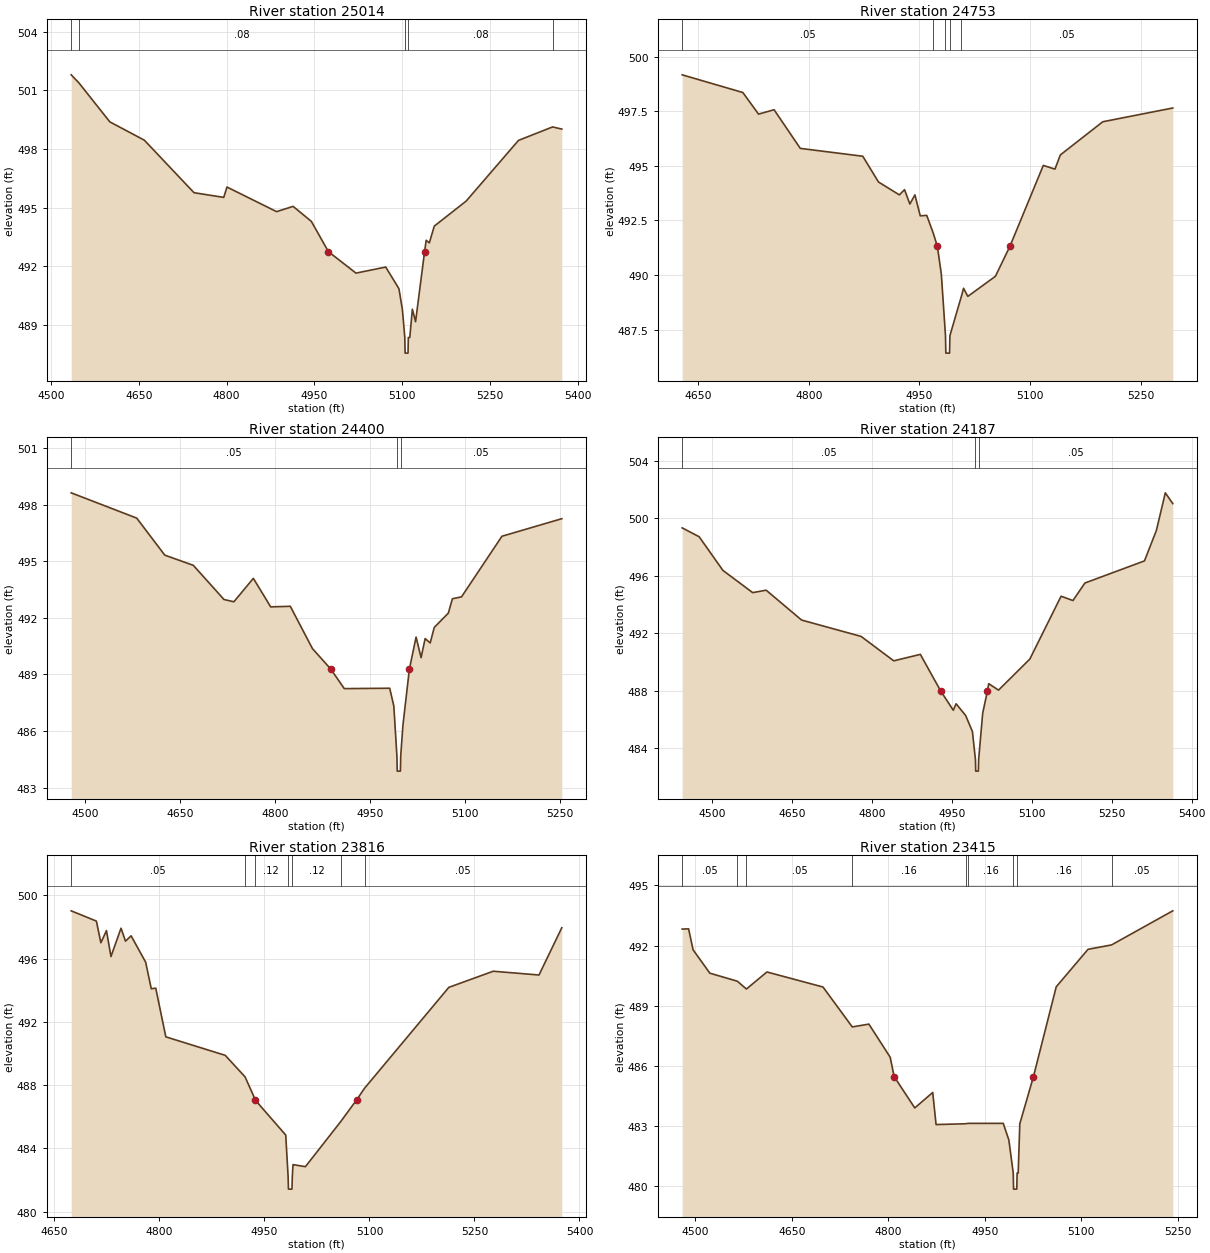
Type RM Length L Ch R = 1,25014,261,261,261
BEGIN DESCRIPTION:
UNT 161 in LFCCL Watershed 38.0
END DESCRIPTION:
XS GIS Cut Line= 3
      2789335.60      7021653.46      2789852.92      7021403.48
      2790095.16      7021299.66
#Sta/Elev= 30
  4534.5  501.80  4547.6  501.39  4600.5  499.39  4659.5  498.45  4744.3  495.76
  4795.1  495.52  4800.6  496.05  4885.4  494.79  4913.6  495.06  4944.8  494.29
  4973.9  492.74  5021.0  491.64  5071.8  491.95  5094.4  490.84  5100.3  489.77
  5104.4  488.34  5104.9  487.54  5109.9  487.54  5110.4  488.34  5112.9  488.34
  5117.3  489.79  5122.8  489.15  5138.2  492.74  5140.9  493.32  5146.3  493.19
  5154.8  494.05  5209.2  495.33  5298.6  498.44  5356.8  499.13  5372.6  499.02
#Mann=5,-1,0
  4534.5    0.05       0  4547.6    0.08       0  5104.4    0.07       0
  5110.4    0.08       0  5356.8    0.05       0
Bank Sta=4973.9,5138.2
Exp/Cntr=0.3,0.1

Type RM Length L Ch R = 1,24753,353,353,353
BEGIN DESCRIPTION:
XS3903A
END DESCRIPTION:
XS GIS Cut Line= 3
      2789634.16      7021910.44      2789863.34      7021674.31
      2790030.01      7021382.64
#Sta/Elev= 30
  4628.4  499.17  4710.6  498.36  4731.9  497.37  4753.0  497.57  4788.5  495.80
  4873.2  495.44  4894.5  494.26  4922.8  493.67  4929.8  493.91  4937.0  493.25
  4943.9  493.67  4951.1  492.71  4959.9  492.73  4968.7  491.92  4974.3  491.31
  4979.7  490.03  4985.3  487.22  4985.8  486.42  4990.8  486.42  4991.3  487.22
  5007.0  489.04  5009.8  489.39  5015.6  489.02  5053.0  489.94  5072.6  491.31
  5117.9  495.02  5133.7  494.85  5141.0  495.50  5198.5  497.02  5293.4  497.65
#Mann=5,-1,0
  4628.4    0.05       0  4968.7     0.1       0  4985.3    0.07       0
  4991.3     0.1       0  5007.0    0.05       0
Bank Sta=4974.3,5072.6
Exp/Cntr=0.3,0.1

Type RM Length L Ch R = 1,24400,213,213,213
BEGIN DESCRIPTION:
XS3904A
END DESCRIPTION:
XS GIS Cut Line= 3
      2789738.30      7021941.70      2790095.98      7021726.39
      2790373.77      7021500.69
#Sta/Elev= 30
  4478.2  498.62  4581.8  497.28  4626.1  495.32  4671.2  494.78  4719.7  492.97
  4735.3  492.85  4766.1  494.09  4793.5  492.58  4824.5  492.61  4859.5  490.37
  4888.6  489.28  4909.8  488.25  4981.6  488.27  4988.1  487.33  4993.0  484.68
  4993.5  483.88  4998.5  483.88  4999.0  484.68  5002.5  486.31  5012.7  489.28
  5023.3  490.98  5031.2  489.89  5037.6  490.90  5045.6  490.67  5052.0  491.49
  5074.3  492.25  5080.7  493.01  5095.1  493.11  5159.0  496.32  5253.6  497.25
#Mann=3,-1,0
  4478.2    0.05       0  4993.0    0.03       0  4999.0    0.05       0
Bank Sta=4888.6,5012.7
Exp/Cntr=0.3,0.1

Type RM Length L Ch R = 1,24187,371,371,371
BEGIN DESCRIPTION:
UNT 161 in LFCCL Watershed 36.0
END DESCRIPTION:
XS GIS Cut Line= 3
      2789775.05      7022024.98      2790325.00      7021825.00
      2790625.00      7021675.00
#Sta/Elev= 30
  4444.0  499.33  4475.9  498.71  4520.4  496.37  4576.3  494.82  4601.6  494.99
  4668.1  492.91  4779.8  491.77  4841.0  490.07  4890.9  490.52  4928.8  487.99
  4952.7  486.63  4958.0  487.08  4976.0  486.26  4988.6  485.15  4994.3  483.19
  4994.8  482.39  4999.8  482.39  5000.3  483.19  5007.9  486.42  5016.9  487.99
  5019.2  488.48  5037.6  488.03  5096.3  490.19  5155.0  494.57  5177.3  494.27
  5199.7  495.49  5311.5  497.03  5333.9  499.16  5350.6  501.77  5364.6  501.02
#Mann=3,-1,0
  4444.0    0.05       0  4994.3    0.03       0  5000.3    0.05       0
Bank Sta=4928.8,5016.9
Exp/Cntr=0.3,0.1

Type RM Length L Ch R = 1,23816,401,401,401
BEGIN DESCRIPTION:
UNT 161 in LFCCL Watershed 35.0
END DESCRIPTION:
XS GIS Cut Line= 3
      2790175.02      7022324.99      2790425.00      7022125.00
      2790574.99      7021775.02
#Sta/Elev= 30
  4673.9  499.03  4709.9  498.38  4716.3  497.01  4724.3  497.78  4730.7  496.14
  4745.1  497.93  4751.5  497.11  4759.5  497.45  4780.3  495.78  4788.3  494.10
  4794.7  494.14  4809.1  491.06  4894.0  489.89  4922.3  488.53  4935.8  487.19
  4936.7  487.07  4980.4  484.85  4983.8  482.23  4984.3  481.43  4989.3  481.43
  4989.8  482.23  4990.8  482.98  5008.5  482.85  5059.1  485.71  5081.8  487.08
  5093.0  487.81  5213.4  494.19  5276.9  495.21  5342.2  494.97  5374.8  497.96
#Mann=7,-1,0
  4673.9    0.05       0  4922.3    0.16       0  4935.8    0.12       0
  4983.8    0.07       0  4989.8    0.12       0  5059.1    0.16       0
  5093.0    0.05       0
Bank Sta=4936.7,5081.8
Exp/Cntr=0.3,0.1

Type RM Length L Ch R = 1,23415,402,402,402
BEGIN DESCRIPTION:
UNT 161 in LFCCL Watershed 34.0
END DESCRIPTION:
XS GIS Cut Line= 3
      2790238.84      7022392.38      2790738.89      7022242.36
      2790914.93      7022078.89
#Sta/Elev= 30
  4479.7  492.82  4489.7  492.83  4496.6  491.79  4522.7  490.62  4565.4  490.22
  4579.5  489.83  4611.4  490.68  4698.5  489.93  4744.0  487.94  4769.8  488.08
  4802.9  486.43  4809.1  485.46  4841.1  483.90  4869.0  484.67  4874.2  483.07
  4920.0  483.11  4923.5  483.13  4978.6  483.13  4987.3  482.30  4994.1  480.65
  4994.6  479.85  4999.6  479.85  5000.1  480.65  5001.8  480.65  5004.3  483.11
  5025.5  485.46  5060.9  489.94  5110.3  491.81  5146.9  492.03  5242.0  493.73
#Mann=9,-1,0
  4479.7    0.05       0  4565.4    0.16       0  4579.5    0.05       0
  4744.0    0.16       0  4920.0    0.12       0  4923.5    0.16       0
  4994.1    0.07       0  5000.1    0.16       0  5146.9    0.05       0
Bank Sta=4809.1,5025.5
Exp/Cntr=0.3,0.1

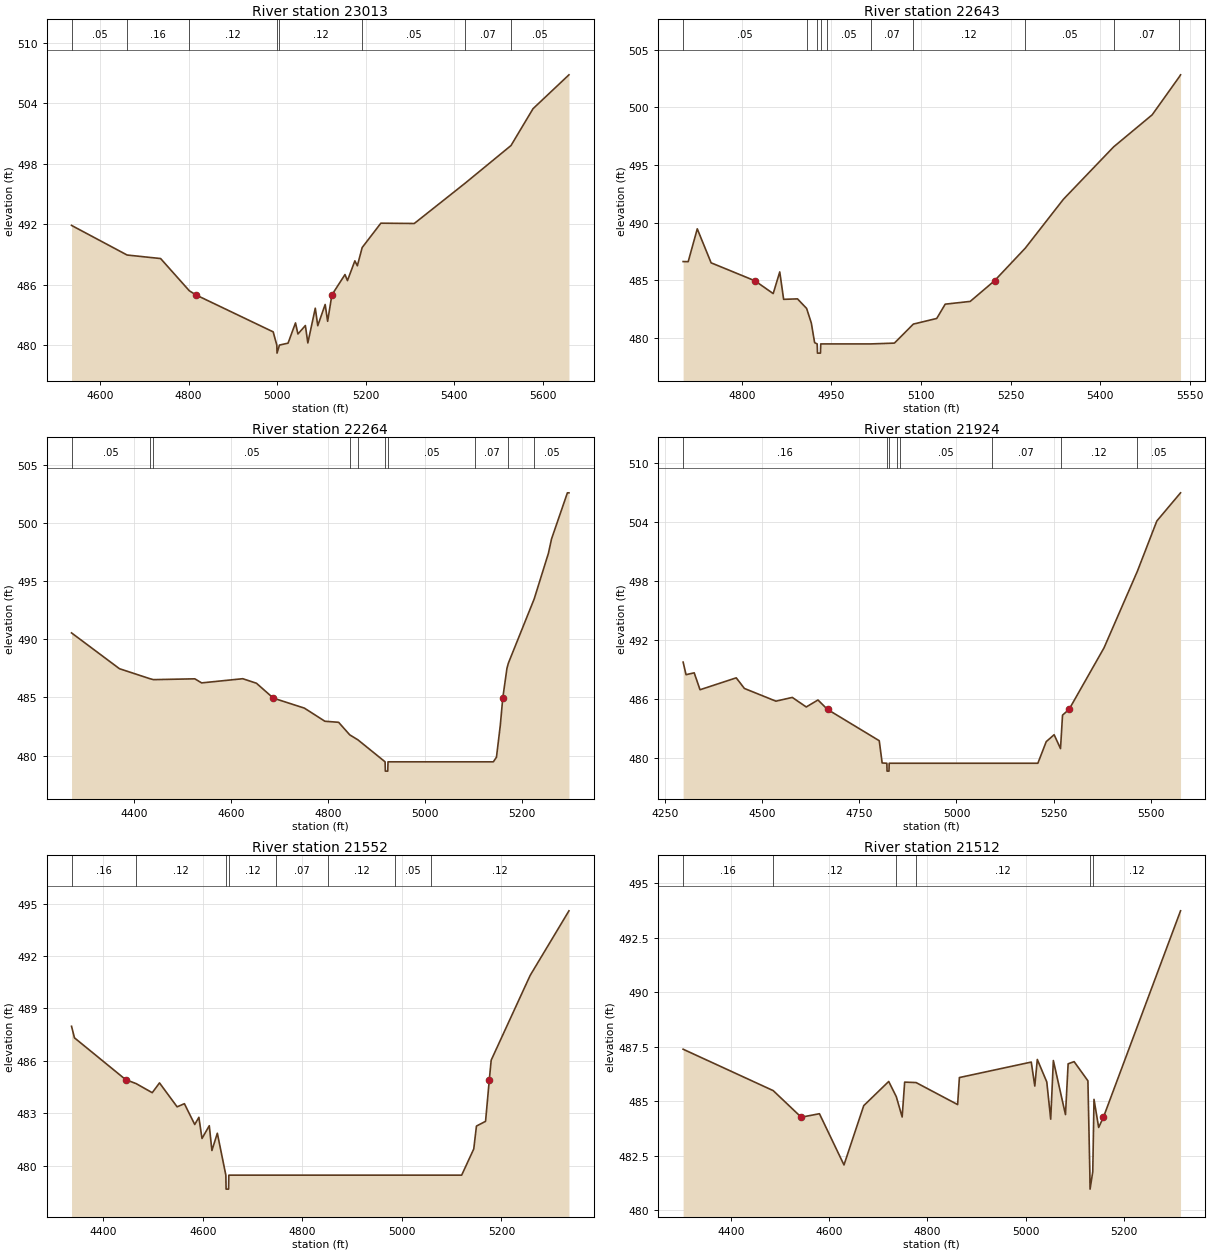
Type RM Length L Ch R = 1,23013,370,370,370
BEGIN DESCRIPTION:
UNT 161 in LFCCL Watershed 33.0
END DESCRIPTION:
XS GIS Cut Line= 3
      2790425.02      7022525.00      2790875.00      7022475.00
      2791475.02      7022174.99
#Sta/Elev= 30
  4535.6  491.88  4661.1  488.94  4736.8  488.59  4801.7  485.39  4816.6  484.98
  4991.1  481.31  4999.3  480.00  4999.8  479.20  5005.3  480.00  5024.7  480.19
  5041.5  482.20  5047.0  481.10  5063.8  481.94  5069.4  480.21  5086.2  483.66
  5091.8  481.92  5108.5  484.03  5114.1  482.36  5123.7  484.98  5153.3  487.00
  5158.9  486.40  5175.6  488.36  5181.2  487.87  5192.1  489.68  5234.3  492.10
  5309.8  492.07  5424.1  496.05  5528.3  499.81  5578.1  503.47  5659.2  506.83
#Mann=8,-1,0
  4535.6    0.05       0  4661.1    0.16       0  4801.7    0.12       0
  4999.3    0.07       0  5005.3    0.12       0  5192.1    0.05       0
  5424.1    0.07       0  5528.3    0.05       0
Bank Sta=4816.6,5123.7
Exp/Cntr=0.3,0.1

Type RM Length L Ch R = 1,22643,379,379,379
BEGIN DESCRIPTION:
UNT 161 in LFCCL Watershed 32.0
END DESCRIPTION:
XS GIS Cut Line= 3
      2790950.84      7022952.79      2791075.00      7022675.00
      2791430.01      7022282.65
#Sta/Elev= 30
  4701.5  486.61  4710.0  486.60  4725.2  489.45  4748.4  486.50  4821.8  484.94
  4852.4  483.83  4863.4  485.71  4869.9  483.33  4893.1  483.37  4908.4  482.54
  4916.3  481.27  4921.8  479.57  4926.1  479.46  4926.6  478.66  4931.6  478.66
  4932.1  479.46  4942.1  479.46  5016.3  479.46  5055.5  479.53  5087.2  481.18
  5126.4  481.67  5140.6  482.91  5182.5  483.15  5223.2  484.94  5274.7  487.77
  5338.7  492.02  5422.9  496.57  5487.4  499.35  5533.0  502.66  5534.9  502.82
#Mann=10,-1,0
  4701.5    0.05       0  4908.4    0.07       0  4926.1   0.033       0
  4932.1    0.07       0  4942.1    0.05       0  5016.3    0.07       0
  5087.2    0.12       0  5274.7    0.05       0  5422.9    0.07       0
  5533.0    0.05       0
Bank Sta=4821.8,5223.2
Exp/Cntr=0.3,0.1

Type RM Length L Ch R = 1,22264,340,340,340
BEGIN DESCRIPTION:
UNT 161 in LFCCL Watershed 31.0
END DESCRIPTION:
XS GIS Cut Line= 3
      2790924.97      7023275.03      2791425.00      7022775.00
      2791625.00      7022525.00
#Sta/Elev= 30
  4270.7  490.55  4369.7  487.47  4431.9  486.62  4439.8  486.53  4525.3  486.60
  4539.4  486.25  4624.3  486.61  4652.6  486.22  4687.5  484.94  4751.6  484.08
  4794.0  482.95  4822.3  482.86  4845.3  481.78  4862.2  481.35  4918.3  479.46
  4918.8  478.66  4923.8  478.66  4924.3  479.46  5103.2  479.46  5141.9  479.46
  5148.3  479.86  5156.3  482.63  5161.3  484.94  5169.9  487.49  5172.9  487.95
  5226.1  493.46  5255.6  497.40  5262.0  498.63  5294.8  502.60  5298.0  502.60
#Mann=10,-1,0
  4270.7    0.05       0  4431.9    0.16       0  4439.8    0.05       0
  4845.3    0.07       0  4862.2    0.05       0  4918.3   0.033       0
  4924.3    0.05       0  5103.2    0.07       0  5172.9    0.12       0
  5226.1    0.05       0
Bank Sta=4687.5,5161.3
Exp/Cntr=0.3,0.1

Type RM Length L Ch R = 1,21924,372,372,372
BEGIN DESCRIPTION:
UNT 161 in LFCCL Watershed 30.0
END DESCRIPTION:
XS GIS Cut Line= 3
      2791225.03      7023624.96      2791625.00      7023025.00
      2791725.00      7022474.98
#Sta/Elev= 30
  4296.6  489.74  4304.1  488.46  4325.1  488.65  4340.1  486.93  4433.3  488.14
  4454.3  487.06  4535.4  485.77  4577.5  486.15  4613.5  485.18  4643.6  485.89
  4668.2  484.93  4801.3  481.75  4808.8  479.49  4820.9  479.46  4821.4  478.66
  4826.4  478.66  4826.9  479.46  4847.0  479.46  4853.9  479.46  5091.0  479.46
  5209.5  479.46  5231.1  481.66  5251.4  482.36  5267.8  480.95  5273.0  484.35
  5289.8  484.93  5379.8  491.19  5465.8  498.99  5515.7  504.08  5576.7  506.94
#Mann=8,-1,0
  4296.6    0.16       0  4820.9   0.033       0  4826.9    0.16       0
  4847.0    0.07       0  4853.9    0.05       0  5091.0    0.07       0
  5267.8    0.12       0  5465.8    0.05       0
Bank Sta=4668.2,5289.8
Exp/Cntr=0.3,0.1

Type RM Length L Ch R = 1,21552,40,40,40
BEGIN DESCRIPTION:
XS3905A
END DESCRIPTION:
XS GIS Cut Line= 6
      2791329.29      7023526.58      2791558.48      7023354.69
      2791727.75      7023339.07      2791829.31      7023320.84
      2791891.81      7023294.80      2792029.51      7022949.26
#Sta/Elev= 30
  4336.0  487.98  4341.9  487.32  4444.7  484.93  4465.8  484.70  4498.2  484.18
  4512.8  484.74  4548.2  483.37  4562.8  483.55  4583.6  482.36  4591.9  482.77
  4598.2  481.56  4612.8  482.29  4618.1  480.87  4629.0  481.86  4646.1  479.46
  4646.6  478.66  4651.6  478.66  4652.1  479.46  4747.7  479.46  4851.0  479.46
  4986.9  479.46  5057.5  479.46  5120.0  479.46  5144.3  480.96  5149.7  482.27
  5168.0  482.54  5175.6  484.93  5179.3  486.04  5257.6  490.89  5335.6  494.59
#Mann=8,-1,0
  4336.0    0.16       0  4465.8    0.12       0  4646.1   0.033       0
  4652.1    0.12       0  4747.7    0.07       0  4851.0    0.12       0
  4986.9    0.05       0  5057.5    0.12       0
Bank Sta=4444.7,5175.6
Exp/Cntr=0.3,0.1

Type RM Length L Ch R = 1,21512,83,83,83
BEGIN DESCRIPTION:
XS3906A
END DESCRIPTION:
XS GIS Cut Line= 6
      2791352.72      7023586.49      2791548.06      7023398.96
      2791837.13      7023359.90      2791902.23      7023333.86
      2791946.50      7023276.57      2792063.67      7022992.75
#Sta/Elev= 30
  4302.4  487.39  4485.9  485.49  4543.0  484.27  4580.1  484.43  4630.1  482.08
  4670.3  484.80  4721.2  485.91  4736.7  485.21  4748.6  484.28  4753.7  485.88
  4776.9  485.86  4861.6  484.85  4865.2  486.09  5011.6  486.80  5018.8  485.70
  5023.9  486.92  5043.2  485.89  5051.2  484.18  5056.6  486.87  5081.3  484.39
  5086.7  486.72  5098.9  486.82  5127.0  485.94  5130.9  481.77  5131.4  480.97
  5136.9  481.77  5139.4  485.09  5148.9  483.80  5158.6  484.27  5315.7  493.74
#Mann=6,-1,0
  4302.4    0.16       0  4485.9    0.12       0  4736.7    0.07       0
  4776.9    0.12       0  5130.9    0.07       0  5136.9    0.12       0
Bank Sta=4543,5158.6
Exp/Cntr=0.3,0.1

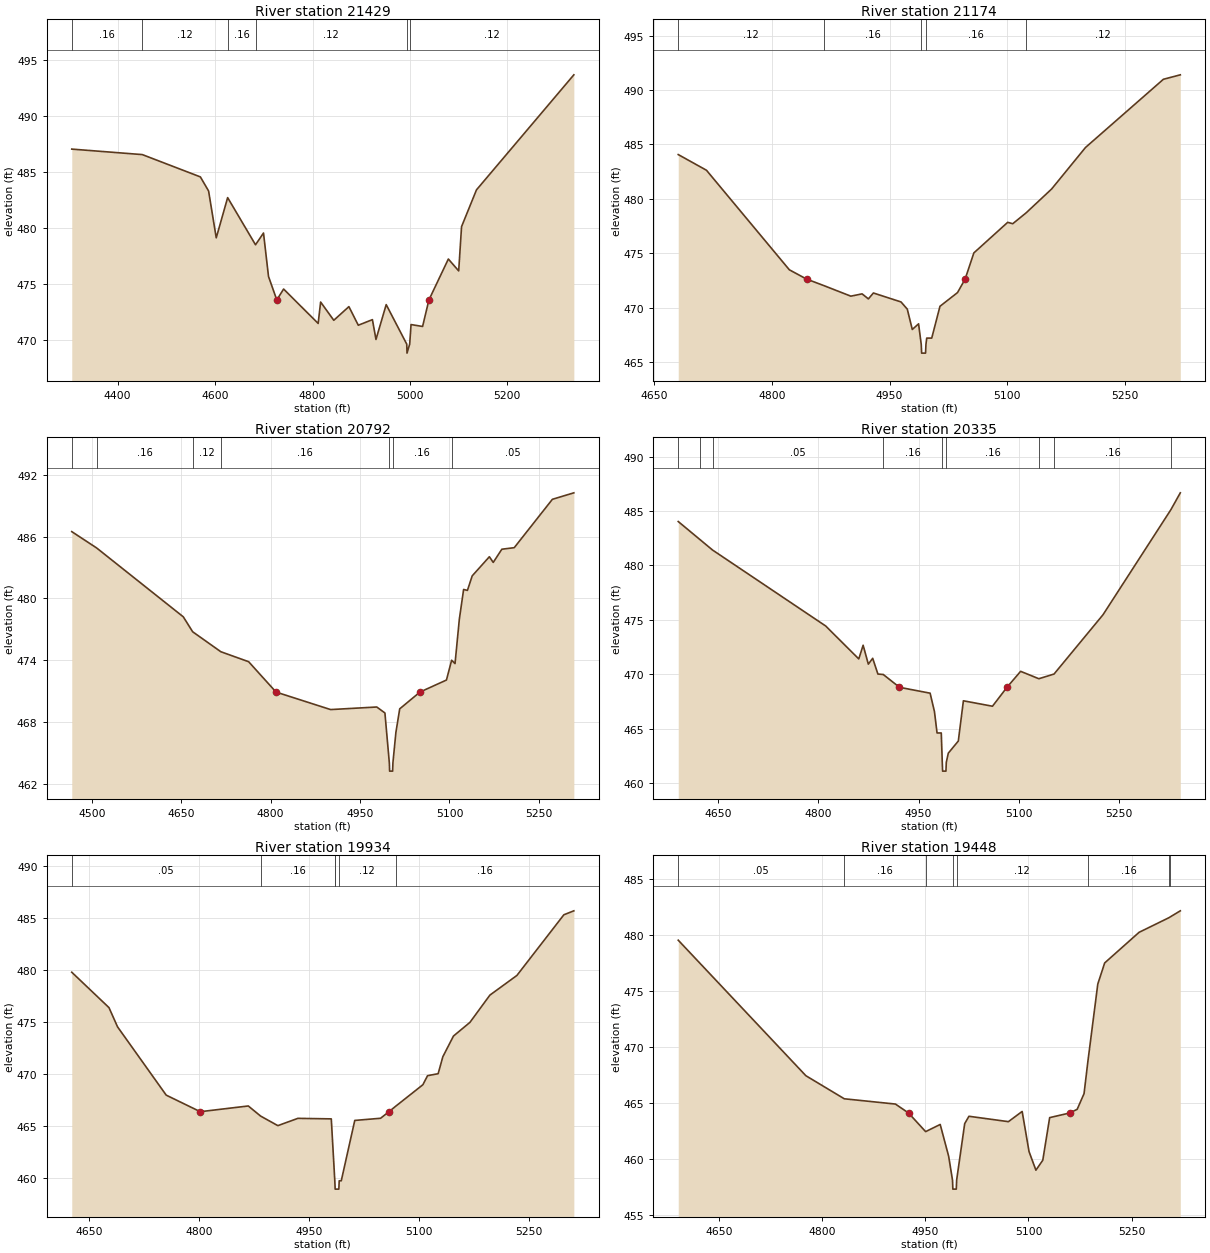
Type RM Length L Ch R = 1,21429,255,255,255
BEGIN DESCRIPTION:
XS3907A
END DESCRIPTION:
XS GIS Cut Line= 6
      2791391.79      7023599.50      2791743.38      7023451.05
      2791962.13      7023396.36      2791995.98      7023365.11
      2792035.04      7023279.17      2792185.95      7023039.80
#Sta/Elev= 30
  4305.8  487.03  4450.6  486.54  4569.8  484.55  4586.7  483.29  4602.4  479.11
  4625.8  482.70  4683.0  478.49  4699.4  479.54  4709.7  475.66  4726.7  473.57
  4740.7  474.54  4811.6  471.47  4816.7  473.38  4843.7  471.75  4874.7  472.97
  4894.0  471.31  4923.0  471.81  4930.3  470.04  4951.3  473.15  4993.5  469.62
  4994.0  468.82  4999.5  469.62  5002.3  471.37  5026.0  471.20  5039.0  473.57
  5078.9  477.22  5100.1  476.16  5106.0  480.11  5136.6  483.39  5336.5  493.66
#Mann=6,-1,0
  4305.8    0.16       0  4450.6    0.12       0  4625.8    0.16       0
  4683.0    0.12       0  4993.5    0.07       0  4999.5    0.12       0
Bank Sta=4726.7,5039
Exp/Cntr=0.3,0.1

Type RM Length L Ch R = 1,21174,382,382,382
BEGIN DESCRIPTION:
UNT 161 in LFCCL Watershed 28.0
END DESCRIPTION:
XS GIS Cut Line= 3
      2791875.01      7023674.99      2792125.00      7023475.00
      2792325.00      7023225.00
#Sta/Elev= 30
  4680.5  484.07  4716.5  482.63  4822.2  473.49  4844.1  472.64  4866.2  472.04
  4900.6  471.07  4915.0  471.28  4923.0  470.82  4929.4  471.36  4964.6  470.54
  4972.6  469.88  4979.0  468.01  4987.0  468.53  4990.4  466.64  4990.9  465.84
  4995.9  465.84  4996.4  466.64  4997.4  467.22  5003.8  467.22  5014.3  470.14
  5036.7  471.40  5046.4  472.64  5057.5  475.04  5100.7  477.85  5107.1  477.72
  5124.2  478.72  5156.7  480.91  5199.9  484.72  5299.2  490.98  5320.8  491.39
#Mann=5,-1,0
  4680.5    0.12       0  4866.2    0.16       0  4990.4    0.07       0
  4996.4    0.16       0  5124.2    0.12       0
Bank Sta=4844.1,5046.4
Exp/Cntr=0.3,0.1

Type RM Length L Ch R = 1,20792,457,457,457
BEGIN DESCRIPTION:
UNT 161 in LFCCL Watershed 27.0
END DESCRIPTION:
XS GIS Cut Line= 3
      2791874.96      7023825.01      2792375.00      7023675.00
      2792574.99      7023425.01
#Sta/Elev= 30
  4466.4  486.48  4508.2  484.89  4653.5  478.20  4669.2  476.75  4716.5  474.81
  4763.1  473.84  4809.1  470.89  4900.6  469.19  4978.0  469.44  4991.7  468.86
  4999.1  464.01  4999.6  463.21  5004.6  463.21  5005.1  464.01  5010.1  466.97
  5016.5  469.26  5050.4  470.89  5094.9  472.06  5103.6  473.98  5109.3  473.66
  5116.5  477.96  5123.7  480.86  5130.1  480.77  5138.1  482.18  5166.9  484.04
  5173.4  483.49  5187.8  484.77  5208.6  484.92  5272.6  489.62  5308.6  490.25
#Mann=7,-1,0
  4466.4    0.12       0  4508.2    0.16       0  4669.2    0.12       0
  4716.5    0.16       0  4999.1    0.07       0  5005.1    0.16       0
  5103.6    0.05       0
Bank Sta=4809.1,5050.4
Exp/Cntr=0.3,0.1

Type RM Length L Ch R = 1,20335,401,401,401
BEGIN DESCRIPTION:
UNT 161 in LFCCL Watershed 26.0
END DESCRIPTION:
XS GIS Cut Line= 3
      2792325.01      7024174.99      2792625.00      7023925.00
      2792825.02      7023624.96
#Sta/Elev= 30
  4590.4  484.04  4623.1  482.37  4641.7  481.42  4811.0  474.43  4860.5  471.40
  4867.0  472.66  4874.8  470.92  4881.3  471.46  4889.1  470.01  4897.1  469.97
  4921.4  468.79  4967.2  468.25  4973.7  466.56  4977.6  464.59  4983.9  464.59
  4985.4  461.88  4985.9  461.08  4990.9  461.08  4991.4  461.88  4994.4  462.73
  5009.4  463.85  5017.0  467.55  5060.5  467.05  5082.2  468.79  5102.6  470.26
  5129.9  469.58  5152.6  470.01  5225.8  475.46  5327.4  485.13  5341.5  486.68
#Mann=9,-1,0
  4590.4    0.05       0  4623.1    0.08       0  4641.7    0.05       0
  4897.1    0.16       0  4985.4    0.07       0  4991.4    0.16       0
  5129.9    0.12       0  5152.6    0.16       0  5327.4    0.05       0
Bank Sta=4921.4,5082.2
Exp/Cntr=0.3,0.1

Type RM Length L Ch R = 1,19934,486,486,486
BEGIN DESCRIPTION:
UNT 161 in LFCCL Watershed 25.0
END DESCRIPTION:
XS GIS Cut Line= 3
      2792825.01      7024424.98      2792925.00      7024075.00
      2793124.98      7023825.03
#Sta/Elev= 30
  4626.5  479.79  4677.2  476.39  4688.9  474.54  4755.2  467.98  4801.6  466.39
  4867.0  466.94  4883.8  465.97  4907.3  465.05  4934.6  465.75  4980.1  465.70
  4984.8  459.87  4984.9  459.75  4985.4  458.95  4990.4  458.95  4990.9  459.75
  4993.7  459.75  5012.1  465.55  5047.3  465.76  5058.7  466.39  5067.6  466.90
  5104.9  468.98  5111.3  469.85  5125.7  470.04  5132.1  471.67  5146.6  473.66
  5169.0  474.97  5196.2  477.59  5233.0  479.48  5297.0  485.31  5310.6  485.69
#Mann=6,-1,0
  4626.5    0.05       0  4883.8    0.16       0  4984.8    0.12       0
  4984.9    0.07       0  4990.9    0.12       0  5067.6    0.16       0
Bank Sta=4801.6,5058.7
Exp/Cntr=0.3,0.1

Type RM Length L Ch R = 1,19448,513,513,513
BEGIN DESCRIPTION:
UNT 161 in LFCCL Watershed 24.0
END DESCRIPTION:
XS GIS Cut Line= 3
      2792974.98      7024575.03      2793225.00      7024225.00
      2793225.00      7023924.95
#Sta/Elev= 30
  4590.6  479.56  4776.2  467.47  4832.1  465.41  4906.5  464.94  4925.6  464.14
  4950.4  462.48  4971.6  463.12  4983.9  460.28  4989.5  458.15  4990.0  457.35
  4995.0  457.35  4995.5  458.15  5007.2  463.19  5013.4  463.85  5070.8  463.37
  5090.8  464.28  5100.8  460.70  5110.8  459.04  5120.8  459.93  5130.8  463.73
  5159.7  464.14  5170.8  464.47  5180.8  465.87  5186.4  468.75  5200.8  475.65
  5210.8  477.53  5260.8  480.26  5304.7  481.58  5305.4  481.61  5320.8  482.18
#Mann=8,-1,0
  4590.6    0.05       0  4832.1    0.16       0  4950.4    0.12       0
  4989.5    0.07       0  4995.5    0.12       0  5186.4    0.16       0
  5304.7    0.12       0  5305.4    0.16       0
Bank Sta=4925.6,5159.7
Exp/Cntr=0.3,0.1

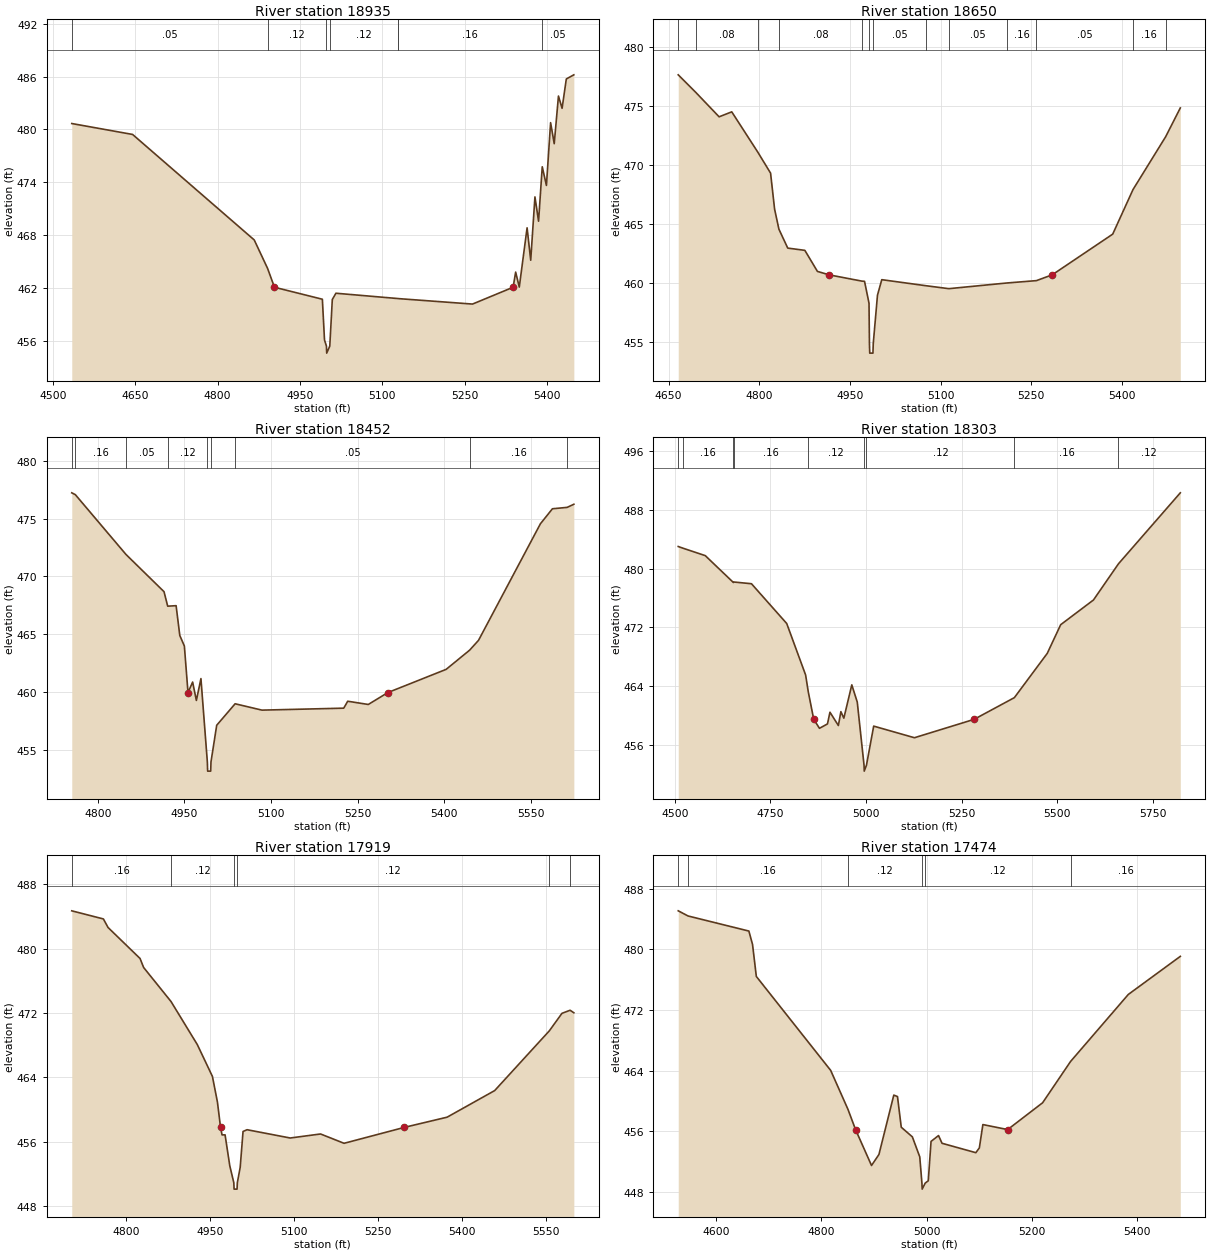
Type RM Length L Ch R = 1,18935,285,285,285
BEGIN DESCRIPTION:
UNT 161 in LFCCL Watershed 23.0
END DESCRIPTION:
XS GIS Cut Line= 3
      2792924.95      7024624.99      2793375.00      7024675.00
      2793725.00      7024375.00
#Sta/Elev= 30
  4534.6  480.67  4645.3  479.43  4866.7  467.45  4891.0  464.22  4903.5  462.08
  4990.7  460.72  4994.6  456.09  4998.1  455.40  4998.6  454.60  5004.2  455.40
  5008.8  460.69  5015.4  461.40  5127.7  460.80  5129.0  460.79  5264.0  460.17
  5337.9  462.08  5342.5  463.80  5349.1  462.10  5363.3  468.83  5369.9  465.15
  5377.6  472.34  5384.2  469.58  5390.9  475.76  5398.5  473.64  5406.1  480.77
  5412.7  478.38  5420.4  483.79  5427.0  482.40  5434.7  485.73  5448.4  486.20
#Mann=7,-1,0
  4534.6    0.05       0  4891.0    0.12       0  4998.1    0.07       0
  5004.2    0.12       0  5127.7    0.07       0  5129.0    0.16       0
  5390.9    0.05       0
Bank Sta=4903.5,5337.9
Exp/Cntr=0.3,0.1

Type RM Length L Ch R = 1,18650,198,198,198
BEGIN DESCRIPTION:
XS3908A
END DESCRIPTION:
XS GIS Cut Line= 3
      2793149.59      7025155.07      2793385.74      7024939.76
      2793743.39      7024575.17
#Sta/Elev= 30
  4666.1  477.61  4695.6  476.10  4733.7  474.06  4754.6  474.48  4797.6  471.08
  4818.8  469.30  4825.5  466.24  4832.6  464.56  4847.2  462.96  4875.5  462.77
  4896.3  460.99  4915.5  460.70  4969.6  460.17  4974.2  460.15  4981.6  458.30
  4982.3  454.88  4982.8  454.08  4988.1  454.08  4988.6  454.88  4995.6  458.98
  5002.7  460.29  5075.6  459.78  5113.6  459.53  5209.6  460.01  5258.5  460.21
  5284.6  460.70  5384.6  464.14  5418.2  467.91  5472.1  472.37  5496.4  474.81
#Mann=13,-1,0
  4666.1    0.16       0  4695.6    0.08       0  4797.6    0.05       0
  4832.6    0.08       0  4969.6    0.05       0  4982.3    0.04       0
  4988.6    0.05       0  5075.6    0.16       0  5113.6    0.05       0
  5209.6    0.16       0  5258.5    0.05       0  5418.2    0.16       0
  5472.1    0.05       0
Bank Sta=4915.5,5284.6
Exp/Cntr=0.3,0.1

Type RM Length L Ch R = 1,18452,149,149,149
BEGIN DESCRIPTION:
XS3909A
END DESCRIPTION:
XS GIS Cut Line= 4
      2793264.18      7025238.41      2793430.88      7025036.99
      2793691.29      7024790.46      2793885.74      7024634.21
#Sta/Elev= 30
  4754.8  477.23  4761.0  477.07  4848.6  471.90  4914.6  468.67  4920.9  467.42
  4935.5  467.46  4941.9  464.88  4949.8  463.97  4956.1  459.94  4964.1  460.85
  4970.6  459.26  4978.5  461.15  4989.6  453.94  4990.1  453.14  4995.4  453.14
  4995.9  453.94  5005.8  457.11  5037.7  458.97  5084.2  458.42  5225.8  458.59
  5232.7  459.19  5268.3  458.91  5302.2  459.94  5403.2  461.95  5443.8  463.61
  5459.2  464.46  5566.4  474.55  5587.2  475.85  5612.7  475.97  5624.3  476.24
#Mann=9,-1,0
  4754.8    0.05       0  4761.0    0.16       0  4848.6    0.05       0
  4920.9    0.12       0  4989.6    0.07       0  4995.9    0.12       0
  5037.7    0.05       0  5443.8    0.16       0  5612.7    0.05       0
Bank Sta=4956.1,5302.2
Exp/Cntr=0.3,0.1

Type RM Length L Ch R = 1,18303,384,384,384
BEGIN DESCRIPTION:
UNT 161 in LFCCL Watershed 22.0
END DESCRIPTION:
XS GIS Cut Line= 3
      2793154.20      7025454.14      2793504.17      7025154.17
      2794154.16      7024604.17
#Sta/Elev= 30
  4509.2  482.99  4522.2  482.75  4579.9  481.75  4653.3  478.10  4655.3  478.16
  4700.6  477.93  4792.8  472.52  4842.2  465.52  4849.2  463.21  4863.4  459.49
  4878.4  458.27  4899.3  458.87  4905.8  460.46  4927.8  458.65  4934.4  460.54
  4942.1  459.65  4962.9  464.18  4977.2  461.83  4994.9  453.25  4995.4  452.45
  5001.2  453.25  5020.1  458.57  5126.6  456.99  5282.6  459.49  5387.8  462.44
  5473.8  468.46  5508.9  472.36  5594.6  475.72  5659.8  480.63  5821.6  490.29
#Mann=9,-1,0
  4509.2    0.05       0  4522.2    0.16       0  4653.3    0.05       0
  4655.3    0.16       0  4849.2    0.12       0  4994.9    0.07       0
  5001.2    0.12       0  5387.8    0.16       0  5659.8    0.12       0
Bank Sta=4863.4,5282.6
Exp/Cntr=0.3,0.1

Type RM Length L Ch R = 1,17919,445,445,445
BEGIN DESCRIPTION:
XS3910A
END DESCRIPTION:
XS GIS Cut Line= 4
      2793482.97      7025582.11      2793632.26      7025356.43
      2793666.99      7025210.60      2794014.18      7024884.24
#Sta/Elev= 30
  4703.6  484.72  4760.1  483.71  4768.4  482.65  4825.6  478.79  4832.0  477.67
  4880.9  473.44  4927.9  468.08  4954.9  464.12  4963.9  460.91  4969.4  457.78
  4972.1  456.85  4977.5  456.85  4985.9  453.01  4993.1  450.90  4993.6  450.10
  4998.9  450.10  4999.4  450.90  5004.5  452.81  5009.6  457.27  5016.8  457.49
  5093.9  456.46  5148.1  456.96  5190.1  455.80  5297.7  457.78  5374.2  459.05
  5459.2  462.36  5556.8  469.79  5579.4  471.97  5593.9  472.35  5600.6  472.04
#Mann=6,-1,0
  4703.6    0.16       0  4880.9    0.12       0  4993.1    0.07       0
  4999.4    0.12       0  5556.8    0.16       0  5593.9    0.12       0
Bank Sta=4969.4,5297.7
Exp/Cntr=0.3,0.1

Type RM Length L Ch R = 1,17474,578,578,578
BEGIN DESCRIPTION:
UNT 161 in LFCCL Watershed 21.0
END DESCRIPTION:
XS GIS Cut Line= 3
      2793574.99      7025675.01      2793903.01      7025334.79
      2794224.98      7024975.02
#Sta/Elev= 30
  4527.4  485.08  4546.1  484.40  4661.8  482.41  4668.8  480.64  4676.0  476.42
  4817.5  464.02  4850.5  458.86  4864.8  456.21  4895.2  451.47  4909.3  452.92
  4937.6  460.76  4944.6  460.57  4951.8  456.52  4972.9  455.25  4987.0  452.61
  4991.1  449.15  4991.6  448.35  4997.4  449.15  5003.2  449.45  5008.5  454.65
  5022.7  455.42  5029.4  454.40  5093.7  453.16  5100.4  453.79  5107.1  456.87
  5154.3  456.21  5220.8  459.75  5274.0  465.20  5383.8  474.04  5482.8  479.07
#Mann=6,-1,0
  4527.4    0.05       0  4546.1    0.16       0  4850.5    0.12       0
  4991.1    0.07       0  4997.4    0.12       0  5274.0    0.16       0
Bank Sta=4864.8,5154.3
Exp/Cntr=0.3,0.1

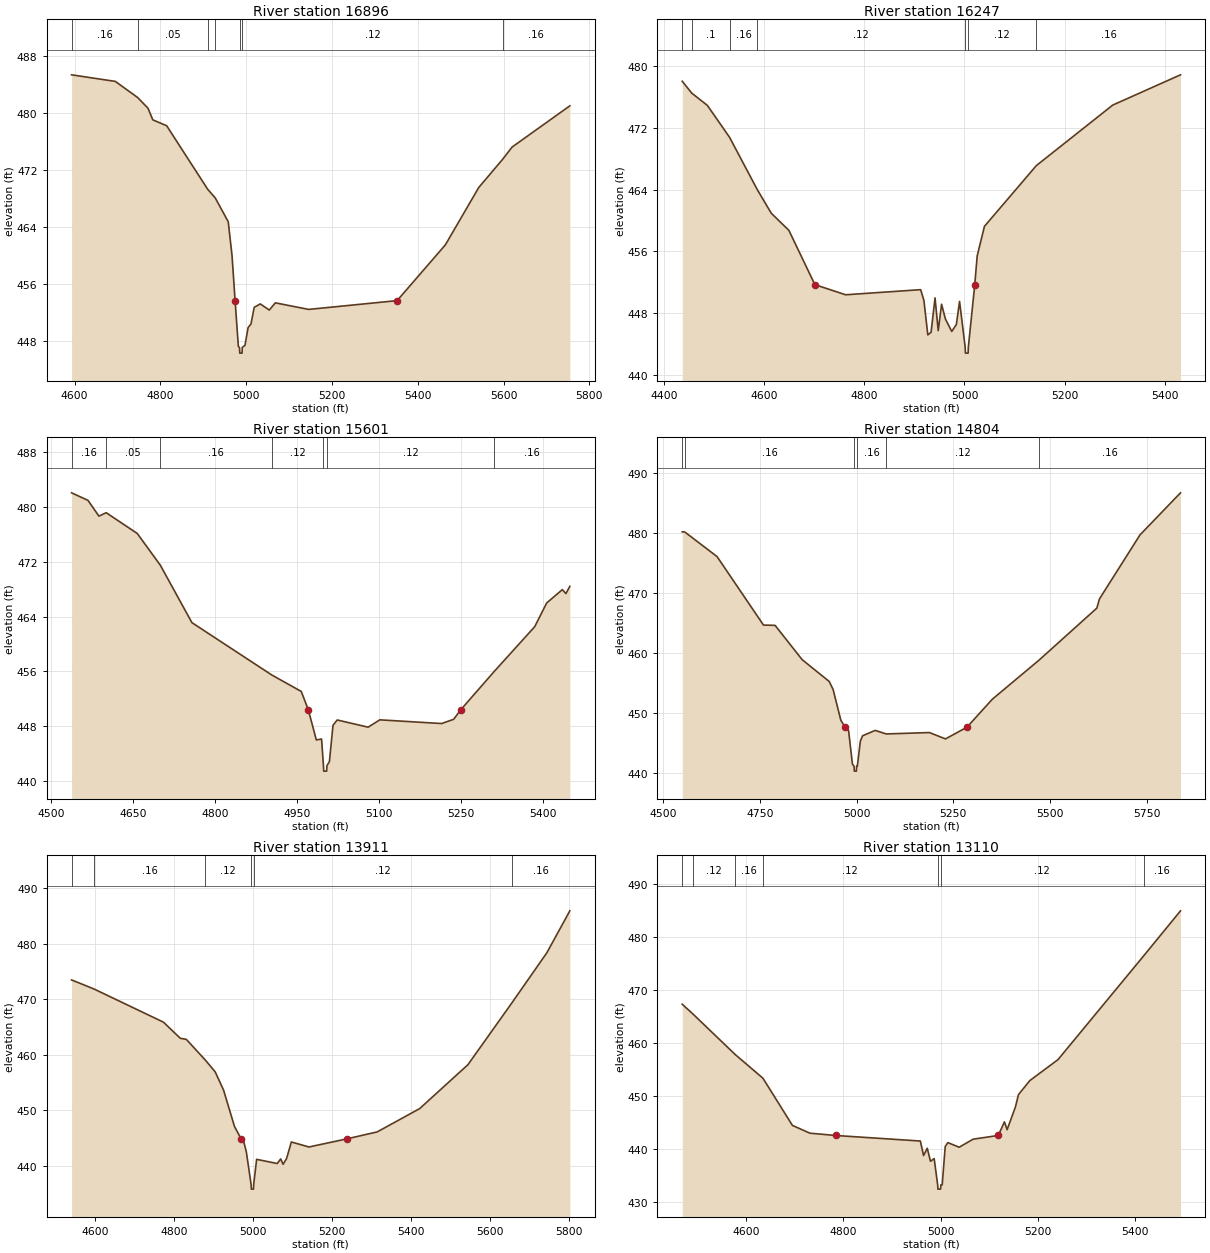
Type RM Length L Ch R = 1,16896,649,649,649
BEGIN DESCRIPTION:
UNT 161 in LFCCL Watershed 20.0
END DESCRIPTION:
XS GIS Cut Line= 3
      2793641.25      7025892.59      2794008.09      7025735.30
      2794525.03      7025174.97
#Sta/Elev= 30
  4592.9  485.32  4694.9  484.40  4747.0  482.14  4771.1  480.64  4782.2  479.02
  4814.6  478.19  4910.3  469.29  4927.8  468.09  4958.1  464.75  4966.9  460.04
  4974.1  453.71  4981.7  447.29  4984.4  447.16  4984.9  446.36  4990.3  446.36
  4990.8  447.16  4997.1  447.45  5004.4  449.93  5011.2  450.45  5018.6  452.77
  5032.8  453.25  5053.8  452.39  5067.9  453.40  5145.6  452.48  5351.8  453.71
  5464.3  461.52  5542.0  469.54  5598.1  473.52  5619.7  475.20  5754.4  480.98
#Mann=7,-1,0
  4592.9    0.16       0  4747.0    0.05       0  4910.3    0.16       0
  4927.8    0.12       0  4984.4    0.07       0  4990.8    0.12       0
  5598.1    0.16       0
Bank Sta=4974.1,5351.8
Exp/Cntr=0.3,0.1

Type RM Length L Ch R = 1,16247,646,646,646
BEGIN DESCRIPTION:
UNT 161 in LFCCL Watershed 19.0
END DESCRIPTION:
XS GIS Cut Line= 3
      2794025.04      7026124.97      2794441.34      7025782.22
      2794725.00      7025424.99
#Sta/Elev= 30
  4436.2  477.99  4455.3  476.45  4486.4  474.87  4530.7  470.75  4586.1  463.99
  4614.1  460.93  4649.2  458.73  4701.2  451.71  4762.6  450.40  4912.5  451.06
  4919.0  449.66  4926.8  445.22  4933.3  445.55  4941.2  450.00  4947.6  445.77
  4954.3  449.18  4962.0  447.26  4974.6  445.66  4983.8  446.56  4990.2  449.54
  5001.4  443.66  5001.9  442.86  5007.3  442.86  5007.8  443.66  5020.6  451.71
  5025.4  455.41  5039.9  459.24  5143.6  467.09  5296.2  474.91  5431.6  478.82
#Mann=7,-1,0
  4436.2    0.05       0  4455.3     0.1       0  4530.7    0.16       0
  4586.1    0.12       0  5001.4    0.07       0  5007.8    0.12       0
  5143.6    0.16       0
Bank Sta=4701.2,5020.6
Exp/Cntr=0.3,0.1

Type RM Length L Ch R = 1,15601,797,797,797
BEGIN DESCRIPTION:
UNT 161 in LFCCL Watershed 18.0
END DESCRIPTION:
XS GIS Cut Line= 3
      2793975.01      7026175.00      2794425.00      7026175.00
      2794725.02      7025824.98
#Sta/Elev= 30
  4537.9  482.05  4567.9  480.95  4587.9  478.65  4601.2  479.15  4657.9  476.13
  4700.2  471.49  4757.9  463.12  4903.8  455.49  4957.9  453.08  4970.8  450.39
  4985.4  446.01  4995.0  446.14  4998.4  442.26  4998.9  441.46  5004.3  441.46
  5004.8  442.26  5009.3  442.84  5015.9  448.15  5023.6  448.92  5080.1  447.87
  5101.5  448.94  5214.5  448.40  5236.5  449.02  5249.3  450.39  5309.9  455.93
  5384.7  462.53  5406.6  465.99  5435.2  467.93  5441.7  467.35  5448.9  468.41
#Mann=7,-1,0
  4537.9    0.16       0  4601.2    0.05       0  4700.2    0.16       0
  4903.8    0.12       0  4998.4    0.07       0  5004.8    0.12       0
  5309.9    0.16       0
Bank Sta=4970.8,5249.3
Exp/Cntr=0.3,0.1

Type RM Length L Ch R = 1,14804,893,893,893
BEGIN DESCRIPTION:
UNT 161 in LFCCL Watershed 17.0
END DESCRIPTION:
XS GIS Cut Line= 3
      2794125.01      7026425.00      2794575.00      7026425.00
      2795374.96      7026175.01
#Sta/Elev= 30
  4549.2  480.16  4555.6  480.15  4639.2  476.05  4759.2  464.65  4789.2  464.60
  4859.2  458.89  4929.2  455.26  4939.2  453.93  4959.2  448.81  4970.1  447.65
  4979.2  447.09  4989.2  441.51  4993.5  441.14  4994.0  440.34  4999.4  440.34
  4999.9  441.14  5001.8  441.14  5009.7  445.34  5015.4  446.22  5047.9  447.12
  5076.5  446.53  5188.3  446.76  5229.7  445.70  5285.2  447.65  5350.7  452.30
  5471.9  458.83  5621.0  467.47  5627.8  469.00  5732.6  479.66  5837.3  486.66
#Mann=6,-1,0
  4549.2    0.05       0  4555.6    0.16       0  4993.5    0.07       0
  4999.9    0.16       0  5076.5    0.12       0  5471.9    0.16       0
Bank Sta=4970.1,5285.2
Exp/Cntr=0.3,0.1

Type RM Length L Ch R = 1,13911,801,801,801
BEGIN DESCRIPTION:
UNT 161 in LFCCL Watershed 16.0
END DESCRIPTION:
XS GIS Cut Line= 3
      2794424.99      7027025.00      2794825.00      7026775.00
      2795475.02      7026324.99
#Sta/Elev= 30
  4540.0  473.51  4596.4  471.89  4772.9  465.89  4815.4  462.99  4830.7  462.79
  4879.1  459.04  4903.8  456.94  4925.0  453.66  4952.7  447.09  4969.5  444.86
  4976.3  444.31  4982.8  442.49  4994.9  436.59  4995.4  435.79  5000.8  435.79
  5001.3  436.59  5008.8  441.16  5061.0  440.41  5069.8  441.23  5075.9  440.27
  5084.7  441.30  5096.8  444.29  5141.4  443.39  5237.9  444.86  5314.4  446.11
  5421.9  450.31  5544.2  458.23  5654.6  469.28  5744.2  478.42  5802.3  485.97
#Mann=6,-1,0
  4540.0    0.12       0  4596.4    0.16       0  4879.1    0.12       0
  4994.9    0.07       0  5001.3    0.12       0  5654.6    0.16       0
Bank Sta=4969.5,5237.9
Exp/Cntr=0.3,0.1

Type RM Length L Ch R = 1,13110,582,582,582
BEGIN DESCRIPTION:
UNT 161 in LFCCL Watershed 15.0
END DESCRIPTION:
XS GIS Cut Line= 3
      2794925.01      7027174.99      2795325.00      7026825.00
      2795524.98      7026375.04
#Sta/Elev= 30
  4468.8  467.36  4490.0  465.59  4577.6  457.88  4634.6  453.41  4695.2  444.51
  4731.2  443.04  4783.9  442.61  4958.1  441.56  4964.7  438.83  4972.3  440.20
  4978.9  437.74  4986.5  438.24  4993.7  433.29  4994.2  432.49  4999.7  432.49
  5000.2  433.29  5003.0  433.29  5009.2  440.53  5014.7  441.26  5037.9  440.39
  5066.6  441.91  5118.3  442.61  5130.9  445.18  5136.4  443.70  5153.5  447.99
  5159.7  450.31  5182.9  452.95  5241.0  456.92  5417.4  476.53  5492.7  484.98
#Mann=7,-1,0
  4468.8    0.16       0  4490.0    0.12       0  4577.6    0.16       0
  4634.6    0.12       0  4993.7    0.07       0  5000.2    0.12       0
  5417.4    0.16       0
Bank Sta=4783.9,5118.3
Exp/Cntr=0.3,0.1