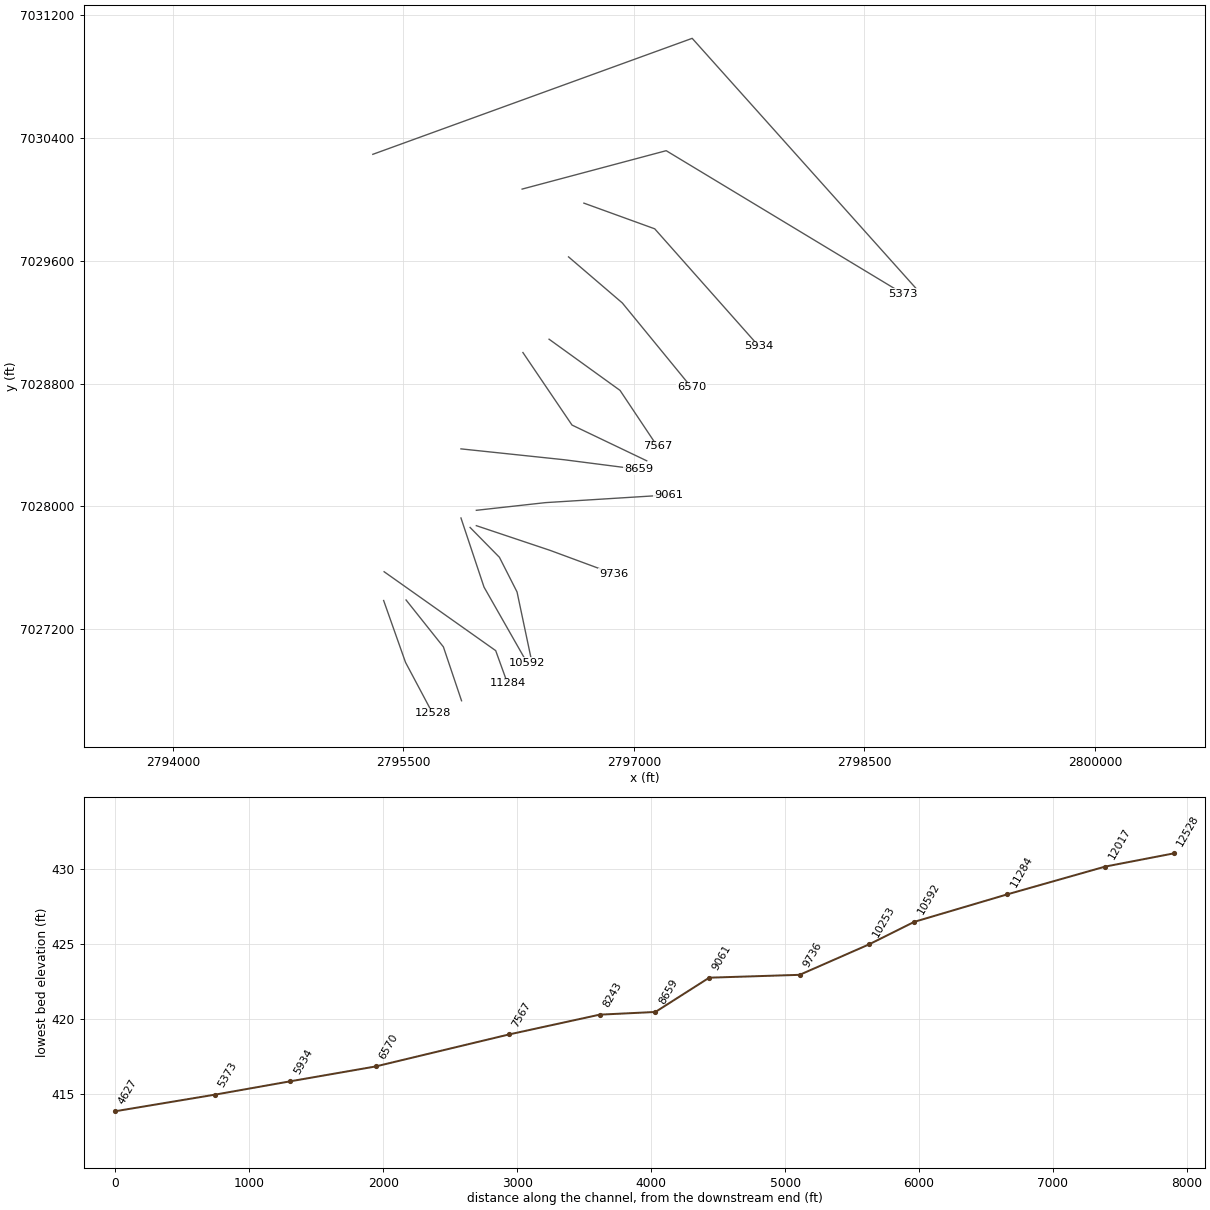
HEC-RAS study UNT 161 in LFCCL Watershed.prj: UNT 161 in LFCCL Watershed Base Level Engineering

--- UNT 161 in LFCCL Watershed.g01 (geometry) --- (continued)

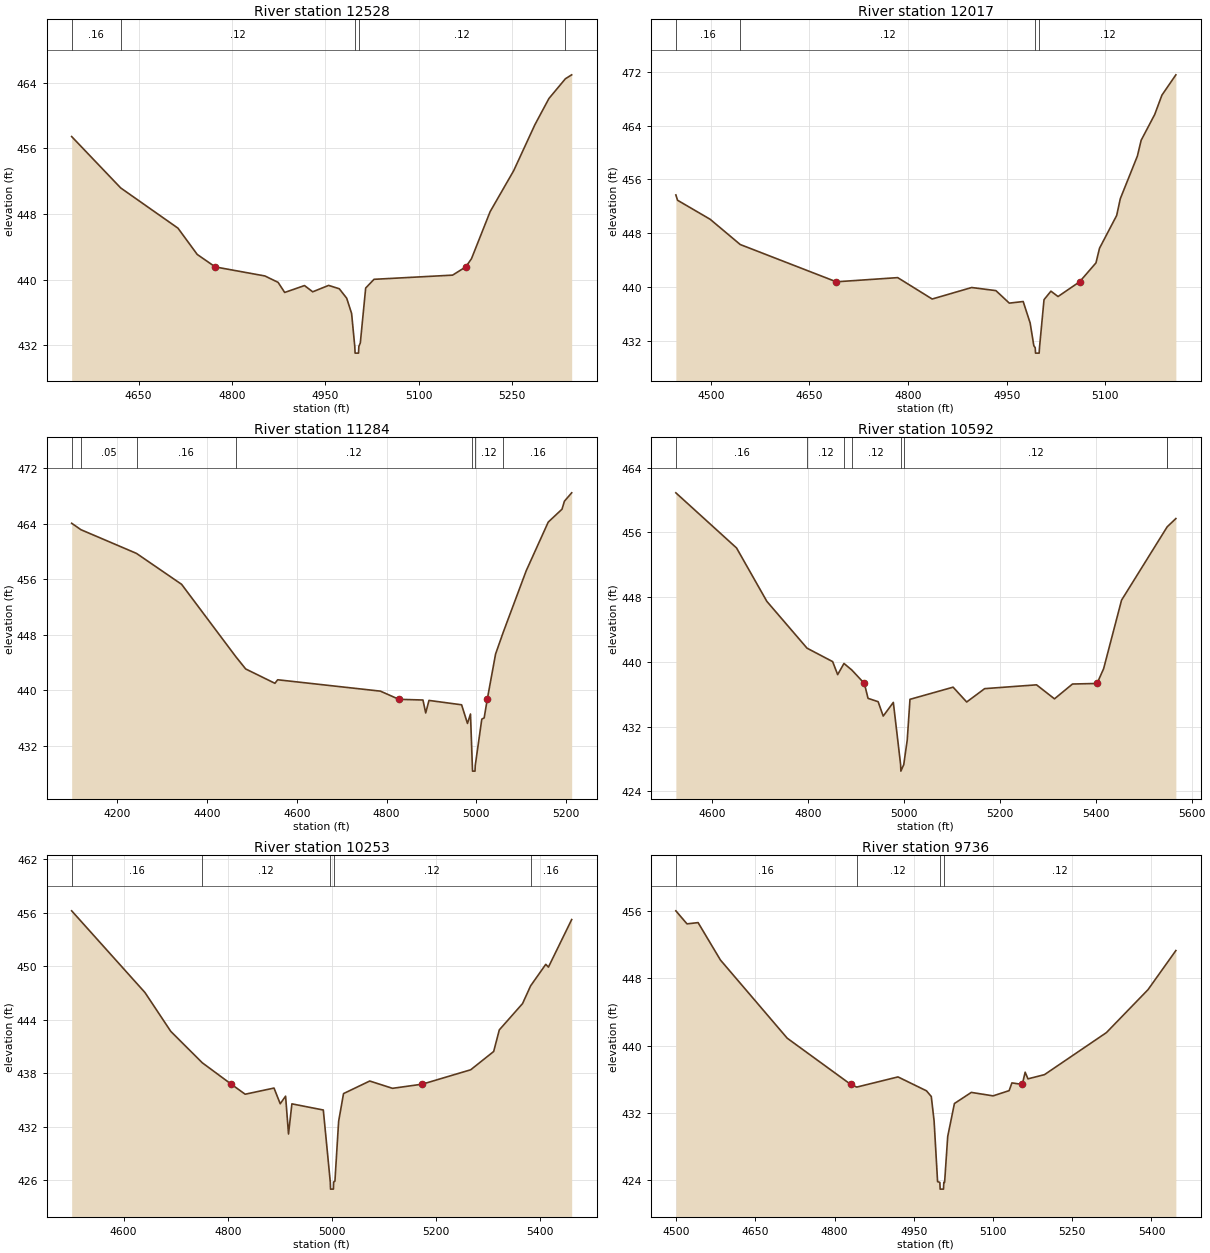
Type RM Length L Ch R = 1,12528,511,511,511
BEGIN DESCRIPTION:
XS3911A
END DESCRIPTION:
XS GIS Cut Line= 3
      2795371.86      7027387.63      2795514.21      7026984.90
      2795690.64      7026652.80
#Sta/Elev= 30
  4542.4  457.45  4621.2  451.19  4713.2  446.29  4744.1  443.09  4773.1  441.57
  4852.8  440.47  4874.0  439.69  4884.6  438.46  4916.4  439.30  4929.6  438.54
  4955.2  439.32  4972.3  438.91  4984.2  437.76  4992.1  435.90  4997.2  431.87
  4997.7  431.07  5003.2  431.07  5003.7  431.87  5006.1  432.32  5014.7  439.00
  5028.1  440.06  5154.3  440.57  5175.4  441.57  5184.6  442.56  5214.6  448.30
  5252.5  453.30  5286.5  458.89  5309.1  462.09  5335.5  464.49  5345.6  464.97
#Mann=5,-1,0
  4542.4    0.16       0  4621.2    0.12       0  4997.2    0.07       0
  5003.7    0.12       0  5335.5    0.16       0
Bank Sta=4773.1,5175.4
Exp/Cntr=0.3,0.1

Type RM Length L Ch R = 1,12017,733,733,733
BEGIN DESCRIPTION:
XS3912A
END DESCRIPTION:
XS GIS Cut Line= 3
      2795517.69      7027391.14      2795760.74      7027085.60
      2795878.78      7026734.95
#Sta/Elev= 30
  4446.9  453.70  4449.5  452.91  4499.1  450.08  4544.8  446.33  4690.9  440.79
  4784.3  441.41  4836.7  438.23  4896.8  439.94  4933.6  439.48  4954.0  437.62
  4975.1  437.86  4985.7  434.67  4991.3  431.29  4993.4  430.99  4993.9  430.19
  4999.4  430.19  4999.9  430.99  5006.8  438.13  5017.3  439.40  5028.1  438.60
  5060.9  440.79  5085.8  443.60  5091.2  445.78  5117.3  450.65  5122.8  453.14
  5148.8  459.48  5154.5  461.82  5175.1  465.65  5186.1  468.53  5207.3  471.55
#Mann=4,-1,0
  4446.9    0.16       0  4544.8    0.12       0  4993.4    0.07       0
  4999.9    0.12       0
Bank Sta=4690.9,5060.9
Exp/Cntr=0.3,0.1

Type RM Length L Ch R = 1,11284,692,692,692
BEGIN DESCRIPTION:
UNT 161 in LFCCL Watershed 14.0
END DESCRIPTION:
XS GIS Cut Line= 3
      2795374.96      7027575.03      2796101.01      7027061.29
      2796177.31      7026849.75
#Sta/Elev= 30
  4098.0  464.09  4118.7  463.16  4242.5  459.74  4343.0  455.28  4463.6  444.86
  4485.8  443.07  4551.0  441.00  4557.1  441.51  4786.0  439.87  4827.3  438.69
  4880.9  438.59  4887.0  436.72  4894.3  438.53  4967.0  437.90  4980.1  435.21
  4986.8  436.57  4990.9  429.13  4991.4  428.33  4996.9  428.33  4997.4  429.13
  5012.0  435.83  5017.3  436.01  5024.2  438.69  5042.7  445.22  5059.6  448.33
  5111.0  457.24  5160.1  464.26  5190.8  466.12  5196.1  467.27  5212.3  468.48
#Mann=7,-1,0
  4098.0    0.16       0  4118.7    0.05       0  4242.5    0.16       0
  4463.6    0.12       0  4990.9    0.07       0  4997.4    0.12       0
  5059.6    0.16       0
Bank Sta=4827.3,5024.2
Exp/Cntr=0.3,0.1

Type RM Length L Ch R = 1,10592,339,339,339
BEGIN DESCRIPTION:
UNT 161 in LFCCL Watershed 13.0
END DESCRIPTION:
XS GIS Cut Line= 3
      2795875.00      7027925.00      2796025.00      7027475.00
      2796305.86      7026981.46
#Sta/Elev= 30
  4524.9  460.88  4651.4  454.07  4714.6  447.47  4798.3  441.69  4851.7  440.03
  4862.2  438.42  4875.3  439.80  4891.5  439.00  4917.8  437.33  4925.5  435.49
  4946.5  435.08  4957.1  433.30  4978.2  434.99  4993.4  427.30  4993.9  426.50
  4999.9  427.30  5007.2  430.35  5012.9  435.37  5102.8  436.87  5131.1  435.04
  5168.6  436.69  5276.7  437.16  5314.1  435.43  5351.6  437.26  5402.8  437.33
  5416.5  439.15  5453.9  447.62  5548.7  456.65  5549.2  456.69  5567.1  457.70
#Mann=8,-1,0
  4524.9    0.16       0  4798.3    0.12       0  4875.3    0.16       0
  4891.5    0.12       0  4993.4    0.07       0  4999.9    0.12       0
  5548.7    0.16       0  5549.2    0.12       0
Bank Sta=4917.8,5402.8
Exp/Cntr=0.3,0.1

Type RM Length L Ch R = 1,10253,517,517,517
BEGIN DESCRIPTION:
XS3913A
END DESCRIPTION:
XS GIS Cut Line= 4
      2795934.37      7027863.35      2796125.32      7027668.93
      2796239.90      7027443.24      2796329.68      7027018.54
#Sta/Elev= 30
  4500.5  456.19  4641.2  447.03  4690.7  442.68  4751.1  439.16  4806.7  436.76
  4833.5  435.63  4888.9  436.32  4900.8  434.56  4911.1  435.41  4916.7  431.17
  4923.2  434.55  4983.5  433.86  4996.9  425.79  4997.4  424.99  5002.9  424.99
  5003.4  425.79  5005.8  425.88  5012.9  432.58  5022.3  435.70  5072.6  437.11
  5116.3  436.29  5173.7  436.76  5266.4  438.37  5310.5  440.42  5321.3  442.84
  5365.9  445.79  5381.4  447.78  5410.5  450.19  5415.6  449.88  5460.2  455.21
#Mann=5,-1,0
  4500.5    0.16       0  4751.1    0.12       0  4996.9    0.07       0
  5003.4    0.12       0  5381.4    0.16       0
Bank Sta=4806.7,5173.7
Exp/Cntr=0.3,0.1

Type RM Length L Ch R = 1,9736,675,675,675
BEGIN DESCRIPTION:
UNT 161 in LFCCL Watershed 12.0
END DESCRIPTION:
XS GIS Cut Line= 3
      2795974.99      7027875.00      2796455.18      7027714.07
      2796868.40      7027561.28
#Sta/Elev= 30
  4499.2  456.02  4520.3  454.47  4541.3  454.62  4583.6  450.18  4710.1  440.89
  4830.4  435.40  4841.8  435.08  4919.9  436.29  4973.8  434.64  4983.0  433.96
  4988.3  431.06  4994.9  423.85  4999.2  423.76  4999.8  422.96  5006.1  422.96
  5006.7  423.76  5008.2  423.76  5014.1  429.22  5026.8  433.13  5058.8  434.45
  5100.0  434.04  5130.4  434.66  5135.7  435.58  5155.3  435.40  5160.8  436.85
  5166.1  436.06  5197.4  436.56  5314.6  441.55  5393.4  446.65  5446.2  451.30
#Mann=4,-1,0
  4499.2    0.16       0  4841.8    0.12       0  4999.2    0.07       0
  5006.7    0.12       0
Bank Sta=4830.4,5155.3
Exp/Cntr=0.3,0.1

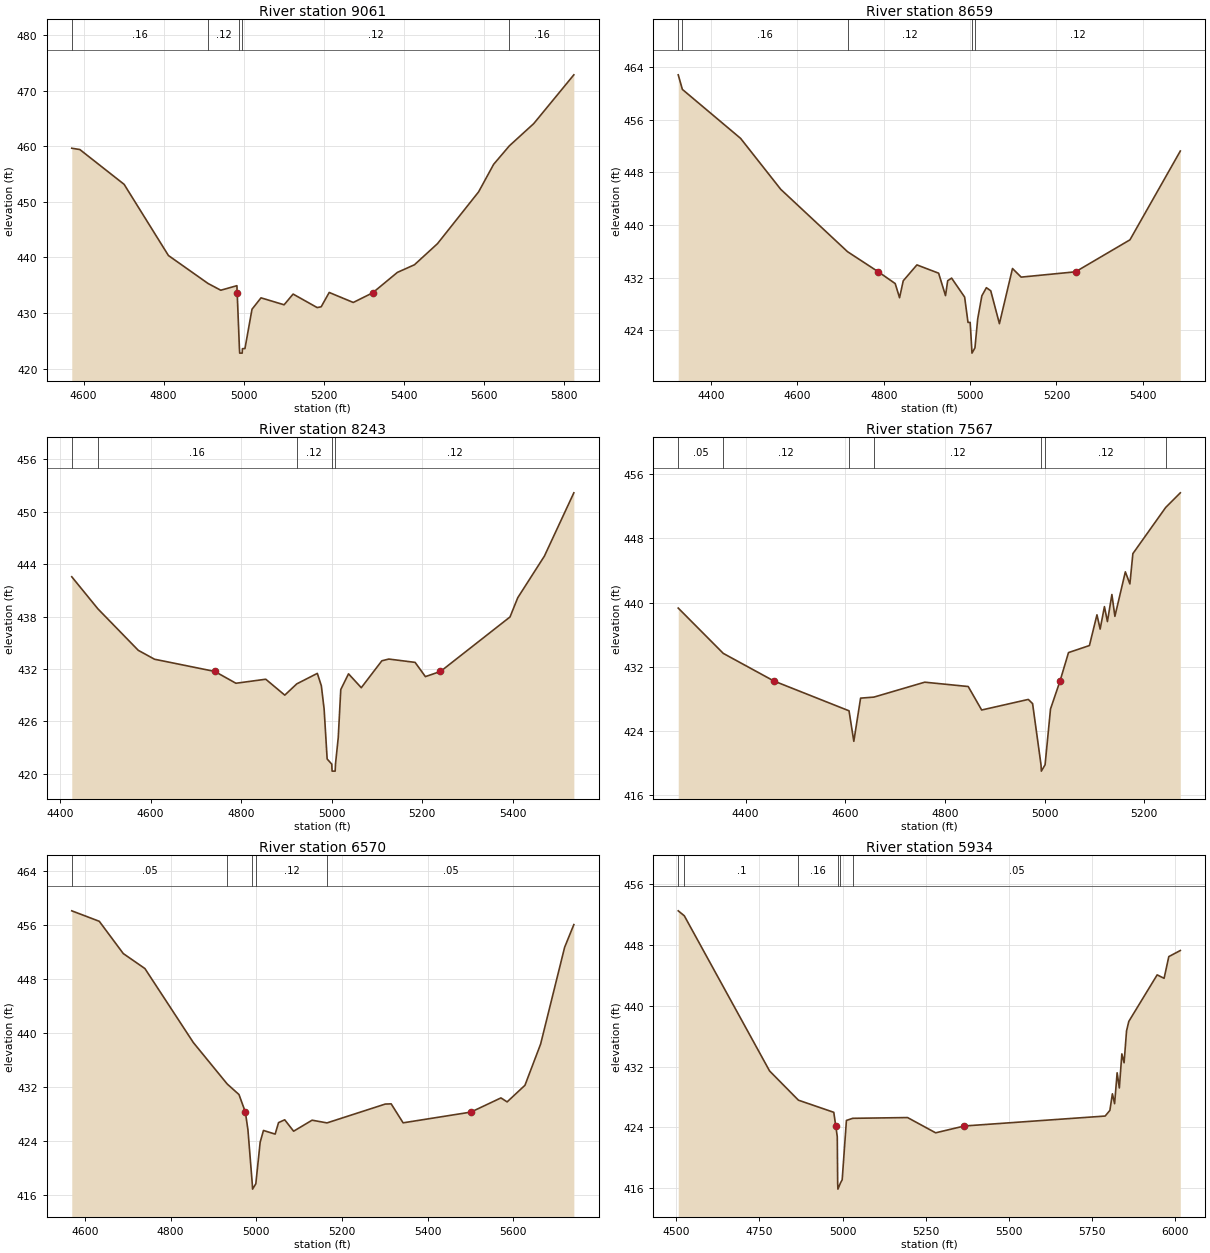
Type RM Length L Ch R = 1,9061,402,402,402
BEGIN DESCRIPTION:
UNT 161 in LFCCL Watershed 11.0
END DESCRIPTION:
XS GIS Cut Line= 3
      2795974.96      7027975.00      2796425.00      7028025.00
      2797225.03      7028075.00
#Sta/Elev= 30
  4570.5  459.65  4590.7  459.41  4701.3  453.15  4812.0  440.34  4910.9  435.31
  4942.8  434.09  4983.1  434.91  4983.8  433.62  4989.4  423.57  4990.0  422.77
  4996.3  422.77  4996.9  423.57  5003.2  423.59  5020.8  430.67  5043.3  432.72
  5101.0  431.47  5123.5  433.40  5183.6  430.97  5193.6  431.11  5213.7  433.69
  5273.8  431.89  5322.2  433.62  5384.0  437.30  5426.6  438.67  5484.2  442.47
  5586.9  451.79  5624.5  456.75  5663.8  460.08  5724.7  464.08  5824.9  472.86
#Mann=5,-1,0
  4570.5    0.16       0  4910.9    0.12       0  4989.4    0.07       0
  4996.9    0.12       0  5663.8    0.16       0
Bank Sta=4983.8,5322.2
Exp/Cntr=0.3,0.1

Type RM Length L Ch R = 1,8659,416,416,416
BEGIN DESCRIPTION:
UNT 161 in LFCCL Watershed 10.0
END DESCRIPTION:
XS GIS Cut Line= 3
      2795874.96      7028375.00      2796545.46      7028304.35
      2797030.76      7028241.95
#Sta/Elev= 30
  4323.7  462.88  4333.3  460.66  4468.2  453.20  4561.2  445.44  4716.1  435.93
  4787.3  432.87  4826.5  431.08  4836.6  428.92  4845.1  431.50  4876.8  433.92
  4927.1  432.66  4943.1  429.24  4948.1  431.51  4957.2  431.91  4987.4  429.02
  4995.2  425.16  5000.2  425.16  5003.8  421.28  5004.4  420.48  5011.3  421.28
  5017.6  425.66  5027.3  429.21  5037.8  430.45  5047.9  429.98  5068.0  424.97
  5098.3  433.37  5118.4  432.06  5244.4  432.87  5370.5  437.74  5487.2  451.27
#Mann=5,-1,0
  4323.7    0.05       0  4333.3    0.16       0  4716.1    0.12       0
  5003.8    0.07       0  5011.3    0.12       0
Bank Sta=4787.3,5244.4
Exp/Cntr=0.3,0.1

Type RM Length L Ch R = 1,8243,676,676,676
BEGIN DESCRIPTION:
XS3914A
END DESCRIPTION:
XS GIS Cut Line= 3
      2796278.11      7029002.24      2796597.54      7028530.04
      2797083.64      7028297.41
#Sta/Elev= 30
  4425.9  442.55  4483.6  438.88  4572.8  434.13  4608.7  433.11  4741.9  431.71
  4788.5  430.36  4854.4  430.82  4896.4  429.00  4922.9  430.29  4968.3  431.49
  4977.2  430.07  4983.3  427.41  4990.0  421.69  5000.2  421.10  5000.9  420.30
  5007.7  420.30  5008.4  421.10  5014.5  424.14  5020.1  429.64  5037.2  431.44
  5065.4  429.85  5110.8  432.93  5126.2  433.13  5184.3  432.75  5207.0  431.12
  5240.3  431.71  5393.9  437.95  5411.0  440.15  5469.9  444.92  5534.9  452.16
#Mann=5,-1,0
  4425.9    0.05       0  4483.6    0.16       0  4922.9    0.12       0
  5000.2    0.07       0  5008.4    0.12       0
Bank Sta=4741.9,5240.3
Exp/Cntr=0.3,0.1

Type RM Length L Ch R = 1,7567,997,997,997
BEGIN DESCRIPTION:
XS3915A
END DESCRIPTION:
XS GIS Cut Line= 3
      2796448.24      7029089.07      2796910.04      7028755.74
      2797153.09      7028391.16
#Sta/Elev= 30
  4264.7  439.31  4355.1  433.66  4456.6  430.22  4607.5  426.50  4617.1  422.70
  4630.7  428.08  4657.5  428.21  4759.4  430.07  4846.7  429.53  4873.7  426.60
  4967.3  427.92  4975.9  427.40  4992.8  419.78  4993.5  418.98  5001.0  419.78
  5011.9  426.73  5031.0  430.22  5048.0  433.76  5090.0  434.64  5105.1  438.47
  5111.5  436.69  5120.1  439.49  5126.1  437.63  5135.1  441.00  5141.1  438.28
  5162.1  443.83  5171.2  442.32  5177.2  446.10  5243.1  451.86  5272.4  453.68
#Mann=7,-1,0
  4264.7    0.05       0  4355.1    0.12       0  4607.5    0.16       0
  4657.5    0.12       0  4992.8    0.07       0  5001.0    0.12       0
  5243.1    0.05       0
Bank Sta=4456.6,5031
Exp/Cntr=0.3,0.1

Type RM Length L Ch R = 1,6570,636,636,636
BEGIN DESCRIPTION:
UNT 161 in LFCCL Watershed 9.0
END DESCRIPTION:
XS GIS Cut Line= 3
      2796574.99      7029625.01      2796925.00      7029325.00
      2797374.98      7028775.02
#Sta/Elev= 30
  4569.5  458.06  4633.7  456.51  4689.7  451.73  4740.2  449.51  4853.2  438.55
  4932.1  432.42  4959.7  430.85  4974.6  428.25  4980.6  425.62  4990.7  417.64
  4991.4  416.84  4999.0  417.64  5009.1  423.78  5016.8  425.53  5044.1  424.99
  5052.0  426.69  5066.4  427.11  5087.2  425.42  5130.3  427.05  5165.1  426.65
  5301.1  429.44  5314.8  429.47  5342.7  426.66  5500.9  428.25  5571.0  430.35
  5585.4  429.76  5627.0  432.22  5663.6  438.33  5719.6  452.66  5741.1  456.02
#Mann=5,-1,0
  4569.5    0.05       0  4932.1    0.12       0  4990.7    0.07       0
  4999.0    0.12       0  5165.1    0.05       0
Bank Sta=4974.6,5500.9
Exp/Cntr=0.3,0.1

Type RM Length L Ch R = 1,5934,561,561,561
BEGIN DESCRIPTION:
UNT 161 in LFCCL Watershed 7.0
END DESCRIPTION:
XS GIS Cut Line= 3
      2796674.97      7029975.01      2797135.74      7029807.82
      2797812.80      7029043.95
#Sta/Elev= 30
  4505.5  452.52  4523.7  451.87  4780.4  431.42  4867.2  427.57  4973.6  425.97
  4979.5  424.17  4984.1  422.76  4985.3  416.65  4986.0  415.85  4993.6  416.65
  4998.9  417.09  5011.6  424.90  5030.5  425.18  5195.6  425.28  5280.1  423.27
  5366.6  424.17  5790.3  425.48  5804.5  426.23  5812.0  428.41  5818.7  427.11
  5826.3  431.18  5832.9  429.18  5840.5  433.67  5847.2  432.50  5854.6  436.70
  5861.4  437.95  5946.7  444.08  5967.6  443.63  5981.8  446.49  6016.4  447.29
#Mann=6,-1,0
  4505.5    0.05       0  4523.7     0.1       0  4867.2    0.16       0
  4985.3    0.07       0  4993.6    0.16       0  5030.5    0.05       0
Bank Sta=4979.5,5366.6
Exp/Cntr=0.3,0.1

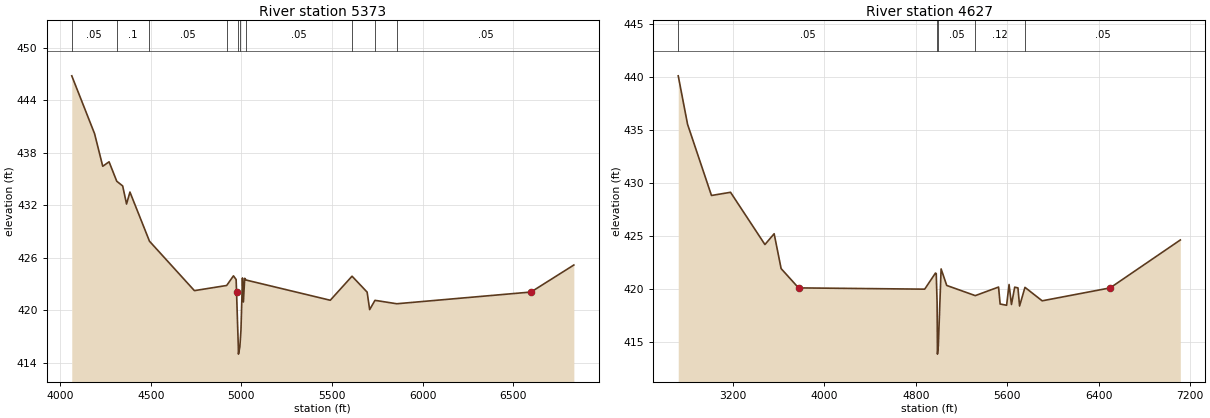
Type RM Length L Ch R = 1,5373,746,746,746
BEGIN DESCRIPTION:
UNT 161 in LFCCL Watershed 6.0
END DESCRIPTION:
XS GIS Cut Line= 3
      2796272.89      7030066.50      2797210.39      7030316.50
      2798751.37      7029385.58
#Sta/Elev= 30
  4064.5  446.78  4190.1  440.18  4235.4  436.44  4270.3  436.95  4312.7  434.73
  4345.4  434.19  4366.8  432.12  4385.5  433.49  4493.4  427.87  4741.2  422.22
  4919.4  422.81  4956.7  423.91  4971.5  423.49  4973.8  422.06  4983.6  415.76
  4984.3  414.96  4991.9  415.76  4998.1  417.69  5006.4  423.67  5011.6  420.92
  5018.8  423.63  5026.6  423.43  5491.0  421.12  5611.1  423.87  5694.4  422.05
  5708.4  420.05  5737.7  421.11  5858.1  420.72  6598.6  422.06  6835.1  425.15
#Mann=10,-1,0
  4064.5    0.05       0  4312.7     0.1       0  4493.4    0.05       0
  4919.4    0.16       0  4983.6    0.07       0  4991.9    0.16       0
  5026.6    0.05       0  5611.1    0.12       0  5737.7    0.07       0
  5858.1    0.05       0
Bank Sta=4973.8,6598.6
Exp/Cntr=0.3,0.1

Type RM Length L Ch R = 1,4627,0,0,0
BEGIN DESCRIPTION:
UNT 161 in LFCCL Watershed 5.0
END DESCRIPTION:
XS GIS Cut Line= 3
      2795301.38      7030292.86      2797379.49      7031048.06
      2798836.83      7029418.96
#Sta/Elev= 30
  2719.5  440.11  2801.1  435.54  3010.6  428.82  3177.6  429.12  3478.8  424.19
  3559.4  425.21  3620.6  421.92  3773.3  420.10  4877.8  419.98  4972.3  421.50
  4979.0  421.45  4986.5  418.70  4989.0  414.65  4989.7  413.85  4997.3  414.65
  5021.6  421.89  5070.9  420.33  5320.8  419.37  5524.8  420.18  5538.5  418.58
  5595.1  418.46  5616.8  420.42  5637.7  418.53  5666.1  420.17  5694.5  420.10
  5708.7  418.39  5756.0  420.15  5906.8  418.88  6501.9  420.10  7116.4  424.62
#Mann=5,-1,0
  2719.5    0.05       0  4989.0    0.03       0  4997.3    0.05       0
  5320.8    0.12       0  5756.0    0.05       0
Bank Sta=3773.3,6501.9
Exp/Cntr=0.3,0.1

Chan Stop Cuts=-1