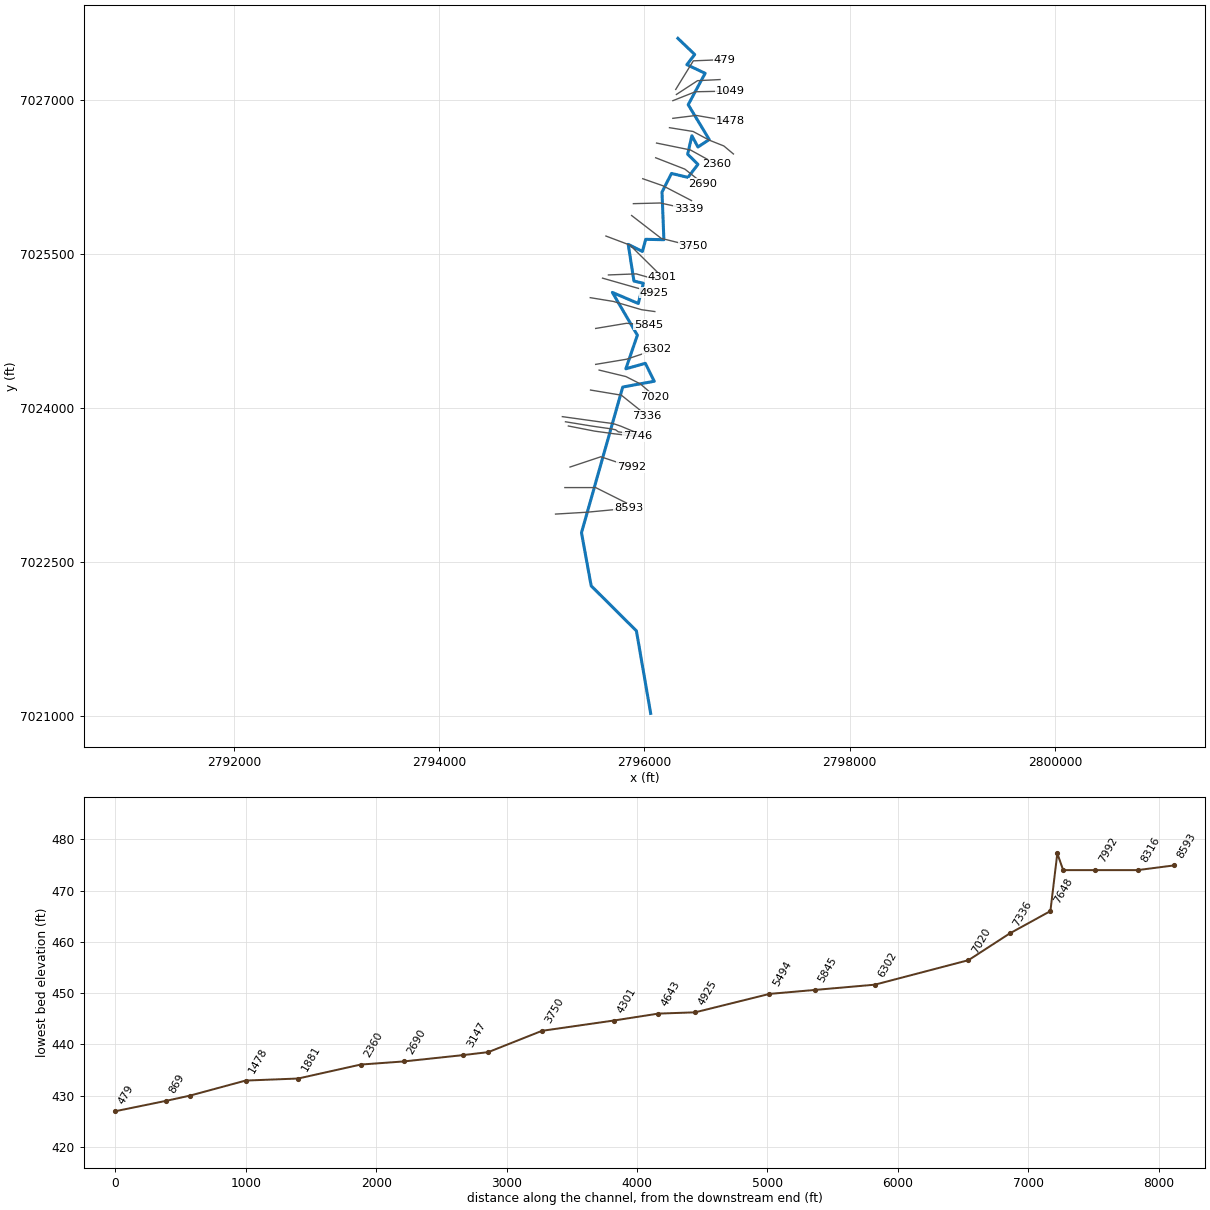
--- UNT 162 in LFCCL Watershed.prj (project) ---

Proj Title=UNT 162 in LFCCL Watershed Base Level Engineering
Current Plan=p01
Default Exp/Contr=0.3,0.1
English Units
Geom File=g01
Flow File=f01
Plan File=p01
BEGIN DESCRIPTION:
UNT 162 in LFCCL Watershed
END DESCRIPTION:

--- UNT 162 in LFCCL Watershed.p01 (plan) ---

Plan Title=Multiple Run
Short Identifier=Multiple
Geom File=g01
Flow File=f01
Subcritical Flow
K Sum by GR= 0
Std Step Tol= 0.01
Critical Tol= 0.01
Num of Std Step Trials= 20
Max Error Tol= 0.3
Flow Tol Ratio= 0.001
Split Flow NTrial= 30
Split Flow Tol= 0.02
Split Flow Ratio= 0.02
Log Output Level= 0
Friction Slope Method= 1
Unsteady Friction Slope Method= 2
Unsteady Bridges Friction Slope Method= 1
Parabolic Critical Depth
Global Vel Dist=  1 , 1 , 1
Global Log Level= 0
CheckData=True
Encroach Param= -1, 0, 0, 0
BEGIN DESCRIPTION:
Multiple Run
END DESCRIPTION:

--- UNT 162 in LFCCL Watershed.f01 (steady flow) ---

Flow Title=Multiple
Number of Profiles=7
Profile Names=10-year,25-year,50-year,1pct_min,100-year,1pct_plu,500-year
River Rch & RM= UNT 162 in LFCCL,Reach-1,8593
     213     267     308     177     354     706     466
River Rch & RM= UNT 162 in LFCCL,Reach-1,6302
     469     618     737     437     873    1741    1225
Boundary for River Rch & Prof#=UNT 162 in LFCCL,Reach-1,1
Up Type=0
Dn Type=3
Dn Slope=0.005
Boundary for River Rch & Prof#=UNT 162 in LFCCL,Reach-1,2
Up Type=0
Dn Type=3
Dn Slope=0.005
Boundary for River Rch & Prof#=UNT 162 in LFCCL,Reach-1,3
Up Type=0
Dn Type=3
Dn Slope=0.005
Boundary for River Rch & Prof#=UNT 162 in LFCCL,Reach-1,4
Up Type=0
Dn Type=3
Dn Slope=0.005
Boundary for River Rch & Prof#=UNT 162 in LFCCL,Reach-1,5
Up Type=0
Dn Type=3
Dn Slope=0.005
Boundary for River Rch & Prof#=UNT 162 in LFCCL,Reach-1,6
Up Type=0
Dn Type=3
Dn Slope=0.005
Boundary for River Rch & Prof#=UNT 162 in LFCCL,Reach-1,7
Up Type=0
Dn Type=3
Dn Slope=0.005

--- UNT 162 in LFCCL Watershed.g01 (geometry) ---

Geom Title=Existing Conditions

River Reach=UNT 162 in LFCCL,Reach-1
Reach XY= 30
      2796060.59      7021025.71      2795921.84      7021829.16
      2795481.16      7022268.06      2795386.85      7022785.39
      2795788.38      7024204.10      2796095.59      7024260.71
      2796008.59      7024435.38      2795818.95      7024381.86
      2795931.04      7024709.46      2795687.62      7025125.79
      2795940.23      7025018.04      2795989.12      7025215.13
      2795897.78      7025236.48      2795841.98      7025593.94
      2795980.43      7025524.83      2796012.29      7025643.07
      2796189.36      7025639.42      2796171.06      7026103.14
      2796263.43      7026284.75      2796423.99      7026246.24
      2796521.32      7026373.34      2796420.88      7026472.19
      2796462.12      7026651.82      2796521.07      7026542.37
      2796631.01      7026614.92      2796426.30      7026954.12
      2796591.04      7027259.98      2796413.21      7027344.43
      2796489.71      7027443.44      2796325.59      7027600.71

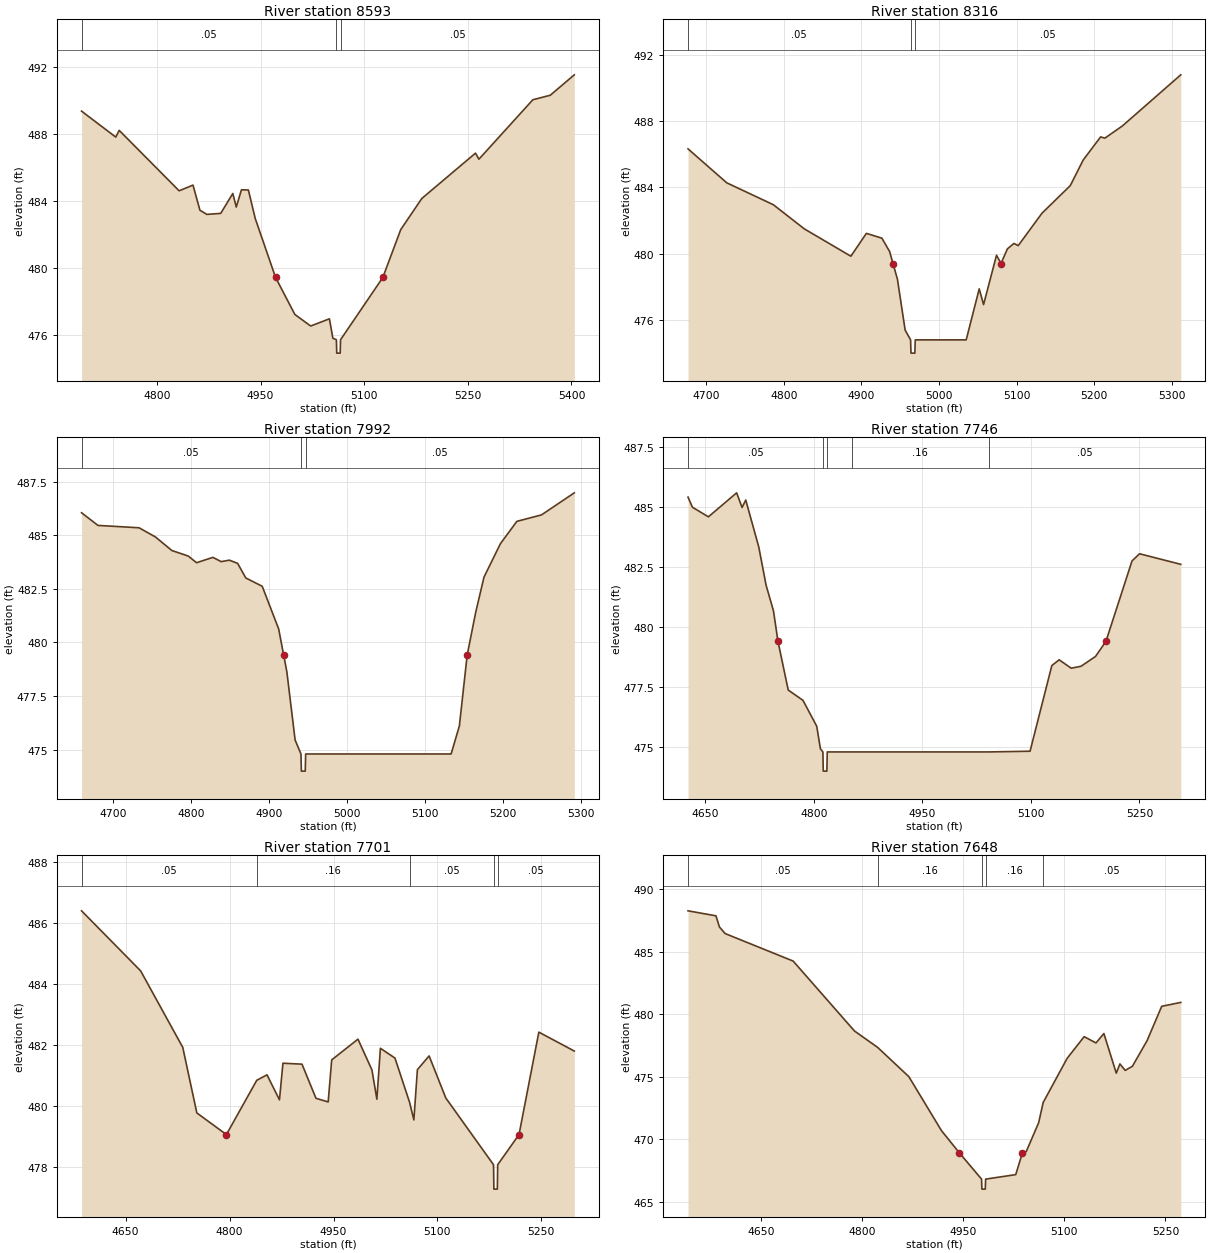
Type RM Length L Ch R = 1,8593,277,277,277
BEGIN DESCRIPTION:
Mapping XS a5679cdd
END DESCRIPTION:
XS GIS Cut Line= 3
      2795134.00      7022966.86      2795444.38      7022985.31
      2795844.76      7023023.28
#Sta/Elev= 30
  4691.0  489.37  4740.5  487.82  4745.5  488.22  4832.2  484.61  4852.3  484.95
  4862.3  483.45  4872.3  483.20  4892.4  483.26  4909.9  484.45  4914.9  483.64
  4922.4  484.67  4932.4  484.66  4942.4  482.95  4971.8  479.43  4999.7  477.22
  5022.6  476.53  5049.7  476.96  5054.7  475.80  5059.8  475.71  5060.3  474.91
  5065.3  474.91  5065.8  475.71  5127.0  479.43  5152.9  482.29  5183.4  484.15
  5261.1  486.86  5266.1  486.50  5344.1  490.05  5369.3  490.32  5404.1  491.54
#Mann=3,-1,0
  4691.0    0.05       0  5059.8    0.03       0  5065.8    0.05       0
Bank Sta=4971.8,5127
Exp/Cntr=0.3,0.1

Type RM Length L Ch R = 1,8316,324,324,324
BEGIN DESCRIPTION:
UNT 162 in LFCCL Watershed 15.0
END DESCRIPTION:
XS GIS Cut Line= 3
      2795224.98      7023225.00      2795525.00      7023225.00
      2795824.98      7023075.01
#Sta/Elev= 30
  4676.4  486.33  4726.4  484.28  4786.4  482.96  4826.4  481.50  4886.4  479.85
  4906.4  481.23  4926.4  480.94  4936.4  480.13  4940.7  479.41  4946.4  478.47
  4956.4  475.39  4963.4  474.80  4963.9  474.00  4968.9  474.00  4969.4  474.80
  5035.1  474.80  5051.9  477.88  5057.5  476.93  5074.2  479.91  5080.0  479.41
  5088.2  480.29  5096.6  480.62  5102.2  480.49  5132.9  482.45  5169.3  484.11
  5186.0  485.66  5208.4  487.05  5214.0  486.98  5236.4  487.71  5311.8  490.80
#Mann=3,-1,0
  4676.4    0.05       0  4963.4    0.03       0  4969.4    0.05       0
Bank Sta=4940.7,5080
Exp/Cntr=0.3,0.1

Type RM Length L Ch R = 1,7992,246,246,246
BEGIN DESCRIPTION:
UNT 162 in LFCCL Watershed 14.0
END DESCRIPTION:
XS GIS Cut Line= 3
      2795275.01      7023425.00      2795575.00      7023525.00
      2795874.95      7023425.02
#Sta/Elev= 30
  4659.2  486.05  4680.3  485.46  4733.0  485.35  4754.1  484.92  4775.1  484.29
  4796.2  484.03  4806.8  483.72  4827.8  483.97  4838.4  483.77  4848.9  483.84
  4859.5  483.69  4870.0  483.01  4891.1  482.62  4912.2  480.63  4918.6  479.41
  4922.7  478.63  4933.3  475.45  4940.8  474.80  4941.3  474.00  4946.3  474.00
  4946.8  474.80  5133.5  474.80  5144.1  476.11  5154.1  479.41  5165.2  481.43
  5175.7  483.05  5196.8  484.61  5217.9  485.65  5249.5  485.95  5291.6  486.98
#Mann=3,-1,0
  4659.2    0.05       0  4940.8   0.033       0  4946.8    0.05       0
Bank Sta=4918.6,5154.1
Exp/Cntr=0.3,0.1

Type RM Length L Ch R = 1,7746,45,45,45
BEGIN DESCRIPTION:
XS3916A
END DESCRIPTION:
XS GIS Cut Line= 4
      2795259.05      7023824.77      2795515.10      7023774.86
      2795706.07      7023748.82      2795932.00      7023723.00
#Sta/Elev= 30
  4626.1  485.42  4632.2  485.00  4654.3  484.60  4693.3  485.60  4700.8  484.99
  4705.9  485.30  4723.9  483.34  4734.0  481.75  4744.2  480.68  4750.4  479.41
  4764.6  477.38  4785.0  476.95  4804.0  475.87  4809.1  474.93  4812.5  474.80
  4813.0  474.00  4818.0  474.00  4818.5  474.80  4852.6  474.80  5041.7  474.80
  5098.8  474.83  5128.9  478.40  5139.0  478.64  5155.7  478.29  5169.2  478.37
  5189.3  478.78  5203.7  479.41  5239.7  482.76  5250.1  483.06  5307.1  482.62
#Mann=5,-1,0
  4626.1    0.05       0  4812.5    0.07       0  4818.5    0.05       0
  4852.6    0.16       0  5041.7    0.05       0
Bank Sta=4750.4,5203.7
Exp/Cntr=0.3,0.1

Type RM Length L Ch R = 1,7701,53,53,53
BEGIN DESCRIPTION:
XS3917A
END DESCRIPTION:
XS GIS Cut Line= 6
      2795230.79      7023866.01      2795482.55      7023824.77
      2795677.86      7023796.56      2795719.09      7023787.88
      2795745.14      7023768.35      2795927.45      7023742.30
#Sta/Elev= 30
  4586.3  486.39  4671.6  484.42  4732.4  481.91  4752.7  479.76  4795.4  479.05
  4839.2  480.83  4854.0  481.01  4872.0  480.19  4877.0  481.39  4904.5  481.36
  4924.7  480.24  4942.3  480.12  4947.4  481.50  4985.3  482.18  5005.5  481.17
  5012.6  480.21  5017.7  481.88  5038.7  481.56  5059.8  480.11  5066.0  479.53
  5071.1  481.18  5088.0  481.63  5112.1  480.25  5181.0  478.06  5181.5  477.26
  5186.5  477.26  5187.0  478.06  5217.8  479.05  5246.4  482.41  5297.6  481.79
#Mann=5,-1,0
  4586.3    0.05       0  4839.2    0.16       0  5059.8    0.05       0
  5181.0    0.07       0  5187.0    0.05       0
Bank Sta=4795.4,5217.8
Exp/Cntr=0.3,0.1

Type RM Length L Ch R = 1,7648,312,312,312
BEGIN DESCRIPTION:
XS3918A
END DESCRIPTION:
XS GIS Cut Line= 5
      2795200.44      7023915.92      2795575.86      7023863.84
      2795695.22      7023848.64      2795771.18      7023822.60
      2795911.14      7023764.46
#Sta/Elev= 30
  4541.6  488.28  4583.1  487.88  4588.2  486.99  4596.7  486.46  4697.6  484.26
  4788.5  478.67  4823.0  477.35  4869.3  475.01  4917.7  470.69  4944.0  468.93
  4977.2  466.81  4977.7  466.01  4982.7  466.01  4983.2  466.81  5027.9  467.17
  5037.9  468.93  5043.5  469.02  5061.9  471.32  5068.6  472.94  5104.1  476.47
  5129.4  478.21  5147.0  477.71  5158.7  478.46  5177.1  475.29  5182.5  476.03
  5190.3  475.51  5201.0  475.84  5222.8  477.89  5244.5  480.64  5272.8  480.95
#Mann=5,-1,0
  4541.6    0.05       0  4823.0    0.16       0  4977.2    0.07       0
  4983.2    0.16       0  5068.6    0.05       0
Bank Sta=4944,5037.9
Exp/Cntr=0.3,0.1

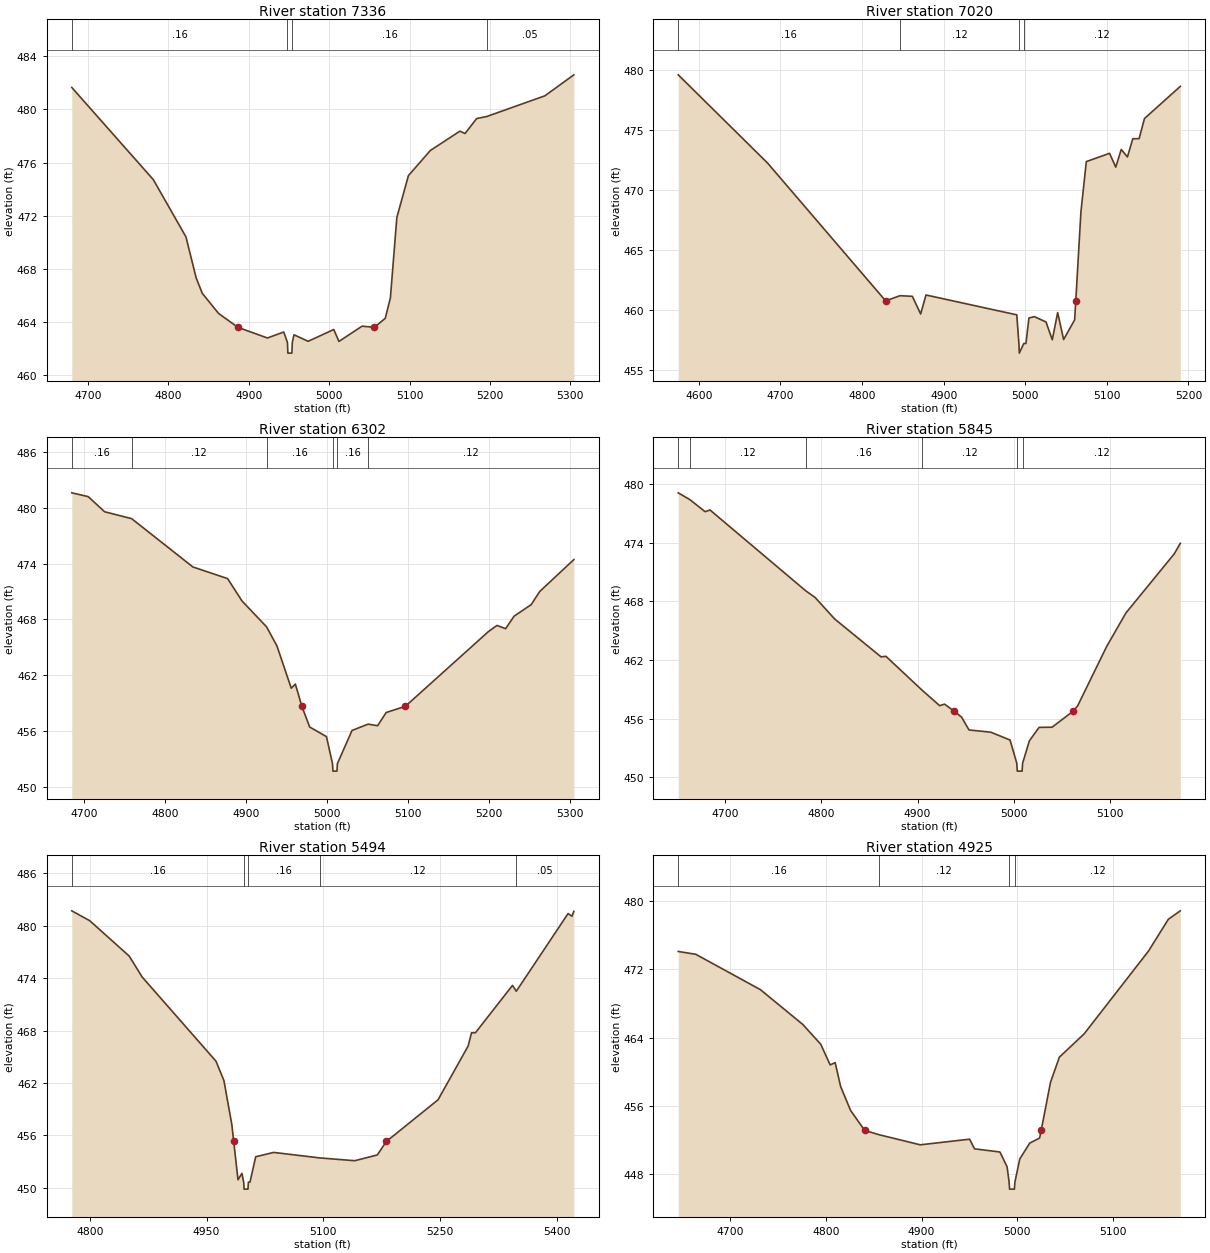
Type RM Length L Ch R = 1,7336,316,316,316
BEGIN DESCRIPTION:
UNT 162 in LFCCL Watershed 12.0
END DESCRIPTION:
XS GIS Cut Line= 3
      2795474.98      7024175.00      2795775.00      7024125.00
      2796024.99      7023925.01
#Sta/Elev= 30
  4680.0  481.65  4781.4  474.71  4822.0  470.40  4834.6  467.33  4842.2  466.16
  4862.5  464.64  4886.6  463.59  4923.3  462.79  4943.6  463.24  4948.2  462.45
  4948.7  461.65  4953.7  461.65  4954.2  462.45  4956.3  463.03  4974.0  462.54
  5005.8  463.43  5012.2  462.53  5041.0  463.68  5056.2  463.59  5069.8  464.27
  5076.2  465.81  5084.2  471.86  5098.6  475.01  5125.8  476.90  5162.6  478.36
  5169.0  478.18  5183.5  479.31  5195.9  479.46  5268.3  481.02  5304.3  482.60
#Mann=4,-1,0
  4680.0    0.16       0  4948.2    0.07       0  4954.2    0.16       0
  5195.9    0.05       0
Bank Sta=4886.6,5056.2
Exp/Cntr=0.3,0.1

Type RM Length L Ch R = 1,7020,718,718,718
BEGIN DESCRIPTION:
XS3919A
END DESCRIPTION:
XS GIS Cut Line= 4
      2795558.55      7024369.47      2795818.92      7024306.54
      2795959.98      7024234.93      2796103.20      7024111.24
#Sta/Elev= 30
  4574.7  479.56  4684.2  472.23  4828.9  460.78  4846.4  461.21  4861.6  461.16
  4871.8  459.69  4878.3  461.27  4989.6  459.62  4992.2  457.24  4992.7  456.44
  4998.2  457.24  5000.8  457.24  5004.5  459.36  5011.2  459.47  5025.4  459.03
  5033.1  457.55  5039.7  459.81  5047.0  457.57  5060.5  459.20  5061.9  460.78
  5068.2  468.17  5074.8  472.35  5103.3  473.04  5110.9  471.89  5117.6  473.36
  5125.2  472.74  5131.8  474.25  5139.5  474.26  5146.1  475.93  5190.0  478.60
#Mann=4,-1,0
  4574.7    0.16       0  4846.4    0.12       0  4992.2    0.07       0
  4998.2    0.12       0
Bank Sta=4828.9,5061.9
Exp/Cntr=0.3,0.1

Type RM Length L Ch R = 1,6302,457,457,457
BEGIN DESCRIPTION:
UNT 162 in LFCCL Watershed 10.0
END DESCRIPTION:
XS GIS Cut Line= 3
      2795524.98      7024425.00      2795825.00      7024475.00
      2796125.01      7024575.00
#Sta/Elev= 30
  4684.3  481.63  4704.6  481.22  4724.9  479.59  4758.3  478.85  4833.9  473.65
  4876.9  472.39  4894.7  469.98  4925.0  467.20  4937.8  465.15  4955.5  460.59
  4960.6  461.03  4968.6  458.64  4978.3  456.41  4999.0  455.38  5006.5  452.46
  5007.0  451.66  5012.0  451.66  5012.5  452.46  5030.6  456.04  5050.5  456.72
  5062.2  456.55  5072.8  457.97  5096.5  458.64  5199.3  466.70  5209.8  467.35
  5220.4  467.00  5230.9  468.35  5252.0  469.59  5262.5  471.00  5304.7  474.44
#Mann=6,-1,0
  4684.3    0.16       0  4758.3    0.12       0  4925.0    0.16       0
  5006.5    0.07       0  5012.5    0.16       0  5050.5    0.12       0
Bank Sta=4968.6,5096.5
Exp/Cntr=0.3,0.1

Type RM Length L Ch R = 1,5845,351,351,351
BEGIN DESCRIPTION:
UNT 162 in LFCCL Watershed 9.0
END DESCRIPTION:
XS GIS Cut Line= 3
      2795525.01      7024775.00      2795825.00      7024825.00
      2796041.27      7024811.82
#Sta/Elev= 30
  4651.8  479.09  4664.1  478.38  4679.7  477.16  4684.7  477.34  4784.1  469.07
  4793.7  468.40  4814.0  466.20  4862.2  462.32  4867.2  462.38  4904.7  458.92
  4923.0  457.33  4928.0  457.49  4938.1  456.76  4945.8  456.15  4953.4  454.85
  4976.0  454.62  4996.0  453.82  5003.0  451.44  5003.5  450.64  5008.5  450.64
  5009.0  451.44  5016.0  453.73  5026.1  455.11  5039.6  455.13  5061.3  456.76
  5066.1  457.31  5096.2  463.38  5116.2  466.81  5166.3  472.85  5172.6  473.93
#Mann=6,-1,0
  4651.8    0.16       0  4664.1    0.12       0  4784.1    0.16       0
  4904.7    0.12       0  5003.0    0.07       0  5009.0    0.12       0
Bank Sta=4938.1,5061.3
Exp/Cntr=0.3,0.1

Type RM Length L Ch R = 1,5494,569,569,569
BEGIN DESCRIPTION:
XS3920A
END DESCRIPTION:
XS GIS Cut Line= 4
      2795472.17      7025074.77      2795696.09      7025038.31
      2795972.13      7024957.59      2796101.20      7024939.52
#Sta/Elev= 30
  4776.9  481.70  4800.0  480.57  4850.7  476.52  4867.3  474.13  4962.1  464.50
  4972.3  462.28  4982.4  457.29  4984.9  455.31  4990.4  450.93  4995.4  451.66
  4997.7  450.66  4998.2  449.86  5003.2  449.86  5003.7  450.66  5005.8  450.66
  5013.1  453.56  5036.2  454.06  5095.5  453.43  5140.3  453.11  5169.3  453.77
  5180.9  455.31  5247.3  460.08  5286.0  466.24  5290.3  467.75  5295.3  467.75
  5342.9  473.17  5347.8  472.50  5414.3  481.39  5419.3  481.08  5421.7  481.64
#Mann=5,-1,0
  4776.9    0.16       0  4997.7    0.07       0  5003.7    0.16       0
  5095.5    0.12       0  5347.8    0.05       0
Bank Sta=4984.9,5180.9
Exp/Cntr=0.3,0.1

Type RM Length L Ch R = 1,4925,282,282,282
BEGIN DESCRIPTION:
XS3921A
END DESCRIPTION:
XS GIS Cut Line= 3
      2795591.92      7025264.88      2795920.05      7025171.13
      2796097.09      7025124.26
#Sta/Elev= 30
  4645.9  474.11  4664.2  473.78  4731.8  469.63  4776.0  465.56  4794.7  463.25
  4804.6  460.82  4809.8  461.09  4815.5  458.30  4825.9  455.49  4840.6  453.15
  4855.8  452.64  4898.7  451.46  4950.2  452.12  4955.4  450.99  4981.9  450.62
  4989.4  448.88  4991.5  447.07  4992.0  446.27  4997.0  446.27  4997.5  447.07
  5002.6  449.79  5013.0  451.66  5023.3  452.25  5025.0  453.15  5034.7  458.77
  5044.0  461.73  5069.8  464.45  5137.1  474.16  5157.8  477.88  5170.3  478.87
#Mann=4,-1,0
  4645.9    0.16       0  4855.8    0.12       0  4991.5    0.07       0
  4997.5    0.12       0
Bank Sta=4840.6,5025
Exp/Cntr=0.3,0.1

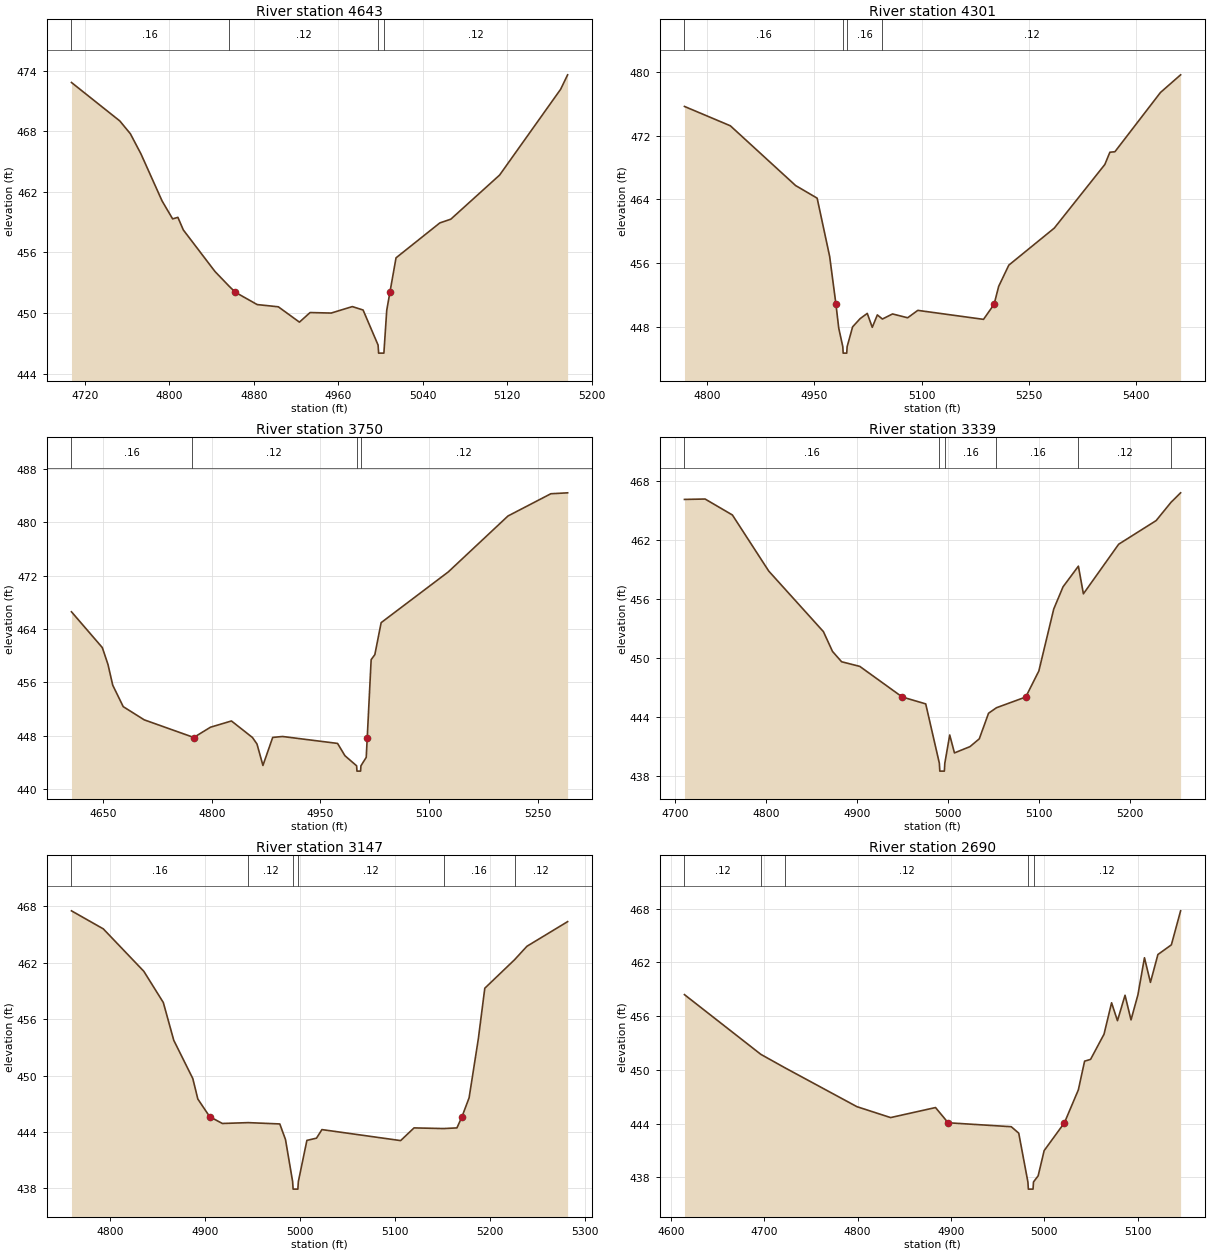
Type RM Length L Ch R = 1,4643,342,342,342
BEGIN DESCRIPTION:
XS3922A
END DESCRIPTION:
XS GIS Cut Line= 3
      2795649.21      7025296.13      2795920.05      7025306.54
      2796111.36      7025252.25
#Sta/Elev= 30
  4707.2  472.83  4753.0  469.02  4763.0  467.75  4773.0  465.76  4793.0  461.10
  4803.0  459.32  4808.0  459.47  4813.1  458.23  4843.1  454.11  4856.6  452.64
  4862.4  452.05  4883.1  450.83  4903.1  450.61  4923.1  449.09  4933.2  450.04
  4953.2  449.99  4973.2  450.63  4983.4  450.29  4997.6  446.82  4998.1  446.02
  5003.1  446.02  5003.6  446.82  5005.8  450.27  5008.8  452.05  5014.6  455.46
  5056.1  458.92  5066.5  459.29  5112.7  463.66  5170.5  472.16  5177.1  473.59
#Mann=4,-1,0
  4707.2    0.16       0  4856.6    0.12       0  4997.6    0.07       0
  5003.6    0.12       0
Bank Sta=4862.4,5008.8
Exp/Cntr=0.3,0.1

Type RM Length L Ch R = 1,4301,551,551,551
BEGIN DESCRIPTION:
UNT 162 in LFCCL Watershed 6.0
END DESCRIPTION:
XS GIS Cut Line= 3
      2795624.96      7025675.01      2795859.56      7025586.46
      2796174.97      7025275.03
#Sta/Elev= 30
  4768.3  475.65  4832.5  473.22  4923.7  465.72  4953.9  464.13  4971.4  456.81
  4980.2  450.80  4984.1  447.81  4989.8  445.47  4990.3  444.67  4995.3  444.67
  4995.8  445.47  5003.5  447.97  5014.0  449.00  5024.0  449.66  5031.0  447.91
  5038.1  449.47  5045.2  448.95  5059.3  449.59  5080.5  449.11  5094.7  450.04
  5186.6  448.91  5201.4  450.80  5207.8  453.05  5222.0  455.72  5285.6  460.37
  5356.3  468.36  5363.4  469.90  5370.4  469.96  5434.1  477.40  5462.3  479.62
#Mann=4,-1,0
  4768.3    0.16       0  4989.8    0.07       0  4995.8    0.16       0
  5045.2    0.12       0
Bank Sta=4980.2,5201.4
Exp/Cntr=0.3,0.1

Type RM Length L Ch R = 1,3750,411,411,411
BEGIN DESCRIPTION:
UNT 162 in LFCCL Watershed 5.0
END DESCRIPTION:
XS GIS Cut Line= 3
      2795875.01      7025874.99      2796163.19      7025652.41
      2796474.99      7025575.00
#Sta/Elev= 30
  4606.1  466.58  4648.7  461.21  4656.6  458.65  4663.1  455.56  4677.6  452.34
  4706.6  450.36  4772.8  447.80  4774.7  447.69  4798.1  449.25  4827.1  450.19
  4856.1  447.71  4862.4  446.73  4870.6  443.51  4884.1  447.72  4897.7  447.86
  4973.7  446.82  4983.9  444.97  5000.0  443.46  5000.5  442.66  5005.5  442.66
  5006.0  443.46  5013.3  444.73  5014.7  447.69  5020.1  459.40  5025.2  460.15
  5033.9  464.95  5126.7  472.57  5209.1  480.96  5268.3  484.30  5291.5  484.44
#Mann=4,-1,0
  4606.1    0.16       0  4772.8    0.12       0  5000.0    0.07       0
  5006.0    0.12       0
Bank Sta=4774.7,5014.7
Exp/Cntr=0.3,0.1

Type RM Length L Ch R = 1,3339,192,192,192
BEGIN DESCRIPTION:
XS3924A
END DESCRIPTION:
XS GIS Cut Line= 3
      2795892.29      7025990.43      2796154.86      7025996.94
      2796431.28      7025936.47
#Sta/Elev= 30
  4710.1  466.11  4732.8  466.15  4762.8  464.53  4802.8  458.83  4862.9  452.68
  4872.9  450.67  4882.9  449.62  4902.9  449.15  4949.6  446.04  4975.4  445.34
  4990.4  439.31  4990.9  438.51  4995.9  438.51  4996.4  439.31  5001.8  442.18
  5007.0  440.36  5024.1  441.00  5034.3  441.79  5044.5  444.39  5053.2  444.95
  5085.4  446.04  5099.8  448.68  5116.2  454.98  5126.4  457.23  5143.3  459.33
  5148.8  456.52  5187.6  461.56  5228.8  463.96  5245.2  465.82  5255.7  466.78
#Mann=6,-1,0
  4710.1    0.16       0  4990.4    0.07       0  4996.4    0.16       0
  5053.2    0.16       0  5143.3    0.12       0  5245.2    0.16       0
Bank Sta=4949.6,5085.4
Exp/Cntr=0.3,0.1

Type RM Length L Ch R = 1,3147,457,457,457
BEGIN DESCRIPTION:
XS3925A
END DESCRIPTION:
XS GIS Cut Line= 3
      2795983.42      7026233.48      2796180.55      7026164.56
      2796458.36      7026020.44
#Sta/Elev= 30
  4759.7  467.52  4793.2  465.60  4835.8  461.09  4856.3  457.77  4867.3  453.75
  4887.3  449.69  4892.6  447.51  4905.1  445.63  4918.4  444.91  4945.7  445.00
  4978.8  444.86  4984.8  443.20  4992.3  438.73  4992.8  437.93  4997.8  437.93
  4998.3  438.73  5007.3  443.11  5017.4  443.35  5023.1  444.26  5105.9  443.09
  5120.0  444.44  5151.0  444.37  5165.1  444.44  5170.4  445.63  5177.9  447.64
  5187.6  453.91  5194.4  459.29  5225.7  462.32  5238.7  463.75  5281.5  466.37
#Mann=6,-1,0
  4759.7    0.16       0  4945.7    0.12       0  4992.3    0.07       0
  4998.3    0.12       0  5151.0    0.16       0  5225.7    0.12       0
Bank Sta=4905.1,5170.4
Exp/Cntr=0.3,0.1

Type RM Length L Ch R = 1,2690,330,330,330
BEGIN DESCRIPTION:
XS3926A
END DESCRIPTION:
XS GIS Cut Line= 3
      2796109.30      7026437.47      2796393.57      7026326.80
      2796570.80      7026186.32
#Sta/Elev= 30
  4614.6  458.41  4696.4  451.74  4722.2  450.24  4799.2  445.90  4835.3  444.68
  4883.4  445.80  4896.9  444.10  4964.5  443.66  4972.5  442.94  4982.3  437.49
  4982.8  436.69  4987.8  436.69  4988.3  437.49  4993.3  438.18  4999.7  440.99
  5021.4  444.10  5036.3  447.77  5043.0  450.98  5049.4  451.18  5063.8  453.99
  5071.9  457.50  5078.2  455.50  5086.3  458.34  5092.7  455.59  5100.1  458.39
  5107.1  462.53  5113.5  459.78  5121.5  462.89  5135.9  463.97  5145.8  467.77
#Mann=5,-1,0
  4614.6    0.12       0  4696.4    0.16       0  4722.2    0.12       0
  4982.3    0.07       0  4988.3    0.12       0
Bank Sta=4896.9,5021.4
Exp/Cntr=0.3,0.1

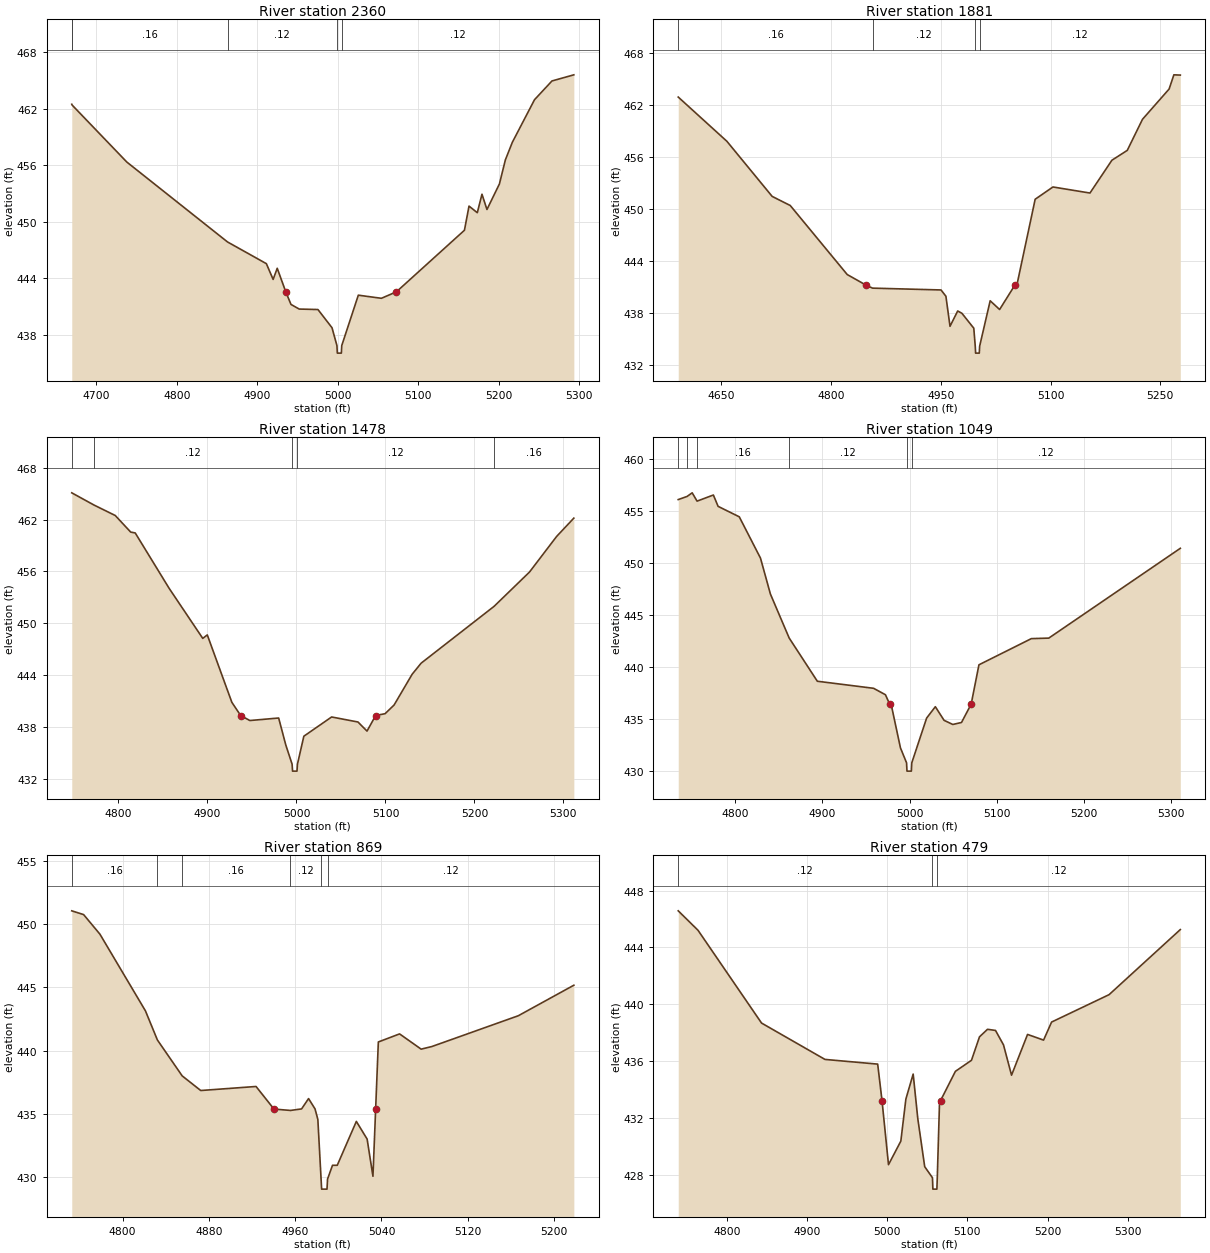
Type RM Length L Ch R = 1,2360,479,479,479
BEGIN DESCRIPTION:
XS3927A
END DESCRIPTION:
XS GIS Cut Line= 3
      2796118.01      7026580.70      2796447.83      7026513.43
      2796699.55      7026374.55
#Sta/Elev= 30
  4669.5  462.45  4669.9  462.37  4737.9  456.33  4863.1  447.86  4911.4  445.56
  4919.8  443.89  4924.9  445.07  4935.5  442.58  4942.0  441.24  4952.2  440.75
  4975.5  440.70  4993.0  438.77  4999.1  436.88  4999.6  436.08  5004.6  436.08
  5005.1  436.88  5025.7  442.22  5054.4  441.89  5073.1  442.58  5157.6  449.10
  5163.3  451.66  5173.6  450.96  5179.4  452.92  5185.6  451.30  5201.1  454.01
  5208.5  456.56  5217.2  458.43  5244.7  462.93  5266.4  464.92  5293.6  465.57
#Mann=5,-1,0
  4669.5    0.12       0  4669.9    0.16       0  4863.1    0.12       0
  4999.1    0.07       0  5005.1    0.12       0
Bank Sta=4935.5,5073.1
Exp/Cntr=0.3,0.1

Type RM Length L Ch R = 1,1881,403,403,403
BEGIN DESCRIPTION:
XS3929A
END DESCRIPTION:
XS GIS Cut Line= 5
      2796243.85      7026730.44      2796473.87      7026693.55
      2796628.80      7026609.97      2796773.35      7026552.49
      2796866.69      7026474.34
#Sta/Elev= 30
  4591.0  462.95  4657.5  457.84  4719.4  451.47  4744.1  450.42  4822.0  442.44
  4847.9  441.21  4856.6  440.87  4950.2  440.66  4956.9  439.93  4962.5  436.46
  4973.0  438.23  4978.8  437.96  4995.0  436.24  4997.0  434.16  4997.5  433.36
  5002.5  433.36  5003.0  434.16  5017.4  439.41  5030.3  438.40  5051.1  441.21
  5054.6  441.50  5078.9  451.14  5103.2  452.56  5153.8  451.86  5183.8  455.65
  5204.8  456.79  5225.6  460.38  5262.0  463.88  5268.5  465.52  5277.3  465.49
#Mann=4,-1,0
  4591.0    0.16       0  4856.6    0.12       0  4997.0    0.07       0
  5003.0    0.12       0
Bank Sta=4847.9,5051.1
Exp/Cntr=0.3,0.1

Type RM Length L Ch R = 1,1478,429,429,429
BEGIN DESCRIPTION:
XS3928A
END DESCRIPTION:
XS GIS Cut Line= 3
      2796276.43      7026821.60      2796504.25      7026849.80
      2796834.09      7026793.38
#Sta/Elev= 30
  4747.5  465.08  4772.3  463.68  4796.4  462.46  4813.7  460.55  4818.8  460.45
  4856.9  454.06  4894.7  448.28  4899.8  448.68  4927.4  440.90  4937.3  439.38
  4947.6  438.80  4980.0  439.09  4988.0  435.98  4995.1  433.76  4995.6  432.96
  5000.6  432.96  5001.1  433.76  5008.3  436.99  5039.5  439.21  5069.1  438.63
  5079.3  437.58  5089.0  439.38  5099.6  439.59  5109.7  440.59  5130.0  444.14
  5140.1  445.42  5222.1  451.98  5261.9  455.94  5292.3  460.04  5311.7  462.16
#Mann=5,-1,0
  4747.5    0.16       0  4772.3    0.12       0  4995.1    0.07       0
  5001.1    0.12       0  5222.1    0.16       0
Bank Sta=4937.3,5089
Exp/Cntr=0.3,0.1

Type RM Length L Ch R = 1,1049,180,180,180
BEGIN DESCRIPTION:
XS3923A
END DESCRIPTION:
XS GIS Cut Line= 3
      2796276.78      7026993.45      2796495.57      7027080.27
      2796835.81      7027087.21
#Sta/Elev= 30
  4734.6  456.14  4744.7  456.44  4750.6  456.79  4756.2  455.99  4774.9  456.58
  4780.3  455.49  4804.6  454.48  4828.9  450.51  4840.3  447.05  4861.8  442.82
  4894.1  438.66  4958.6  437.98  4972.2  437.36  4977.0  436.46  4979.4  436.18
  4989.4  432.25  4996.4  430.81  4996.9  430.01  5001.9  430.01  5002.4  430.81
  5019.4  435.11  5029.4  436.21  5039.4  434.90  5049.4  434.50  5059.4  434.69
  5070.5  436.46  5079.4  440.24  5139.5  442.76  5159.5  442.81  5310.3  451.45
#Mann=6,-1,0
  4734.6    0.16       0  4744.7    0.12       0  4756.2    0.16       0
  4861.8    0.12       0  4996.4    0.07       0  5002.4    0.12       0
Bank Sta=4977,5070.5
Exp/Cntr=0.3,0.1

Type RM Length L Ch R = 1,869,390,390,390
BEGIN DESCRIPTION:
XS3930A
END DESCRIPTION:
XS GIS Cut Line= 3
      2796311.11      7027053.79      2796517.27      7027188.34
      2796736.42      7027199.19
#Sta/Elev= 30
  4752.8  451.08  4763.8  450.78  4778.9  449.23  4821.1  443.15  4832.2  440.84
  4855.2  437.99  4872.4  436.83  4923.7  437.15  4940.3  435.36  4955.6  435.25
  4965.9  435.37  4972.4  436.19  4978.4  435.37  4981.0  434.54  4984.0  429.81
  4984.5  429.01  4989.5  429.01  4990.0  429.81  4994.6  430.90  4999.0  430.90
  5016.7  434.38  5026.7  432.98  5032.1  430.03  5034.6  435.36  5037.1  440.68
  5056.8  441.32  5076.8  440.11  5086.8  440.32  5166.9  442.76  5218.4  445.18
#Mann=6,-1,0
  4752.8    0.16       0  4832.2    0.12       0  4855.2    0.16       0
  4955.6    0.12       0  4984.0    0.07       0  4990.0    0.12       0
Bank Sta=4940.3,5034.6
Exp/Cntr=0.3,0.1

Type RM Length L Ch R = 1,479,0,0,0
BEGIN DESCRIPTION:
UNT 162 in LFCCL Watershed 4.0
END DESCRIPTION:
XS GIS Cut Line= 3
      2796304.59      7027102.97      2796476.04      7027381.49
      2796775.53      7027393.78
#Sta/Elev= 30
  4739.0  446.57  4763.7  445.20  4843.0  438.67  4922.2  436.11  4988.0  435.78
  4993.4  433.21  5001.5  428.70  5016.9  430.36  5023.2  433.32  5032.3  435.08
  5038.1  431.93  5046.7  428.56  5056.4  427.78  5056.9  426.98  5061.9  426.98
  5062.4  427.78  5065.2  433.07  5066.5  433.21  5085.0  435.27  5105.1  436.05
  5115.1  437.70  5125.1  438.23  5135.1  438.15  5145.1  437.13  5155.1  435.00
  5175.1  437.87  5195.1  437.47  5205.1  438.74  5276.9  440.67  5365.8  445.25
#Mann=3,-1,0
  4739.0    0.12       0  5056.4    0.07       0  5062.4    0.12       0
Bank Sta=4993.4,5066.5
Exp/Cntr=0.3,0.1

Chan Stop Cuts=-1