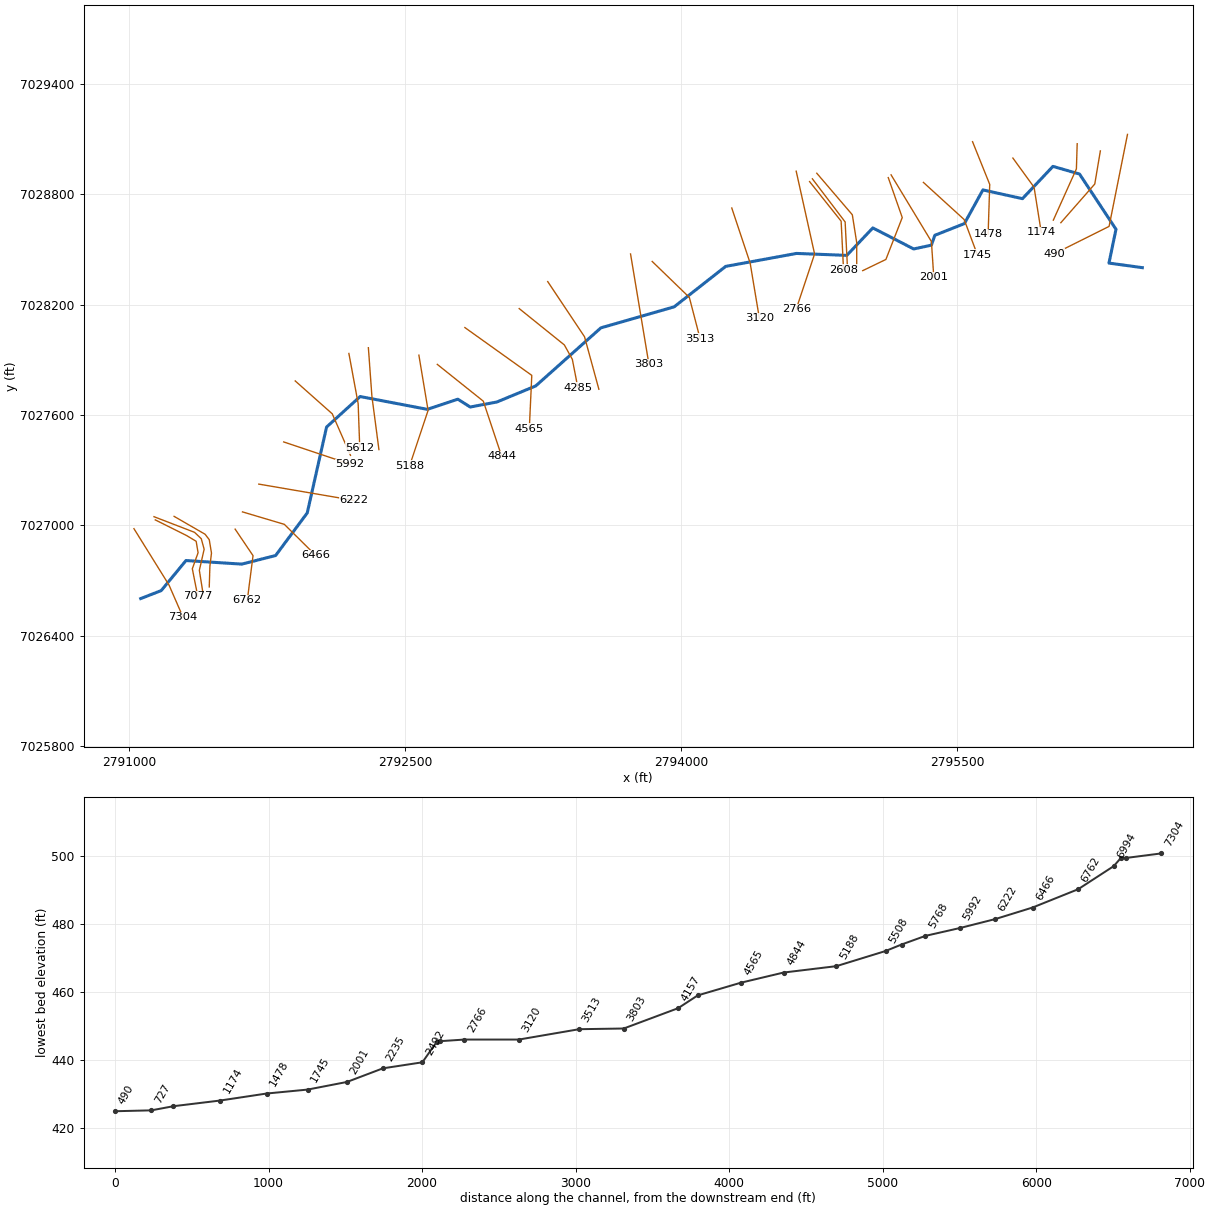
--- UNT 163 in LFCCL Watershed.prj (project) ---

Proj Title=UNT 163 in LFCCL Watershed Base Level Engineering
Current Plan=p01
Default Exp/Contr=0.3,0.1
English Units
Geom File=g01
Flow File=f01
Plan File=p01
BEGIN DESCRIPTION:
UNT 163 in LFCCL Watershed
END DESCRIPTION:

--- UNT 163 in LFCCL Watershed.p01 (plan) ---

Plan Title=Multiple Run
Short Identifier=Multiple
Geom File=g01
Flow File=f01
Subcritical Flow
K Sum by GR= 0
Std Step Tol= 0.01
Critical Tol= 0.01
Num of Std Step Trials= 20
Max Error Tol= 0.3
Flow Tol Ratio= 0.001
Split Flow NTrial= 30
Split Flow Tol= 0.02
Split Flow Ratio= 0.02
Log Output Level= 0
Friction Slope Method= 1
Unsteady Friction Slope Method= 2
Unsteady Bridges Friction Slope Method= 1
Parabolic Critical Depth
Global Vel Dist=  1 , 1 , 1
Global Log Level= 0
CheckData=True
Encroach Param= -1, 0, 0, 0
BEGIN DESCRIPTION:
Multiple Run
END DESCRIPTION:

--- UNT 163 in LFCCL Watershed.f01 (steady flow) ---

Flow Title=Multiple
Number of Profiles=7
Profile Names=10-year,25-year,50-year,1pct_min,100-year,1pct_plu,500-year
River Rch & RM= UNT 163 in LFCCL,Reach-1,7304
     237     300     348     202     403     805     540
River Rch & RM= UNT 163 in LFCCL,Reach-1,2001
     327     423     498     293     584    1165     802
Boundary for River Rch & Prof#=UNT 163 in LFCCL,Reach-1,1
Up Type=0
Dn Type=3
Dn Slope=0.005
Boundary for River Rch & Prof#=UNT 163 in LFCCL,Reach-1,2
Up Type=0
Dn Type=3
Dn Slope=0.005
Boundary for River Rch & Prof#=UNT 163 in LFCCL,Reach-1,3
Up Type=0
Dn Type=3
Dn Slope=0.005
Boundary for River Rch & Prof#=UNT 163 in LFCCL,Reach-1,4
Up Type=0
Dn Type=3
Dn Slope=0.005
Boundary for River Rch & Prof#=UNT 163 in LFCCL,Reach-1,5
Up Type=0
Dn Type=3
Dn Slope=0.005
Boundary for River Rch & Prof#=UNT 163 in LFCCL,Reach-1,6
Up Type=0
Dn Type=3
Dn Slope=0.005
Boundary for River Rch & Prof#=UNT 163 in LFCCL,Reach-1,7
Up Type=0
Dn Type=3
Dn Slope=0.005

--- UNT 163 in LFCCL Watershed.g01 (geometry) ---

Geom Title=Existing Conditions

River Reach=UNT 163 in LFCCL,Reach-1
Reach XY= 30
      2791063.51      7026602.01      2791175.05      7026645.41
      2791309.60      7026808.78      2791612.38      7026789.33
      2791796.41      7026835.86      2791968.46      7027067.63
      2792073.49      7027534.43      2792255.78      7027700.23
      2792620.77      7027630.52      2792786.66      7027685.71
      2792853.92      7027643.24      2792998.78      7027670.52
      2793209.72      7027757.76      2793564.04      7028073.55
      2793961.89      7028187.65      2794241.94      7028407.57
      2794626.80      7028478.01      2794899.92      7028467.39
      2795041.41      7028616.72      2795263.44      7028502.29
      2795359.49      7028522.96      2795378.27      7028576.55
      2795538.78      7028640.19      2795639.45      7028823.23
      2795854.39      7028775.64      2796019.90      7028951.06
      2796164.21      7028909.70      2796362.52      7028609.17
      2796324.33      7028425.55      2796505.59      7028400.71

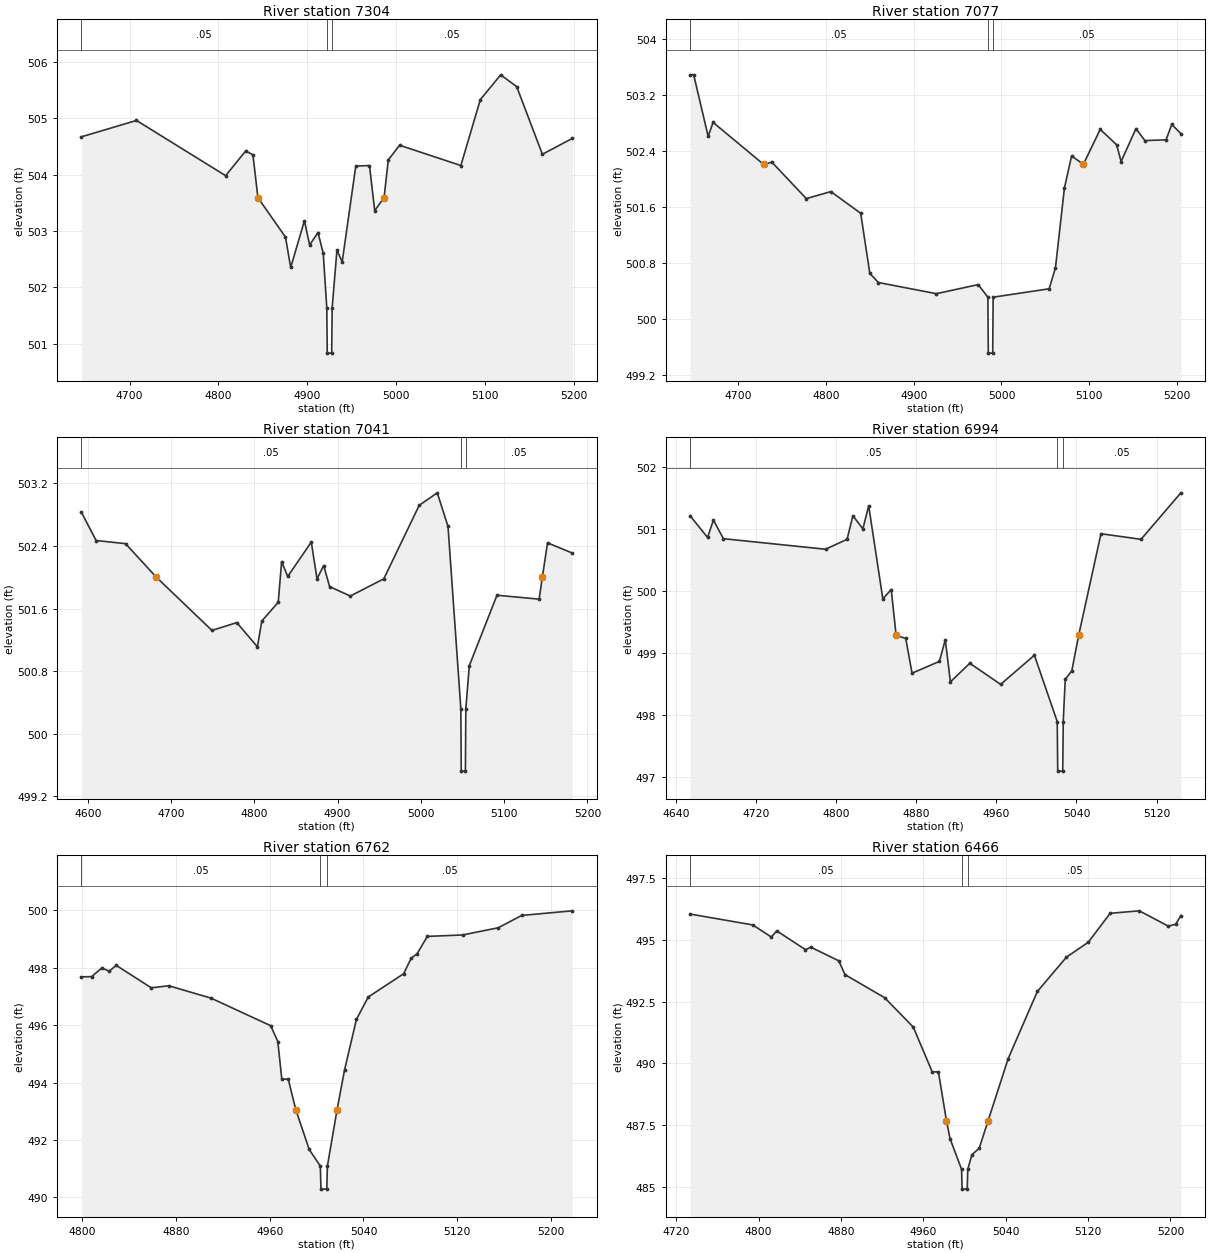
Type RM Length L Ch R = 1,7304,227,227,227
BEGIN DESCRIPTION:
UNT 163 in LFCCL Watershed 15.0
END DESCRIPTION:
XS GIS Cut Line= 3
      2791026.95      7026981.96      2791217.19      7026675.99
      2791293.88      7026500.18
#Sta/Elev= 30
  4645.9  504.67  4707.8  504.96  4808.1  503.98  4830.7  504.42  4838.8  504.35
  4844.4  503.59  4875.4  502.89  4881.3  502.35  4896.7  503.18  4902.6  502.75
  4912.0  502.97  4917.9  502.60  4921.9  501.63  4922.4  500.83  4927.4  500.83
  4927.9  501.63  4933.3  502.66  4939.2  502.45  4954.5  504.15  4969.9  504.16
  4975.8  503.36  4986.3  503.59  4991.1  504.26  5003.8  504.52  5072.7  504.16
  5094.6  505.33  5117.5  505.77  5135.5  505.56  5164.4  504.36  5198.0  504.64
#Mann=3,-1,0
  4645.9    0.05       0  4921.9    0.03       0  4927.9    0.05       0
Bank Sta=4844.4,4986.3
Exp/Cntr=0.3,0.1

Type RM Length L Ch R = 1,7077,36,36,36
BEGIN DESCRIPTION:
XS3931A
END DESCRIPTION:
XS GIS Cut Line= 6
      2791142.65      7027029.78      2791312.77      7026944.72
      2791364.85      7026913.47      2791375.27      7026850.97
      2791344.02      7026764.16      2791373.54      7026614.82
#Sta/Elev= 30
  4645.2  503.49  4649.3  503.49  4665.8  502.61  4671.4  502.81  4728.9  502.21
  4738.5  502.24  4777.6  501.72  4805.6  501.82  4839.6  501.51  4850.0  500.65
  4859.7  500.52  4925.8  500.36  4973.5  500.49  4984.5  500.31  4985.0  499.51
  4990.0  499.51  4990.5  500.31  5054.3  500.43  5061.5  500.73  5071.7  501.87
  5079.9  502.33  5093.3  502.21  5112.5  502.71  5131.2  502.49  5136.3  502.25
  5153.2  502.72  5163.4  502.55  5187.5  502.56  5194.0  502.78  5204.4  502.65
#Mann=3,-1,0
  4645.2    0.05       0  4984.5    0.03       0  4990.5    0.05       0
Bank Sta=4728.9,5093.3
Exp/Cntr=0.3,0.1

Type RM Length L Ch R = 1,7041,47,47,47
BEGIN DESCRIPTION:
XS3932A
END DESCRIPTION:
XS GIS Cut Line= 6
      2791135.73      7027047.13      2791356.17      7026962.08
      2791392.63      7026927.36      2791408.26      7026870.06
      2791382.21      7026755.48      2791401.31      7026635.68
#Sta/Elev= 30
  4592.4  502.83  4610.0  502.47  4645.3  502.43  4682.4  502.00  4749.1  501.32
  4779.0  501.42  4803.7  501.11  4809.0  501.44  4828.7  501.68  4832.8  502.20
  4840.1  502.01  4868.4  502.45  4875.3  501.98  4883.3  502.15  4890.4  501.88
  4915.3  501.76  4955.5  501.98  4998.0  502.92  5019.7  503.08  5032.6  502.65
  5048.0  500.32  5048.5  499.52  5053.5  499.52  5054.0  500.32  5058.2  500.87
  5091.4  501.77  5142.0  501.72  5145.9  502.00  5152.1  502.44  5181.8  502.31
#Mann=3,-1,0
  4592.4    0.05       0  5048.0    0.03       0  5054.0    0.05       0
Bank Sta=4682.4,5145.9
Exp/Cntr=0.3,0.1

Type RM Length L Ch R = 1,6994,232,232,232
BEGIN DESCRIPTION:
XS3933A
END DESCRIPTION:
XS GIS Cut Line= 6
      2791245.04      7027048.90      2791413.46      7026951.66
      2791436.03      7026922.15      2791448.19      7026849.23
      2791439.51      7026778.05      2791436.03      7026665.21
#Sta/Elev= 30
  4654.1  501.21  4671.6  500.86  4677.4  501.14  4687.4  500.84  4789.4  500.67
  4810.9  500.83  4816.7  501.21  4826.7  501.00  4832.5  501.37  4846.6  499.87
  4855.0  500.02  4859.9  499.28  4869.5  499.23  4875.8  498.67  4903.1  498.86
  4909.0  499.21  4914.1  498.53  4933.5  498.83  4964.3  498.49  4998.0  498.96
  5020.8  497.89  5021.3  497.09  5026.3  497.09  5026.8  497.89  5028.8  498.57
  5035.4  498.71  5042.2  499.28  5064.5  500.92  5104.5  500.83  5144.3  501.58
#Mann=3,-1,0
  4654.1    0.05       0  5020.8    0.03       0  5026.8    0.05       0
Bank Sta=4859.9,5042.2
Exp/Cntr=0.3,0.1

Type RM Length L Ch R = 1,6762,296,296,296
BEGIN DESCRIPTION:
XS3934A
END DESCRIPTION:
XS GIS Cut Line= 3
      2791576.65      7026979.46      2791673.88      7026835.34
      2791642.63      7026592.29
#Sta/Elev= 30
  4799.3  497.68  4808.0  497.69  4816.7  497.99  4823.0  497.88  4829.0  498.08
  4858.9  497.30  4873.9  497.37  4909.9  496.94  4960.8  495.98  4966.9  495.43
  4970.3  494.12  4975.8  494.12  4982.2  493.06  4993.7  491.67  5003.2  491.09
  5003.7  490.29  5008.7  490.29  5009.2  491.09  5017.5  493.06  5023.9  494.45
  5034.0  496.20  5044.1  496.98  5074.3  497.79  5080.7  498.33  5085.7  498.48
  5094.5  499.09  5124.7  499.14  5155.0  499.39  5175.1  499.82  5218.2  499.98
#Mann=3,-1,0
  4799.3    0.05       0  5003.2    0.03       0  5009.2    0.05       0
Bank Sta=4982.2,5017.5
Exp/Cntr=0.3,0.1

Type RM Length L Ch R = 1,6466,244,244,244
BEGIN DESCRIPTION:
XS3935A
END DESCRIPTION:
XS GIS Cut Line= 3
      2791616.59      7027073.19      2791844.02      7027005.48
      2792014.17      7026837.07
#Sta/Elev= 30
  4733.4  496.04  4794.3  495.60  4812.3  495.11  4817.6  495.36  4845.5  494.60
  4850.7  494.70  4877.8  494.15  4883.9  493.59  4922.3  492.66  4950.2  491.47
  4968.6  489.66  4974.6  489.66  4982.4  487.69  4985.9  486.96  4997.1  485.72
  4997.6  484.92  5002.6  484.92  5003.1  485.72  5007.1  486.31  5014.2  486.57
  5022.9  487.69  5042.4  490.20  5070.7  492.91  5099.0  494.30  5120.2  494.90
  5141.4  496.07  5169.7  496.17  5198.0  495.55  5205.1  495.63  5210.1  495.98
#Mann=3,-1,0
  4733.4    0.05       0  4997.1    0.03       0  5003.1    0.05       0
Bank Sta=4982.4,5022.9
Exp/Cntr=0.3,0.1

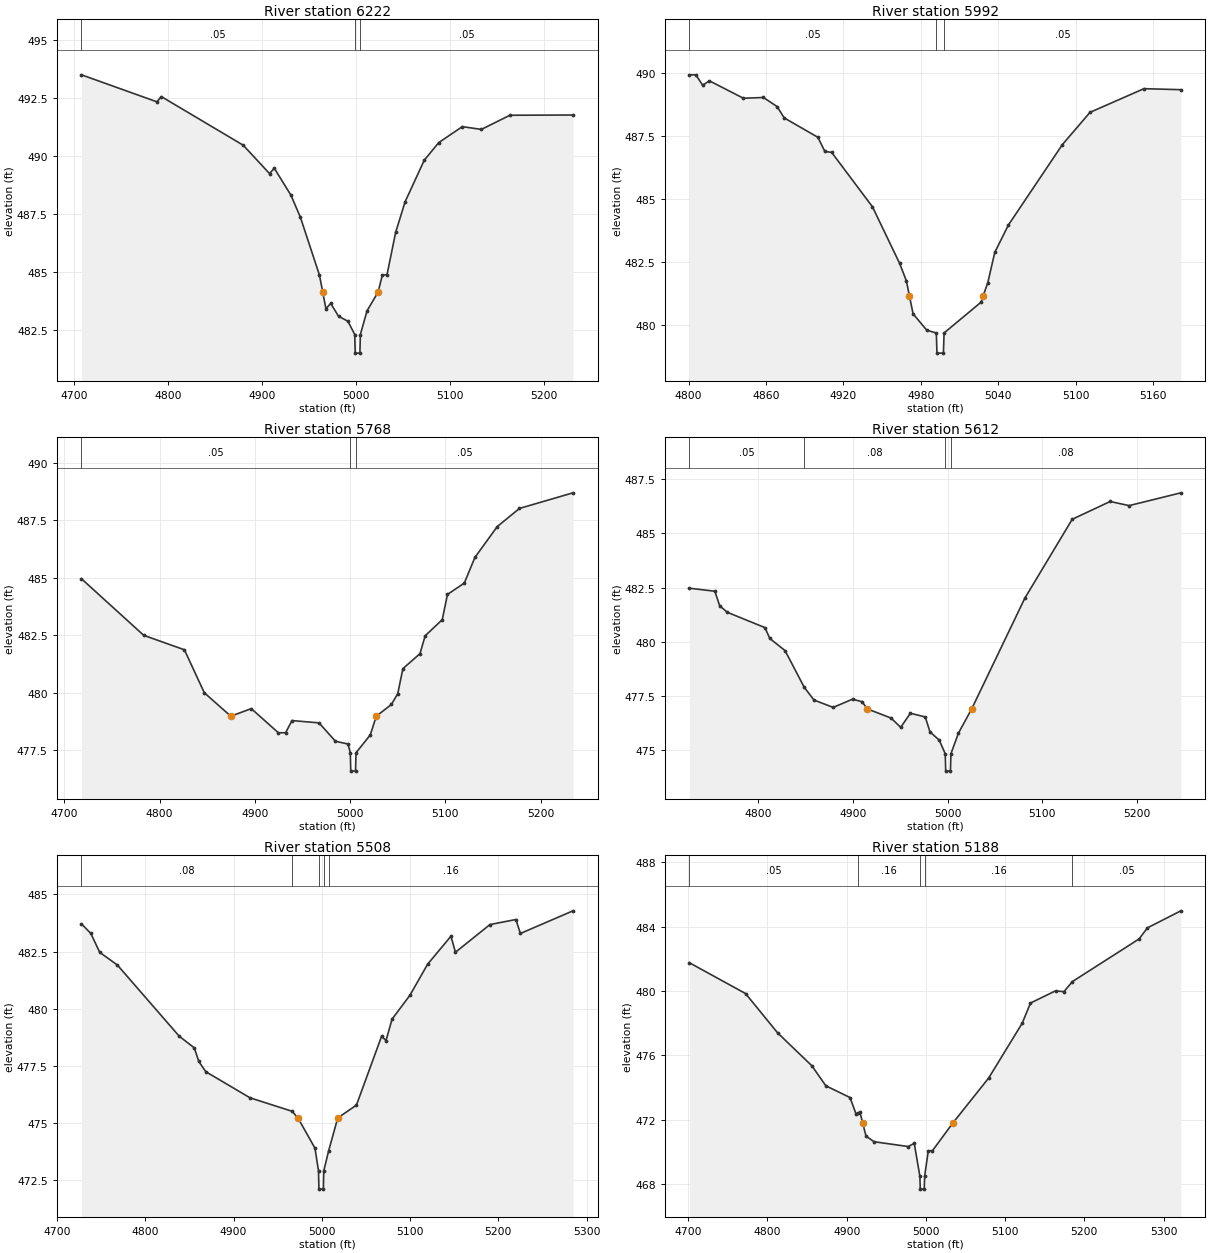
Type RM Length L Ch R = 1,6222,230,230,230
BEGIN DESCRIPTION:
XS3936A
END DESCRIPTION:
XS GIS Cut Line= 2
      2791705.13      7027224.23      2792221.23      7027135.91
#Sta/Elev= 30
  4707.8  493.49  4788.0  492.33  4793.0  492.55  4880.1  490.46  4908.1  489.24
  4913.2  489.47  4930.9  488.31  4941.0  487.36  4961.3  484.87  4964.8  484.14
  4968.2  483.42  4973.3  483.65  4981.6  483.10  4991.7  482.88  4998.9  482.31
  4999.4  481.51  5004.4  481.51  5004.9  482.31  5012.0  483.33  5023.8  484.14
  5028.3  484.87  5033.3  484.89  5042.5  486.71  5052.6  488.03  5072.9  489.81
  5088.3  490.57  5113.5  491.26  5133.8  491.14  5164.2  491.75  5231.4  491.76
#Mann=3,-1,0
  4707.8    0.05       0  4998.9    0.03       0  5004.9    0.05       0
Bank Sta=4964.8,5023.8
Exp/Cntr=0.3,0.1

Type RM Length L Ch R = 1,5992,224,224,224
BEGIN DESCRIPTION:
XS3937A
END DESCRIPTION:
XS GIS Cut Line= 2
      2791840.54      7027453.40      2792201.72      7027332.43
#Sta/Elev= 30
  4800.6  489.93  4805.6  489.93  4810.9  489.52  4816.2  489.69  4842.5  489.00
  4858.0  489.03  4868.6  488.67  4874.1  488.22  4900.2  487.45  4905.6  486.89
  4910.9  486.85  4942.5  484.69  4963.5  482.45  4968.8  481.75  4971.2  481.14
  4974.0  480.44  4984.6  479.79  4992.0  479.68  4992.5  478.88  4997.5  478.88
  4998.0  479.68  5026.6  480.90  5028.2  481.14  5031.9  481.68  5037.3  482.88
  5047.9  483.97  5089.7  487.16  5111.1  488.44  5152.9  489.38  5181.5  489.34
#Mann=3,-1,0
  4800.6    0.05       0  4992.0    0.03       0  4998.0    0.05       0
Bank Sta=4971.2,5028.2
Exp/Cntr=0.3,0.1

Type RM Length L Ch R = 1,5768,156,156,156
BEGIN DESCRIPTION:
XS3938A
END DESCRIPTION:
XS GIS Cut Line= 3
      2791903.02      7027785.02      2792104.44      7027606.18
      2792203.40      7027380.48
#Sta/Elev= 30
  4718.1  484.95  4783.4  482.49  4826.1  481.86  4847.0  479.99  4874.8  478.97
  4896.3  479.30  4924.7  478.25  4932.3  478.25  4939.0  478.78  4967.4  478.68
  4984.6  477.88  4997.8  477.76  5000.2  477.38  5000.7  476.58  5005.7  476.58
  5006.2  477.38  5021.1  478.15  5027.5  478.97  5043.3  479.48  5050.0  479.95
  5055.4  481.04  5073.3  481.69  5078.8  482.47  5096.7  483.17  5102.2  484.27
  5119.8  484.76  5131.0  485.88  5154.4  487.22  5177.7  488.01  5233.9  488.69
#Mann=3,-1,0
  4718.1    0.05       0  5000.2    0.03       0  5006.2    0.05       0
Bank Sta=4874.8,5027.5
Exp/Cntr=0.3,0.1

Type RM Length L Ch R = 1,5612,104,104,104
BEGIN DESCRIPTION:
XS3939A
END DESCRIPTION:
XS GIS Cut Line= 3
      2792194.72      7027934.29      2792245.06      7027661.73
      2792253.74      7027420.46
#Sta/Elev= 30
  4727.5  482.47  4754.4  482.33  4759.5  481.66  4767.5  481.36  4807.3  480.65
  4812.4  480.15  4828.5  479.59  4848.7  477.90  4859.0  477.31  4879.3  476.97
  4899.7  477.35  4909.8  477.23  4915.3  476.90  4940.3  476.48  4950.5  476.05
  4960.7  476.70  4976.4  476.53  4981.4  475.84  4991.2  475.46  4997.5  474.83
  4998.0  474.03  5003.0  474.03  5003.5  474.83  5011.4  475.78  5025.4  476.90
  5081.5  482.01  5131.5  485.65  5171.5  486.47  5191.5  486.28  5246.1  486.87
#Mann=4,-1,0
  4727.5    0.05       0  4848.7    0.08       0  4997.5    0.07       0
  5003.5    0.08       0
Bank Sta=4915.3,5025.4
Exp/Cntr=0.3,0.1

Type RM Length L Ch R = 1,5508,320,320,320
BEGIN DESCRIPTION:
XS3940A
END DESCRIPTION:
XS GIS Cut Line= 3
      2792300.62      7027965.55      2792319.71      7027701.66
      2792357.91      7027411.74
#Sta/Elev= 30
  4727.6  483.71  4738.2  483.29  4748.2  482.47  4768.3  481.91  4838.4  478.80
  4855.5  478.29  4860.5  477.70  4868.5  477.25  4918.6  476.11  4966.4  475.52
  4972.9  475.23  4992.2  473.91  4996.2  472.92  4996.7  472.12  5001.7  472.12
  5002.2  472.92  5007.6  473.78  5018.0  475.23  5039.2  475.79  5067.7  478.80
  5072.7  478.61  5079.6  479.55  5099.8  480.59  5119.9  481.95  5146.3  483.17
  5151.4  482.47  5190.5  483.68  5219.9  483.90  5225.0  483.29  5284.6  484.28
#Mann=5,-1,0
  4727.6    0.08       0  4966.4    0.05       0  4996.2    0.03       0
  5002.2    0.05       0  5007.6    0.16       0
Bank Sta=4972.9,5018
Exp/Cntr=0.3,0.1

Type RM Length L Ch R = 1,5188,344,344,344
BEGIN DESCRIPTION:
UNT 163 in LFCCL Watershed 14.0
END DESCRIPTION:
XS GIS Cut Line= 3
      2792575.00      7027925.00      2792625.00      7027625.00
      2792524.99      7027324.96
#Sta/Elev= 30
  4701.4  481.76  4772.4  479.84  4812.9  477.39  4856.0  475.35  4873.7  474.10
  4904.2  473.37  4911.8  472.35  4913.8  472.39  4916.8  472.45  4920.2  471.79
  4924.4  470.97  4934.6  470.62  4977.7  470.32  4985.3  470.52  4992.4  468.47
  4992.9  467.67  4997.9  467.67  4998.4  468.47  5003.0  470.06  5008.2  470.06
  5034.1  471.79  5079.3  474.59  5121.5  477.99  5132.0  479.25  5163.6  480.01
  5174.2  479.96  5185.0  480.59  5269.1  483.24  5279.6  483.93  5321.8  484.99
#Mann=5,-1,0
  4701.4    0.05       0  4913.8    0.16       0  4992.4    0.07       0
  4998.4    0.16       0  5185.0    0.05       0
Bank Sta=4920.2,5034.1
Exp/Cntr=0.3,0.1

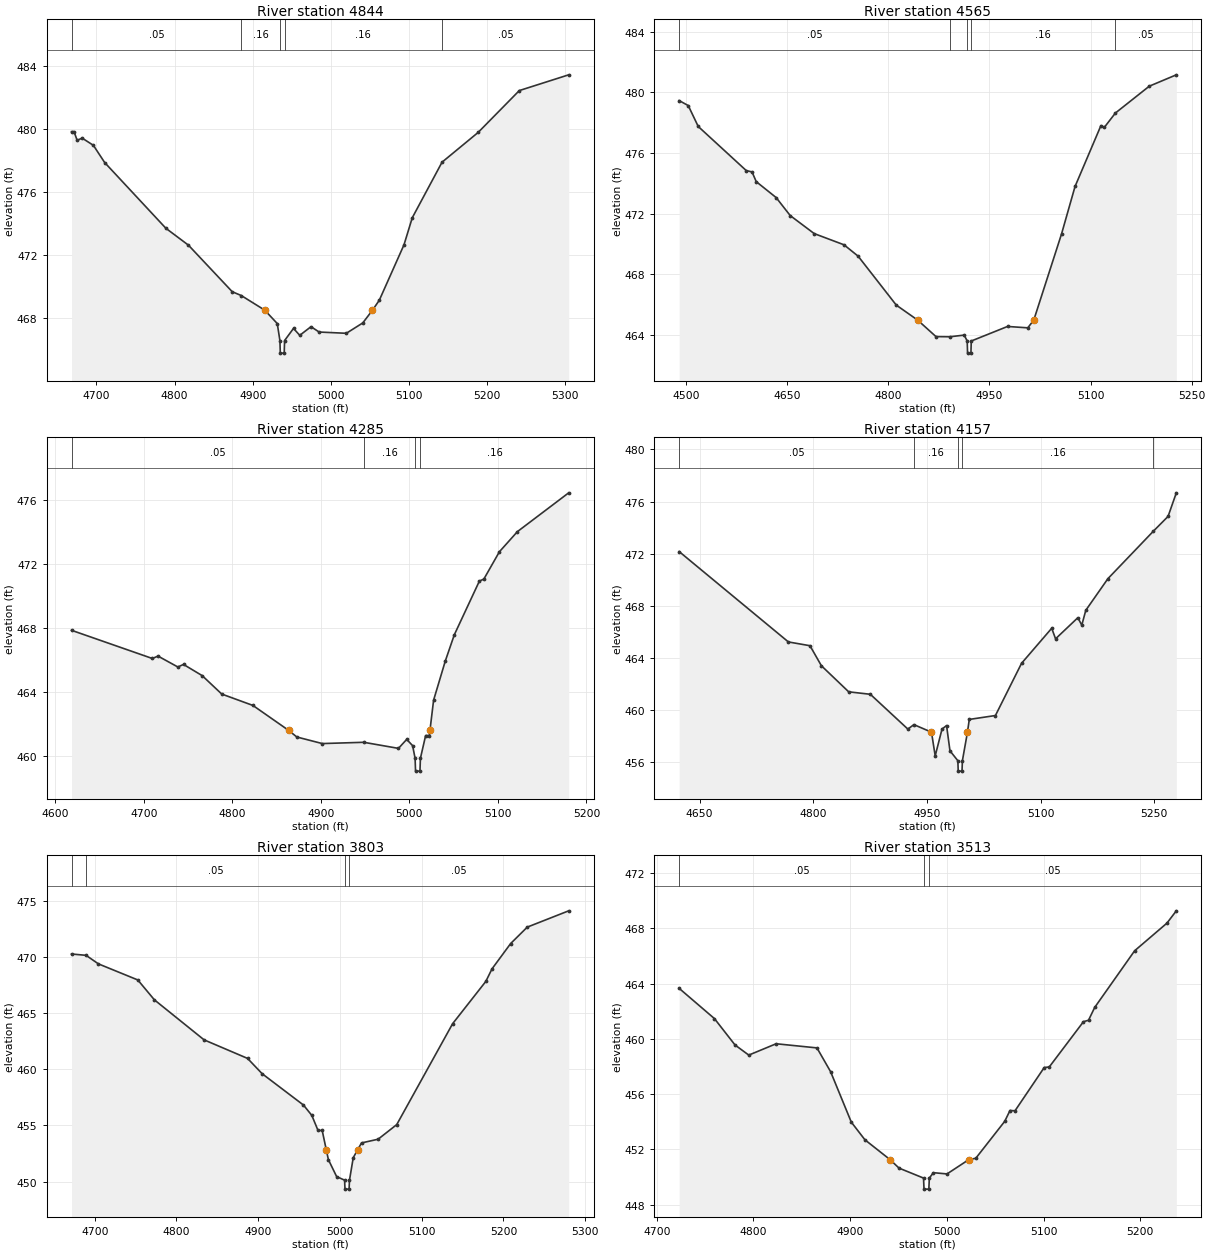
Type RM Length L Ch R = 1,4844,279,279,279
BEGIN DESCRIPTION:
UNT 163 in LFCCL Watershed 13.0
END DESCRIPTION:
XS GIS Cut Line= 3
      2792675.03      7027874.98      2792925.00      7027675.00
      2793024.98      7027375.05
#Sta/Elev= 30
  4668.2  479.86  4671.4  479.86  4675.4  479.31  4681.8  479.45  4696.2  478.99
  4710.6  477.90  4789.0  473.72  4817.8  472.65  4873.9  469.69  4885.4  469.45
  4915.5  468.52  4931.5  467.67  4934.9  466.59  4935.4  465.79  4940.4  465.79
  4940.9  466.59  4952.3  467.36  4960.3  466.92  4974.7  467.47  4985.1  467.13
  5019.9  467.05  5041.0  467.71  5053.4  468.52  5062.1  469.15  5093.7  472.67
  5104.3  474.39  5142.4  477.92  5188.6  479.81  5241.3  482.47  5304.5  483.47
#Mann=5,-1,0
  4668.2    0.05       0  4885.4    0.16       0  4934.9    0.07       0
  4940.9    0.16       0  5142.4    0.05       0
Bank Sta=4915.5,5053.4
Exp/Cntr=0.3,0.1

Type RM Length L Ch R = 1,4565,280,280,280
BEGIN DESCRIPTION:
UNT 163 in LFCCL Watershed 12.0
END DESCRIPTION:
XS GIS Cut Line= 3
      2792824.99      7028075.01      2793188.40      7027815.29
      2793175.00      7027524.98
#Sta/Elev= 30
  4489.9  479.46  4503.4  479.13  4518.2  477.75  4589.4  474.84  4598.0  474.75
  4604.2  474.11  4633.7  473.06  4654.6  471.87  4690.2  470.68  4734.4  469.94
  4755.3  469.19  4811.9  465.96  4843.6  464.97  4870.8  463.88  4891.5  463.87
  4912.6  463.98  4917.1  463.59  4917.6  462.79  4922.6  462.79  4923.1  463.59
  4976.9  464.55  5006.9  464.46  5015.8  464.97  5057.0  470.66  5077.0  473.79
  5115.4  477.81  5120.4  477.69  5136.9  478.64  5187.1  480.41  5227.2  481.16
#Mann=5,-1,0
  4489.9    0.05       0  4891.5    0.16       0  4917.1    0.07       0
  4923.1    0.16       0  5136.9    0.05       0
Bank Sta=4843.6,5015.8
Exp/Cntr=0.3,0.1

Type RM Length L Ch R = 1,4285,128,128,128
BEGIN DESCRIPTION:
XS3941A
END DESCRIPTION:
XS GIS Cut Line= 4
      2793120.06      7028178.22      2793365.29      7027980.74
      2793408.69      7027902.62      2793438.73      7027748.14
#Sta/Elev= 30
  4618.4  467.86  4709.7  466.10  4716.1  466.25  4738.5  465.57  4744.9  465.73
  4766.0  465.03  4788.1  463.88  4823.3  463.17  4863.5  461.62  4872.9  461.20
  4901.7  460.79  4948.5  460.87  4987.7  460.49  4997.0  461.05  5003.7  460.66
  5006.5  459.87  5007.0  459.07  5012.0  459.07  5012.5  459.87  5018.4  461.29
  5022.6  461.29  5023.3  461.62  5027.4  463.50  5040.6  465.94  5050.8  467.58
  5079.1  470.93  5084.2  471.06  5101.7  472.76  5122.1  474.02  5180.0  476.44
#Mann=4,-1,0
  4618.4    0.05       0  4948.5    0.16       0  5006.5    0.07       0
  5012.5    0.16       0
Bank Sta=4863.5,5023.3
Exp/Cntr=0.3,0.1

Type RM Length L Ch R = 1,4157,354,354,354
BEGIN DESCRIPTION:
UNT 163 in LFCCL Watershed 11.0
END DESCRIPTION:
XS GIS Cut Line= 3
      2793275.01      7028324.98      2793475.00      7028025.00
      2793552.90      7027739.67
#Sta/Elev= 30
  4622.9  472.16  4767.1  465.22  4795.6  464.93  4810.7  463.39  4846.7  461.39
  4875.3  461.20  4924.8  458.53  4932.8  458.87  4956.0  458.29  4960.9  456.47
  4969.9  458.53  4975.9  458.80  4980.4  456.86  4990.8  456.10  4991.3  455.30
  4996.3  455.30  4996.8  456.10  5003.5  458.29  5005.9  459.27  5040.4  459.57
  5074.9  463.58  5114.7  466.27  5119.8  465.46  5149.2  467.08  5154.4  466.51
  5159.7  467.65  5188.9  470.08  5249.0  473.73  5268.3  474.86  5279.2  476.67
#Mann=5,-1,0
  4622.9    0.05       0  4932.8    0.16       0  4990.8    0.07       0
  4996.8    0.16       0  5249.0    0.05       0
Bank Sta=4956,5003.5
Exp/Cntr=0.3,0.1

Type RM Length L Ch R = 1,3803,290,290,290
BEGIN DESCRIPTION:
UNT 163 in LFCCL Watershed 10.0
END DESCRIPTION:
XS GIS Cut Line= 3
      2793725.00      7028474.98      2793775.00      7028175.00
      2793825.01      7027874.96
#Sta/Elev= 30
  4671.6  470.25  4689.4  470.13  4704.5  469.37  4752.7  467.94  4773.0  466.17
  4833.8  462.61  4887.0  460.96  4904.8  459.60  4955.4  456.81  4965.6  455.89
  4973.2  454.55  4978.3  454.55  4983.3  452.83  4985.9  451.95  4996.0  450.44
  5005.7  450.13  5006.2  449.33  5011.2  449.33  5011.7  450.13  5016.3  452.13
  5021.7  452.83  5026.4  453.44  5046.7  453.77  5069.5  455.07  5137.9  464.05
  5178.5  467.81  5186.1  468.93  5208.9  471.18  5229.2  472.64  5279.9  474.09
#Mann=4,-1,0
  4671.6    0.16       0  4689.4    0.05       0  5005.7    0.03       0
  5011.7    0.05       0
Bank Sta=4983.3,5021.7
Exp/Cntr=0.3,0.1

Type RM Length L Ch R = 1,3513,393,393,393
BEGIN DESCRIPTION:
XS3942A
END DESCRIPTION:
XS GIS Cut Line= 3
      2793842.69      7028434.33      2794044.54      7028238.99
      2794103.14      7028013.27
#Sta/Elev= 30
  4723.2  463.66  4759.7  461.47  4781.0  459.56  4795.2  458.83  4823.5  459.65
  4865.7  459.35  4879.8  457.63  4901.2  453.98  4915.3  452.70  4941.2  451.27
  4950.6  450.65  4975.9  449.93  4976.4  449.13  4981.4  449.13  4981.9  449.93
  4986.1  450.32  5000.2  450.23  5022.8  451.27  5029.9  451.36  5059.9  454.04
  5065.3  454.82  5070.5  454.80  5100.7  457.93  5105.9  457.97  5141.3  461.25
  5146.5  461.35  5152.9  462.28  5194.2  466.38  5227.6  468.38  5237.3  469.27
#Mann=3,-1,0
  4723.2    0.05       0  4975.9    0.03       0  4981.9    0.05       0
Bank Sta=4941.2,5022.8
Exp/Cntr=0.3,0.1

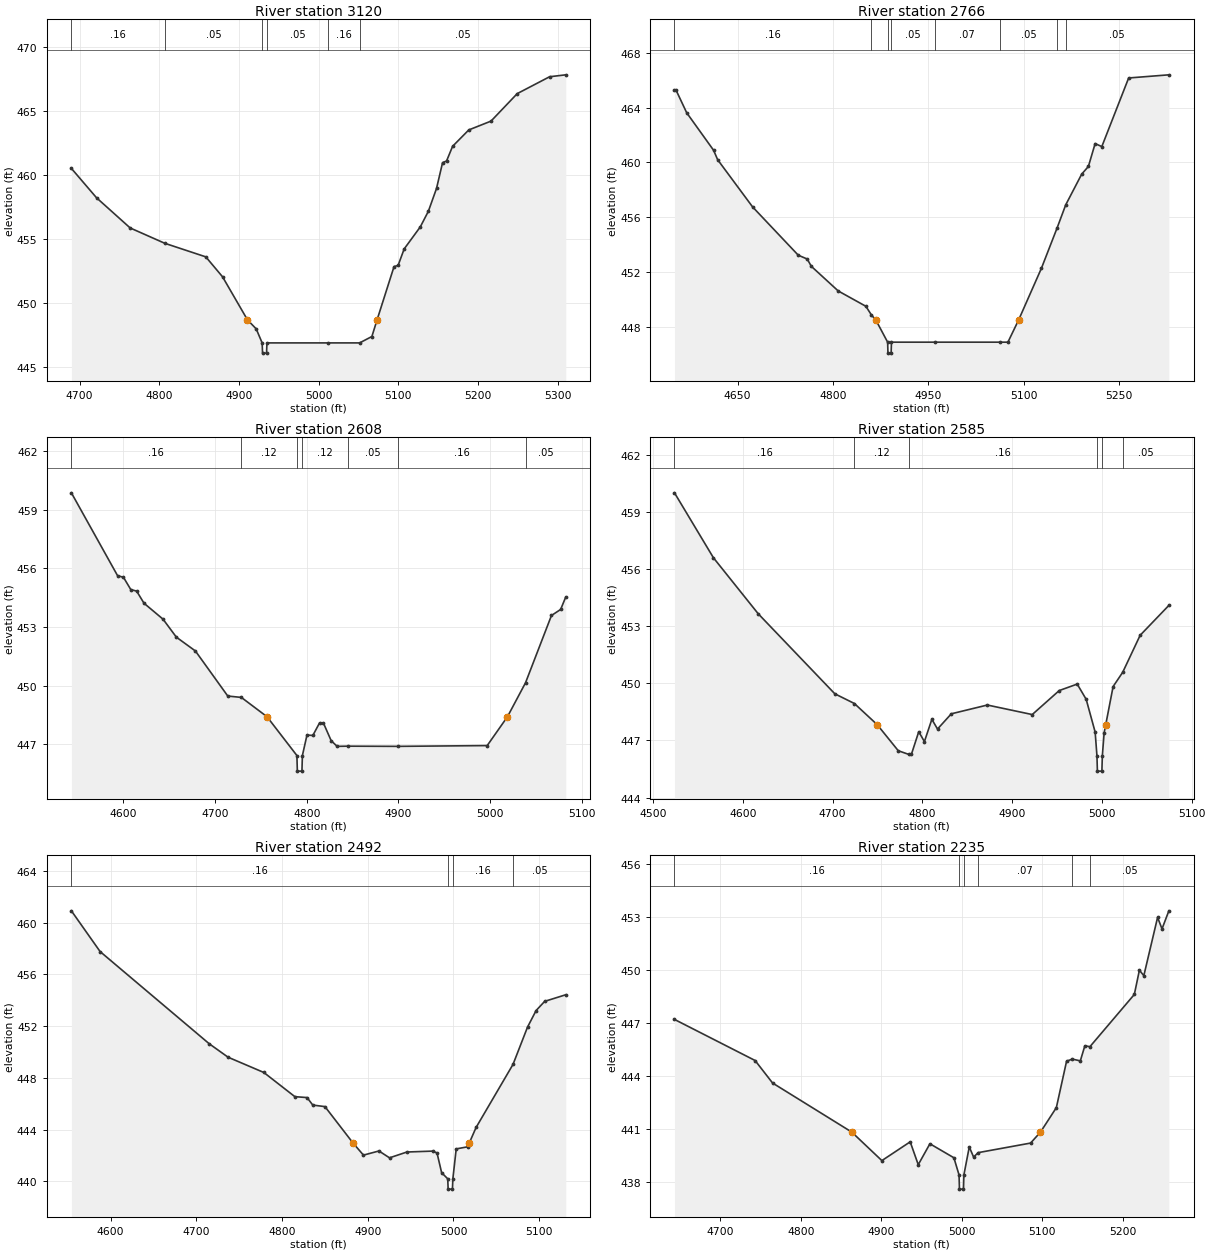
Type RM Length L Ch R = 1,3120,354,354,354
BEGIN DESCRIPTION:
UNT 163 in LFCCL Watershed 8.0
END DESCRIPTION:
XS GIS Cut Line= 3
      2794275.00      7028725.01      2794375.00      7028425.00
      2794425.00      7028124.97
#Sta/Elev= 30
  4689.7  460.53  4721.3  458.23  4763.5  455.87  4807.0  454.67  4858.4  453.61
  4879.4  452.05  4910.7  448.68  4921.6  447.98  4929.1  446.88  4929.6  446.08
  4934.6  446.08  4935.1  446.88  5011.4  446.88  5051.4  446.88  5066.8  447.38
  5073.3  448.68  5094.6  452.85  5099.7  452.94  5107.3  454.23  5127.6  455.96
  5137.7  457.18  5147.9  458.96  5155.5  460.98  5160.5  461.11  5168.1  462.26
  5188.4  463.54  5216.3  464.23  5249.2  466.38  5289.8  467.70  5310.1  467.85
#Mann=6,-1,0
  4689.7    0.16       0  4807.0    0.05       0  4929.1   0.035       0
  4935.1    0.05       0  5011.4    0.16       0  5051.4    0.05       0
Bank Sta=4910.7,5073.3
Exp/Cntr=0.3,0.1

Type RM Length L Ch R = 1,2766,158,158,158
BEGIN DESCRIPTION:
UNT 163 in LFCCL Watershed 7.0
END DESCRIPTION:
XS GIS Cut Line= 3
      2794625.00      7028925.01      2794725.00      7028475.00
      2794625.01      7028175.02
#Sta/Elev= 30
  4550.9  465.27  4553.5  465.27  4570.1  463.63  4612.4  460.89  4618.8  460.20
  4673.8  456.75  4745.5  453.23  4759.6  452.95  4766.0  452.42  4808.3  450.62
  4851.8  449.50  4860.6  448.86  4867.3  448.51  4886.0  446.88  4886.5  446.08
  4891.5  446.08  4892.0  446.88  4960.3  446.88  5062.0  446.88  5075.1  446.88
  5092.0  448.51  5127.8  452.28  5152.5  455.23  5166.0  456.91  5191.1  459.15
  5201.6  459.71  5212.2  461.38  5222.7  461.16  5264.9  466.17  5328.1  466.40
#Mann=8,-1,0
  4550.9    0.16       0  4860.6    0.05       0  4886.0    0.07       0
  4892.0    0.05       0  4960.3    0.07       0  5062.0    0.05       0
  5152.5    0.16       0  5166.0    0.05       0
Bank Sta=4867.3,5092
Exp/Cntr=0.3,0.1

Type RM Length L Ch R = 1,2608,23,23,23
BEGIN DESCRIPTION:
XS3943A
END DESCRIPTION:
XS GIS Cut Line= 3
      2794697.73      7028868.36      2794869.19      7028653.48
      2794882.18      7028389.41
#Sta/Elev= 30
  4543.2  459.88  4593.6  455.63  4600.0  455.55  4608.0  454.92  4614.4  454.84
  4622.4  454.22  4643.2  453.40  4657.7  452.48  4678.5  451.77  4713.8  449.46
  4728.6  449.39  4756.6  448.40  4789.2  446.41  4789.7  445.61  4794.7  445.61
  4795.2  446.41  4800.2  447.46  4806.6  447.44  4813.9  448.08  4818.1  448.08
  4826.6  447.17  4833.1  446.88  4844.7  446.89  4899.2  446.88  4996.8  446.92
  5018.9  448.40  5038.6  450.14  5066.9  453.59  5076.9  453.90  5082.5  454.54
#Mann=7,-1,0
  4543.2    0.16       0  4728.6    0.12       0  4789.2    0.07       0
  4795.2    0.12       0  4844.7    0.05       0  4899.2    0.16       0
  5038.6    0.05       0
Bank Sta=4756.6,5018.9
Exp/Cntr=0.3,0.1

Type RM Length L Ch R = 1,2585,93,93,93
BEGIN DESCRIPTION:
XS3944A
END DESCRIPTION:
XS GIS Cut Line= 3
      2794712.96      7028883.50      2794890.89      7028649.14
      2794903.92      7028393.02
#Sta/Elev= 30
  4523.9  460.00  4567.3  456.59  4617.2  453.65  4702.5  449.45  4724.3  448.94
  4749.7  447.83  4773.2  446.46  4784.8  446.27  4787.8  446.27  4796.0  447.46
  4802.3  446.94  4810.6  448.11  4816.9  447.60  4832.3  448.40  4872.4  448.86
  4922.4  448.36  4952.5  449.62  4972.5  449.96  4982.5  449.16  4992.5  447.44
  4994.5  446.19  4995.0  445.39  5000.0  445.39  5000.5  446.19  5002.5  447.40
  5004.3  447.83  5012.5  449.83  5023.2  450.58  5042.6  452.52  5074.6  454.09
#Mann=6,-1,0
  4523.9    0.16       0  4724.3    0.12       0  4784.8    0.16       0
  4994.5    0.07       0  5000.5    0.16       0  5023.2    0.05       0
Bank Sta=4749.7,5004.3
Exp/Cntr=0.3,0.1

Type RM Length L Ch R = 1,2492,257,257,257
BEGIN DESCRIPTION:
XS3945A
END DESCRIPTION:
XS GIS Cut Line= 4
      2794736.85      7028913.87      2794929.96      7028688.21
      2794953.83      7028536.30      2794953.83      7028410.38
#Sta/Elev= 30
  4554.3  460.91  4587.8  457.76  4715.1  450.63  4737.1  449.59  4778.8  448.41
  4815.0  446.54  4829.2  446.47  4835.9  445.89  4850.1  445.77  4882.9  442.95
  4895.0  442.02  4913.1  442.34  4925.4  441.81  4945.7  442.26  4975.7  442.33
  4980.8  442.19  4986.2  440.66  4993.3  440.19  4993.8  439.39  4998.8  439.39
  4999.3  440.19  5003.2  442.50  5016.4  442.66  5018.4  442.95  5026.4  444.16
  5069.5  449.04  5086.4  451.92  5096.4  453.20  5106.4  453.91  5131.0  454.42
#Mann=4,-1,0
  4554.3    0.16       0  4993.3    0.07       0  4999.3    0.16       0
  5069.5    0.05       0
Bank Sta=4882.9,5018.4
Exp/Cntr=0.3,0.1

Type RM Length L Ch R = 1,2235,234,234,234
BEGIN DESCRIPTION:
XS3947A
END DESCRIPTION:
XS GIS Cut Line= 4
      2795125.28      7028890.01      2795201.22      7028673.02
      2795112.25      7028445.15      2794986.37      7028384.38
#Sta/Elev= 30
  4643.1  447.20  4743.3  444.88  4765.0  443.61  4863.4  440.84  4900.8  439.23
  4936.0  440.29  4946.0  439.00  4960.5  440.18  4990.3  439.39  4996.7  438.42
  4997.2  437.62  5002.2  437.62  5002.7  438.42  5009.4  440.00  5014.8  439.43
  5020.5  439.68  5085.6  440.22  5097.9  440.84  5117.6  442.22  5130.3  444.84
  5137.4  444.96  5147.4  444.86  5153.0  445.71  5159.3  445.66  5214.5  448.61
  5220.8  449.98  5226.3  449.67  5243.4  452.96  5248.9  452.31  5257.4  453.33
#Mann=6,-1,0
  4643.1    0.16       0  4996.7    0.07       0  5002.7    0.16       0
  5020.5    0.07       0  5137.4    0.16       0  5159.3    0.05       0
Bank Sta=4863.4,5097.9
Exp/Cntr=0.3,0.1

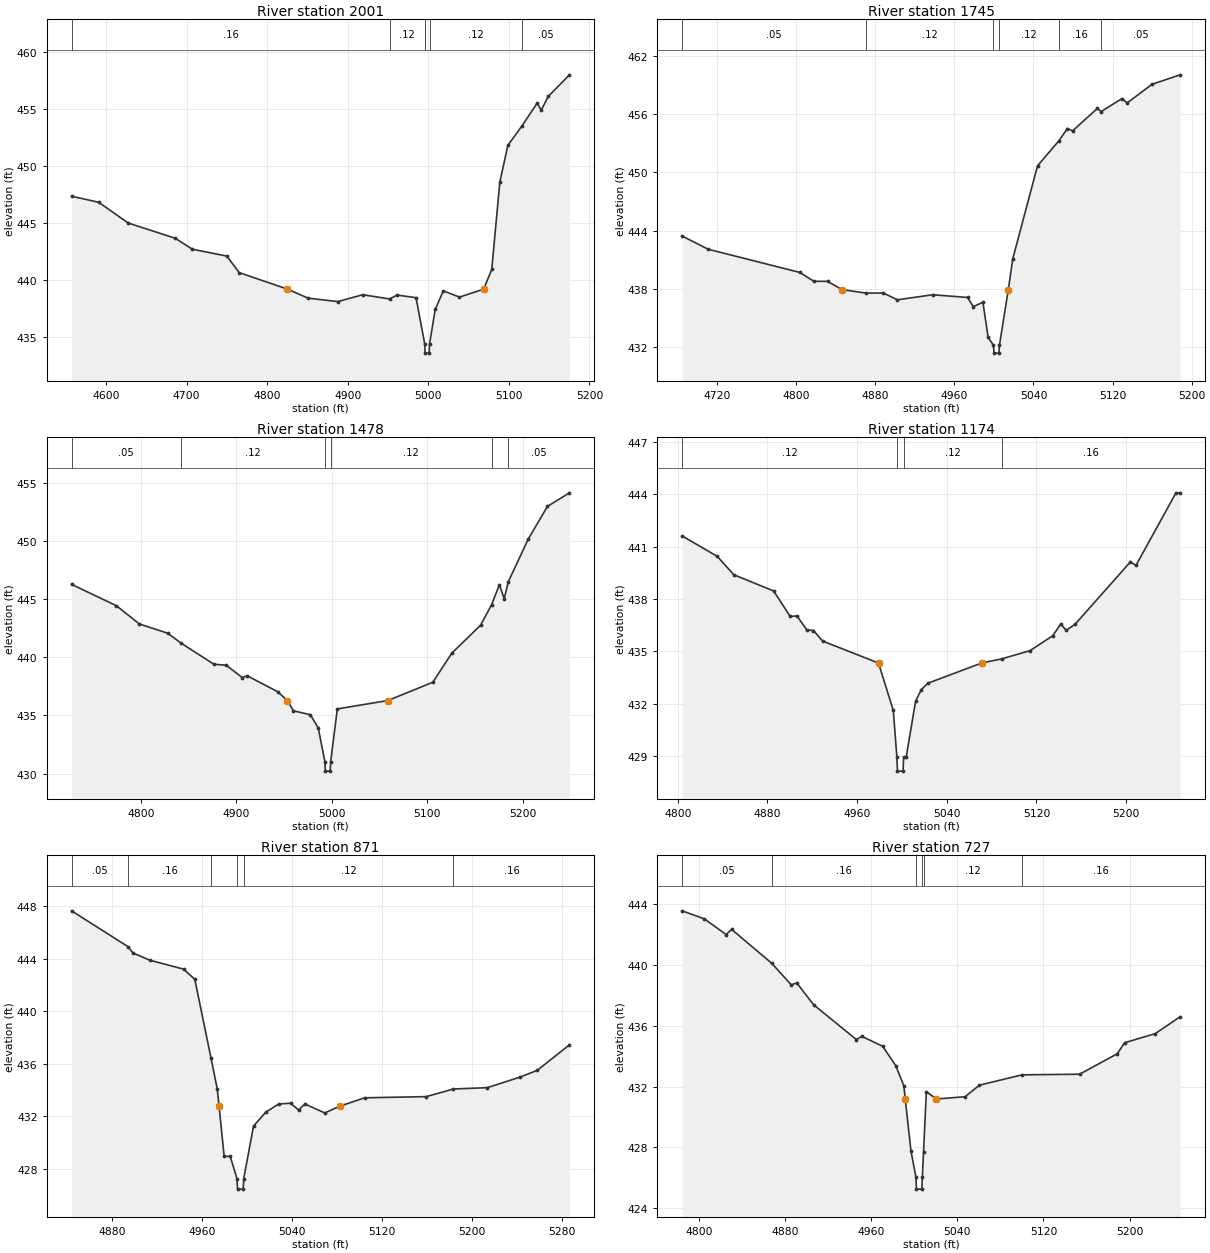
Type RM Length L Ch R = 1,2001,256,256,256
BEGIN DESCRIPTION:
XS3946A
END DESCRIPTION:
XS GIS Cut Line= 3
      2795140.45      7028905.24      2795359.64      7028542.81
      2795372.59      7028348.70
#Sta/Elev= 30
  4557.2  447.34  4590.8  446.81  4627.6  444.99  4685.9  443.66  4707.2  442.70
  4749.9  442.10  4765.4  440.65  4824.8  439.22  4850.8  438.42  4887.7  438.12
  4918.7  438.72  4951.9  438.35  4961.4  438.69  4984.8  438.46  4995.6  434.41
  4996.1  433.61  5001.1  433.61  5001.6  434.41  5008.6  437.43  5018.7  439.06
  5038.7  438.51  5068.8  439.21  5078.8  440.94  5088.8  448.56  5098.8  451.79
  5115.9  453.45  5135.2  455.49  5140.2  454.86  5148.9  456.07  5175.3  457.96
#Mann=5,-1,0
  4557.2    0.16       0  4951.9    0.12       0  4995.6    0.07       0
  5001.6    0.12       0  5115.9    0.05       0
Bank Sta=4824.8,5068.8
Exp/Cntr=0.3,0.1

Type RM Length L Ch R = 1,1745,267,267,267
BEGIN DESCRIPTION:
XS3948A
END DESCRIPTION:
XS GIS Cut Line= 3
      2795316.27      7028863.96      2795537.60      7028662.16
      2795609.22      7028471.16
#Sta/Elev= 30
  4684.8  443.44  4711.2  442.08  4803.8  439.69  4817.9  438.78  4831.9  438.77
  4846.3  437.92  4870.9  437.56  4888.2  437.57  4902.4  436.87  4938.2  437.39
  4973.4  437.11  4979.2  436.17  4988.9  436.61  4994.2  433.00  4999.6  432.17
  5000.1  431.37  5005.1  431.37  5005.6  432.17  5014.6  437.92  5019.1  441.10
  5044.1  450.68  5065.8  453.28  5074.3  454.53  5079.7  454.30  5104.6  456.60
  5108.5  456.28  5129.5  457.62  5134.8  457.17  5159.8  459.09  5188.3  460.07
#Mann=6,-1,0
  4684.8    0.05       0  4870.9    0.12       0  4999.6    0.07       0
  5005.6    0.12       0  5065.8    0.16       0  5108.5    0.05       0
Bank Sta=4846.3,5014.6
Exp/Cntr=0.3,0.1

Type RM Length L Ch R = 1,1478,304,304,304
BEGIN DESCRIPTION:
XS3949A
END DESCRIPTION:
XS GIS Cut Line= 3
      2795583.18      7029085.31      2795676.49      7028853.14
      2795667.81      7028581.89
#Sta/Elev= 30
  4727.5  446.27  4774.5  444.43  4798.6  442.86  4828.2  442.07  4842.0  441.23
  4876.6  439.40  4889.5  439.32  4906.2  438.26  4911.6  438.40  4943.4  437.04
  4953.5  436.28  4959.9  435.40  4977.7  435.06  4985.9  433.92  4992.9  431.01
  4993.4  430.21  4998.4  430.21  4998.9  431.01  5005.9  435.56  5058.8  436.28
  5105.9  437.85  5125.9  440.36  5155.9  442.75  5167.4  444.50  5175.7  446.24
  5180.7  445.04  5185.1  446.51  5206.0  450.18  5226.0  452.97  5249.1  454.14
#Mann=6,-1,0
  4727.5    0.05       0  4842.0    0.12       0  4992.9    0.07       0
  4998.9    0.12       0  5167.4    0.16       0  5185.1    0.05       0
Bank Sta=4953.5,5058.8
Exp/Cntr=0.3,0.1

Type RM Length L Ch R = 1,1174,303,303,303
BEGIN DESCRIPTION:
XS3951A
END DESCRIPTION:
XS GIS Cut Line= 3
      2795802.34      7028996.39      2795917.37      7028837.95
      2795956.43      7028592.73
#Sta/Elev= 30
  4804.0  441.61  4835.3  440.44  4850.0  439.39  4885.6  438.46  4900.3  437.00
  4906.4  437.03  4915.0  436.24  4921.1  436.19  4929.3  435.59  4979.1  434.33
  4992.3  431.62  4995.5  428.94  4996.0  428.14  5001.0  428.14  5001.5  428.94
  5003.8  428.94  5012.2  432.15  5017.2  432.80  5023.0  433.17  5071.0  434.33
  5089.0  434.57  5114.2  435.04  5134.4  435.89  5141.6  436.56  5146.6  436.20
  5154.7  436.57  5203.7  440.12  5208.8  439.93  5244.4  444.08  5248.1  444.08
#Mann=4,-1,0
  4804.0    0.12       0  4995.5    0.07       0  5001.5    0.12       0
  5089.0    0.16       0
Bank Sta=4979.1,5071
Exp/Cntr=0.3,0.1

Type RM Length L Ch R = 1,871,144,144,144
BEGIN DESCRIPTION:
XS3950A
END DESCRIPTION:
XS GIS Cut Line= 3
      2796151.74      7029074.45      2796147.41      7028937.77
      2796022.02      7028658.91
#Sta/Elev= 30
  4844.0  447.63  4894.1  444.91  4898.7  444.42  4913.5  443.88  4943.5  443.20
  4953.5  442.43  4967.9  436.45  4973.5  434.08  4975.1  432.78  4979.6  428.97
  4985.0  428.97  4991.0  427.28  4991.5  426.48  4996.5  426.48  4997.0  427.28
  5005.7  431.27  5016.7  432.34  5028.2  432.95  5038.6  433.01  5045.8  432.49
  5051.3  432.95  5069.0  432.27  5082.3  432.78  5104.4  433.42  5159.2  433.51
  5183.4  434.09  5213.4  434.19  5242.1  434.98  5257.9  435.51  5286.5  437.45
#Mann=6,-1,0
  4844.0    0.05       0  4894.1    0.16       0  4967.9    0.12       0
  4991.0    0.07       0  4997.0    0.12       0  5183.4    0.16       0
Bank Sta=4975.1,5082.3
Exp/Cntr=0.3,0.1

Type RM Length L Ch R = 1,727,237,237,237
BEGIN DESCRIPTION:
XS3952A
END DESCRIPTION:
XS GIS Cut Line= 3
      2796277.61      7029035.41      2796247.23      7028855.31
      2796062.79      7028644.83
#Sta/Elev= 30
  4784.4  443.57  4805.1  443.04  4825.2  442.01  4830.3  442.35  4867.6  440.12
  4885.7  438.70  4890.8  438.83  4906.5  437.39  4946.2  435.10  4951.3  435.31
  4970.6  434.66  4982.7  433.39  4990.3  432.06  4991.6  431.19  4996.9  427.77
  5001.5  426.06  5002.0  425.26  5007.0  425.26  5007.5  426.06  5008.6  427.73
  5011.2  431.67  5020.6  431.19  5047.2  431.34  5060.5  432.10  5100.1  432.78
  5153.5  432.82  5188.6  434.17  5195.3  434.89  5223.8  435.49  5246.9  436.60
#Mann=6,-1,0
  4784.4    0.05       0  4867.6    0.16       0  5001.5    0.07       0
  5007.5    0.16       0  5008.6    0.12       0  5100.1    0.16       0
Bank Sta=4991.6,5020.6
Exp/Cntr=0.3,0.1

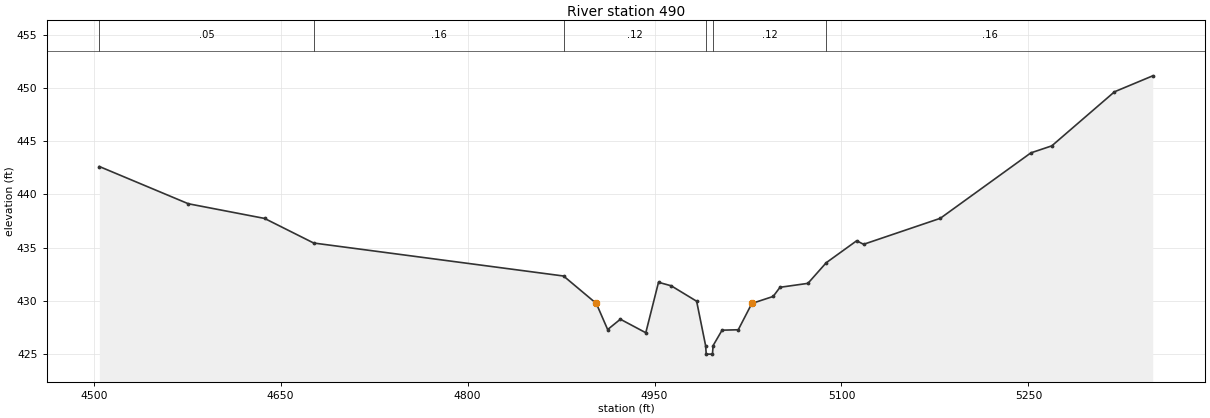
Type RM Length L Ch R = 1,490,0,0,0
BEGIN DESCRIPTION:
UNT 163 in LFCCL Watershed 1.0
END DESCRIPTION:
XS GIS Cut Line= 3
      2796425.00      7029125.00      2796325.00      7028625.00
      2796025.01      7028475.01
#Sta/Elev= 30
  4504.5  442.63  4575.9  439.13  4637.1  437.75  4676.5  435.44  4877.0  432.34
  4903.3  429.76  4912.4  427.31  4922.6  428.28  4943.0  427.01  4953.2  431.75
  4963.4  431.42  4983.8  429.97  4991.0  425.80  4991.5  425.00  4996.5  425.00
  4997.0  425.80  5004.2  427.25  5017.2  427.29  5028.1  429.76  5045.2  430.42
  5050.7  431.28  5073.1  431.65  5087.8  433.59  5112.2  435.65  5117.8  435.32
  5179.3  437.76  5252.0  443.91  5268.8  444.57  5319.1  449.65  5349.8  451.15
#Mann=6,-1,0
  4504.5    0.05       0  4676.5    0.16       0  4877.0    0.12       0
  4991.0    0.07       0  4997.0    0.12       0  5087.8    0.16       0
Bank Sta=4903.3,5028.1
Exp/Cntr=0.3,0.1

Chan Stop Cuts=-1