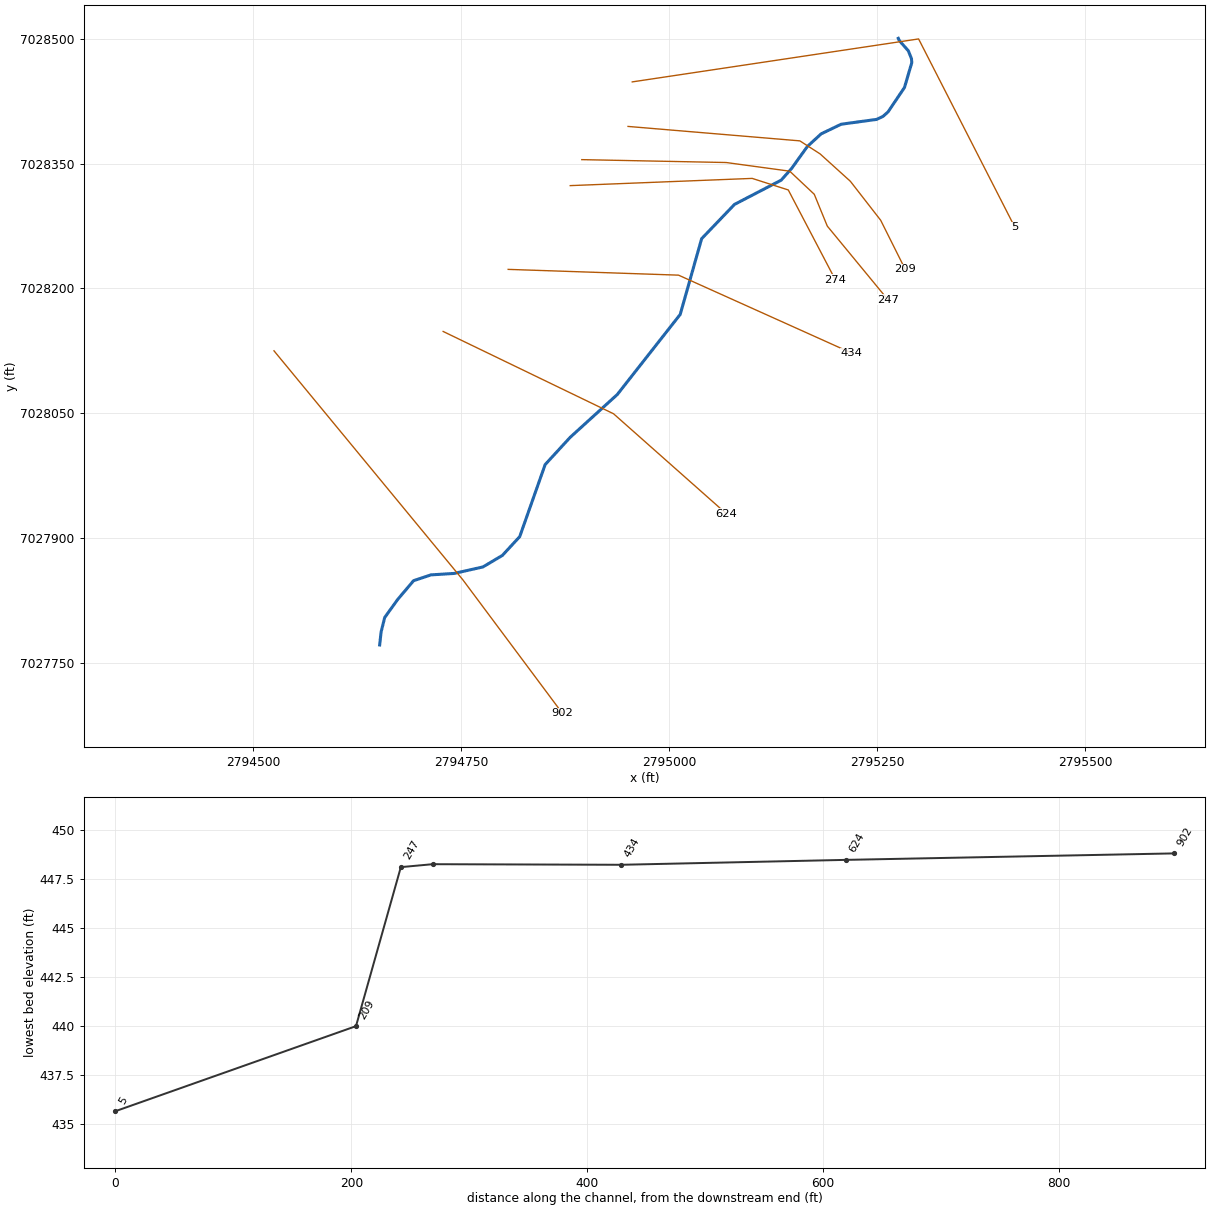
--- UNT 164 in LFCCL Watershed.prj (project) ---

Proj Title=UNT 164 in LFCCL Watershed Base Level Engineering
Current Plan=p01
Default Exp/Contr=0.3,0.1
English Units
Geom File=g01
Flow File=f01
Plan File=p01
BEGIN DESCRIPTION:
UNT 164 in LFCCL Watershed
END DESCRIPTION:

--- UNT 164 in LFCCL Watershed.p01 (plan) ---

Plan Title=Multiple Run
Short Identifier=Multiple
Geom File=g01
Flow File=f01
Subcritical Flow
K Sum by GR= 0
Std Step Tol= 0.01
Critical Tol= 0.01
Num of Std Step Trials= 20
Max Error Tol= 0.3
Flow Tol Ratio= 0.001
Split Flow NTrial= 30
Split Flow Tol= 0.02
Split Flow Ratio= 0.02
Log Output Level= 0
Friction Slope Method= 1
Unsteady Friction Slope Method= 2
Unsteady Bridges Friction Slope Method= 1
Parabolic Critical Depth
Global Vel Dist=  1 , 1 , 1
Global Log Level= 0
CheckData=True
Encroach Param= -1, 0, 0, 0
BEGIN DESCRIPTION:
Multiple Run
END DESCRIPTION:

--- UNT 164 in LFCCL Watershed.f01 (steady flow) ---

Flow Title=Multiple
Number of Profiles=7
Profile Names=10-year,25-year,50-year,1pct_min,100-year,1pct_plu,500-year
River Rch & RM= UNT 164 in LFCCL,Reach-1,902
     115     138     155      87     174     347     217
Boundary for River Rch & Prof#=UNT 164 in LFCCL,Reach-1,1
Up Type=0
Dn Type=3
Dn Slope=0.005
Boundary for River Rch & Prof#=UNT 164 in LFCCL,Reach-1,2
Up Type=0
Dn Type=3
Dn Slope=0.005
Boundary for River Rch & Prof#=UNT 164 in LFCCL,Reach-1,3
Up Type=0
Dn Type=3
Dn Slope=0.005
Boundary for River Rch & Prof#=UNT 164 in LFCCL,Reach-1,4
Up Type=0
Dn Type=3
Dn Slope=0.005
Boundary for River Rch & Prof#=UNT 164 in LFCCL,Reach-1,5
Up Type=0
Dn Type=3
Dn Slope=0.005
Boundary for River Rch & Prof#=UNT 164 in LFCCL,Reach-1,6
Up Type=0
Dn Type=3
Dn Slope=0.005
Boundary for River Rch & Prof#=UNT 164 in LFCCL,Reach-1,7
Up Type=0
Dn Type=3
Dn Slope=0.005

--- UNT 164 in LFCCL Watershed.g01 (geometry) ---

Geom Title=Existing Conditions

River Reach=UNT 164 in LFCCL,Reach-1
Reach XY= 30
      2794652.03      7027771.40      2794653.77      7027787.03
      2794658.11      7027804.39      2794673.74      7027826.09
      2794692.83      7027848.66      2794713.67      7027855.61
      2794741.44      7027857.34      2794776.17      7027865.15
      2794799.60      7027879.04      2794820.44      7027901.61
      2794850.99      7027988.20      2794881.08      7028020.99
      2794937.78      7028072.53      2795013.38      7028168.75
      2795039.15      7028259.81      2795078.67      7028301.04
      2795134.78      7028330.18      2795147.39      7028344.36
      2795166.25      7028370.64      2795182.88      7028385.89
      2795206.98      7028397.47      2795249.44      7028403.22
      2795257.16      7028406.80      2795263.26      7028412.27
      2795283.03      7028441.59      2795291.80      7028471.41
      2795291.44      7028476.30      2795287.74      7028485.58
      2795276.74      7028498.10      2795275.59      7028500.71

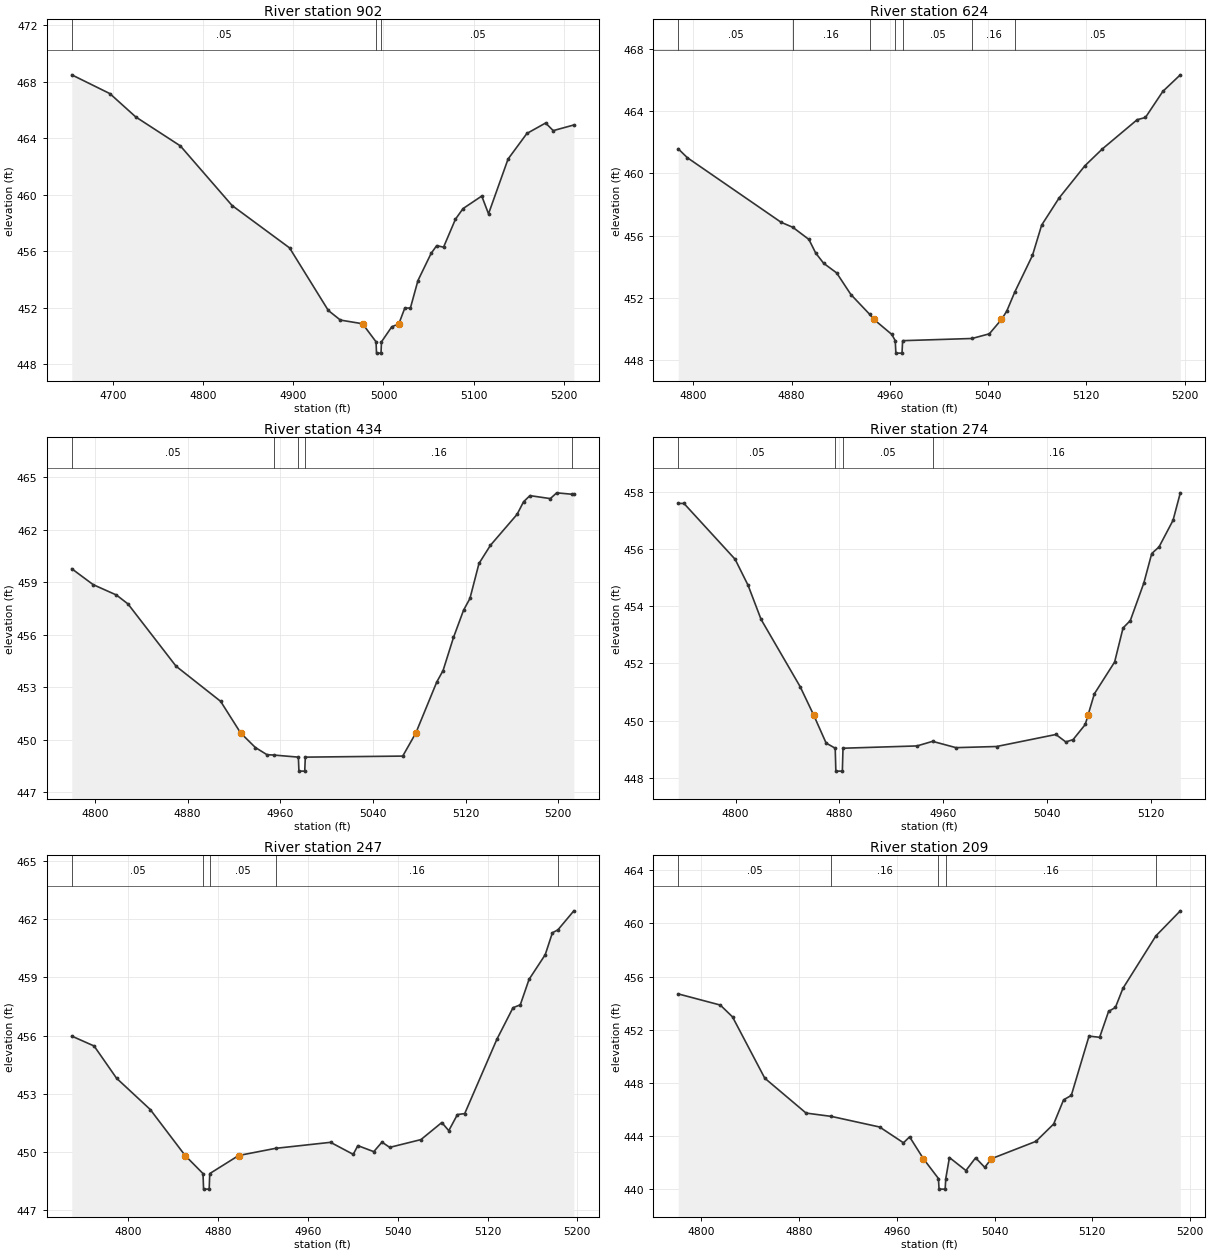
Type RM Length L Ch R = 1,902,278,278,278
BEGIN DESCRIPTION:
UNT 164 in LFCCL Watershed 1.0
END DESCRIPTION:
XS GIS Cut Line= 3
      2794524.99      7028125.01      2794752.08      7027849.65
      2794871.82      7027689.11
#Sta/Elev= 30
  4654.1  468.49  4696.4  467.16  4725.1  465.51  4774.6  463.46  4832.0  459.24
  4895.8  456.24  4938.8  451.81  4952.2  451.13  4976.8  450.87  4991.8  449.59
  4992.3  448.79  4997.3  448.79  4997.8  449.59  5009.2  450.65  5017.1  450.87
  5023.7  451.98  5029.9  451.98  5038.3  453.93  5052.9  455.85  5059.1  456.40
  5066.7  456.29  5079.9  458.27  5088.3  459.02  5109.1  459.91  5116.6  458.65
  5138.3  462.53  5159.2  464.34  5180.0  465.08  5188.4  464.54  5211.3  464.94
#Mann=3,-1,0
  4654.1    0.05       0  4991.8    0.03       0  4997.8    0.05       0
Bank Sta=4976.8,5017.1
Exp/Cntr=0.3,0.1

Type RM Length L Ch R = 1,624,190,190,190
BEGIN DESCRIPTION:
XS3956A
END DESCRIPTION:
XS GIS Cut Line= 3
      2794728.37      7028148.29      2794933.25      7028049.32
      2795068.92      7027929.11
#Sta/Elev= 30
  4787.7  461.58  4795.1  461.01  4871.5  456.86  4881.0  456.54  4894.1  455.76
  4899.6  454.89  4906.1  454.23  4916.7  453.61  4928.3  452.22  4943.6  450.95
  4947.1  450.62  4961.6  449.66  4964.4  449.26  4964.9  448.46  4969.9  448.46
  4970.4  449.26  5026.9  449.40  5041.0  449.70  5050.9  450.62  5055.2  451.16
  5061.7  452.38  5076.1  454.73  5083.6  456.68  5097.7  458.41  5118.8  460.49
  5133.0  461.57  5161.4  463.45  5168.1  463.59  5182.3  465.27  5196.5  466.33
#Mann=7,-1,0
  4787.7    0.05       0  4881.0    0.16       0  4943.6    0.05       0
  4964.4    0.03       0  4970.4    0.05       0  5026.9    0.16       0
  5061.7    0.05       0
Bank Sta=4947.1,5050.9
Exp/Cntr=0.3,0.1

Type RM Length L Ch R = 1,434,160,160,160
BEGIN DESCRIPTION:
XS3957A
END DESCRIPTION:
XS GIS Cut Line= 3
      2794806.55      7028222.93      2795011.38      7028215.99
      2795219.71      7028122.24
#Sta/Elev= 30
  4780.1  459.78  4798.6  458.87  4818.6  458.28  4828.6  457.77  4870.1  454.21
  4908.6  452.20  4925.9  450.39  4938.6  449.56  4948.6  449.15  4954.3  449.13
  4975.7  449.01  4976.2  448.21  4981.2  448.21  4981.7  449.01  5065.8  449.07
  5077.1  450.39  5095.2  453.31  5100.6  453.96  5109.6  455.85  5118.3  457.41
  5123.8  458.08  5131.6  460.08  5141.5  461.12  5164.5  462.89  5170.1  463.61
  5175.6  463.96  5193.2  463.79  5198.7  464.12  5211.7  464.04  5213.5  464.04
#Mann=5,-1,0
  4780.1    0.05       0  4954.3    0.16       0  4975.7    0.07       0
  4981.7    0.16       0  5211.7    0.05       0
Bank Sta=4925.9,5077.1
Exp/Cntr=0.3,0.1

Type RM Length L Ch R = 1,274,27,27,27
BEGIN DESCRIPTION:
XS3953A
END DESCRIPTION:
XS GIS Cut Line= 4
      2794881.20      7028323.63      2795099.92      7028332.31
      2795143.32      7028318.42      2795200.04      7028210.14
#Sta/Elev= 30
  4755.8  457.59  4760.2  457.59  4799.6  455.64  4809.6  454.73  4819.6  453.54
  4849.7  451.19  4860.0  450.21  4869.7  449.22  4876.7  449.04  4877.2  448.24
  4882.2  448.24  4882.7  449.04  4939.7  449.12  4951.7  449.28  4969.7  449.06
  5001.0  449.10  5046.7  449.52  5054.3  449.26  5059.9  449.34  5069.3  449.87
  5071.5  450.21  5076.3  450.94  5091.9  452.05  5098.4  453.24  5104.0  453.50
  5114.4  454.81  5120.5  455.84  5126.1  456.07  5136.9  457.00  5142.5  457.96
#Mann=4,-1,0
  4755.8    0.05       0  4876.7    0.07       0  4882.7    0.05       0
  4951.7    0.16       0
Bank Sta=4860,5071.5
Exp/Cntr=0.3,0.1

Type RM Length L Ch R = 1,247,38,38,38
BEGIN DESCRIPTION:
XS3955A
END DESCRIPTION:
XS GIS Cut Line= 6
      2794895.08      7028354.87      2795068.67      7028351.40
      2795145.06      7028340.99      2795174.57      7028313.21
      2795190.20      7028275.01      2795263.10      7028186.49
#Sta/Elev= 30
  4749.7  455.97  4769.6  455.46  4789.6  453.80  4819.6  452.19  4850.7  449.82
  4866.6  448.89  4867.1  448.09  4872.1  448.09  4872.6  448.89  4898.3  449.82
  4931.2  450.19  4980.2  450.50  5000.4  449.88  5004.5  450.33  5018.7  450.02
  5026.0  450.51  5032.9  450.24  5060.7  450.64  5079.3  451.52  5085.5  451.10
  5093.2  451.93  5099.7  451.98  5128.3  455.80  5142.7  457.43  5149.2  457.58
  5157.0  458.89  5171.4  460.16  5177.8  461.29  5182.7  461.44  5196.9  462.42
#Mann=5,-1,0
  4749.7    0.05       0  4866.6    0.07       0  4872.6    0.05       0
  4931.2    0.16       0  5182.7    0.05       0
Bank Sta=4850.7,4898.3
Exp/Cntr=0.3,0.1

Type RM Length L Ch R = 1,209,204,204,204
BEGIN DESCRIPTION:
XS3954A
END DESCRIPTION:
XS GIS Cut Line= 6
      2794950.66      7028394.80      2795157.21      7028377.44
      2795181.52      7028361.82      2795217.98      7028328.83
      2795254.43      7028281.96      2795283.94      7028222.94
#Sta/Elev= 30
  4781.2  454.69  4815.6  453.85  4825.6  452.96  4852.0  448.34  4885.8  445.71
  4906.5  445.46  4946.0  444.66  4965.5  443.47  4970.5  443.92  4981.8  442.27
  4994.1  440.78  4994.6  439.98  4999.6  439.98  5000.1  440.78  5003.1  442.36
  5016.6  441.38  5024.5  442.34  5032.0  441.62  5037.4  442.27  5073.9  443.58
  5088.4  444.89  5096.5  446.71  5102.8  447.04  5117.3  451.51  5126.0  451.42
  5133.3  453.37  5138.9  453.67  5145.0  455.10  5172.0  459.06  5192.0  460.95
#Mann=5,-1,0
  4781.2    0.05       0  4906.5    0.16       0  4994.1    0.07       0
  5000.1    0.16       0  5172.0    0.05       0
Bank Sta=4981.8,5037.4
Exp/Cntr=0.3,0.1

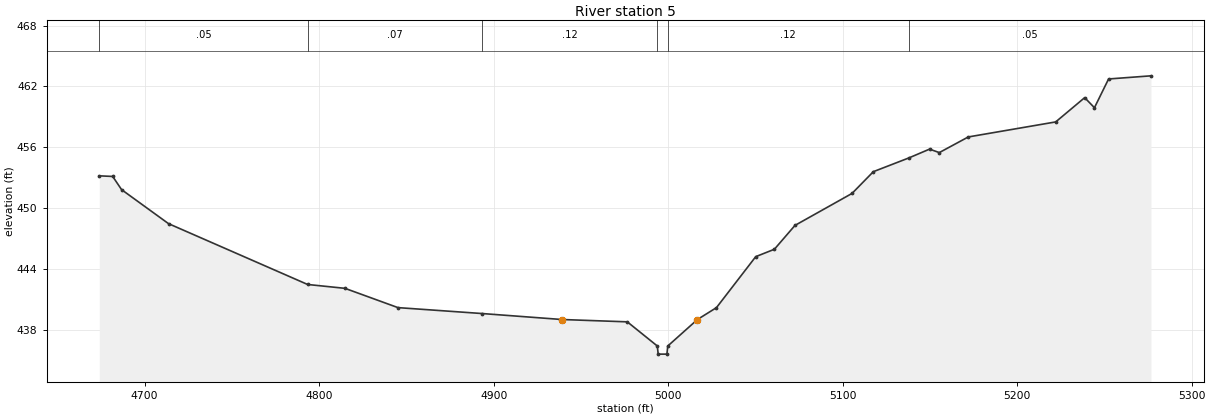
Type RM Length L Ch R = 1,5,0,0,0
BEGIN DESCRIPTION:
UNT 164 in LFCCL Watershed 0.0
END DESCRIPTION:
XS GIS Cut Line= 3
      2794955.73      7028448.34      2795300.00      7028500.00
      2795415.87      7028273.32
#Sta/Elev= 30
  4674.0  453.20  4681.7  453.14  4686.8  451.84  4713.7  448.49  4793.4  442.50
  4814.8  442.12  4845.2  440.22  4893.2  439.64  4939.1  439.05  4976.6  438.82
  4993.8  436.44  4994.3  435.64  4999.3  435.64  4999.8  436.44  5016.8  439.05
  5027.7  440.22  5050.2  445.24  5060.9  445.97  5072.7  448.32  5105.4  451.47
  5117.6  453.61  5137.9  454.96  5149.8  455.83  5155.4  455.49  5172.0  457.03
  5222.1  458.51  5238.7  460.90  5244.3  459.91  5252.4  462.74  5276.7  463.05
#Mann=6,-1,0
  4674.0    0.05       0  4793.4    0.07       0  4893.2    0.12       0
  4993.8    0.07       0  4999.8    0.12       0  5137.9    0.05       0
Bank Sta=4939.1,5016.8
Exp/Cntr=0.3,0.1

Chan Stop Cuts=-1