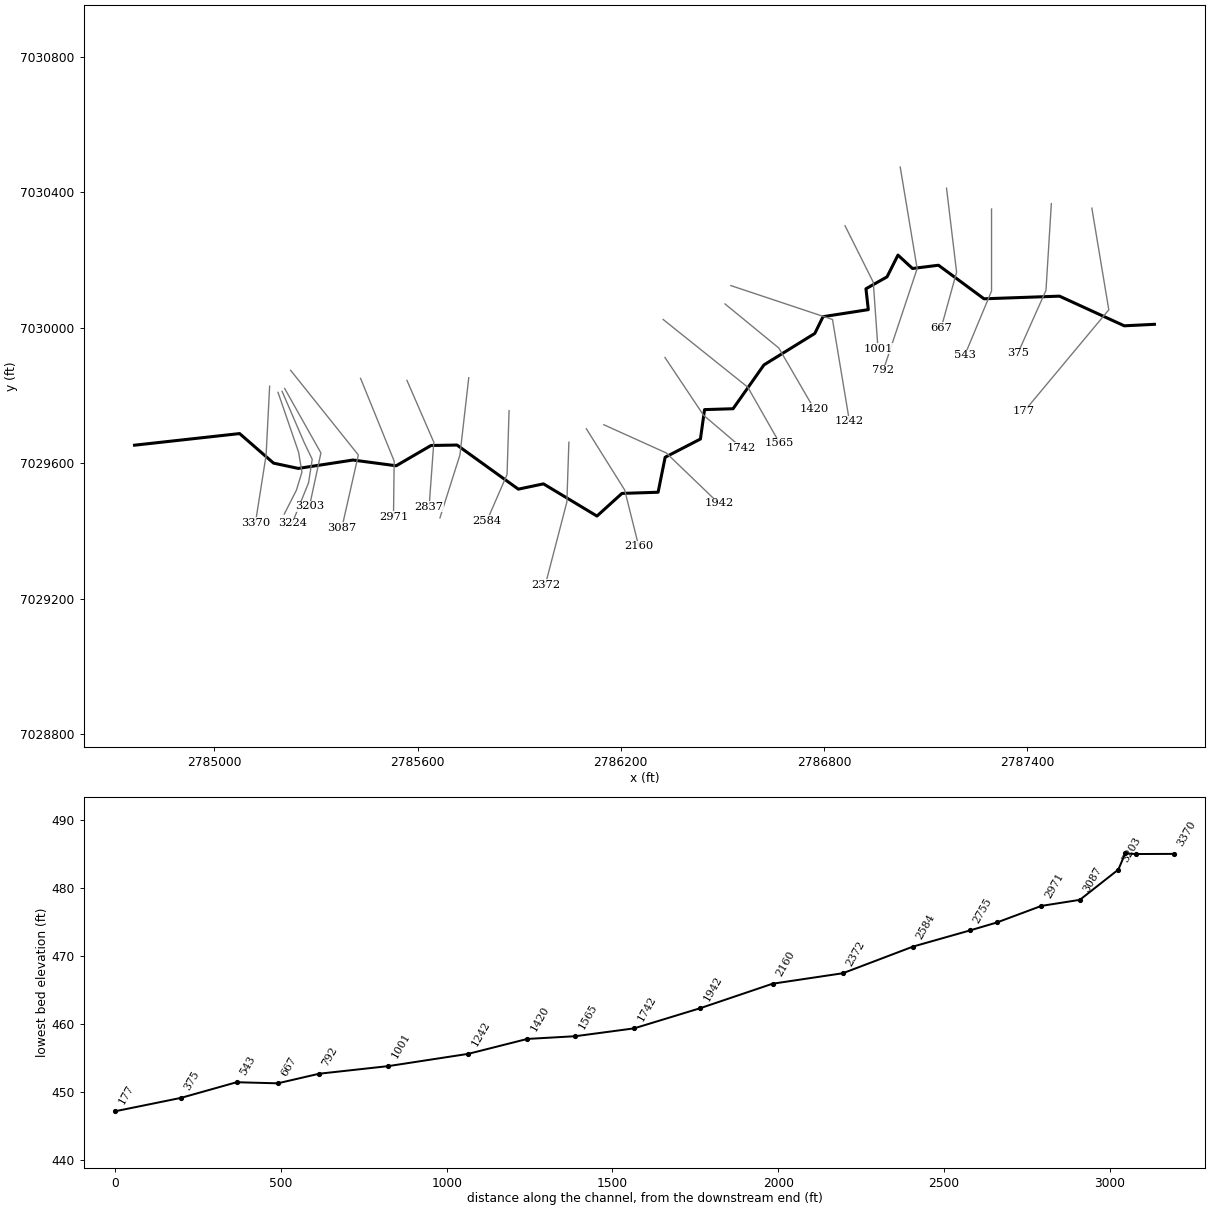
--- UNT 166 in LFCCL Watershed.prj (project) ---

Proj Title=UNT 166 in LFCCL Watershed Base Level Engineering
Current Plan=p01
Default Exp/Contr=0.3,0.1
English Units
Geom File=g01
Flow File=f01
Plan File=p01
BEGIN DESCRIPTION:
UNT 166 in LFCCL Watershed
END DESCRIPTION:

--- UNT 166 in LFCCL Watershed.p01 (plan) ---

Plan Title=Multiple Run
Short Identifier=Multiple
Geom File=g01
Flow File=f01
Subcritical Flow
K Sum by GR= 0
Std Step Tol= 0.01
Critical Tol= 0.01
Num of Std Step Trials= 20
Max Error Tol= 0.3
Flow Tol Ratio= 0.001
Split Flow NTrial= 30
Split Flow Tol= 0.02
Split Flow Ratio= 0.02
Log Output Level= 0
Friction Slope Method= 1
Unsteady Friction Slope Method= 2
Unsteady Bridges Friction Slope Method= 1
Parabolic Critical Depth
Global Vel Dist=  1 , 1 , 1
Global Log Level= 0
CheckData=True
Encroach Param= -1, 0, 0, 0
BEGIN DESCRIPTION:
Multiple Run
END DESCRIPTION:

--- UNT 166 in LFCCL Watershed.f01 (steady flow) ---

Flow Title=Multiple
Number of Profiles=7
Profile Names=10-year,25-year,50-year,1pct_min,100-year,1pct_plu,500-year
River Rch & RM= UNT 166 in LFCCL,Reach-1,3370
     163     202     230     132     263     525     342
Boundary for River Rch & Prof#=UNT 166 in LFCCL,Reach-1,1
Up Type=0
Dn Type=3
Dn Slope=0.005
Boundary for River Rch & Prof#=UNT 166 in LFCCL,Reach-1,2
Up Type=0
Dn Type=3
Dn Slope=0.005
Boundary for River Rch & Prof#=UNT 166 in LFCCL,Reach-1,3
Up Type=0
Dn Type=3
Dn Slope=0.005
Boundary for River Rch & Prof#=UNT 166 in LFCCL,Reach-1,4
Up Type=0
Dn Type=3
Dn Slope=0.005
Boundary for River Rch & Prof#=UNT 166 in LFCCL,Reach-1,5
Up Type=0
Dn Type=3
Dn Slope=0.005
Boundary for River Rch & Prof#=UNT 166 in LFCCL,Reach-1,6
Up Type=0
Dn Type=3
Dn Slope=0.005
Boundary for River Rch & Prof#=UNT 166 in LFCCL,Reach-1,7
Up Type=0
Dn Type=3
Dn Slope=0.005

--- UNT 166 in LFCCL Watershed.g01 (geometry) ---

Geom Title=Existing Conditions

River Reach=UNT 166 in LFCCL,Reach-1
Reach XY= 30
      2784764.20      7029653.89      2785074.44      7029688.17
      2785174.70      7029600.93      2785247.62      7029585.31
      2785409.08      7029610.05      2785536.68      7029593.12
      2785639.55      7029653.02      2785716.37      7029654.32
      2785897.36      7029524.11      2785971.58      7029539.74
      2786129.56      7029444.68      2786203.35      7029511.52
      2786310.12      7029515.00      2786330.95      7029618.30
      2786435.12      7029672.11      2786447.27      7029758.92
      2786531.47      7029761.52      2786622.62      7029890.86
      2786772.79      7029983.75      2786797.10      7030033.23
      2786930.78      7030054.06      2786923.84      7030115.69
      2786986.06      7030150.76      2787018.37      7030215.09
      2787061.17      7030175.51      2787137.97      7030185.14
      2787272.42      7030086.05      2787495.28      7030093.86
      2787686.58      7030006.29      2787775.59      7030010.71

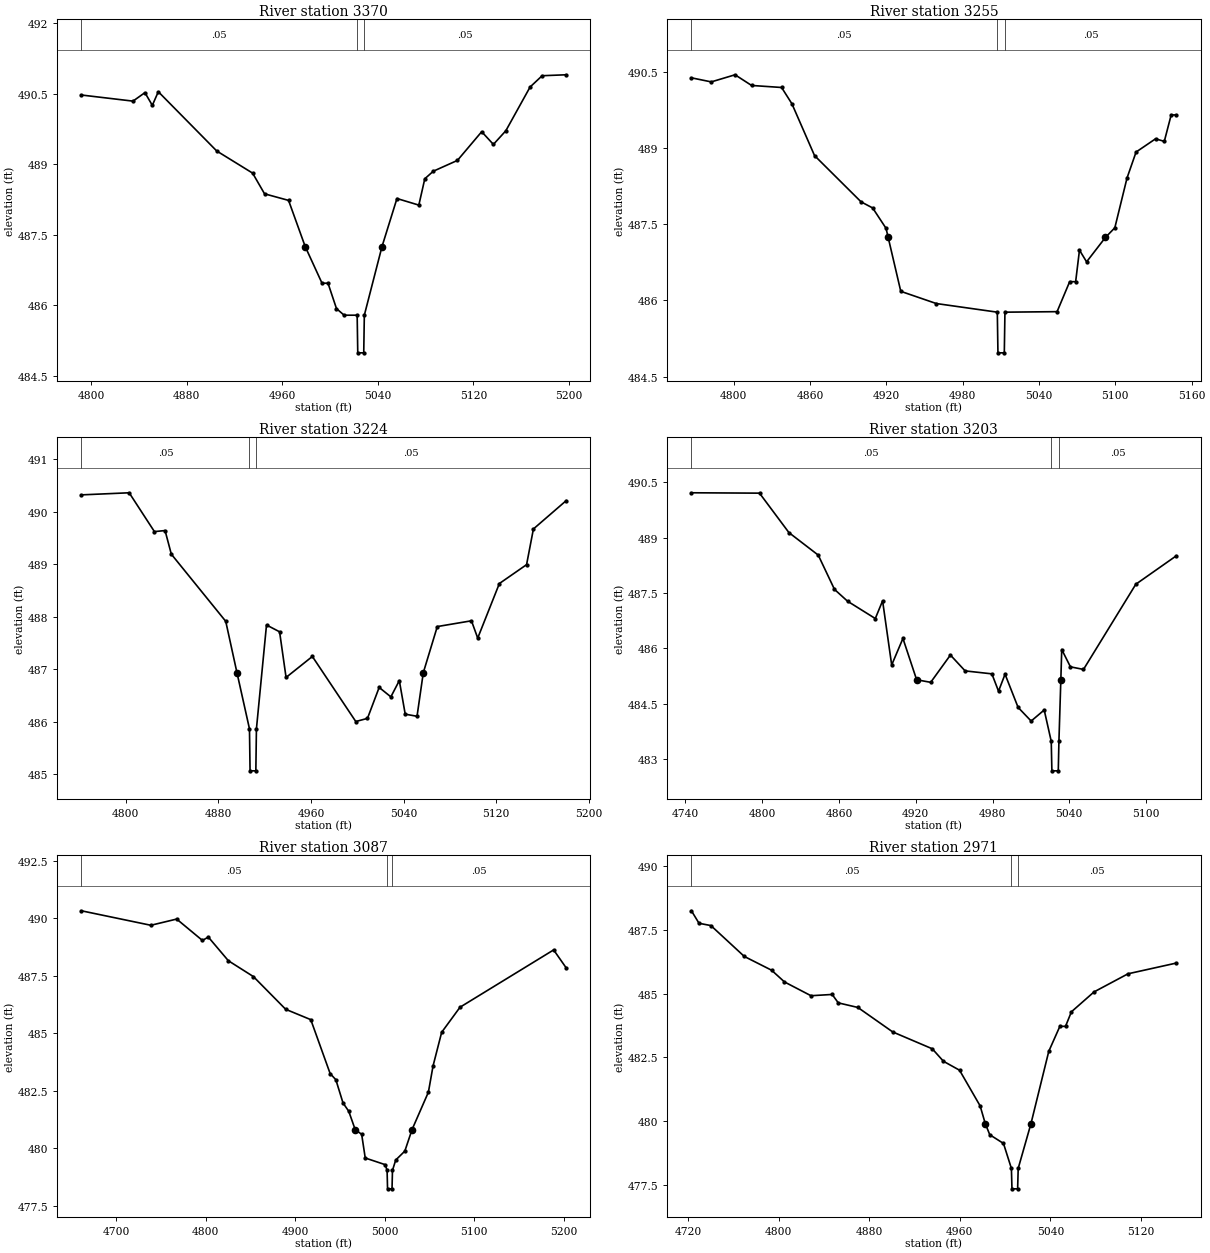
Type RM Length L Ch R = 1,3370,115,115,115
BEGIN DESCRIPTION:
XS3958A
END DESCRIPTION:
XS GIS Cut Line= 3
      2785163.10      7029828.13      2785152.64      7029624.00
      2785121.24      7029425.16
#Sta/Elev= 30
  4791.9  490.47  4835.1  490.34  4845.1  490.52  4851.3  490.25  4856.3  490.54
  4905.2  489.28  4935.2  488.81  4945.2  488.37  4965.3  488.23  4979.2  487.25
  4993.3  486.47  4998.3  486.47  5005.4  485.93  5011.8  485.79  5022.7  485.79
  5023.2  484.99  5028.2  484.99  5028.7  485.79  5043.5  487.25  5056.0  488.27
  5074.3  488.13  5079.3  488.69  5086.4  488.85  5106.6  489.08  5126.9  489.69
  5136.7  489.42  5147.1  489.71  5167.4  490.64  5177.5  490.88  5197.6  490.90
#Mann=3,-1,0
  4791.9    0.05       0  5022.7    0.03       0  5028.7    0.05       0
Bank Sta=4979.2,5043.5
Exp/Cntr=0.3,0.1

Type RM Length L Ch R = 1,3255,31,31,31
BEGIN DESCRIPTION:
Mapping XS 54cdd730
END DESCRIPTION:
XS GIS Cut Line= 5
      2785187.91      7029809.73      2785248.69      7029632.82
      2785258.45      7029574.23      2785242.18      7029521.06
      2785206.35      7029450.49
#Sta/Elev= 30
  4766.7  490.38  4782.3  490.30  4801.0  490.44  4814.0  490.23  4837.6  490.19
  4845.7  489.87  4863.5  488.85  4900.1  487.94  4909.2  487.82  4919.7  487.42
  4921.4  487.24  4931.3  486.18  4959.2  485.94  5007.2  485.77  5007.7  484.97
  5012.7  484.97  5013.2  485.77  5054.2  485.78  5064.1  486.37  5068.8  486.37
  5071.8  486.99  5077.4  486.76  5092.2  487.24  5099.6  487.43  5109.2  488.41
  5116.3  488.92  5131.6  489.18  5138.5  489.13  5143.9  489.65  5147.9  489.65
#Mann=3,-1,0
  4766.7    0.05       0  5007.2    0.03       0  5013.2    0.05       0
Bank Sta=4921.4,5092.2
Exp/Cntr=0.3,0.1

Type RM Length L Ch R = 1,3224,21,21,21
BEGIN DESCRIPTION:
Mapping XS c5f25419
END DESCRIPTION:
XS GIS Cut Line= 5
      2785199.88      7029812.90      2785264.96      7029662.12
      2785288.84      7029612.20      2785277.99      7029542.76
      2785229.58      7029423.35
#Sta/Elev= 30
  4761.7  490.32  4803.0  490.36  4824.8  489.62  4834.0  489.64  4839.4  489.19
  4886.4  487.91  4896.1  486.93  4906.9  485.86  4907.4  485.06  4912.4  485.06
  4912.9  485.86  4921.6  487.84  4932.9  487.71  4938.5  486.84  4961.2  487.24
  4998.7  486.00  5008.8  486.06  5018.9  486.65  5029.0  486.47  5036.3  486.78
  5041.4  486.14  5051.6  486.10  5057.0  486.93  5069.1  487.81  5098.6  487.92
  5104.0  487.59  5122.7  488.63  5146.2  488.99  5152.1  489.67  5180.4  490.21
#Mann=3,-1,0
  4761.7    0.05       0  4906.9    0.03       0  4912.9    0.05       0
Bank Sta=4896.1,5057
Exp/Cntr=0.3,0.1

Type RM Length L Ch R = 1,3203,116,116,116
BEGIN DESCRIPTION:
XS3959A
END DESCRIPTION:
XS GIS Cut Line= 3
      2785207.40      7029821.38      2785314.54      7029630.92
      2785280.80      7029474.14
#Sta/Elev= 30
  4744.7  490.22  4797.9  490.21  4820.9  489.14  4843.8  488.53  4856.5  487.60
  4866.7  487.28  4888.4  486.81  4894.1  487.29  4901.2  485.55  4910.0  486.27
  4920.7  485.15  4931.7  485.08  4947.1  485.82  4958.6  485.39  4979.5  485.31
  4984.7  484.84  4989.8  485.30  5000.0  484.40  5010.2  484.03  5020.4  484.33
  5025.9  483.48  5026.4  482.68  5031.4  482.68  5031.9  483.48  5033.4  485.15
  5034.1  485.97  5040.9  485.50  5051.1  485.43  5092.0  487.74  5123.6  488.51
#Mann=3,-1,0
  4744.7    0.05       0  5025.9    0.03       0  5031.9    0.05       0
Bank Sta=4920.7,5033.4
Exp/Cntr=0.3,0.1

Type RM Length L Ch R = 1,3087,116,116,116
BEGIN DESCRIPTION:
UNT 166 in LFCCL Watershed 8.0
END DESCRIPTION:
XS GIS Cut Line= 3
      2785225.01      7029874.99      2785425.00      7029625.00
      2785376.20      7029409.39
#Sta/Elev= 30
  4661.3  490.32  4738.9  489.69  4767.7  489.96  4796.5  489.03  4803.0  489.18
  4825.4  488.15  4853.4  487.46  4889.4  486.04  4917.4  485.59  4939.0  483.25
  4945.4  482.98  4953.4  481.97  4959.8  481.61  4967.0  480.81  4974.2  480.61
  4978.2  479.58  5000.5  479.29  5002.6  479.04  5003.1  478.24  5008.1  478.24
  5008.6  479.04  5012.2  479.49  5022.4  479.88  5030.4  480.81  5048.7  482.44
  5053.9  483.58  5063.5  485.04  5084.0  486.13  5188.5  488.62  5202.5  487.84
#Mann=3,-1,0
  4661.3    0.05       0  5002.6    0.03       0  5008.6    0.05       0
Bank Sta=4967,5030.4
Exp/Cntr=0.3,0.1

Type RM Length L Ch R = 1,2971,134,134,134
BEGIN DESCRIPTION:
XS3960A
END DESCRIPTION:
XS GIS Cut Line= 3
      2785431.59      7029851.19      2785530.81      7029607.12
      2785528.82      7029442.40
#Sta/Elev= 30
  4723.0  488.25  4729.7  487.76  4740.2  487.67  4769.7  486.46  4793.8  485.92
  4805.2  485.46  4828.6  484.92  4847.3  484.97  4852.7  484.64  4870.0  484.46
  4900.8  483.50  4935.7  482.84  4945.6  482.35  4959.8  482.00  4978.0  480.60
  4982.5  479.91  4986.5  479.47  4998.6  479.13  5005.6  478.15  5006.1  477.35
  5011.1  477.35  5011.6  478.15  5022.9  479.91  5038.6  482.74  5048.4  483.72
  5053.4  483.72  5058.6  484.29  5078.6  485.07  5108.6  485.78  5151.2  486.20
#Mann=3,-1,0
  4723.0    0.05       0  5005.6    0.03       0  5011.6    0.05       0
Bank Sta=4982.5,5022.9
Exp/Cntr=0.3,0.1

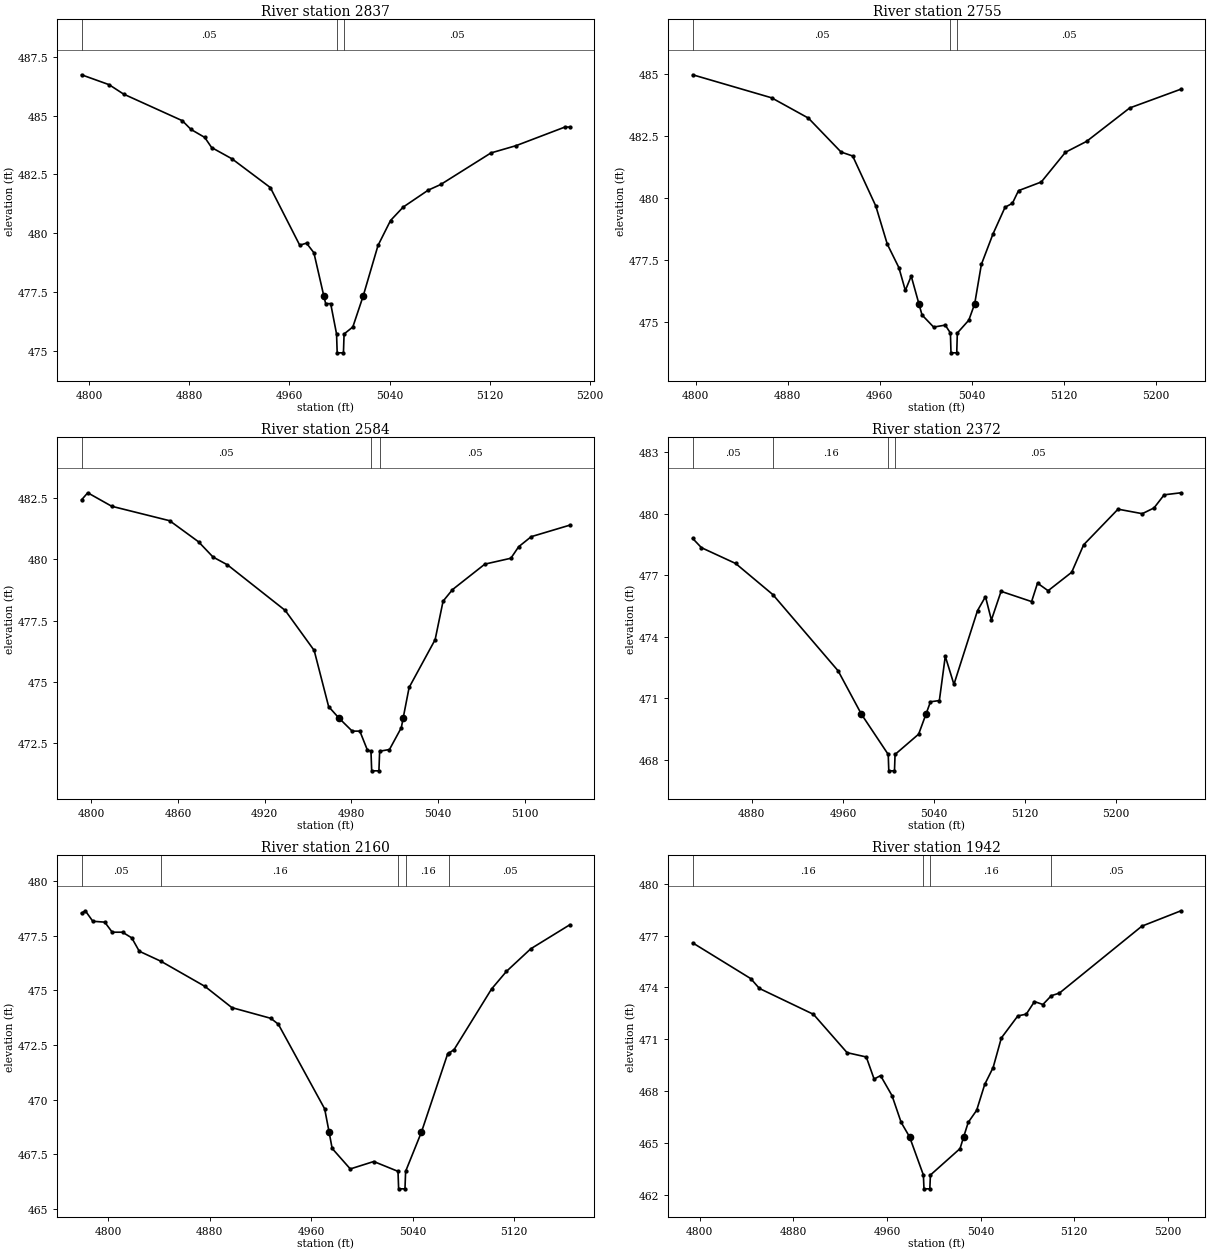
Type RM Length L Ch R = 1,2837,82,82,82
BEGIN DESCRIPTION:
XS3961A
END DESCRIPTION:
XS GIS Cut Line= 3
      2785568.51      7029845.20      2785647.87      7029662.67
      2785633.98      7029472.21
#Sta/Elev= 30
  4793.9  486.73  4815.9  486.31  4827.5  485.91  4874.4  484.78  4881.3  484.41
  4892.3  484.07  4897.8  483.64  4914.1  483.16  4944.7  481.94  4968.2  479.49
  4973.6  479.58  4979.5  479.17  4987.4  477.34  4988.9  477.01  4992.9  477.01
  4997.6  475.72  4998.1  474.92  5003.1  474.92  5003.6  475.72  5010.6  476.02
  5018.9  477.34  5030.7  479.48  5040.7  480.54  5050.8  481.11  5070.8  481.83
  5080.8  482.07  5120.9  483.41  5141.0  483.72  5180.0  484.51  5183.9  484.51
#Mann=3,-1,0
  4793.9    0.05       0  4997.6    0.03       0  5003.6    0.05       0
Bank Sta=4987.4,5018.9
Exp/Cntr=0.3,0.1

Type RM Length L Ch R = 1,2755,171,171,171
BEGIN DESCRIPTION:
UNT 166 in LFCCL Watershed 7.0
END DESCRIPTION:
XS GIS Cut Line= 3
      2785751.04      7029853.16      2785725.00      7029625.00
      2785665.96      7029439.19
#Sta/Elev= 30
  4797.3  484.97  4865.9  484.04  4897.9  483.22  4926.3  481.85  4936.4  481.69
  4956.5  479.67  4966.5  478.13  4976.6  477.18  4982.2  476.26  4987.3  476.84
  4994.0  475.72  4996.7  475.27  5006.8  474.78  5016.9  474.86  5021.4  474.54
  5021.9  473.74  5026.9  473.74  5027.4  474.54  5037.4  475.06  5042.5  475.72
  5048.3  477.31  5058.4  478.54  5068.9  479.62  5075.3  479.78  5080.6  480.29
  5100.4  480.64  5121.4  481.84  5139.8  482.28  5177.3  483.63  5221.9  484.39
#Mann=3,-1,0
  4797.3    0.05       0  5021.4    0.03       0  5027.4    0.05       0
Bank Sta=4994,5042.5
Exp/Cntr=0.3,0.1

Type RM Length L Ch R = 1,2584,212,212,212
BEGIN DESCRIPTION:
XS3962A
END DESCRIPTION:
XS GIS Cut Line= 3
      2785870.09      7029755.94      2785864.13      7029567.43
      2785804.60      7029430.51
#Sta/Elev= 30
  4793.2  482.43  4797.5  482.72  4814.1  482.17  4854.2  481.58  4874.2  480.72
  4884.2  480.10  4894.2  479.78  4934.2  477.92  4954.2  476.29  4964.2  474.00
  4971.2  473.54  4980.5  473.00  4985.8  473.00  4991.0  472.23  4993.5  472.18
  4994.0  471.38  4999.0  471.38  4999.5  472.18  5006.3  472.25  5014.5  473.14
  5015.8  473.54  5019.9  474.78  5037.9  476.73  5043.4  478.30  5049.9  478.77
  5072.3  479.81  5090.3  480.05  5095.7  480.52  5104.4  480.93  5131.1  481.40
#Mann=3,-1,0
  4793.2    0.05       0  4993.5    0.03       0  4999.5    0.05       0
Bank Sta=4971.2,5015.8
Exp/Cntr=0.3,0.1

Type RM Length L Ch R = 1,2372,212,212,212
BEGIN DESCRIPTION:
UNT 166 in LFCCL Watershed 6.0
END DESCRIPTION:
XS GIS Cut Line= 3
      2786046.67      7029662.65      2786040.72      7029486.09
      2785977.24      7029242.07
#Sta/Elev= 30
  4828.1  478.80  4835.8  478.35  4865.8  477.58  4898.5  476.06  4955.8  472.34
  4976.3  470.22  4999.8  468.26  5000.3  467.46  5005.3  467.46  5005.8  468.26
  5026.5  469.25  5032.9  470.22  5036.9  470.83  5044.7  470.89  5049.9  473.05
  5057.5  471.68  5078.2  475.28  5085.2  475.96  5090.4  474.82  5098.9  476.22
  5125.7  475.72  5130.9  476.62  5140.2  476.25  5160.9  477.15  5171.4  478.49
  5201.6  480.23  5222.9  480.01  5233.2  480.29  5242.1  480.93  5256.9  481.03
#Mann=4,-1,0
  4828.1    0.05       0  4898.5    0.16       0  4999.8    0.07       0
  5005.8    0.05       0
Bank Sta=4976.3,5032.9
Exp/Cntr=0.3,0.1

Type RM Length L Ch R = 1,2160,218,218,218
BEGIN DESCRIPTION:
XS3963A
END DESCRIPTION:
XS GIS Cut Line= 3
      2786098.27      7029702.34      2786211.35      7029521.80
      2786253.01      7029355.16
#Sta/Elev= 30
  4779.1  478.53  4782.1  478.64  4788.0  478.16  4797.4  478.12  4803.3  477.66
  4811.4  477.66  4818.7  477.40  4824.6  476.79  4841.7  476.33  4876.4  475.18
  4897.6  474.21  4928.3  473.72  4934.2  473.45  4970.7  469.58  4974.2  468.52
  4976.6  467.77  4990.9  466.83  5009.4  467.17  5028.5  466.72  5029.0  465.92
  5034.0  465.92  5034.5  466.72  5047.0  468.52  5067.6  472.09  5068.9  472.14
  5072.7  472.29  5102.2  475.06  5114.0  475.87  5133.1  476.90  5163.9  478.00
#Mann=5,-1,0
  4779.1    0.05       0  4841.7    0.16       0  5028.5    0.07       0
  5034.5    0.16       0  5068.9    0.05       0
Bank Sta=4974.2,5047
Exp/Cntr=0.3,0.1

Type RM Length L Ch R = 1,1942,200,200,200
BEGIN DESCRIPTION:
XS3964A
END DESCRIPTION:
XS GIS Cut Line= 3
      2786149.83      7029714.26      2786334.37      7029630.92
      2786489.14      7029482.10
#Sta/Elev= 30
  4794.0  476.58  4843.6  474.51  4851.0  473.94  4897.2  472.44  4925.9  470.22
  4942.3  469.97  4949.0  468.69  4954.5  468.89  4964.3  467.73  4972.1  466.18
  4979.3  465.34  4991.1  463.13  4991.6  462.33  4996.6  462.33  4997.1  463.13
  5022.4  464.66  5025.5  465.34  5029.4  466.18  5036.6  466.88  5043.5  468.38
  5050.7  469.36  5057.7  471.07  5071.8  472.35  5079.0  472.45  5086.0  473.18
  5093.2  473.01  5100.4  473.52  5107.3  473.67  5177.8  477.55  5211.2  478.44
#Mann=4,-1,0
  4794.0    0.16       0  4991.1    0.07       0  4997.1    0.16       0
  5100.4    0.05       0
Bank Sta=4979.3,5025.5
Exp/Cntr=0.3,0.1

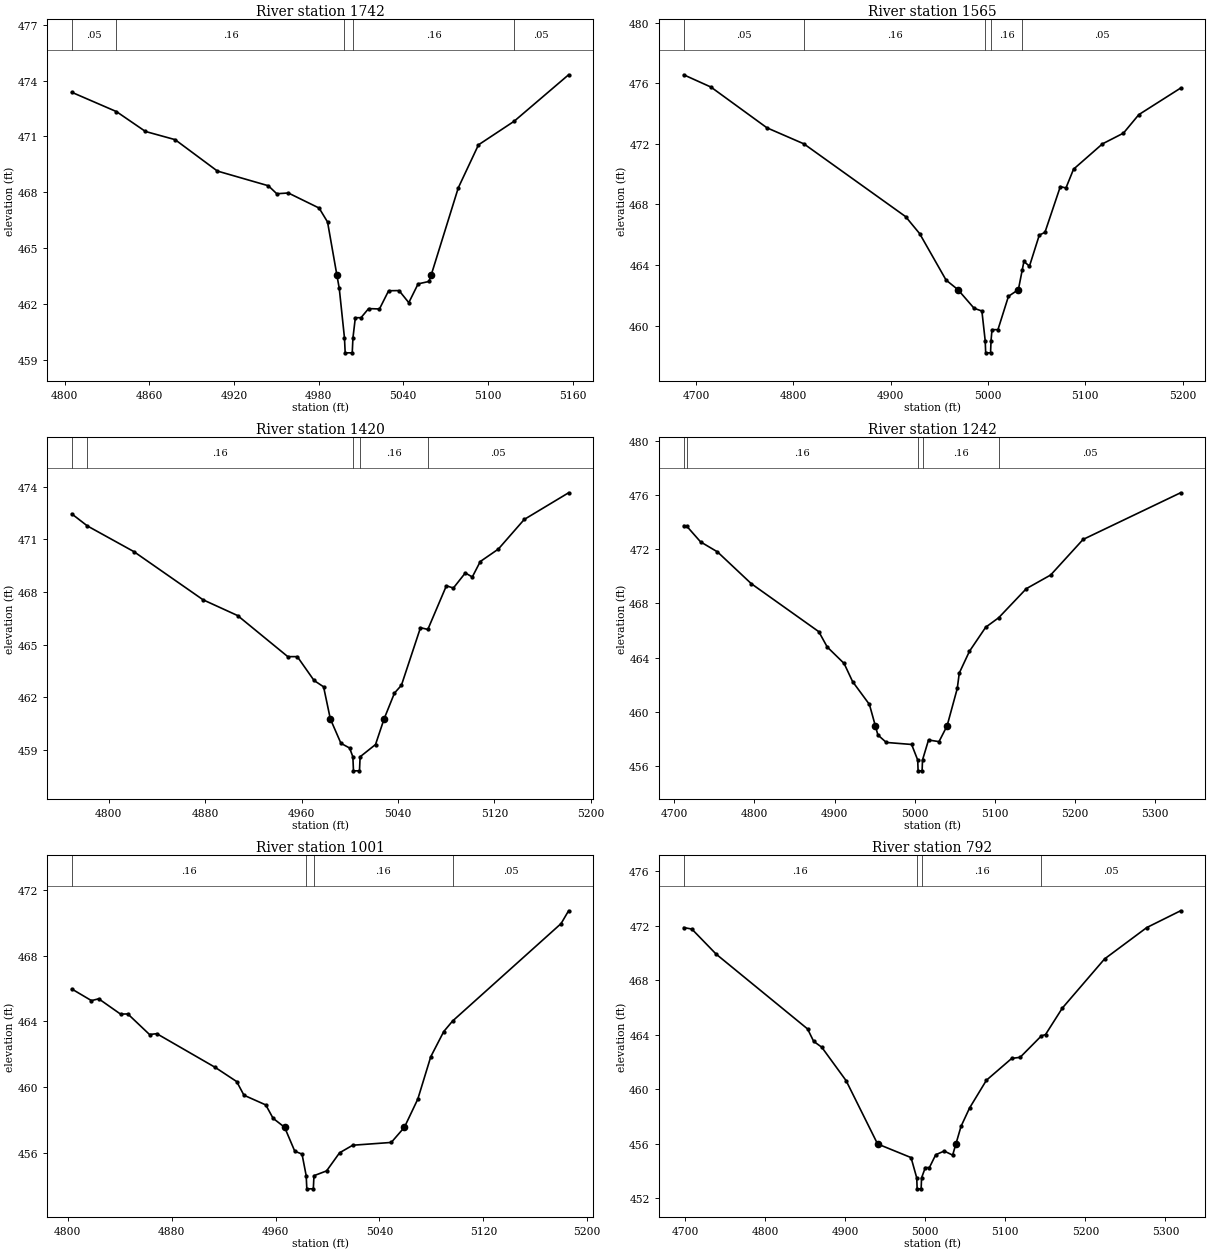
Type RM Length L Ch R = 1,1742,177,177,177
BEGIN DESCRIPTION:
XS3965A
END DESCRIPTION:
XS GIS Cut Line= 3
      2786330.39      7029912.67      2786444.40      7029742.17
      2786556.55      7029646.83
#Sta/Elev= 30
  4804.9  473.38  4836.6  472.34  4857.2  471.27  4878.2  470.83  4908.2  469.14
  4944.3  468.35  4950.3  467.92  4958.5  467.96  4980.3  467.15  4986.3  466.40
  4992.9  463.55  4994.6  462.83  4998.3  460.16  4998.8  459.36  5003.8  459.36
  5004.3  460.16  5006.0  461.25  5010.0  461.25  5015.4  461.74  5023.1  461.72
  5029.6  462.70  5037.0  462.71  5043.9  462.06  5050.5  463.07  5058.2  463.20
  5059.8  463.55  5079.0  468.24  5093.3  470.55  5118.6  471.82  5157.2  474.32
#Mann=5,-1,0
  4804.9    0.05       0  4836.6    0.16       0  4998.3    0.07       0
  5004.3    0.16       0  5118.6    0.05       0
Bank Sta=4992.9,5059.8
Exp/Cntr=0.3,0.1

Type RM Length L Ch R = 1,1565,145,145,145
BEGIN DESCRIPTION:
UNT 166 in LFCCL Watershed 4.0
END DESCRIPTION:
XS GIS Cut Line= 3
      2786325.03      7030024.98      2786575.00      7029825.00
      2786669.29      7029659.38
#Sta/Elev= 30
  4687.2  476.56  4715.2  475.75  4772.8  473.06  4810.8  472.00  4915.3  467.20
  4929.7  466.08  4956.9  463.01  4969.1  462.38  4985.7  461.15  4993.7  460.97
  4997.1  459.01  4997.6  458.21  5002.6  458.21  5003.1  459.01  5004.1  459.74
  5010.2  459.74  5021.0  461.94  5031.2  462.38  5035.2  463.69  5036.9  464.24
  5042.6  463.93  5052.7  465.98  5058.5  466.16  5074.3  469.18  5080.1  469.09
  5087.9  470.33  5117.6  472.00  5139.2  472.71  5155.0  473.93  5197.9  475.68
#Mann=5,-1,0
  4687.2    0.05       0  4810.8    0.16       0  4997.1    0.07       0
  5003.1    0.16       0  5035.2    0.05       0
Bank Sta=4969.1,5031.2
Exp/Cntr=0.3,0.1

Type RM Length L Ch R = 1,1420,178,178,178
BEGIN DESCRIPTION:
XS3970A
END DESCRIPTION:
XS GIS Cut Line= 3
      2786507.83      7030070.78      2786666.69      7029940.56
      2786770.45      7029761.58
#Sta/Elev= 30
  4769.3  472.46  4782.3  471.77  4820.8  470.31  4878.3  467.56  4907.0  466.66
  4948.6  464.32  4956.5  464.32  4970.4  462.96  4978.3  462.60  4983.9  460.77
  4992.7  459.38  4999.9  459.11  5002.6  458.61  5003.1  457.81  5008.1  457.81
  5008.6  458.61  5021.4  459.31  5028.5  460.77  5037.1  462.24  5042.9  462.69
  5058.7  465.97  5064.8  465.87  5080.2  468.36  5086.0  468.23  5095.9  469.09
  5101.7  468.86  5108.3  469.74  5123.3  470.45  5144.8  472.14  5181.6  473.66
#Mann=5,-1,0
  4769.3    0.05       0  4782.3    0.16       0  5002.6    0.07       0
  5008.6    0.16       0  5064.8    0.05       0
Bank Sta=4983.9,5028.5
Exp/Cntr=0.3,0.1

Type RM Length L Ch R = 1,1242,241,241,241
BEGIN DESCRIPTION:
UNT 166 in LFCCL Watershed 3.0
END DESCRIPTION:
XS GIS Cut Line= 3
      2786524.96      7030125.01      2786825.00      7030025.00
      2786875.00      7029725.00
#Sta/Elev= 30
  4711.6  473.75  4715.3  473.72  4732.7  472.55  4753.8  471.81  4796.0  469.46
  4880.3  465.91  4890.8  464.78  4911.9  463.56  4922.5  462.22  4943.5  460.53
  4950.9  458.95  4954.1  458.27  4964.6  457.72  4996.2  457.57  5003.8  456.42
  5004.3  455.62  5009.3  455.62  5009.8  456.42  5017.3  457.90  5030.4  457.78
  5040.5  458.95  5053.2  461.71  5055.7  462.85  5068.4  464.46  5088.7  466.24
  5104.9  466.94  5139.4  469.09  5169.8  470.10  5210.3  472.73  5332.0  476.18
#Mann=5,-1,0
  4711.6    0.05       0  4715.3    0.16       0  5003.8    0.07       0
  5009.8    0.16       0  5104.9    0.05       0
Bank Sta=4950.9,5040.5
Exp/Cntr=0.3,0.1

Type RM Length L Ch R = 1,1001,209,209,209
BEGIN DESCRIPTION:
XS3968A
END DESCRIPTION:
XS GIS Cut Line= 3
      2786862.15      7030301.53      2786945.47      7030134.89
      2786959.31      7029939.19
#Sta/Elev= 30
  4803.1  465.97  4818.3  465.26  4823.9  465.37  4840.7  464.44  4846.3  464.45
  4863.0  463.20  4868.6  463.25  4913.4  461.21  4930.1  460.34  4935.7  459.51
  4952.5  458.92  4958.1  458.11  4967.0  457.56  4974.8  456.11  4980.4  455.93
  4983.6  454.62  4984.1  453.82  4989.1  453.82  4989.6  454.62  4999.3  454.91
  5009.3  456.01  5019.4  456.47  5049.1  456.64  5059.2  457.56  5069.5  459.27
  5079.5  461.85  5089.5  463.38  5096.3  464.02  5179.8  469.94  5185.6  470.72
#Mann=4,-1,0
  4803.1    0.16       0  4983.6    0.07       0  4989.6    0.16       0
  5096.3    0.05       0
Bank Sta=4967,5059.2
Exp/Cntr=0.3,0.1

Type RM Length L Ch R = 1,792,125,125,125
BEGIN DESCRIPTION:
UNT 166 in LFCCL Watershed 2.0
END DESCRIPTION:
XS GIS Cut Line= 3
      2787024.99      7030475.05      2787075.00      7030175.00
      2786975.00      7029875.01
#Sta/Elev= 30
  4698.5  471.85  4708.7  471.74  4739.1  469.90  4853.2  464.42  4860.8  463.51
  4870.9  463.08  4901.3  460.63  4940.6  455.99  4982.4  454.99  4989.5  453.50
  4990.0  452.70  4995.0  452.70  4995.5  453.50  5000.2  454.26  5005.3  454.26
  5013.2  455.20  5023.8  455.47  5034.3  455.17  5038.4  455.99  5044.8  457.28
  5055.4  458.62  5076.5  460.66  5108.1  462.26  5118.6  462.34  5145.1  463.91
  5150.3  464.01  5171.3  465.95  5224.0  469.55  5276.7  471.85  5318.9  473.08
#Mann=4,-1,0
  4698.5    0.16       0  4989.5    0.07       0  4995.5    0.16       0
  5145.1    0.05       0
Bank Sta=4940.6,5038.4
Exp/Cntr=0.3,0.1

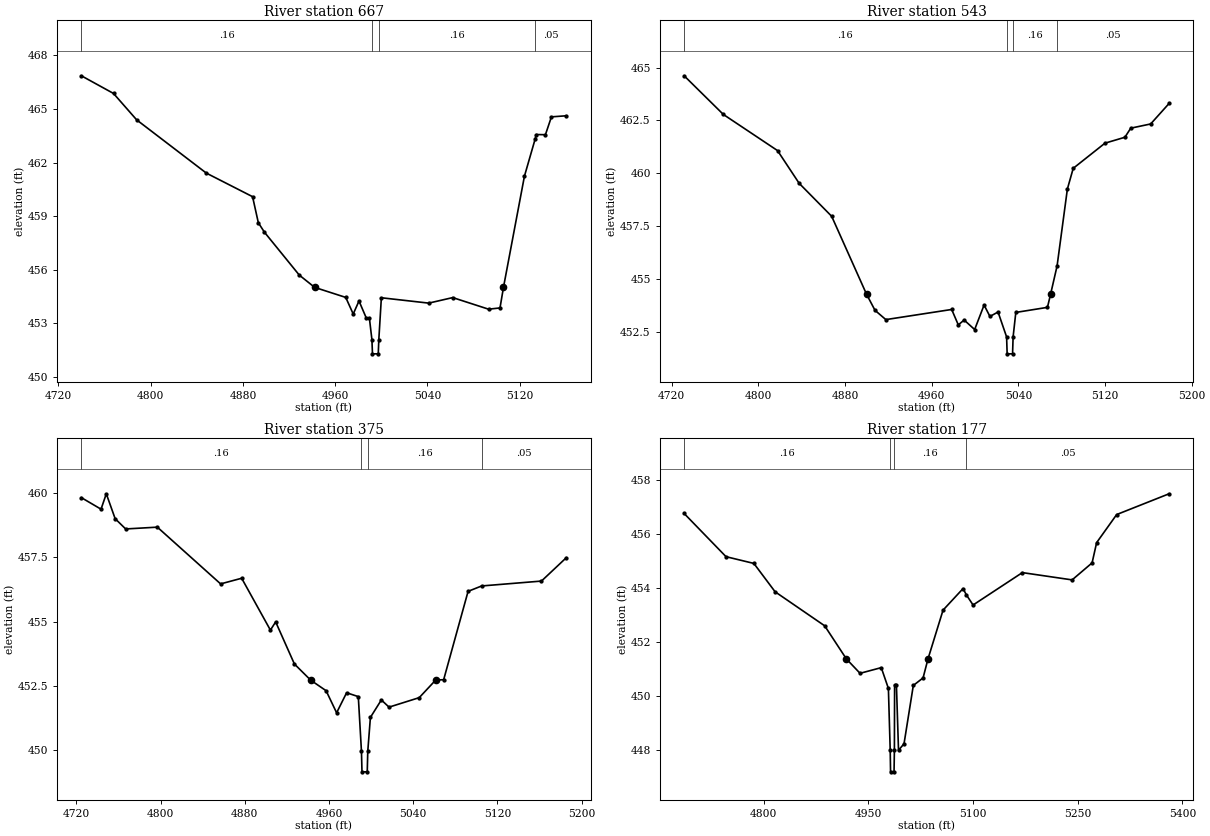
Type RM Length L Ch R = 1,667,124,124,124
BEGIN DESCRIPTION:
XS3969A
END DESCRIPTION:
XS GIS Cut Line= 3
      2787161.74      7030412.65      2787191.50      7030164.65
      2787145.88      7030000.04
#Sta/Elev= 30
  4739.9  466.86  4767.8  465.87  4787.9  464.39  4848.3  461.41  4888.4  460.09
  4893.4  458.63  4898.7  458.10  4928.9  455.70  4942.3  455.01  4969.2  454.45
  4975.7  453.52  4980.7  454.25  4987.0  453.30  4989.7  453.30  4991.9  452.09
  4992.4  451.29  4997.4  451.29  4997.9  452.09  5000.1  454.43  5041.2  454.13
  5062.0  454.44  5093.1  453.79  5103.0  453.86  5106.0  455.01  5124.2  461.24
  5133.4  463.30  5134.6  463.57  5142.4  463.56  5147.6  464.56  5160.5  464.62
#Mann=4,-1,0
  4739.9    0.16       0  4991.9    0.07       0  4997.9    0.16       0
  5133.4    0.05       0
Bank Sta=4942.3,5106
Exp/Cntr=0.3,0.1

Type RM Length L Ch R = 1,543,168,168,168
BEGIN DESCRIPTION:
XS3967A
END DESCRIPTION:
XS GIS Cut Line= 3
      2787294.67      7030351.17      2787294.67      7030109.09
      2787215.58      7029919.29
#Sta/Elev= 30
  4731.4  464.61  4767.6  462.78  4817.6  461.07  4837.6  459.52  4867.6  457.96
  4899.8  454.27  4907.6  453.51  4917.6  453.07  4978.4  453.55  4984.5  452.82
  4989.9  453.05  4999.6  452.60  5008.3  453.76  5013.7  453.22  5021.2  453.43
  5029.1  452.25  5029.6  451.45  5034.6  451.45  5035.1  452.25  5037.6  453.41
  5066.8  453.65  5069.7  454.27  5075.7  455.61  5085.2  459.25  5090.6  460.23
  5119.9  461.42  5138.3  461.70  5143.7  462.13  5162.1  462.33  5179.1  463.30
#Mann=4,-1,0
  4731.4    0.16       0  5029.1    0.07       0  5035.1    0.16       0
  5075.7    0.05       0
Bank Sta=4899.8,5069.7
Exp/Cntr=0.3,0.1

Type RM Length L Ch R = 1,375,198,198,198
BEGIN DESCRIPTION:
XS3966A
END DESCRIPTION:
XS GIS Cut Line= 3
      2787471.25      7030367.03      2787455.38      7030111.08
      2787372.06      7029924.59
#Sta/Elev= 30
  4724.8  459.83  4743.5  459.38  4748.5  459.98  4756.9  459.01  4766.9  458.61
  4797.0  458.68  4857.1  456.47  4877.1  456.69  4904.4  454.67  4909.4  454.99
  4927.2  453.35  4942.7  452.72  4957.3  452.31  4967.3  451.45  4976.8  452.23
  4987.9  452.08  4990.9  449.95  4991.4  449.15  4996.4  449.15  4996.9  449.95
  4999.4  451.27  5009.8  451.95  5017.1  451.67  5045.8  452.04  5061.3  452.72
  5069.0  452.74  5092.2  456.18  5105.1  456.39  5161.9  456.58  5185.5  457.49
#Mann=4,-1,0
  4724.8    0.16       0  4990.9    0.07       0  4996.9    0.16       0
  5105.1    0.05       0
Bank Sta=4942.7,5061.3
Exp/Cntr=0.3,0.1

Type RM Length L Ch R = 1,177,0,0,0
BEGIN DESCRIPTION:
UNT 166 in LFCCL Watershed 1.0
END DESCRIPTION:
XS GIS Cut Line= 3
      2787590.87      7030353.57      2787640.87      7030053.57
      2787390.84      7029753.53
#Sta/Elev= 30
  4686.3  456.76  4746.3  455.16  4786.2  454.91  4816.6  453.86  4887.6  452.60
  4918.8  451.37  4938.3  450.84  4968.7  451.05  4978.9  450.28  4981.5  447.99
  4982.0  447.19  4987.0  447.19  4987.5  447.99  4987.8  450.41  4990.4  450.41
  4993.4  447.99  5001.3  448.23  5014.6  450.39  5028.6  450.67  5035.6  451.37
  5057.2  453.18  5085.9  453.98  5090.5  453.75  5100.2  453.37  5170.8  454.57
  5242.1  454.30  5270.7  454.93  5277.2  455.68  5305.9  456.72  5381.0  457.49
#Mann=4,-1,0
  4686.3    0.16       0  4981.5    0.07       0  4987.5    0.16       0
  5090.5    0.05       0
Bank Sta=4918.8,5035.6
Exp/Cntr=0.3,0.1

Chan Stop Cuts=-1