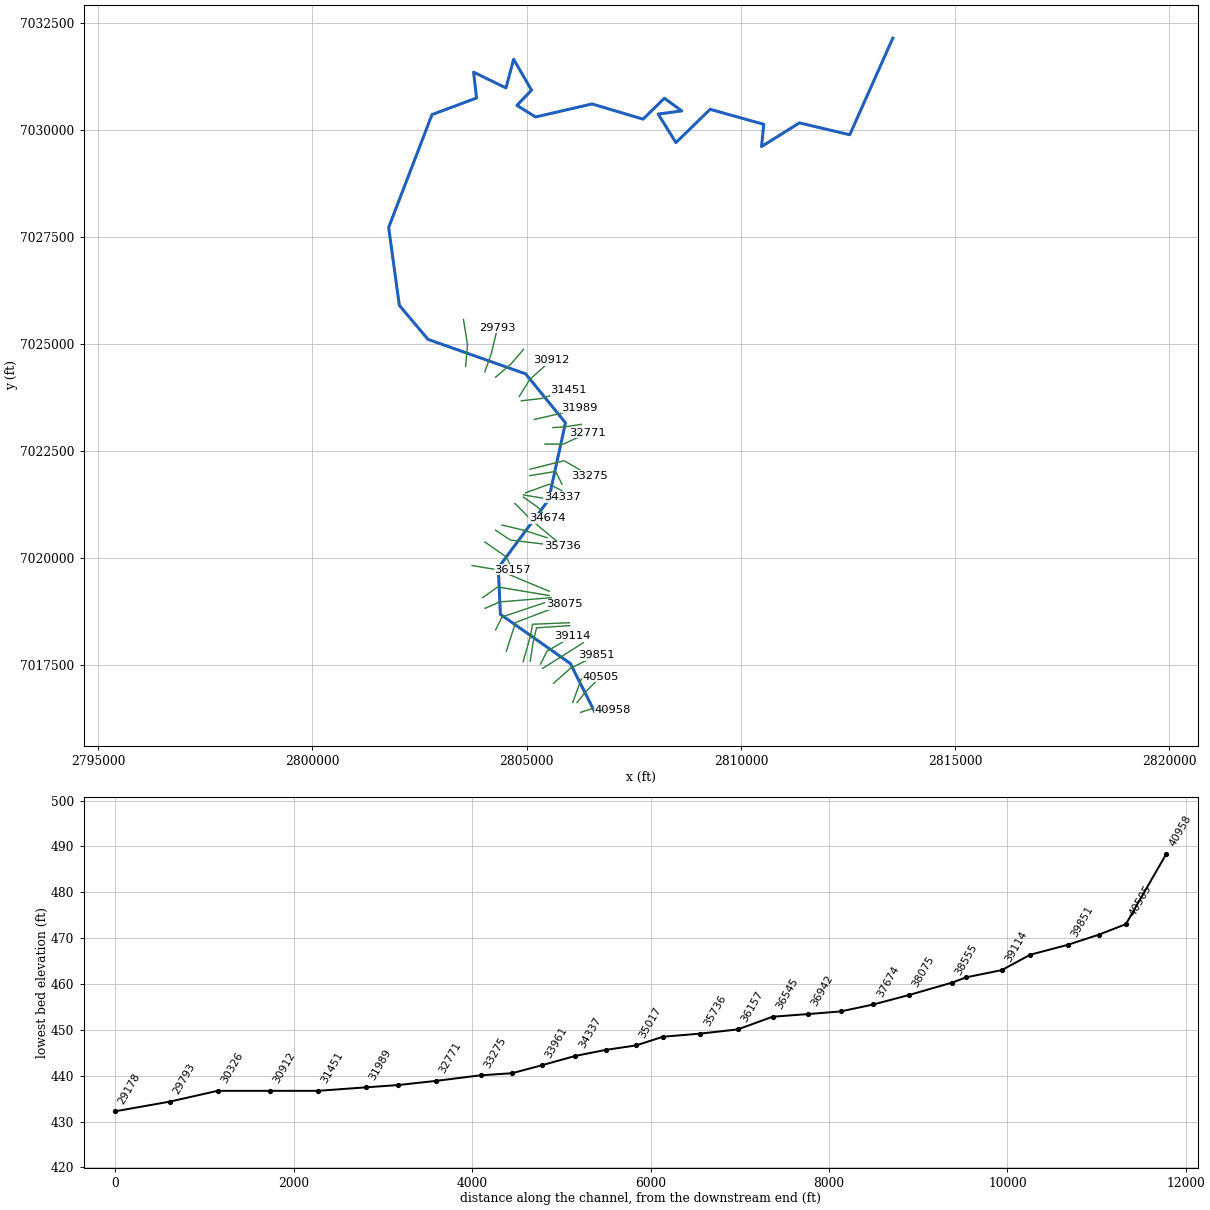
--- UNT 167 in LFCCL Watershed.prj (project) ---

Proj Title=UNT 167 in LFCCL Watershed Base Level Engineering
Current Plan=p01
Default Exp/Contr=0.3,0.1
English Units
Geom File=g01
Flow File=f01
Plan File=p01
Y Axis Title=Elevation
X Axis Title(PF)=Main Channel Distance
X Axis Title(XS)=Station
BEGIN DESCRIPTION:
UNT 167 in LFCCL Watershed
END DESCRIPTION:
DSS Export Rating Curves= 0
DSS Export Rating Curve Sorted= 0
DSS Export Volume Flow Curves= 0
DXF OffsetX= 0
DXF OffsetY= 0
DXF ScaleX= 1
DXF ScaleY= 10

--- UNT 167 in LFCCL Watershed.p01 (plan) ---

Plan Title=Multiple Run
Short Identifier=Multiple
Geom File=g01
Flow File=f01
Subcritical Flow
K Sum by GR= 0
Std Step Tol= 0.01
Critical Tol= 0.01
Num of Std Step Trials= 20
Max Error Tol= 0.3
Flow Tol Ratio= 0.001
Split Flow NTrial= 30
Split Flow Tol= 0.02
Split Flow Ratio= 0.02
Log Output Level= 0
Friction Slope Method= 1
Unsteady Friction Slope Method= 2
Unsteady Bridges Friction Slope Method= 1
Parabolic Critical Depth
Global Vel Dist=  1 , 1 , 1
Global Log Level= 0
CheckData=True
Encroach Param= -1, 0, 0, 0
BEGIN DESCRIPTION:
Multiple Run
END DESCRIPTION:

--- UNT 167 in LFCCL Watershed.f01 (steady flow) ---

Flow Title=Multiple
Program Version=5.07
Number of Profiles= 7
Profile Names=10-year,25-year,50-year,1pct_min,100-year,1pct_plu,500-year
River Rch & RM=UNT 167 in LFCCL,Reach-1         ,40958
     483     637     760     451     900    1795    1262
River Rch & RM=UNT 167 in LFCCL,Reach-1         ,32350
     603     801     961     573    1143    2280    1618
River Rch & RM=UNT 167 in LFCCL,Reach-1         ,28136
    1037    1419    1735    1051    2098    4186    3075
Boundary for River Rch & Prof#=UNT 167 in LFCCL,Reach-1         , 1
Up Type= 0
Dn Type= 3
Dn Slope=0.005
Boundary for River Rch & Prof#=UNT 167 in LFCCL,Reach-1         , 2
Up Type= 0
Dn Type= 3
Dn Slope=0.005
Boundary for River Rch & Prof#=UNT 167 in LFCCL,Reach-1         , 3
Up Type= 0
Dn Type= 3
Dn Slope=0.005
Boundary for River Rch & Prof#=UNT 167 in LFCCL,Reach-1         , 4
Up Type= 0
Dn Type= 3
Dn Slope=0.005
Boundary for River Rch & Prof#=UNT 167 in LFCCL,Reach-1         , 5
Up Type= 0
Dn Type= 3
Dn Slope=0.005
Boundary for River Rch & Prof#=UNT 167 in LFCCL,Reach-1         , 6
Up Type= 0
Dn Type= 3
Dn Slope=0.005
Boundary for River Rch & Prof#=UNT 167 in LFCCL,Reach-1         , 7
Up Type= 0
Dn Type= 3
Dn Slope=0.005
DSS Import GetInterval= 0
DSS Import GetPeak= 0
DSS Import FillOption= 0

--- UNT 167 in LFCCL Watershed.g01 (geometry) ---

Geom Title=Existing Conditions

River Reach=UNT 167 in LFCCL,Reach-1
Reach XY= 30
      2806585.93      7016408.27      2806019.01      7017537.68
      2804385.97      7018685.72      2804337.77      7019774.86
      2805512.54      7021361.83      2805905.59      7023160.71
      2804976.96      7024303.75      2802695.68      7025109.91
      2802027.20      7025906.38      2801778.58      7027725.03
      2802790.15      7030360.86      2803830.18      7030749.15
      2803761.45      7031352.78      2804516.27      7030983.96
      2804696.10      7031654.02      2805113.02      7030932.42
      2804771.69      7030576.20      2805208.09      7030305.88
      2806525.30      7030609.42      2807716.52      7030255.49
      2808214.77      7030743.43      2808619.09      7030447.91
      2808069.30      7030373.46      2808483.94      7029706.84
      2809282.28      7030484.57      2810533.96      7030134.09
      2810482.66      7029614.06      2811365.77      7030167.29
      2812540.95      7029890.10      2813544.70      7032143.95

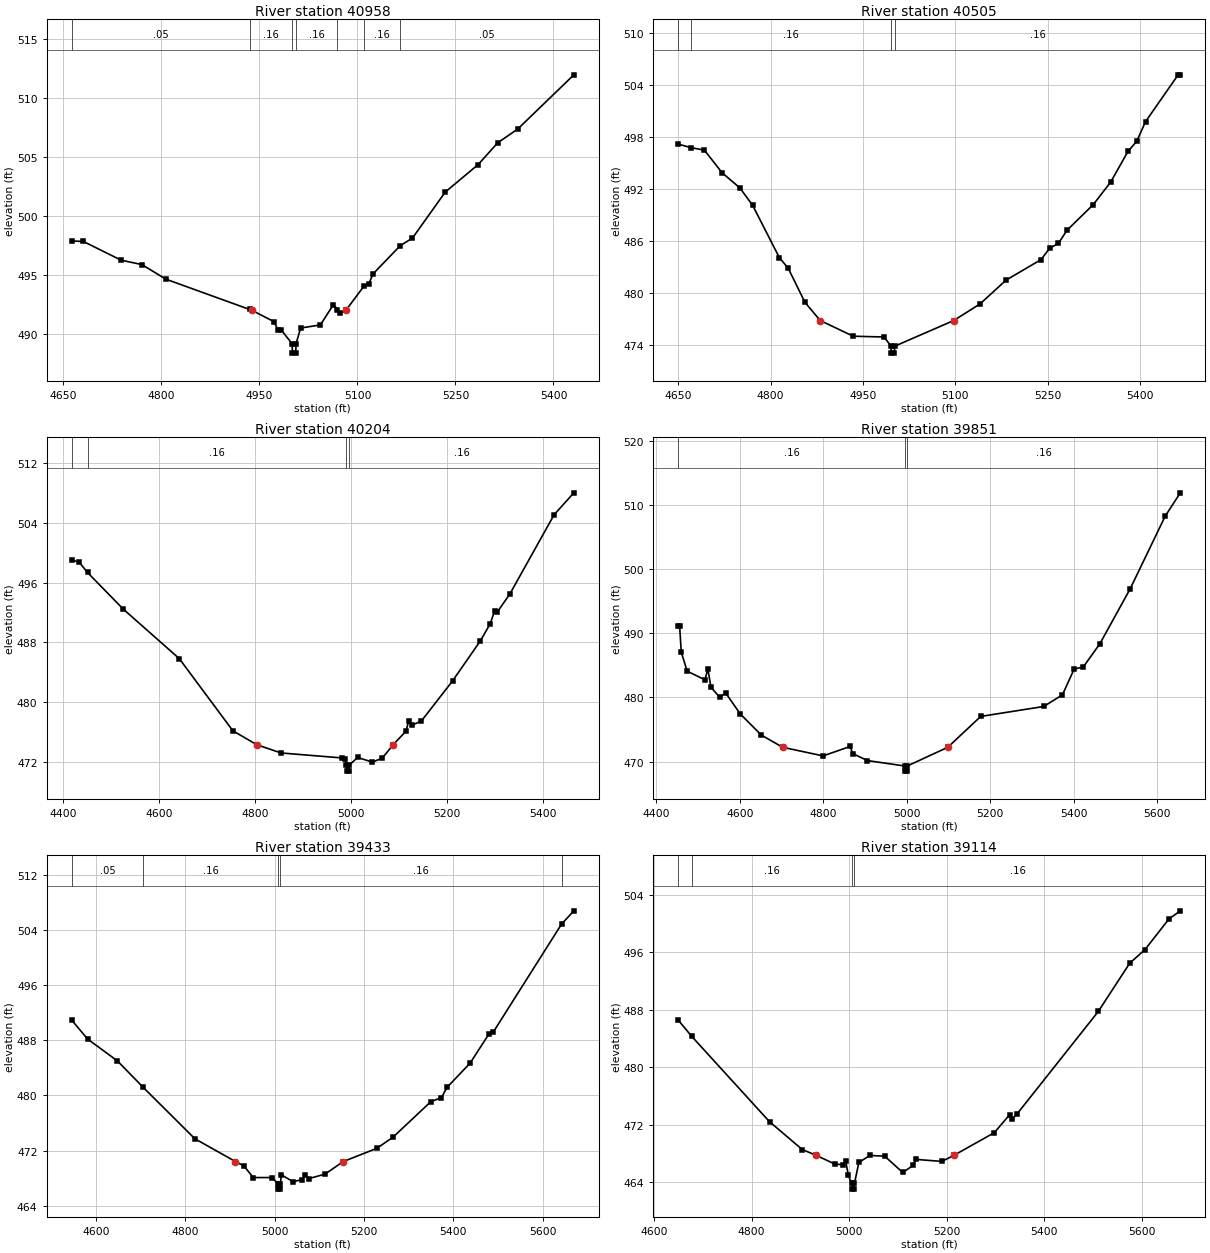
Type RM Length L Ch R = 1,40958,453,453,453
BEGIN DESCRIPTION:
UNT 167 in LFCCL Watershed 61.0
END DESCRIPTION:
XS GIS Cut Line= 3
      2806261.10      7016395.13      2806561.11      7016495.14
      2807010.60      7016445.20
#Sta/Elev= 30
  4662.7  497.90  4680.4  497.86  4738.3  496.27  4770.0  495.90  4806.8  494.66
  4935.1  492.09  4938.4  492.02  4972.5  491.05  4978.4  490.34  4983.4  490.34
  5000.0  489.19  5000.5  488.39  5005.5  488.39  5006.0  489.19  5013.0  490.52
  5043.2  490.78  5063.3  492.51  5069.4  492.08  5073.4  491.80  5082.3  492.02
  5109.9  494.07  5117.4  494.25  5123.7  495.10  5165.6  497.51  5184.1  498.14
  5234.4  502.05  5284.7  504.38  5314.9  506.24  5345.1  507.38  5431.2  511.99
#Mann=7,-1,0
  4662.7    0.05       0  4935.1    0.16       0  5000.0    0.07       0
  5006.0    0.16       0  5069.4    0.05       0  5109.9    0.16       0
  5165.6    0.05       0
Bank Sta=4938.4,5082.3
Exp/Cntr=0.3,0.1

Type RM Length L Ch R = 1,40505,301,301,301
BEGIN DESCRIPTION:
UNT 167 in LFCCL Watershed 60.0
END DESCRIPTION:
XS GIS Cut Line= 3
      2806175.00      7016624.99      2806375.00      7016875.00
      2806724.97      7017224.97
#Sta/Elev= 30
  4650.2  497.16  4671.0  496.75  4692.6  496.47  4721.4  493.86  4750.3  492.11
  4771.1  490.09  4814.3  484.08  4828.7  482.85  4855.9  478.92  4880.7  476.82
  4934.3  475.01  4984.5  474.92  4995.6  473.86  4996.1  473.06  5001.1  473.06
  5001.6  473.86  5097.5  476.82  5140.1  478.73  5182.5  481.48  5239.1  483.84
  5253.2  485.15  5267.3  485.71  5281.5  487.24  5323.9  490.18  5352.2  492.78
  5380.5  496.34  5394.6  497.49  5408.8  499.75  5461.8  505.15  5465.3  505.15
#Mann=4,-1,0
  4650.2    0.05       0  4671.0    0.16       0  4995.6    0.07       0
  5001.6    0.16       0
Bank Sta=4880.7,5097.5
Exp/Cntr=0.3,0.1

Type RM Length L Ch R = 1,40204,353,353,353
BEGIN DESCRIPTION:
UNT 167 in LFCCL Watershed 59.0
END DESCRIPTION:
XS GIS Cut Line= 3
      2806075.00      7016625.00      2806275.00      7017175.00
      2806724.98      7017275.00
#Sta/Elev= 30
  4418.7  499.02  4434.0  498.75  4451.5  497.36  4525.8  492.47  4642.8  485.83
  4754.5  476.17  4804.7  474.30  4855.0  473.21  4982.7  472.54  4988.6  472.38
  4991.0  471.58  4991.5  470.78  4996.5  470.78  4997.0  471.58  5014.2  472.61
  5044.9  471.99  5065.4  472.50  5088.3  474.30  5115.3  476.15  5120.5  477.44
  5126.9  476.91  5147.4  477.50  5212.7  482.90  5270.3  488.23  5290.8  490.52
  5299.7  492.23  5304.9  492.02  5331.7  494.50  5423.9  505.10  5464.9  508.02
#Mann=4,-1,0
  4418.7    0.05       0  4451.5    0.16       0  4991.0    0.07       0
  4997.0    0.16       0
Bank Sta=4804.7,5088.3
Exp/Cntr=0.3,0.1

Type RM Length L Ch R = 1,39851,418,418,418
BEGIN DESCRIPTION:
UNT 167 in LFCCL Watershed 58.0
END DESCRIPTION:
XS GIS Cut Line= 3
      2805624.97      7017074.97      2806025.00      7017425.00
      2806625.03      7017725.01
#Sta/Elev= 30
  4452.7  491.09  4456.1  491.09  4459.9  487.08  4474.1  484.10  4516.8  482.75
  4523.5  484.48  4531.0  481.60  4551.9  480.04  4566.2  480.72  4601.3  477.43
  4651.6  474.15  4702.5  472.25  4799.6  470.90  4864.2  472.37  4870.8  471.26
  4905.9  470.17  4995.2  469.33  4995.7  468.53  5000.7  468.53  5001.2  469.33
  5098.4  472.25  5177.1  477.05  5328.0  478.60  5372.8  480.41  5400.7  484.41
  5423.1  484.79  5462.2  488.34  5534.9  496.91  5618.7  508.22  5655.1  511.88
#Mann=3,-1,0
  4452.7    0.16       0  4995.2    0.07       0  5001.2    0.16       0
Bank Sta=4702.5,5098.4
Exp/Cntr=0.3,0.1

Type RM Length L Ch R = 1,39433,319,319,319
BEGIN DESCRIPTION:
UNT 167 in LFCCL Watershed 57.0
END DESCRIPTION:
XS GIS Cut Line= 3
      2805375.00      7017425.00      2805775.00      7017675.00
      2806324.98      7018024.99
#Sta/Elev= 30
  4545.9  490.93  4581.3  488.19  4647.9  485.02  4705.9  481.16  4821.3  473.71
  4912.1  470.40  4930.9  469.77  4952.2  468.07  4994.6  468.07  5006.9  467.19
  5007.4  466.39  5012.4  466.39  5012.9  467.19  5014.7  468.48  5040.5  467.49
  5061.6  467.75  5067.6  468.47  5076.9  467.93  5112.4  468.56  5153.6  470.40
  5228.4  472.31  5264.8  473.93  5349.5  479.10  5373.2  479.68  5385.9  481.18
  5437.5  484.70  5479.9  488.96  5489.2  489.20  5642.0  504.88  5669.5  506.81
#Mann=5,-1,0
  4545.9    0.05       0  4705.9    0.16       0  5006.9    0.07       0
  5012.9    0.16       0  5642.0    0.05       0
Bank Sta=4912.1,5153.6
Exp/Cntr=0.3,0.1

Type RM Length L Ch R = 1,39114,398,398,398
BEGIN DESCRIPTION:
UNT 167 in LFCCL Watershed 56.0
END DESCRIPTION:
XS GIS Cut Line= 3
      2805324.99      7017524.98      2805475.00      7017825.00
      2806075.04      7018175.02
#Sta/Elev= 30
  4649.5  486.57  4676.8  484.34  4836.8  472.42  4903.9  468.55  4932.3  467.74
  4971.0  466.52  4987.8  466.43  4992.8  467.00  4998.6  464.95  5005.1  463.83
  5005.6  463.03  5010.6  463.03  5011.1  463.83  5020.1  466.76  5042.8  467.72
  5073.0  467.62  5110.2  465.35  5131.7  466.35  5137.5  467.17  5190.4  466.89
  5215.2  467.74  5297.9  470.89  5329.4  473.39  5335.1  472.84  5343.8  473.43
  5511.3  487.78  5575.8  494.50  5607.2  496.41  5656.4  500.67  5679.6  501.80
#Mann=4,-1,0
  4649.5    0.05       0  4676.8    0.16       0  5005.1    0.07       0
  5011.1    0.16       0
Bank Sta=4932.3,5215.2
Exp/Cntr=0.3,0.1

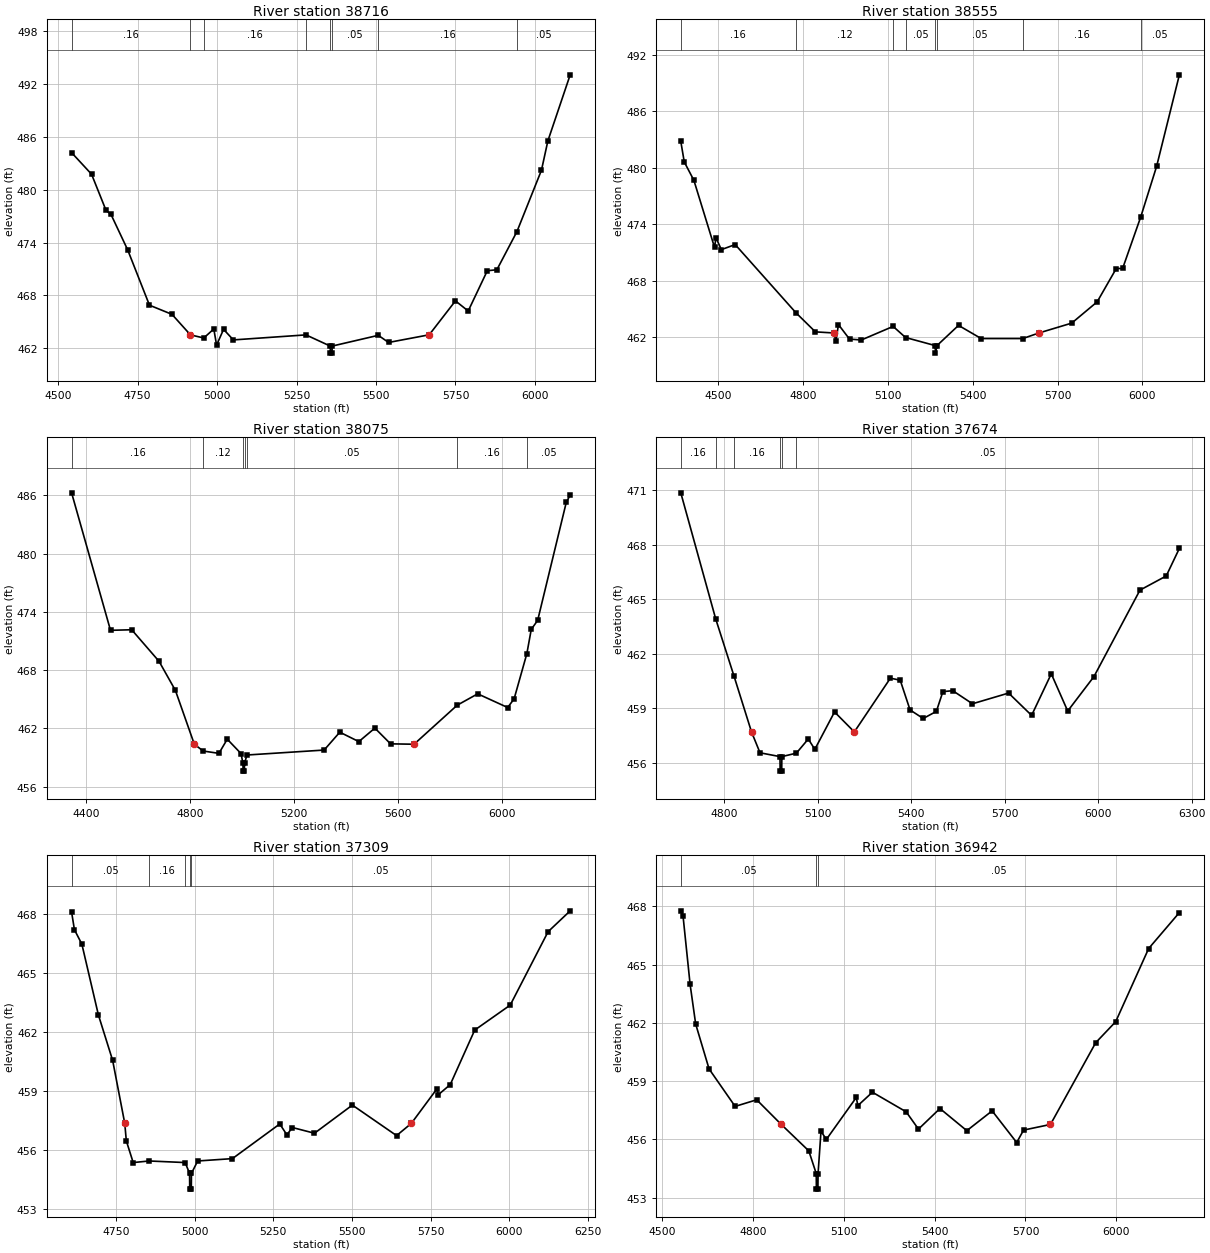
Type RM Length L Ch R = 1,38716,161,161,161
BEGIN DESCRIPTION:
Mapping XS 78b7df3a
END DESCRIPTION:
XS GIS Cut Line= 4
      2805083.39      7017592.95      2805153.79      7018047.40
      2805230.60      7018370.64      2806005.09      7018421.85
#Sta/Elev= 30
  4542.5  484.21  4605.3  481.76  4650.9  477.65  4666.0  477.23  4719.0  473.17
  4787.4  466.90  4858.3  465.86  4915.6  463.56  4916.2  463.53  4958.3  463.18
  4989.8  464.20  4998.6  462.37  5020.5  464.16  5051.3  462.96  5279.7  463.53
  5356.1  462.26  5356.6  461.46  5361.6  461.46  5362.1  462.26  5507.3  463.48
  5539.5  462.67  5667.4  463.54  5749.9  467.39  5790.0  466.24  5850.1  470.81
  5880.2  470.92  5943.3  475.25  6020.5  482.22  6040.6  485.54  6110.8  493.04
#Mann=8,-1,0
  4542.5    0.16       0  4915.6    0.12       0  4958.3    0.16       0
  5279.7    0.05       0  5356.1    0.07       0  5362.1    0.05       0
  5507.3    0.16       0  5943.3    0.05       0
Bank Sta=4916.2,5667.4
Exp/Cntr=0.3,0.1

Type RM Length L Ch R = 1,38555,480,480,480
BEGIN DESCRIPTION:
Mapping XS 802e6ccb
END DESCRIPTION:
XS GIS Cut Line= 4
      2804916.97      7017576.96      2805086.58      7018175.41
      2805137.79      7018453.85      2805995.53      7018489.06
#Sta/Elev= 30
  4367.4  482.80  4379.7  480.61  4413.7  478.66  4486.7  471.53  4491.9  472.55
  4510.9  471.29  4559.8  471.83  4774.4  464.59  4843.5  462.55  4909.5  462.43
  4916.2  461.56  4925.0  463.33  4964.2  461.78  5006.3  461.69  5118.5  463.13
  5162.4  461.95  5267.6  461.09  5268.1  460.29  5273.6  461.09  5349.8  463.24
  5429.9  461.84  5577.2  461.84  5634.0  462.43  5750.2  463.48  5840.2  465.74
  5907.7  469.28  5930.3  469.29  5994.6  474.79  6050.4  480.13  6131.0  489.87
#Mann=8,-1,0
  4367.4    0.16       0  4774.4    0.12       0  5118.5    0.16       0
  5162.4    0.05       0  5267.6    0.07       0  5273.6    0.05       0
  5577.2    0.16       0  5994.6    0.05       0
Bank Sta=4909.5,5634
Exp/Cntr=0.3,0.1

Type RM Length L Ch R = 1,38075,401,401,401
BEGIN DESCRIPTION:
UNT 167 in LFCCL Watershed 53.0
END DESCRIPTION:
XS GIS Cut Line= 3
      2804524.99      7017824.98      2804740.93      7018495.46
      2805875.02      7018925.01
#Sta/Elev= 30
  4345.3  486.26  4494.9  472.10  4576.4  472.16  4681.5  468.91  4744.5  465.91
  4817.2  460.37  4851.2  459.67  4911.8  459.43  4943.8  460.89  4996.7  459.41
  5004.2  458.40  5004.7  457.60  5009.7  457.60  5010.2  458.40  5019.5  459.26
  5316.3  459.77  5376.6  461.61  5449.7  460.64  5511.4  462.03  5571.7  460.41
  5662.1  460.37  5828.0  464.39  5906.8  465.56  6022.1  464.15  6046.9  465.05
  6095.8  469.70  6112.7  472.19  6137.4  473.13  6247.3  485.27  6262.4  486.04
#Mann=7,-1,0
  4345.3    0.16       0  4851.2    0.12       0  5004.2    0.07       0
  5010.2    0.12       0  5019.5    0.05       0  5828.0    0.16       0
  6095.8    0.05       0
Bank Sta=4817.2,5662.1
Exp/Cntr=0.3,0.1

Type RM Length L Ch R = 1,37674,365,365,365
BEGIN DESCRIPTION:
UNT 167 in LFCCL Watershed 52.0
END DESCRIPTION:
XS GIS Cut Line= 3
      2804275.01      7018325.03      2804425.00      7018625.00
      2805625.01      7019025.00
#Sta/Elev= 30
  4660.4  470.86  4772.4  463.92  4831.5  460.75  4887.4  457.69  4914.7  456.54
  4978.8  456.33  4979.3  455.53  4984.3  455.53  4984.8  456.33  5031.4  456.52
  5069.6  457.30  5090.6  456.73  5153.9  458.79  5217.4  457.69  5333.1  460.65
  5364.7  460.54  5396.3  458.90  5438.5  458.43  5480.7  458.82  5501.7  459.91
  5533.4  459.96  5596.6  459.24  5712.6  459.83  5786.4  458.60  5849.6  460.89
  5902.3  458.84  5986.6  460.74  6134.2  465.50  6218.5  466.28  6260.7  467.80
#Mann=6,-1,0
  4660.4    0.16       0  4772.4    0.05       0  4831.5    0.16       0
  4978.8    0.07       0  4984.8    0.16       0  5031.4    0.05       0
Bank Sta=4887.4,5217.4
Exp/Cntr=0.3,0.1

Type RM Length L Ch R = 1,37309,367,367,367
BEGIN DESCRIPTION:
UNT 167 in LFCCL Watershed 51.0
END DESCRIPTION:
XS GIS Cut Line= 3
      2804025.02      7018825.01      2804375.00      7018975.00
      2805574.98      7019075.00
#Sta/Elev= 30
  4608.6  468.10  4617.6  467.20  4641.2  466.47  4693.8  462.87  4739.1  460.56
  4777.6  457.36  4782.6  456.47  4804.4  455.37  4855.3  455.45  4969.6  455.37
  4983.6  454.82  4984.1  454.02  4989.1  454.02  4989.6  454.82  5009.4  455.45
  5119.8  455.57  5270.3  457.33  5292.9  456.78  5310.5  457.15  5380.7  456.86
  5501.1  458.29  5641.6  456.74  5688.6  457.36  5769.6  459.11  5774.6  458.82
  5812.2  459.33  5890.0  462.10  6002.9  463.37  6123.3  467.10  6193.5  468.16
#Mann=5,-1,0
  4608.6    0.05       0  4855.3    0.16       0  4969.6    0.05       0
  4983.6    0.03       0  4989.6    0.05       0
Bank Sta=4777.6,5688.6
Exp/Cntr=0.3,0.1

Type RM Length L Ch R = 1,36942,397,397,397
BEGIN DESCRIPTION:
UNT 167 in LFCCL Watershed 50.0
END DESCRIPTION:
XS GIS Cut Line= 3
      2803974.97      7019074.98      2804325.00      7019325.00
      2805525.00      7019125.00
#Sta/Elev= 30
  4561.5  467.77  4568.9  467.51  4592.3  463.98  4610.7  461.94  4654.9  459.63
  4741.0  457.70  4812.2  458.04  4893.4  456.77  4984.3  455.41  5008.9  454.24
  5009.4  453.44  5014.4  453.44  5014.9  454.24  5024.6  456.42  5042.3  456.00
  5141.2  458.16  5146.3  457.74  5194.4  458.43  5305.9  457.42  5346.5  456.53
  5417.4  457.59  5506.2  456.45  5589.8  457.47  5670.9  455.84  5693.7  456.48
  5782.5  456.77  5931.9  460.98  5997.8  462.06  6106.8  465.83  6208.2  467.68
#Mann=3,-1,0
  4561.5    0.05       0  5008.9    0.03       0  5014.9    0.05       0
Bank Sta=4893.4,5782.5
Exp/Cntr=0.3,0.1

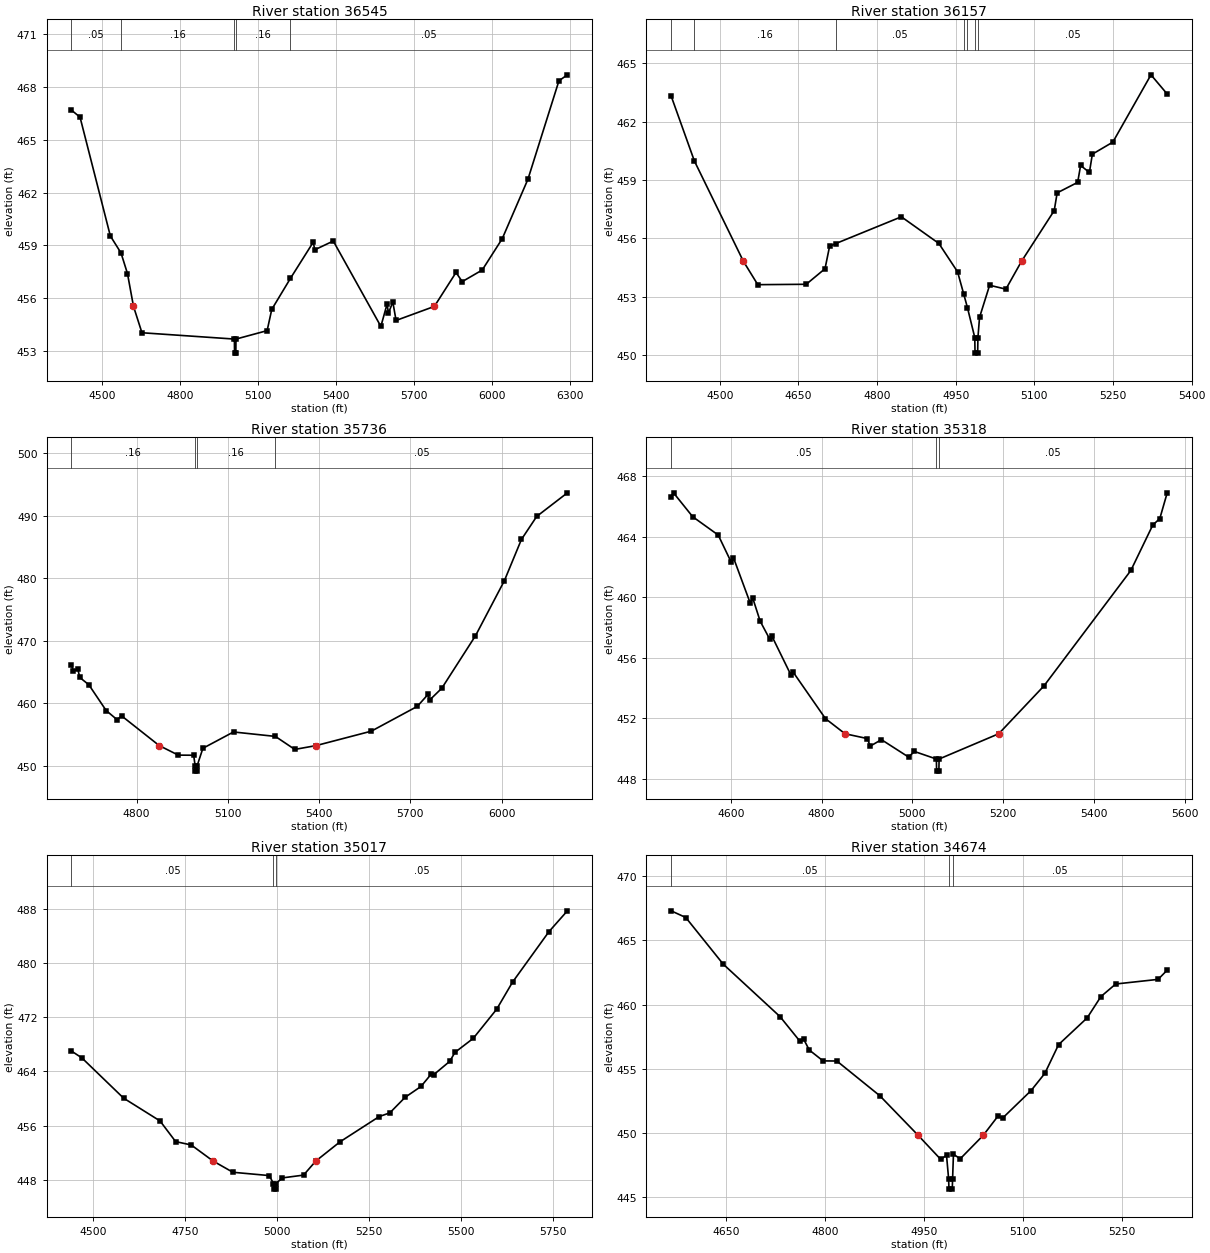
Type RM Length L Ch R = 1,36545,388,388,388
BEGIN DESCRIPTION:
UNT 167 in LFCCL Watershed 49.0
END DESCRIPTION:
XS GIS Cut Line= 3
      2803724.98      7019825.00      2804325.00      7019725.00
      2805525.00      7019225.00
#Sta/Elev= 30
  4380.6  466.69  4413.6  466.29  4530.2  459.53  4571.3  458.56  4596.1  457.39
  4619.3  455.52  4651.8  454.02  5007.6  453.66  5008.1  452.86  5013.1  452.86
  5013.6  453.66  5133.5  454.14  5151.4  455.35  5223.0  457.11  5311.2  459.18
  5316.6  458.74  5388.1  459.24  5571.2  454.38  5595.0  455.65  5600.4  455.14
  5617.2  455.77  5629.7  454.72  5777.1  455.52  5860.4  457.45  5884.3  456.93
  5961.2  457.59  6038.1  459.37  6137.2  462.76  6256.4  468.36  6288.9  468.70
#Mann=5,-1,0
  4380.6    0.05       0  4571.3    0.16       0  5007.6    0.07       0
  5013.6    0.16       0  5223.0    0.05       0
Bank Sta=4619.3,5777.1
Exp/Cntr=0.3,0.1

Type RM Length L Ch R = 1,36157,421,421,421
BEGIN DESCRIPTION:
UNT 167 in LFCCL Watershed 48.0
END DESCRIPTION:
XS GIS Cut Line= 3
      2804025.01      7020375.00      2804525.00      7020025.00
      2804674.99      7019725.03
#Sta/Elev= 30
  4407.4  463.32  4451.7  459.98  4545.2  454.82  4572.6  453.62  4665.0  453.64
  4700.8  454.44  4709.5  455.59  4721.0  455.73  4846.4  457.11  4917.9  455.74
  4953.6  454.28  4965.5  453.12  4972.5  452.43  4986.4  450.90  4986.9  450.10
  4991.9  450.10  4992.4  450.90  4995.5  451.94  5014.7  453.59  5045.7  453.39
  5075.5  454.82  5137.9  457.43  5143.5  458.34  5182.6  458.88  5188.2  459.75
  5205.0  459.39  5210.6  460.33  5249.7  460.95  5322.4  464.41  5353.1  463.43
#Mann=7,-1,0
  4407.4    0.05       0  4451.7    0.16       0  4721.0    0.05       0
  4965.5    0.16       0  4972.5    0.05       0  4986.4    0.03       0
  4992.4    0.05       0
Bank Sta=4545.2,5075.5
Exp/Cntr=0.3,0.1

Type RM Length L Ch R = 1,35736,418,418,418
BEGIN DESCRIPTION:
UNT 167 in LFCCL Watershed 47.0
END DESCRIPTION:
XS GIS Cut Line= 3
      2804273.65      7020652.58      2804617.22      7020421.05
      2805825.02      7020275.00
#Sta/Elev= 30
  4585.7  466.11  4591.8  465.21  4606.8  465.47  4612.8  464.16  4642.8  462.99
  4699.8  458.87  4735.8  457.40  4750.7  458.01  4874.4  453.26  4937.0  451.74
  4987.6  451.72  4992.6  449.98  4993.1  449.18  4998.1  449.18  4998.6  449.98
  5017.9  452.83  5118.6  455.44  5256.3  454.73  5320.1  452.65  5390.0  453.26
  5571.9  455.57  5723.0  459.53  5758.4  461.45  5763.4  460.53  5803.6  462.43
  5914.4  470.82  6009.2  479.60  6065.5  486.22  6115.8  489.90  6216.6  493.67
#Mann=4,-1,0
  4585.7    0.16       0  4992.6    0.07       0  4998.6    0.16       0
  5256.3    0.05       0
Bank Sta=4874.4,5390
Exp/Cntr=0.3,0.1

Type RM Length L Ch R = 1,35318,301,301,301
BEGIN DESCRIPTION:
UNT 167 in LFCCL Watershed 46.0
END DESCRIPTION:
XS GIS Cut Line= 3
      2804424.12      7020770.98      2804941.19      7020648.87
      2805474.99      7020475.00
#Sta/Elev= 30
  4468.7  466.64  4473.9  466.89  4516.2  465.31  4572.4  464.10  4600.8  462.32
  4605.9  462.61  4643.1  459.59  4648.2  459.96  4664.8  458.41  4685.4  457.25
  4690.5  457.43  4732.8  454.84  4738.0  455.02  4808.7  451.97  4851.8  450.97
  4901.2  450.65  4907.2  450.15  4932.0  450.58  4991.8  449.43  5004.6  449.80
  5053.1  449.30  5053.6  448.50  5058.6  448.50  5059.1  449.30  5190.5  450.97
  5290.1  454.13  5481.6  461.76  5529.9  464.76  5545.4  465.19  5561.4  466.86
#Mann=3,-1,0
  4468.7    0.05       0  5053.1    0.03       0  5059.1    0.05       0
Bank Sta=4851.8,5190.5
Exp/Cntr=0.3,0.1

Type RM Length L Ch R = 1,35017,343,343,343
BEGIN DESCRIPTION:
UNT 167 in LFCCL Watershed 45.0
END DESCRIPTION:
XS GIS Cut Line= 3
      2804724.97      7021275.03      2805125.00      7020875.00
      2805724.96      7020375.03
#Sta/Elev= 30
  4441.8  467.00  4470.1  465.99  4583.3  460.05  4682.3  456.68  4724.7  453.63
  4767.1  453.13  4826.4  450.76  4880.2  449.10  4979.2  448.61  4990.4  447.41
  4990.9  446.61  4995.9  446.61  4996.4  447.41  5014.7  448.27  5072.0  448.68
  5105.4  450.76  5170.9  453.59  5277.6  457.33  5306.3  457.87  5347.9  460.17
  5390.9  461.77  5419.5  463.65  5426.0  463.53  5469.0  465.48  5483.3  466.81
  5532.8  468.87  5596.5  473.18  5639.5  477.17  5738.4  484.63  5788.5  487.71
#Mann=3,-1,0
  4441.8    0.05       0  4990.4    0.03       0  4996.4    0.05       0
Bank Sta=4826.4,5105.4
Exp/Cntr=0.3,0.1

Type RM Length L Ch R = 1,34674,337,337,337
BEGIN DESCRIPTION:
UNT 167 in LFCCL Watershed 44.0
END DESCRIPTION:
XS GIS Cut Line= 3
      2804924.99      7021425.00      2805275.00      7021175.00
      2805475.01      7020924.98
#Sta/Elev= 30
  4567.4  467.30  4589.5  466.78  4646.1  463.15  4732.1  459.06  4761.6  457.18
  4767.7  457.32  4776.3  456.46  4797.2  455.61  4818.1  455.60  4883.2  452.89
  4941.3  449.80  4975.4  447.93  4984.0  448.27  4987.2  446.42  4987.7  445.62
  4992.7  445.62  4993.2  446.42  4994.5  448.34  5004.7  447.98  5039.4  449.80
  5061.6  451.29  5068.8  451.15  5112.0  453.30  5132.8  454.64  5153.6  456.88
  5196.8  458.96  5217.6  460.62  5240.0  461.60  5304.1  461.96  5317.7  462.67
#Mann=3,-1,0
  4567.4    0.05       0  4987.2    0.03       0  4993.2    0.05       0
Bank Sta=4941.3,5039.4
Exp/Cntr=0.3,0.1

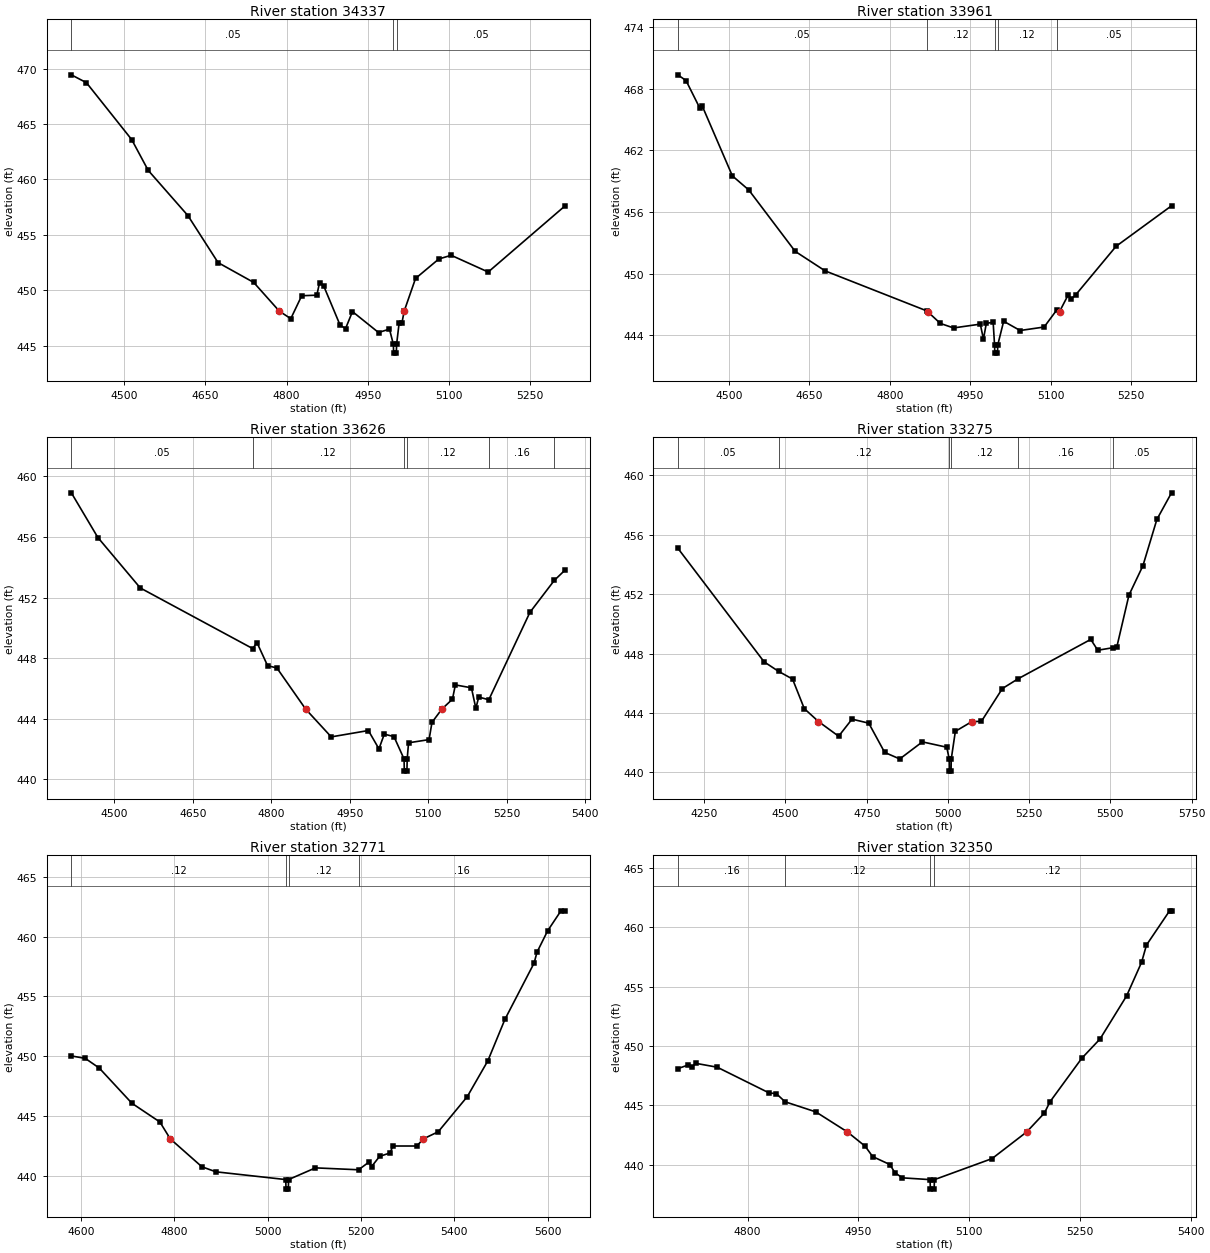
Type RM Length L Ch R = 1,34337,376,376,376
BEGIN DESCRIPTION:
UNT 167 in LFCCL Watershed 43.0
END DESCRIPTION:
XS GIS Cut Line= 3
      2804924.96      7021475.01      2805525.00      7021375.00
      2805825.04      7021425.01
#Sta/Elev= 30
  4402.1  469.44  4430.0  468.73  4513.7  463.59  4544.1  460.82  4617.6  456.73
  4673.3  452.49  4739.2  450.70  4786.5  448.11  4807.7  447.43  4827.9  449.50
  4855.8  449.55  4860.9  450.68  4868.5  450.39  4898.9  446.84  4909.0  446.54
  4921.7  448.07  4969.9  446.18  4990.1  446.49  4997.3  445.12  4997.8  444.32
  5002.8  444.32  5003.3  445.12  5007.9  447.01  5013.0  447.01  5017.3  448.11
  5038.3  451.06  5081.4  452.82  5104.2  453.15  5172.6  451.64  5314.6  457.61
#Mann=3,-1,0
  4402.1    0.05       0  4997.3    0.03       0  5003.3    0.05       0
Bank Sta=4786.5,5017.3
Exp/Cntr=0.3,0.1

Type RM Length L Ch R = 1,33961,335,335,335
BEGIN DESCRIPTION:
UNT 167 in LFCCL Watershed 42.0
END DESCRIPTION:
XS GIS Cut Line= 3
      2804975.00      7021525.00      2805525.00      7021725.00
      2805824.96      7021575.02
#Sta/Elev= 30
  4404.7  469.35  4420.0  468.79  4445.3  466.15  4450.6  466.27  4506.4  459.52
  4537.0  458.15  4623.5  452.18  4679.4  450.28  4868.9  446.39  4870.4  446.32
  4894.2  445.17  4918.8  444.73  4968.7  445.10  4974.6  443.65  4980.0  445.18
  4992.7  445.28  4995.3  443.08  4995.8  442.28  5000.8  442.28  5001.3  443.08
  5012.3  445.38  5043.0  444.48  5087.8  444.82  5111.6  446.50  5116.5  446.32
  5132.5  447.93  5138.1  447.55  5146.5  447.94  5221.9  452.67  5325.3  456.61
#Mann=5,-1,0
  4404.7    0.05       0  4868.9    0.12       0  4995.3    0.07       0
  5001.3    0.12       0  5111.6    0.05       0
Bank Sta=4870.4,5116.5
Exp/Cntr=0.3,0.1

Type RM Length L Ch R = 1,33626,351,351,351
BEGIN DESCRIPTION:
UNT 167 in LFCCL Watershed 41.0
END DESCRIPTION:
XS GIS Cut Line= 3
      2805074.97      7021925.00      2805675.00      7022025.00
      2805824.99      7021725.01
#Sta/Elev= 30
  4417.7  458.91  4468.4  455.96  4549.5  452.63  4764.3  448.63  4772.6  449.02
  4792.8  447.50  4810.6  447.35  4865.7  444.63  4914.5  442.80  4985.5  443.22
  5005.7  442.01  5015.9  442.98  5034.4  442.82  5053.7  441.34  5054.2  440.54
  5059.2  440.54  5059.7  441.34  5062.3  442.41  5101.5  442.62  5107.1  443.76
  5125.9  444.63  5146.2  445.29  5151.8  446.23  5182.5  446.04  5190.9  444.69
  5196.5  445.43  5215.7  445.25  5294.3  451.02  5340.9  453.13  5361.4  453.81
#Mann=6,-1,0
  4417.7    0.05       0  4764.3    0.12       0  5053.7    0.07       0
  5059.7    0.12       0  5215.7    0.16       0  5340.9    0.05       0
Bank Sta=4865.7,5125.9
Exp/Cntr=0.3,0.1

Type RM Length L Ch R = 1,33275,504,504,504
BEGIN DESCRIPTION:
UNT 167 in LFCCL Watershed 40.0
END DESCRIPTION:
XS GIS Cut Line= 3
      2805075.01      7022075.00      2805875.00      7022275.00
      2806474.97      7021925.02
#Sta/Elev= 30
  4168.8  455.10  4434.2  447.45  4478.6  446.81  4521.8  446.29  4557.9  444.30
  4601.6  443.43  4663.6  442.44  4704.8  443.59  4756.3  443.32  4805.3  441.35
  4851.7  440.91  4921.3  442.06  4996.3  441.70  5004.1  440.89  5004.6  440.09
  5009.6  440.09  5010.1  440.89  5022.8  442.77  5074.1  443.43  5103.0  443.44
  5167.5  445.65  5216.0  446.31  5439.5  448.96  5461.0  448.23  5507.5  448.40
  5519.8  448.46  5557.0  451.94  5600.0  453.92  5643.0  457.04  5688.0  458.83
#Mann=6,-1,0
  4168.8    0.05       0  4478.6    0.12       0  5004.1    0.07       0
  5010.1    0.12       0  5216.0    0.16       0  5507.5    0.05       0
Bank Sta=4601.6,5074.1
Exp/Cntr=0.3,0.1

Type RM Length L Ch R = 1,32771,421,421,421
BEGIN DESCRIPTION:
UNT 167 in LFCCL Watershed 39.0
END DESCRIPTION:
XS GIS Cut Line= 3
      2805425.27      7022662.52      2805859.25      7022662.52
      2806425.04      7022925.02
#Sta/Elev= 30
  4579.5  450.01  4609.2  449.81  4639.2  449.00  4709.2  446.05  4769.2  444.48
  4791.4  443.07  4859.2  440.73  4889.2  440.31  5038.9  439.66  5039.4  438.86
  5044.4  438.86  5044.9  439.66  5102.5  440.64  5194.8  440.48  5217.0  441.12
  5222.6  440.74  5239.9  441.60  5262.3  441.89  5268.4  442.47  5319.7  442.47
  5333.7  443.07  5365.5  443.66  5427.7  446.60  5471.8  449.60  5508.4  453.07
  5571.0  457.79  5577.1  458.69  5600.0  460.49  5628.5  462.16  5637.2  462.13
#Mann=4,-1,0
  4579.5    0.12       0  5038.9    0.07       0  5044.9    0.12       0
  5194.8    0.16       0
Bank Sta=4791.4,5333.7
Exp/Cntr=0.3,0.1

Type RM Length L Ch R = 1,32350,361,361,361
BEGIN DESCRIPTION:
UNT 167 in LFCCL Watershed 38.0
END DESCRIPTION:
XS GIS Cut Line= 3
      2805611.82      7023048.80      2805898.32      7023066.16
      2806275.03      7023125.00
#Sta/Elev= 30
  4705.6  448.10  4718.8  448.39  4724.6  448.22  4729.6  448.55  4758.9  448.22
  4829.0  446.06  4839.0  445.99  4850.8  445.31  4892.4  444.46  4935.2  442.77
  4959.2  441.57  4969.3  440.70  4992.6  440.03  4999.4  439.35  5009.5  438.91
  5047.0  438.76  5047.5  437.96  5052.5  437.96  5053.0  438.76  5131.0  440.53
  5177.8  442.77  5201.8  444.36  5209.4  445.31  5252.4  448.97  5277.2  450.60
  5313.1  454.22  5333.4  457.05  5340.0  458.50  5371.3  461.38  5373.9  461.38
#Mann=4,-1,0
  4705.6    0.16       0  4850.8    0.12       0  5047.0    0.07       0
  5053.0    0.12       0
Bank Sta=4935.2,5177.8
Exp/Cntr=0.3,0.1

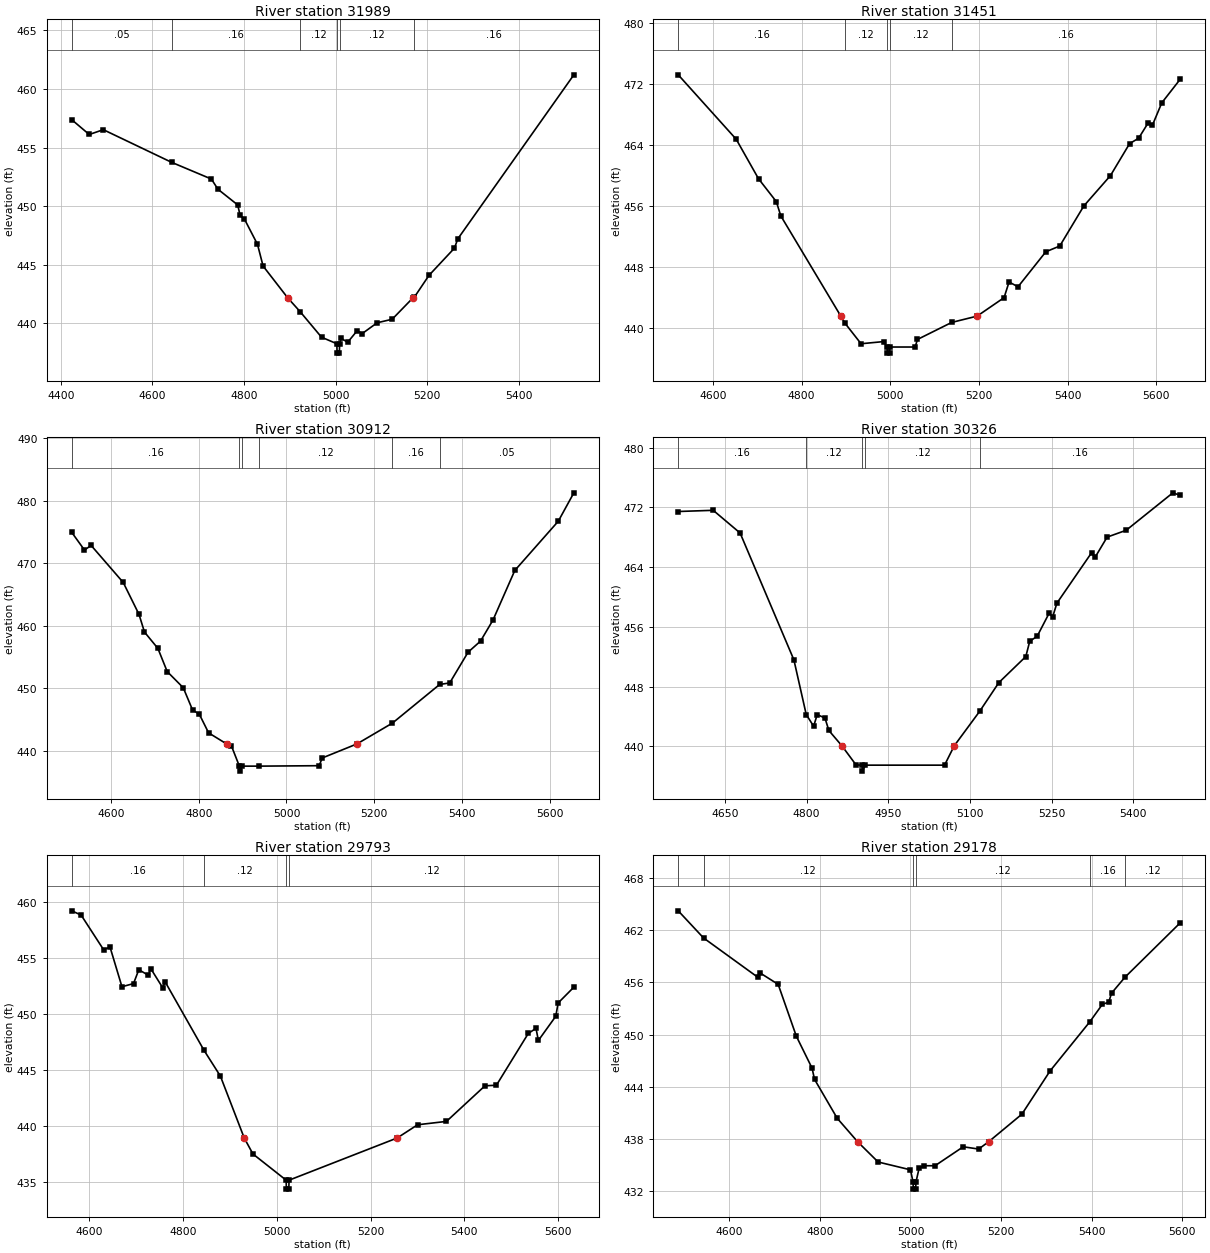
Type RM Length L Ch R = 1,31989,538,538,538
BEGIN DESCRIPTION:
UNT 167 in LFCCL Watershed 37.0
END DESCRIPTION:
XS GIS Cut Line= 3
      2805177.82      7023239.77      2805775.00      7023375.00
      2806236.90      7023517.57
#Sta/Elev= 30
  4424.0  457.37  4462.1  456.11  4492.9  456.52  4641.7  453.74  4728.7  452.31
  4743.0  451.44  4786.2  450.10  4791.3  449.21  4800.5  448.92  4829.3  446.74
  4841.5  444.89  4895.4  442.17  4922.5  440.99  4969.0  438.82  5002.5  438.26
  5003.0  437.46  5008.0  437.46  5008.5  438.26  5012.2  438.72  5026.0  438.38
  5046.8  439.37  5057.9  439.13  5090.5  440.05  5123.2  440.35  5168.5  442.17
  5171.9  442.25  5203.7  444.10  5259.0  446.41  5266.5  447.21  5519.7  461.20
#Mann=6,-1,0
  4424.0    0.05       0  4641.7    0.16       0  4922.5    0.12       0
  5002.5    0.07       0  5008.5    0.12       0  5171.9    0.16       0
Bank Sta=4895.4,5168.5
Exp/Cntr=0.3,0.1

Type RM Length L Ch R = 1,31451,539,539,539
BEGIN DESCRIPTION:
UNT 167 in LFCCL Watershed 36.0
END DESCRIPTION:
XS GIS Cut Line= 3
      2804875.02      7023675.00      2805325.00      7023725.00
      2805974.98      7023924.99
#Sta/Elev= 30
  4521.6  473.16  4652.4  464.72  4702.7  459.55  4742.9  456.55  4753.0  454.68
  4888.4  441.55  4898.2  440.59  4934.1  437.93  4984.8  438.21  4992.9  437.50
  4993.4  436.70  4998.4  436.70  4998.9  437.50  5056.1  437.50  5061.3  438.49
  5138.5  440.72  5196.0  441.55  5256.8  443.97  5268.0  446.02  5288.2  445.39
  5351.0  449.98  5382.4  450.73  5436.7  455.98  5496.8  459.96  5540.0  464.15
  5560.3  464.85  5581.2  466.80  5591.6  466.58  5612.6  469.49  5654.4  472.60
#Mann=5,-1,0
  4521.6    0.16       0  4898.2    0.12       0  4992.9    0.07       0
  4998.9    0.12       0  5138.5    0.16       0
Bank Sta=4888.4,5196
Exp/Cntr=0.3,0.1

Type RM Length L Ch R = 1,30912,586,586,586
BEGIN DESCRIPTION:
UNT 167 in LFCCL Watershed 35.0
END DESCRIPTION:
XS GIS Cut Line= 3
      2804825.01      7023775.02      2805075.00      7024175.00
      2805575.03      7024625.03
#Sta/Elev= 30
  4510.6  474.94  4539.5  472.12  4554.8  472.85  4627.9  466.92  4663.9  461.80
  4676.3  458.98  4706.9  456.36  4728.1  452.65  4764.7  450.06  4785.9  446.50
  4801.3  445.82  4822.5  442.83  4863.5  441.06  4874.4  440.76  4892.6  437.50
  4893.1  436.70  4898.7  437.50  4938.2  437.50  5074.6  437.57  5081.3  438.80
  5160.7  441.06  5241.6  444.40  5349.1  450.58  5372.1  450.83  5413.9  455.75
  5442.3  457.53  5470.7  460.90  5520.4  468.84  5619.5  476.73  5655.0  481.28
#Mann=6,-1,0
  4510.6    0.16       0  4892.6    0.07       0  4898.7    0.16       0
  4938.2    0.12       0  5241.6    0.16       0  5349.1    0.05       0
Bank Sta=4863.5,5160.7
Exp/Cntr=0.3,0.1

Type RM Length L Ch R = 1,30326,533,533,533
BEGIN DESCRIPTION:
UNT 167 in LFCCL Watershed 34.0
END DESCRIPTION:
XS GIS Cut Line= 3
      2804275.01      7024225.01      2804625.00      7024525.00
      2804924.97      7024874.97
#Sta/Elev= 30
  4564.4  471.46  4628.6  471.62  4678.0  468.58  4776.8  451.59  4799.4  444.28
  4813.0  442.71  4819.6  444.27  4833.8  443.81  4841.0  442.14  4864.9  440.09
  4890.9  437.53  4902.1  437.50  4902.6  436.70  4908.2  437.50  5053.4  437.50
  5071.2  440.09  5118.3  444.75  5153.2  448.56  5202.6  452.04  5209.8  454.08
  5223.5  454.76  5245.4  457.84  5252.0  457.37  5259.7  459.19  5323.4  465.94
  5329.9  465.34  5351.9  468.03  5387.0  468.95  5472.6  473.96  5486.3  473.62
#Mann=5,-1,0
  4564.4    0.16       0  4799.4    0.12       0  4902.1    0.07       0
  4908.2    0.12       0  5118.3    0.16       0
Bank Sta=4864.9,5071.2
Exp/Cntr=0.3,0.1

Type RM Length L Ch R = 1,29793,615,615,615
BEGIN DESCRIPTION:
UNT 167 in LFCCL Watershed 33.0
END DESCRIPTION:
XS GIS Cut Line= 3
      2804023.33      7024350.93      2804175.00      7024775.00
      2804318.45      7025379.53
#Sta/Elev= 30
  4562.2  459.21  4582.2  458.83  4630.2  455.73  4643.8  455.98  4669.3  452.43
  4694.0  452.71  4705.3  453.95  4725.5  453.46  4730.8  454.05  4756.3  452.34
  4761.6  452.86  4844.6  446.74  4879.4  444.45  4930.3  438.92  4948.9  437.49
  5019.8  435.15  5020.3  434.35  5025.5  434.35  5026.0  435.15  5256.9  438.92
  5300.4  440.10  5362.0  440.40  5444.2  443.58  5468.6  443.63  5536.7  448.26
  5553.1  448.71  5558.2  447.63  5595.3  449.79  5600.4  450.98  5633.9  452.39
#Mann=4,-1,0
  4562.2    0.16       0  4844.6    0.12       0  5019.8    0.07       0
  5026.0    0.12       0
Bank Sta=4930.3,5256.9
Exp/Cntr=0.3,0.1

Type RM Length L Ch R = 1,29178,502,502,502
BEGIN DESCRIPTION:
UNT 167 in LFCCL Watershed 32.0
END DESCRIPTION:
XS GIS Cut Line= 3
      2803575.00      7024475.02      2803618.47      7024986.28
      2803525.00      7025575.00
#Sta/Elev= 30
  4486.9  464.24  4542.8  461.12  4663.2  456.58  4668.2  457.08  4707.7  455.78
  4747.8  449.82  4782.5  446.15  4788.0  444.86  4838.1  440.38  4883.2  437.68
  4928.5  435.35  5000.0  434.45  5005.7  433.03  5006.2  432.23  5011.5  432.23
  5012.0  433.03  5019.0  434.62  5029.1  434.92  5054.2  434.92  5116.5  437.10
  5150.6  436.84  5172.7  437.68  5246.1  440.85  5308.3  445.82  5396.4  451.49
  5424.0  453.49  5437.9  453.73  5444.2  454.77  5473.8  456.60  5596.1  462.87
#Mann=6,-1,0
  4486.9    0.16       0  4542.8    0.12       0  5005.7    0.07       0
  5012.0    0.12       0  5396.4    0.16       0  5473.8    0.12       0
Bank Sta=4883.2,5172.7
Exp/Cntr=0.3,0.1