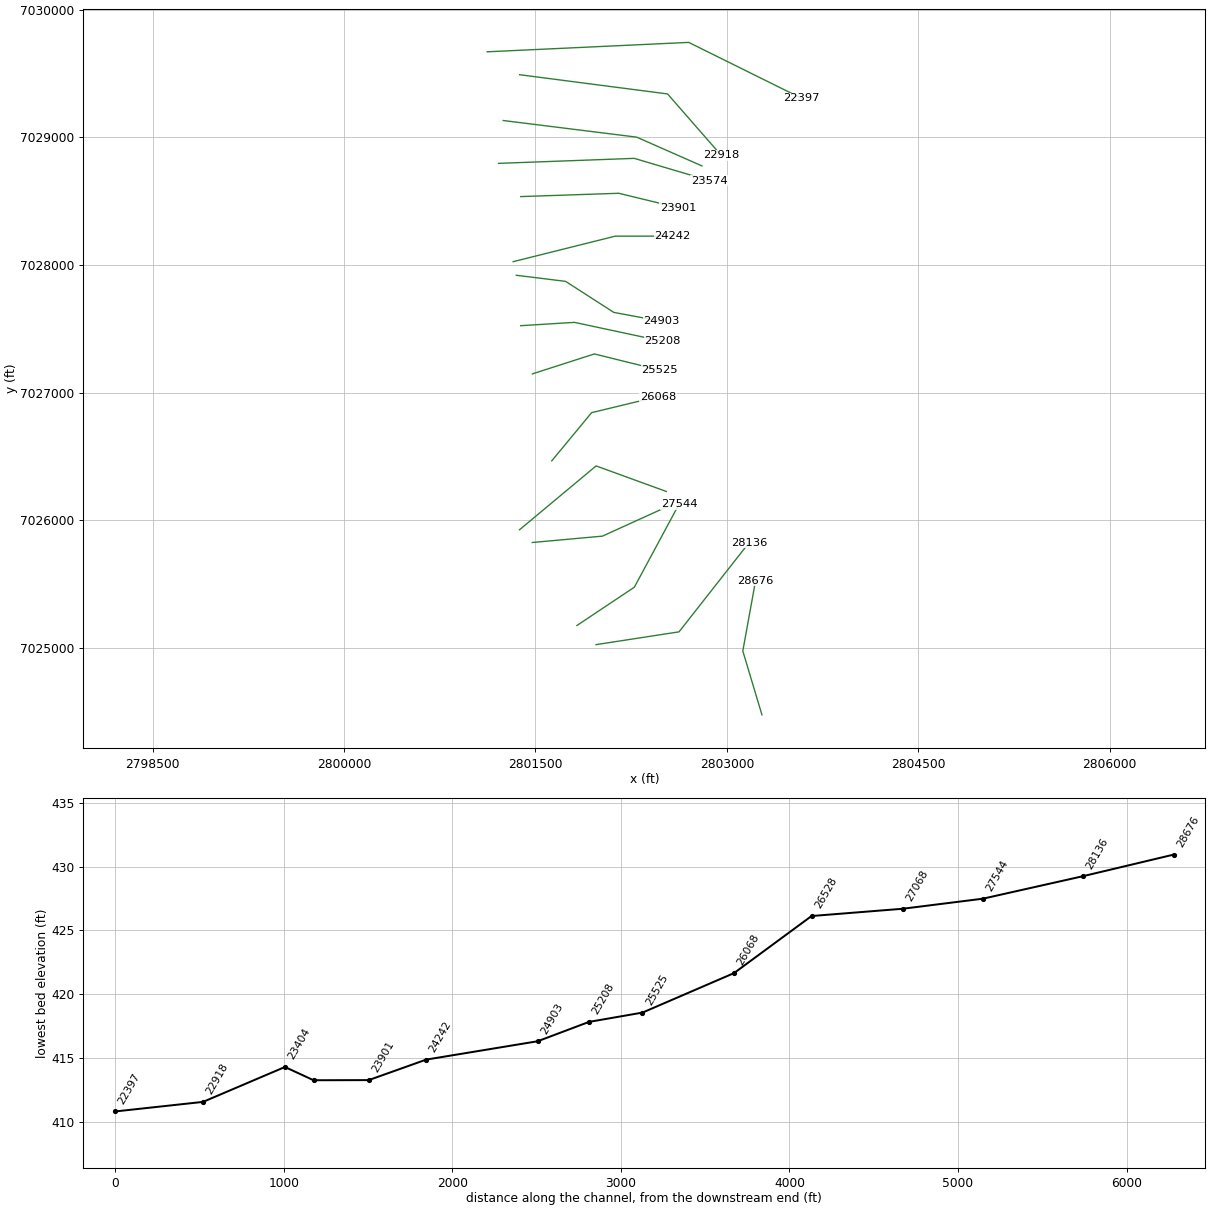
HEC-RAS study UNT 167 in LFCCL Watershed.prj: UNT 167 in LFCCL Watershed Base Level Engineering

--- UNT 167 in LFCCL Watershed.g01 (geometry) --- (continued)

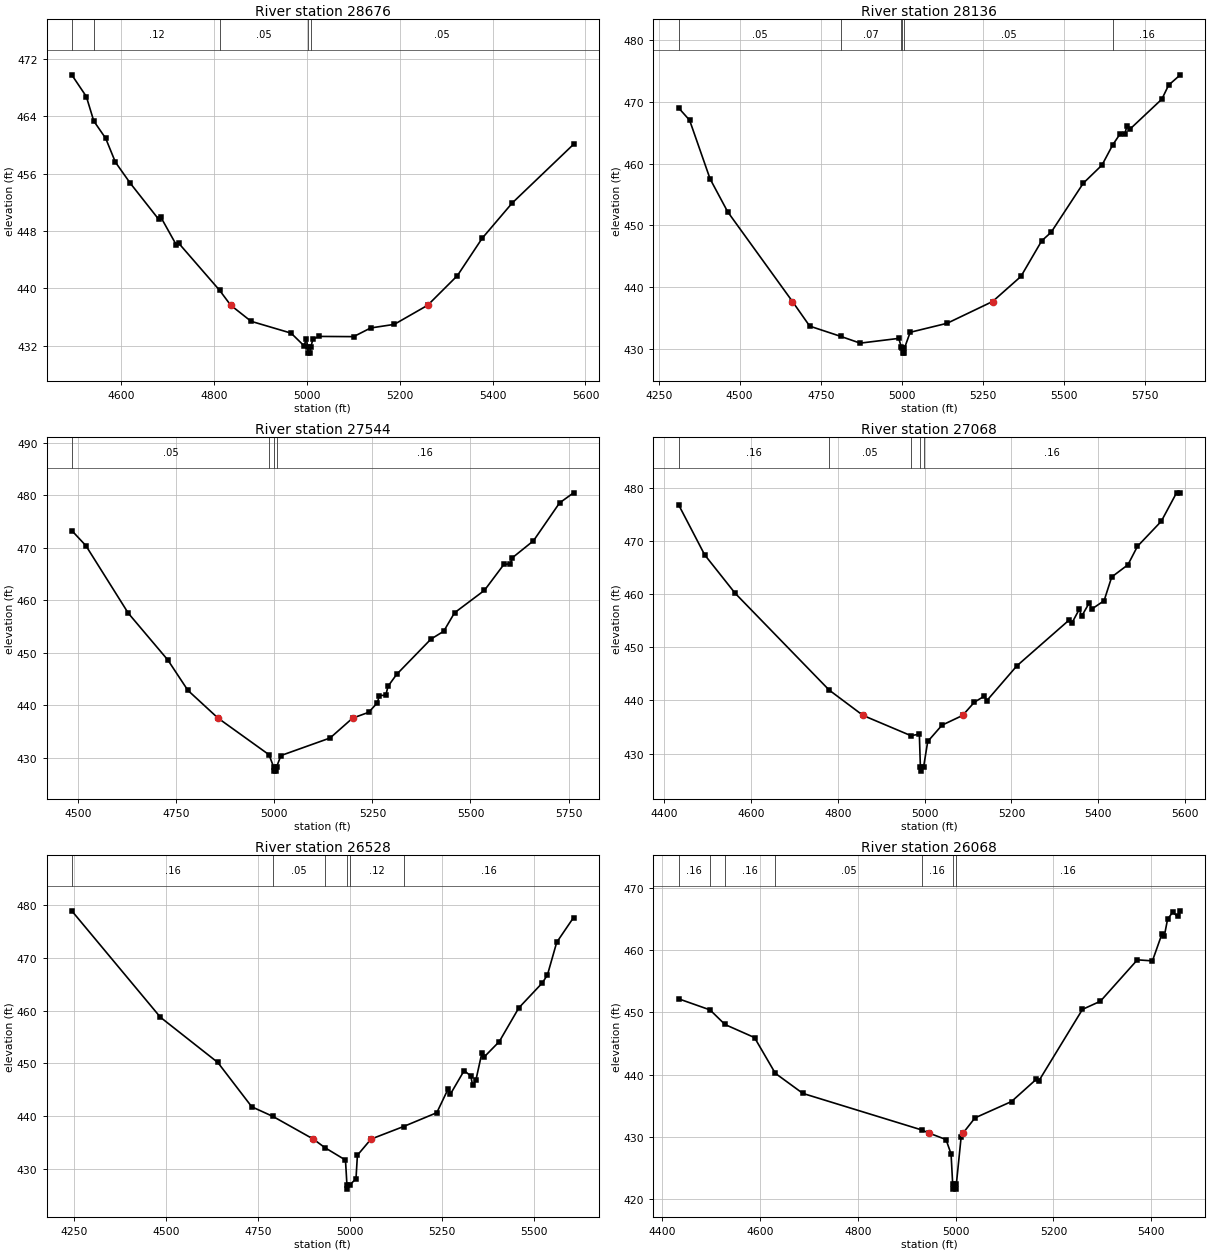
Type RM Length L Ch R = 1,28676,540,540,540
BEGIN DESCRIPTION:
UNT 167 in LFCCL Watershed 31.0
END DESCRIPTION:
XS GIS Cut Line= 3
      2803275.01      7024474.95      2803125.00      7024975.00
      2803225.00      7025525.02
#Sta/Elev= 30
  4493.3  469.77  4524.7  466.74  4540.7  463.33  4566.4  460.91  4587.3  457.59
  4619.5  454.64  4680.4  449.63  4685.6  449.87  4718.7  446.03  4723.9  446.27
  4811.7  439.72  4835.8  437.63  4879.6  435.39  4965.8  433.74  4993.6  431.98
  4998.8  432.94  5001.8  431.75  5002.3  430.95  5007.6  430.95  5008.1  431.75
  5012.8  432.88  5025.5  433.28  5100.5  433.25  5137.3  434.46  5188.1  434.96
  5260.1  437.63  5324.1  441.76  5377.5  446.97  5442.2  451.89  5574.4  460.08
#Mann=5,-1,0
  4493.3    0.05       0  4540.7    0.12       0  4811.7    0.05       0
  5001.8   0.035       0  5008.1    0.05       0
Bank Sta=4835.8,5260.1
Exp/Cntr=0.3,0.1

Type RM Length L Ch R = 1,28136,592,592,592
BEGIN DESCRIPTION:
UNT 167 in LFCCL Watershed 30.0
END DESCRIPTION:
XS GIS Cut Line= 3
      2801974.98      7025025.00      2802625.00      7025125.00
      2803175.00      7025825.01
#Sta/Elev= 30
  4311.3  469.04  4345.5  467.03  4408.7  457.51  4463.1  452.16  4662.8  437.62
  4716.0  433.63  4811.5  431.97  4871.6  430.87  4990.6  431.64  4998.9  430.20
  5001.9  430.05  5002.4  429.25  5007.7  429.25  5008.2  430.05  5025.9  432.63
  5139.8  434.09  5280.1  437.62  5367.5  441.69  5431.7  447.47  5460.6  448.84
  5560.0  456.82  5617.6  459.75  5650.6  463.02  5673.9  464.85  5688.4  464.86
  5694.7  466.17  5702.8  465.53  5802.3  470.45  5823.1  472.72  5859.2  474.39
#Mann=6,-1,0
  4311.3    0.05       0  4811.5    0.07       0  4998.9    0.05       0
  5001.9    0.03       0  5008.2    0.05       0  5650.6    0.16       0
Bank Sta=4662.8,5280.1
Exp/Cntr=0.3,0.1

Type RM Length L Ch R = 1,27544,476,476,476
BEGIN DESCRIPTION:
UNT 167 in LFCCL Watershed 29.0
END DESCRIPTION:
XS GIS Cut Line= 3
      2801824.98      7025174.99      2802275.00      7025475.00
      2802625.00      7026125.01
#Sta/Elev= 30
  4483.7  473.30  4519.8  470.41  4627.9  457.55  4728.6  448.65  4779.7  442.87
  4856.6  437.58  4986.4  430.62  4998.3  428.29  4998.9  427.49  5005.2  427.49
  5005.7  428.29  5017.0  430.46  5142.2  433.80  5199.5  437.58  5240.3  438.68
  5262.3  440.46  5267.9  441.88  5284.2  441.94  5289.8  443.64  5311.7  445.90
  5399.4  452.64  5431.8  454.12  5459.4  457.64  5535.6  461.91  5585.1  466.84
  5601.4  466.97  5607.0  468.13  5660.6  471.35  5727.1  478.56  5762.8  480.48
#Mann=4,-1,0
  4483.7    0.05       0  4986.4    0.16       0  4998.3    0.07       0
  5005.7    0.16       0
Bank Sta=4856.6,5199.5
Exp/Cntr=0.3,0.1

Type RM Length L Ch R = 1,27068,540,540,540
BEGIN DESCRIPTION:
UNT 167 in LFCCL Watershed 28.0
END DESCRIPTION:
XS GIS Cut Line= 3
      2801474.97      7025825.00      2802025.00      7025875.00
      2802574.96      7026124.98
#Sta/Elev= 30
  4432.8  476.81  4493.1  467.36  4563.4  460.13  4780.1  441.93  4858.1  437.17
  4968.3  433.37  4987.8  433.64  4990.2  427.50  4990.7  426.70  4997.6  427.50
  5007.1  432.27  5040.0  435.34  5087.5  437.17  5114.7  439.67  5137.8  440.81
  5143.3  439.95  5212.5  446.49  5333.3  455.13  5338.8  454.46  5356.4  457.13
  5361.9  455.83  5379.4  458.34  5384.9  457.15  5413.5  458.74  5431.1  463.20
  5468.4  465.49  5490.4  468.96  5545.3  473.67  5580.5  479.02  5589.2  479.02
#Mann=5,-1,0
  4432.8    0.16       0  4780.1    0.05       0  4968.3    0.16       0
  4990.2    0.07       0  4997.6    0.16       0
Bank Sta=4858.1,5087.5
Exp/Cntr=0.3,0.1

Type RM Length L Ch R = 1,26528,460,460,460
BEGIN DESCRIPTION:
UNT 167 in LFCCL Watershed 27.0
END DESCRIPTION:
XS GIS Cut Line= 3
      2801375.03      7025925.03      2801975.00      7026425.00
      2802524.98      7026225.01
#Sta/Elev= 30
  4242.7  478.97  4484.1  458.76  4640.3  450.18  4732.8  441.76  4790.8  439.92
  4900.4  435.63  4931.6  434.02  4987.9  431.65  4991.9  426.93  4992.5  426.13
  4999.4  426.93  5016.5  428.08  5020.4  432.57  5057.5  435.63  5146.2  438.02
  5236.5  440.64  5267.8  445.21  5273.1  444.11  5311.0  448.63  5328.9  447.63
  5334.3  445.81  5342.9  446.80  5359.5  452.06  5364.8  451.17  5406.7  454.15
  5459.9  460.55  5523.8  465.28  5537.8  466.81  5563.0  472.99  5608.9  477.70
#Mann=6,-1,0
  4242.7    0.16       0  4790.8    0.05       0  4931.6    0.12       0
  4991.9    0.07       0  4999.4    0.12       0  5146.2    0.16       0
Bank Sta=4900.4,5057.5
Exp/Cntr=0.3,0.1

Type RM Length L Ch R = 1,26068,543,543,543
BEGIN DESCRIPTION:
UNT 167 in LFCCL Watershed 26.0
END DESCRIPTION:
XS GIS Cut Line= 3
      2801627.50      7026464.63      2801939.98      7026842.21
      2802460.39      7026967.97
#Sta/Elev= 30
  4433.7  452.18  4498.1  450.40  4528.6  448.06  4589.0  445.96  4631.5  440.23
  4687.9  437.00  4930.4  431.15  4945.3  430.65  4980.4  429.60  4990.7  427.29
  4994.0  422.45  4994.6  421.65  5000.9  421.65  5001.5  422.45  5011.3  430.05
  5015.3  430.65  5039.6  433.08  5114.2  435.70  5165.1  439.29  5170.3  439.04
  5259.2  450.48  5295.9  451.79  5371.4  458.43  5402.2  458.26  5421.5  462.55
  5426.6  462.30  5433.1  464.93  5443.4  466.05  5453.7  465.40  5459.2  466.29
#Mann=7,-1,0
  4433.7    0.16       0  4498.1    0.05       0  4528.6    0.16       0
  4631.5    0.05       0  4930.4    0.16       0  4994.0    0.07       0
  5001.5    0.16       0
Bank Sta=4945.3,5015.3
Exp/Cntr=0.3,0.1

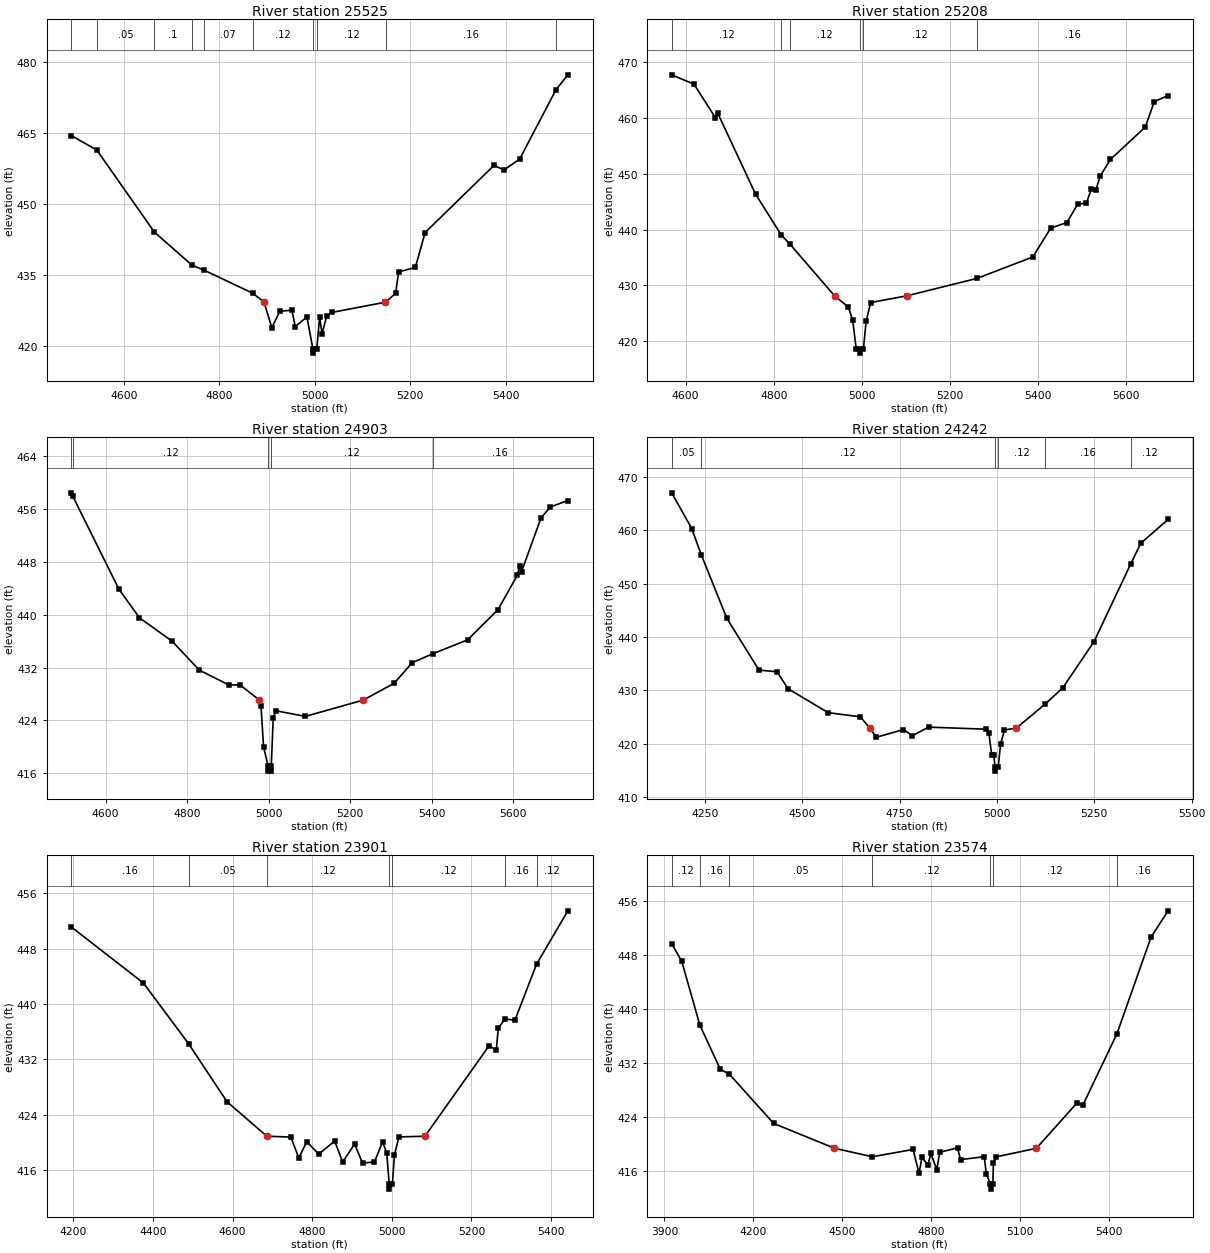
Type RM Length L Ch R = 1,25525,317,317,317
BEGIN DESCRIPTION:
UNT 167 in LFCCL Watershed 25.0
END DESCRIPTION:
XS GIS Cut Line= 3
      2801475.61      7027146.04      2801961.68      7027302.28
      2802474.98      7027175.01
#Sta/Elev= 30
  4490.6  464.46  4543.8  461.40  4664.1  444.11  4742.9  437.12  4767.4  436.10
  4870.6  431.18  4893.9  429.30  4910.1  423.94  4927.1  427.40  4952.1  427.60
  4959.2  424.15  4983.6  426.18  4996.3  419.35  4997.0  418.55  5004.2  419.35
  5010.2  426.17  5015.3  422.67  5025.2  426.42  5035.5  427.14  5148.0  429.30
  5149.2  429.36  5169.4  431.21  5175.7  435.70  5210.6  436.64  5231.2  444.01
  5375.5  458.20  5396.1  457.19  5429.1  459.52  5505.4  474.20  5530.0  477.30
#Mann=10,-1,0
  4490.6    0.16       0  4543.8    0.05       0  4664.1     0.1       0
  4742.9    0.05       0  4767.4    0.07       0  4870.6    0.12       0
  4996.3    0.07       0  5004.2    0.12       0  5149.2    0.16       0
  5505.4    0.05       0
Bank Sta=4893.9,5148
Exp/Cntr=0.3,0.1

Type RM Length L Ch R = 1,25208,305,305,305
BEGIN DESCRIPTION:
XS3971A
END DESCRIPTION:
XS GIS Cut Line= 3
      2801384.44      7027523.63      2801805.43      7027549.67
      2802495.54      7027402.10
#Sta/Elev= 30
  4568.2  467.78  4618.9  466.11  4667.6  460.08  4672.7  460.92  4759.1  446.31
  4816.9  439.06  4836.3  437.43  4938.3  428.10  4969.5  426.09  4979.5  423.71
  4987.3  418.62  4995.8  418.62  4996.5  417.82  5003.8  418.62  5010.0  423.57
  5020.2  426.90  5102.1  428.10  5261.9  431.24  5388.4  435.08  5429.3  440.26
  5465.9  441.26  5490.6  444.56  5510.2  444.76  5521.3  447.20  5531.5  447.06
  5541.8  449.61  5564.8  452.59  5644.0  458.39  5664.5  462.98  5695.7  464.06
#Mann=6,-1,0
  4568.2    0.12       0  4816.9    0.16       0  4836.3    0.12       0
  4995.8    0.07       0  5003.8    0.12       0  5261.9    0.16       0
Bank Sta=4938.3,5102.1
Exp/Cntr=0.3,0.1

Type RM Length L Ch R = 1,24903,661,661,661
BEGIN DESCRIPTION:
XS3972A
END DESCRIPTION:
XS GIS Cut Line= 4
      2801349.70      7027918.60      2801735.99      7027870.85
      2802113.59      7027627.80      2802486.90      7027558.34
#Sta/Elev= 30
  4516.3  458.49  4519.7  457.94  4632.5  443.90  4682.9  439.56  4763.5  435.98
  4830.0  431.61  4902.5  429.36  4929.8  429.37  4977.5  427.07  4981.3  426.22
  4987.6  420.02  4998.5  417.10  4999.2  416.30  5005.8  416.30  5006.5  417.10
  5011.4  424.41  5017.6  425.45  5090.3  424.60  5232.3  427.07  5308.2  429.62
  5352.6  432.75  5402.8  434.09  5488.3  436.20  5562.9  440.78  5610.3  445.99
  5615.7  447.35  5620.7  446.54  5668.4  454.68  5691.7  456.36  5734.3  457.32
#Mann=5,-1,0
  4516.3    0.05       0  4519.7    0.12       0  4998.5    0.07       0
  5006.5    0.12       0  5402.8    0.16       0
Bank Sta=4977.5,5232.3
Exp/Cntr=0.3,0.1

Type RM Length L Ch R = 1,24242,341,341,341
BEGIN DESCRIPTION:
UNT 167 in LFCCL Watershed 23.0
END DESCRIPTION:
XS GIS Cut Line= 3
      2801325.03      7028025.01      2802125.00      7028225.00
      2802575.01      7028225.00
#Sta/Elev= 30
  4164.7  467.06  4216.2  460.36  4240.5  455.48  4306.4  443.52  4388.9  433.81
  4435.2  433.50  4463.6  430.32  4566.7  425.82  4649.1  425.05  4673.5  422.93
  4690.4  421.21  4759.9  422.66  4783.1  421.51  4824.4  423.11  4971.2  422.73
  4979.0  422.09  4986.7  417.83  4991.8  417.83  4995.3  415.66  4995.9  414.86
  5003.3  415.66  5009.3  419.94  5019.3  422.59  5049.8  422.93  5123.0  427.39
  5169.3  430.51  5249.3  439.16  5343.7  453.75  5369.3  457.60  5439.3  462.06
#Mann=6,-1,0
  4164.7    0.05       0  4240.5    0.12       0  4995.3    0.07       0
  5003.3    0.12       0  5123.0    0.16       0  5343.7    0.12       0
Bank Sta=4673.5,5049.8
Exp/Cntr=0.3,0.1

Type RM Length L Ch R = 1,23901,327,327,327
BEGIN DESCRIPTION:
XS3974A
END DESCRIPTION:
XS GIS Cut Line= 3
      2801384.42      7028534.91      2802152.66      7028560.96
      2802617.07      7028448.11
#Sta/Elev= 30
  4195.6  451.10  4376.3  443.02  4489.9  434.24  4586.4  425.86  4685.7  420.92
  4687.8  420.89  4746.5  420.77  4766.5  417.75  4786.5  420.11  4816.5  418.30
  4856.6  420.20  4876.6  417.16  4906.6  419.77  4926.6  417.01  4956.6  417.18
  4977.0  420.10  4987.3  418.45  4993.5  414.05  4994.2  413.25  5001.6  414.05
  5006.7  418.20  5018.1  420.79  5083.3  420.89  5244.5  433.97  5262.4  433.32
  5267.5  436.48  5283.8  437.82  5309.3  437.66  5363.5  445.73  5442.2  453.45
#Mann=7,-1,0
  4195.6    0.16       0  4489.9    0.05       0  4685.7    0.12       0
  4993.5    0.07       0  5001.6    0.12       0  5283.8    0.16       0
  5363.5    0.12       0
Bank Sta=4687.8,5083.3
Exp/Cntr=0.3,0.1

Type RM Length L Ch R = 1,23574,170,170,170
BEGIN DESCRIPTION:
XS3973A
END DESCRIPTION:
XS GIS Cut Line= 3
      2801210.80      7028795.33      2802274.18      7028834.39
      2802860.10      7028660.79
#Sta/Elev= 30
  3924.4  449.71  3958.6  447.05  4019.7  437.58  4088.7  431.03  4118.7  430.33
  4268.8  422.99  4473.8  419.31  4601.6  418.05  4739.2  419.13  4759.2  415.58
  4769.2  417.96  4789.2  416.79  4799.2  418.55  4819.2  416.13  4829.2  418.72
  4889.3  419.37  4899.3  417.62  4979.3  418.06  4986.4  415.45  5000.4  414.04
  5001.1  413.24  5008.5  414.04  5010.2  417.08  5020.6  418.04  5155.5  419.31
  5291.8  426.01  5312.7  425.76  5427.2  436.31  5542.1  450.65  5599.6  454.57
#Mann=7,-1,0
  3924.4    0.12       0  4019.7    0.16       0  4118.7    0.05       0
  4601.6    0.12       0  5000.4    0.07       0  5008.5    0.12       0
  5427.2    0.16       0
Bank Sta=4473.8,5155.5
Exp/Cntr=0.3,0.1

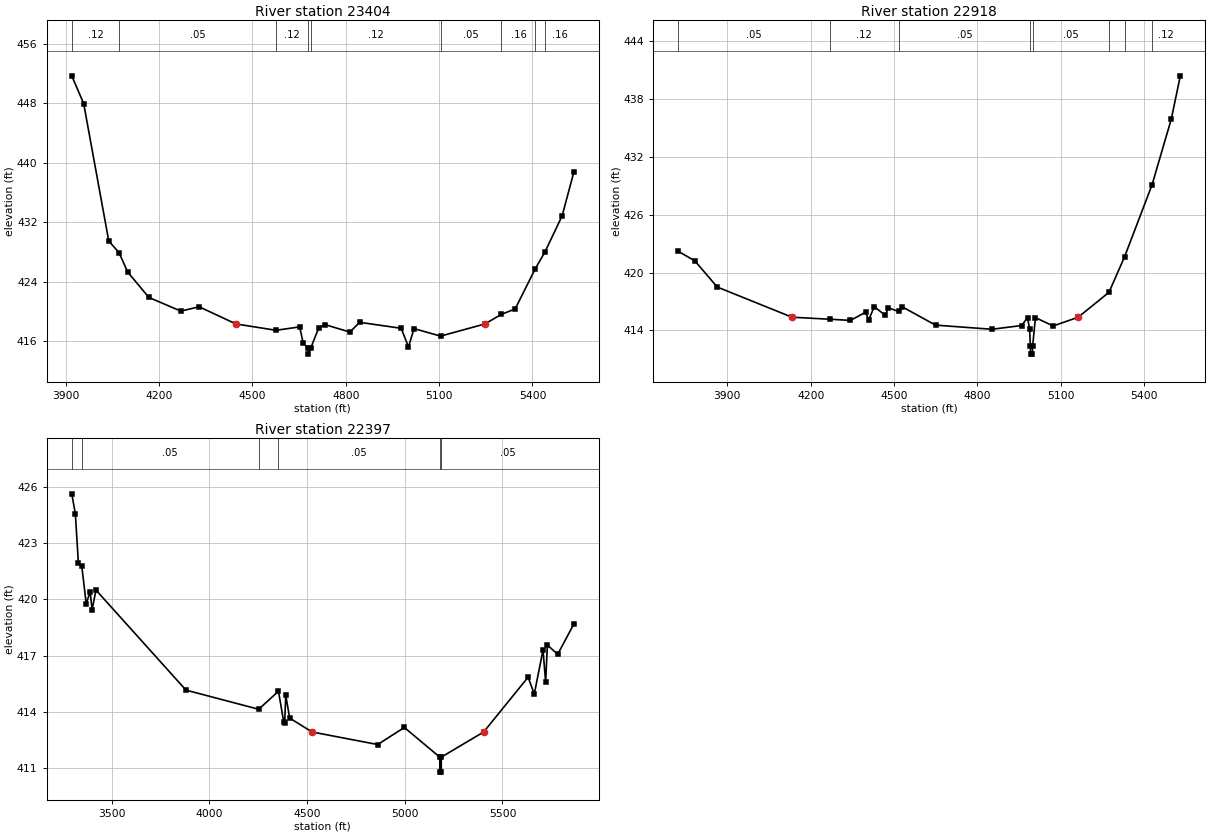
Type RM Length L Ch R = 1,23404,486,486,486
BEGIN DESCRIPTION:
XS3976A
END DESCRIPTION:
XS GIS Cut Line= 3
      2801247.02      7029130.97      2802292.99      7029000.77
      2802805.13      7028775.08
#Sta/Elev= 30
  3919.3  451.66  3957.6  447.93  4038.2  429.47  4071.1  427.92  4098.7  425.33
  4167.1  421.89  4270.0  420.06  4328.7  420.64  4447.1  418.33  4576.1  417.48
  4651.8  417.94  4663.0  415.78  4679.1  415.08  4679.8  414.28  4687.2  415.08
  4713.4  417.83  4732.6  418.25  4813.4  417.24  4844.4  418.55  4978.1  417.75
  5001.5  415.24  5019.3  417.71  5104.7  416.70  5246.9  418.33  5300.1  419.62
  5344.4  420.35  5409.4  425.77  5440.6  428.04  5495.3  432.85  5533.0  438.72
#Mann=9,-1,0
  3919.3    0.12       0  4071.1    0.05       0  4576.1    0.12       0
  4679.1    0.07       0  4687.2    0.12       0  5104.7    0.05       0
  5300.1    0.16       0  5409.4    0.12       0  5440.6    0.16       0
Bank Sta=4447.1,5246.9
Exp/Cntr=0.3,0.1

Type RM Length L Ch R = 1,22918,521,521,521
BEGIN DESCRIPTION:
UNT 167 in LFCCL Watershed 22.0
END DESCRIPTION:
XS GIS Cut Line= 3
      2801375.79      7029489.77      2802535.42      7029339.06
      2802954.45      7028859.27
#Sta/Elev= 30
  3723.6  422.21  3783.3  421.22  3864.0  418.50  4133.3  415.37  4269.4  415.16
  4342.8  415.04  4398.4  415.89  4408.5  415.06  4428.7  416.46  4469.0  415.56
  4479.1  416.34  4516.2  415.98  4529.5  416.45  4649.2  414.55  4852.2  414.12
  4959.4  414.51  4980.3  415.34  4987.9  414.13  4990.5  412.34  4991.2  411.54
  4997.9  411.54  4998.6  412.34  5008.8  415.33  5072.4  414.46  5162.5  415.37
  5273.5  417.96  5329.3  421.63  5428.3  429.11  5497.7  435.95  5530.0  440.42
#Mann=8,-1,0
  3723.6    0.05       0  4269.4    0.12       0  4516.2    0.05       0
  4990.5    0.03       0  4998.6    0.05       0  5273.5    0.12       0
  5329.3    0.16       0  5428.3    0.12       0
Bank Sta=4133.3,5162.5
Exp/Cntr=0.3,0.1

Type RM Length L Ch R = 1,22397,0,0,0
BEGIN DESCRIPTION:
XS3975A
END DESCRIPTION:
XS GIS Cut Line= 3
      2801121.14      7029669.18      2802700.98      7029742.96
      2803586.44      7029304.57
#Sta/Elev= 30
  3295.6  425.62  3313.9  424.56  3329.5  421.92  3346.5  421.80  3369.5  419.77
  3389.6  420.40  3399.6  419.45  3419.6  420.49  3880.1  415.16  4252.3  414.14
  4353.5  415.10  4380.3  413.47  4385.3  413.43  4390.7  414.89  4410.7  413.67
  4525.3  412.93  4861.2  412.26  4997.7  413.17  5178.9  411.59  5179.6  410.79
  5186.3  410.79  5187.0  411.59  5403.7  412.93  5631.2  415.85  5662.7  414.95
  5707.4  417.30  5720.9  415.58  5729.7  417.56  5782.6  417.07  5865.2  418.68
#Mann=6,-1,0
  3295.6    0.16       0  3346.5    0.05       0  4252.3    0.12       0
  4353.5    0.05       0  5178.9    0.03       0  5187.0    0.05       0
Bank Sta=4525.3,5403.7
Exp/Cntr=0.3,0.1

Chan Stop Cuts=-1