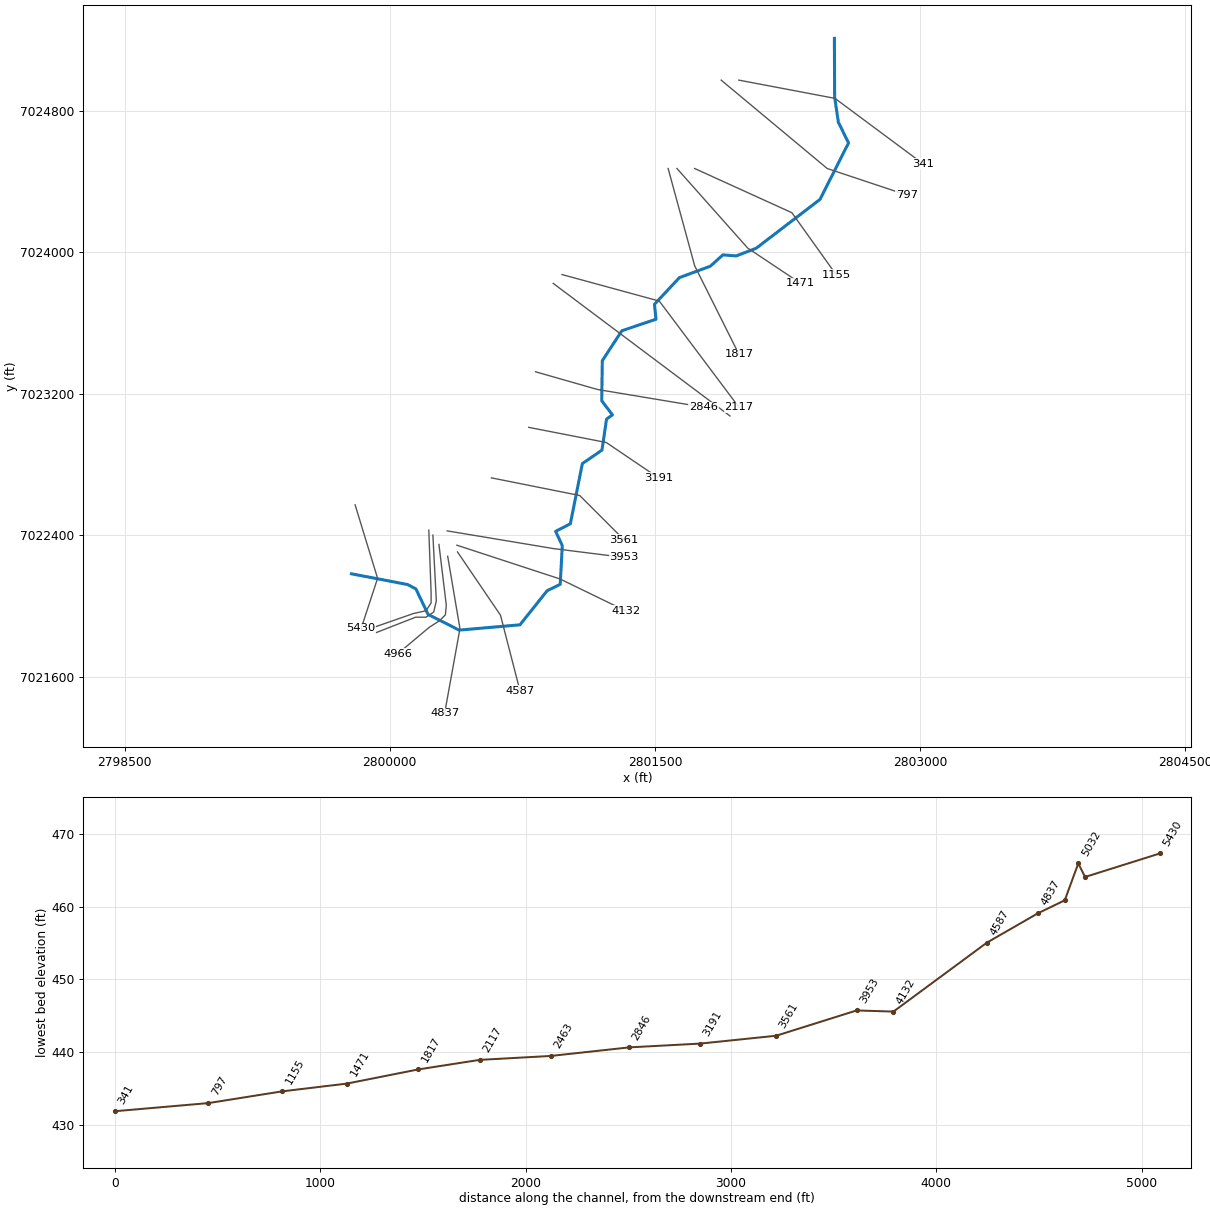
--- UNT 168 in LFCCL Watershed.prj (project) ---

Proj Title=UNT 168 in LFCCL Watershed Base Level Engineering
Current Plan=p01
Default Exp/Contr=0.3,0.1
English Units
Geom File=g01
Flow File=f01
Plan File=p01
BEGIN DESCRIPTION:
UNT 168 in LFCCL Watershed
END DESCRIPTION:

--- UNT 168 in LFCCL Watershed.p01 (plan) ---

Plan Title=Multiple Run
Short Identifier=Multiple
Geom File=g01
Flow File=f01
Subcritical Flow
K Sum by GR= 0
Std Step Tol= 0.01
Critical Tol= 0.01
Num of Std Step Trials= 20
Max Error Tol= 0.3
Flow Tol Ratio= 0.001
Split Flow NTrial= 30
Split Flow Tol= 0.02
Split Flow Ratio= 0.02
Log Output Level= 0
Friction Slope Method= 1
Unsteady Friction Slope Method= 2
Unsteady Bridges Friction Slope Method= 1
Parabolic Critical Depth
Global Vel Dist=  1 , 1 , 1
Global Log Level= 0
CheckData=True
Encroach Param= -1, 0, 0, 0
BEGIN DESCRIPTION:
Multiple Run
END DESCRIPTION:

--- UNT 168 in LFCCL Watershed.f01 (steady flow) ---

Flow Title=Multiple
Number of Profiles=7
Profile Names=10-year,25-year,50-year,1pct_min,100-year,1pct_plu,500-year
River Rch & RM= UNT 168 in LFCCL,Reach-1,5430
     618     834    1012     611    1219    2432    1770
Boundary for River Rch & Prof#=UNT 168 in LFCCL,Reach-1,1
Up Type=0
Dn Type=3
Dn Slope=0.005
Boundary for River Rch & Prof#=UNT 168 in LFCCL,Reach-1,2
Up Type=0
Dn Type=3
Dn Slope=0.005
Boundary for River Rch & Prof#=UNT 168 in LFCCL,Reach-1,3
Up Type=0
Dn Type=3
Dn Slope=0.005
Boundary for River Rch & Prof#=UNT 168 in LFCCL,Reach-1,4
Up Type=0
Dn Type=3
Dn Slope=0.005
Boundary for River Rch & Prof#=UNT 168 in LFCCL,Reach-1,5
Up Type=0
Dn Type=3
Dn Slope=0.005
Boundary for River Rch & Prof#=UNT 168 in LFCCL,Reach-1,6
Up Type=0
Dn Type=3
Dn Slope=0.005
Boundary for River Rch & Prof#=UNT 168 in LFCCL,Reach-1,7
Up Type=0
Dn Type=3
Dn Slope=0.005

--- UNT 168 in LFCCL Watershed.g01 (geometry) ---

Geom Title=Existing Conditions

River Reach=UNT 168 in LFCCL,Reach-1
Reach XY= 30
      2799783.51      7022182.19      2800101.21      7022121.43
      2800148.09      7022096.69      2800217.10      7021952.16
      2800392.88      7021863.61      2800736.63      7021893.56
      2800890.28      7022086.27      2800964.50      7022122.73
      2800976.21      7022341.48      2800938.45      7022422.21
      2801021.79      7022465.18      2801089.50      7022805.45
      2801200.61      7022881.84      2801226.65      7023057.19
      2801259.63      7023081.50      2801199.30      7023161.14
      2801202.56      7023387.92      2801313.24      7023557.19
      2801506.38      7023622.29      2801497.70      7023706.93
      2801638.76      7023857.75      2801813.45      7023922.21
      2801885.07      7023986.44      2801959.72      7023980.37
      2802073.00      7024023.77      2802434.30      7024300.31
      2802595.69      7024619.68      2802537.91      7024736.67
      2802516.87      7024880.94      2802515.62      7025211.42

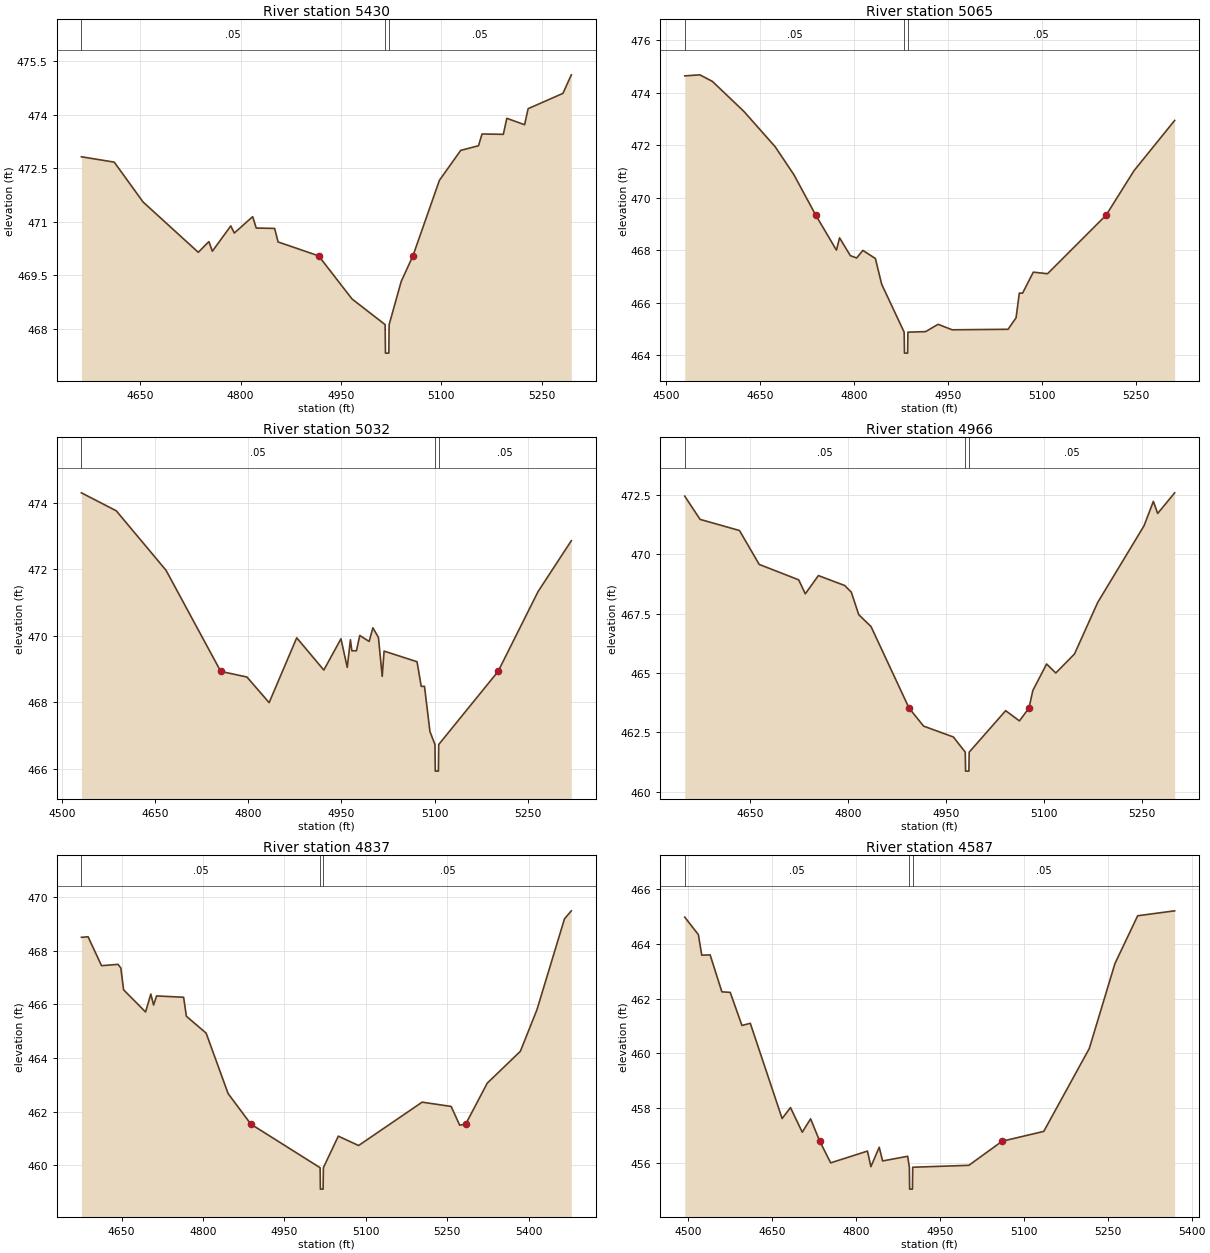
Type RM Length L Ch R = 1,5430,365,365,365
BEGIN DESCRIPTION:
UNT 168 in LFCCL Watershed 12.0
END DESCRIPTION:
XS GIS Cut Line= 3
      2799804.17      7022572.13      2799931.26      7022156.65
      2799838.39      7021873.16
#Sta/Elev= 30
  4561.8  472.82  4610.9  472.67  4654.1  471.55  4736.6  470.14  4752.5  470.44
  4757.7  470.17  4785.2  470.88  4790.5  470.68  4818.0  471.14  4823.3  470.82
  4850.8  470.81  4856.0  470.43  4916.6  470.04  4966.6  468.83  5016.1  468.11
  5016.6  467.31  5021.6  467.31  5022.1  468.11  5040.1  469.32  5057.7  470.04
  5097.3  472.16  5129.2  473.00  5155.8  473.13  5161.0  473.46  5192.9  473.45
  5198.1  473.90  5224.7  473.72  5230.0  474.17  5282.1  474.60  5294.6  475.12
#Mann=3,-1,0
  4561.8    0.05       0  5016.1    0.03       0  5022.1    0.05       0
Bank Sta=4916.6,5057.7
Exp/Cntr=0.3,0.1

Type RM Length L Ch R = 1,5065,33,33,33
BEGIN DESCRIPTION:
XS3978A
END DESCRIPTION:
XS GIS Cut Line= 6
      2800221.07      7022429.12      2800234.09      7022072.32
      2800234.09      7022017.63      2800205.44      7021973.36
      2800135.13      7021957.73      2799903.38      7021877.01
#Sta/Elev= 30
  4529.5  474.65  4553.6  474.69  4573.6  474.44  4623.7  473.30  4673.7  471.95
  4703.7  470.88  4738.5  469.34  4771.6  468.00  4776.6  468.47  4793.8  467.79
  4803.8  467.70  4813.8  467.99  4833.8  467.68  4843.8  466.70  4879.7  464.87
  4880.2  464.07  4885.2  464.07  4885.7  464.87  4913.9  464.89  4933.9  465.17
  4956.3  464.96  5045.6  464.98  5058.3  465.42  5063.5  466.36  5068.7  466.36
  5085.8  467.16  5108.5  467.10  5202.2  469.34  5246.5  471.03  5311.4  472.95
#Mann=3,-1,0
  4529.5    0.05       0  4879.7    0.03       0  4885.7    0.05       0
Bank Sta=4738.5,5202.2
Exp/Cntr=0.3,0.1

Type RM Length L Ch R = 1,5032,66,66,66
BEGIN DESCRIPTION:
XS3977A
END DESCRIPTION:
XS GIS Cut Line= 6
      2800244.09      7022401.03      2800263.64      7022029.56
      2800248.98      7021966.02      2800204.99      7021936.69
      2800146.33      7021936.69      2799923.14      7021849.35
#Sta/Elev= 30
  4531.5  474.30  4587.6  473.76  4667.7  471.97  4755.7  468.93  4797.9  468.76
  4833.6  467.99  4878.0  469.94  4921.6  468.97  4949.2  469.91  4959.3  469.05
  4964.4  469.88  4966.7  469.55  4974.1  469.55  4979.5  470.01  4994.5  469.83
  5000.6  470.24  5009.5  469.95  5015.6  468.78  5018.6  469.54  5071.6  469.22
  5078.4  468.48  5083.6  468.48  5092.4  467.12  5100.5  466.73  5101.0  465.93
  5106.0  465.93  5106.5  466.73  5202.1  468.93  5266.4  471.33  5319.9  472.86
#Mann=3,-1,0
  4531.5    0.05       0  5100.5    0.03       0  5106.5    0.05       0
Bank Sta=4755.7,5202.1
Exp/Cntr=0.3,0.1

Type RM Length L Ch R = 1,4966,129,129,129
BEGIN DESCRIPTION:
XS3979A
END DESCRIPTION:
XS GIS Cut Line= 6
      2800278.37      7022348.32      2800320.03      7022004.61
      2800314.82      7021949.92      2800280.97      7021916.07
      2800223.67      7021879.61      2800044.82      7021729.26
#Sta/Elev= 30
  4549.7  472.46  4573.2  471.48  4633.6  471.01  4663.8  469.58  4724.3  468.93
  4734.4  468.34  4754.5  469.11  4794.8  468.69  4804.9  468.41  4816.3  467.46
  4835.1  466.96  4893.4  463.52  4915.6  462.76  4961.3  462.30  4979.5  461.66
  4980.0  460.86  4985.0  460.86  4985.5  461.66  5041.4  463.41  5062.5  462.98
  5077.1  463.52  5083.0  464.26  5104.1  465.38  5118.2  465.00  5146.8  465.80
  5182.5  467.98  5253.4  471.21  5267.7  472.24  5274.3  471.73  5300.3  472.60
#Mann=3,-1,0
  4549.7    0.05       0  4979.5    0.03       0  4985.5    0.05       0
Bank Sta=4893.4,5077.1
Exp/Cntr=0.3,0.1

Type RM Length L Ch R = 1,4837,250,250,250
BEGIN DESCRIPTION:
XS3980A
END DESCRIPTION:
XS GIS Cut Line= 3
      2800327.84      7022281.54      2800397.28      7021871.79
      2800310.47      7021392.58
#Sta/Elev= 30
  4576.1  468.51  4588.4  468.53  4613.2  467.45  4643.6  467.50  4648.8  467.36
  4653.8  466.55  4694.3  465.72  4704.0  466.39  4709.1  465.98  4714.6  466.32
  4764.4  466.27  4769.5  465.56  4805.9  464.93  4846.4  462.67  4888.3  461.53
  5015.9  459.90  5016.4  459.10  5021.4  459.10  5021.9  459.90  5049.4  461.08
  5086.8  460.73  5203.9  462.35  5257.3  462.19  5273.0  461.49  5284.1  461.53
  5323.8  463.06  5384.8  464.25  5415.3  465.80  5466.1  469.20  5478.7  469.50
#Mann=3,-1,0
  4576.1    0.05       0  5015.9    0.03       0  5021.9    0.05       0
Bank Sta=4888.3,5284.1
Exp/Cntr=0.3,0.1

Type RM Length L Ch R = 1,4587,455,455,455
BEGIN DESCRIPTION:
XS3981A
END DESCRIPTION:
XS GIS Cut Line= 3
      2800383.37      7022305.86      2800626.45      7021948.18
      2800737.26      7021518.81
#Sta/Elev= 30
  4493.7  464.98  4518.1  464.34  4524.1  463.59  4539.1  463.60  4560.1  462.25
  4575.0  462.23  4596.0  461.02  4610.9  461.10  4667.8  457.62  4682.8  458.02
  4703.8  457.12  4718.7  457.61  4735.1  456.79  4754.6  456.00  4820.4  456.43
  4826.5  455.86  4841.4  456.57  4847.5  456.07  4892.3  456.24  4895.3  455.84
  4895.8  455.04  4900.8  455.04  4901.3  455.84  5001.7  455.91  5061.1  456.79
  5135.6  457.15  5217.0  460.18  5262.8  463.28  5303.5  465.03  5369.6  465.21
#Mann=3,-1,0
  4493.7    0.05       0  4895.3    0.03       0  4901.3    0.05       0
Bank Sta=4735.1,5061.1
Exp/Cntr=0.3,0.1

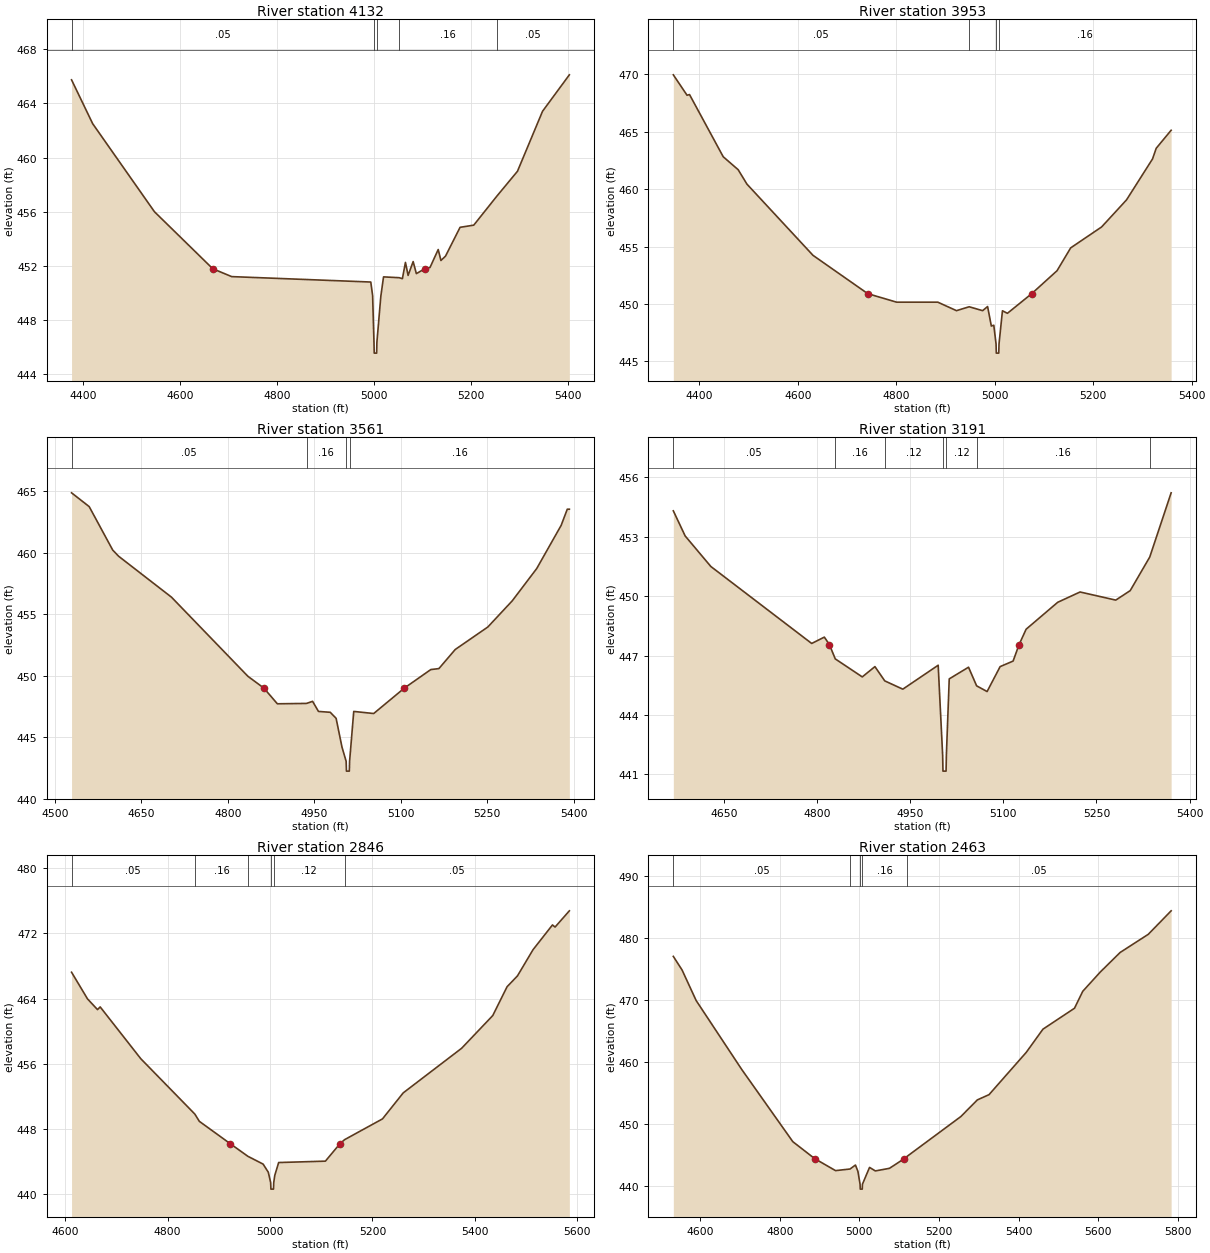
Type RM Length L Ch R = 1,4132,179,179,179
BEGIN DESCRIPTION:
XS3982A
END DESCRIPTION:
XS GIS Cut Line= 3
      2800379.97      7022344.00      2800963.26      7022153.04
      2801334.76      7021972.50
#Sta/Elev= 30
  4375.4  465.74  4419.0  462.50  4546.4  456.00  4666.7  451.79  4705.7  451.21
  4992.6  450.81  4996.4  449.81  4999.2  446.36  4999.7  445.56  5004.7  445.56
  5005.2  446.36  5013.3  449.75  5018.9  451.19  5051.1  451.13  5057.8  451.06
  5064.1  452.26  5069.6  451.30  5080.0  452.32  5086.6  451.43  5104.0  451.79
  5114.7  451.88  5131.7  453.21  5137.3  452.40  5146.7  452.72  5176.8  454.85
  5205.0  455.01  5252.6  457.15  5295.2  458.99  5346.9  463.42  5402.2  466.11
#Mann=5,-1,0
  4375.4    0.05       0  4999.2    0.03       0  5005.2    0.05       0
  5051.1    0.16       0  5252.6    0.05       0
Bank Sta=4666.7,5104
Exp/Cntr=0.3,0.1

Type RM Length L Ch R = 1,3953,392,392,392
BEGIN DESCRIPTION:
UNT 168 in LFCCL Watershed 11.0
END DESCRIPTION:
XS GIS Cut Line= 3
      2800325.01      7022425.00      2800925.00      7022325.00
      2801325.02      7022275.00
#Sta/Elev= 30
  4346.9  469.97  4374.8  468.19  4379.8  468.25  4448.3  462.83  4478.7  461.70
  4496.4  460.45  4630.7  454.24  4742.0  450.90  4800.6  450.16  4884.2  450.16
  4922.2  449.42  4948.0  449.76  4975.3  449.42  4985.4  449.78  4993.0  448.08
  4998.0  448.15  5002.6  446.52  5003.1  445.72  5008.1  445.72  5008.6  446.52
  5015.6  449.41  5025.7  449.19  5075.0  450.90  5126.5  452.90  5154.2  454.89
  5217.2  456.72  5267.6  459.07  5320.5  462.64  5328.0  463.57  5358.3  465.14
#Mann=4,-1,0
  4346.9    0.05       0  4948.0    0.16       0  5002.6    0.07       0
  5008.6    0.16       0
Bank Sta=4742,5075
Exp/Cntr=0.3,0.1

Type RM Length L Ch R = 1,3561,370,370,370
BEGIN DESCRIPTION:
UNT 168 in LFCCL Watershed 10.0
END DESCRIPTION:
XS GIS Cut Line= 3
      2800574.97      7022725.01      2801075.00      7022625.00
      2801325.01      7022374.99
#Sta/Elev= 30
  4528.8  464.85  4559.4  463.73  4600.2  460.20  4610.4  459.70  4702.2  456.37
  4834.8  449.94  4862.3  448.99  4885.8  447.71  4936.4  447.74  4946.9  447.91
  4957.1  447.09  4977.5  447.02  4987.7  446.53  4997.9  444.19  5005.1  443.04
  5005.6  442.24  5010.6  442.24  5011.1  443.04  5018.3  447.09  5052.9  446.92
  5106.2  448.99  5151.9  450.49  5166.0  450.57  5194.3  452.12  5250.9  453.95
  5293.3  456.08  5335.7  458.70  5378.1  462.21  5388.7  463.52  5392.3  463.52
#Mann=4,-1,0
  4528.8    0.05       0  4936.4    0.16       0  5005.1    0.07       0
  5011.1    0.16       0
Bank Sta=4862.3,5106.2
Exp/Cntr=0.3,0.1

Type RM Length L Ch R = 1,3191,345,345,345
BEGIN DESCRIPTION:
UNT 168 in LFCCL Watershed 9.0
END DESCRIPTION:
XS GIS Cut Line= 3
      2800786.21      7023010.68      2801225.00      7022925.00
      2801518.84      7022725.94
#Sta/Elev= 30
  4568.3  454.31  4587.4  453.04  4628.7  451.50  4791.2  447.61  4811.6  447.93
  4819.8  447.55  4829.2  446.83  4872.7  445.92  4893.1  446.44  4908.9  445.72
  4938.0  445.30  4995.0  446.51  5002.2  441.96  5002.7  441.16  5007.7  441.16
  5008.2  441.96  5012.8  445.82  5043.9  446.41  5056.9  445.47  5073.8  445.18
  5094.8  446.44  5115.7  446.72  5125.3  447.55  5136.7  448.33  5187.6  449.69
  5223.6  450.21  5281.1  449.80  5304.4  450.28  5335.9  451.98  5370.3  455.22
#Mann=7,-1,0
  4568.3    0.05       0  4829.2    0.16       0  4908.9    0.12       0
  5002.2    0.07       0  5008.2    0.12       0  5056.9    0.16       0
  5335.9    0.05       0
Bank Sta=4819.8,5125.3
Exp/Cntr=0.3,0.1

Type RM Length L Ch R = 1,2846,383,383,383
BEGIN DESCRIPTION:
UNT 168 in LFCCL Watershed 8.0
END DESCRIPTION:
XS GIS Cut Line= 3
      2800825.02      7023324.99      2801175.00      7023225.00
      2801775.04      7023124.99
#Sta/Elev= 30
  4612.4  467.23  4643.6  463.96  4663.1  462.65  4668.3  462.98  4747.6  456.63
  4853.2  449.84  4862.0  448.95  4922.8  446.19  4956.9  444.66  4986.5  443.71
  4996.7  442.71  5001.3  441.44  5001.8  440.64  5006.8  440.64  5007.3  441.44
  5009.3  442.32  5016.9  443.90  5108.2  444.07  5136.4  446.19  5145.6  446.70
  5219.7  449.25  5260.2  452.44  5374.3  457.91  5435.1  461.92  5463.0  465.45
  5483.3  466.78  5513.7  469.99  5551.7  473.03  5556.8  472.77  5584.7  474.76
#Mann=6,-1,0
  4612.4    0.05       0  4853.2    0.16       0  4956.9    0.12       0
  5001.3    0.07       0  5007.3    0.12       0  5145.6    0.05       0
Bank Sta=4922.8,5136.4
Exp/Cntr=0.3,0.1

Type RM Length L Ch R = 1,2463,346,346,346
BEGIN DESCRIPTION:
UNT 168 in LFCCL Watershed 7.0
END DESCRIPTION:
XS GIS Cut Line= 3
      2800925.02      7023824.99      2801325.00      7023525.00
      2801925.02      7023074.99
#Sta/Elev= 30
  4532.9  477.06  4554.8  474.87  4590.2  469.93  4704.8  458.78  4832.9  447.13
  4887.8  444.39  4940.2  442.45  4976.7  442.71  4990.2  443.35  4996.4  442.33
  5001.8  440.26  5002.3  439.46  5007.3  439.46  5007.8  440.26  5025.6  442.97
  5040.2  442.40  5075.6  442.82  5113.0  444.39  5119.2  444.72  5254.8  451.18
  5296.4  453.88  5325.6  454.72  5419.3  461.57  5461.0  465.30  5540.2  468.68
  5561.0  471.42  5604.8  474.52  5654.8  477.69  5725.6  480.63  5782.9  484.42
#Mann=5,-1,0
  4532.9    0.05       0  4976.7    0.16       0  5001.8    0.07       0
  5007.8    0.16       0  5119.2    0.05       0
Bank Sta=4887.8,5113
Exp/Cntr=0.3,0.1

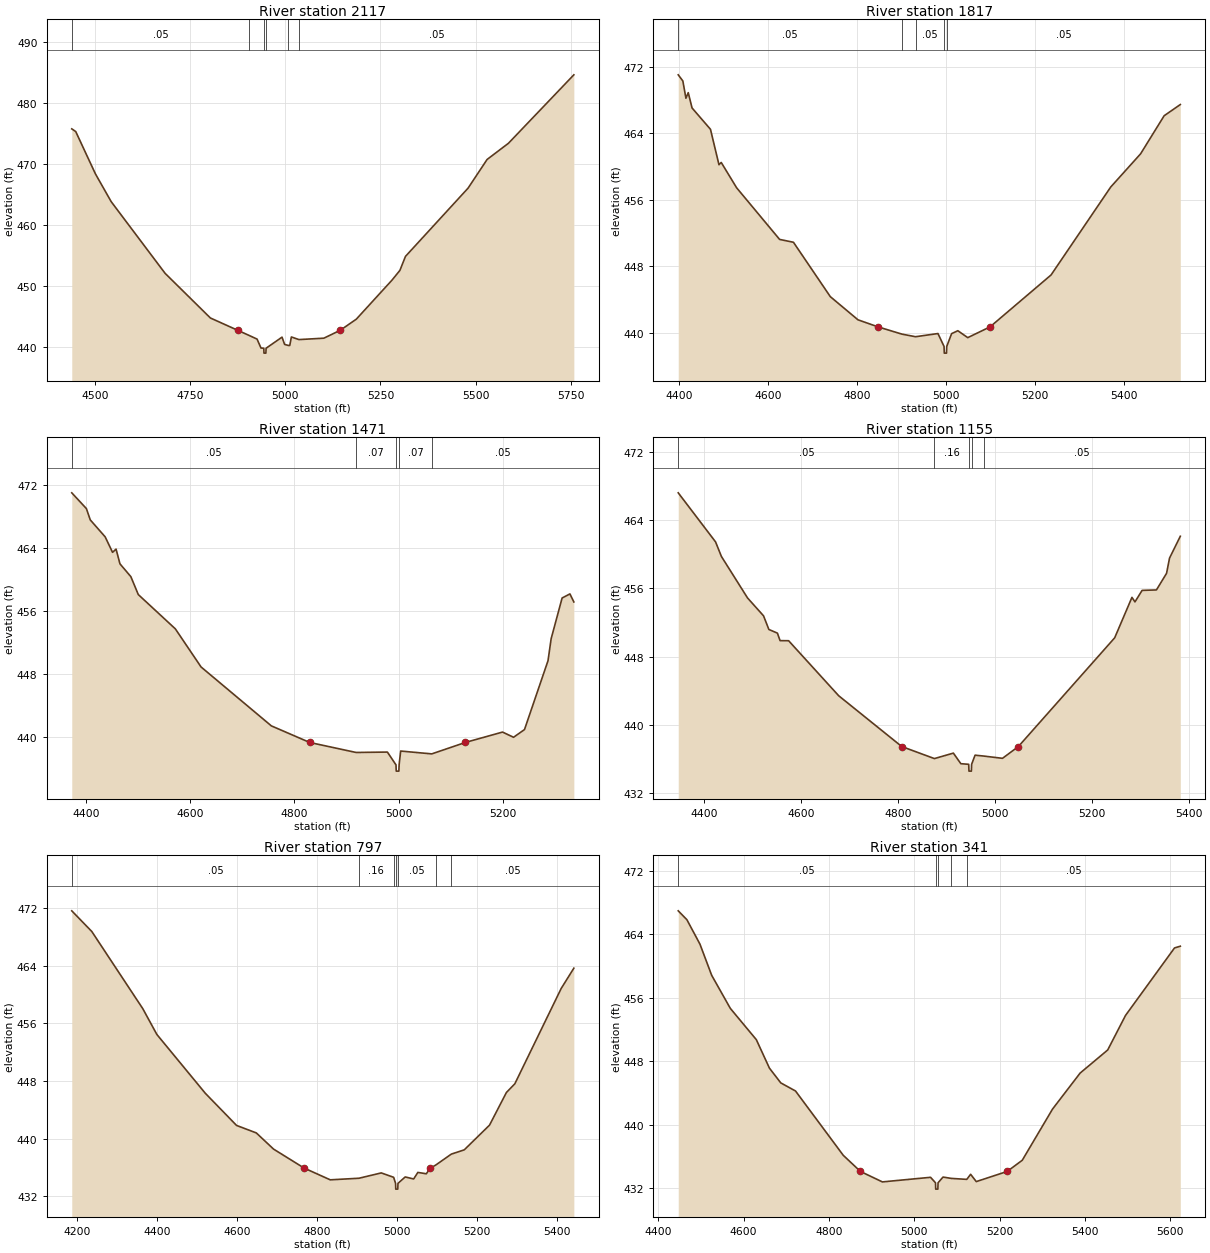
Type RM Length L Ch R = 1,2117,300,300,300
BEGIN DESCRIPTION:
UNT 168 in LFCCL Watershed 6.0
END DESCRIPTION:
XS GIS Cut Line= 3
      2800974.99      7023875.00      2801525.00      7023725.00
      2801975.00      7023125.00
#Sta/Elev= 30
  4438.3  475.69  4448.7  475.25  4500.5  468.31  4542.0  463.75  4683.6  452.01
  4802.8  444.68  4874.8  442.66  4904.6  441.82  4925.5  441.22  4935.8  439.76
  4943.2  439.72  4943.7  438.92  4948.7  438.92  4949.2  439.72  4991.1  441.54
  4998.0  440.34  5008.0  440.18  5011.5  440.18  5015.7  441.57  5035.6  441.14
  5101.1  441.37  5144.1  442.66  5186.5  444.49  5280.3  450.89  5301.1  452.49
  5315.7  454.78  5480.3  465.97  5530.3  470.67  5586.5  473.33  5758.4  484.55
#Mann=6,-1,0
  4438.3    0.05       0  4904.6    0.16       0  4943.2    0.07       0
  4949.2    0.16       0  5008.0     0.1       0  5035.6    0.05       0
Bank Sta=4874.8,5144.1
Exp/Cntr=0.3,0.1

Type RM Length L Ch R = 1,1817,346,346,346
BEGIN DESCRIPTION:
UNT 168 in LFCCL Watershed 5.0
END DESCRIPTION:
XS GIS Cut Line= 3
      2801575.00      7024474.99      2801725.00      7023925.00
      2801975.00      7023425.00
#Sta/Elev= 30
  4398.3  471.01  4408.7  470.27  4415.6  468.20  4420.8  468.87  4429.4  467.03
  4470.8  464.47  4489.9  460.22  4495.0  460.49  4529.6  457.45  4626.3  451.25
  4657.4  450.91  4740.3  444.38  4802.5  441.60  4847.8  440.75  4901.5  439.88
  4931.9  439.57  4982.4  439.95  4996.1  438.40  4996.6  437.60  5001.6  437.60
  5002.1  438.40  5013.1  439.94  5027.1  440.29  5049.4  439.46  5099.5  440.75
  5236.7  446.98  5370.9  457.54  5438.0  461.52  5491.1  466.10  5527.4  467.44
#Mann=5,-1,0
  4398.3    0.05       0  4901.5    0.07       0  4931.9    0.05       0
  4996.1    0.03       0  5002.1    0.05       0
Bank Sta=4847.8,5099.5
Exp/Cntr=0.3,0.1

Type RM Length L Ch R = 1,1471,316,316,316
BEGIN DESCRIPTION:
UNT 168 in LFCCL Watershed 4.0
END DESCRIPTION:
XS GIS Cut Line= 3
      2801625.00      7024475.01      2802025.00      7024025.00
      2802324.96      7023825.02
#Sta/Elev= 30
  4373.3  471.01  4401.3  469.01  4408.8  467.57  4437.3  465.42  4451.5  463.45
  4458.2  463.86  4465.7  461.99  4486.6  460.36  4500.8  458.09  4571.9  453.73
  4621.2  448.89  4755.9  441.41  4829.5  439.30  4918.4  438.03  4978.4  438.08
  4994.9  436.46  4995.4  435.66  5000.4  435.66  5000.9  436.46  5003.9  438.21
  5063.5  437.85  5127.8  439.30  5199.2  440.62  5220.3  439.96  5241.3  440.94
  5286.4  449.69  5292.4  452.48  5313.4  457.65  5328.4  458.17  5335.9  457.15
#Mann=5,-1,0
  4373.3    0.05       0  4918.4    0.07       0  4994.9    0.07       0
  5000.9    0.07       0  5063.5    0.05       0
Bank Sta=4829.5,5127.8
Exp/Cntr=0.3,0.1

Type RM Length L Ch R = 1,1155,358,358,358
BEGIN DESCRIPTION:
UNT 168 in LFCCL Watershed 3.0
END DESCRIPTION:
XS GIS Cut Line= 3
      2801725.01      7024475.00      2802275.00      7024225.00
      2802525.02      7023874.97
#Sta/Elev= 30
  4347.5  467.20  4424.4  461.45  4436.5  459.74  4490.3  454.88  4523.2  452.79
  4534.2  451.19  4551.8  450.76  4557.3  449.88  4574.9  449.87  4678.1  443.42
  4808.0  437.47  4875.2  436.06  4914.3  436.70  4929.7  435.46  4945.9  435.39
  4946.4  434.59  4951.4  434.59  4951.9  435.39  4959.0  436.46  4977.6  436.35
  5015.5  436.09  5048.2  437.47  5246.6  450.21  5282.2  454.95  5288.4  454.42
  5303.1  455.77  5332.6  455.82  5353.5  457.77  5359.6  459.55  5381.8  462.11
#Mann=5,-1,0
  4347.5    0.05       0  4875.2    0.16       0  4945.9    0.03       0
  4951.9    0.16       0  4977.6    0.05       0
Bank Sta=4808,5048.2
Exp/Cntr=0.3,0.1

Type RM Length L Ch R = 1,797,456,456,456
BEGIN DESCRIPTION:
UNT 168 in LFCCL Watershed 2.0
END DESCRIPTION:
XS GIS Cut Line= 3
      2801875.02      7024974.98      2802475.00      7024475.00
      2802924.96      7024325.01
#Sta/Elev= 30
  4186.9  471.60  4237.0  468.73  4364.6  458.01  4399.7  454.44  4520.8  446.28
  4598.9  441.82  4648.3  440.78  4691.3  438.54  4767.9  435.90  4833.2  434.27
  4904.9  434.49  4960.7  435.23  4991.7  434.62  4996.5  433.78  4997.0  432.98
  5002.0  432.98  5002.5  433.78  5020.6  434.67  5041.7  434.39  5052.2  435.30
  5073.3  435.11  5083.4  435.90  5096.9  436.32  5135.9  437.84  5168.2  438.43
  5231.4  441.86  5273.6  446.39  5294.7  447.60  5410.6  460.83  5442.2  463.64
#Mann=7,-1,0
  4186.9    0.05       0  4904.9    0.16       0  4991.7    0.05       0
  4996.5    0.03       0  5002.5    0.05       0  5096.9    0.16       0
  5135.9    0.05       0
Bank Sta=4767.9,5083.4
Exp/Cntr=0.3,0.1

Type RM Length L Ch R = 1,341,0,0,0
BEGIN DESCRIPTION:
UNT 168 in LFCCL Watershed 1.0
END DESCRIPTION:
XS GIS Cut Line= 3
      2801975.04      7024974.99      2802518.55      7024871.94
      2803018.80      7024500.28
#Sta/Elev= 30
  4446.8  466.94  4467.1  465.82  4497.7  462.74  4525.2  458.81  4568.9  454.64
  4629.8  450.70  4660.5  447.11  4687.1  445.25  4721.6  444.23  4833.5  436.12
  4873.7  434.09  4925.1  432.77  5038.0  433.35  5049.6  432.66  5050.1  431.86
  5055.1  431.86  5055.6  432.66  5067.2  433.38  5086.9  433.21  5122.9  433.09
  5131.9  433.73  5145.1  432.81  5217.6  434.09  5252.9  435.50  5323.8  441.95
  5388.5  446.49  5453.1  449.40  5494.8  453.75  5609.6  462.26  5623.2  462.48
#Mann=5,-1,0
  4446.8    0.05       0  5049.6    0.03       0  5055.6    0.05       0
  5086.9    0.16       0  5122.9    0.05       0
Bank Sta=4873.7,5217.6
Exp/Cntr=0.3,0.1

Chan Stop Cuts=-1