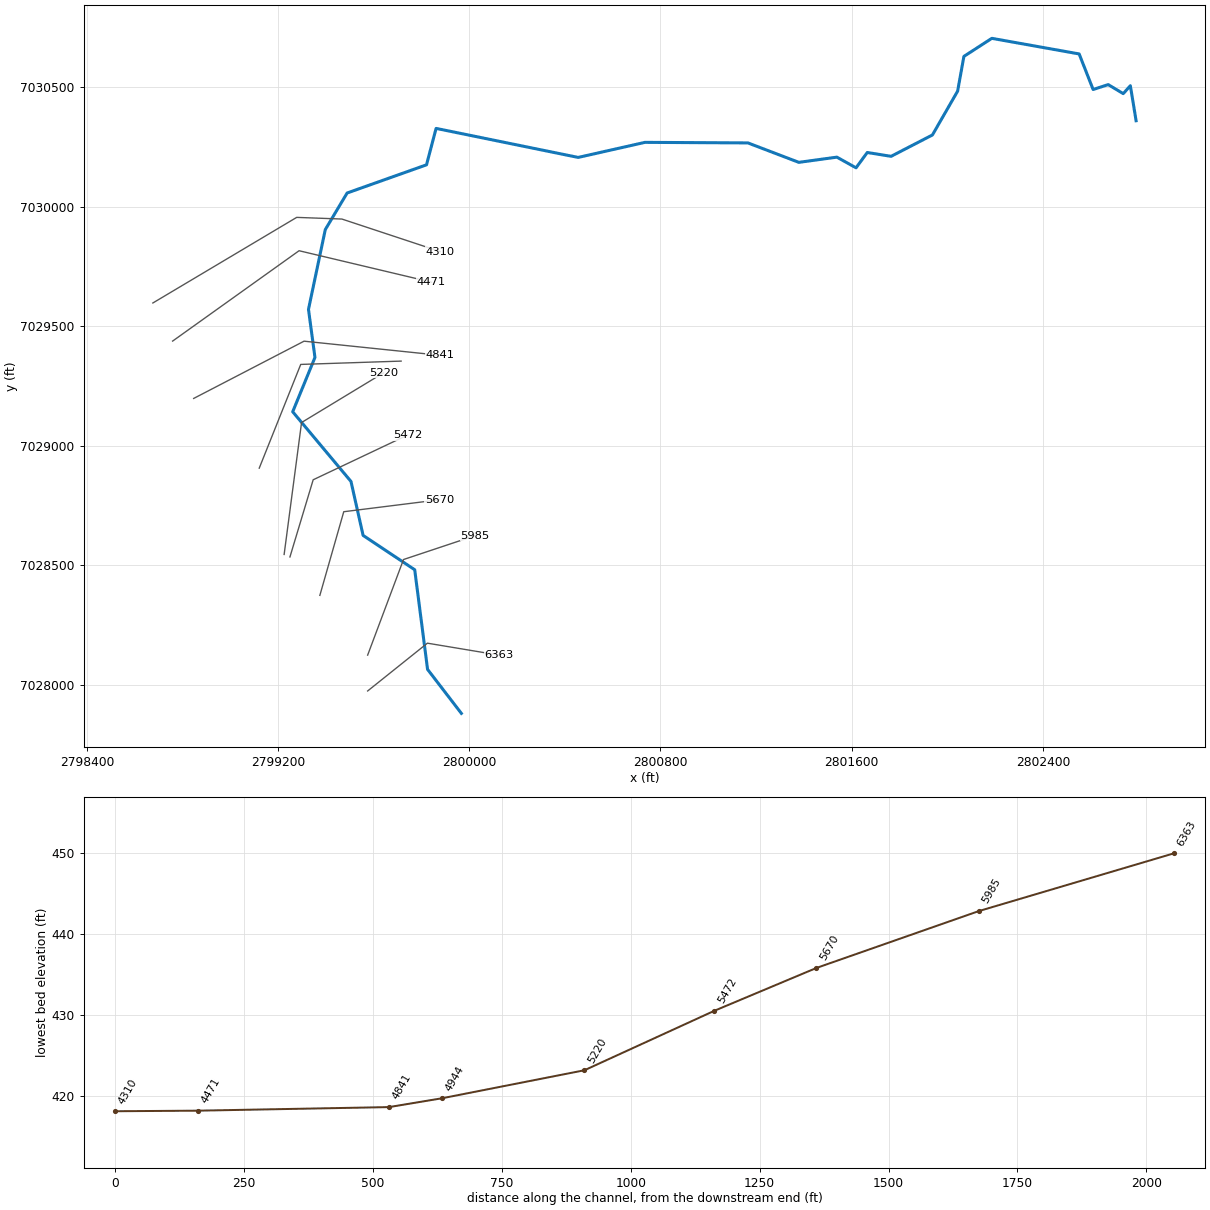
--- UNT 169 in LFCCL Watershed.prj (project) ---

Proj Title=UNT 169 in LFCCL Watershed Base Level Engineering
Current Plan=p01
Default Exp/Contr=0.3,0.1
English Units
Geom File=g01
Flow File=f01
Plan File=p01
BEGIN DESCRIPTION:
UNT 169 in LFCCL Watershed
END DESCRIPTION:

--- UNT 169 in LFCCL Watershed.p01 (plan) ---

Plan Title=Multiple Run
Short Identifier=Multiple
Geom File=g01
Flow File=f01
Subcritical Flow
K Sum by GR= 0
Std Step Tol= 0.01
Critical Tol= 0.01
Num of Std Step Trials= 20
Max Error Tol= 0.3
Flow Tol Ratio= 0.001
Split Flow NTrial= 30
Split Flow Tol= 0.02
Split Flow Ratio= 0.02
Log Output Level= 0
Friction Slope Method= 1
Unsteady Friction Slope Method= 2
Unsteady Bridges Friction Slope Method= 1
Parabolic Critical Depth
Global Vel Dist=  1 , 1 , 1
Global Log Level= 0
CheckData=True
Encroach Param= -1, 0, 0, 0
BEGIN DESCRIPTION:
Multiple Run
END DESCRIPTION:

--- UNT 169 in LFCCL Watershed.f01 (steady flow) ---

Flow Title=Multiple
Number of Profiles=7
Profile Names=10-year,25-year,50-year,1pct_min,100-year,1pct_plu,500-year
River Rch & RM= UNT 169 in LFCCL,Reach-1,6363
     578     776     936     562    1122    2239    1614
Boundary for River Rch & Prof#=UNT 169 in LFCCL,Reach-1,1
Up Type=0
Dn Type=3
Dn Slope=0.005
Boundary for River Rch & Prof#=UNT 169 in LFCCL,Reach-1,2
Up Type=0
Dn Type=3
Dn Slope=0.005
Boundary for River Rch & Prof#=UNT 169 in LFCCL,Reach-1,3
Up Type=0
Dn Type=3
Dn Slope=0.005
Boundary for River Rch & Prof#=UNT 169 in LFCCL,Reach-1,4
Up Type=0
Dn Type=3
Dn Slope=0.005
Boundary for River Rch & Prof#=UNT 169 in LFCCL,Reach-1,5
Up Type=0
Dn Type=3
Dn Slope=0.005
Boundary for River Rch & Prof#=UNT 169 in LFCCL,Reach-1,6
Up Type=0
Dn Type=3
Dn Slope=0.005
Boundary for River Rch & Prof#=UNT 169 in LFCCL,Reach-1,7
Up Type=0
Dn Type=3
Dn Slope=0.005

--- UNT 169 in LFCCL Watershed.g01 (geometry) ---

Geom Title=Existing Conditions

River Reach=UNT 169 in LFCCL,Reach-1
Reach XY= 30
      2799967.09      7027881.28      2799825.65      7028065.40
      2799771.92      7028482.15      2799555.95      7028625.90
      2799505.25      7028851.60      2799261.40      7029143.16
      2799354.50      7029370.53      2799327.43      7029571.67
      2799397.76      7029905.46      2799489.11      7030058.48
      2799821.27      7030176.45      2799861.36      7030328.79
      2800455.83      7030207.38      2800735.30      7030270.38
      2801165.97      7030268.09      2801379.02      7030186.76
      2801538.23      7030208.53      2801618.41      7030163.86
      2801665.37      7030228.00      2801765.02      7030211.96
      2801937.97      7030301.30      2802043.35      7030484.57
      2802069.70      7030630.03      2802186.53      7030705.63
      2802551.91      7030640.34      2802610.32      7030491.44
      2802673.32      7030512.06      2802736.32      7030474.26
      2802766.10      7030507.48      2802790.15      7030360.86

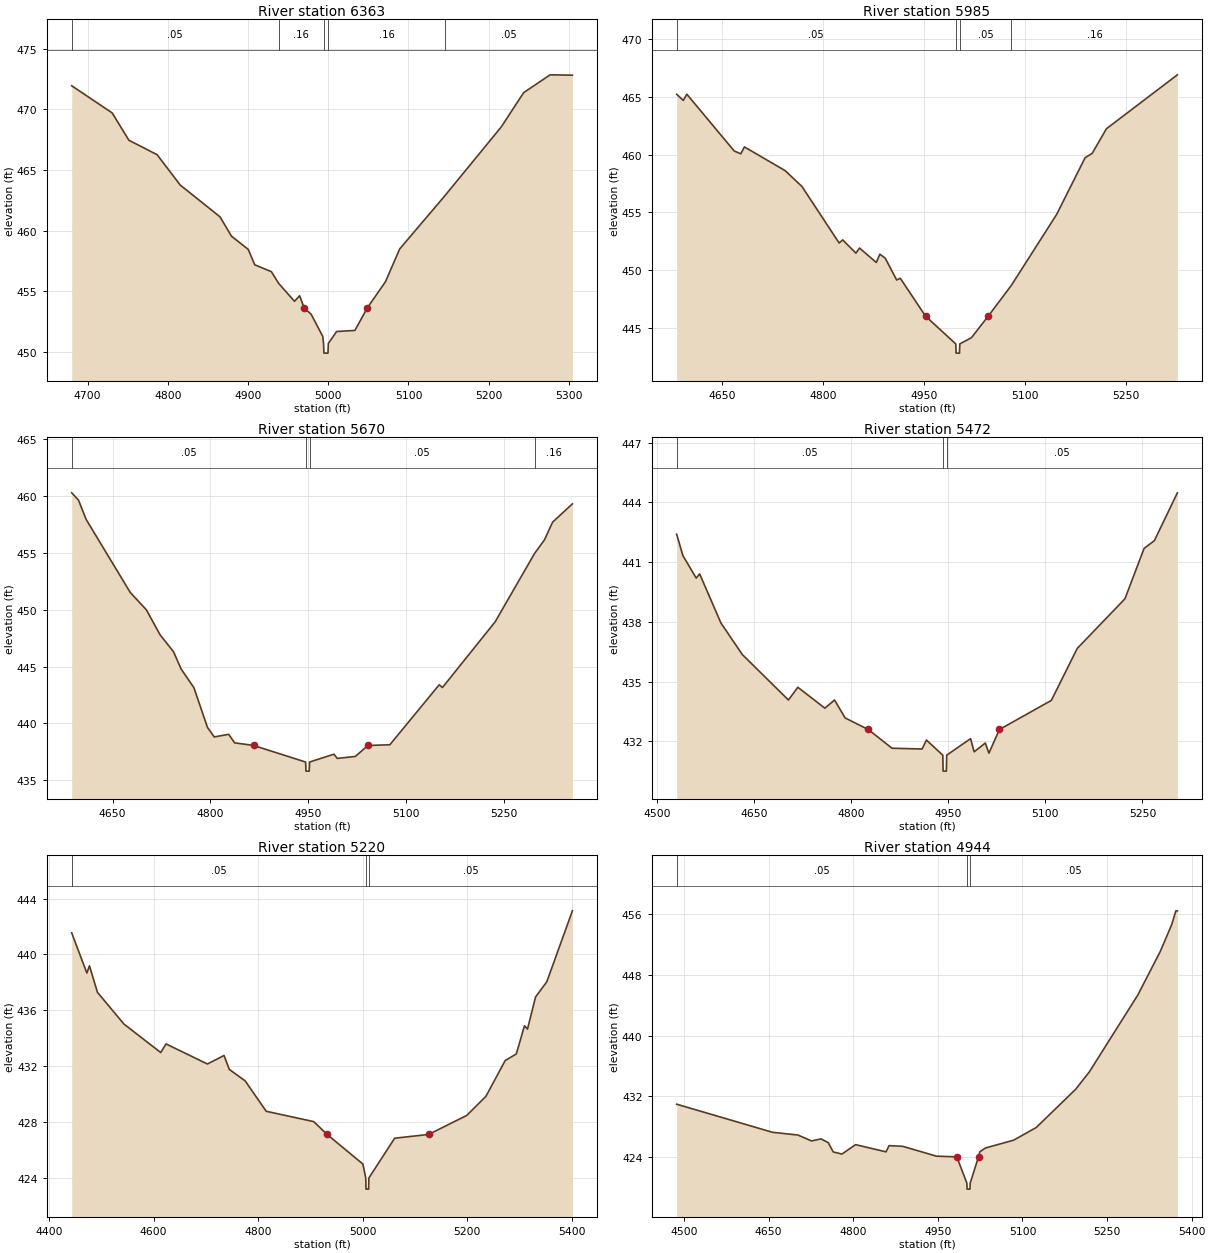
Type RM Length L Ch R = 1,6363,378,378,378
BEGIN DESCRIPTION:
UNT 169 in LFCCL Watershed 7.0
END DESCRIPTION:
XS GIS Cut Line= 3
      2799574.97      7027974.97      2799825.00      7028175.00
      2800124.96      7028125.01
#Sta/Elev= 30
  4680.1  471.94  4730.6  469.70  4751.4  467.45  4786.6  466.26  4815.4  463.76
  4865.0  461.14  4879.4  459.54  4900.2  458.46  4908.3  457.19  4929.1  456.62
  4938.2  455.65  4957.9  454.18  4964.3  454.64  4969.9  453.64  4978.7  453.11
  4993.1  451.29  4994.1  450.71  4994.6  449.91  4999.6  449.91  5000.1  450.71
  5010.4  451.69  5033.2  451.78  5048.7  453.64  5071.3  455.79  5089.0  458.49
  5145.3  462.87  5215.7  468.55  5243.6  471.37  5276.6  472.84  5304.4  472.81
#Mann=5,-1,0
  4680.1    0.05       0  4938.2    0.16       0  4994.1    0.07       0
  5000.1    0.16       0  5145.3    0.05       0
Bank Sta=4969.9,5048.7
Exp/Cntr=0.3,0.1

Type RM Length L Ch R = 1,5985,315,315,315
BEGIN DESCRIPTION:
UNT 169 in LFCCL Watershed 6.0
END DESCRIPTION:
XS GIS Cut Line= 3
      2799575.00      7028125.00      2799725.00      7028525.00
      2800024.97      7028624.99
#Sta/Elev= 30
  4582.7  465.25  4592.5  464.71  4597.8  465.25  4668.1  460.33  4677.9  460.08
  4683.3  460.68  4743.8  458.62  4768.7  457.25  4823.9  452.35  4829.2  452.62
  4848.8  451.47  4854.2  451.91  4879.1  450.66  4884.4  451.38  4892.4  451.03
  4909.3  449.14  4914.7  449.29  4952.3  446.00  4997.1  443.60  4997.6  442.80
  5002.6  442.80  5003.1  443.60  5020.4  444.14  5045.2  446.00  5079.8  448.69
  5146.9  454.83  5189.1  459.74  5199.6  460.12  5220.7  462.25  5326.1  466.93
#Mann=4,-1,0
  4582.7    0.05       0  4997.1    0.03       0  5003.1    0.05       0
  5079.8    0.16       0
Bank Sta=4952.3,5045.2
Exp/Cntr=0.3,0.1

Type RM Length L Ch R = 1,5670,198,198,198
BEGIN DESCRIPTION:
UNT 169 in LFCCL Watershed 5.0
END DESCRIPTION:
XS GIS Cut Line= 3
      2799375.01      7028375.03      2799475.00      7028725.00
      2799875.02      7028775.00
#Sta/Elev= 30
  4587.4  460.29  4597.8  459.65  4609.5  457.95  4677.1  451.52  4701.8  449.99
  4722.6  447.81  4743.4  446.30  4755.1  444.77  4774.6  443.14  4795.4  439.64
  4805.8  438.80  4827.9  439.03  4837.0  438.28  4866.0  438.05  4945.8  436.59
  4946.3  435.79  4951.3  435.79  4951.8  436.59  4989.2  437.28  4994.2  436.91
  5021.9  437.08  5041.2  438.05  5074.8  438.11  5150.4  443.39  5155.4  443.15
  5236.1  448.93  5296.5  454.95  5311.7  456.15  5324.2  457.71  5354.5  459.32
#Mann=4,-1,0
  4587.4    0.05       0  4945.8    0.03       0  4951.8    0.05       0
  5296.5    0.16       0
Bank Sta=4866,5041.2
Exp/Cntr=0.3,0.1

Type RM Length L Ch R = 1,5472,252,252,252
BEGIN DESCRIPTION:
XS3983A
END DESCRIPTION:
XS GIS Cut Line= 3
      2799249.86      7028535.77      2799347.08      7028858.65
      2799741.47      7029045.47
#Sta/Elev= 30
  4530.4  442.40  4540.0  441.33  4560.6  440.20  4565.9  440.41  4598.9  437.94
  4631.9  436.36  4703.1  434.08  4717.6  434.72  4759.4  433.67  4774.3  434.08
  4790.7  433.18  4826.4  432.60  4863.1  431.66  4909.6  431.62  4916.3  432.07
  4941.6  431.31  4942.1  430.51  4947.1  430.51  4947.6  431.31  4984.5  432.14
  4990.0  431.48  5007.3  431.92  5012.8  431.41  5029.1  432.60  5109.3  434.06
  5149.3  436.67  5223.0  439.16  5252.6  441.69  5268.5  442.08  5304.0  444.48
#Mann=3,-1,0
  4530.4    0.05       0  4941.6    0.03       0  4947.6    0.05       0
Bank Sta=4826.4,5029.1
Exp/Cntr=0.3,0.1

Type RM Length L Ch R = 1,5220,276,276,276
BEGIN DESCRIPTION:
UNT 169 in LFCCL Watershed 4.0
END DESCRIPTION:
XS GIS Cut Line= 3
      2799225.55      7028546.19      2799298.47      7029098.24
      2799641.11      7029305.90
#Sta/Elev= 30
  4443.5  441.55  4472.5  438.67  4477.5  439.19  4492.7  437.29  4543.2  435.02
  4613.8  432.97  4623.9  433.59  4703.0  432.15  4734.8  432.76  4744.9  431.76
  4775.2  430.94  4815.5  428.76  4906.3  428.02  4931.9  427.10  5000.3  424.98
  5005.8  423.98  5006.3  423.18  5011.3  423.18  5011.8  423.98  5061.1  426.83
  5126.1  427.10  5198.8  428.46  5235.6  429.83  5272.5  432.40  5293.8  432.87
  5309.3  434.89  5315.1  434.65  5330.6  436.96  5352.0  438.04  5401.0  443.13
#Mann=3,-1,0
  4443.5    0.05       0  5005.8    0.03       0  5011.8    0.05       0
Bank Sta=4931.9,5126.1
Exp/Cntr=0.3,0.1

Type RM Length L Ch R = 1,4944,103,103,103
BEGIN DESCRIPTION:
XS3986A
END DESCRIPTION:
XS GIS Cut Line= 3
      2799121.39      7028907.29      2799294.99      7029341.29
      2799715.12      7029355.18
#Sta/Elev= 30
  4486.9  430.94  4656.8  427.23  4701.9  426.87  4726.1  426.09  4742.9  426.36
  4755.7  425.86  4764.5  424.64  4780.0  424.36  4804.2  425.60  4858.1  424.65
  4863.5  425.47  4887.7  425.38  4947.6  424.08  4983.6  423.99  5001.4  420.53
  5001.9  419.73  5006.9  419.73  5007.4  420.53  5022.1  423.99  5024.4  424.65
  5034.4  425.16  5084.4  426.19  5124.4  427.86  5194.5  432.92  5218.7  435.21
  5304.5  445.34  5344.6  451.13  5364.6  454.63  5372.1  456.46  5374.7  456.46
#Mann=3,-1,0
  4486.9    0.05       0  5001.4    0.03       0  5007.4    0.05       0
Bank Sta=4983.6,5022.1
Exp/Cntr=0.3,0.1

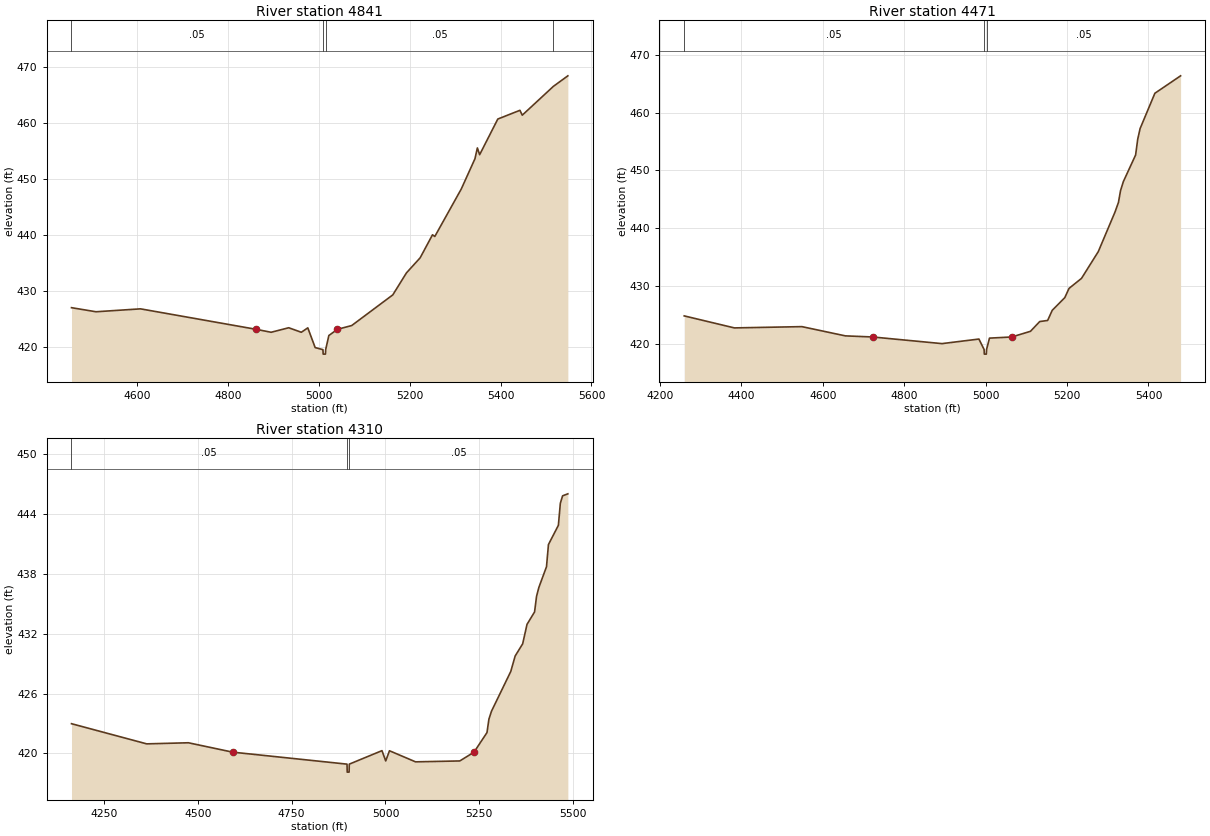
Type RM Length L Ch R = 1,4841,370,370,370
BEGIN DESCRIPTION:
XS3985A
END DESCRIPTION:
XS GIS Cut Line= 3
      2798847.07      7029198.93      2799308.88      7029438.52
      2799878.37      7029379.48
#Sta/Elev= 30
  4455.2  426.95  4509.2  426.22  4607.2  426.74  4861.6  423.08  4894.8  422.55
  4933.5  423.36  4961.2  422.55  4975.5  423.34  4991.7  419.81  5008.8  419.44
  5009.3  418.64  5014.3  418.64  5014.8  419.44  5021.8  421.97  5040.7  423.08
  5072.1  423.75  5162.6  429.24  5192.7  433.18  5222.9  435.88  5250.0  439.99
  5255.1  439.69  5313.4  448.19  5343.5  453.60  5348.8  455.53  5353.8  454.32
  5393.8  460.70  5442.5  462.26  5447.6  461.39  5516.1  466.54  5548.0  468.43
#Mann=4,-1,0
  4455.2    0.05       0  5008.8    0.03       0  5014.8    0.05       0
  5516.1    0.16       0
Bank Sta=4861.6,5040.7
Exp/Cntr=0.3,0.1

Type RM Length L Ch R = 1,4471,161,161,161
BEGIN DESCRIPTION:
XS3984A
END DESCRIPTION:
XS GIS Cut Line= 3
      2798758.98      7029438.90      2799288.05      7029816.99
      2799841.77      7029685.48
#Sta/Elev= 30
  4259.5  424.82  4382.7  422.74  4548.6  422.96  4655.5  421.36  4722.3  421.17
  4892.7  420.02  4983.5  420.81  4996.2  419.00  4996.7  418.20  5001.7  418.20
  5002.2  419.00  5009.4  420.97  5064.1  421.17  5110.1  422.15  5132.8  423.84
  5152.3  424.03  5163.6  425.79  5194.4  427.98  5204.8  429.58  5235.5  431.32
  5276.7  435.95  5317.8  442.81  5326.2  444.46  5331.4  446.52  5338.3  448.08
  5368.4  452.68  5373.5  455.39  5379.4  457.25  5415.7  463.37  5478.9  466.39
#Mann=3,-1,0
  4259.5    0.05       0  4996.2    0.03       0  5002.2    0.05       0
Bank Sta=4722.3,5064.1
Exp/Cntr=0.3,0.1

Type RM Length L Ch R = 1,4310,0,0,0
BEGIN DESCRIPTION:
XS3987A
END DESCRIPTION:
XS GIS Cut Line= 4
      2798676.30      7029598.35      2799278.08      7029956.52
      2799467.30      7029949.54      2799878.32      7029813.52
#Sta/Elev= 30
  4163.4  422.98  4363.8  420.96  4474.9  421.07  4592.9  420.13  4897.6  418.93
  4898.1  418.13  4903.1  418.13  4903.6  418.93  4990.7  420.28  5000.7  419.25
  5010.7  420.27  5080.2  419.16  5198.1  419.25  5236.0  420.13  5270.5  422.09
  5275.7  423.44  5282.4  424.22  5333.9  428.21  5345.6  429.76  5365.6  430.98
  5377.2  432.93  5397.3  434.17  5402.6  435.74  5408.8  436.63  5429.1  438.70
  5434.3  440.92  5460.8  442.85  5466.0  445.06  5472.0  445.80  5486.0  446.00
#Mann=3,-1,0
  4163.4    0.05       0  4897.6    0.03       0  4903.6    0.05       0
Bank Sta=4592.9,5236
Exp/Cntr=0.3,0.1

Chan Stop Cuts=-1