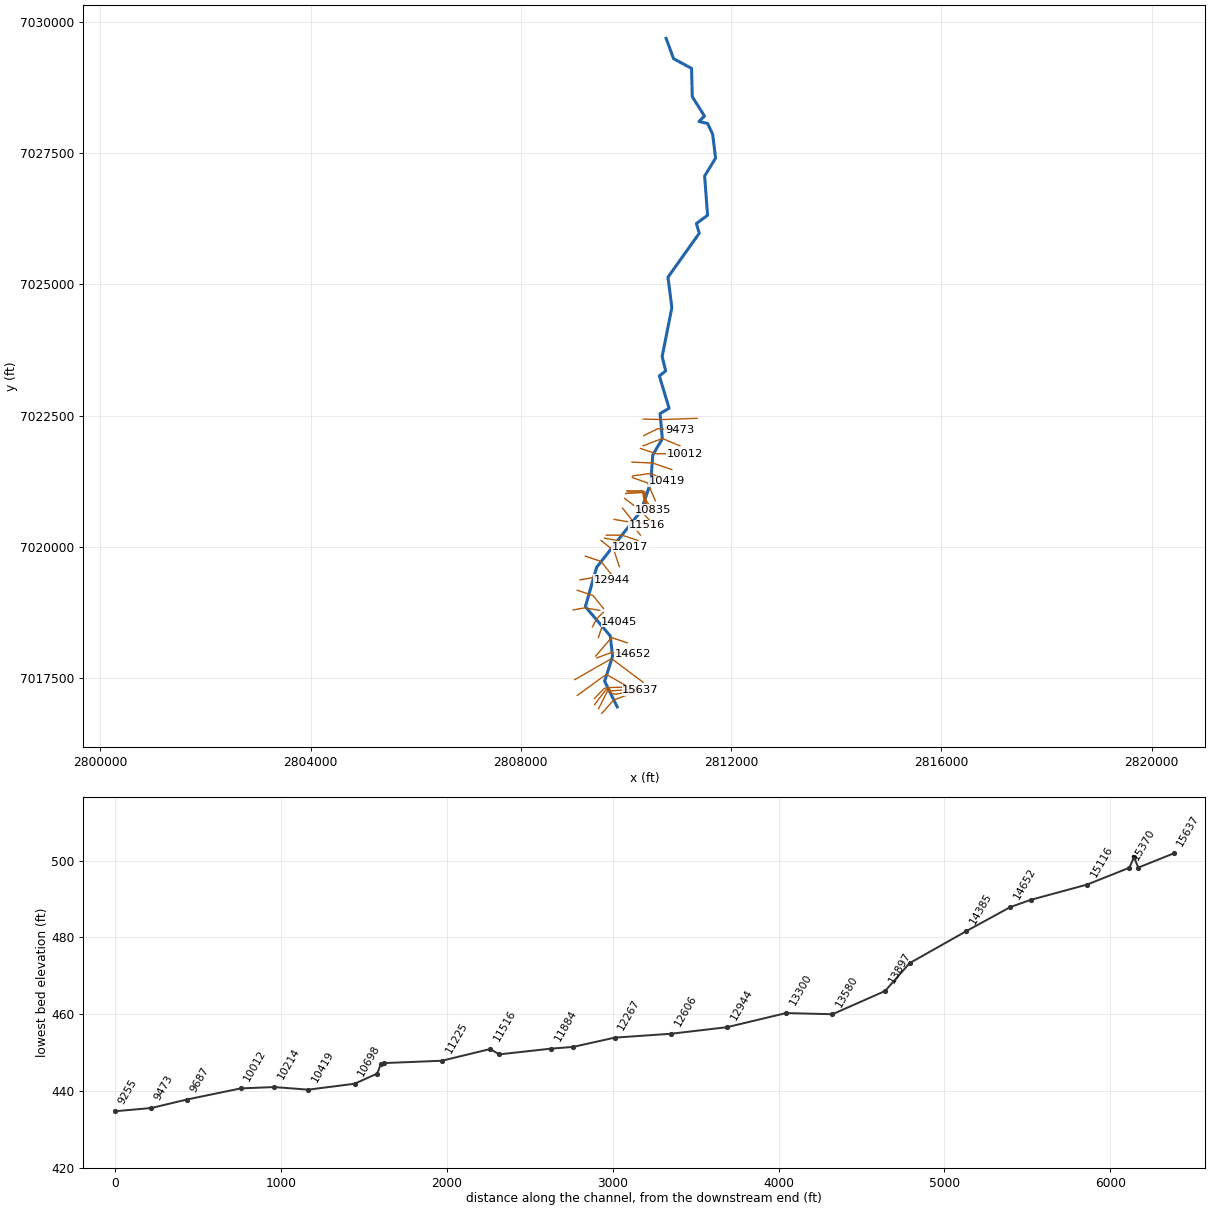
--- UNT 170 in LFCCL Watershed.prj (project) ---

Proj Title=UNT 170 in LFCCL Watershed Base Level Engineering
Current Plan=p01
Default Exp/Contr=0.3,0.1
English Units
Geom File=g01
Flow File=f01
Plan File=p01
BEGIN DESCRIPTION:
UNT 170 in LFCCL Watershed
END DESCRIPTION:

--- UNT 170 in LFCCL Watershed.p01 (plan) ---

Plan Title=Multiple Run
Short Identifier=Multiple
Geom File=g01
Flow File=f01
Subcritical Flow
K Sum by GR= 0
Std Step Tol= 0.01
Critical Tol= 0.01
Num of Std Step Trials= 20
Max Error Tol= 0.3
Flow Tol Ratio= 0.001
Split Flow NTrial= 30
Split Flow Tol= 0.02
Split Flow Ratio= 0.02
Log Output Level= 0
Friction Slope Method= 1
Unsteady Friction Slope Method= 2
Unsteady Bridges Friction Slope Method= 1
Parabolic Critical Depth
Global Vel Dist=  1 , 1 , 1
Global Log Level= 0
CheckData=True
Encroach Param= -1, 0, 0, 0
BEGIN DESCRIPTION:
Multiple Run
END DESCRIPTION:

--- UNT 170 in LFCCL Watershed.f01 (steady flow) ---

Flow Title=Multiple
Number of Profiles=7
Profile Names=10-year,25-year,50-year,1pct_min,100-year,1pct_plu,500-year
River Rch & RM= UNT 170 in LFCCL,Reach-1,15637
     288     370     435     255     508    1013     693
River Rch & RM= UNT 170 in LFCCL,Reach-1,10419
     507     675     810     484     965    1926    1372
River Rch & RM= UNT 170 in LFCCL,Reach-1,6007
     846    1154    1409     854    1704    3399    2495
Boundary for River Rch & Prof#=UNT 170 in LFCCL,Reach-1,1
Up Type=0
Dn Type=3
Dn Slope=0.005
Boundary for River Rch & Prof#=UNT 170 in LFCCL,Reach-1,2
Up Type=0
Dn Type=3
Dn Slope=0.005
Boundary for River Rch & Prof#=UNT 170 in LFCCL,Reach-1,3
Up Type=0
Dn Type=3
Dn Slope=0.005
Boundary for River Rch & Prof#=UNT 170 in LFCCL,Reach-1,4
Up Type=0
Dn Type=3
Dn Slope=0.005
Boundary for River Rch & Prof#=UNT 170 in LFCCL,Reach-1,5
Up Type=0
Dn Type=3
Dn Slope=0.005
Boundary for River Rch & Prof#=UNT 170 in LFCCL,Reach-1,6
Up Type=0
Dn Type=3
Dn Slope=0.005
Boundary for River Rch & Prof#=UNT 170 in LFCCL,Reach-1,7
Up Type=0
Dn Type=3
Dn Slope=0.005

--- UNT 170 in LFCCL Watershed.g01 (geometry) ---

Geom Title=Existing Conditions

River Reach=UNT 170 in LFCCL,Reach-1
Reach XY= 30
      2809832.95      7016956.77      2809593.80      7017443.53
      2809743.58      7017915.31      2809701.91      7018305.93
      2809227.45      7018864.88      2809441.39      7019613.03
      2810288.30      7020689.60      2810473.12      7021236.98
      2810508.88      7021749.79      2810691.41      7022061.22
      2810647.87      7022539.81      2810819.90      7022639.93
      2810634.83      7023256.12      2810754.96      7023350.84
      2810688.21      7023625.13      2810872.49      7024556.22
      2810798.38      7025135.67      2811393.86      7025971.48
      2811338.85      7026156.72      2811551.64      7026312.89
      2811495.87      7027060.25      2811704.15      7027401.72
      2811647.93      7027857.99      2811552.30      7028062.49
      2811387.56      7028097.52      2811492.66      7028202.61
      2811260.70      7028571.85      2811247.44      7029108.67
      2810904.71      7029295.18      2810763.14      7029681.83

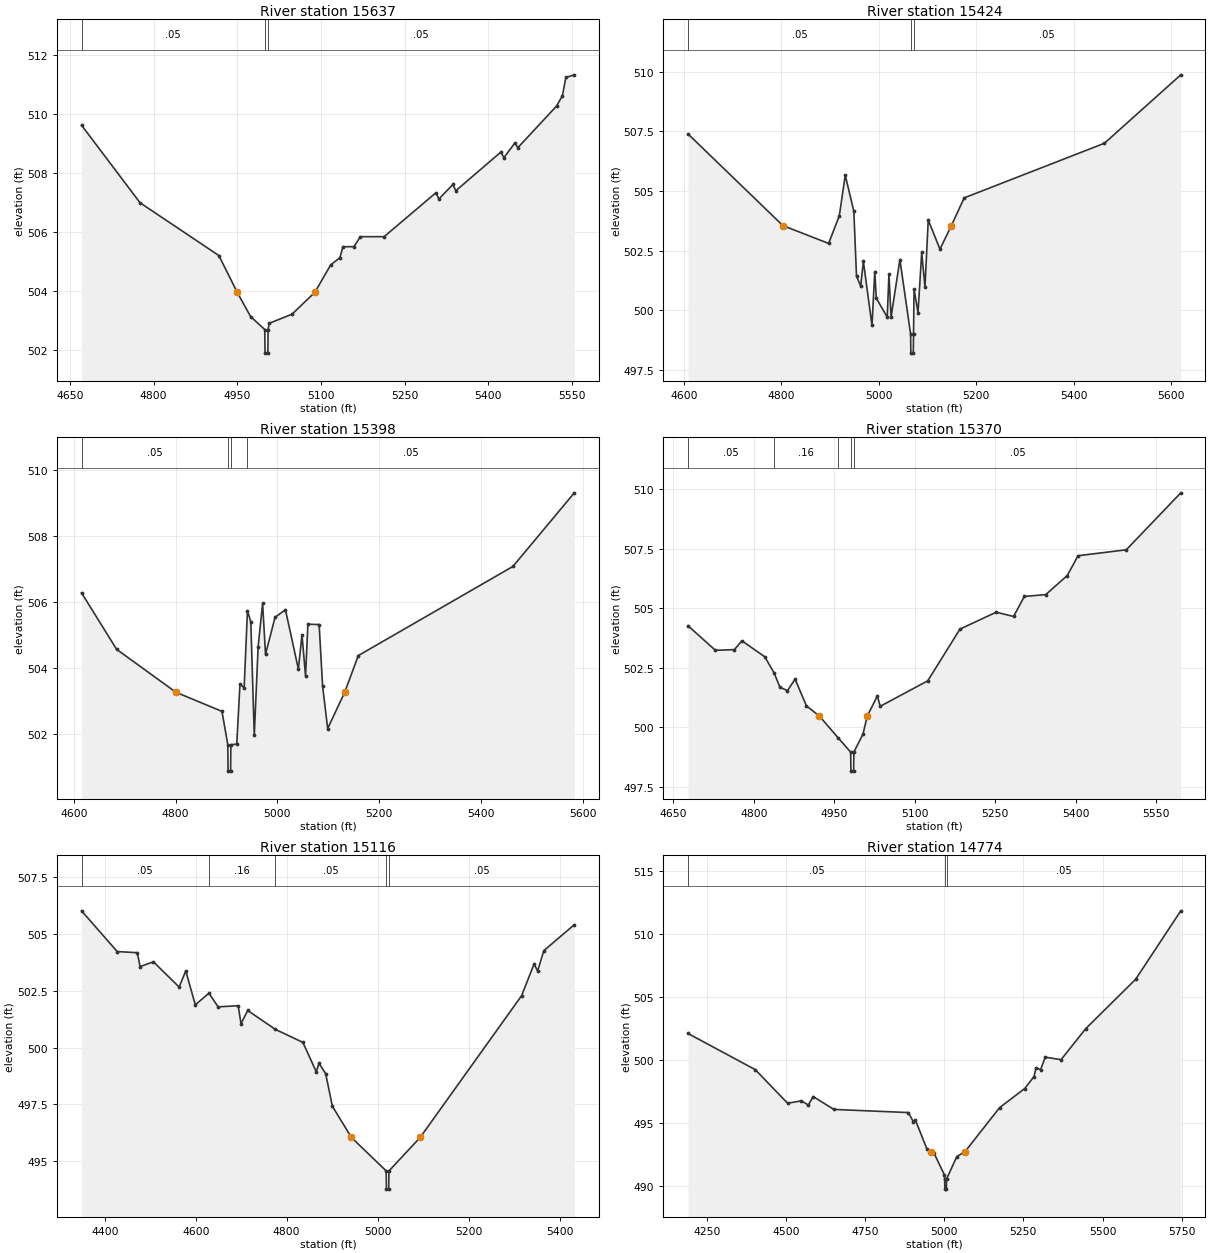
Type RM Length L Ch R = 1,15637,213,213,213
BEGIN DESCRIPTION:
UNT 170 in LFCCL Watershed 36.0
END DESCRIPTION:
XS GIS Cut Line= 3
      2809539.46      7016832.63      2809765.24      7017087.23
      2810274.96      7017274.99
#Sta/Elev= 30
  4670.9  509.62  4775.8  506.99  4917.1  505.20  4950.1  503.95  4974.0  503.13
  4999.4  502.69  4999.9  501.89  5004.9  501.89  5005.4  502.69  5007.2  502.90
  5048.2  503.21  5089.1  503.95  5117.5  504.88  5134.2  505.13  5139.5  505.50
  5159.3  505.50  5170.8  505.84  5213.4  505.84  5306.3  507.33  5311.6  507.12
  5336.7  507.61  5342.0  507.40  5422.7  508.71  5428.1  508.52  5447.9  509.02
  5453.2  508.86  5522.5  510.27  5533.1  510.62  5539.2  511.24  5554.4  511.33
#Mann=3,-1,0
  4670.9    0.05       0  4999.4    0.03       0  5005.4    0.05       0
Bank Sta=4950.1,5089.1
Exp/Cntr=0.3,0.1

Type RM Length L Ch R = 1,15424,26,26,26
BEGIN DESCRIPTION:
XS3990A
END DESCRIPTION:
XS GIS Cut Line= 6
      2809478.65      7016921.94      2809650.53      7017263.10
      2809694.80      7017260.49      2809723.45      7017211.02
      2809811.99      7017197.99      2810230.58      7017281.19
#Sta/Elev= 30
  4608.3  507.39  4803.0  503.55  4897.0  502.80  4919.0  503.96  4931.2  505.66
  4948.8  504.15  4954.3  501.43  4962.9  501.01  4968.4  502.05  4986.1  499.36
  4991.8  501.62  4995.0  500.50  5017.4  499.71  5020.9  501.51  5025.3  499.71
  5043.4  502.12  5065.4  499.00  5065.9  498.20  5070.9  498.20  5071.4  499.00
  5072.5  500.88  5080.6  499.90  5088.2  502.42  5094.9  500.97  5101.6  503.78
  5125.7  502.56  5149.2  503.55  5175.4  504.71  5463.4  507.00  5620.2  509.87
#Mann=3,-1,0
  4608.3    0.05       0  5065.4    0.03       0  5071.4    0.05       0
Bank Sta=4803,5149.2
Exp/Cntr=0.3,0.1

Type RM Length L Ch R = 1,15398,28,28,28
BEGIN DESCRIPTION:
XS3989A
END DESCRIPTION:
XS GIS Cut Line= 6
      2809403.15      7017000.10      2809608.87      7017270.91
      2809637.51      7017286.54      2809686.99      7017291.74
      2809718.24      7017260.49      2810218.29      7017299.56
#Sta/Elev= 30
  4615.3  506.27  4684.2  504.56  4800.7  503.26  4891.3  502.68  4902.8  501.67
  4903.3  500.87  4908.3  500.87  4908.8  501.67  4920.4  501.69  4926.7  503.51
  4934.9  503.39  4941.4  505.73  4948.0  505.39  4954.8  501.95  4962.4  504.64
  4971.2  505.95  4976.9  504.41  4995.7  505.53  5016.1  505.76  5041.5  503.96
  5048.6  505.00  5055.6  503.75  5060.2  505.32  5082.3  505.31  5089.1  503.45
  5099.1  502.16  5132.6  503.26  5159.3  504.37  5463.2  507.07  5583.9  509.30
#Mann=4,-1,0
  4615.3    0.05       0  4902.8    0.03       0  4908.8    0.05       0
  4941.4    0.05       0
Bank Sta=4800.7,5132.6
Exp/Cntr=0.3,0.1

Type RM Length L Ch R = 1,15370,254,254,254
BEGIN DESCRIPTION:
XS3988A
END DESCRIPTION:
XS GIS Cut Line= 4
      2809400.53      7017117.27      2809588.03      7017309.97
      2809720.84      7017325.60      2810236.48      7017338.62
#Sta/Elev= 30
  4677.4  504.26  4728.5  503.23  4763.8  503.26  4777.9  503.63  4820.4  502.96
  4837.7  502.29  4848.7  501.68  4862.8  501.54  4877.0  502.02  4898.1  500.90
  4922.3  500.47  4957.5  499.55  4980.5  498.96  4981.0  498.16  4986.0  498.16
  4986.5  498.96  5003.6  499.72  5011.4  500.47  5030.4  501.32  5035.5  500.88
  5124.2  501.95  5184.2  504.12  5251.8  504.83  5284.2  504.65  5304.2  505.49
  5344.2  505.57  5384.3  506.37  5404.3  507.20  5494.3  507.45  5595.8  509.84
#Mann=5,-1,0
  4677.4    0.05       0  4837.7    0.16       0  4957.5    0.05       0
  4980.5    0.03       0  4986.5    0.05       0
Bank Sta=4922.3,5011.4
Exp/Cntr=0.3,0.1

Type RM Length L Ch R = 1,15116,342,342,342
BEGIN DESCRIPTION:
UNT 170 in LFCCL Watershed 35.0
END DESCRIPTION:
XS GIS Cut Line= 3
      2809075.00      7017175.00      2809625.00      7017575.00
      2809975.01      7017375.00
#Sta/Elev= 30
  4349.1  506.01  4427.5  504.22  4471.6  504.17  4477.8  503.56  4507.1  503.77
  4563.6  502.66  4578.2  503.37  4599.1  501.88  4629.1  502.39  4649.3  501.79
  4693.4  501.84  4699.6  501.05  4714.3  501.63  4775.2  500.80  4835.6  500.23
  4865.0  498.94  4871.1  499.31  4885.8  498.85  4900.5  497.42  4942.4  496.05
  5018.8  494.58  5019.3  493.78  5024.3  493.78  5024.8  494.58  5093.4  496.05
  5316.4  502.28  5343.8  503.67  5351.7  503.37  5365.3  504.26  5432.3  505.40
#Mann=5,-1,0
  4349.1    0.05       0  4629.1    0.16       0  4775.2    0.05       0
  5018.8    0.03       0  5024.8    0.05       0
Bank Sta=4942.4,5093.4
Exp/Cntr=0.3,0.1

Type RM Length L Ch R = 1,14774,122,122,122
BEGIN DESCRIPTION:
UNT 170 in LFCCL Watershed 34.0
END DESCRIPTION:
XS GIS Cut Line= 3
      2809025.03      7017475.02      2809725.00      7017875.00
      2810325.00      7017425.00
#Sta/Elev= 30
  4191.0  502.13  4403.3  499.26  4505.5  496.59  4548.7  496.78  4571.0  496.45
  4586.2  497.12  4651.7  496.10  4887.1  495.85  4902.9  495.10  4908.7  495.28
  4946.1  492.92  4959.2  492.74  4967.7  492.64  5000.3  490.92  5001.5  490.57
  5002.0  489.77  5007.0  489.77  5007.5  490.57  5039.9  492.36  5065.5  492.74
  5175.3  496.25  5254.5  497.76  5283.7  498.71  5289.9  499.39  5304.5  499.26
  5319.1  500.25  5369.1  500.05  5447.2  502.52  5604.5  506.43  5747.2  511.87
#Mann=3,-1,0
  4191.0    0.05       0  5001.5    0.03       0  5007.5    0.05       0
Bank Sta=4959.2,5065.5
Exp/Cntr=0.3,0.1

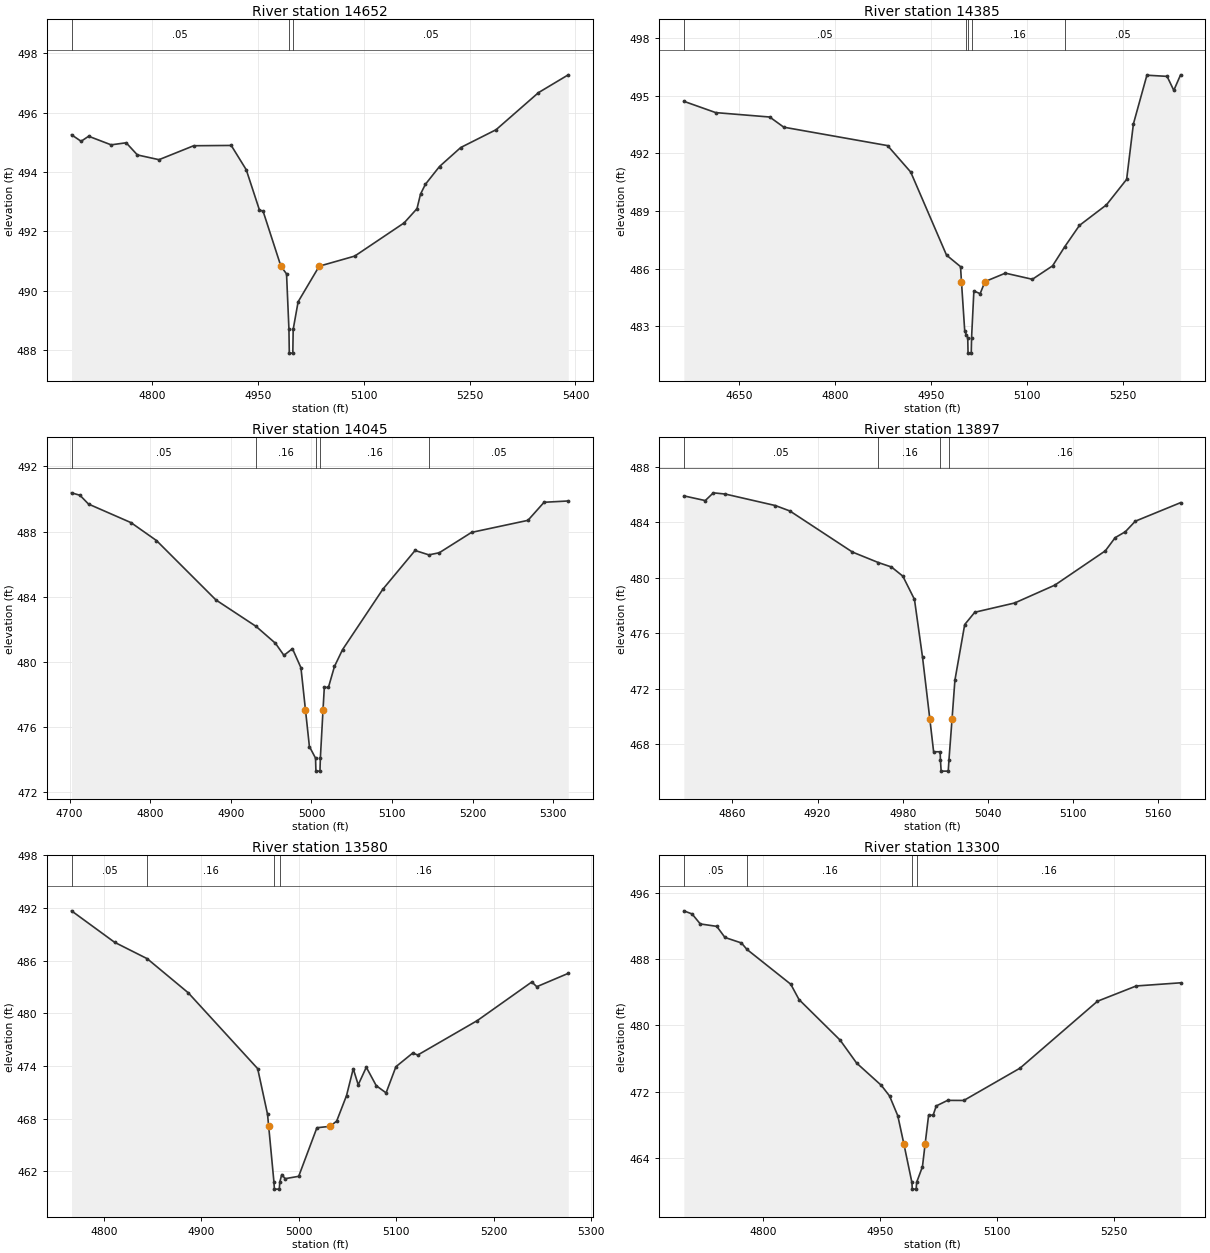
Type RM Length L Ch R = 1,14652,267,267,267
BEGIN DESCRIPTION:
XS3991A
END DESCRIPTION:
XS GIS Cut Line= 3
      2809442.19      7017888.10      2809728.66      7017992.27
      2810127.09      7017966.22
#Sta/Elev= 30
  4685.7  495.26  4699.3  495.04  4710.0  495.21  4741.9  494.92  4763.2  494.99
  4779.1  494.58  4809.7  494.42  4858.9  494.89  4912.1  494.90  4933.4  494.08
  4952.0  492.73  4957.3  492.68  4982.5  490.83  4990.5  490.57  4993.9  488.70
  4994.4  487.90  4999.4  487.90  4999.9  488.70  5006.9  489.63  5036.8  490.83
  5087.1  491.17  5157.2  492.29  5175.4  492.77  5180.4  493.26  5187.3  493.59
  5207.3  494.19  5237.4  494.83  5287.5  495.43  5347.6  496.68  5389.8  497.28
#Mann=3,-1,0
  4685.7    0.05       0  4993.9    0.03       0  4999.9    0.05       0
Bank Sta=4982.5,5036.8
Exp/Cntr=0.3,0.1

Type RM Length L Ch R = 1,14385,340,340,340
BEGIN DESCRIPTION:
UNT 170 in LFCCL Watershed 33.0
END DESCRIPTION:
XS GIS Cut Line= 3
      2809425.03      7017925.03      2809725.00      7018275.00
      2810025.04      7018174.99
#Sta/Elev= 30
  4563.1  494.72  4613.0  494.13  4697.5  493.90  4719.5  493.37  4881.9  492.41
  4918.1  491.03  4974.1  486.70  4996.0  486.10  4997.5  485.31  5002.6  482.74
  5005.1  482.55  5007.3  482.39  5007.8  481.59  5012.8  481.59  5013.3  482.39
  5016.9  484.83  5026.7  484.69  5034.3  485.32  5066.2  485.76  5108.4  485.44
  5140.0  486.14  5158.9  487.13  5182.1  488.25  5224.3  489.32  5255.9  490.65
  5266.5  493.54  5287.6  496.08  5319.2  496.02  5329.7  495.29  5340.3  496.10
#Mann=5,-1,0
  4563.1    0.05       0  5005.1    0.16       0  5007.3    0.03       0
  5013.3    0.16       0  5158.9    0.05       0
Bank Sta=4997.5,5034.3
Exp/Cntr=0.3,0.1

Type RM Length L Ch R = 1,14045,148,148,148
BEGIN DESCRIPTION:
UNT 170 in LFCCL Watershed 32.0
END DESCRIPTION:
XS GIS Cut Line= 3
      2809475.00      7018275.00      2809575.00      7018575.00
      2809874.97      7018575.00
#Sta/Elev= 30
  4702.3  490.38  4712.8  490.23  4723.4  489.69  4776.1  488.55  4807.7  487.45
  4881.5  483.80  4931.2  482.18  4955.3  481.14  4965.8  480.40  4976.4  480.81
  4986.9  479.64  4992.5  477.06  4997.4  474.80  5005.0  474.09  5005.5  473.29
  5010.5  473.29  5011.0  474.09  5014.3  477.06  5015.9  478.43  5021.0  478.43
  5028.5  479.72  5038.5  480.75  5088.5  484.46  5128.5  486.84  5145.6  486.57
  5158.5  486.70  5198.5  487.95  5268.5  488.69  5288.5  489.80  5318.5  489.88
#Mann=5,-1,0
  4702.3    0.05       0  4931.2    0.16       0  5005.0    0.07       0
  5011.0    0.16       0  5145.6    0.05       0
Bank Sta=4992.5,5014.3
Exp/Cntr=0.3,0.1

Type RM Length L Ch R = 1,13897,317,317,317
BEGIN DESCRIPTION:
XS3992A
END DESCRIPTION:
XS GIS Cut Line= 3
      2809361.48      7018479.26      2809447.41      7018638.10
      2809569.77      7018755.25
#Sta/Elev= 30
  4825.8  485.92  4840.9  485.58  4846.6  486.14  4855.1  486.05  4890.3  485.22
  4900.5  484.83  4944.6  481.86  4962.9  481.10  4972.1  480.78  4980.1  480.12
  4988.3  478.44  4994.0  474.25  4999.1  469.82  5001.8  467.43  5006.4  467.43
  5006.6  466.83  5007.1  466.03  5012.1  466.03  5012.6  466.83  5014.8  469.82
  5016.8  472.60  5023.7  476.62  5030.8  477.51  5058.9  478.18  5087.2  479.47
  5122.8  481.95  5129.7  482.90  5136.9  483.33  5143.9  484.09  5175.8  485.43
#Mann=4,-1,0
  4825.8    0.05       0  4962.9    0.16       0  5006.6    0.07       0
  5012.6    0.16       0
Bank Sta=4999.1,5014.8
Exp/Cntr=0.3,0.1

Type RM Length L Ch R = 1,13580,280,280,280
BEGIN DESCRIPTION:
XS3993A
END DESCRIPTION:
XS GIS Cut Line= 3
      2808996.92      7018802.17      2809215.64      7018841.22
      2809499.52      7018794.34
#Sta/Elev= 30
  4766.7  491.67  4810.9  488.09  4844.4  486.22  4886.6  482.33  4957.8  473.70
  4967.9  468.52  4969.1  467.13  4974.5  460.78  4975.0  459.98  4980.0  459.98
  4980.5  460.78  4982.5  461.64  4986.0  461.17  4999.9  461.44  5018.6  466.97
  5032.1  467.13  5038.9  467.73  5049.0  470.63  5055.9  473.69  5061.0  471.86
  5069.3  473.86  5079.5  471.76  5089.6  470.94  5099.7  473.92  5117.0  475.48
  5122.1  475.25  5183.2  479.17  5239.2  483.57  5244.3  483.03  5276.6  484.55
#Mann=4,-1,0
  4766.7    0.05       0  4844.4    0.16       0  4974.5    0.07       0
  4980.5    0.16       0
Bank Sta=4969.1,5032.1
Exp/Cntr=0.3,0.1

Type RM Length L Ch R = 1,13300,356,356,356
BEGIN DESCRIPTION:
UNT 170 in LFCCL Watershed 30.0
END DESCRIPTION:
XS GIS Cut Line= 3
      2809074.98      7019175.01      2809375.00      7019075.00
      2809575.00      7018825.00
#Sta/Elev= 30
  4698.7  493.80  4709.3  493.42  4719.8  492.22  4740.9  491.93  4751.4  490.59
  4772.5  489.93  4779.6  489.15  4835.7  484.96  4846.3  483.11  4899.0  478.22
  4920.1  475.46  4951.7  472.78  4962.2  471.51  4972.8  469.12  4980.5  465.77
  4990.9  461.08  4991.4  460.28  4996.4  460.28  4996.9  461.08  5004.4  462.98
  5007.9  465.77  5012.3  469.19  5018.1  469.19  5022.1  470.30  5036.6  470.97
  5057.4  470.96  5129.4  474.85  5228.6  482.91  5278.3  484.75  5335.1  485.13
#Mann=4,-1,0
  4698.7    0.05       0  4779.6    0.16       0  4990.9    0.07       0
  4996.9    0.16       0
Bank Sta=4980.5,5007.9
Exp/Cntr=0.3,0.1

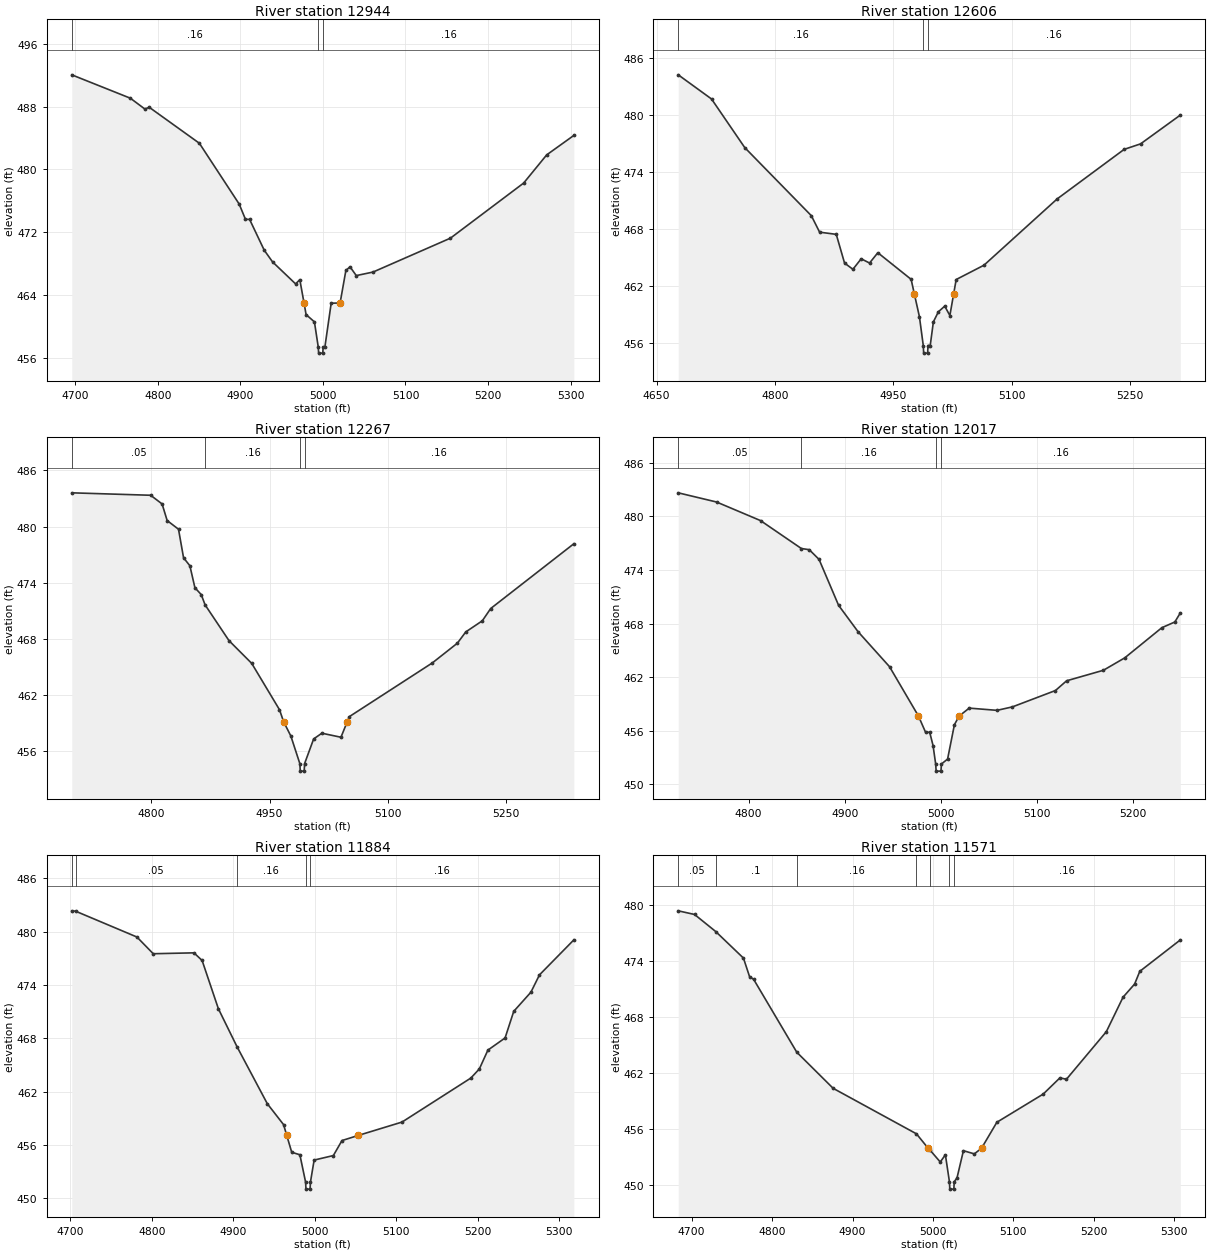
Type RM Length L Ch R = 1,12944,338,338,338
BEGIN DESCRIPTION:
UNT 170 in LFCCL Watershed 29.0
END DESCRIPTION:
XS GIS Cut Line= 3
      2809124.96      7019374.99      2809425.00      7019425.00
      2809724.99      7019375.00
#Sta/Elev= 30
  4695.7  492.06  4766.7  489.08  4784.4  487.69  4789.5  487.93  4850.3  483.34
  4898.5  475.60  4906.1  473.66  4911.2  473.63  4928.9  469.71  4939.0  468.22
  4966.9  465.42  4972.0  465.96  4977.1  462.99  4979.6  461.51  4989.7  460.58
  4994.3  457.40  4994.8  456.60  4999.8  456.60  5000.3  457.40  5002.4  457.40
  5010.0  462.96  5020.8  462.99  5027.8  467.13  5032.8  467.60  5040.4  466.48
  5060.7  466.93  5154.5  471.25  5243.2  478.27  5271.1  481.86  5304.0  484.34
#Mann=3,-1,0
  4695.7    0.16       0  4994.3    0.07       0  5000.3    0.16       0
Bank Sta=4977.1,5020.8
Exp/Cntr=0.3,0.1

Type RM Length L Ch R = 1,12606,339,339,339
BEGIN DESCRIPTION:
UNT 170 in LFCCL Watershed 28.0
END DESCRIPTION:
XS GIS Cut Line= 3
      2809224.99      7019825.00      2809525.00      7019725.00
      2809725.00      7019475.00
#Sta/Elev= 30
  4677.5  484.27  4719.7  481.72  4761.8  476.59  4846.2  469.40  4856.7  467.66
  4877.8  467.43  4888.3  464.40  4898.9  463.74  4909.4  464.85  4920.0  464.40
  4930.5  465.49  4972.7  462.68  4976.9  461.09  4983.2  458.74  4988.1  455.69
  4988.6  454.89  4993.6  454.89  4994.1  455.69  4996.9  455.69  5000.9  458.19
  5007.3  459.26  5015.3  459.85  5021.8  458.86  5026.5  461.09  5029.8  462.66
  5065.0  464.17  5157.8  471.17  5242.7  476.40  5263.5  476.98  5313.9  480.02
#Mann=3,-1,0
  4677.5    0.16       0  4988.1    0.07       0  4994.1    0.16       0
Bank Sta=4976.9,5026.5
Exp/Cntr=0.3,0.1

Type RM Length L Ch R = 1,12267,250,250,250
BEGIN DESCRIPTION:
UNT 170 in LFCCL Watershed 27.0
END DESCRIPTION:
XS GIS Cut Line= 3
      2809525.00      7020125.00      2809775.00      7019925.00
      2809875.00      7019624.99
#Sta/Elev= 30
  4699.3  483.61  4799.3  483.35  4813.8  482.42  4820.2  480.65  4834.6  479.72
  4841.0  476.67  4849.0  475.82  4855.4  473.47  4863.4  472.74  4868.3  471.64
  4898.6  467.82  4927.4  465.39  4962.6  460.44  4967.8  459.16  4977.0  457.63
  4988.4  454.68  4988.9  453.88  4993.9  453.88  4994.4  454.68  5005.9  457.32
  5016.3  457.93  5040.5  457.50  5048.5  459.16  5051.1  459.70  5156.5  465.45
  5188.1  467.55  5198.7  468.75  5219.7  469.94  5230.3  471.25  5335.7  478.17
#Mann=4,-1,0
  4699.3    0.05       0  4868.3    0.16       0  4988.4    0.07       0
  4994.4    0.16       0
Bank Sta=4967.8,5048.5
Exp/Cntr=0.3,0.1

Type RM Length L Ch R = 1,12017,133,133,133
BEGIN DESCRIPTION:
XS3994A
END DESCRIPTION:
XS GIS Cut Line= 3
      2809590.65      7020166.74      2809848.45      7020122.47
      2810080.07      7020002.76
#Sta/Elev= 30
  4726.9  482.65  4766.8  481.62  4812.5  479.54  4855.0  476.41  4863.2  476.28
  4873.4  475.19  4893.7  470.05  4913.9  467.10  4946.7  463.17  4976.8  457.64
  4984.2  455.82  4988.5  455.82  4992.0  454.33  4994.7  452.27  4995.2  451.47
  5000.2  451.47  5000.7  452.27  5007.1  452.82  5014.2  456.67  5019.1  457.64
  5029.6  458.53  5058.5  458.28  5074.6  458.67  5119.3  460.50  5130.9  461.59
  5169.2  462.77  5191.4  464.16  5230.0  467.54  5243.5  468.18  5249.2  469.19
#Mann=4,-1,0
  4726.9    0.05       0  4855.0    0.16       0  4994.7    0.07       0
  5000.7    0.16       0
Bank Sta=4976.8,5019.1
Exp/Cntr=0.3,0.1

Type RM Length L Ch R = 1,11884,313,313,313
BEGIN DESCRIPTION:
UNT 170 in LFCCL Watershed 26.0
END DESCRIPTION:
XS GIS Cut Line= 3
      2809624.97      7020225.00      2809925.00      7020225.00
      2810225.04      7020124.99
#Sta/Elev= 30
  4701.9  482.35  4706.6  482.31  4781.9  479.40  4801.9  477.52  4851.9  477.62
  4861.9  476.76  4881.9  471.32  4904.7  467.06  4941.9  460.64  4961.9  458.28
  4965.8  457.06  4971.9  455.17  4981.9  454.89  4988.9  451.82  4989.4  451.02
  4994.4  451.02  4994.9  451.82  4999.4  454.29  5023.0  454.80  5033.6  456.49
  5053.4  457.06  5107.3  458.57  5191.7  463.52  5202.2  464.55  5212.7  466.67
  5233.8  468.04  5244.4  471.03  5265.5  473.19  5276.0  475.14  5318.2  479.08
#Mann=5,-1,0
  4701.9    0.08       0  4706.6    0.05       0  4904.7    0.16       0
  4988.9    0.07       0  4994.9    0.16       0
Bank Sta=4965.8,5053.4
Exp/Cntr=0.3,0.1

Type RM Length L Ch R = 1,11571,55,55,55
BEGIN DESCRIPTION:
UNT 170 in LFCCL Watershed 25.0
END DESCRIPTION:
XS GIS Cut Line= 3
      2809774.97      7020525.00      2810075.00      7020475.00
      2810274.99      7020225.02
#Sta/Elev= 30
  4683.3  479.36  4703.6  478.97  4729.9  477.14  4764.4  474.29  4772.0  472.30
  4777.1  472.01  4830.7  464.20  4875.9  460.33  4979.5  455.45  4994.1  453.90
  4996.5  453.69  5009.1  452.43  5015.5  453.20  5020.5  450.32  5021.0  449.52
  5026.0  449.52  5026.5  450.32  5029.9  450.71  5037.9  453.64  5051.5  453.30
  5060.4  453.90  5079.5  456.69  5137.1  459.71  5157.9  461.45  5166.0  461.30
  5215.6  466.40  5236.4  470.10  5250.8  471.51  5257.2  472.87  5307.6  476.24
#Mann=7,-1,0
  4683.3    0.05       0  4729.9     0.1       0  4830.7    0.16       0
  4979.5    0.05       0  4996.5    0.16       0  5020.5    0.07       0
  5026.5    0.16       0
Bank Sta=4994.1,5060.4
Exp/Cntr=0.3,0.1

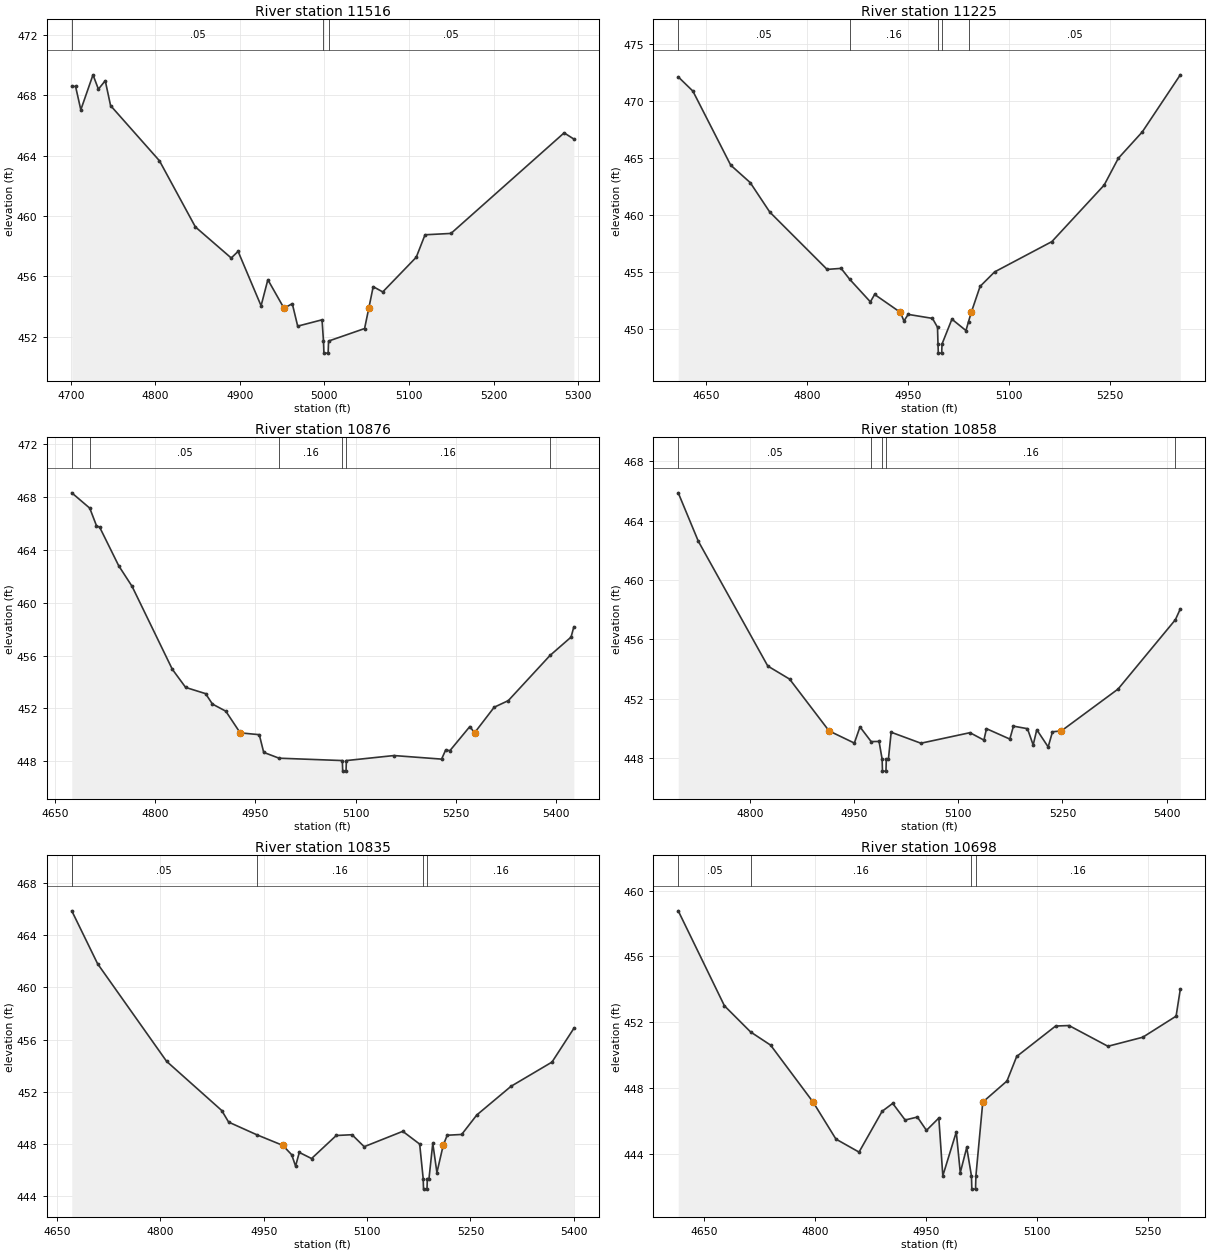
Type RM Length L Ch R = 1,11516,291,291,291
BEGIN DESCRIPTION:
XS3995A
END DESCRIPTION:
XS GIS Cut Line= 4
      2809934.37      7020739.68      2810121.89      7020502.68
      2810270.32      7020471.43      2810397.95      7020414.13
#Sta/Elev= 30
  4701.2  468.60  4705.7  468.60  4711.9  467.05  4726.3  469.37  4732.7  468.42
  4740.8  468.98  4747.1  467.33  4804.9  463.67  4847.4  459.28  4889.8  457.22
  4897.9  457.66  4925.1  454.05  4933.1  455.78  4952.2  453.89  4962.0  454.19
  4968.4  452.70  4997.2  453.12  4998.9  451.71  4999.4  450.91  5004.4  450.91
  5004.9  451.71  5047.5  452.54  5052.5  453.89  5057.7  455.32  5069.0  454.97
  5108.6  457.27  5119.0  458.76  5149.7  458.85  5283.5  465.52  5295.0  465.11
#Mann=3,-1,0
  4701.2    0.05       0  4998.9    0.04       0  5004.9    0.05       0
Bank Sta=4952.2,5052.5
Exp/Cntr=0.3,0.1

Type RM Length L Ch R = 1,11225,349,349,349
BEGIN DESCRIPTION:
UNT 170 in LFCCL Watershed 24.0
END DESCRIPTION:
XS GIS Cut Line= 3
      2809974.98      7020925.02      2810285.90      7020686.95
      2810525.03      7020424.97
#Sta/Elev= 30
  4608.4  472.11  4630.2  470.86  4686.4  464.36  4715.4  462.83  4744.5  460.24
  4829.7  455.21  4850.5  455.30  4863.3  454.34  4894.0  452.36  4900.3  453.01
  4938.6  451.44  4943.9  450.68  4950.2  451.26  4986.3  450.91  4993.8  450.13
  4994.5  448.66  4995.0  447.86  5000.0  447.86  5000.5  448.66  5015.2  450.84
  5036.1  449.84  5039.9  450.63  5044.0  451.44  5057.1  453.72  5078.7  454.99
  5163.8  457.65  5241.5  462.61  5262.5  464.96  5298.2  467.28  5354.7  472.29
#Mann=5,-1,0
  4608.4    0.05       0  4863.3    0.16       0  4994.5    0.07       0
  5000.5    0.16       0  5039.9    0.05       0
Bank Sta=4938.6,5044
Exp/Cntr=0.3,0.1

Type RM Length L Ch R = 1,10876,18,18,18
BEGIN DESCRIPTION:
Mapping XS 2d6aef22
END DESCRIPTION:
XS GIS Cut Line= 6
      2809994.91      7021017.68      2810283.11      7021035.04
      2810328.25      7021024.62      2810326.51      7020967.33
      2810361.24      7020840.59      2810483.84      7020648.92
#Sta/Elev= 30
  4675.2  468.33  4702.1  467.17  4712.1  465.85  4717.1  465.71  4745.4  462.81
  4765.5  461.24  4825.6  454.97  4845.6  453.59  4875.4  453.12  4885.7  452.33
  4905.7  451.79  4927.2  450.15  4955.8  450.01  4962.4  448.67  4985.4  448.23
  5080.1  448.05  5080.6  447.25  5085.6  447.25  5086.1  448.05  5157.3  448.43
  5228.6  448.16  5234.5  448.83  5241.2  448.81  5270.9  450.63  5277.9  450.15
  5307.3  452.09  5328.4  452.59  5390.8  456.01  5422.3  457.40  5426.5  458.18
#Mann=6,-1,0
  4675.2    0.08       0  4702.1    0.05       0  4985.4    0.16       0
  5080.1    0.07       0  5086.1    0.16       0  5390.8    0.05       0
Bank Sta=4927.2,5277.9
Exp/Cntr=0.3,0.1

Type RM Length L Ch R = 1,10858,23,23,23
BEGIN DESCRIPTION:
Mapping XS 87f5f157
END DESCRIPTION:
XS GIS Cut Line= 6
      2810026.14      7021048.93      2810324.78      7021045.45
      2810347.35      7021024.62      2810349.08      7020970.80
      2810382.07      7020837.12      2810500.09      7020673.98
#Sta/Elev= 30
  4697.0  465.88  4725.9  462.62  4825.9  454.21  4857.3  453.33  4914.1  449.84
  4950.5  449.02  4958.6  450.11  4974.7  449.12  4986.1  449.13  4990.5  447.93
  4991.0  447.13  4996.0  447.13  4996.5  447.93  4999.5  447.93  5003.5  449.75
  5046.3  449.01  5116.9  449.72  5137.0  449.22  5140.7  449.99  5174.3  449.29
  5179.5  450.16  5199.7  449.99  5207.9  448.89  5213.1  449.92  5229.5  448.76
  5235.7  449.78  5248.5  449.84  5330.1  452.66  5412.6  457.33  5419.7  458.06
#Mann=5,-1,0
  4697.0    0.05       0  4974.7    0.16       0  4990.5    0.07       0
  4996.5    0.16       0  5412.6    0.05       0
Bank Sta=4914.1,5248.5
Exp/Cntr=0.3,0.1

Type RM Length L Ch R = 1,10835,137,137,137
BEGIN DESCRIPTION:
Mapping XS cb514c2e
END DESCRIPTION:
XS GIS Cut Line= 6
      2810017.49      7021068.02      2810316.10      7021069.76
      2810359.50      7021052.40      2810371.65      7020995.11
      2810383.80      7020884.00      2810504.85      7020709.34
#Sta/Elev= 30
  4671.7  465.89  4709.2  461.82  4809.2  454.33  4889.2  450.55  4899.2  449.66
  4939.9  448.69  4977.8  447.87  4990.7  447.15  4996.3  446.28  5001.7  447.33
  5019.5  446.86  5055.3  448.63  5078.2  448.69  5095.8  447.77  5151.8  448.95
  5176.3  447.97  5181.4  445.31  5181.9  444.51  5186.9  444.51  5187.4  445.31
  5189.8  445.31  5195.3  448.03  5201.3  445.78  5210.4  447.87  5216.2  448.65
  5237.2  448.71  5259.2  450.21  5308.8  452.41  5368.2  454.27  5399.9  456.86
#Mann=4,-1,0
  4671.7    0.05       0  4939.9    0.16       0  5181.4    0.07       0
  5187.4    0.16       0
Bank Sta=4977.8,5210.4
Exp/Cntr=0.3,0.1

Type RM Length L Ch R = 1,10698,279,279,279
BEGIN DESCRIPTION:
XS3997A
END DESCRIPTION:
XS GIS Cut Line= 3
      2810121.05      7021320.38      2810412.68      7021219.70
      2810558.38      7020879.73
#Sta/Elev= 30
  4615.0  458.77  4677.4  453.00  4712.8  451.41  4739.8  450.61  4797.2  447.15
  4828.1  444.90  4859.3  444.11  4890.5  446.59  4904.8  447.07  4921.6  446.06
  4938.1  446.24  4950.4  445.43  4967.1  446.18  4972.5  442.67  4990.7  445.33
  4996.1  442.86  5004.8  444.39  5011.2  442.66  5011.7  441.86  5016.7  441.86
  5017.2  442.66  5026.5  447.15  5059.2  448.43  5072.3  449.92  5124.9  451.77
  5143.0  451.80  5195.6  450.54  5242.7  451.09  5287.7  452.37  5293.4  454.01
#Mann=4,-1,0
  4615.0    0.05       0  4712.8    0.16       0  5011.2    0.07       0
  5017.2    0.16       0
Bank Sta=4797.2,5026.5
Exp/Cntr=0.3,0.1

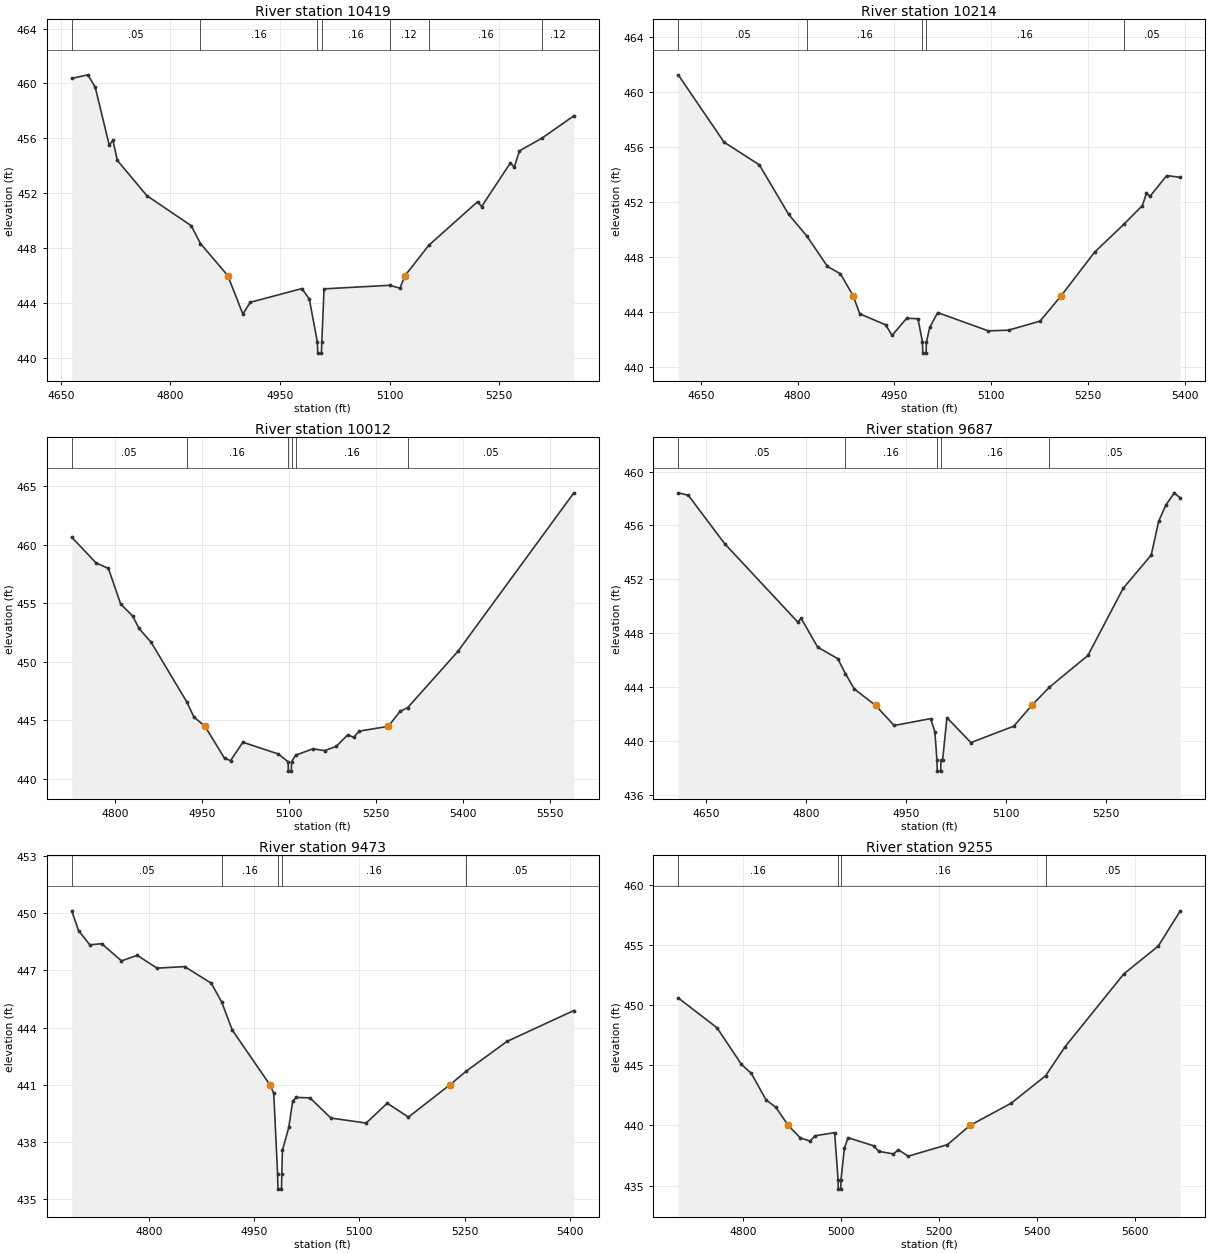
Type RM Length L Ch R = 1,10419,205,205,205
BEGIN DESCRIPTION:
UNT 170 in LFCCL Watershed 22.0
END DESCRIPTION:
XS GIS Cut Line= 3
      2810123.19      7021352.19      2810473.16      7021402.18
      2810771.61      7021252.96
#Sta/Elev= 30
  4665.0  460.37  4687.0  460.63  4697.1  459.73  4716.3  455.49  4721.3  455.86
  4727.4  454.38  4767.8  451.81  4828.5  449.62  4841.1  448.32  4878.5  445.98
  4899.2  443.17  4909.3  444.03  4980.0  445.03  4990.1  444.27  5001.2  441.12
  5001.7  440.32  5006.7  440.32  5007.2  441.12  5010.3  445.01  5100.0  445.27
  5114.2  445.06  5121.2  445.98  5153.5  448.18  5220.4  451.37  5226.0  451.02
  5265.2  454.19  5270.8  453.91  5277.7  455.08  5308.9  456.02  5352.2  457.64
#Mann=7,-1,0
  4665.0    0.05       0  4841.1    0.16       0  5001.2    0.07       0
  5007.2    0.16       0  5100.0    0.12       0  5153.5    0.16       0
  5308.9    0.12       0
Bank Sta=4878.5,5121.2
Exp/Cntr=0.3,0.1

Type RM Length L Ch R = 1,10214,202,202,202
BEGIN DESCRIPTION:
XS3998A
END DESCRIPTION:
XS GIS Cut Line= 3
      2810114.08      7021615.53      2810506.43      7021598.17
      2810870.50      7021473.35
#Sta/Elev= 30
  4615.2  461.25  4686.2  456.35  4740.8  454.70  4786.3  451.09  4814.7  449.50
  4846.3  447.31  4866.4  446.77  4885.9  445.19  4896.4  443.86  4936.4  443.06
  4946.4  442.29  4969.0  443.54  4986.5  443.50  4993.5  441.80  4994.0  441.00
  4999.0  441.00  4999.5  441.80  5004.7  442.87  5017.0  443.95  5095.5  442.62
  5126.8  442.67  5175.6  443.33  5208.5  445.19  5260.1  448.35  5305.7  450.39
  5334.1  451.74  5340.4  452.63  5345.7  452.40  5371.7  453.92  5392.8  453.79
#Mann=5,-1,0
  4615.2    0.05       0  4814.7    0.16       0  4993.5    0.07       0
  4999.5    0.16       0  5305.7    0.05       0
Bank Sta=4885.9,5208.5
Exp/Cntr=0.3,0.1

Type RM Length L Ch R = 1,10012,325,325,325
BEGIN DESCRIPTION:
UNT 170 in LFCCL Watershed 21.0
END DESCRIPTION:
XS GIS Cut Line= 3
      2810275.05      7021874.98      2810575.00      7021775.00
      2811125.02      7021775.00
#Sta/Elev= 30
  4724.8  460.64  4766.9  458.44  4788.0  457.98  4809.1  454.94  4830.2  453.89
  4840.7  452.85  4861.8  451.66  4922.8  446.60  4935.6  445.27  4954.7  444.48
  4988.3  441.75  4998.8  441.55  5019.9  443.12  5081.0  442.12  5098.0  441.45
  5098.5  440.65  5103.5  440.65  5104.0  441.45  5111.0  442.01  5141.0  442.56
  5161.0  442.40  5181.0  442.76  5201.0  443.76  5211.0  443.54  5221.0  444.07
  5270.9  444.48  5291.0  445.75  5304.4  446.08  5391.0  450.89  5591.0  464.44
#Mann=6,-1,0
  4724.8    0.05       0  4922.8    0.16       0  5098.0    0.07       0
  5104.0    0.16       0  5111.0    0.16       0  5304.4    0.05       0
Bank Sta=4954.7,5270.9
Exp/Cntr=0.3,0.1

Type RM Length L Ch R = 1,9687,214,214,214
BEGIN DESCRIPTION:
UNT 170 in LFCCL Watershed 20.0
END DESCRIPTION:
XS GIS Cut Line= 3
      2810324.95      7021924.98      2810691.49      7022065.10
      2811024.96      7021925.02
#Sta/Elev= 30
  4607.6  458.42  4622.7  458.24  4677.4  454.64  4787.0  448.83  4792.3  449.09
  4817.1  446.95  4847.1  446.11  4858.8  444.99  4871.8  443.86  4903.9  442.64
  4931.9  441.14  4986.7  441.65  4993.1  440.66  4996.2  438.55  4996.7  437.75
  5001.7  437.75  5002.2  438.55  5004.6  438.55  5011.2  441.72  5047.2  439.87
  5111.6  441.09  5138.7  442.64  5165.0  443.98  5222.9  446.34  5275.9  451.33
  5318.0  453.80  5329.2  456.31  5340.1  457.52  5352.6  458.41  5361.7  458.04
#Mann=5,-1,0
  4607.6    0.05       0  4858.8    0.16       0  4996.2    0.07       0
  5002.2    0.16       0  5165.0    0.05       0
Bank Sta=4903.9,5138.7
Exp/Cntr=0.3,0.1

Type RM Length L Ch R = 1,9473,218,218,218
BEGIN DESCRIPTION:
XS3999A
END DESCRIPTION:
XS GIS Cut Line= 3
      2810336.33      7022119.02      2810607.13      7022250.95
      2811020.17      7022223.18
#Sta/Elev= 30
  4690.3  450.11  4699.9  449.08  4716.0  448.33  4733.0  448.39  4761.1  447.49
  4783.6  447.78  4811.7  447.11  4851.2  447.19  4889.0  446.32  4903.8  445.34
  4918.9  443.87  4972.6  441.00  4978.0  440.56  4983.5  436.34  4984.0  435.54
  4989.0  435.54  4989.5  436.34  4990.4  437.57  4999.4  438.77  5005.0  440.15
  5010.0  440.34  5029.5  440.32  5059.5  439.26  5109.7  439.00  5139.7  440.04
  5169.8  439.31  5228.9  441.00  5252.4  441.72  5310.1  443.27  5405.5  444.89
#Mann=5,-1,0
  4690.3    0.05       0  4903.8    0.16       0  4983.5    0.07       0
  4989.5    0.16       0  5252.4    0.05       0
Bank Sta=4972.6,5228.9
Exp/Cntr=0.3,0.1

Type RM Length L Ch R = 1,9255,381,381,381
BEGIN DESCRIPTION:
UNT 170 in LFCCL Watershed 19.0
END DESCRIPTION:
XS GIS Cut Line= 3
      2810325.91      7022434.97      2810675.00      7022425.00
      2811350.05      7022448.86
#Sta/Elev= 30
  4667.9  450.61  4747.0  448.13  4797.0  445.08  4817.1  444.33  4847.1  442.13
  4867.1  441.51  4892.4  440.00  4917.1  438.96  4937.1  438.70  4947.1  439.14
  4987.1  439.40  4994.1  435.50  4994.6  434.70  4999.6  434.70  5000.1  435.50
  5007.1  438.13  5014.6  438.98  5067.2  438.30  5077.2  437.84  5107.2  437.63
  5117.2  437.98  5137.2  437.44  5217.3  438.40  5263.3  440.00  5347.3  441.85
  5417.6  444.13  5457.4  446.55  5577.5  452.62  5647.5  454.92  5692.6  457.86
#Mann=4,-1,0
  4667.9    0.16       0  4994.1    0.07       0  5000.1    0.16       0
  5417.6    0.05       0
Bank Sta=4892.4,5263.3
Exp/Cntr=0.3,0.1