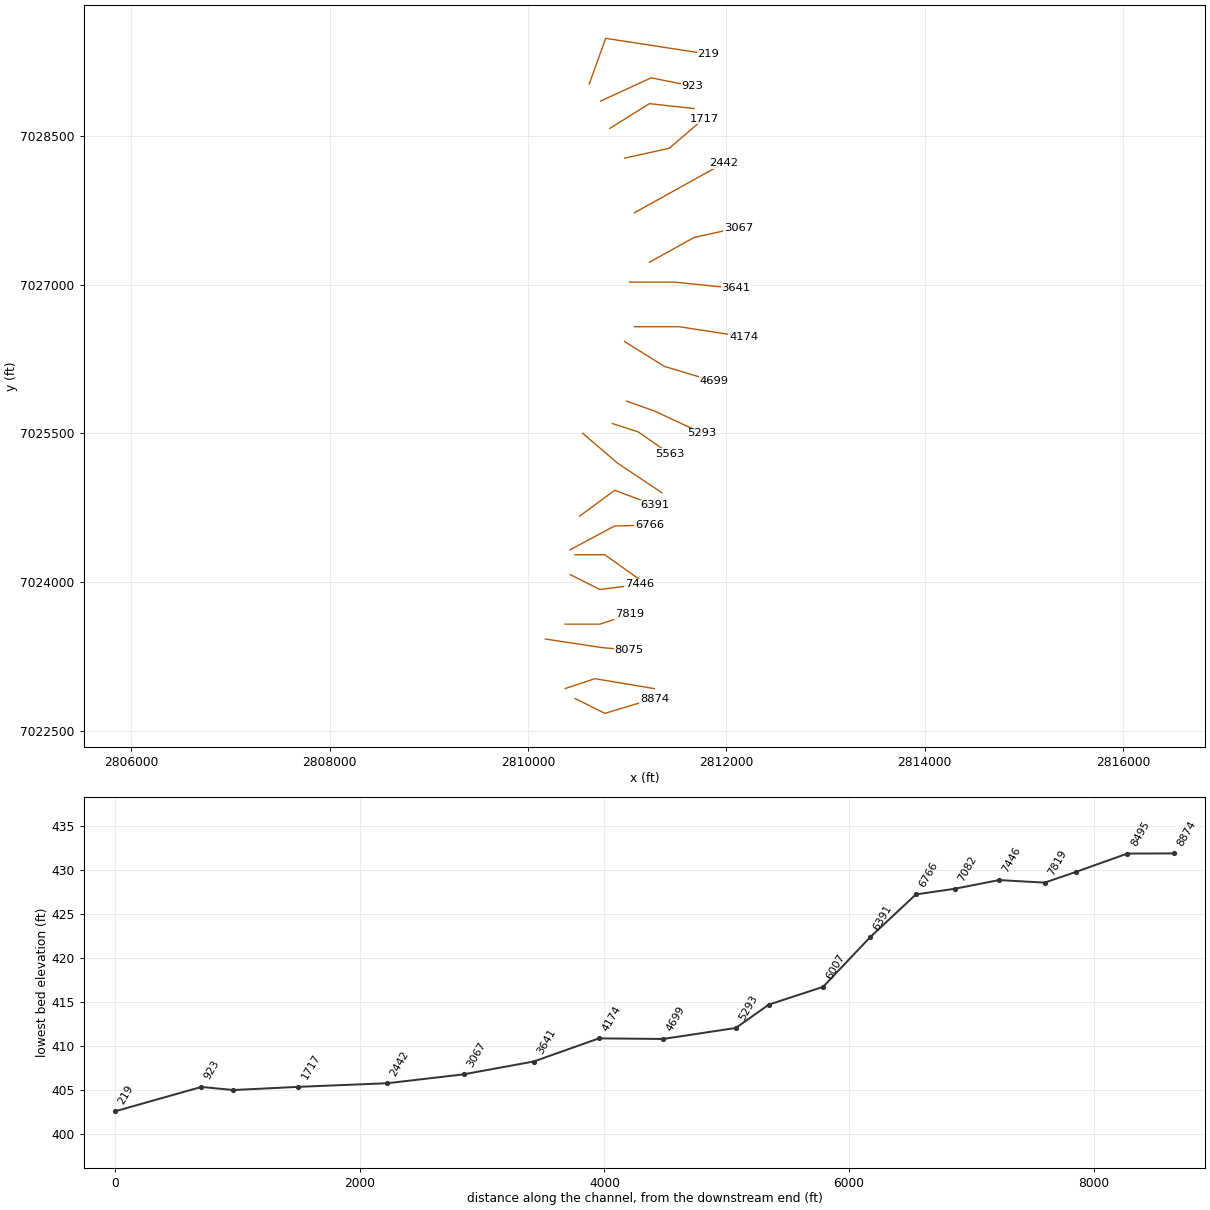
HEC-RAS study UNT 170 in LFCCL Watershed.prj: UNT 170 in LFCCL Watershed Base Level Engineering

--- UNT 170 in LFCCL Watershed.g01 (geometry) --- (continued)

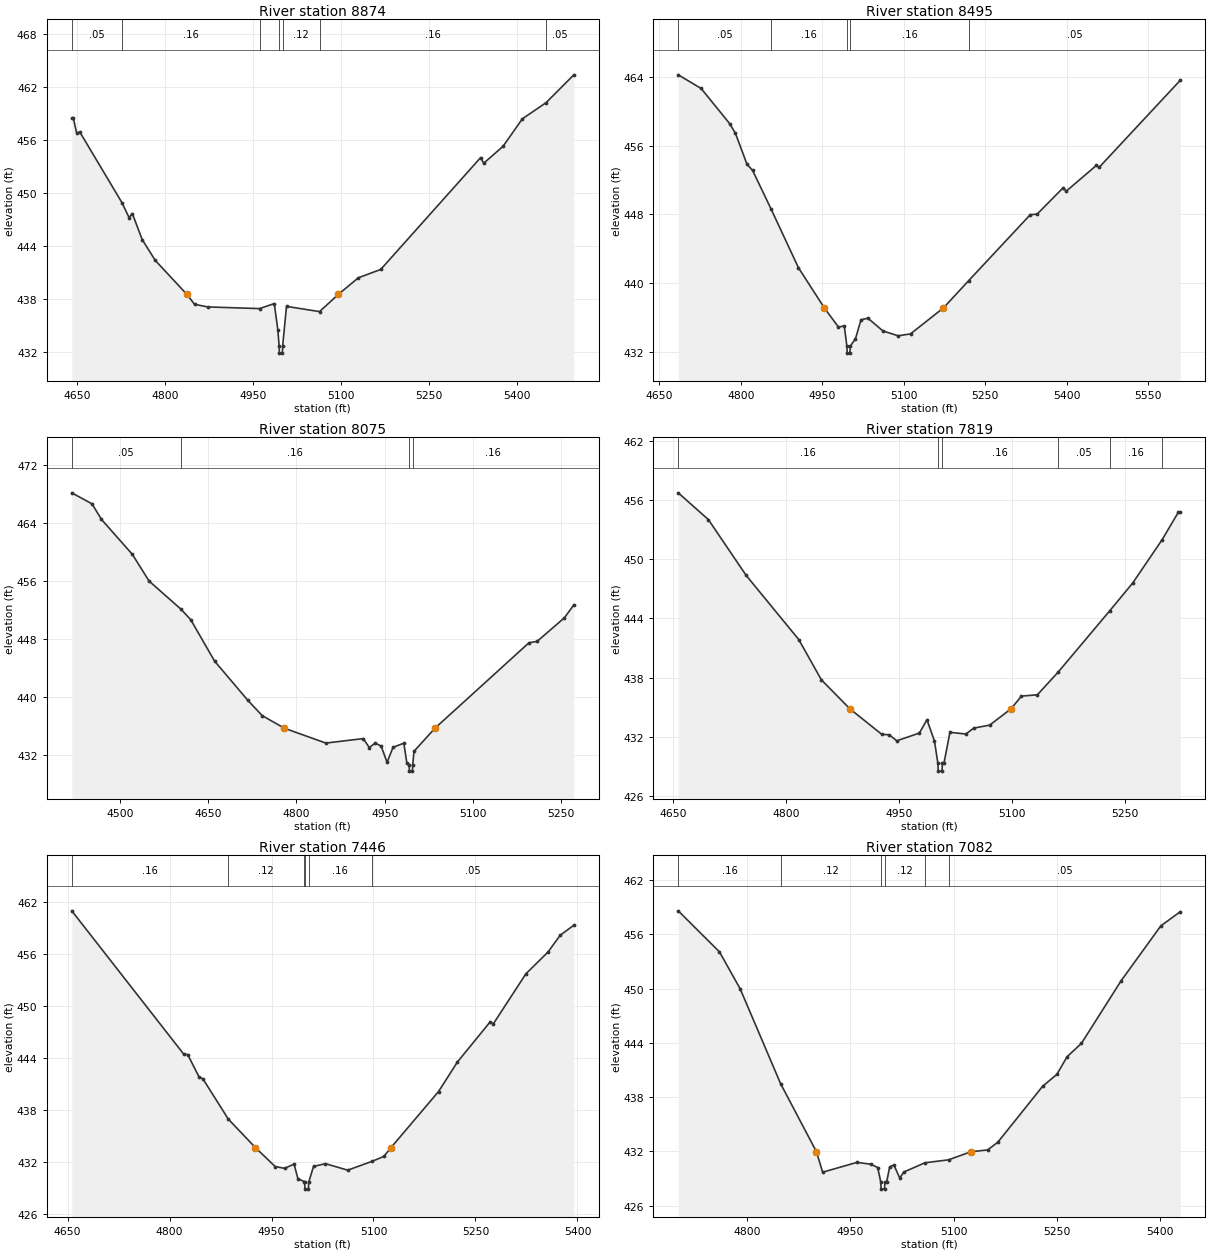
Type RM Length L Ch R = 1,8874,379,379,379
BEGIN DESCRIPTION:
UNT 170 in LFCCL Watershed 18.0
END DESCRIPTION:
XS GIS Cut Line= 3
      2810475.03      7022824.98      2810775.00      7022675.00
      2811275.01      7022825.00
#Sta/Elev= 30
  4640.5  458.42  4643.3  458.42  4648.8  456.78  4654.4  456.86  4726.3  448.87
  4738.3  447.19  4743.9  447.65  4760.7  444.71  4783.0  442.35  4837.2  438.49
  4850.1  437.38  4872.5  437.08  4961.3  436.89  4986.3  437.46  4992.4  434.50
  4994.6  432.65  4995.1  431.85  5000.1  431.85  5000.6  432.65  5007.2  437.14
  5063.6  436.55  5095.6  438.49  5129.9  440.38  5168.1  441.32  5338.7  453.98
  5343.9  453.34  5377.0  455.26  5410.0  458.37  5450.7  460.21  5497.9  463.35
#Mann=7,-1,0
  4640.5    0.05       0  4726.3    0.16       0  4961.3    0.12       0
  4994.6    0.07       0  5000.6    0.12       0  5063.6    0.16       0
  5450.7    0.05       0
Bank Sta=4837.2,5095.6
Exp/Cntr=0.3,0.1

Type RM Length L Ch R = 1,8495,420,420,420
BEGIN DESCRIPTION:
UNT 170 in LFCCL Watershed 17.0
END DESCRIPTION:
XS GIS Cut Line= 3
      2810375.01      7022925.00      2810675.00      7023025.00
      2811275.00      7022925.00
#Sta/Elev= 30
  4685.0  464.24  4727.2  462.65  4779.9  458.54  4790.4  457.42  4811.5  453.84
  4822.0  453.10  4855.6  448.66  4906.4  441.77  4954.0  437.10  4980.1  434.86
  4990.7  435.01  4995.6  432.63  4996.1  431.83  5001.1  431.83  5001.6  432.63
  5011.4  433.51  5021.5  435.71  5034.2  435.90  5062.0  434.41  5089.9  433.85
  5112.7  434.07  5173.4  437.10  5219.8  440.27  5333.2  447.95  5345.9  448.02
  5394.1  451.11  5399.1  450.67  5454.9  453.69  5460.0  453.46  5609.5  463.61
#Mann=5,-1,0
  4685.0    0.05       0  4855.6    0.16       0  4995.6    0.07       0
  5001.6    0.16       0  5219.8    0.05       0
Bank Sta=4954,5173.4
Exp/Cntr=0.3,0.1

Type RM Length L Ch R = 1,8075,256,256,256
BEGIN DESCRIPTION:
UNT 170 in LFCCL Watershed 16.0
END DESCRIPTION:
XS GIS Cut Line= 3
      2810175.04      7023424.99      2810750.48      7023337.85
      2811020.97      7023314.52
#Sta/Elev= 30
  4418.0  468.15  4452.4  466.63  4468.5  464.48  4521.1  459.65  4549.4  455.98
  4603.4  452.11  4620.2  450.65  4660.7  444.94  4717.4  439.51  4741.6  437.42
  4779.1  435.68  4849.9  433.62  4913.5  434.24  4923.8  433.00  4933.8  433.62
  4943.9  433.21  4954.0  430.96  4964.1  433.03  4982.5  433.61  4987.5  430.94
  4991.5  430.55  4992.0  429.75  4997.0  429.75  4997.5  430.55  4999.8  432.49
  5035.5  435.68  5195.2  447.46  5209.0  447.65  5255.5  450.91  5271.5  452.69
#Mann=4,-1,0
  4418.0    0.05       0  4603.4    0.16       0  4991.5    0.07       0
  4997.5    0.16       0
Bank Sta=4779.1,5035.5
Exp/Cntr=0.3,0.1

Type RM Length L Ch R = 1,7819,373,373,373
BEGIN DESCRIPTION:
UNT 170 in LFCCL Watershed 15.0
END DESCRIPTION:
XS GIS Cut Line= 3
      2810375.01      7023575.00      2810725.00      7023575.00
      2811024.99      7023675.00
#Sta/Elev= 30
  4657.3  456.72  4697.3  454.01  4747.3  448.37  4817.3  441.85  4847.3  437.77
  4885.1  434.84  4927.3  432.26  4937.3  432.21  4947.3  431.60  4977.3  432.39
  4987.3  433.74  4997.3  431.58  5001.8  429.33  5002.3  428.53  5007.3  428.53
  5007.8  429.33  5009.9  429.33  5017.8  432.46  5038.9  432.29  5049.5  432.89
  5070.5  433.19  5098.9  434.84  5112.7  436.13  5133.8  436.26  5161.3  438.55
  5229.6  444.75  5260.3  447.58  5299.2  451.95  5320.9  454.75  5323.5  454.75
#Mann=6,-1,0
  4657.3    0.16       0  5001.8    0.07       0  5007.8    0.16       0
  5161.3    0.05       0  5229.6    0.16       0  5299.2    0.05       0
Bank Sta=4885.1,5098.9
Exp/Cntr=0.3,0.1

Type RM Length L Ch R = 1,7446,364,364,364
BEGIN DESCRIPTION:
UNT 170 in LFCCL Watershed 14.0
END DESCRIPTION:
XS GIS Cut Line= 3
      2810425.01      7024075.00      2810725.00      7023925.00
      2811124.99      7023975.00
#Sta/Elev= 30
  4656.2  460.95  4821.1  444.38  4826.7  444.36  4843.5  441.76  4849.1  441.55
  4886.6  436.89  4926.4  433.61  4955.3  431.43  4969.2  431.22  4983.2  431.71
  4988.8  430.03  4997.8  429.70  4998.7  429.62  4999.2  428.82  5004.2  428.82
  5004.7  429.62  5011.8  431.44  5029.4  431.76  5062.1  431.01  5097.3  432.01
  5115.1  432.59  5125.7  433.61  5195.7  440.09  5223.4  443.49  5271.3  448.10
  5276.3  447.91  5324.2  453.68  5356.9  456.21  5374.6  458.13  5394.7  459.29
#Mann=6,-1,0
  4656.2    0.16       0  4886.6    0.12       0  4997.8    0.16       0
  4998.7    0.07       0  5004.7    0.16       0  5097.3    0.05       0
Bank Sta=4926.4,5125.7
Exp/Cntr=0.3,0.1

Type RM Length L Ch R = 1,7082,316,316,316
BEGIN DESCRIPTION:
UNT 170 in LFCCL Watershed 13.0
END DESCRIPTION:
XS GIS Cut Line= 3
      2810475.01      7024275.00      2810775.00      7024275.00
      2811124.99      7024025.01
#Sta/Elev= 30
  4699.7  458.59  4759.7  454.05  4789.7  449.98  4848.6  439.48  4900.7  431.96
  4909.7  429.70  4959.7  430.79  4979.7  430.58  4989.7  430.22  4994.2  428.63
  4994.7  427.83  4999.7  427.83  5000.2  428.63  5002.8  428.63  5007.1  430.27
  5013.2  430.51  5021.8  429.06  5028.0  429.73  5058.4  430.74  5092.9  431.07
  5125.1  431.96  5149.6  432.16  5164.4  433.01  5229.5  439.19  5250.4  440.52
  5265.1  442.46  5286.0  443.94  5343.8  450.87  5401.5  456.93  5429.8  458.49
#Mann=6,-1,0
  4699.7    0.16       0  4848.6    0.12       0  4994.2    0.07       0
  5000.2    0.12       0  5058.4    0.16       0  5092.9    0.05       0
Bank Sta=4900.7,5125.1
Exp/Cntr=0.3,0.1

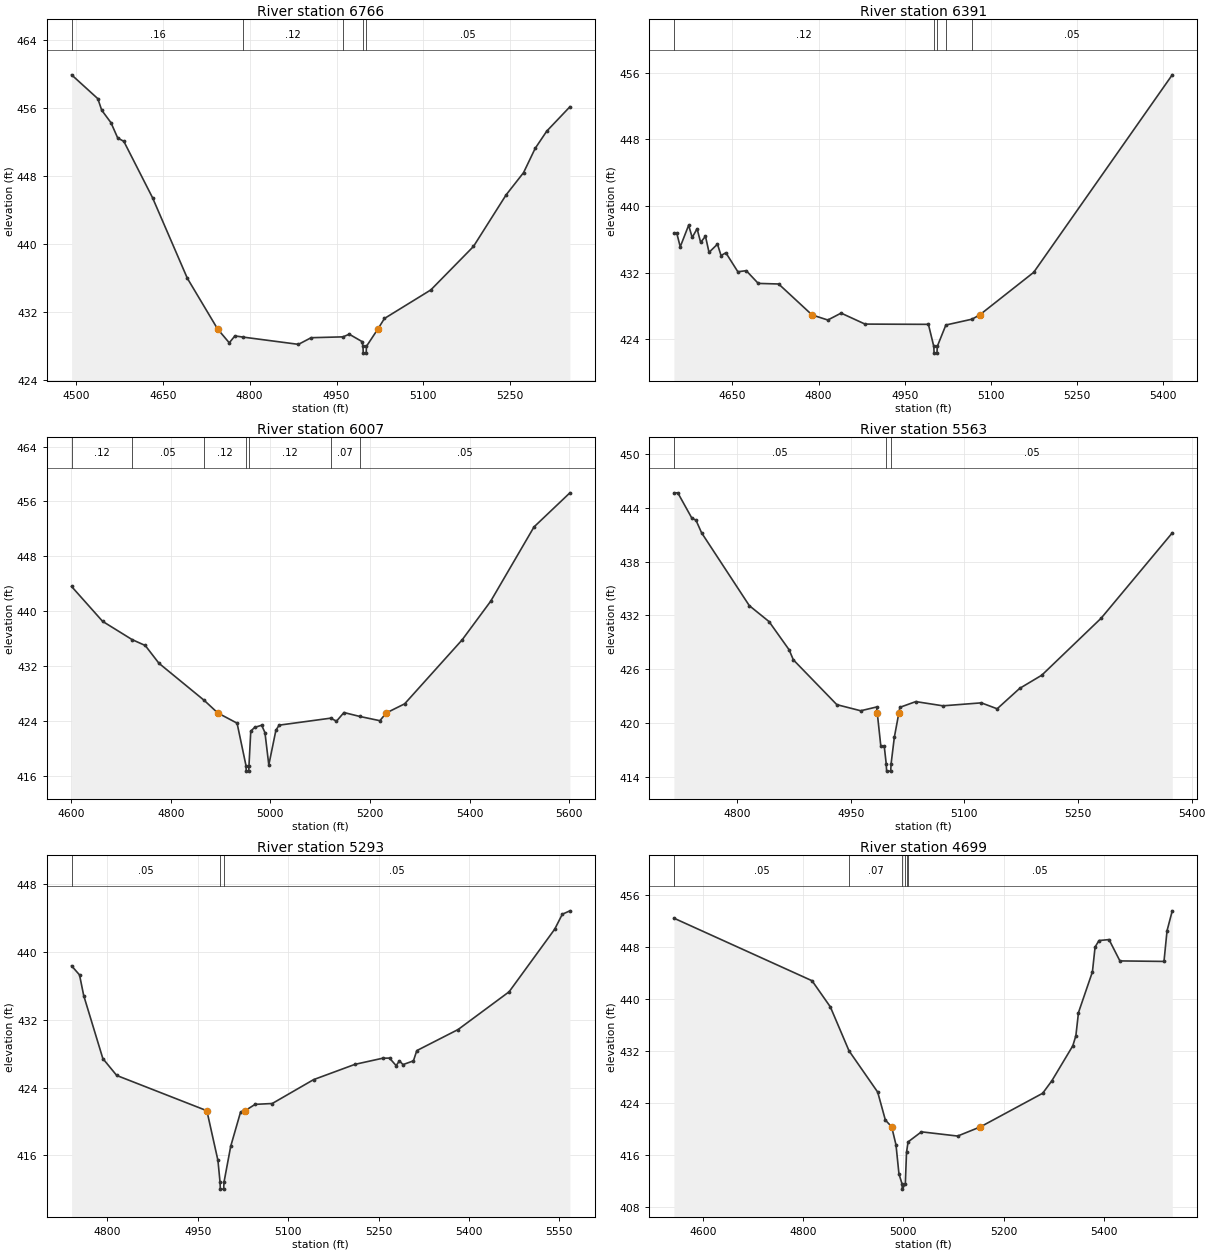
Type RM Length L Ch R = 1,6766,375,375,375
BEGIN DESCRIPTION:
UNT 170 in LFCCL Watershed 12.0
END DESCRIPTION:
XS GIS Cut Line= 3
      2810425.04      7024325.02      2810872.26      7024564.50
      2811225.00      7024575.00
#Sta/Elev= 30
  4492.7  459.86  4538.0  457.06  4544.7  455.71  4560.7  454.24  4572.3  452.45
  4582.9  452.05  4632.4  445.44  4692.5  435.98  4744.8  430.02  4764.9  428.40
  4774.6  429.21  4789.0  429.07  4884.3  428.22  4906.2  429.00  4961.2  429.10
  4972.0  429.41  4994.0  428.55  4995.7  427.99  4996.2  427.19  5001.2  427.19
  5001.7  427.99  5021.4  430.02  5032.8  431.26  5112.8  434.61  5186.4  439.71
  5242.8  445.77  5272.9  448.38  5292.9  451.22  5312.9  453.25  5352.9  456.11
#Mann=5,-1,0
  4492.7    0.16       0  4789.0    0.12       0  4961.2    0.05       0
  4995.7    0.03       0  5001.7    0.05       0
Bank Sta=4744.8,5021.4
Exp/Cntr=0.3,0.1

Type RM Length L Ch R = 1,6391,384,384,384
BEGIN DESCRIPTION:
UNT 170 in LFCCL Watershed 11.0
END DESCRIPTION:
XS GIS Cut Line= 3
      2810520.30      7024664.13      2810875.00      7024925.00
      2811275.00      7024775.00
#Sta/Elev= 30
  4548.3  436.72  4553.3  436.72  4559.3  435.10  4573.9  437.69  4580.1  436.22
  4588.6  437.27  4594.8  435.63  4603.2  436.37  4609.4  434.43  4624.1  435.42
  4630.3  434.05  4638.7  434.38  4659.6  432.10  4674.2  432.23  4695.1  430.70
  4730.6  430.63  4788.8  426.91  4816.2  426.30  4839.3  427.13  4881.0  425.81
  4991.3  425.78  5000.7  423.12  5001.2  422.32  5006.2  422.32  5006.7  423.12
  5021.7  425.70  5067.2  426.40  5080.5  426.91  5174.6  432.03  5415.8  455.77
#Mann=5,-1,0
  4548.3    0.12       0  5000.7    0.07       0  5006.7    0.12       0
  5021.7    0.07       0  5067.2    0.05       0
Bank Sta=4788.8,5080.5
Exp/Cntr=0.3,0.1

Type RM Length L Ch R = 1,6007,444,444,444
BEGIN DESCRIPTION:
UNT 170 in LFCCL Watershed 10.0
END DESCRIPTION:
XS GIS Cut Line= 3
      2810552.05      7025500.03      2810902.08      7025200.00
      2811351.04      7024900.70
#Sta/Elev= 30
  4601.0  443.60  4663.3  438.52  4722.5  435.86  4748.9  435.00  4776.4  432.41
  4867.5  426.99  4894.5  425.17  4933.3  423.68  4951.2  417.49  4951.7  416.69
  4956.7  416.69  4957.2  417.49  4960.8  422.52  4968.5  423.06  4982.7  423.38
  4989.3  422.29  4997.0  417.59  5011.3  422.66  5017.8  423.39  5121.3  424.41
  5132.9  423.97  5147.9  425.23  5179.6  424.66  5220.0  424.04  5232.9  425.17
  5269.8  426.50  5385.3  435.83  5442.4  441.44  5529.5  452.28  5601.6  457.25
#Mann=7,-1,0
  4601.0    0.12       0  4722.5    0.05       0  4867.5    0.12       0
  4951.2    0.07       0  4957.2    0.12       0  5121.3    0.07       0
  5179.6    0.05       0
Bank Sta=4894.5,5232.9
Exp/Cntr=0.3,0.1

Type RM Length L Ch R = 1,5563,270,270,270
BEGIN DESCRIPTION:
XS4000A
END DESCRIPTION:
XS GIS Cut Line= 3
      2810850.22      7025598.16      2811110.60      7025514.83
      2811426.58      7025296.08
#Sta/Elev= 30
  4716.7  445.65  4721.8  445.65  4740.5  442.81  4745.7  442.62  4753.2  441.20
  4816.2  433.09  4842.2  431.32  4868.7  428.18  4874.3  427.06  4931.7  422.07
  4963.2  421.39  4984.2  421.81  4985.1  421.12  4989.8  417.42  4994.3  417.42
  4996.9  415.47  4997.4  414.67  5002.8  414.67  5003.3  415.47  5007.6  418.44
  5013.5  421.12  5014.9  421.77  5035.9  422.41  5071.7  421.94  5122.4  422.27
  5143.3  421.61  5173.0  423.88  5202.2  425.35  5280.5  431.69  5374.4  441.19
#Mann=3,-1,0
  4716.7    0.05       0  4996.9    0.03       0  5003.3    0.05       0
Bank Sta=4985.1,5013.5
Exp/Cntr=0.3,0.1

Type RM Length L Ch R = 1,5293,594,594,594
BEGIN DESCRIPTION:
UNT 170 in LFCCL Watershed 9.0
END DESCRIPTION:
XS GIS Cut Line= 3
      2810996.05      7025823.85      2811275.00      7025725.00
      2811756.46      7025500.93
#Sta/Elev= 30
  4740.6  438.36  4753.8  437.29  4760.7  434.86  4792.5  427.42  4815.5  425.43
  4965.1  421.27  4983.5  415.40  4987.0  412.82  4987.5  412.02  4993.0  412.02
  4993.5  412.82  5004.7  417.08  5021.1  421.13  5028.5  421.27  5045.2  422.02
  5073.6  422.12  5142.3  424.94  5210.9  426.74  5256.7  427.46  5268.2  427.48
  5279.2  426.59  5284.7  427.15  5290.6  426.71  5307.9  427.15  5313.5  428.36
  5382.1  430.85  5466.7  435.30  5542.3  442.68  5555.0  444.45  5567.6  444.85
#Mann=3,-1,0
  4740.6    0.05       0  4987.0    0.03       0  4993.5    0.05       0
Bank Sta=4965.1,5028.5
Exp/Cntr=0.3,0.1

Type RM Length L Ch R = 1,4699,525,525,525
BEGIN DESCRIPTION:
UNT 170 in LFCCL Watershed 8.0
END DESCRIPTION:
XS GIS Cut Line= 3
      2810974.97      7026425.02      2811375.00      7026175.00
      2811874.96      7026025.01
#Sta/Elev= 30
  4542.4  452.43  4817.8  442.81  4854.3  438.79  4891.5  432.04  4948.7  425.69
  4964.0  421.39  4976.6  420.35  4985.2  417.58  4991.1  413.12  4997.3  411.57
  4997.8  410.77  5003.8  411.57  5006.2  416.43  5009.3  418.03  5035.9  419.58
  5108.1  418.93  5153.7  420.35  5277.7  425.51  5296.0  427.43  5337.8  432.81
  5343.9  434.36  5349.1  437.92  5376.9  444.18  5382.2  448.00  5390.0  448.99
  5410.0  449.14  5431.7  445.86  5519.6  445.78  5525.7  450.50  5536.1  453.56
#Mann=6,-1,0
  4542.4    0.05       0  4891.5    0.07       0  4997.3    0.07       0
  5003.8    0.07       0  5006.2    0.12       0  5009.3    0.05       0
Bank Sta=4976.6,5153.7
Exp/Cntr=0.3,0.1

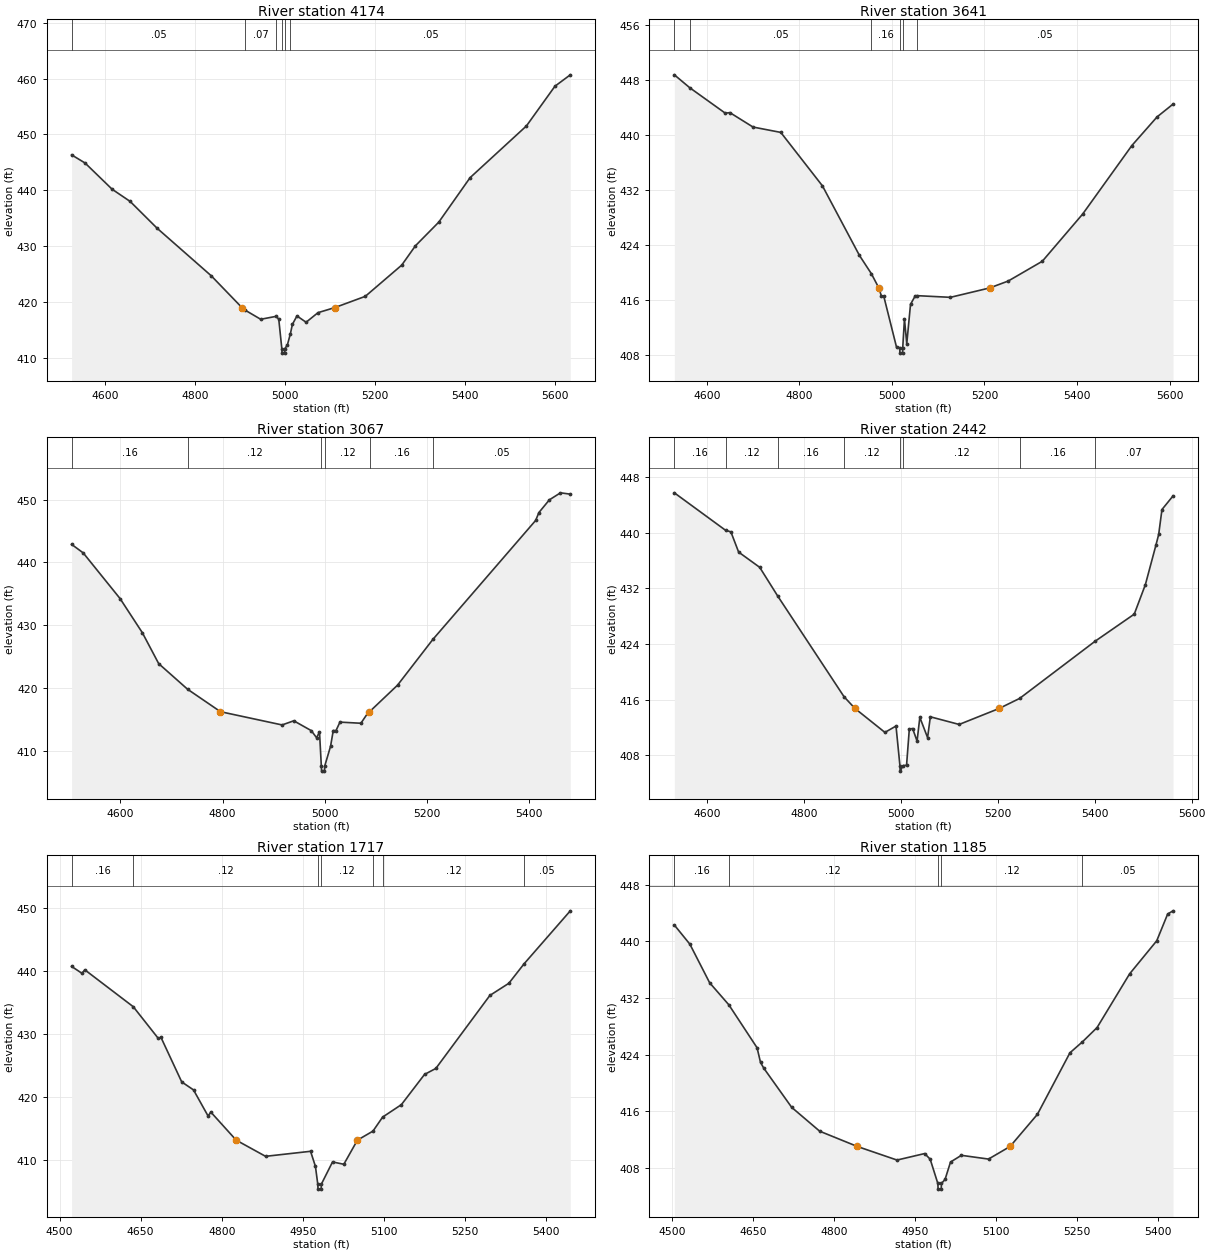
Type RM Length L Ch R = 1,4174,533,533,533
BEGIN DESCRIPTION:
UNT 170 in LFCCL Watershed 7.0
END DESCRIPTION:
XS GIS Cut Line= 3
      2811075.05      7026575.00      2811525.00      7026575.00
      2812175.00      7026475.00
#Sta/Elev= 30
  4526.5  446.35  4556.5  444.88  4616.5  440.19  4656.5  438.01  4716.5  433.20
  4836.5  424.70  4904.9  418.99  4912.7  418.50  4946.5  416.90  4980.9  417.43
  4986.6  416.91  4993.4  411.64  4993.9  410.84  4999.4  410.84  4999.9  411.64
  5005.5  412.24  5012.3  414.27  5016.9  415.99  5027.0  417.50  5047.3  416.37
  5073.8  418.09  5110.9  418.99  5178.8  421.01  5259.7  426.60  5290.1  430.06
  5342.0  434.30  5411.5  442.26  5536.7  451.53  5600.0  458.64  5634.1  460.68
#Mann=6,-1,0
  4526.5    0.05       0  4912.7    0.07       0  4980.9    0.12       0
  4993.4    0.07       0  4999.9    0.12       0  5012.3    0.05       0
Bank Sta=4904.9,5110.9
Exp/Cntr=0.3,0.1

Type RM Length L Ch R = 1,3641,574,574,574
BEGIN DESCRIPTION:
UNT 170 in LFCCL Watershed 6.0
END DESCRIPTION:
XS GIS Cut Line= 3
      2811024.98      7027025.00      2811475.00      7027025.00
      2812099.31      7026961.02
#Sta/Elev= 30
  4529.9  448.71  4563.2  446.83  4639.9  443.13  4649.9  443.21  4699.9  441.11
  4759.9  440.33  4849.9  432.55  4929.9  422.42  4955.6  419.77  4971.7  417.70
  4977.4  416.49  4982.4  416.49  5010.1  409.04  5016.8  409.01  5017.3  408.21
  5022.9  408.21  5023.4  409.01  5027.1  413.17  5032.1  409.59  5040.2  415.31
  5050.3  416.53  5055.2  416.57  5126.4  416.33  5211.4  417.70  5251.3  418.70
  5325.0  421.58  5412.2  428.45  5518.5  438.42  5573.0  442.59  5607.5  444.45
#Mann=6,-1,0
  4529.9    0.16       0  4563.2    0.05       0  4955.6    0.16       0
  5016.8    0.07       0  5023.4    0.16       0  5055.2    0.05       0
Bank Sta=4971.7,5211.4
Exp/Cntr=0.3,0.1

Type RM Length L Ch R = 1,3067,625,625,625
BEGIN DESCRIPTION:
UNT 170 in LFCCL Watershed 5.0
END DESCRIPTION:
XS GIS Cut Line= 3
      2811225.03      7027225.02      2811675.00      7027475.00
      2812124.98      7027575.00
#Sta/Elev= 30
  4504.6  442.89  4527.4  441.52  4599.5  434.24  4643.0  428.81  4675.0  423.88
  4731.5  419.80  4795.9  416.22  4916.4  414.11  4939.3  414.77  4973.6  413.20
  4983.9  412.07  4989.6  413.00  4993.2  407.55  4993.7  406.75  4999.3  406.75
  4999.8  407.55  5011.3  410.73  5016.5  413.21  5021.9  413.21  5029.6  414.56
  5070.6  414.38  5085.9  416.22  5089.0  416.33  5142.3  420.45  5211.3  427.73
  5412.5  446.70  5418.9  447.96  5439.3  449.98  5461.1  451.10  5480.3  450.89
#Mann=6,-1,0
  4504.6    0.16       0  4731.5    0.12       0  4993.2    0.07       0
  4999.8    0.12       0  5089.0    0.16       0  5211.3    0.05       0
Bank Sta=4795.9,5085.9
Exp/Cntr=0.3,0.1

Type RM Length L Ch R = 1,2442,725,725,725
BEGIN DESCRIPTION:
UNT 170 in LFCCL Watershed 4.0
END DESCRIPTION:
XS GIS Cut Line= 3
      2811074.97      7027724.98      2811525.00      7027975.00
      2811975.00      7028225.00
#Sta/Elev= 30
  4532.0  445.75  4637.6  440.37  4648.7  440.14  4664.7  437.23  4708.2  435.04
  4745.2  430.93  4882.4  416.43  4904.9  414.75  4966.7  411.31  4989.6  412.22
  4997.7  406.54  4998.2  405.74  5004.4  406.54  5011.4  406.58  5017.1  411.80
  5023.9  411.86  5033.1  410.06  5038.8  413.47  5054.8  410.56  5060.5  413.55
  5120.0  412.45  5202.6  414.75  5244.8  416.19  5400.8  424.42  5481.5  428.31
  5504.4  432.54  5526.1  438.19  5531.9  439.76  5538.7  443.35  5561.6  445.31
#Mann=8,-1,0
  4532.0    0.16       0  4637.6    0.12       0  4745.2    0.16       0
  4882.4    0.12       0  4997.7    0.07       0  5004.4    0.12       0
  5244.8    0.16       0  5400.8    0.07       0
Bank Sta=4904.9,5202.6
Exp/Cntr=0.3,0.1

Type RM Length L Ch R = 1,1717,532,532,532
BEGIN DESCRIPTION:
UNT 170 in LFCCL Watershed 3.0
END DESCRIPTION:
XS GIS Cut Line= 3
      2810974.98      7028275.00      2811425.00      7028375.00
      2811775.02      7028675.02
#Sta/Elev= 30
  4522.3  440.71  4541.5  439.61  4546.7  440.17  4636.4  434.30  4682.4  429.29
  4687.5  429.44  4725.9  422.36  4747.7  421.09  4774.6  416.95  4779.7  417.57
  4826.6  413.11  4880.9  410.54  4964.1  411.34  4973.1  408.94  4977.4  406.13
  4977.9  405.33  4983.6  405.33  4984.1  406.13  5004.7  409.65  5025.6  409.28
  5050.7  413.11  5079.5  414.55  5097.3  416.77  5132.0  418.75  5174.8  423.55
  5195.7  424.50  5295.6  436.10  5330.7  438.03  5359.0  441.14  5444.3  449.54
#Mann=7,-1,0
  4522.3    0.16       0  4636.4    0.12       0  4977.4    0.07       0
  4984.1    0.12       0  5079.5    0.16       0  5097.3    0.12       0
  5359.0    0.05       0
Bank Sta=4826.6,5050.7
Exp/Cntr=0.3,0.1

Type RM Length L Ch R = 1,1185,262,262,262
BEGIN DESCRIPTION:
UNT 170 in LFCCL Watershed 2.0
END DESCRIPTION:
XS GIS Cut Line= 3
      2810825.04      7028575.03      2811225.00      7028825.00
      2811674.98      7028775.00
#Sta/Elev= 30
  4504.0  442.31  4532.8  439.60  4569.4  434.15  4605.0  431.03  4657.3  424.96
  4663.7  422.89  4669.6  422.09  4721.5  416.53  4773.4  413.16  4843.2  411.00
  4916.7  409.08  4968.0  410.00  4978.2  409.20  4992.4  405.77  4992.9  404.97
  4998.6  404.97  4999.1  405.77  5005.8  406.35  5015.9  408.80  5036.0  409.75
  5086.3  409.22  5126.3  411.00  5176.9  415.54  5237.3  424.25  5260.5  425.80
  5287.6  427.82  5347.9  435.41  5398.2  440.09  5418.4  443.87  5428.4  444.32
#Mann=5,-1,0
  4504.0    0.16       0  4605.0    0.12       0  4992.4    0.07       0
  4999.1    0.12       0  5260.5    0.05       0
Bank Sta=4843.2,5126.3
Exp/Cntr=0.3,0.1

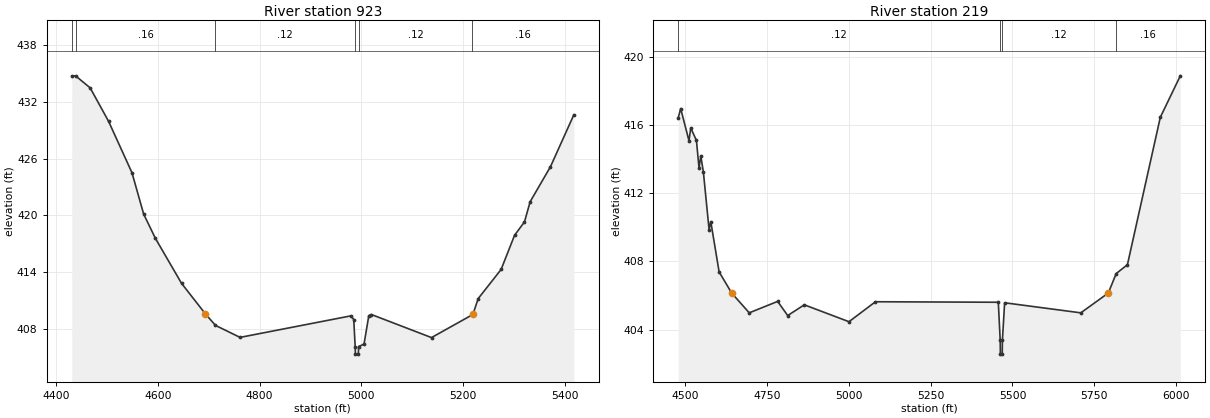
Type RM Length L Ch R = 1,923,704,704,704
BEGIN DESCRIPTION:
XS4001A
END DESCRIPTION:
XS GIS Cut Line= 3
      2810732.15      7028850.78      2811242.55      7029085.15
      2811659.26      7029001.80
#Sta/Elev= 30
  4431.1  434.73  4438.5  434.76  4467.2  433.49  4503.4  429.95  4549.4  424.51
  4572.4  420.13  4595.4  417.57  4646.9  412.80  4693.8  409.57  4713.5  408.36
  4761.8  407.09  4979.7  409.37  4985.2  408.98  4988.0  406.12  4988.5  405.32
  4994.2  405.32  4994.7  406.12  5005.4  406.38  5014.8  409.39  5019.9  409.51
  5138.0  407.07  5218.1  409.48  5219.6  409.57  5229.8  411.20  5274.8  414.28
  5301.2  417.89  5320.7  419.31  5331.8  421.44  5371.7  425.14  5417.7  430.64
#Mann=6,-1,0
  4431.1    0.12       0  4438.5    0.16       0  4713.5    0.12       0
  4988.0    0.07       0  4994.7    0.12       0  5218.1    0.16       0
Bank Sta=4693.8,5219.6
Exp/Cntr=0.3,0.1

Type RM Length L Ch R = 1,219,0,0,0
BEGIN DESCRIPTION:
UNT 170 in LFCCL Watershed 1.0
END DESCRIPTION:
XS GIS Cut Line= 3
      2810617.55      7029022.67      2810783.86      7029483.64
      2811815.44      7029324.73
#Sta/Elev= 30
  4479.0  416.41  4486.5  416.95  4511.9  415.06  4517.2  415.82  4534.6  415.08
  4542.5  413.47  4547.9  414.18  4555.9  413.22  4573.2  409.86  4578.5  410.32
  4603.9  407.38  4642.3  406.14  4695.9  404.98  4782.7  405.65  4813.4  404.82
  4864.1  405.45  5000.6  404.46  5081.5  405.63  5456.8  405.60  5462.6  403.36
  5463.1  402.56  5468.8  402.56  5469.3  403.36  5476.1  405.57  5708.8  404.98
  5792.8  406.14  5816.9  407.28  5851.2  407.80  5951.7  416.44  6012.8  418.87
#Mann=4,-1,0
  4479.0    0.12       0  5462.6    0.07       0  5469.3    0.12       0
  5816.9    0.16       0
Bank Sta=4642.3,5792.8
Exp/Cntr=0.3,0.1

Chan Stop Cuts=-1