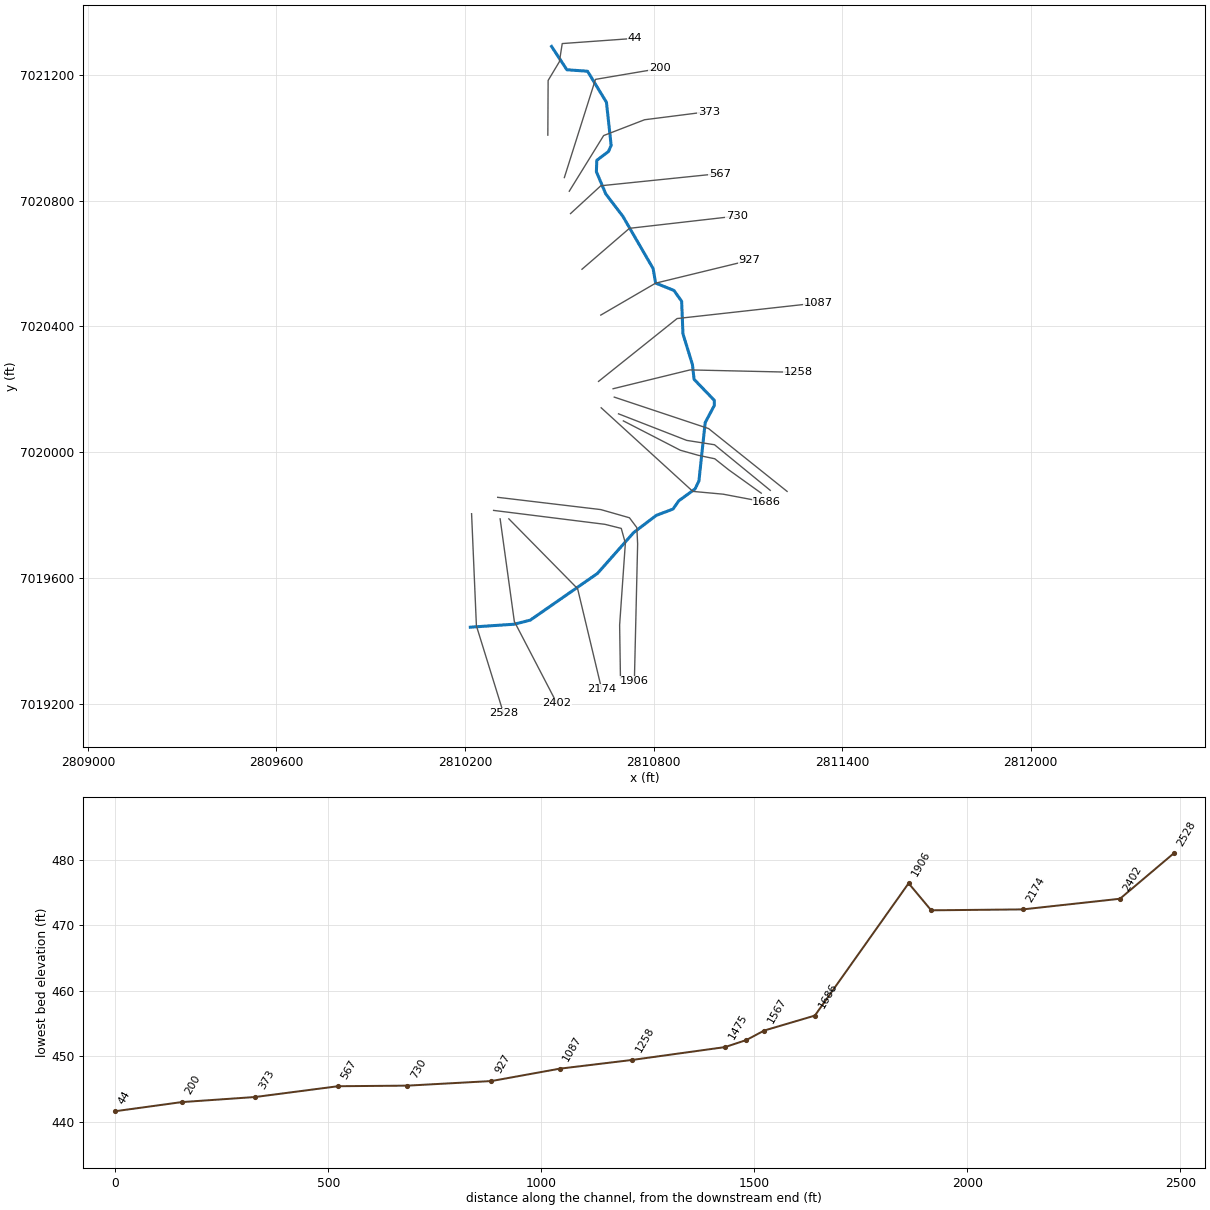
--- UNT 171 in LFCCL Watershed.prj (project) ---

Proj Title=UNT 171 in LFCCL Watershed Base Level Engineering
Current Plan=p01
Default Exp/Contr=0.3,0.1
English Units
Geom File=g01
Flow File=f01
Plan File=p01
BEGIN DESCRIPTION:
UNT 171 in LFCCL Watershed
END DESCRIPTION:

--- UNT 171 in LFCCL Watershed.p01 (plan) ---

Plan Title=Multiple Run
Short Identifier=Multiple
Geom File=g01
Flow File=f01
Subcritical Flow
K Sum by GR= 0
Std Step Tol= 0.01
Critical Tol= 0.01
Num of Std Step Trials= 20
Max Error Tol= 0.3
Flow Tol Ratio= 0.001
Split Flow NTrial= 30
Split Flow Tol= 0.02
Split Flow Ratio= 0.02
Log Output Level= 0
Friction Slope Method= 1
Unsteady Friction Slope Method= 2
Unsteady Bridges Friction Slope Method= 1
Parabolic Critical Depth
Global Vel Dist=  1 , 1 , 1
Global Log Level= 0
CheckData=True
Encroach Param= -1, 0, 0, 0
BEGIN DESCRIPTION:
Multiple Run
END DESCRIPTION:

--- UNT 171 in LFCCL Watershed.f01 (steady flow) ---

Flow Title=Multiple
Number of Profiles=7
Profile Names=10-year,25-year,50-year,1pct_min,100-year,1pct_plu,500-year
River Rch & RM= UNT 171 in LFCCL,Reach-1,2528
     142     174     198     113     225     449     290
Boundary for River Rch & Prof#=UNT 171 in LFCCL,Reach-1,1
Up Type=0
Dn Type=3
Dn Slope=0.005
Boundary for River Rch & Prof#=UNT 171 in LFCCL,Reach-1,2
Up Type=0
Dn Type=3
Dn Slope=0.005
Boundary for River Rch & Prof#=UNT 171 in LFCCL,Reach-1,3
Up Type=0
Dn Type=3
Dn Slope=0.005
Boundary for River Rch & Prof#=UNT 171 in LFCCL,Reach-1,4
Up Type=0
Dn Type=3
Dn Slope=0.005
Boundary for River Rch & Prof#=UNT 171 in LFCCL,Reach-1,5
Up Type=0
Dn Type=3
Dn Slope=0.005
Boundary for River Rch & Prof#=UNT 171 in LFCCL,Reach-1,6
Up Type=0
Dn Type=3
Dn Slope=0.005
Boundary for River Rch & Prof#=UNT 171 in LFCCL,Reach-1,7
Up Type=0
Dn Type=3
Dn Slope=0.005

--- UNT 171 in LFCCL Watershed.g01 (geometry) ---

Geom Title=Existing Conditions

River Reach=UNT 171 in LFCCL,Reach-1
Reach XY= 30
      2810216.98      7019442.92      2810357.61      7019452.47
      2810407.96      7019465.49      2810621.50      7019613.93
      2810736.95      7019744.14      2810809.00      7019798.83
      2810861.95      7019818.79      2810880.18      7019844.83
      2810932.26      7019883.03      2810944.41      7019908.20
      2810964.38      7020093.97      2810993.46      7020148.44
      2810993.46      7020164.71      2810929.01      7020231.60
      2810923.80      7020278.47      2810893.59      7020376.39
      2810889.42      7020480.03      2810864.94      7020514.41
      2810806.61      7020537.85      2810798.70      7020583.95
      2810702.83      7020749.57      2810647.96      7020821.72
      2810618.12      7020892.30      2810619.46      7020928.31
      2810656.63      7020956.50      2810665.14      7020975.98
      2810650.14      7021113.18      2810589.99      7021211.92
      2810524.23      7021216.62      2810475.59      7021290.71

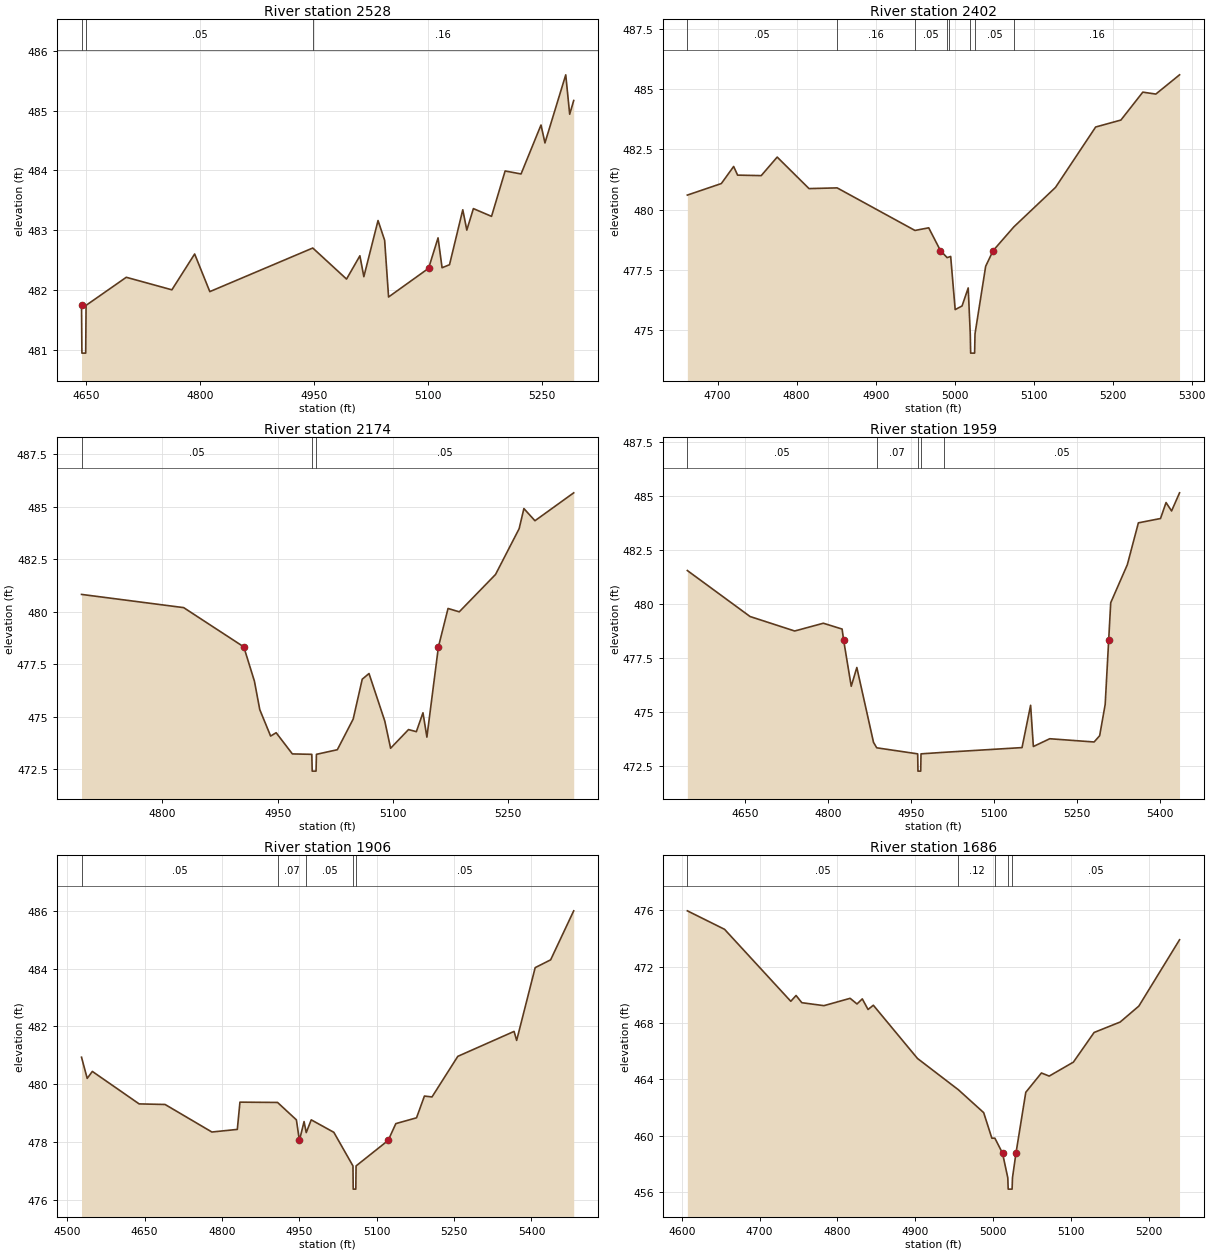
Type RM Length L Ch R = 1,2528,126,126,126
BEGIN DESCRIPTION:
UNT 171 in LFCCL Watershed 4.0
END DESCRIPTION:
XS GIS Cut Line= 3
      2810221.04      7019803.98      2810236.39      7019447.33
      2810322.74      7019168.68
#Sta/Elev= 30
  4643.6  481.74  4644.1  480.94  4649.1  480.94  4649.6  481.74  4702.6  482.21
  4762.7  482.00  4792.7  482.60  4812.7  481.97  4948.4  482.70  4992.9  482.18
  5010.5  482.57  5015.7  482.22  5034.4  483.16  5043.1  482.83  5048.3  481.88
  5101.0  482.36  5113.5  482.87  5118.8  482.37  5128.6  482.42  5146.1  483.34
  5151.4  483.00  5160.1  483.36  5184.0  483.23  5201.9  483.99  5222.9  483.94
  5249.2  484.76  5254.4  484.46  5281.8  485.60  5287.0  484.94  5292.3  485.17
#Mann=3,-1,0
  4643.6    0.07       0  4649.6    0.05       0  4948.4    0.16       0
Bank Sta=4643.6,5101
Exp/Cntr=0.3,0.1

Type RM Length L Ch R = 1,2402,228,228,228
BEGIN DESCRIPTION:
XS4012A
END DESCRIPTION:
XS GIS Cut Line= 3
      2810311.92      7019787.58      2810357.05      7019461.22
      2810492.47      7019200.79
#Sta/Elev= 30
  4661.7  480.60  4704.7  481.08  4720.3  481.79  4725.3  481.43  4755.2  481.41
  4775.4  482.18  4815.7  480.87  4851.3  480.90  4949.8  479.13  4967.2  479.24
  4982.1  478.29  4990.5  478.00  4993.3  478.03  4995.0  478.05  5000.7  475.84
  5009.4  475.99  5017.2  476.74  5019.8  474.83  5020.3  474.03  5025.3  474.03
  5025.8  474.83  5039.3  477.64  5048.7  478.29  5075.0  479.28  5127.7  480.92
  5178.5  483.43  5210.5  483.72  5238.2  484.88  5254.7  484.80  5284.7  485.60
#Mann=8,-1,0
  4661.7    0.05       0  4851.3    0.16       0  4949.8    0.05       0
  4990.5    0.16       0  4993.3    0.05       0  5019.8    0.03       0
  5025.8    0.05       0  5075.0    0.16       0
Bank Sta=4982.1,5048.7
Exp/Cntr=0.3,0.1

Type RM Length L Ch R = 1,2174,215,215,215
BEGIN DESCRIPTION:
XS4013A
END DESCRIPTION:
XS GIS Cut Line= 3
      2810339.66      7019787.64      2810558.44      7019565.39
      2810634.83      7019245.96
#Sta/Elev= 30
  4694.8  480.83  4827.7  480.20  4905.9  478.33  4919.7  476.70  4926.7  475.34
  4940.8  474.08  4948.0  474.24  4969.1  473.23  4994.4  473.21  4994.9  472.41
  4999.9  472.41  5000.4  473.21  5027.6  473.43  5048.2  474.89  5060.0  476.79
  5068.8  477.06  5089.3  474.80  5096.9  473.50  5120.2  474.39  5130.4  474.29
  5139.0  475.19  5144.1  474.03  5159.1  478.33  5171.6  480.16  5186.2  480.00
  5233.4  481.78  5264.1  483.96  5270.3  484.92  5284.7  484.34  5335.1  485.67
#Mann=3,-1,0
  4694.8    0.05       0  4994.4   0.033       0  5000.4    0.05       0
Bank Sta=4905.9,5159.1
Exp/Cntr=0.3,0.1

Type RM Length L Ch R = 1,1959,53,53,53
BEGIN DESCRIPTION:
XS4003A
END DESCRIPTION:
XS GIS Cut Line= 6
      2810291.11      7019814.51      2810645.25      7019770.25
      2810697.33      7019757.23      2810710.35      7019710.35
      2810692.12      7019449.94      2810694.73      7019280.65
#Sta/Elev= 30
  4546.0  481.56  4659.4  479.43  4740.0  478.76  4791.8  479.12  4825.7  478.85
  4828.5  478.33  4842.2  476.20  4852.3  477.07  4882.5  473.60  4888.3  473.35
  4962.3  473.07  4962.8  472.27  4967.8  472.27  4968.3  473.07  5009.2  473.14
  5150.9  473.36  5166.4  475.32  5171.4  473.41  5201.0  473.77  5281.2  473.62
  5291.2  473.91  5301.2  475.36  5307.5  478.33  5311.2  480.07  5341.2  481.83
  5361.2  483.77  5401.2  483.97  5411.2  484.71  5421.2  484.32  5435.6  485.16
#Mann=5,-1,0
  4546.0    0.05       0  4888.3    0.07       0  4962.3    0.07       0
  4968.3    0.07       0  5009.2    0.05       0
Bank Sta=4828.5,5307.5
Exp/Cntr=0.3,0.1

Type RM Length L Ch R = 1,1906,220,220,220
BEGIN DESCRIPTION:
XS4002A
END DESCRIPTION:
XS GIS Cut Line= 6
      2810304.12      7019856.18      2810632.23      7019817.12
      2810723.37      7019791.08      2810746.81      7019759.83
      2810749.41      7019707.75      2810739.00      7019270.30
#Sta/Elev= 30
  4527.8  480.94  4538.8  480.21  4548.8  480.45  4639.5  479.33  4689.8  479.31
  4780.5  478.36  4829.8  478.45  4834.9  479.39  4907.8  479.38  4944.3  478.78
  4950.2  478.07  4959.2  478.72  4963.4  478.34  4973.1  478.78  5016.9  478.35
  5054.0  477.19  5054.5  476.39  5059.5  476.39  5060.0  477.19  5122.2  478.07
  5137.1  478.65  5177.2  478.85  5192.5  479.60  5207.2  479.57  5257.2  480.97
  5366.3  481.83  5371.3  481.52  5407.2  484.03  5437.2  484.30  5481.9  485.99
#Mann=5,-1,0
  4527.8    0.05       0  4907.8    0.07       0  4963.4    0.05       0
  5054.0    0.03       0  5060.0    0.05       0
Bank Sta=4950.2,5122.2
Exp/Cntr=0.3,0.1

Type RM Length L Ch R = 1,1686,119,119,119
BEGIN DESCRIPTION:
XS4007A
END DESCRIPTION:
XS GIS Cut Line= 4
      2810633.43      7020141.04      2810925.00      7019875.00
      2811021.80      7019866.11      2811159.95      7019840.00
#Sta/Elev= 30
  4607.1  475.95  4654.9  474.64  4740.0  469.54  4746.8  469.95  4754.2  469.44
  4782.6  469.23  4816.3  469.75  4825.1  469.35  4831.9  469.71  4839.3  468.96
  4846.1  469.26  4902.8  465.49  4955.4  463.27  4987.9  461.65  4998.4  459.84
  5002.3  459.84  5012.1  458.78  5018.9  457.03  5019.4  456.23  5024.4  456.23
  5024.9  457.03  5029.4  458.78  5042.0  463.09  5062.1  464.46  5072.1  464.24
  5103.2  465.23  5129.8  467.33  5163.3  468.07  5187.3  469.20  5239.6  473.90
#Mann=5,-1,0
  4607.1    0.05       0  4955.4    0.12       0  5002.3    0.05       0
  5018.9    0.07       0  5024.9    0.05       0
Bank Sta=5012.1,5029.4
Exp/Cntr=0.3,0.1

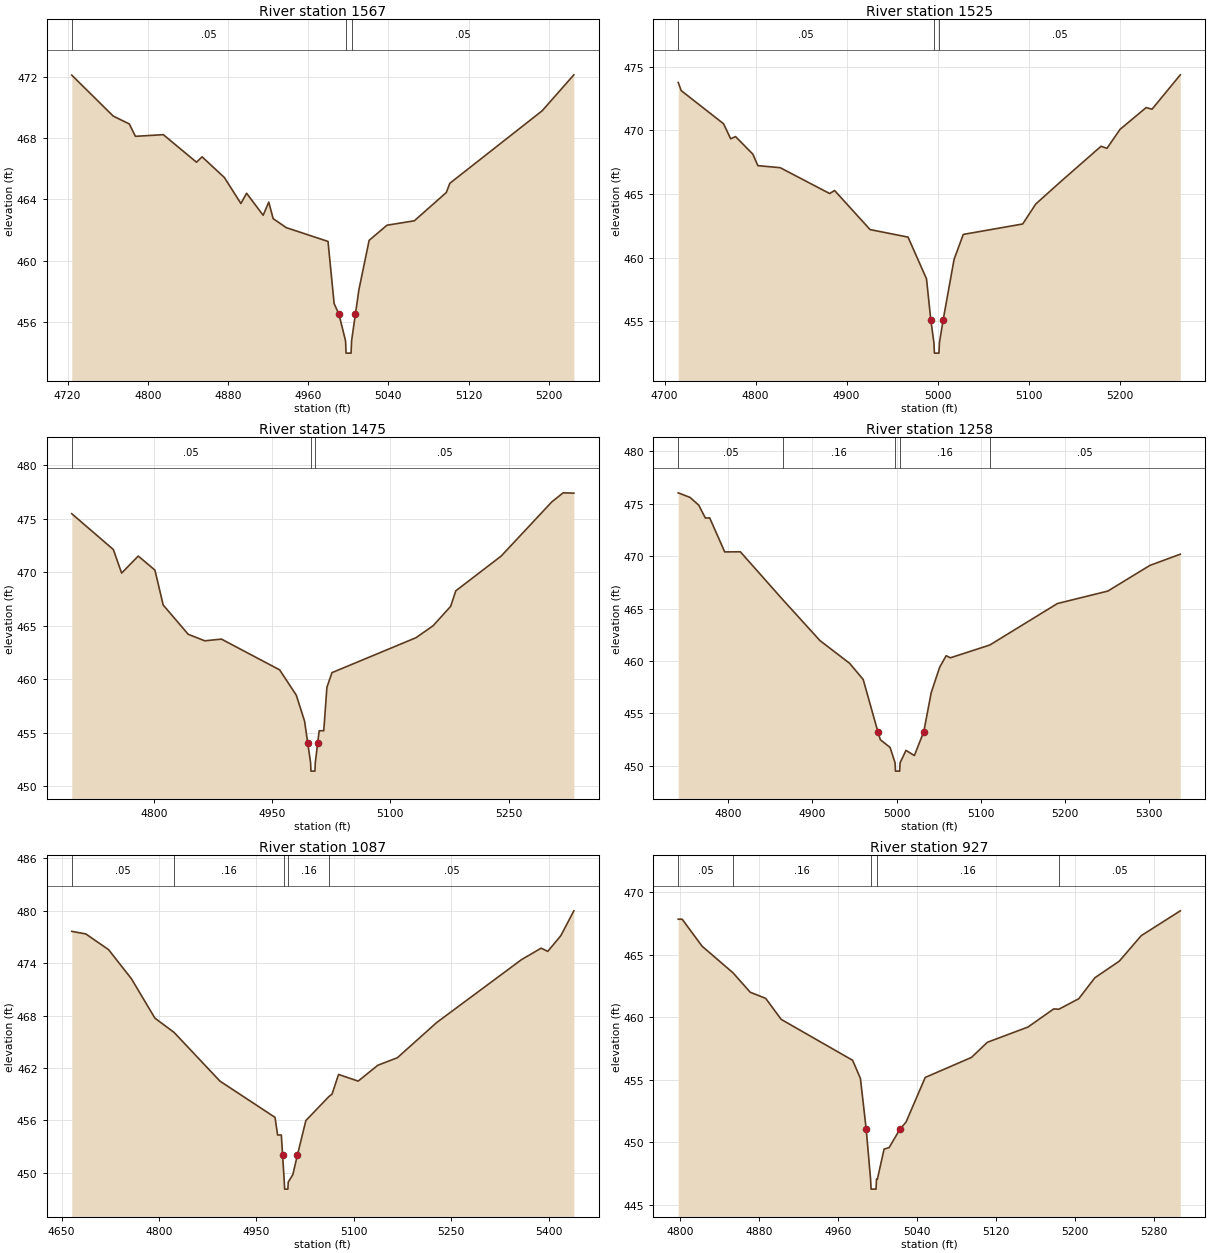
Type RM Length L Ch R = 1,1567,42,42,42
BEGIN DESCRIPTION:
XS4005A
END DESCRIPTION:
XS GIS Cut Line= 6
      2810704.00      7020099.32      2810885.23      7020006.00
      2810942.74      7019989.72      2810994.82      7019978.87
      2811039.24      7019943.57      2811142.66      7019869.44
#Sta/Elev= 30
  4724.2  472.12  4765.6  469.44  4781.6  468.93  4787.7  468.12  4815.5  468.23
  4848.6  466.43  4854.2  466.78  4876.4  465.43  4892.9  463.73  4898.6  464.40
  4915.1  462.96  4920.7  463.82  4925.1  462.74  4938.2  462.15  4979.8  461.25
  4985.9  457.19  4990.7  456.49  4997.3  454.75  4997.8  453.95  5002.8  453.95
  5003.3  454.75  5007.1  456.49  5010.6  458.09  5020.8  461.32  5038.6  462.31
  5065.9  462.60  5097.8  464.45  5101.3  465.05  5193.4  469.79  5225.0  472.14
#Mann=3,-1,0
  4724.2    0.05       0  4997.3    0.03       0  5003.3    0.05       0
Bank Sta=4990.7,5007.1
Exp/Cntr=0.3,0.1

Type RM Length L Ch R = 1,1525,50,50,50
BEGIN DESCRIPTION:
XS4006A
END DESCRIPTION:
XS GIS Cut Line= 4
      2810688.60      7020121.83      2810905.56      7020037.32
      2810994.10      7020023.43      2811171.52      7019878.25
#Sta/Elev= 30
  4715.0  473.75  4718.3  473.11  4764.8  470.51  4772.6  469.33  4778.0  469.50
  4797.0  468.12  4802.5  467.22  4827.0  467.06  4881.4  465.03  4886.8  465.27
  4925.8  462.20  4967.5  461.61  4987.8  458.34  4992.6  455.07  4996.0  453.30
  4996.5  452.50  5001.5  452.50  5002.0  453.30  5006.0  455.07  5018.1  459.86
  5028.2  461.82  5093.5  462.64  5107.9  464.21  5136.6  466.05  5179.6  468.74
  5186.1  468.58  5200.5  470.07  5229.2  471.78  5235.6  471.65  5266.7  474.35
#Mann=3,-1,0
  4715.0    0.05       0  4996.0    0.03       0  5002.0    0.05       0
Bank Sta=4992.6,5006
Exp/Cntr=0.3,0.1

Type RM Length L Ch R = 1,1475,217,217,217
BEGIN DESCRIPTION:
UNT 171 in LFCCL Watershed 3.0
END DESCRIPTION:
XS GIS Cut Line= 3
      2810675.02      7020174.99      2810975.00      7020075.00
      2811225.03      7019874.98
#Sta/Elev= 30
  4696.1  475.45  4748.8  472.11  4759.3  469.91  4780.4  471.50  4801.5  470.19
  4812.0  466.93  4843.7  464.20  4864.7  463.59  4885.8  463.75  4959.6  460.88
  4980.7  458.52  4991.2  456.09  4995.2  454.06  4998.8  452.23  4999.3  451.43
  5004.3  451.43  5004.8  452.23  5007.8  454.06  5009.7  455.20  5015.5  455.20
  5019.5  459.25  5025.9  460.62  5132.4  463.88  5154.0  464.99  5176.4  466.81
  5182.8  468.25  5240.4  471.50  5304.5  476.55  5318.9  477.40  5332.5  477.37
#Mann=3,-1,0
  4696.1    0.05       0  4998.8    0.03       0  5004.8    0.05       0
Bank Sta=4995.2,5007.8
Exp/Cntr=0.3,0.1

Type RM Length L Ch R = 1,1258,171,171,171
BEGIN DESCRIPTION:
XS4008A
END DESCRIPTION:
XS GIS Cut Line= 3
      2810671.32      7020201.68      2810916.08      7020261.57
      2811261.21      7020253.78
#Sta/Elev= 30
  4740.3  476.05  4754.4  475.61  4764.7  474.87  4772.6  473.64  4777.7  473.66
  4795.6  470.41  4814.2  470.42  4865.0  465.82  4908.8  461.95  4944.2  459.77
  4960.3  458.23  4977.7  453.26  4980.7  452.48  4992.3  451.74  4998.2  450.28
  4998.7  449.48  5003.7  449.48  5004.2  450.28  5011.2  451.46  5021.2  450.97
  5032.4  453.26  5041.2  456.97  5051.2  459.39  5059.0  460.50  5064.0  460.30
  5110.9  461.52  5191.3  465.48  5251.3  466.67  5301.3  469.12  5337.5  470.19
#Mann=5,-1,0
  4740.3    0.05       0  4865.0    0.16       0  4998.2    0.07       0
  5004.2    0.16       0  5110.9    0.05       0
Bank Sta=4977.7,5032.4
Exp/Cntr=0.3,0.1

Type RM Length L Ch R = 1,1087,160,160,160
BEGIN DESCRIPTION:
UNT 171 in LFCCL Watershed 2.0
END DESCRIPTION:
XS GIS Cut Line= 3
      2810625.02      7020225.02      2810875.00      7020425.00
      2811325.00      7020475.00
#Sta/Elev= 30
  4665.8  477.63  4687.4  477.34  4722.6  475.53  4757.8  472.19  4793.8  467.70
  4823.3  466.07  4893.9  460.50  4978.7  456.35  4982.7  454.33  4988.4  454.33
  4990.4  451.99  4993.0  448.94  4993.5  448.14  4998.5  448.14  4999.0  448.94
  5006.1  449.80  5013.0  451.99  5026.2  455.99  5061.9  458.75  5066.4  459.00
  5076.5  461.26  5106.7  460.50  5136.9  462.31  5167.0  463.17  5227.4  467.19
  5358.2  474.40  5388.4  475.71  5398.5  475.34  5418.6  477.13  5438.7  479.98
#Mann=5,-1,0
  4665.8    0.05       0  4823.3    0.16       0  4993.0    0.07       0
  4999.0    0.16       0  5061.9    0.05       0
Bank Sta=4990.4,5013
Exp/Cntr=0.3,0.1

Type RM Length L Ch R = 1,927,197,197,197
BEGIN DESCRIPTION:
XS4011A
END DESCRIPTION:
XS GIS Cut Line= 3
      2810632.19      7020436.03      2810806.70      7020537.61
      2811105.06      7020610.25
#Sta/Elev= 30
  4798.0  467.84  4802.0  467.84  4822.2  465.68  4853.6  463.55  4871.0  462.00
  4886.7  461.51  4902.4  459.83  4974.8  456.56  4982.7  455.11  4988.6  451.03
  4993.0  447.06  4993.5  446.26  4998.5  446.26  4999.0  447.06  4999.9  447.06
  5006.7  449.46  5011.8  449.58  5022.6  451.03  5029.0  451.63  5048.4  455.19
  5095.3  456.79  5111.4  458.00  5152.6  459.22  5178.7  460.67  5183.8  460.64
  5204.0  461.48  5220.4  463.16  5245.2  464.49  5267.3  466.52  5307.0  468.51
#Mann=5,-1,0
  4798.0    0.05       0  4853.6    0.16       0  4993.0    0.07       0
  4999.0    0.16       0  5183.8    0.05       0
Bank Sta=4988.6,5022.6
Exp/Cntr=0.3,0.1

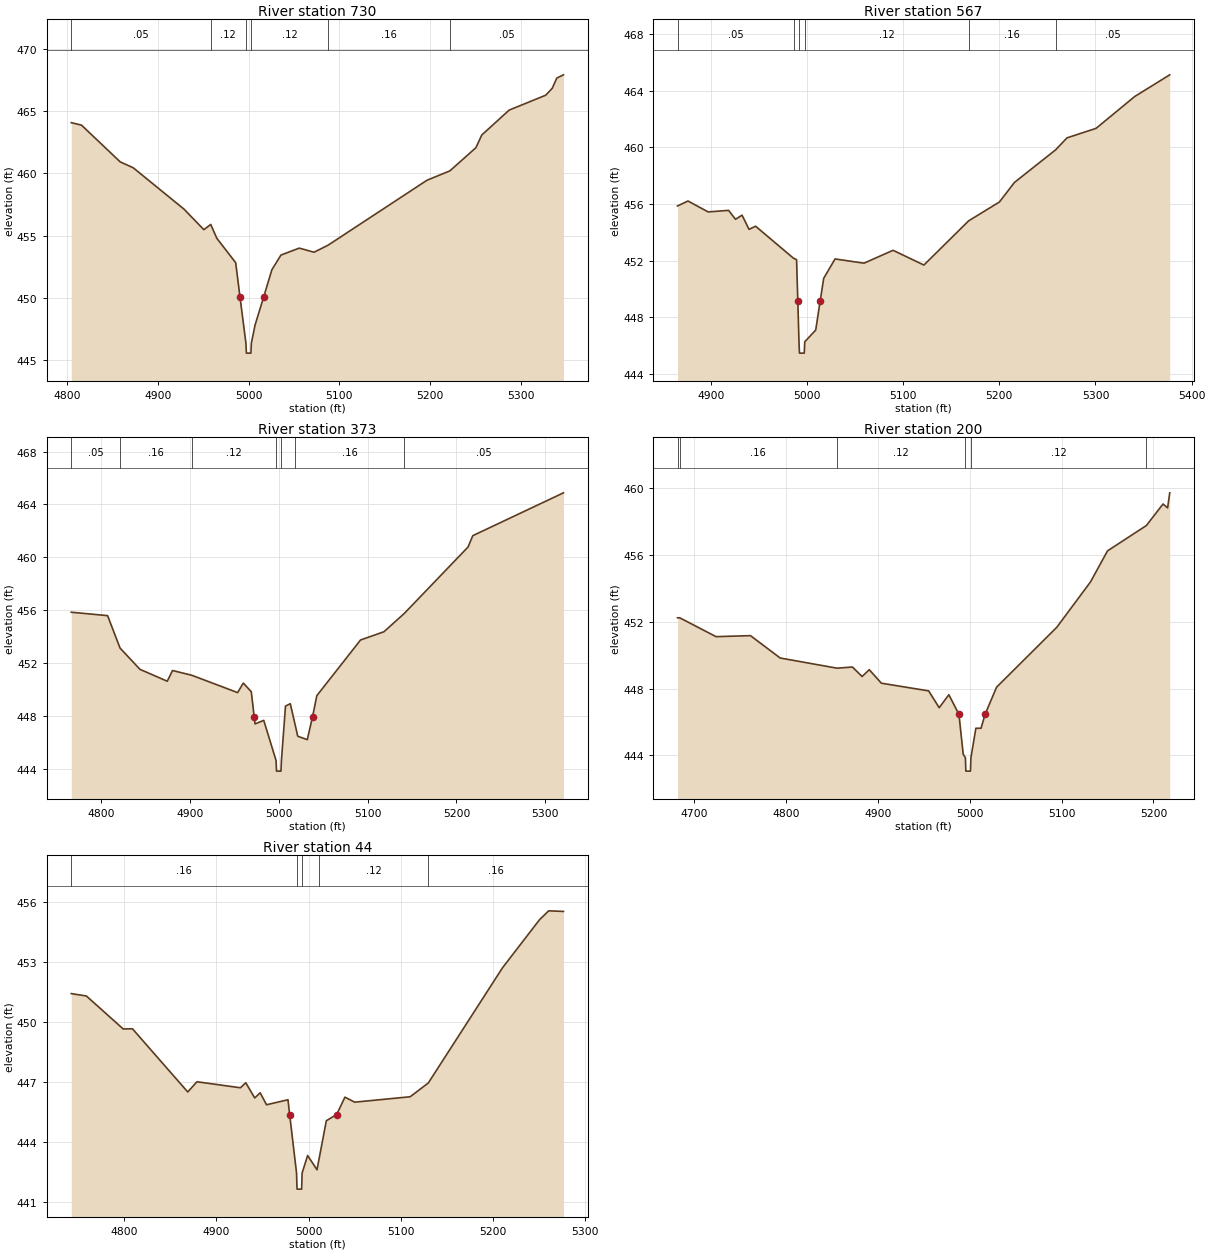
Type RM Length L Ch R = 1,730,163,163,163
BEGIN DESCRIPTION:
XS4010A
END DESCRIPTION:
XS GIS Cut Line= 3
      2810572.34      7020581.89      2810723.37      7020712.09
      2811064.54      7020751.15
#Sta/Elev= 30
  4804.4  464.06  4815.7  463.86  4858.4  460.91  4872.7  460.44  4928.7  457.12
  4950.6  455.47  4958.2  455.89  4964.9  454.78  4985.7  452.82  4990.4  450.10
  4997.0  446.36  4997.5  445.56  5002.5  445.56  5003.0  446.36  5007.1  447.82
  5016.7  450.10  5025.6  452.25  5035.6  453.43  5055.8  453.99  5072.1  453.66
  5087.5  454.22  5196.7  459.44  5221.9  460.19  5250.6  462.05  5257.1  463.07
  5287.3  465.07  5327.5  466.26  5334.8  466.82  5339.8  467.64  5347.2  467.90
#Mann=6,-1,0
  4804.4    0.05       0  4958.2    0.12       0  4997.0    0.07       0
  5003.0    0.12       0  5087.5    0.16       0  5221.9    0.05       0
Bank Sta=4990.4,5016.7
Exp/Cntr=0.3,0.1

Type RM Length L Ch R = 1,567,194,194,194
BEGIN DESCRIPTION:
XS4009A
END DESCRIPTION:
XS GIS Cut Line= 3
      2810535.89      7020758.98      2810632.23      7020847.51
      2811011.20      7020886.44
#Sta/Elev= 30
  4865.4  455.86  4876.3  456.21  4897.3  455.44  4918.5  455.55  4925.7  454.92
  4932.5  455.21  4939.8  454.21  4946.6  454.43  4986.0  452.17  4989.2  452.07
  4990.5  449.13  4991.7  446.27  4992.2  445.47  4997.2  445.47  4997.7  446.27
  5009.1  447.10  5013.7  449.14  5017.4  450.75  5029.2  452.12  5059.3  451.82
  5089.5  452.73  5121.6  451.69  5168.1  454.81  5200.1  456.14  5215.7  457.52
  5258.5  459.82  5270.4  460.67  5300.6  461.34  5340.8  463.59  5377.2  465.12
#Mann=6,-1,0
  4865.4    0.05       0  4986.0    0.12       0  4991.7    0.07       0
  4997.7    0.12       0  5168.1    0.16       0  5258.5    0.05       0
Bank Sta=4990.5,5013.7
Exp/Cntr=0.3,0.1

Type RM Length L Ch R = 1,373,173,173,173
BEGIN DESCRIPTION:
Mapping XS 6aea5beb
END DESCRIPTION:
XS GIS Cut Line= 4
      2810531.88      7020830.17      2810641.24      7021007.22
      2810771.45      7021057.57      2810976.29      7021083.61
#Sta/Elev= 30
  4766.3  455.85  4807.2  455.59  4821.2  453.14  4843.6  451.53  4874.4  450.63
  4880.3  451.44  4902.0  451.08  4953.6  449.77  4960.0  450.49  4969.0  449.83
  4972.2  447.96  4973.2  447.40  4983.0  447.67  4996.9  444.63  4997.4  443.83
  5002.4  443.83  5002.9  444.63  5007.5  448.75  5012.9  448.93  5018.0  447.44
  5021.3  446.47  5032.0  446.21  5038.0  447.96  5042.8  449.54  5092.0  453.75
  5118.3  454.37  5141.3  455.76  5213.0  460.78  5218.4  461.64  5320.5  464.88
#Mann=7,-1,0
  4766.3    0.05       0  4821.2    0.16       0  4902.0    0.12       0
  4996.9    0.07       0  5002.9    0.12       0  5018.0    0.16       0
  5141.3    0.05       0
Bank Sta=4972.2,5038
Exp/Cntr=0.3,0.1

Type RM Length L Ch R = 1,200,156,156,156
BEGIN DESCRIPTION:
Mapping XS 8a210f2e
END DESCRIPTION:
XS GIS Cut Line= 3
      2810516.24      7020873.56      2810615.20      7021186.04
      2810820.00      7021220.75
#Sta/Elev= 30
  4682.2  452.24  4684.6  452.24  4724.1  451.11  4761.6  451.17  4793.9  449.83
  4855.7  449.22  4872.5  449.29  4883.0  448.72  4890.8  449.13  4904.0  448.32
  4955.4  447.86  4966.9  446.85  4977.4  447.63  4988.4  446.45  4993.0  444.07
  4995.4  443.85  4995.9  443.05  5000.9  443.05  5001.4  443.85  5006.8  445.62
  5012.4  445.62  5016.8  446.45  5029.3  448.08  5094.8  451.67  5131.5  454.39
  5150.0  456.25  5192.3  457.77  5210.4  459.06  5215.4  458.83  5217.7  459.73
#Mann=6,-1,0
  4682.2    0.05       0  4684.6    0.16       0  4855.7    0.12       0
  4995.4    0.07       0  5001.4    0.12       0  5192.3    0.05       0
Bank Sta=4988.4,5016.8
Exp/Cntr=0.3,0.1

Type RM Length L Ch R = 1,44,0,0,0
BEGIN DESCRIPTION:
UNT 171 in LFCCL Watershed 1.0
END DESCRIPTION:
XS GIS Cut Line= 5
      2810463.67      7021008.56      2810464.59      7021182.57
      2810500.40      7021242.16      2810509.50      7021300.00
      2810741.01      7021316.62
#Sta/Elev= 30
  4742.5  451.44  4758.9  451.32  4798.9  449.67  4808.9  449.68  4868.9  446.52
  4878.9  447.03  4926.1  446.73  4931.9  446.98  4941.6  446.22  4947.5  446.48
  4954.4  445.88  4977.7  446.13  4979.5  445.39  4987.0  442.46  4987.5  441.66
  4992.5  441.66  4993.0  442.46  4999.0  443.34  5009.2  442.63  5011.1  443.09
  5019.3  445.08  5030.5  445.39  5039.5  446.26  5050.1  446.01  5110.3  446.28
  5130.0  446.97  5210.5  452.73  5250.6  455.13  5260.6  455.58  5276.7  455.55
#Mann=5,-1,0
  4742.5    0.16       0  4987.0    0.07       0  4993.0    0.16       0
  5011.1    0.12       0  5130.0    0.16       0
Bank Sta=4979.5,5030.5
Exp/Cntr=0.3,0.1

Chan Stop Cuts=-1