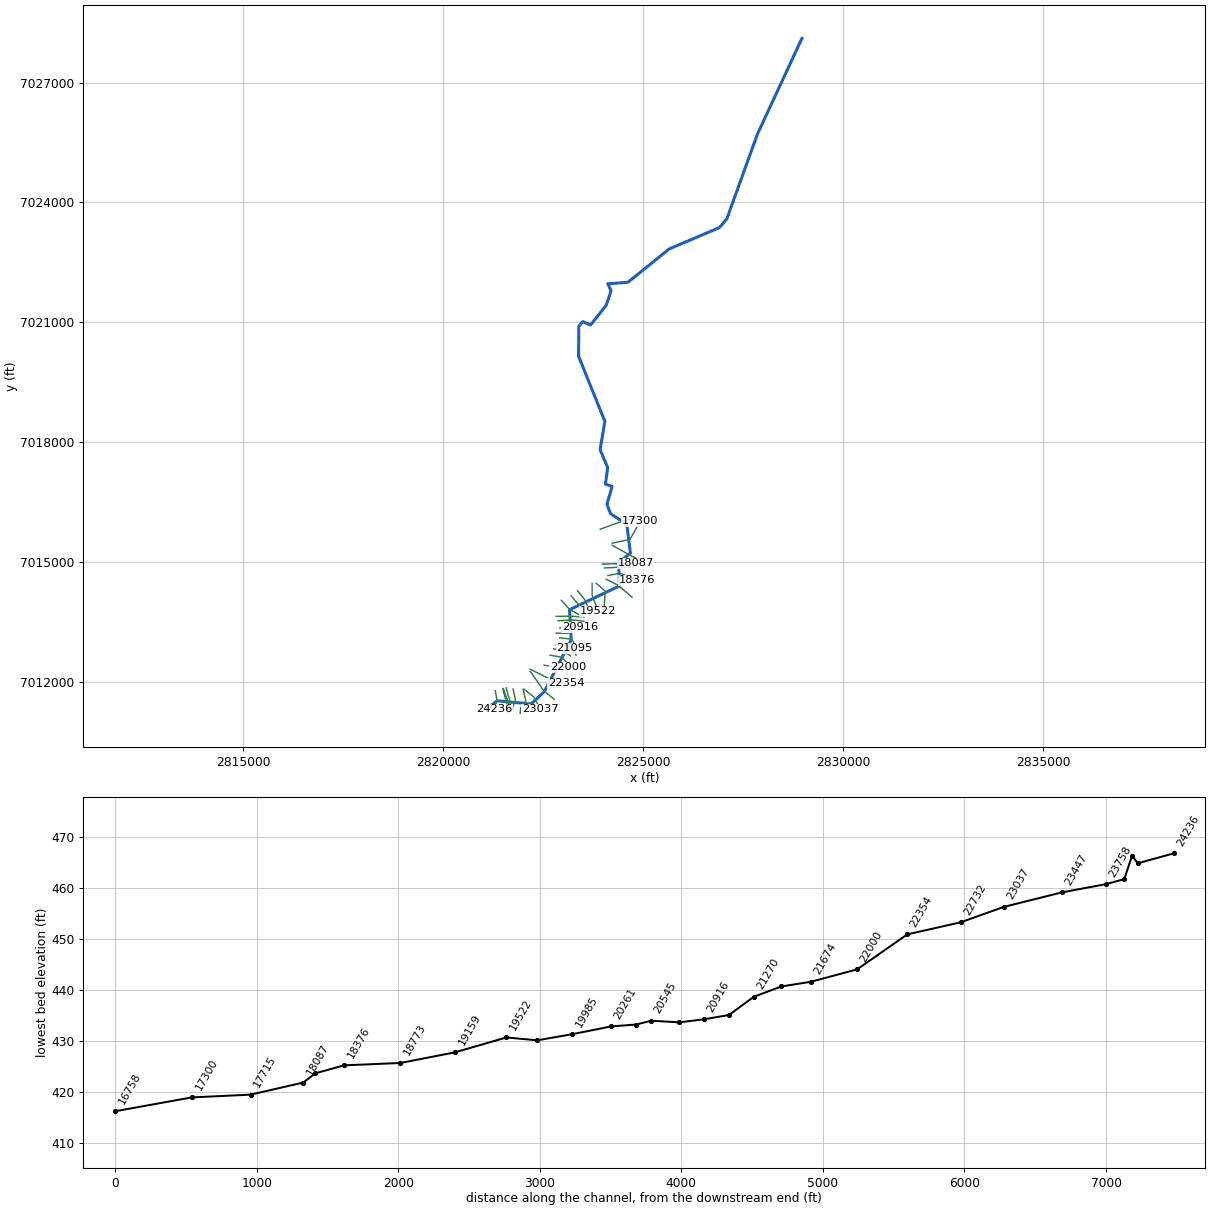
--- UNT 173 in LFCCL Watershed.prj (project) ---

Proj Title=UNT 173 in LFCCL Watershed Base Level Engineering
Current Plan=p01
Default Exp/Contr=0.3,0.1
English Units
Geom File=g01
Flow File=f01
Plan File=p01
BEGIN DESCRIPTION:
UNT 173 in LFCCL Watershed
END DESCRIPTION:

--- UNT 173 in LFCCL Watershed.p01 (plan) ---

Plan Title=Multiple Run
Short Identifier=Multiple
Geom File=g01
Flow File=f01
Subcritical Flow
K Sum by GR= 0
Std Step Tol= 0.01
Critical Tol= 0.01
Num of Std Step Trials= 20
Max Error Tol= 0.3
Flow Tol Ratio= 0.001
Split Flow NTrial= 30
Split Flow Tol= 0.02
Split Flow Ratio= 0.02
Log Output Level= 0
Friction Slope Method= 1
Unsteady Friction Slope Method= 2
Unsteady Bridges Friction Slope Method= 1
Parabolic Critical Depth
Global Vel Dist=  1 , 1 , 1
Global Log Level= 0
CheckData=True
Encroach Param= -1, 0, 0, 0
BEGIN DESCRIPTION:
Multiple Run
END DESCRIPTION:

--- UNT 173 in LFCCL Watershed.f01 (steady flow) ---

Flow Title=Multiple
Program Version=5.07
Number of Profiles= 7
Profile Names=10-year,25-year,50-year,1pct_min,100-year,1pct_plu,500-year
River Rch & RM=UNT 173 in LFCCL,Reach-1         ,24236
     251     319     371     215     430     858     576
River Rch & RM=UNT 173 in LFCCL,Reach-1         ,20916
     565     754     908     543    1083    2162    1546
River Rch & RM=UNT 173 in LFCCL,Reach-1         ,16758
     869    1186    1449     878    1753    3497    2569
River Rch & RM=UNT 173 in LFCCL,Reach-1         ,12716
     931    1274    1559     947    1889    3769    2779
River Rch & RM=UNT 173 in LFCCL,Reach-1         ,12141
    1290    1791    2212    1354    2701    5389    4038
River Rch & RM=UNT 173 in LFCCL,Reach-1         ,10207
    1566    2191    2719    1671    3335    6653    5028
River Rch & RM=UNT 173 in LFCCL,Reach-1         ,5201
    1608    2240    2771    1697    3386    6755    5068
Boundary for River Rch & Prof#=UNT 173 in LFCCL,Reach-1         , 1
Up Type= 0
Dn Type= 3
Dn Slope=0.005
Boundary for River Rch & Prof#=UNT 173 in LFCCL,Reach-1         , 2
Up Type= 0
Dn Type= 3
Dn Slope=0.005
Boundary for River Rch & Prof#=UNT 173 in LFCCL,Reach-1         , 3
Up Type= 0
Dn Type= 3
Dn Slope=0.005
Boundary for River Rch & Prof#=UNT 173 in LFCCL,Reach-1         , 4
Up Type= 0
Dn Type= 3
Dn Slope=0.005
Boundary for River Rch & Prof#=UNT 173 in LFCCL,Reach-1         , 5
Up Type= 0
Dn Type= 3
Dn Slope=0.005
Boundary for River Rch & Prof#=UNT 173 in LFCCL,Reach-1         , 6
Up Type= 0
Dn Type= 3
Dn Slope=0.005
Boundary for River Rch & Prof#=UNT 173 in LFCCL,Reach-1         , 7
Up Type= 0
Dn Type= 3
Dn Slope=0.005
DSS Import GetInterval= 0
DSS Import GetPeak= 0
DSS Import FillOption= 0

--- UNT 173 in LFCCL Watershed.g01 (geometry) ---

Geom Title=Existing Conditions

River Reach=UNT 173 in LFCCL,Reach-1
Reach XY= 30
      2821094.28      7011328.48      2821349.49      7011535.08
      2822199.76      7011453.81      2822529.03      7011763.80
      2823203.19      7013061.81      2823160.79      7013813.44
      2824407.40      7014406.34      2824390.43      7014999.82
      2824683.26      7015226.30      2824591.85      7015949.12
      2824187.79      7016212.56      2824095.59      7016450.71
      2824225.34      7016894.69      2824057.24      7016952.31
      2824114.19      7017369.30      2823924.89      7017815.07
      2824044.37      7018523.39      2823386.81      7020154.01
      2823393.06      7020899.04      2823493.02      7021020.09
      2823685.92      7020933.40      2824076.39      7021427.74
      2824199.00      7021794.79      2824115.44      7021965.04
      2824621.49      7022002.52      2825653.60      7022838.08
      2826906.76      7023369.37      2827091.56      7023585.93
      2827859.62      7025713.99      2828971.14      7028104.72

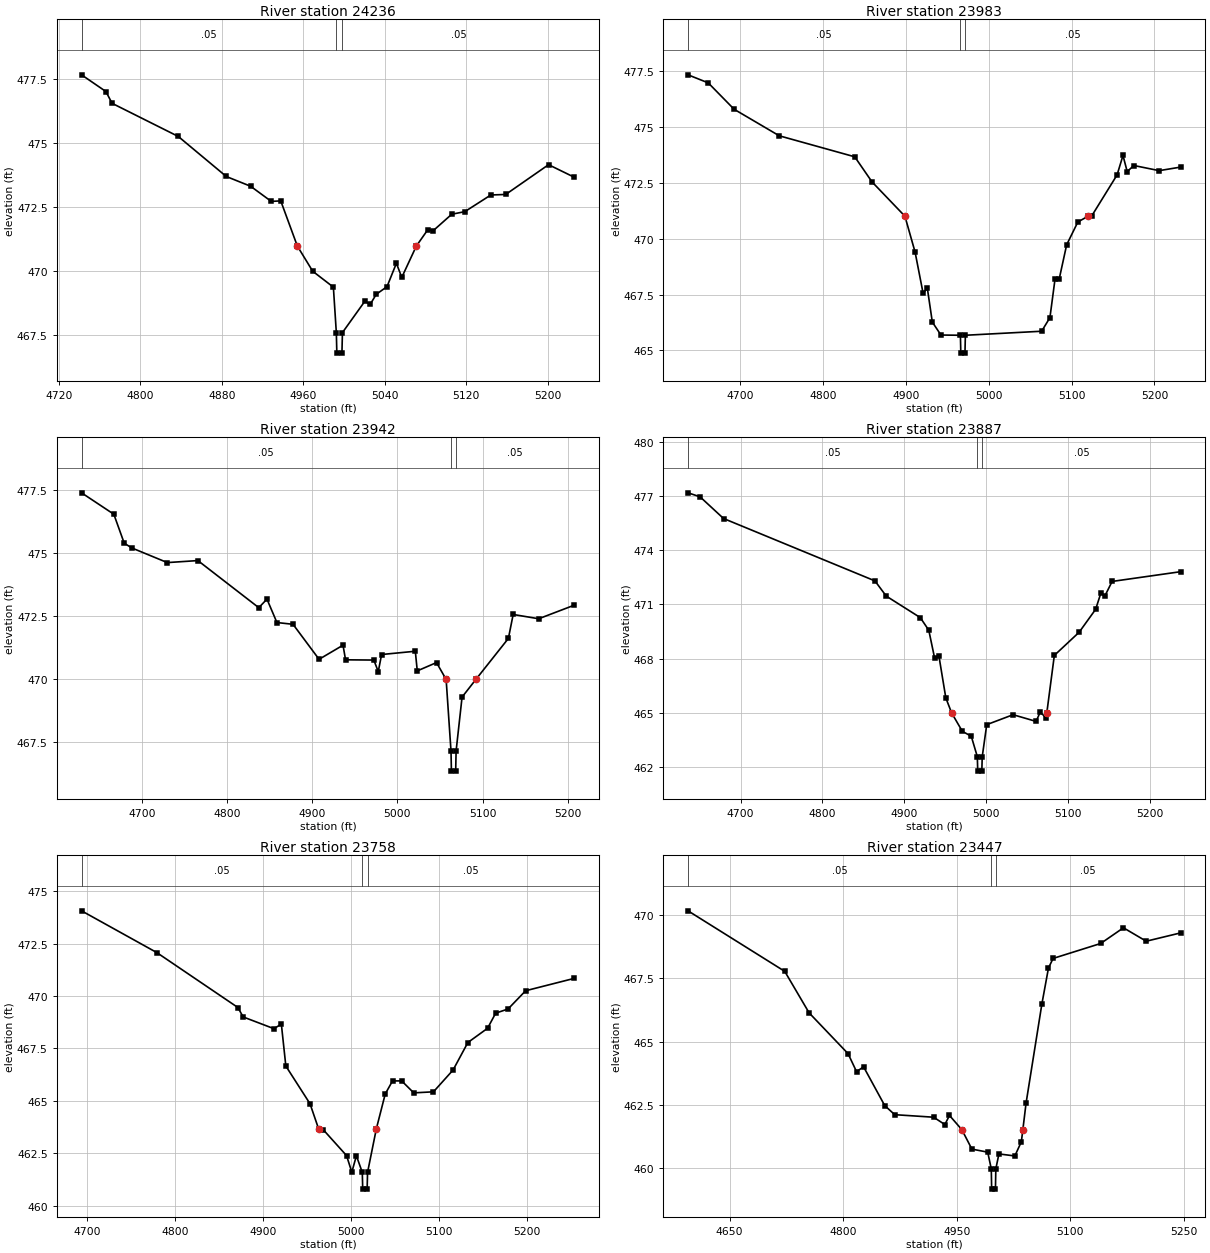
Type RM Length L Ch R = 1,24236,253,253,253
BEGIN DESCRIPTION:
UNT 173 in LFCCL Watershed 47.0
END DESCRIPTION:
XS GIS Cut Line= 3
      2821304.47      7011788.47      2821349.61      7011538.49
      2821273.22      7011321.47
#Sta/Elev= 30
  4742.1  477.65  4766.0  477.00  4772.1  476.54  4837.1  475.25  4884.3  473.69
  4908.2  473.31  4928.5  472.72  4937.8  472.74  4954.1  470.98  4969.2  470.00
  4989.5  469.38  4992.4  467.61  4992.9  466.81  4997.9  466.81  4998.4  467.61
  5020.4  468.83  5025.7  468.71  5031.6  469.10  5042.2  469.40  5051.4  470.31
  5056.7  469.76  5071.0  470.98  5082.3  471.62  5087.6  471.58  5105.8  472.22
  5118.6  472.32  5144.2  472.97  5158.8  472.99  5200.9  474.15  5226.2  473.66
#Mann=3,-1,0
  4742.1    0.05       0  4992.4    0.03       0  4998.4    0.05       0
Bank Sta=4954.1,5071
Exp/Cntr=0.3,0.1

Type RM Length L Ch R = 1,23983,41,41,41
BEGIN DESCRIPTION:
XS4014A
END DESCRIPTION:
XS GIS Cut Line= 5
      2821490.23      7011828.45      2821582.25      7011508.98
      2821589.19      7011456.90      2821585.72      7011397.87
      2821611.64      7011249.24
#Sta/Elev= 30
  4636.8  477.34  4661.2  476.98  4692.4  475.80  4747.0  474.61  4838.1  473.67
  4858.9  472.55  4898.7  471.01  4911.0  469.40  4920.6  467.57  4925.8  467.78
  4931.8  466.27  4942.2  465.69  4965.7  465.68  4966.2  464.88  4971.2  464.88
  4971.7  465.68  5063.8  465.86  5073.8  466.47  5079.9  468.18  5084.9  468.18
  5094.0  469.73  5107.5  470.75  5119.8  471.01  5124.4  471.03  5154.9  472.86
  5162.0  473.73  5167.1  473.01  5175.2  473.28  5205.7  473.05  5231.8  473.21
#Mann=3,-1,0
  4636.8    0.05       0  4965.7    0.03       0  4971.7    0.05       0
Bank Sta=4898.7,5119.8
Exp/Cntr=0.3,0.1

Type RM Length L Ch R = 1,23942,55,55,55
BEGIN DESCRIPTION:
XS4015A
END DESCRIPTION:
XS GIS Cut Line= 6
      2821504.12      7011840.58      2821608.29      7011554.12
      2821622.18      7011507.24      2821630.86      7011465.58
      2821630.86      7011437.80      2821629.12      7011283.25
#Sta/Elev= 30
  4629.2  477.40  4667.1  476.55  4679.3  475.40  4688.3  475.21  4729.9  474.63
  4765.8  474.71  4837.3  472.84  4846.9  473.18  4858.6  472.25  4877.5  472.18
  4908.1  470.79  4936.2  471.35  4939.2  470.77  4972.4  470.76  4977.6  470.30
  4981.5  470.98  5021.1  471.11  5023.4  470.33  5046.0  470.66  5057.3  469.99
  5063.0  467.15  5063.5  466.35  5068.5  466.35  5069.0  467.15  5076.0  469.29
  5092.2  469.99  5130.4  471.62  5136.0  472.57  5166.0  472.40  5207.8  472.94
#Mann=3,-1,0
  4629.2    0.05       0  5063.0    0.03       0  5069.0    0.05       0
Bank Sta=5057.3,5092.2
Exp/Cntr=0.3,0.1

Type RM Length L Ch R = 1,23887,129,129,129
BEGIN DESCRIPTION:
UNT 173 in LFCCL Watershed 46.0
END DESCRIPTION:
XS GIS Cut Line= 3
      2821577.04      7011857.95      2821677.73      7011503.77
      2821647.56      7011271.84
#Sta/Elev= 30
  4635.8  477.17  4650.5  476.95  4679.2  475.75  4864.2  472.30  4878.0  471.46
  4919.6  470.27  4930.0  469.57  4937.2  468.01  4942.4  468.14  4950.8  465.83
  4957.9  465.00  4971.0  463.98  4981.9  463.71  4989.3  462.58  4989.8  461.78
  4994.8  461.78  4995.3  462.58  5000.8  464.35  5033.0  464.90  5061.1  464.53
  5066.1  465.04  5073.4  464.73  5074.2  465.00  5083.4  468.18  5113.7  469.46
  5133.9  470.73  5140.2  471.62  5145.2  471.47  5154.0  472.27  5237.9  472.81
#Mann=3,-1,0
  4635.8    0.05       0  4989.3    0.03       0  4995.3    0.05       0
Bank Sta=4957.9,5074.2
Exp/Cntr=0.3,0.1

Type RM Length L Ch R = 1,23758,311,311,311
BEGIN DESCRIPTION:
XS4017A
END DESCRIPTION:
XS GIS Cut Line= 5
      2821749.78      7011828.42      2821809.68      7011560.19
      2821781.03      7011466.44      2821736.76      7011377.90
      2821734.17      7011289.69
#Sta/Elev= 30
  4694.1  474.06  4779.6  472.07  4871.8  469.45  4877.8  469.00  4912.8  468.44
  4921.2  468.66  4926.3  466.66  4953.8  464.86  4963.5  463.67  4968.9  463.62
  4995.3  462.39  5001.3  461.60  5006.5  462.38  5013.2  461.59  5013.7  460.79
  5018.7  460.79  5019.2  461.59  5029.2  463.67  5039.3  465.33  5047.6  465.95
  5058.0  465.95  5071.7  465.38  5094.1  465.43  5116.4  466.47  5133.2  467.78
  5155.6  468.46  5164.8  469.18  5178.9  469.38  5198.9  470.25  5254.2  470.84
#Mann=3,-1,0
  4694.1    0.05       0  5013.2    0.03       0  5019.2    0.05       0
Bank Sta=4963.5,5029.2
Exp/Cntr=0.3,0.1

Type RM Length L Ch R = 1,23447,410,410,410
BEGIN DESCRIPTION:
XS4016A
END DESCRIPTION:
XS GIS Cut Line= 4
      2821999.78      7011820.61      2822067.49      7011534.15
      2821937.28      7011349.26      2821926.91      7011219.57
#Sta/Elev= 30
  4595.2  470.17  4722.9  467.78  4755.1  466.14  4806.5  464.53  4817.7  463.82
  4827.0  464.01  4854.9  462.48  4868.1  462.12  4919.5  462.02  4934.3  461.73
  4940.4  462.09  4956.7  461.53  4970.0  460.76  4990.9  460.64  4995.6  459.98
  4996.1  459.18  5001.1  459.18  5001.6  459.98  5005.7  460.57  5026.7  460.49
  5035.3  461.05  5037.3  461.53  5041.5  462.57  5062.4  466.49  5071.1  467.91
  5077.2  468.29  5140.0  468.88  5170.1  469.50  5200.2  468.97  5245.8  469.30
#Mann=3,-1,0
  4595.2    0.05       0  4995.6    0.03       0  5001.6    0.05       0
Bank Sta=4956.7,5037.3
Exp/Cntr=0.3,0.1

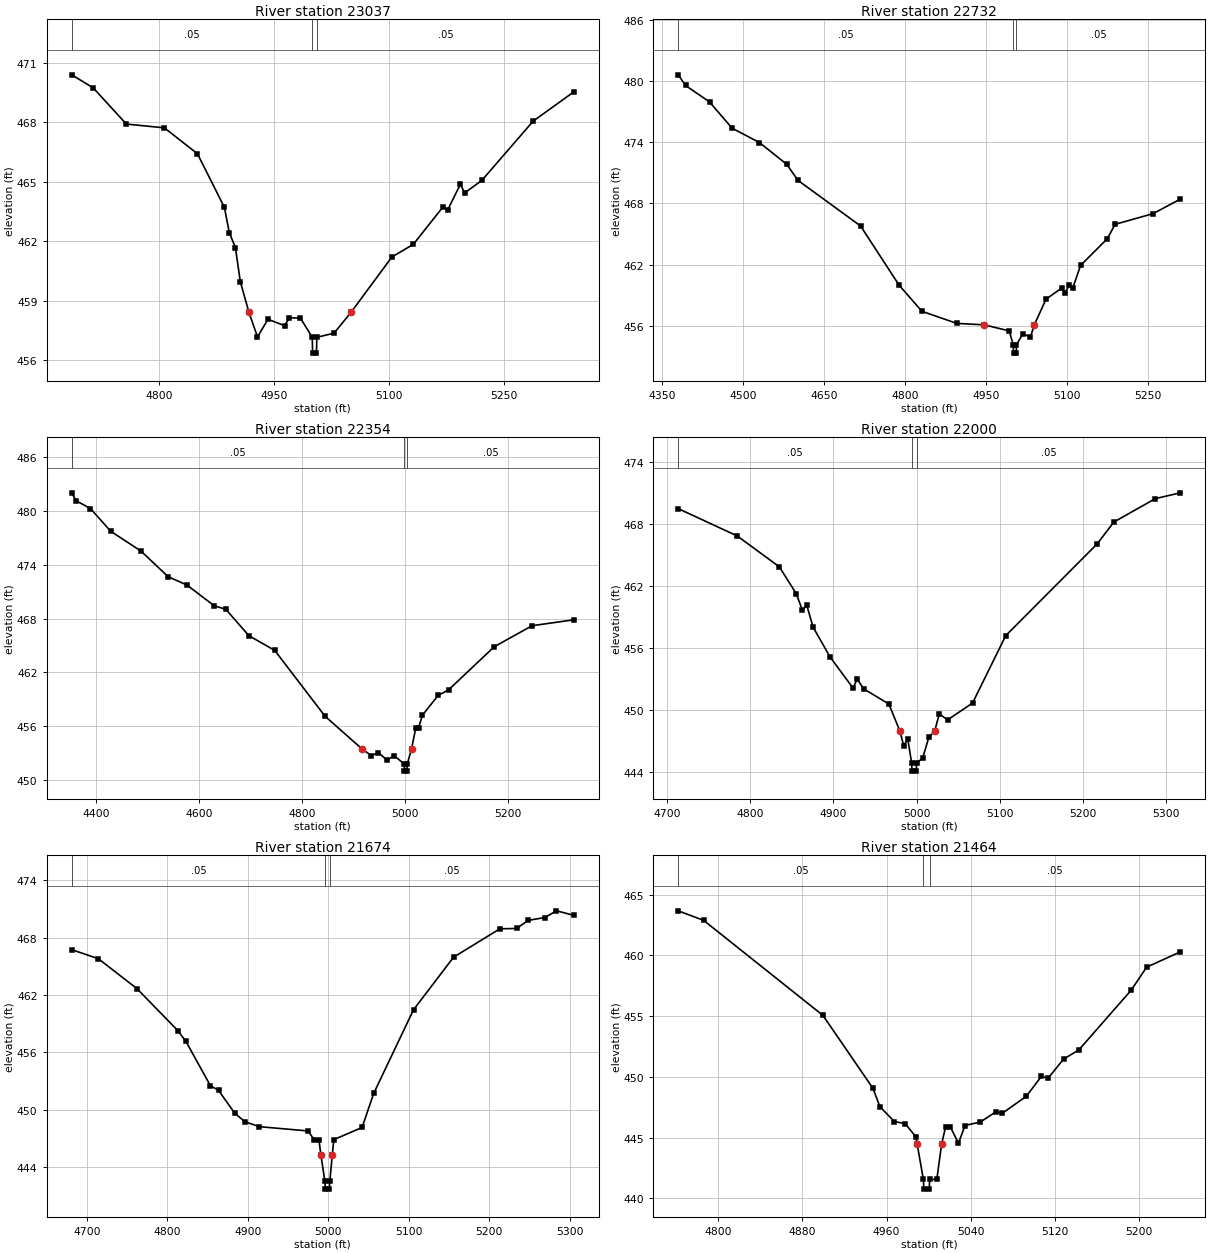
Type RM Length L Ch R = 1,23037,305,305,305
BEGIN DESCRIPTION:
UNT 173 in LFCCL Watershed 44.0
END DESCRIPTION:
XS GIS Cut Line= 3
      2822024.98      7011825.02      2822275.00      7011625.00
      2822425.00      7011325.00
#Sta/Elev= 30
  4686.0  470.41  4714.0  469.75  4757.3  467.92  4806.9  467.73  4850.1  466.42
  4885.3  463.71  4891.7  462.43  4899.7  461.67  4906.1  459.95  4917.3  458.41
  4928.5  457.16  4942.2  458.05  4963.8  457.73  4970.2  458.13  4984.6  458.11
  5000.0  457.14  5000.5  456.34  5005.5  456.34  5006.0  457.14  5028.5  457.35
  5050.8  458.41  5104.0  461.20  5132.0  461.84  5171.1  463.75  5176.7  463.57
  5193.5  464.88  5199.0  464.44  5221.4  465.07  5288.5  468.07  5341.6  469.55
#Mann=3,-1,0
  4686.0    0.05       0  5000.0    0.03       0  5006.0    0.05       0
Bank Sta=4917.3,5050.8
Exp/Cntr=0.3,0.1

Type RM Length L Ch R = 1,22732,378,378,378
BEGIN DESCRIPTION:
UNT 173 in LFCCL Watershed 43.0
END DESCRIPTION:
XS GIS Cut Line= 3
      2822175.00      7012275.01      2822525.00      7011775.00
      2822775.01      7011574.99
#Sta/Elev= 30
  4379.3  480.61  4392.8  479.57  4437.3  477.95  4479.1  475.38  4529.7  473.97
  4580.3  471.84  4601.2  470.26  4717.2  465.79  4788.7  459.98  4830.9  457.42
  4895.9  456.23  4945.8  456.10  4992.8  455.50  5000.2  454.12  5000.7  453.32
  5005.7  453.32  5006.2  454.12  5017.6  455.21  5032.1  454.91  5039.3  456.10
  5060.9  458.61  5089.7  459.69  5096.1  459.24  5104.1  459.98  5110.5  459.69
  5124.9  461.92  5174.5  464.54  5188.9  465.95  5259.4  467.00  5309.8  468.42
#Mann=3,-1,0
  4379.3    0.05       0  5000.2    0.03       0  5006.2    0.05       0
Bank Sta=4945.8,5039.3
Exp/Cntr=0.3,0.1

Type RM Length L Ch R = 1,22354,354,354,354
BEGIN DESCRIPTION:
UNT 173 in LFCCL Watershed 42.0
END DESCRIPTION:
XS GIS Cut Line= 3
      2822175.01      7012325.00      2822775.00      7012025.00
      2823074.95      7011975.01
#Sta/Elev= 30
  4353.5  482.05  4361.9  481.17  4389.8  480.29  4429.0  477.76  4487.7  475.55
  4540.8  472.67  4577.1  471.75  4630.2  469.42  4652.6  469.04  4697.3  466.09
  4747.6  464.44  4845.4  457.08  4917.3  453.42  4934.9  452.69  4948.8  453.01
  4965.6  452.19  4979.6  452.67  4998.9  451.75  4999.4  450.95  5004.4  450.95
  5004.9  451.75  5013.2  453.42  5021.5  455.78  5026.8  455.78  5034.4  457.20
  5064.9  459.41  5085.1  460.03  5173.8  464.85  5247.3  467.20  5328.4  467.86
#Mann=3,-1,0
  4353.5    0.05       0  4998.9    0.03       0  5004.9    0.05       0
Bank Sta=4917.3,5013.2
Exp/Cntr=0.3,0.1

Type RM Length L Ch R = 1,22000,326,326,326
BEGIN DESCRIPTION:
UNT 173 in LFCCL Watershed 41.0
END DESCRIPTION:
XS GIS Cut Line= 3
      2822525.03      7012424.99      2822825.00      7012375.00
      2823124.99      7012375.00
#Sta/Elev= 30
  4713.2  469.51  4784.1  466.87  4834.8  463.88  4855.1  461.29  4862.7  459.65
  4867.8  460.18  4875.4  458.05  4895.7  455.17  4923.5  452.14  4928.6  453.01
  4936.2  452.07  4966.6  450.60  4980.1  447.94  4984.4  446.57  4989.4  447.19
  4994.0  444.90  4994.5  444.10  4999.5  444.10  5000.0  444.90  5007.2  445.34
  5014.8  447.39  5021.6  447.94  5027.3  449.64  5037.3  449.06  5067.3  450.69
  5107.3  457.22  5217.3  466.10  5237.3  468.21  5287.3  470.48  5317.3  471.04
#Mann=3,-1,0
  4713.2    0.05       0  4994.0    0.03       0  5000.0    0.05       0
Bank Sta=4980.1,5021.6
Exp/Cntr=0.3,0.1

Type RM Length L Ch R = 1,21674,210,210,210
BEGIN DESCRIPTION:
UNT 173 in LFCCL Watershed 40.0
END DESCRIPTION:
XS GIS Cut Line= 3
      2822674.96      7012675.01      2822975.00      7012625.00
      2823174.98      7012375.03
#Sta/Elev= 30
  4681.0  466.74  4714.0  465.80  4762.1  462.66  4812.8  458.27  4823.0  457.13
  4853.4  452.50  4863.5  452.01  4883.8  449.60  4896.5  448.72  4914.2  448.21
  4975.0  447.76  4982.6  446.81  4988.4  446.81  4990.7  445.27  4995.8  442.47
  4996.3  441.67  5001.3  441.67  5001.8  442.47  5005.0  445.27  5006.8  446.85
  5042.0  448.13  5056.4  451.69  5106.0  460.46  5155.7  465.95  5213.3  468.93
  5234.1  468.96  5248.5  469.81  5269.3  470.11  5283.7  470.81  5305.3  470.34
#Mann=3,-1,0
  4681.0    0.05       0  4995.8    0.03       0  5001.8    0.05       0
Bank Sta=4990.7,5005
Exp/Cntr=0.3,0.1

Type RM Length L Ch R = 1,21464,194,194,194
BEGIN DESCRIPTION:
XS4018A
END DESCRIPTION:
XS GIS Cut Line= 3
      2822762.80      7012833.63      2823012.80      7012789.36
      2823189.87      7012653.96
#Sta/Elev= 30
  4762.2  463.67  4786.4  462.88  4899.6  455.06  4947.2  449.04  4953.7  447.54
  4967.5  446.31  4977.7  446.15  4987.9  445.05  4989.1  444.46  4995.0  441.55
  4995.5  440.75  5000.5  440.75  5001.0  441.55  5007.8  441.56  5012.3  444.46
  5016.1  445.87  5020.6  445.87  5028.3  444.54  5034.6  445.99  5049.2  446.28
  5063.7  447.11  5070.0  447.00  5092.7  448.39  5107.0  450.03  5113.5  449.89
  5128.1  451.46  5142.6  452.21  5192.5  457.15  5207.0  459.03  5239.0  460.29
#Mann=3,-1,0
  4762.2    0.05       0  4995.0    0.03       0  5001.0    0.05       0
Bank Sta=4989.1,5012.3
Exp/Cntr=0.3,0.1

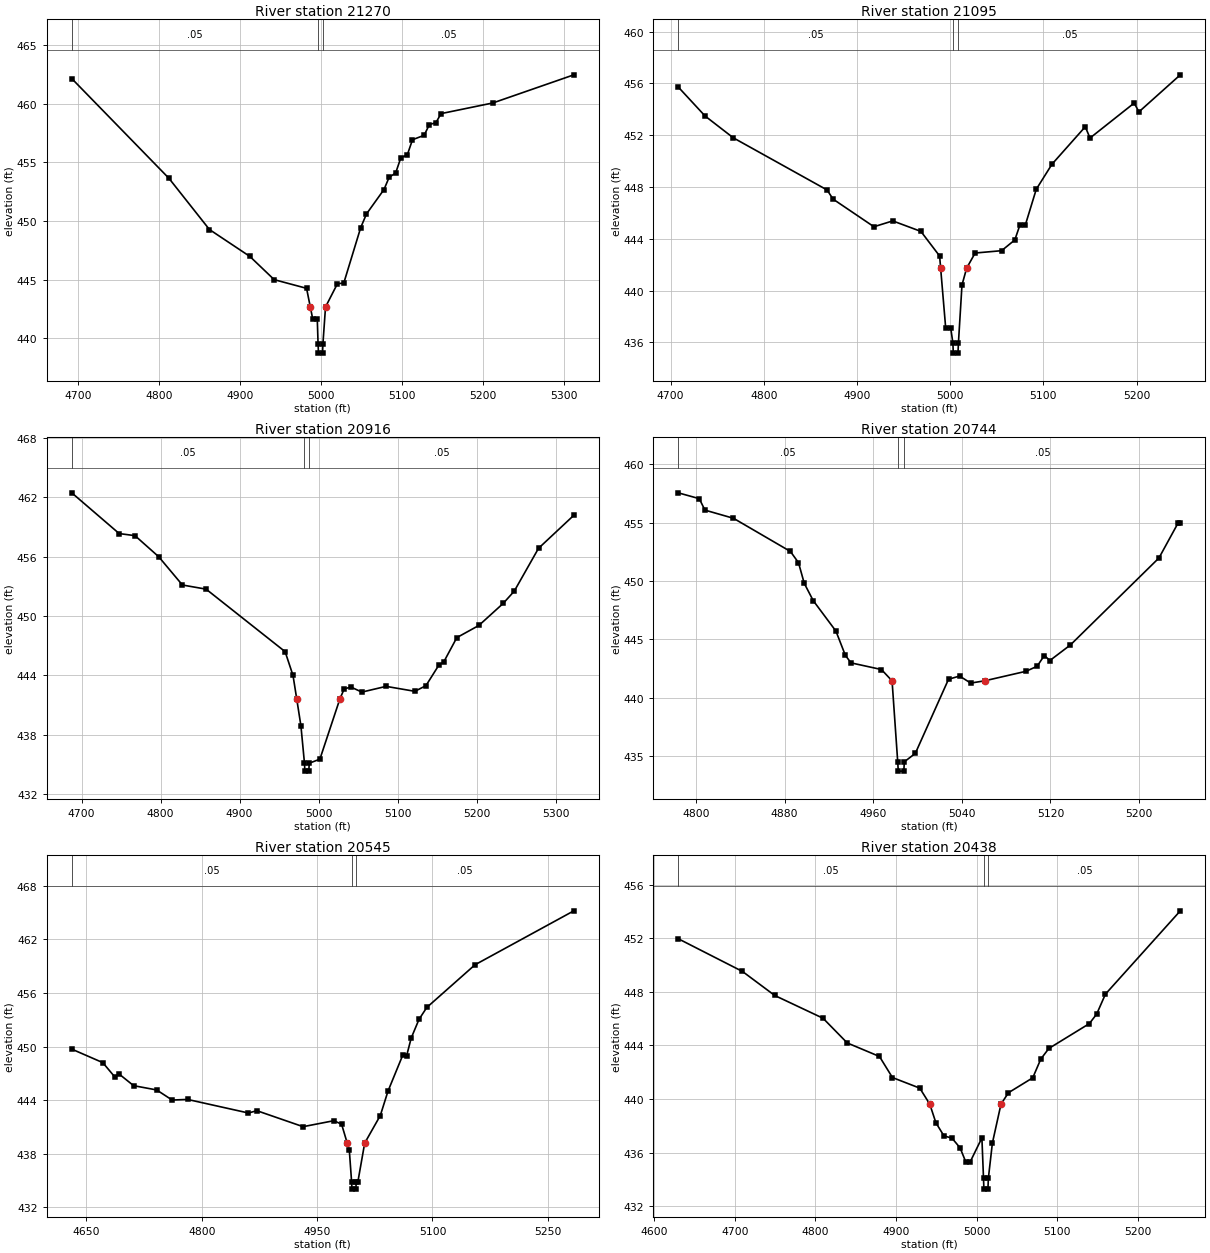
Type RM Length L Ch R = 1,21270,175,175,175
BEGIN DESCRIPTION:
UNT 173 in LFCCL Watershed 39.0
END DESCRIPTION:
XS GIS Cut Line= 3
      2822825.02      7012925.00      2823125.00      7012925.00
      2823324.98      7012675.03
#Sta/Elev= 30
  4691.7  462.16  4811.7  453.65  4861.7  449.28  4911.7  446.98  4941.7  445.00
  4981.7  444.26  4986.3  442.67  4989.2  441.68  4994.9  441.68  4995.9  439.53
  4996.4  438.73  5001.4  438.73  5001.9  439.53  5005.1  442.67  5019.7  444.64
  5027.7  444.72  5048.5  449.43  5055.7  450.61  5077.3  452.69  5083.7  453.74
  5091.7  454.10  5098.1  455.40  5106.1  455.65  5112.5  456.94  5126.9  457.32
  5133.4  458.24  5141.4  458.39  5147.8  459.17  5211.8  460.08  5311.8  462.48
#Mann=3,-1,0
  4691.7    0.05       0  4995.9    0.03       0  5001.9    0.05       0
Bank Sta=4986.3,5005.1
Exp/Cntr=0.3,0.1

Type RM Length L Ch R = 1,21095,179,179,179
BEGIN DESCRIPTION:
XS4019A
END DESCRIPTION:
XS GIS Cut Line= 4
      2822916.42      7013109.68      2823202.91      7013075.82
      2823257.59      7013015.92      2823288.78      7012849.61
#Sta/Elev= 30
  4708.2  455.72  4737.0  453.48  4767.2  451.80  4867.9  447.77  4874.4  447.06
  4918.2  444.93  4938.4  445.38  4968.6  444.57  4988.7  442.67  4989.8  441.73
  4995.2  437.12  5000.6  437.12  5002.9  435.97  5003.4  435.17  5008.4  435.17
  5008.9  435.97  5012.7  440.43  5017.7  441.73  5026.8  442.90  5055.2  443.08
  5069.4  443.91  5075.0  445.09  5080.8  445.09  5092.4  447.82  5109.3  449.76
  5145.0  452.65  5150.1  451.78  5197.5  454.48  5202.6  453.80  5247.0  456.66
#Mann=3,-1,0
  4708.2    0.05       0  5002.9    0.03       0  5008.9    0.05       0
Bank Sta=4989.8,5017.7
Exp/Cntr=0.3,0.1

Type RM Length L Ch R = 1,20916,172,172,172
BEGIN DESCRIPTION:
UNT 173 in LFCCL Watershed 38.0
END DESCRIPTION:
XS GIS Cut Line= 3
      2822824.98      7013225.00      2823125.00      7013225.00
      2823424.98      7013374.99
#Sta/Elev= 30
  4687.6  462.45  4747.6  458.33  4767.6  458.12  4797.6  455.99  4827.6  453.13
  4857.6  452.71  4957.6  446.39  4967.6  443.98  4972.3  441.61  4977.6  438.89
  4982.1  435.11  4982.6  434.31  4987.6  434.31  4988.1  435.11  5001.6  435.52
  5026.9  441.61  5032.3  442.61  5040.7  442.82  5054.7  442.30  5085.4  442.88
  5121.8  442.38  5135.8  442.95  5152.5  445.07  5158.1  445.31  5174.9  447.81
  5202.8  449.04  5233.6  451.27  5247.6  452.51  5278.3  456.84  5323.0  460.18
#Mann=3,-1,0
  4687.6    0.05       0  4982.1    0.03       0  4988.1    0.05       0
Bank Sta=4972.3,5026.9
Exp/Cntr=0.3,0.1

Type RM Length L Ch R = 1,20744,199,199,199
BEGIN DESCRIPTION:
XS4020A
END DESCRIPTION:
XS GIS Cut Line= 3
      2822916.41      7013354.46      2823114.37      7013401.34
      2823364.32      7013398.74
#Sta/Elev= 30
  4783.9  457.55  4802.9  457.05  4808.0  456.07  4833.8  455.37  4885.2  452.53
  4892.5  451.57  4897.7  449.80  4905.8  448.32  4926.3  445.71  4934.8  443.64
  4939.9  442.99  4967.4  442.42  4977.0  441.45  4982.1  434.52  4982.6  433.72
  4987.6  433.72  4988.1  434.52  4998.0  435.24  5028.0  441.59  5038.0  441.86
  5048.0  441.26  5060.5  441.45  5098.0  442.27  5108.0  442.70  5114.5  443.62
  5119.5  443.19  5138.0  444.52  5218.0  451.97  5235.2  454.95  5237.3  454.95
#Mann=3,-1,0
  4783.9    0.05       0  4982.1    0.03       0  4988.1    0.05       0
Bank Sta=4977,5060.5
Exp/Cntr=0.3,0.1

Type RM Length L Ch R = 1,20545,107,107,107
BEGIN DESCRIPTION:
UNT 173 in LFCCL Watershed 37.0
END DESCRIPTION:
XS GIS Cut Line= 3
      2822874.75      7013536.76      2823241.97      7013557.59
      2823524.99      7013525.00
#Sta/Elev= 30
  4631.1  449.71  4671.4  448.20  4687.4  446.56  4692.4  446.94  4711.5  445.62
  4741.5  445.14  4761.6  444.01  4781.6  444.08  4860.8  442.56  4871.7  442.82
  4931.8  441.03  4971.9  441.70  4981.9  441.30  4989.2  439.19  4991.9  438.41
  4994.9  434.84  4995.4  434.04  5000.4  434.04  5000.9  434.84  5003.0  434.84
  5011.9  439.19  5032.2  442.28  5042.2  445.01  5061.3  449.02  5066.3  448.93
  5072.4  450.96  5082.5  453.04  5092.6  454.37  5155.3  459.15  5283.8  465.19
#Mann=3,-1,0
  4631.1    0.05       0  4994.9    0.03       0  5000.9    0.05       0
Bank Sta=4989.2,5011.9
Exp/Cntr=0.3,0.1

Type RM Length L Ch R = 1,20438,177,177,177
BEGIN DESCRIPTION:
XS4021A
END DESCRIPTION:
XS GIS Cut Line= 3
      2822825.33      7013646.13      2823184.68      7013651.34
      2823447.67      7013633.11
#Sta/Elev= 30
  4629.7  451.96  4709.4  449.52  4749.4  447.73  4809.4  446.03  4839.4  444.19
  4879.4  443.18  4895.5  441.61  4929.4  440.82  4941.8  439.63  4949.4  438.24
  4959.4  437.26  4969.4  437.09  4979.4  436.37  4986.7  435.29  4991.7  435.29
  5006.5  437.11  5008.5  434.09  5009.0  433.29  5014.0  433.29  5014.5  434.09
  5019.5  436.72  5030.2  439.63  5039.5  440.48  5069.6  441.59  5079.6  442.99
  5089.6  443.78  5139.8  445.63  5148.9  446.34  5159.8  447.83  5252.7  454.04
#Mann=3,-1,0
  4629.7    0.05       0  5008.5    0.03       0  5014.5    0.05       0
Bank Sta=4941.8,5030.2
Exp/Cntr=0.3,0.1

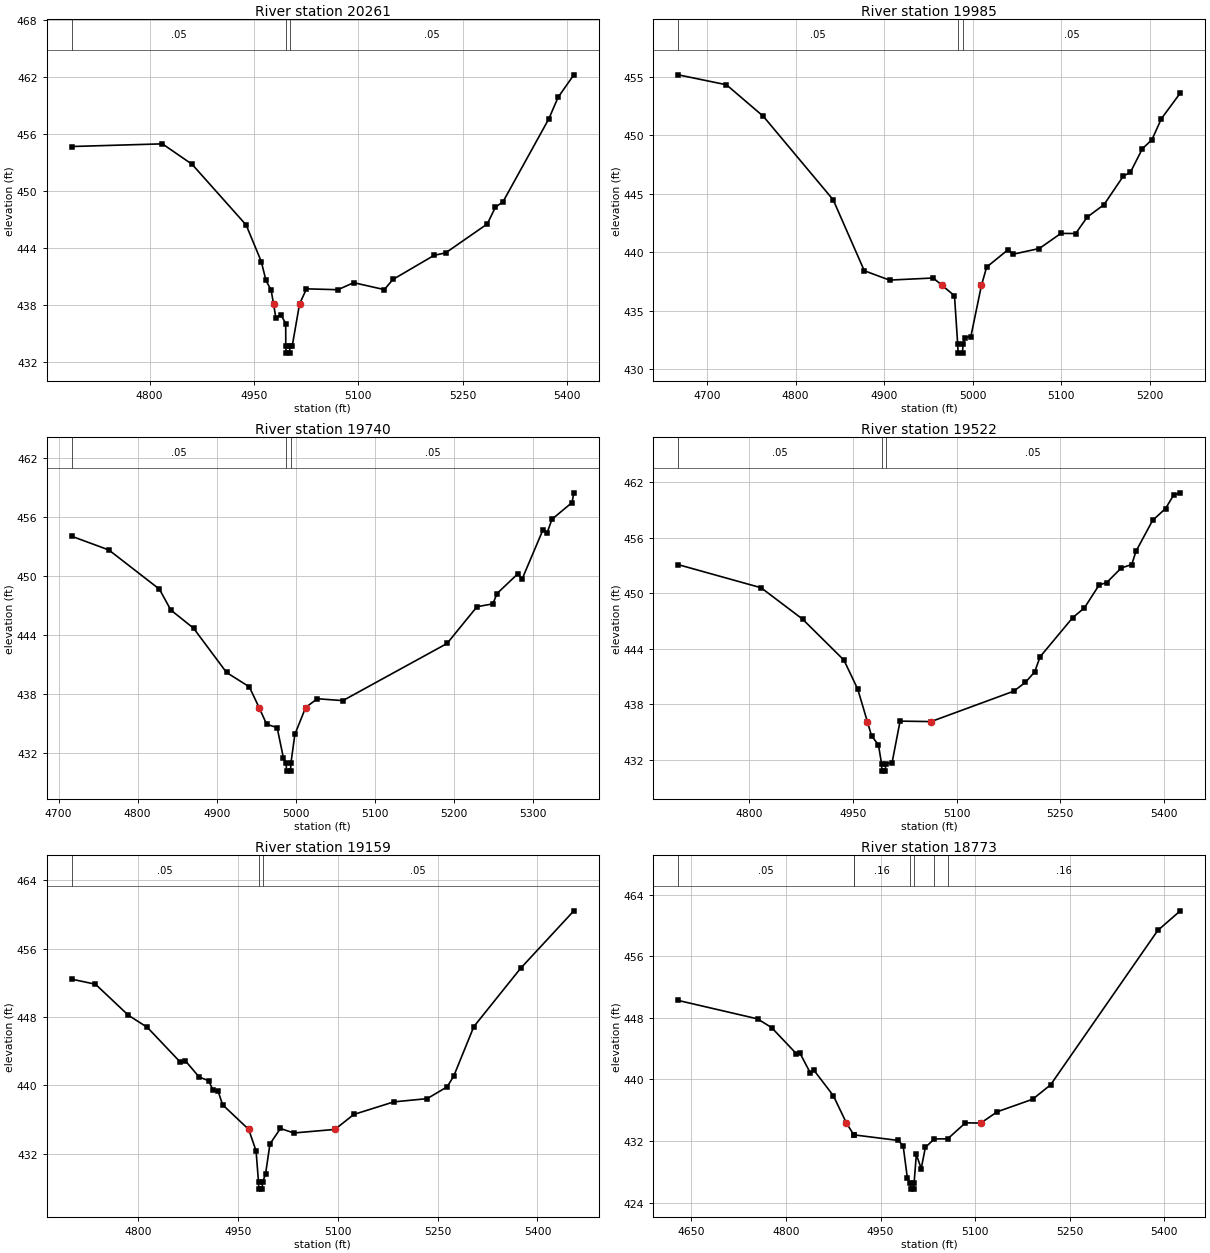
Type RM Length L Ch R = 1,20261,276,276,276
BEGIN DESCRIPTION:
UNT 173 in LFCCL Watershed 36.0
END DESCRIPTION:
XS GIS Cut Line= 3
      2822955.51      7014049.78      2823163.84      7013815.40
      2823525.04      7013624.98
#Sta/Elev= 30
  4688.0  454.65  4818.3  454.93  4861.0  452.78  4938.7  446.40  4960.5  442.55
  4967.2  440.57  4974.7  439.53  4978.1  438.09  4981.4  436.66  4988.7  436.96
  4995.6  436.03  4995.7  433.72  4996.2  432.92  5001.2  432.92  5001.7  433.72
  5005.1  433.72  5015.5  438.09  5025.5  439.68  5070.7  439.59  5093.3  440.33
  5137.4  439.60  5149.8  440.67  5209.1  443.21  5225.5  443.46  5285.5  446.51
  5297.2  448.28  5307.9  448.82  5374.0  457.57  5387.2  459.82  5409.9  462.19
#Mann=3,-1,0
  4688.0    0.05       0  4995.7    0.03       0  5001.7    0.05       0
Bank Sta=4978.1,5015.5
Exp/Cntr=0.3,0.1

Type RM Length L Ch R = 1,19985,245,245,245
BEGIN DESCRIPTION:
XS4022A
END DESCRIPTION:
XS GIS Cut Line= 3
      2823200.32      7014156.53      2823406.03      7013922.17
      2823499.79      7013685.18
#Sta/Elev= 30
  4667.5  455.17  4721.9  454.32  4763.6  451.62  4842.4  444.49  4877.5  438.43
  4906.0  437.63  4955.3  437.81  4965.5  437.17  4979.3  436.29  4982.9  432.19
  4983.4  431.39  4988.4  431.39  4988.9  432.19  4991.3  432.71  4997.8  432.81
  5009.7  437.17  5015.6  438.74  5040.0  440.24  5045.3  439.84  5075.1  440.33
  5099.4  441.62  5116.1  441.61  5129.1  443.01  5148.1  444.08  5169.9  446.52
  5177.8  446.83  5191.4  448.86  5202.1  449.62  5212.9  451.43  5234.2  453.62
#Mann=3,-1,0
  4667.5    0.05       0  4982.9    0.03       0  4988.9    0.05       0
Bank Sta=4965.5,5009.7
Exp/Cntr=0.3,0.1

Type RM Length L Ch R = 1,19740,218,218,218
BEGIN DESCRIPTION:
UNT 173 in LFCCL Watershed 35.0
END DESCRIPTION:
XS GIS Cut Line= 3
      2823361.44      7014287.52      2823561.46      7014037.50
      2823661.04      7013738.74
#Sta/Elev= 30
  4716.7  454.08  4763.6  452.69  4827.6  448.70  4842.0  446.58  4870.8  444.73
  4912.5  440.23  4941.3  438.77  4953.6  436.67  4963.2  434.97  4976.5  434.62
  4984.5  431.51  4987.9  431.00  4988.4  430.20  4993.4  430.20  4993.9  431.00
  4998.9  433.93  5012.5  436.67  5027.3  437.56  5059.6  437.37  5191.4  443.18
  5229.3  446.92  5249.4  447.21  5254.6  448.26  5281.0  450.27  5286.2  449.70
  5312.6  454.71  5317.9  454.41  5324.1  455.81  5349.5  457.51  5351.8  458.50
#Mann=3,-1,0
  4716.7    0.05       0  4987.9    0.03       0  4993.9    0.05       0
Bank Sta=4953.6,5012.5
Exp/Cntr=0.3,0.1

Type RM Length L Ch R = 1,19522,363,363,363
BEGIN DESCRIPTION:
UNT 173 in LFCCL Watershed 34.0
END DESCRIPTION:
XS GIS Cut Line= 3
      2823725.00      7014474.95      2823725.00      7014175.00
      2823875.02      7013774.95
#Sta/Elev= 30
  4696.9  453.10  4816.9  450.60  4876.9  447.21  4936.9  442.77  4956.9  439.63
  4970.8  436.12  4976.9  434.58  4986.9  433.59  4991.4  431.56  4991.9  430.76
  4996.9  430.76  4997.4  431.56  5006.6  431.67  5018.2  436.17  5063.1  436.12
  5182.9  439.41  5199.8  440.37  5213.1  441.49  5221.1  443.14  5268.3  447.37
  5285.2  448.42  5306.6  450.91  5317.3  451.15  5338.6  452.74  5353.7  453.11
  5360.0  454.56  5384.0  457.89  5402.7  459.17  5414.3  460.61  5424.1  460.87
#Mann=3,-1,0
  4696.9    0.05       0  4991.4    0.03       0  4997.4    0.05       0
Bank Sta=4970.8,5063.1
Exp/Cntr=0.3,0.1

Type RM Length L Ch R = 1,19159,386,386,386
BEGIN DESCRIPTION:
UNT 173 in LFCCL Watershed 33.0
END DESCRIPTION:
XS GIS Cut Line= 3
      2823825.03      7014474.98      2824051.39      7014278.86
      2824025.00      7013825.03
#Sta/Elev= 30
  4700.5  452.42  4736.1  451.83  4785.5  448.20  4814.0  446.78  4863.3  442.73
  4871.0  442.88  4891.8  440.97  4906.1  440.54  4912.7  439.42  4920.3  439.32
  4927.0  437.73  4966.2  434.84  4977.3  432.33  4981.0  428.65  4981.5  427.85
  4986.5  427.85  4987.0  428.65  4991.5  429.59  4998.2  433.14  5013.9  434.95
  5033.9  434.42  5095.8  434.84  5124.1  436.59  5184.2  438.06  5234.3  438.44
  5264.3  439.82  5274.3  441.10  5304.4  446.87  5374.5  453.68  5454.6  460.42
#Mann=3,-1,0
  4700.5    0.05       0  4981.0    0.03       0  4987.0    0.05       0
Bank Sta=4966.2,5095.8
Exp/Cntr=0.3,0.1

Type RM Length L Ch R = 1,18773,397,397,397
BEGIN DESCRIPTION:
UNT 173 in LFCCL Watershed 32.0
END DESCRIPTION:
XS GIS Cut Line= 3
      2824074.98      7014575.01      2824375.00      7014425.00
      2824724.99      7014125.01
#Sta/Elev= 30
  4629.1  450.26  4754.9  447.87  4777.3  446.73  4816.4  443.35  4822.0  443.45
  4838.8  440.81  4844.3  441.20  4875.1  437.90  4895.9  434.34  4907.8  432.78
  4908.5  432.80  4978.3  432.08  4985.9  431.37  4992.5  427.22  4997.2  426.56
  4997.7  425.76  5002.7  425.76  5003.2  426.56  5006.8  430.26  5014.5  428.42
  5021.1  431.18  5035.3  432.28  5056.5  432.29  5084.7  434.37  5109.0  434.34
  5135.2  435.81  5191.2  437.43  5219.7  439.30  5389.8  459.36  5425.5  461.90
#Mann=7,-1,0
  4629.1    0.05       0  4907.8    0.07       0  4908.5    0.16       0
  4997.2    0.07       0  5003.2    0.16       0  5035.3    0.12       0
  5056.5    0.16       0
Bank Sta=4895.9,5109
Exp/Cntr=0.3,0.1

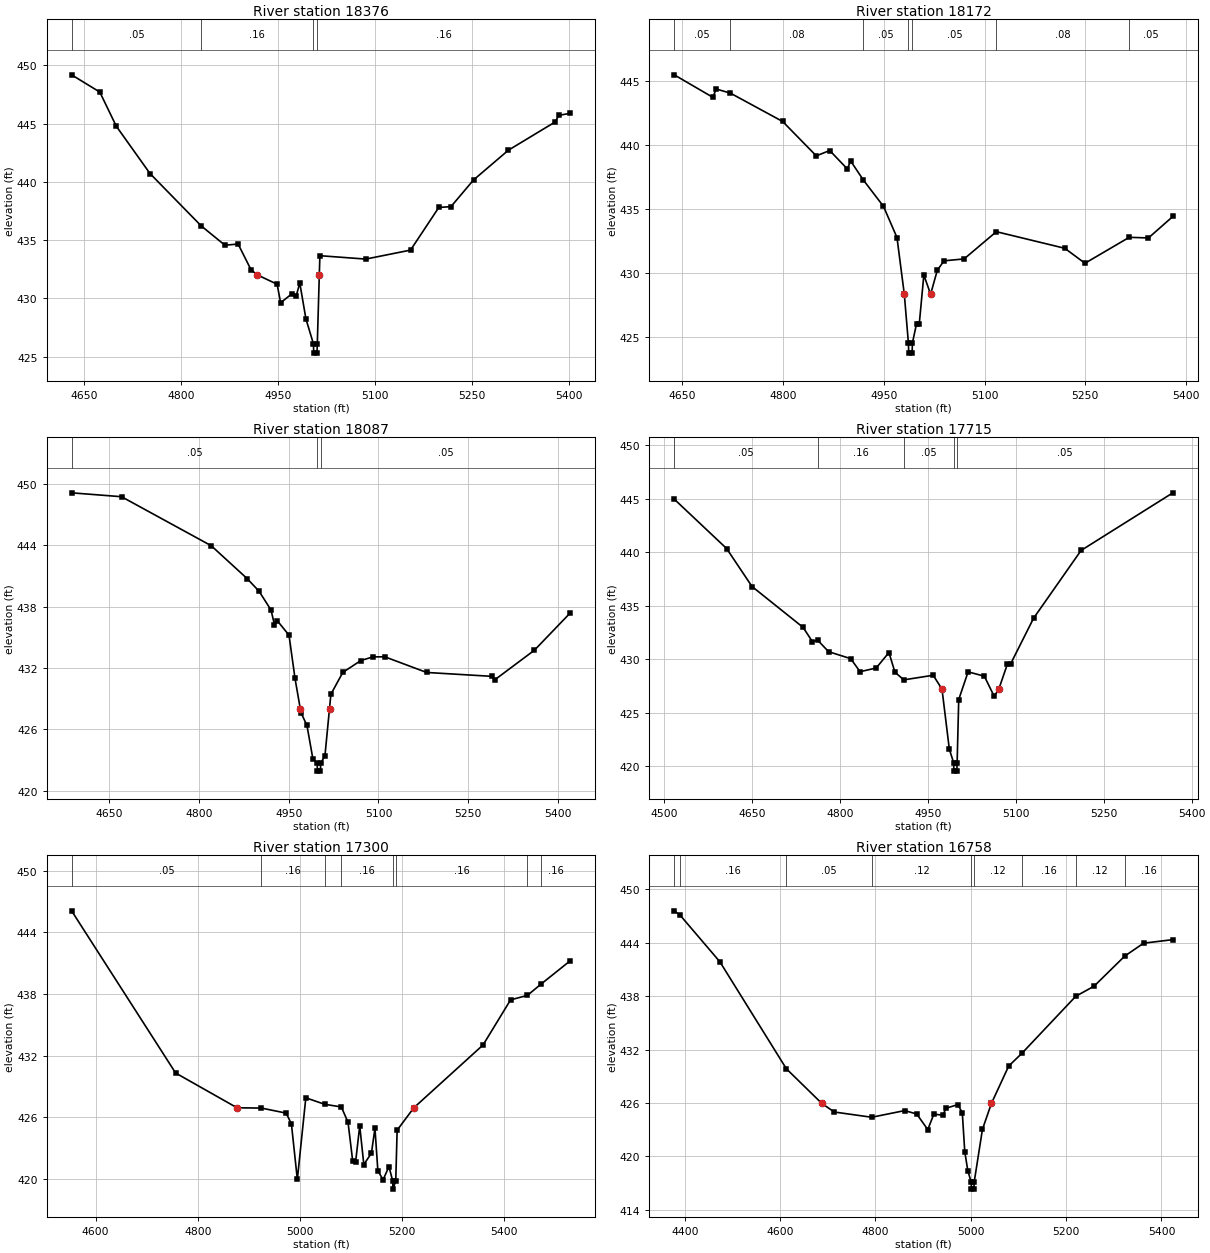
Type RM Length L Ch R = 1,18376,204,204,204
BEGIN DESCRIPTION:
UNT 173 in LFCCL Watershed 31.0
END DESCRIPTION:
XS GIS Cut Line= 3
      2824122.19      7014666.97      2824425.00      7014725.00
      2824853.95      7014552.38
#Sta/Elev= 30
  4631.3  449.18  4674.9  447.70  4700.4  444.77  4752.5  440.71  4831.6  436.22
  4868.3  434.56  4888.7  434.66  4908.5  432.47  4917.8  432.03  4949.0  431.21
  4954.4  429.62  4972.0  430.40  4978.6  430.22  4984.0  431.33  4993.5  428.24
  5005.1  426.10  5005.6  425.30  5010.6  425.30  5011.1  426.10  5014.2  432.03
  5015.1  433.66  5086.0  433.37  5155.2  434.14  5198.9  437.80  5217.7  437.87
  5252.6  440.16  5306.4  442.71  5378.9  445.14  5384.3  445.70  5402.0  445.88
#Mann=4,-1,0
  4631.3    0.05       0  4831.6    0.16       0  5005.1    0.07       0
  5011.1    0.16       0
Bank Sta=4917.8,5014.2
Exp/Cntr=0.3,0.1

Type RM Length L Ch R = 1,18172,85,85,85
BEGIN DESCRIPTION:
XS4023A
END DESCRIPTION:
XS GIS Cut Line= 3
      2824033.66      7014857.07      2824398.22      7014875.30
      2824775.87      7014880.51
#Sta/Elev= 30
  4637.8  445.51  4695.3  443.75  4700.3  444.40  4721.4  444.08  4799.3  441.86
  4849.4  439.17  4869.4  439.59  4895.6  438.15  4900.6  438.77  4919.5  437.28
  4949.5  435.22  4969.6  432.78  4980.5  428.35  4986.6  424.54  4987.1  423.74
  4992.1  423.74  4992.6  424.54  4998.7  426.03  5002.8  426.03  5009.6  429.85
  5019.7  428.35  5029.6  430.21  5039.6  430.96  5069.6  431.11  5117.6  433.24
  5219.6  431.94  5249.6  430.77  5315.6  432.80  5344.2  432.75  5380.5  434.43
#Mann=7,-1,0
  4637.8    0.05       0  4721.4    0.08       0  4919.5    0.05       0
  4986.6    0.04       0  4992.6    0.05       0  5117.6    0.08       0
  5315.6    0.05       0
Bank Sta=4980.5,5019.7
Exp/Cntr=0.3,0.1

Type RM Length L Ch R = 1,18087,372,372,372
BEGIN DESCRIPTION:
XS4024A
END DESCRIPTION:
XS GIS Cut Line= 3
      2823981.51      7014956.03      2824426.87      7014961.24
      2824814.86      7014974.26
#Sta/Elev= 30
  4586.9  449.12  4670.4  448.74  4820.4  443.95  4880.4  440.74  4900.4  439.50
  4920.4  437.66  4926.0  436.24  4931.0  436.61  4950.4  435.21  4960.4  430.99
  4969.2  428.04  4970.4  427.64  4980.4  426.39  4990.4  423.10  4997.4  422.73
  4997.9  421.93  5002.9  421.93  5003.4  422.73  5010.4  423.40  5018.1  428.04
  5020.4  429.44  5040.4  431.58  5070.4  432.73  5090.5  433.09  5110.5  433.10
  5180.5  431.57  5289.6  431.19  5294.6  430.86  5360.6  433.74  5420.5  437.38
#Mann=3,-1,0
  4586.9    0.05       0  4997.4    0.03       0  5003.4    0.05       0
Bank Sta=4969.2,5018.1
Exp/Cntr=0.3,0.1

Type RM Length L Ch R = 1,17715,415,415,415
BEGIN DESCRIPTION:
UNT 173 in LFCCL Watershed 29.0
END DESCRIPTION:
XS GIS Cut Line= 3
      2824224.96      7015425.02      2824675.00      7015175.00
      2824974.97      7015025.02
#Sta/Elev= 30
  4517.7  444.95  4607.0  440.34  4650.4  436.79  4737.4  432.98  4753.4  431.64
  4762.0  431.80  4780.9  430.71  4818.6  430.06  4834.6  428.84  4862.1  429.19
  4883.8  430.63  4894.1  428.79  4909.2  428.08  4959.3  428.51  4974.3  427.21
  4986.8  421.60  4994.1  420.36  4994.6  419.56  4999.6  419.56  5000.1  420.36
  5002.8  426.24  5018.8  428.83  5046.5  428.42  5063.3  426.54  5071.1  427.21
  5085.6  429.52  5091.2  429.56  5130.4  433.83  5211.4  440.16  5367.9  445.54
#Mann=5,-1,0
  4517.7    0.05       0  4762.0    0.16       0  4909.2    0.05       0
  4994.1    0.03       0  5000.1    0.05       0
Bank Sta=4974.3,5071.1
Exp/Cntr=0.3,0.1

Type RM Length L Ch R = 1,17300,542,542,542
BEGIN DESCRIPTION:
UNT 173 in LFCCL Watershed 28.0
END DESCRIPTION:
XS GIS Cut Line= 3
      2824225.01      7015475.00      2824675.00      7015575.00
      2824925.02      7016025.04
#Sta/Elev= 30
  4552.9  446.08  4756.5  430.31  4876.7  426.93  4924.4  426.90  4972.9  426.41
  4983.1  425.36  4994.7  419.96  5011.3  427.90  5048.1  427.27  5080.8  427.01
  5093.9  425.52  5103.1  421.73  5108.8  421.69  5116.8  425.18  5124.8  421.41
  5139.7  422.52  5146.6  424.94  5152.3  420.79  5162.6  419.94  5174.0  421.21
  5181.3  419.82  5181.8  419.02  5187.3  419.82  5190.0  424.75  5222.7  426.93
  5358.2  433.04  5412.0  437.42  5445.0  437.86  5472.5  438.99  5528.7  441.22
#Mann=8,-1,0
  4552.9    0.05       0  4924.4    0.16       0  5048.1    0.05       0
  5080.8    0.16       0  5181.3    0.07       0  5187.3    0.16       0
  5445.0    0.12       0  5472.5    0.16       0
Bank Sta=4876.7,5222.7
Exp/Cntr=0.3,0.1

Type RM Length L Ch R = 1,16758,588,588,588
BEGIN DESCRIPTION:
UNT 173 in LFCCL Watershed 27.0
END DESCRIPTION:
XS GIS Cut Line= 3
      2823924.98      7015824.99      2824475.00      7016025.00
      2824924.97      7016124.99
#Sta/Elev= 30
  4377.7  447.60  4390.5  447.08  4473.5  441.87  4613.0  429.84  4687.5  425.94
  4713.6  424.98  4792.0  424.39  4861.2  425.14  4886.5  424.76  4909.7  423.00
  4922.4  424.74  4941.7  424.62  4947.7  425.40  4973.2  425.82  4982.2  424.85
  4987.3  420.53  4993.7  418.38  5000.8  417.11  5001.3  416.31  5006.6  416.31
  5007.1  417.11  5024.4  423.03  5043.2  425.94  5079.5  430.15  5107.4  431.59
  5220.2  437.99  5258.7  439.13  5323.0  442.51  5362.5  443.96  5423.9  444.36
#Mann=9,-1,0
  4377.7    0.05       0  4390.5    0.16       0  4613.0    0.05       0
  4792.0    0.12       0  5000.8    0.07       0  5007.1    0.12       0
  5107.4    0.16       0  5220.2    0.12       0  5323.0    0.16       0
Bank Sta=4687.5,5043.2
Exp/Cntr=0.3,0.1