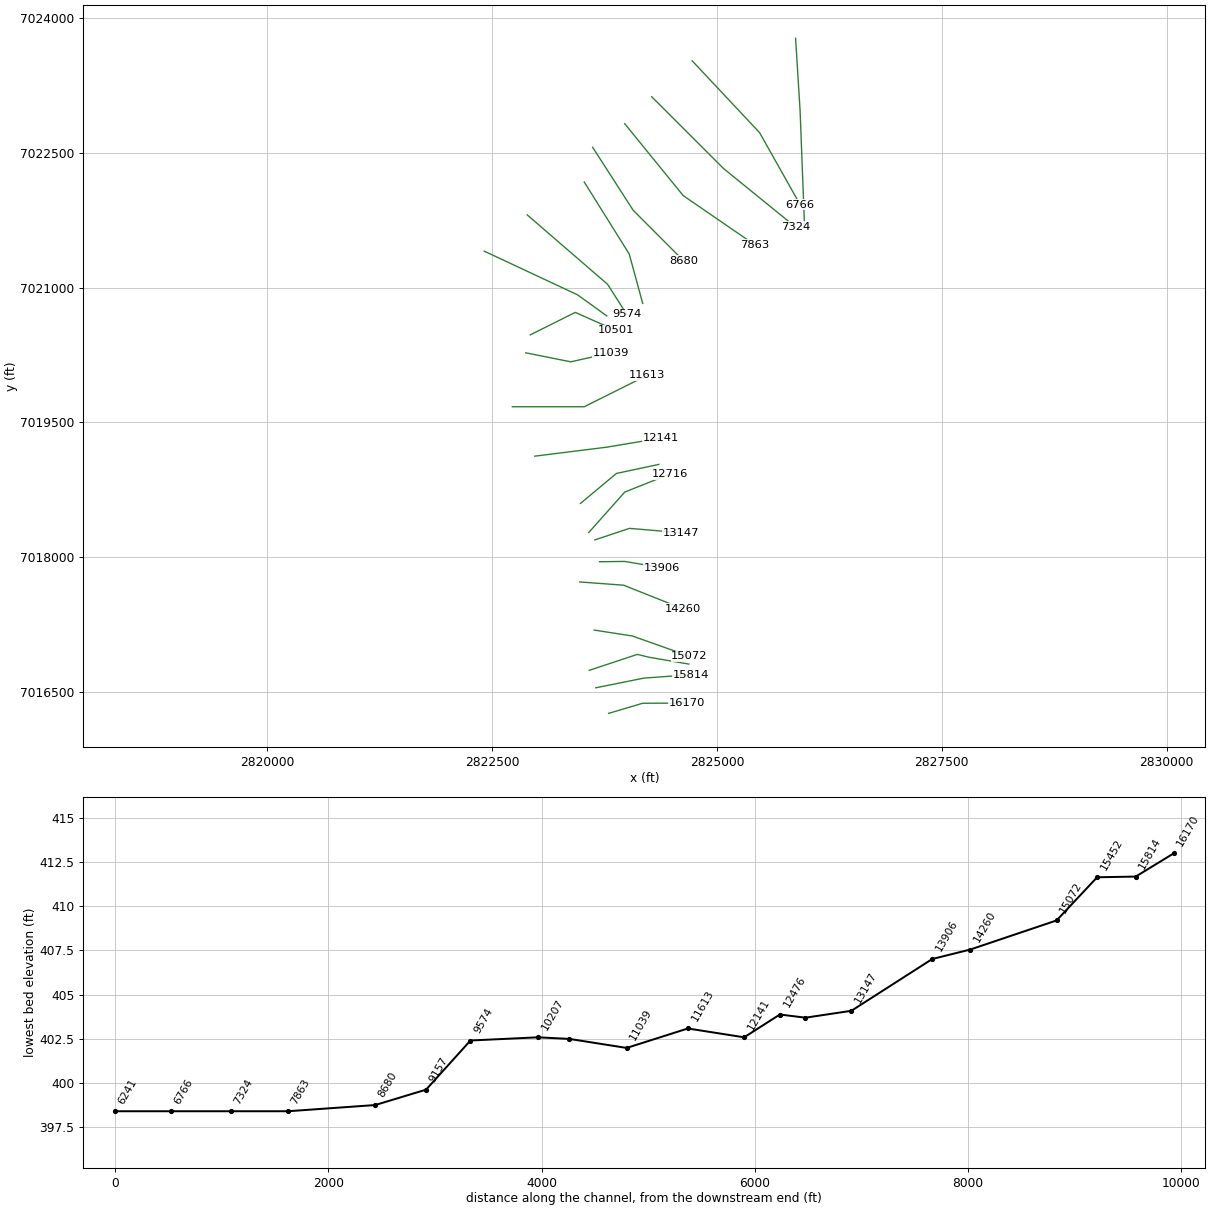
HEC-RAS study UNT 173 in LFCCL Watershed.prj: UNT 173 in LFCCL Watershed Base Level Engineering

--- UNT 173 in LFCCL Watershed.g01 (geometry) --- (continued)

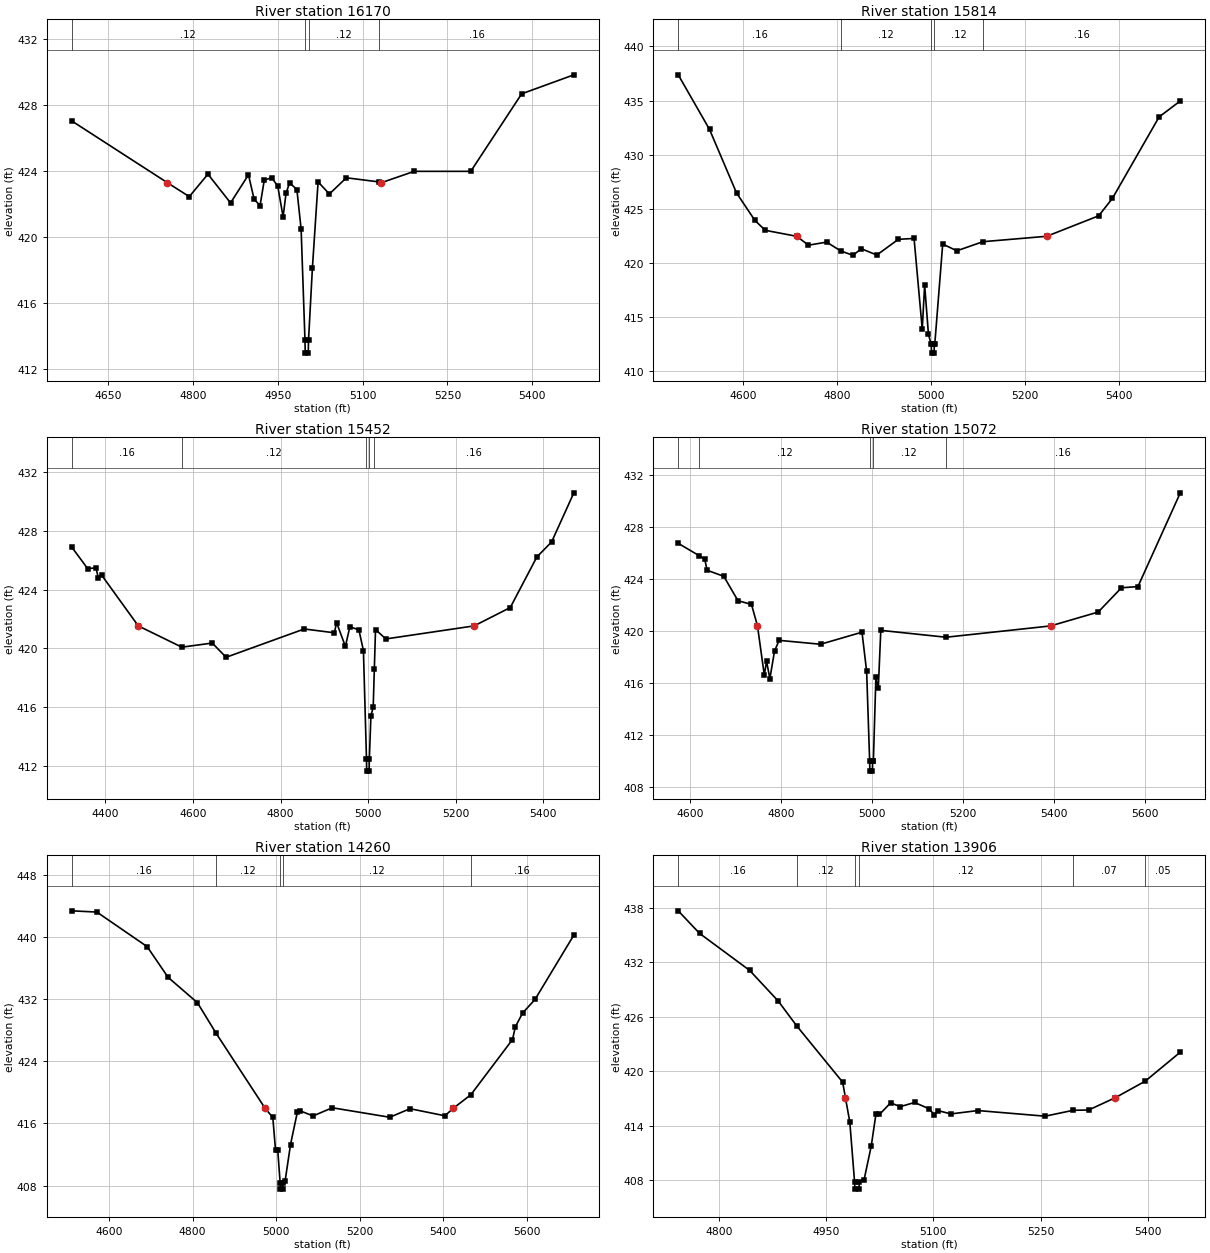
Type RM Length L Ch R = 1,16170,356,356,356
BEGIN DESCRIPTION:
UNT 173 in LFCCL Watershed 26.0
END DESCRIPTION:
XS GIS Cut Line= 3
      2823795.80      7016262.45      2824175.00      7016375.00
      2824667.34      7016377.04
#Sta/Elev= 30
  4585.7  427.04  4754.9  423.30  4793.5  422.46  4826.5  423.82  4866.5  422.08
  4898.2  423.78  4908.2  422.30  4918.7  421.92  4926.2  423.47  4939.5  423.60
  4950.0  423.09  4959.4  421.24  4964.6  422.65  4970.8  423.30  4983.8  422.89
  4991.3  420.49  4998.1  413.79  4998.6  412.99  5003.9  412.99  5004.4  413.79
  5011.3  418.17  5021.3  423.35  5041.3  422.62  5071.3  423.60  5129.1  423.35
  5132.9  423.30  5191.3  423.99  5291.3  423.99  5381.3  428.68  5473.6  429.83
#Mann=4,-1,0
  4585.7    0.12       0  4998.1    0.07       0  5004.4    0.12       0
  5129.1    0.16       0
Bank Sta=4754.9,5132.9
Exp/Cntr=0.3,0.1

Type RM Length L Ch R = 1,15814,362,362,362
BEGIN DESCRIPTION:
XS4025A
END DESCRIPTION:
XS GIS Cut Line= 3
      2823653.40      7016547.17      2824188.15      7016654.81
      2824708.98      7016693.01
#Sta/Elev= 30
  4461.9  437.38  4528.4  432.34  4585.9  426.47  4625.0  423.93  4647.1  423.02
  4713.7  422.47  4738.9  421.65  4777.5  421.93  4807.0  421.13  4833.4  420.71
  4851.2  421.32  4884.2  420.74  4930.0  422.19  4963.4  422.27  4980.8  413.90
  4985.9  417.97  4994.0  413.41  5000.0  412.48  5000.5  411.68  5006.0  411.68
  5006.5  412.48  5007.4  412.48  5024.3  421.75  5054.4  421.13  5109.9  421.97
  5245.5  422.47  5356.0  424.36  5385.2  425.97  5484.5  433.49  5529.6  434.97
#Mann=5,-1,0
  4461.9    0.16       0  4807.0    0.12       0  5000.0    0.07       0
  5006.5    0.12       0  5109.9    0.16       0
Bank Sta=4713.7,5245.5
Exp/Cntr=0.3,0.1

Type RM Length L Ch R = 1,15452,380,380,380
BEGIN DESCRIPTION:
XS4027A
END DESCRIPTION:
XS GIS Cut Line= 4
      2823580.47      7016741.60      2824115.23      7016918.70
      2824243.71      7016887.45      2824688.14      7016811.06
#Sta/Elev= 30
  4323.3  426.91  4359.7  425.44  4378.6  425.50  4383.9  424.81  4391.3  425.01
  4475.2  421.54  4574.6  420.09  4644.1  420.37  4675.7  419.40  4854.2  421.33
  4922.9  421.07  4928.1  421.76  4948.1  420.14  4958.4  421.49  4979.0  421.26
  4989.3  419.86  4996.3  412.44  4996.8  411.64  5002.3  411.64  5002.8  412.44
  5006.4  415.43  5011.6  415.98  5014.2  418.58  5016.9  421.29  5040.5  420.65
  5242.2  421.54  5324.6  422.79  5385.4  426.24  5419.0  427.26  5469.8  430.61
#Mann=5,-1,0
  4323.3    0.16       0  4574.6    0.12       0  4996.3    0.07       0
  5002.8    0.12       0  5014.2    0.16       0
Bank Sta=4475.2,5242.2
Exp/Cntr=0.3,0.1

Type RM Length L Ch R = 1,15072,812,812,812
BEGIN DESCRIPTION:
XS4026A
END DESCRIPTION:
XS GIS Cut Line= 3
      2823636.06      7017189.54      2824059.68      7017123.56
      2824695.07      7016897.88
#Sta/Elev= 30
  4574.5  426.74  4620.5  425.79  4632.8  425.52  4637.8  424.67  4674.6  424.20
  4705.8  422.32  4735.4  422.04  4748.6  420.38  4763.5  416.61  4768.6  417.65
  4775.8  416.32  4786.0  418.44  4796.1  419.27  4887.2  418.97  4978.2  419.90
  4988.4  416.88  4995.0  410.00  4995.5  409.20  5001.1  409.20  5001.6  410.00
  5003.2  410.00  5008.7  416.42  5014.0  415.58  5019.5  420.04  5162.8  419.51
  5392.4  420.38  5497.1  421.45  5548.2  423.32  5584.4  423.41  5677.5  430.63
#Mann=5,-1,0
  4574.5    0.16       0  4620.5    0.12       0  4995.0    0.07       0
  5001.6    0.12       0  5162.8    0.16       0
Bank Sta=4748.6,5392.4
Exp/Cntr=0.3,0.1

Type RM Length L Ch R = 1,14260,354,354,354
BEGIN DESCRIPTION:
UNT 173 in LFCCL Watershed 23.0
END DESCRIPTION:
XS GIS Cut Line= 3
      2823475.04      7017725.00      2823963.02      7017689.00
      2824625.02      7017424.99
#Sta/Elev= 30
  4510.7  443.33  4570.8  443.17  4691.1  438.73  4741.3  434.78  4811.5  431.52
  4856.1  427.60  4973.7  417.93  4992.0  416.77  4998.5  412.56  5003.8  412.56
  5009.6  408.35  5010.1  407.55  5015.8  407.55  5016.3  408.35  5021.3  408.55
  5034.4  413.28  5050.9  417.49  5056.3  417.64  5088.3  416.96  5134.5  418.01
  5272.0  416.79  5320.5  417.89  5404.0  416.98  5423.8  417.93  5466.2  419.69
  5565.8  426.78  5572.7  428.42  5590.0  430.19  5619.7  431.93  5712.7  440.21
#Mann=5,-1,0
  4510.7    0.16       0  4856.1    0.12       0  5009.6    0.07       0
  5016.3    0.12       0  5466.2    0.16       0
Bank Sta=4973.7,5423.8
Exp/Cntr=0.3,0.1

Type RM Length L Ch R = 1,13906,759,759,759
BEGIN DESCRIPTION:
XS4029A
END DESCRIPTION:
XS GIS Cut Line= 3
      2823695.11      7017949.95      2823972.87      7017953.42
      2824391.50      7017884.23
#Sta/Elev= 30
  4743.3  437.66  4773.2  435.17  4843.2  431.10  4883.2  427.72  4908.9  425.00
  4973.2  418.80  4977.1  417.09  4983.2  414.41  4989.9  407.82  4990.4  407.02
  4996.1  407.02  4996.6  407.82  5003.2  408.05  5013.2  411.77  5019.7  415.24
  5024.7  415.24  5040.3  416.52  5053.7  416.10  5073.9  416.56  5094.2  415.86
  5101.3  415.20  5106.4  415.67  5124.6  415.30  5162.4  415.67  5256.4  415.05
  5295.6  415.70  5317.2  415.73  5354.6  417.09  5396.4  418.91  5445.4  422.10
#Mann=6,-1,0
  4743.3    0.16       0  4908.9    0.12       0  4989.9    0.07       0
  4996.6    0.12       0  5295.6    0.07       0  5396.4    0.05       0
Bank Sta=4977.1,5354.6
Exp/Cntr=0.3,0.1

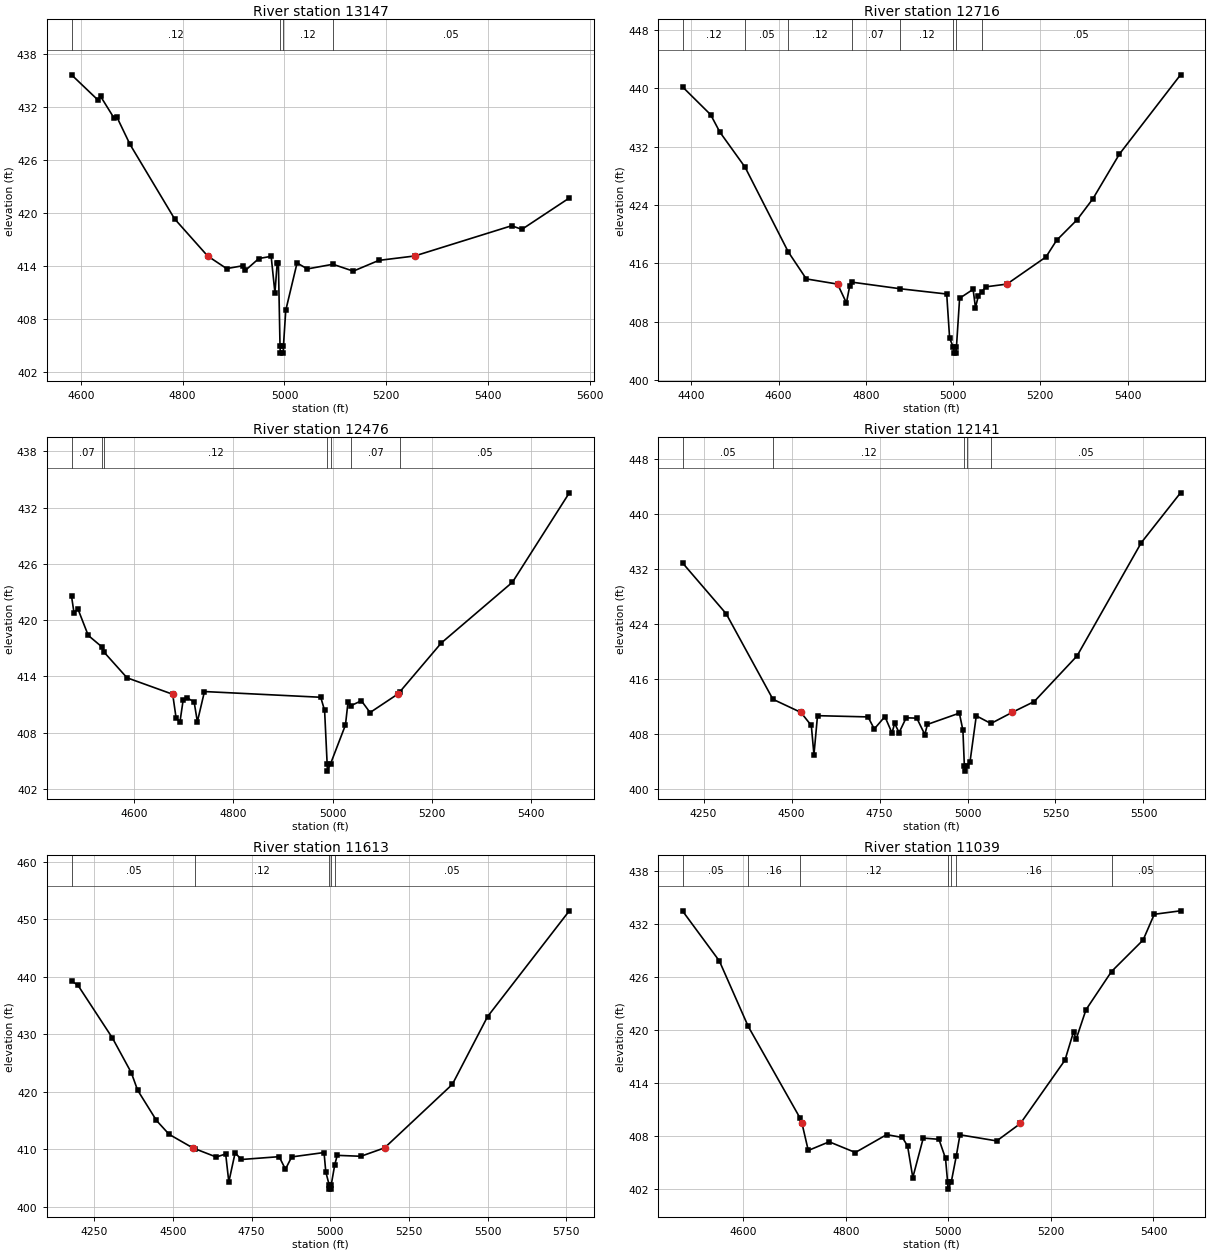
Type RM Length L Ch R = 1,13147,431,431,431
BEGIN DESCRIPTION:
XS4028A
END DESCRIPTION:
XS GIS Cut Line= 3
      2823642.99      7018193.00      2824028.43      7018321.48
      2824597.87      7018272.87
#Sta/Elev= 30
  4581.7  435.66  4633.4  432.81  4638.6  433.23  4665.0  430.77  4670.3  430.92
  4696.6  427.76  4784.1  419.32  4849.0  415.11  4886.3  413.68  4918.0  414.00
  4923.2  413.48  4949.6  414.82  4973.8  415.07  4981.2  410.93  4985.7  414.33
  4988.0  414.33  4991.2  404.89  4991.7  404.09  4997.4  404.09  4997.9  404.89
  5002.5  408.95  5024.7  414.32  5044.8  413.64  5095.1  414.17  5135.1  413.39
  5185.3  414.61  5255.7  415.11  5446.2  418.54  5466.3  418.13  5559.5  421.69
#Mann=4,-1,0
  4581.7    0.12       0  4991.2    0.07       0  4997.9    0.12       0
  5095.1    0.05       0
Bank Sta=4849,5255.7
Exp/Cntr=0.3,0.1

Type RM Length L Ch R = 1,12716,240,240,240
BEGIN DESCRIPTION:
UNT 173 in LFCCL Watershed 21.0
END DESCRIPTION:
XS GIS Cut Line= 3
      2823575.00      7018275.00      2823975.00      7018725.00
      2824475.01      7018925.00
#Sta/Elev= 30
  4380.6  440.16  4444.6  436.37  4465.5  434.00  4523.4  429.18  4622.4  417.57
  4663.7  413.87  4735.4  413.16  4755.6  410.58  4763.2  412.92  4767.6  413.43
  4879.2  412.52  4985.4  411.80  4992.1  405.74  5000.7  404.50  5001.2  403.70
  5007.2  403.70  5007.7  404.50  5015.0  411.22  5045.9  412.44  5051.3  409.95
  5058.1  411.56  5065.3  412.11  5075.6  412.79  5123.4  413.16  5212.9  416.88
  5237.1  419.15  5284.2  421.98  5320.6  424.87  5381.2  430.98  5521.2  441.84
#Mann=8,-1,0
  4380.6    0.12       0  4523.4    0.05       0  4622.4    0.12       0
  4767.6    0.07       0  4879.2    0.12       0  5000.7    0.07       0
  5007.7    0.12       0  5065.3    0.05       0
Bank Sta=4735.4,5123.4
Exp/Cntr=0.3,0.1

Type RM Length L Ch R = 1,12476,335,335,335
BEGIN DESCRIPTION:
XS4030A
END DESCRIPTION:
XS GIS Cut Line= 3
      2823483.29      7018599.26      2823882.59      7018932.59
      2824354.84      7019033.29
#Sta/Elev= 30
  4474.0  422.52  4478.9  420.79  4486.7  421.20  4507.6  418.36  4535.7  417.11
  4539.0  416.60  4585.7  413.84  4677.8  412.08  4684.6  409.57  4692.4  409.12
  4698.9  411.47  4706.7  411.70  4721.0  411.26  4727.5  409.15  4741.8  412.37
  4976.1  411.76  4983.9  410.35  4989.0  404.68  4989.5  403.88  4996.0  404.68
  5025.9  408.80  5031.0  411.21  5037.3  410.87  5058.0  411.39  5075.5  410.13
  5130.8  412.08  5135.5  412.34  5219.0  417.55  5362.5  424.04  5477.0  433.57
#Mann=7,-1,0
  4474.0    0.07       0  4535.7    0.16       0  4539.0    0.12       0
  4989.0    0.07       0  4996.0    0.12       0  5037.3    0.07       0
  5135.5    0.05       0
Bank Sta=4677.8,5130.8
Exp/Cntr=0.3,0.1

Type RM Length L Ch R = 1,12141,528,528,528
BEGIN DESCRIPTION:
double UNT 173 in LFCCL Watershed 20.0
END DESCRIPTION:
XS GIS Cut Line= 3
      2822975.04      7019125.00      2823775.00      7019225.00
      2824375.03      7019325.01
#Sta/Elev= 30
  4190.8  432.89  4314.2  425.52  4447.0  413.06  4526.4  411.15  4556.1  409.24
  4563.6  404.98  4573.7  410.67  4717.3  410.49  4735.0  408.73  4765.2  410.54
  4785.4  408.14  4792.9  409.56  4805.5  408.20  4825.7  410.36  4855.9  410.31
  4878.6  407.92  4886.1  409.40  4976.8  411.04  4986.9  408.55  4991.0  403.39
  4991.5  402.59  4998.0  403.39  5007.1  403.95  5024.9  410.65  5066.5  409.53
  5126.9  411.15  5189.6  412.73  5311.3  419.38  5493.7  435.87  5605.3  443.14
#Mann=5,-1,0
  4190.8    0.05       0  4447.0    0.12       0  4991.0    0.07       0
  4998.0    0.12       0  5066.5    0.05       0
Bank Sta=4526.4,5126.9
Exp/Cntr=0.3,0.1

Type RM Length L Ch R = 1,11613,574,574,574
BEGIN DESCRIPTION:
double UNT 173 in LFCCL Watershed 19.0
END DESCRIPTION:
XS GIS Cut Line= 3
      2822725.04      7019675.00      2823525.00      7019675.00
      2824225.02      7020025.01
#Sta/Elev= 30
  4177.3  439.26  4197.3  438.55  4307.3  429.35  4367.3  423.32  4387.3  420.29
  4447.3  415.02  4487.3  412.62  4562.6  410.26  4570.1  410.10  4637.3  408.67
  4667.3  409.20  4677.3  404.34  4697.3  409.39  4717.3  408.24  4837.3  408.73
  4857.3  406.56  4877.3  408.69  4980.1  409.45  4985.6  406.08  4996.1  403.89
  4996.6  403.09  5002.6  403.09  5003.1  403.89  5014.2  407.36  5022.0  408.96
  5097.4  408.80  5172.5  410.26  5388.1  421.31  5499.9  433.07  5759.9  451.46
#Mann=5,-1,0
  4177.3    0.05       0  4570.1    0.12       0  4996.1    0.07       0
  5003.1    0.12       0  5014.2    0.05       0
Bank Sta=4562.6,5172.5
Exp/Cntr=0.3,0.1

Type RM Length L Ch R = 1,11039,538,538,538
BEGIN DESCRIPTION:
double UNT 173 in LFCCL Watershed 18.0
END DESCRIPTION:
XS GIS Cut Line= 3
      2822874.97      7020275.01      2823375.00      7020175.00
      2823825.00      7020275.00
#Sta/Elev= 30
  4481.9  433.40  4553.3  427.78  4609.6  420.38  4711.1  409.98  4714.5  409.41
  4726.7  406.36  4767.5  407.34  4818.5  406.13  4879.6  408.15  4910.2  407.83
  4920.4  406.87  4930.6  403.30  4951.0  407.76  4981.6  407.62  4994.4  405.47
  4998.5  402.79  4999.1  401.99  5005.6  402.79  5015.4  405.73  5022.6  408.13
  5094.3  407.44  5140.5  409.41  5227.4  416.57  5244.1  419.77  5249.2  418.94
  5268.4  422.27  5318.2  426.59  5379.8  430.15  5401.6  433.06  5452.8  433.45
#Mann=7,-1,0
  4481.9    0.05       0  4609.6    0.16       0  4711.1    0.12       0
  4998.5    0.07       0  5005.6    0.12       0  5015.4    0.16       0
  5318.2    0.05       0
Bank Sta=4714.5,5140.5
Exp/Cntr=0.3,0.1

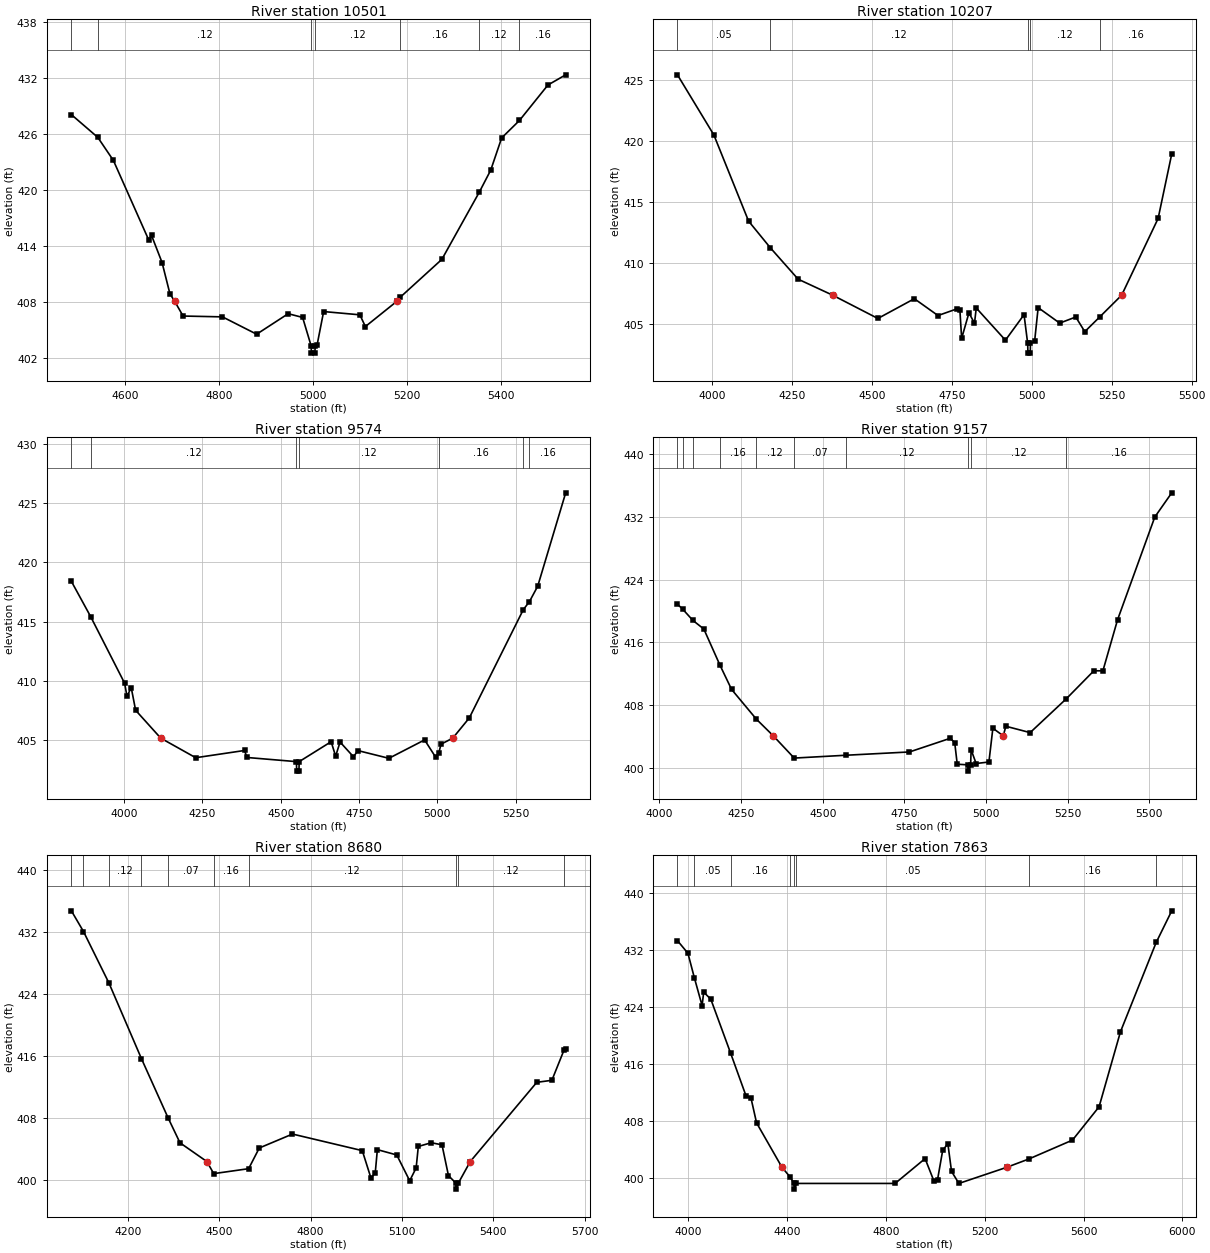
Type RM Length L Ch R = 1,10501,294,294,294
BEGIN DESCRIPTION:
UNT 173 in LFCCL Watershed 17.0
END DESCRIPTION:
XS GIS Cut Line= 3
      2822925.01      7020475.00      2823425.00      7020725.00
      2823875.05      7020524.98
#Sta/Elev= 30
  4485.6  428.09  4541.8  425.65  4575.0  423.17  4650.5  414.60  4656.1  415.13
  4678.5  412.22  4695.2  408.87  4705.0  408.09  4723.2  406.48  4807.0  406.39
  4879.7  404.53  4946.8  406.73  4977.5  406.33  4995.5  403.30  4996.3  402.50
  5003.5  402.50  5004.3  403.30  5008.3  403.38  5022.2  406.96  5099.3  406.61
  5111.0  405.35  5178.7  408.09  5184.8  408.48  5273.7  412.56  5353.1  419.75
  5377.7  422.14  5400.9  425.59  5438.7  427.46  5499.4  431.27  5537.1  432.36
#Mann=7,-1,0
  4485.6    0.16       0  4541.8    0.12       0  4995.5    0.07       0
  5004.3    0.12       0  5184.8    0.16       0  5353.1    0.12       0
  5438.7    0.16       0
Bank Sta=4705,5178.7
Exp/Cntr=0.3,0.1

Type RM Length L Ch R = 1,10207,633,633,633
BEGIN DESCRIPTION:
double XS4031A
END DESCRIPTION:
XS GIS Cut Line= 3
      2822412.97      7021406.55      2823450.30      7020920.44
      2823775.82      7020686.07
#Sta/Elev= 30
  3891.0  425.40  4005.0  420.47  4113.6  413.41  4182.1  411.21  4268.7  408.65
  4376.6  407.34  4518.2  405.43  4632.3  407.05  4706.3  405.67  4765.7  406.22
  4774.8  406.10  4780.3  403.80  4803.1  405.89  4820.5  405.04  4826.0  406.29
  4917.3  403.65  4975.5  405.74  4986.9  403.39  4987.7  402.59  4994.9  402.59
  4995.7  403.39  5008.6  403.56  5019.7  406.32  5087.1  405.05  5137.4  405.55
  5165.6  404.35  5213.3  405.58  5281.0  407.34  5395.1  413.63  5437.7  418.92
#Mann=5,-1,0
  3891.0    0.05       0  4182.1    0.12       0  4986.9    0.07       0
  4995.7    0.12       0  5213.3    0.16       0
Bank Sta=4376.6,5281
Exp/Cntr=0.3,0.1

Type RM Length L Ch R = 1,9574,417,417,417
BEGIN DESCRIPTION:
double XS4032A
END DESCRIPTION:
XS GIS Cut Line= 3
      2822890.44      7021810.16      2823784.50      7021037.63
      2823997.17      7020703.44
#Sta/Elev= 30
  3831.9  418.40  3893.4  415.43  4001.8  409.82  4009.4  408.71  4022.9  409.45
  4036.9  407.54  4117.1  405.19  4228.8  403.54  4384.6  404.15  4392.2  403.56
  4550.2  403.21  4551.0  402.41  4558.2  402.41  4559.0  403.21  4661.0  404.89
  4675.3  403.67  4689.5  404.86  4732.3  403.62  4746.5  404.14  4845.3  403.49
  4959.3  405.04  4994.4  403.59  5004.2  403.91  5011.7  404.68  5049.2  405.19
  5101.9  406.89  5274.4  416.02  5293.8  416.69  5320.3  417.99  5409.6  425.86
#Mann=7,-1,0
  3831.9    0.16       0  3893.4    0.12       0  4550.2    0.07       0
  4559.0    0.12       0  5004.2    0.16       0  5274.4    0.12       0
  5293.8    0.16       0
Bank Sta=4117.1,5049.2
Exp/Cntr=0.3,0.1

Type RM Length L Ch R = 1,9157,477,477,477
BEGIN DESCRIPTION:
double UNT 173 in LFCCL Watershed 15.0
END DESCRIPTION:
XS GIS Cut Line= 3
      2823525.01      7022174.99      2824025.00      7021375.00
      2824175.01      7020824.97
#Sta/Elev= 30
  4055.2  420.87  4071.6  420.22  4102.7  418.80  4136.0  417.71  4185.3  413.12
  4220.9  410.03  4296.9  406.24  4348.7  404.12  4412.7  401.29  4570.7  401.65
  4765.7  402.07  4890.7  403.81  4904.2  403.24  4911.9  400.51  4944.0  400.43
  4944.9  399.63  4952.9  400.43  4954.4  402.35  4969.7  400.60  5008.9  400.79
  5021.0  405.09  5052.7  404.12  5060.8  405.34  5135.1  404.53  5246.2  408.85
  5330.3  412.40  5357.9  412.39  5402.8  418.89  5516.8  431.96  5568.7  435.04
#Mann=10,-1,0
  4055.2    0.12       0  4071.6    0.16       0  4102.7    0.12       0
  4185.3    0.16       0  4296.9    0.12       0  4412.7    0.07       0
  4570.7    0.12       0  4944.0    0.07       0  4952.9    0.12       0
  5246.2    0.16       0
Bank Sta=4348.7,5052.7
Exp/Cntr=0.3,0.1

Type RM Length L Ch R = 1,8680,817,817,817
BEGIN DESCRIPTION:
double UNT 173 in LFCCL Watershed 14.0
END DESCRIPTION:
XS GIS Cut Line= 3
      2823618.56      7022562.01      2824068.58      7021861.98
      2824626.50      7021302.40
#Sta/Elev= 30
  4014.9  434.69  4054.6  432.02  4138.4  425.35  4244.7  415.62  4332.3  407.96
  4371.4  404.74  4459.6  402.32  4482.1  400.76  4596.7  401.40  4631.6  404.07
  4740.6  405.87  4969.7  403.73  4998.0  400.21  5012.2  400.84  5019.2  403.86
  5082.9  403.17  5125.3  399.84  5146.5  401.50  5153.6  404.27  5196.0  404.75
  5231.3  404.48  5252.6  400.50  5276.4  399.56  5277.2  398.76  5285.3  399.56
  5324.1  402.32  5542.5  412.55  5592.0  412.81  5632.0  416.73  5637.3  416.83
#Mann=10,-1,0
  4014.9    0.05       0  4054.6    0.16       0  4138.4    0.12       0
  4244.7    0.16       0  4332.3    0.07       0  4482.1    0.16       0
  4596.7    0.12       0  5276.4    0.07       0  5285.3    0.12       0
  5632.0    0.16       0
Bank Sta=4459.6,5324.1
Exp/Cntr=0.3,0.1

Type RM Length L Ch R = 1,7863,539,539,539
BEGIN DESCRIPTION:
double UNT 173 in LFCCL Watershed 13.0
END DESCRIPTION:
XS GIS Cut Line= 3
      2823975.01      7022824.98      2824625.00      7022025.00
      2825425.02      7021474.99
#Sta/Elev= 30
  3955.6  433.33  3998.0  431.56  4024.2  428.10  4055.4  424.20  4061.9  426.09
  4090.6  425.11  4171.0  417.51  4232.8  411.56  4253.7  411.16  4276.0  407.72
  4379.0  401.47  4410.8  400.16  4427.9  399.21  4428.7  398.41  4436.8  399.21
  4836.9  399.21  4958.4  402.70  4993.8  399.58  5008.7  399.72  5029.7  403.86
  5050.6  404.80  5065.5  400.90  5095.3  399.21  5288.6  401.47  5378.2  402.64
  5555.3  405.30  5662.9  409.98  5749.5  420.52  5894.1  433.07  5957.2  437.52
#Mann=8,-1,0
  3955.6    0.16       0  4024.2    0.05       0  4171.0    0.16       0
  4410.8    0.05       0  4427.9   0.035       0  4436.8    0.05       0
  5378.2    0.16       0  5894.1    0.05       0
Bank Sta=4379,5288.6
Exp/Cntr=0.3,0.1

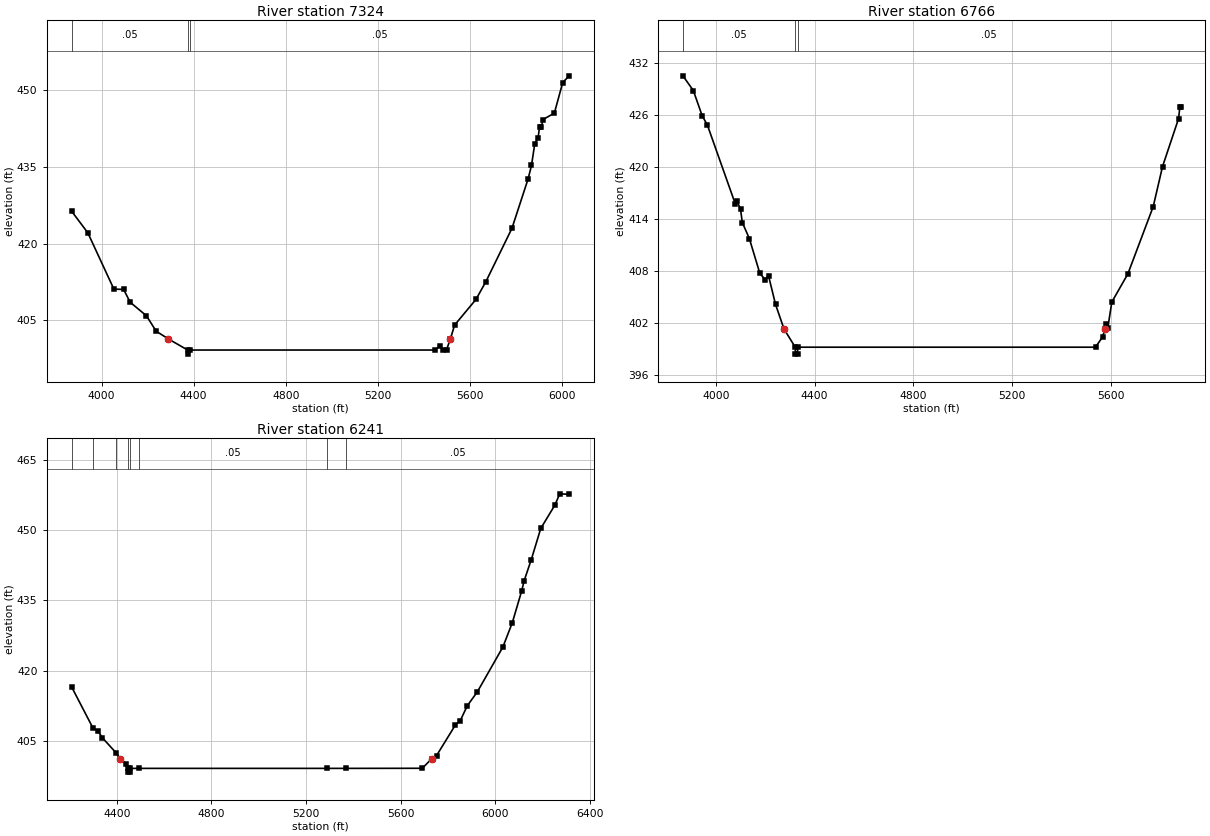
Type RM Length L Ch R = 1,7324,558,558,558
BEGIN DESCRIPTION:
double UNT 173 in LFCCL Watershed 12.0
END DESCRIPTION:
XS GIS Cut Line= 3
      2824275.00      7023125.00      2825075.00      7022325.00
      2825874.97      7021675.03
#Sta/Elev= 30
  3869.4  426.37  3940.1  422.13  4053.2  411.13  4095.7  411.06  4124.0  408.56
  4194.7  405.91  4237.1  402.89  4290.1  401.38  4374.0  399.21  4374.8  398.41
  4383.0  399.21  5449.0  399.21  5469.8  400.03  5484.2  399.21  5498.6  399.27
  5515.5  401.38  5533.7  404.09  5626.4  409.10  5669.5  412.57  5783.0  423.02
  5853.4  432.72  5867.8  435.30  5882.1  439.57  5896.5  440.74  5902.9  442.85
  5910.9  442.80  5917.3  444.26  5967.1  445.53  6003.5  451.51  6031.5  452.82
#Mann=3,-1,0
  3869.4    0.05       0  4374.0   0.035       0  4383.0    0.05       0
Bank Sta=4290.1,5515.5
Exp/Cntr=0.3,0.1

Type RM Length L Ch R = 1,6766,525,525,525
BEGIN DESCRIPTION:
UNT 173 in LFCCL Watershed 11.0
END DESCRIPTION:
XS GIS Cut Line= 3
      2824725.03      7023524.97      2825475.00      7022725.00
      2825924.99      7021925.02
#Sta/Elev= 30
  3867.3  430.52  3909.5  428.82  3945.2  425.92  3966.2  424.85  4079.5  415.73
  4086.6  416.06  4100.5  415.12  4107.8  413.59  4136.2  411.75  4178.6  407.74
  4199.7  407.02  4213.8  407.46  4242.2  404.15  4276.6  401.31  4322.0  399.21
  4323.0  398.41  4331.3  398.41  4332.2  399.21  5537.5  399.21  5565.9  400.39
  5576.0  401.31  5581.8  401.85  5587.6  401.48  5603.5  404.42  5668.5  407.67
  5771.1  415.43  5808.7  420.04  5873.8  425.59  5878.9  426.92  5881.7  426.92
#Mann=3,-1,0
  3867.3    0.05       0  4322.0   0.033       0  4332.2    0.05       0
Bank Sta=4276.6,5576
Exp/Cntr=0.3,0.1

Type RM Length L Ch R = 1,6241,511,511,511
BEGIN DESCRIPTION:
UNT 173 in LFCCL Watershed 10.0
END DESCRIPTION:
XS GIS Cut Line= 3
      2825875.00      7023774.97      2825925.00      7022975.00
      2825975.00      7021674.99
#Sta/Elev= 30
  4209.1  416.60  4300.4  407.72  4319.3  407.25  4339.3  405.73  4398.2  402.47
  4415.6  401.22  4439.5  400.22  4446.9  399.21  4447.8  398.41  4456.2  398.41
  4457.2  399.21  4496.1  399.21  5287.3  399.21  5368.1  399.21  5691.1  399.23
  5730.0  401.22  5751.2  401.93  5831.2  408.48  5851.2  409.36  5881.3  412.56
  5923.8  415.53  6031.4  425.05  6071.4  430.25  6111.4  437.09  6121.4  439.19
  6151.5  443.68  6191.5  450.32  6251.5  455.32  6271.6  457.70  6311.6  457.59
#Mann=8,-1,0
  4209.1    0.05       0  4300.4    0.08       0  4398.2     0.1       0
  4446.9   0.033       0  4457.2     0.1       0  4496.1    0.05       0
  5287.3    0.07       0  5368.1    0.05       0
Bank Sta=4415.6,5730
Exp/Cntr=0.3,0.1