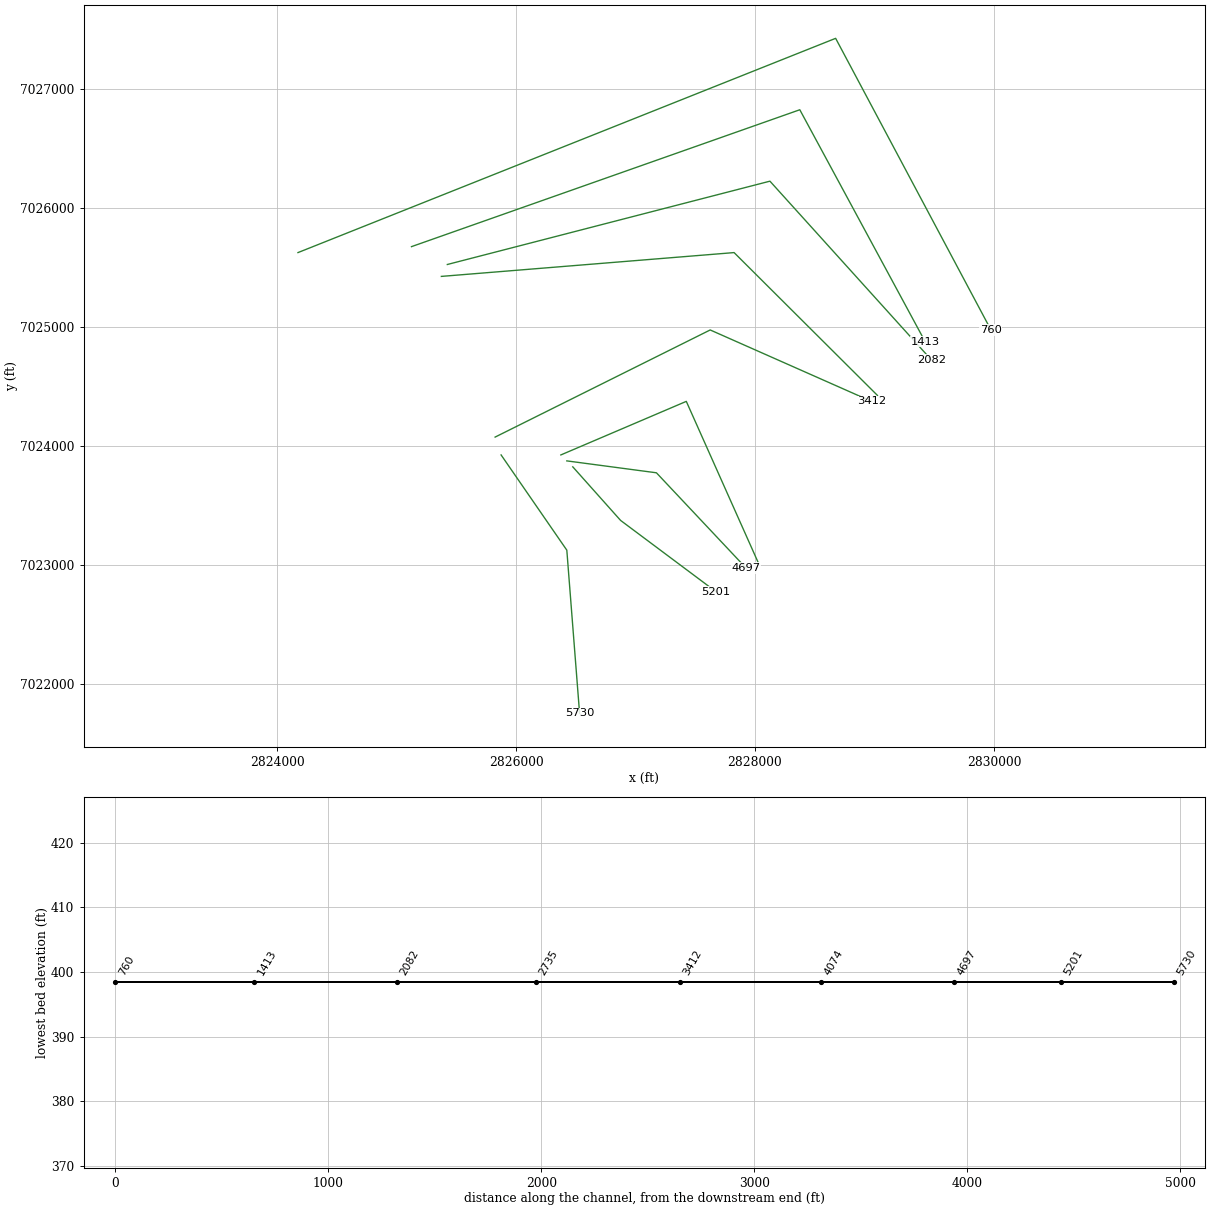
HEC-RAS study UNT 173 in LFCCL Watershed.prj: UNT 173 in LFCCL Watershed Base Level Engineering

--- UNT 173 in LFCCL Watershed.g01 (geometry) --- (continued)

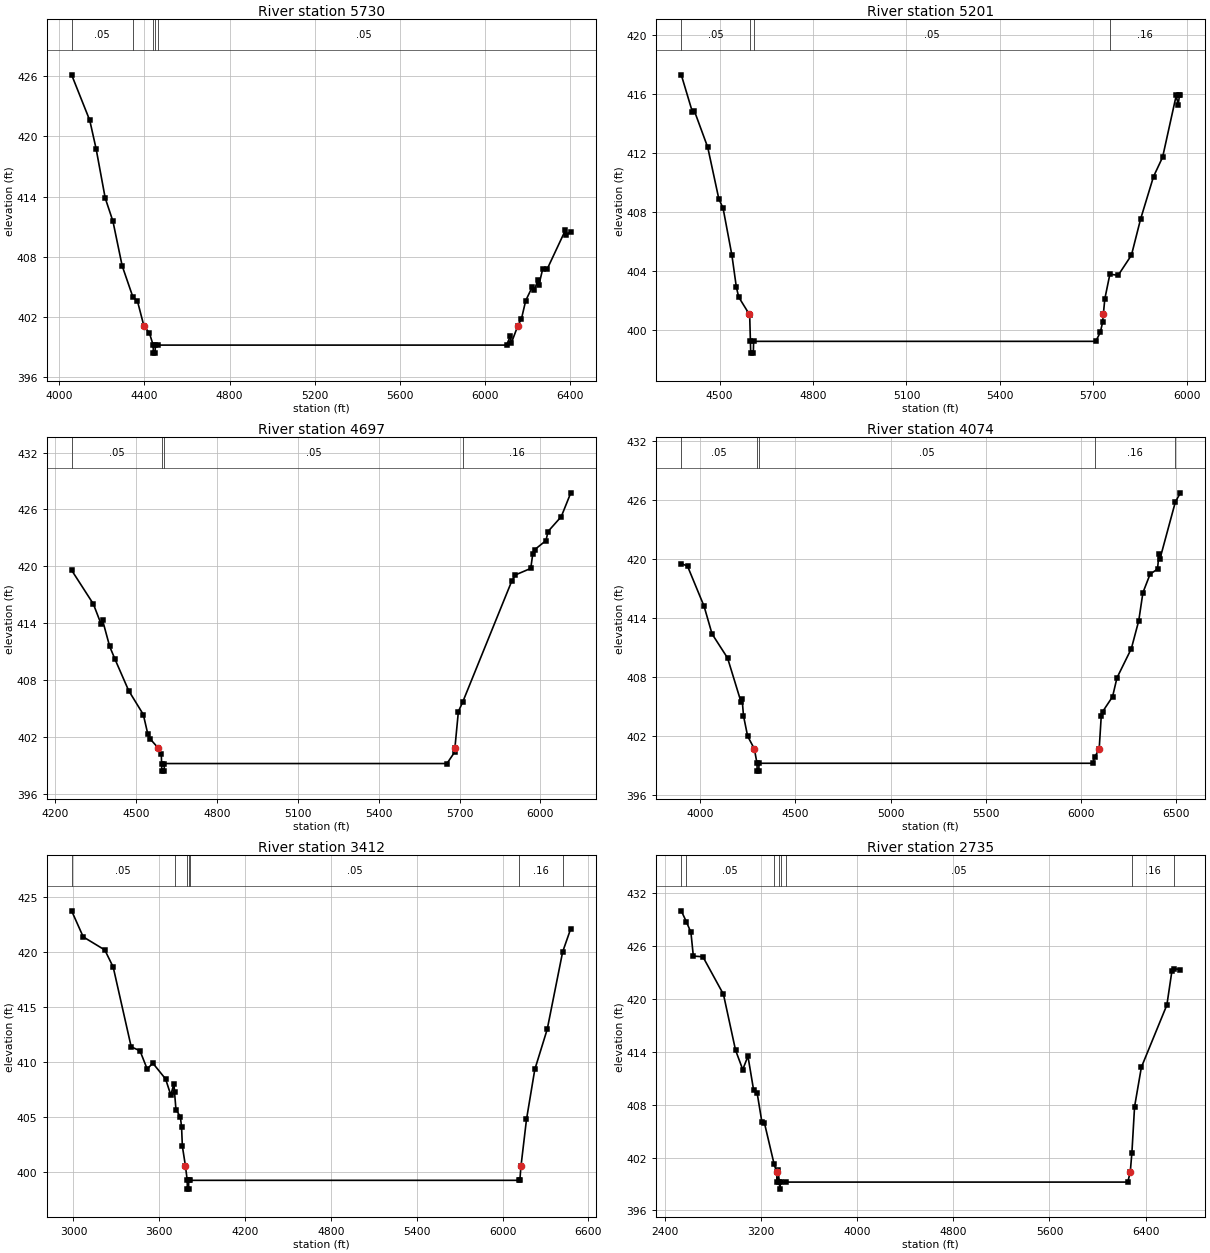
Type RM Length L Ch R = 1,5730,529,529,529
BEGIN DESCRIPTION:
UNT 173 in LFCCL Watershed 9.0
END DESCRIPTION:
XS GIS Cut Line= 3
      2825874.98      7023925.02      2826425.00      7023125.00
      2826531.90      7021753.81
#Sta/Elev= 30
  4057.8  426.13  4143.1  421.59  4172.8  418.77  4215.6  413.86  4252.0  411.54
  4295.3  407.11  4345.9  403.99  4367.0  403.61  4397.1  401.15  4423.8  400.38
  4441.0  399.21  4442.0  398.41  4450.4  398.41  4451.3  399.21  4462.8  399.21
  6101.9  399.21  6119.6  400.08  6124.6  399.42  6155.3  401.15  6172.1  401.83
  6192.2  403.65  6222.3  404.97  6232.3  404.66  6249.1  405.69  6254.2  405.22
  6272.4  406.83  6292.5  406.76  6378.7  410.66  6383.7  410.18  6404.0  410.50
#Mann=5,-1,0
  4057.8    0.05       0  4345.9     0.1       0  4441.0   0.033       0
  4451.3     0.1       0  4462.8    0.05       0
Bank Sta=4397.1,6155.3
Exp/Cntr=0.3,0.1

Type RM Length L Ch R = 1,5201,504,504,504
BEGIN DESCRIPTION:
UNT 173 in LFCCL Watershed 8.0
END DESCRIPTION:
XS GIS Cut Line= 3
      2826475.02      7023824.98      2826875.00      7023375.00
      2827675.04      7022774.97
#Sta/Elev= 30
  4377.3  417.30  4412.8  414.79  4419.5  414.84  4462.2  412.38  4497.7  408.89
  4511.5  408.24  4539.9  405.04  4554.1  402.88  4561.7  402.21  4595.2  401.06
  4596.8  400.99  4599.2  399.21  4600.1  398.41  4608.5  398.41  4609.5  399.21
  5707.5  399.21  5722.1  399.82  5729.4  400.49  5732.0  401.06  5736.6  402.09
  5752.9  403.77  5779.4  403.69  5822.1  405.06  5851.2  407.49  5892.9  410.39
  5922.1  411.71  5965.8  415.90  5972.1  415.26  5976.2  415.90  5979.4  415.90
#Mann=4,-1,0
  4377.3    0.05       0  4599.2   0.033       0  4609.5    0.05       0
  5752.9    0.16       0
Bank Sta=4595.2,5732
Exp/Cntr=0.3,0.1

Type RM Length L Ch R = 1,4697,623,623,623
BEGIN DESCRIPTION:
UNT 173 in LFCCL Watershed 7.0
END DESCRIPTION:
XS GIS Cut Line= 3
      2826424.99      7023875.00      2827175.00      7023775.00
      2827924.98      7022975.02
#Sta/Elev= 30
  4260.0  419.59  4340.7  416.03  4369.7  413.89  4374.8  414.33  4401.2  411.56
  4421.4  410.18  4471.9  406.89  4526.1  404.38  4542.5  402.36  4552.6  401.77
  4580.8  400.87  4592.9  400.24  4594.0  399.21  4594.9  398.41  4603.6  398.41
  4604.4  399.21  5653.3  399.21  5681.7  400.40  5683.0  400.87  5695.8  404.69
  5712.1  405.71  5893.9  418.44  5907.8  419.10  5964.5  419.78  5971.8  421.27
  5978.7  421.75  6021.2  422.72  6028.5  423.67  6077.8  425.24  6113.2  427.75
#Mann=4,-1,0
  4260.0    0.05       0  4594.0   0.033       0  4604.4    0.05       0
  5712.1    0.16       0
Bank Sta=4580.8,5683
Exp/Cntr=0.3,0.1

Type RM Length L Ch R = 1,4074,662,662,662
BEGIN DESCRIPTION:
UNT 173 in LFCCL Watershed 6.0
END DESCRIPTION:
XS GIS Cut Line= 3
      2826374.99      7023925.00      2827425.00      7024375.00
      2828025.00      7023025.01
#Sta/Elev= 30
  3901.3  419.54  3934.0  419.28  4021.0  415.19  4062.7  412.38  4144.3  409.92
  4215.0  405.44  4220.5  405.78  4227.7  404.05  4249.5  401.97  4284.9  400.67
  4298.6  399.21  4299.5  398.41  4308.3  398.41  4309.1  399.21  6060.7  399.21
  6070.6  399.82  6094.5  400.67  6105.2  403.99  6112.7  404.47  6164.7  405.99
  6187.9  407.91  6263.2  410.88  6302.1  413.72  6324.0  416.58  6361.6  418.46
  6400.6  418.98  6408.2  420.52  6413.6  420.03  6494.5  425.83  6521.0  426.74
#Mann=5,-1,0
  3901.3    0.05       0  4298.6   0.033       0  4309.1    0.05       0
  6070.6    0.16       0  6494.5    0.05       0
Bank Sta=4284.9,6094.5
Exp/Cntr=0.3,0.1

Type RM Length L Ch R = 1,3412,677,677,677
BEGIN DESCRIPTION:
UNT 173 in LFCCL Watershed 5.0
END DESCRIPTION:
XS GIS Cut Line= 3
      2825824.99      7024075.00      2827625.00      7024975.00
      2828975.00      7024375.00
#Sta/Elev= 30
  2987.3  423.72  3068.4  421.35  3219.3  420.16  3278.0  418.60  3403.8  411.35
  3465.3  410.99  3515.6  409.33  3554.7  409.87  3644.2  408.43  3680.5  406.97
  3702.9  408.01  3706.8  407.21  3716.8  405.64  3747.6  404.99  3756.0  404.04
  3761.5  402.31  3783.1  400.51  3795.4  399.21  3796.3  398.41  3805.1  398.41
  3805.9  399.21  3816.2  399.21  6113.5  399.21  6120.8  399.21  6128.9  400.51
  6167.3  404.75  6225.4  409.29  6312.3  412.95  6420.2  419.99  6477.1  422.11
#Mann=7,-1,0
  2987.3    0.05       0  3706.8    0.16       0  3795.4   0.033       0
  3805.9    0.16       0  3816.2    0.05       0  6113.5    0.16       0
  6420.2    0.05       0
Bank Sta=3783.1,6128.9
Exp/Cntr=0.3,0.1

Type RM Length L Ch R = 1,2735,653,653,653
BEGIN DESCRIPTION:
UNT 173 in LFCCL Watershed 4.0
END DESCRIPTION:
XS GIS Cut Line= 3
      2825375.02      7025425.00      2827825.00      7025625.00
      2829025.01      7024424.99
#Sta/Elev= 30
  2535.0  430.03  2576.5  428.81  2615.2  427.59  2635.3  424.89  2715.0  424.81
  2886.1  420.54  2986.5  414.21  3046.7  411.99  3089.9  413.52  3137.0  409.67
  3167.1  409.28  3206.6  405.99  3227.3  405.92  3308.3  401.22  3328.3  400.36
  3333.3  399.24  3338.3  400.60  3352.4  399.21  3353.3  398.41  3363.0  399.21
  3407.5  399.21  6251.8  399.21  6272.4  400.36  6286.0  402.55  6308.3  407.78
  6364.9  412.26  6577.1  419.33  6619.5  423.23  6635.9  423.46  6690.2  423.35
#Mann=8,-1,0
  2535.0    0.16       0  2576.5    0.05       0  3308.3     0.1       0
  3352.4   0.033       0  3363.0     0.1       0  3407.5    0.05       0
  6286.0    0.16       0  6635.9    0.05       0
Bank Sta=3328.3,6272.4
Exp/Cntr=0.3,0.1

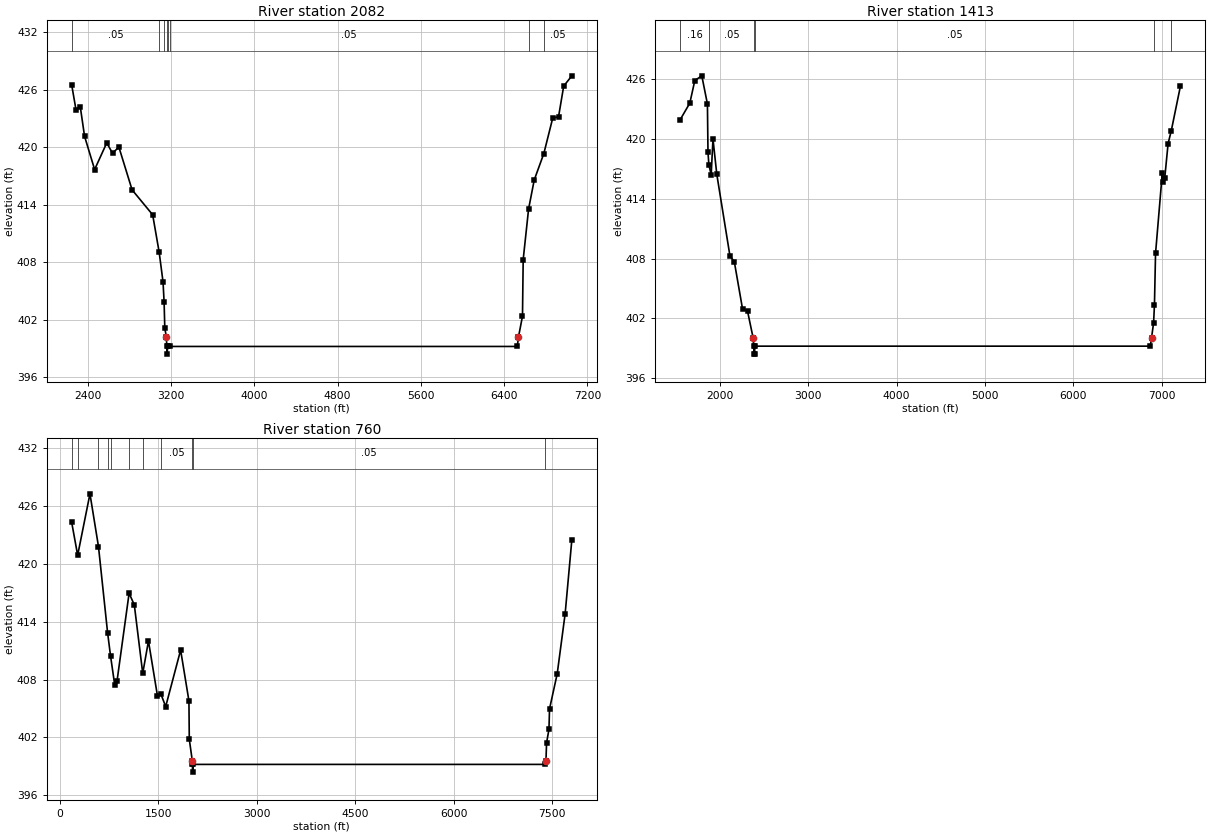
Type RM Length L Ch R = 1,2082,669,669,669
BEGIN DESCRIPTION:
UNT 173 in LFCCL Watershed 3.0
END DESCRIPTION:
XS GIS Cut Line= 3
      2825425.01      7025525.00      2828125.00      7026225.00
      2829475.00      7024725.00
#Sta/Elev= 30
  2243.4  426.50  2284.7  423.90  2326.0  424.21  2367.4  421.12  2464.0  417.66
  2580.6  420.44  2635.9  419.36  2697.2  420.00  2824.1  415.54  3021.9  412.94
  3084.3  409.04  3121.5  405.94  3131.9  403.82  3138.5  401.10  3153.9  400.20
  3157.5  399.21  3158.4  398.41  3168.1  399.21  3186.0  399.21  6526.4  399.21
  6538.0  400.20  6576.5  402.37  6583.2  408.27  6635.2  413.55  6689.3  416.57
  6781.7  419.33  6866.5  423.00  6923.3  423.18  6972.6  426.36  7050.7  427.43
#Mann=8,-1,0
  2243.4    0.05       0  3084.3     0.1       0  3131.9    0.08       0
  3157.5   0.033       0  3168.1    0.08       0  3186.0    0.05       0
  6635.2    0.16       0  6781.7    0.05       0
Bank Sta=3153.9,6538
Exp/Cntr=0.3,0.1

Type RM Length L Ch R = 1,1413,653,653,653
BEGIN DESCRIPTION:
UNT 173 in LFCCL Watershed 2.0
END DESCRIPTION:
XS GIS Cut Line= 3
      2825124.98      7025674.99      2828375.00      7026825.00
      2829425.00      7024875.01
#Sta/Elev= 30
  1551.2  421.96  1659.4  423.61  1715.9  425.88  1795.2  426.35  1858.8  423.52
  1865.1  418.66  1875.2  417.42  1901.3  416.42  1921.6  420.02  1964.9  416.46
  2113.4  408.29  2163.5  407.67  2256.2  402.95  2312.7  402.73  2376.6  400.02
  2383.9  399.21  2384.7  398.41  2393.7  398.41  2394.5  399.21  6872.7  399.21
  6886.3  400.02  6910.0  401.57  6919.5  403.33  6931.9  408.52  7008.2  416.57
  7013.8  415.69  7035.7  416.06  7073.9  419.54  7110.1  420.84  7213.4  425.31
#Mann=6,-1,0
  1551.2    0.16       0  1875.2    0.05       0  2383.9   0.033       0
  2394.5    0.05       0  6919.5    0.16       0  7110.1    0.05       0
Bank Sta=2376.6,6886.3
Exp/Cntr=0.3,0.1

Type RM Length L Ch R = 1,760,0,0,0
BEGIN DESCRIPTION:
UNT 173 in LFCCL Watershed 1.0
END DESCRIPTION:
XS GIS Cut Line= 3
      2824175.04      7025625.02      2828675.00      7027425.00
      2829974.98      7024975.04
#Sta/Elev= 30
   179.7  424.28   271.0  420.87   458.3  427.23   588.1  421.77   727.2  412.83
   771.4  410.47   835.3  407.45   870.3  407.82  1054.7  416.94  1134.2  415.72
  1262.3  408.64  1349.6  411.99  1486.9  406.30  1539.3  406.49  1612.1  405.20
  1839.6  411.05  1966.2  405.79  1971.6  401.82  2018.7  399.52  2020.1  399.21
  2020.9  398.41  2030.8  399.21  7385.4  399.21  7405.6  399.52  7414.9  401.44
  7451.2  402.83  7460.2  404.96  7577.5  408.61  7698.0  414.82  7799.8  422.45
#Mann=11,-1,0
   179.7    0.16       0   271.0    0.05       0   588.1    0.12       0
   727.2    0.16       0   771.4    0.12       0  1054.7    0.16       0
  1262.3    0.12       0  1539.3    0.05       0  2020.1   0.033       0
  2030.8    0.05       0  7385.4    0.16       0
Bank Sta=2018.7,7405.6
Exp/Cntr=0.3,0.1

Chan Stop Cuts=-1