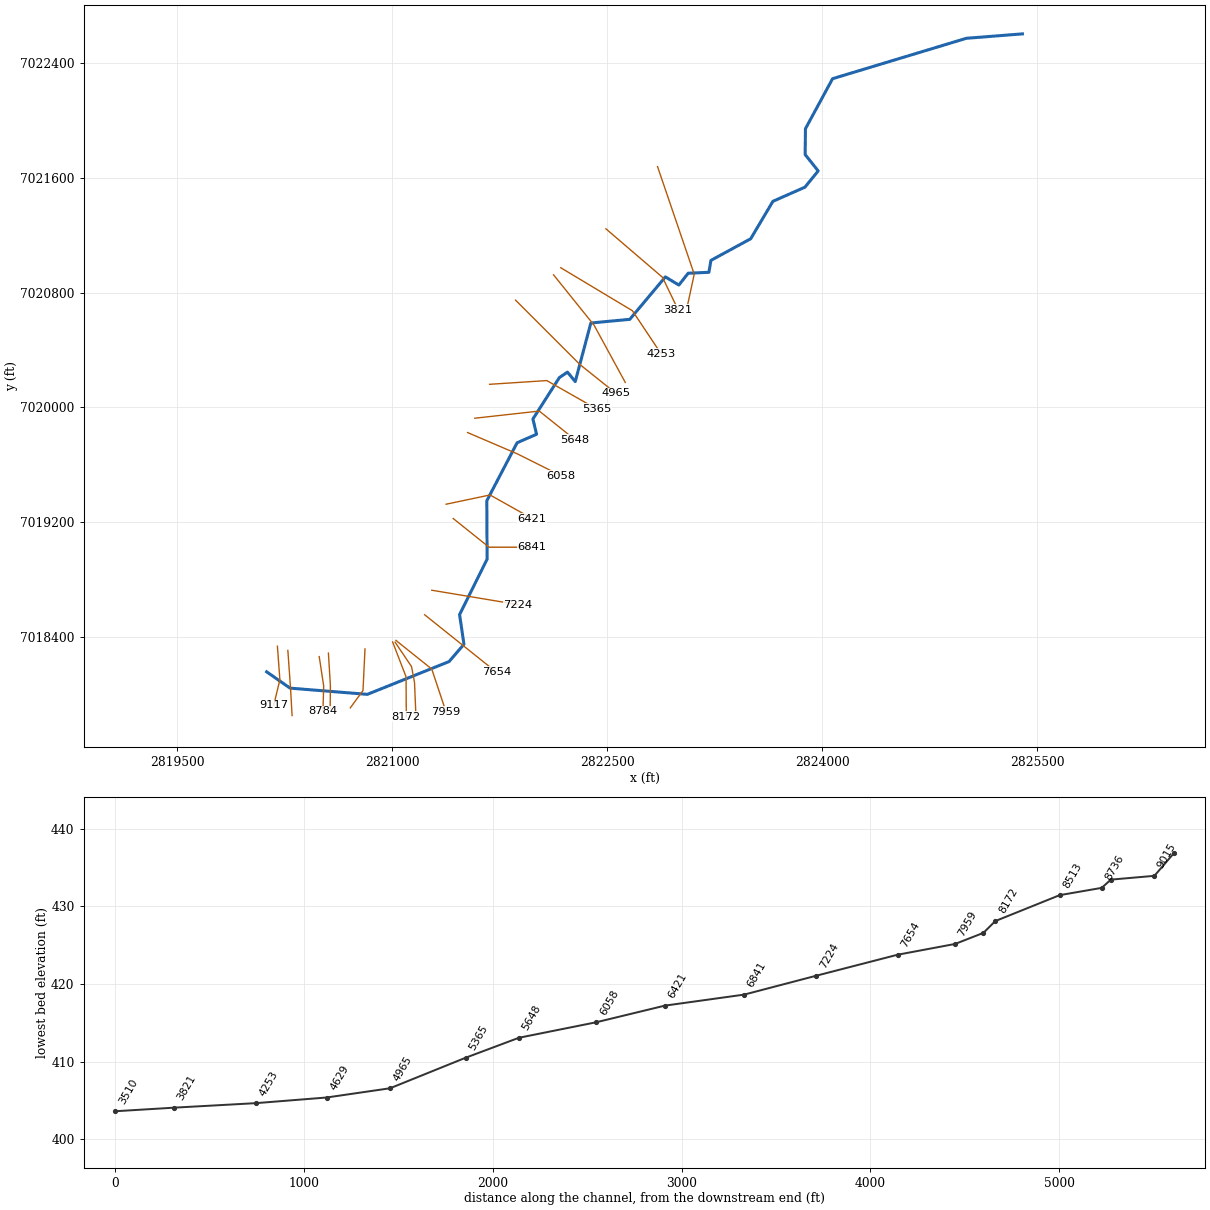
--- UNT 175 in LFCCL Watershed.prj (project) ---

Proj Title=UNT 175 in LFCCL Watershed Base Level Engineering
Current Plan=p01
Default Exp/Contr=0.3,0.1
English Units
Geom File=g01
Flow File=f01
Plan File=p01
BEGIN DESCRIPTION:
UNT 175 in LFCCL Watershed
END DESCRIPTION:

--- UNT 175 in LFCCL Watershed.p01 (plan) ---

Plan Title=Multiple Run
Short Identifier=Multiple
Geom File=g01
Flow File=f01
Subcritical Flow
K Sum by GR= 0
Std Step Tol= 0.01
Critical Tol= 0.01
Num of Std Step Trials= 20
Max Error Tol= 0.3
Flow Tol Ratio= 0.001
Split Flow NTrial= 30
Split Flow Tol= 0.02
Split Flow Ratio= 0.02
Log Output Level= 0
Friction Slope Method= 1
Unsteady Friction Slope Method= 2
Unsteady Bridges Friction Slope Method= 1
Parabolic Critical Depth
Global Vel Dist=  1 , 1 , 1
Global Log Level= 0
CheckData=True
Encroach Param= -1, 0, 0, 0
BEGIN DESCRIPTION:
Multiple Run
END DESCRIPTION:

--- UNT 175 in LFCCL Watershed.f01 (steady flow) ---

Flow Title=Multiple
Number of Profiles=7
Profile Names=10-year,25-year,50-year,1pct_min,100-year,1pct_plu,500-year
River Rch & RM= UNT 175 in LFCCL,Reach-1,9117
     407     534     636     377     752    1500    1052
River Rch & RM= UNT 175 in LFCCL,Reach-1,4629
     606     812     979     587    1172    2338    1680
Boundary for River Rch & Prof#=UNT 175 in LFCCL,Reach-1,1
Up Type=0
Dn Type=3
Dn Slope=0.005
Boundary for River Rch & Prof#=UNT 175 in LFCCL,Reach-1,2
Up Type=0
Dn Type=3
Dn Slope=0.005
Boundary for River Rch & Prof#=UNT 175 in LFCCL,Reach-1,3
Up Type=0
Dn Type=3
Dn Slope=0.005
Boundary for River Rch & Prof#=UNT 175 in LFCCL,Reach-1,4
Up Type=0
Dn Type=3
Dn Slope=0.005
Boundary for River Rch & Prof#=UNT 175 in LFCCL,Reach-1,5
Up Type=0
Dn Type=3
Dn Slope=0.005
Boundary for River Rch & Prof#=UNT 175 in LFCCL,Reach-1,6
Up Type=0
Dn Type=3
Dn Slope=0.005
Boundary for River Rch & Prof#=UNT 175 in LFCCL,Reach-1,7
Up Type=0
Dn Type=3
Dn Slope=0.005

--- UNT 175 in LFCCL Watershed.g01 (geometry) ---

Geom Title=Existing Conditions

River Reach=UNT 175 in LFCCL,Reach-1
Reach XY= 30
      2820123.04      7018155.94      2820286.19      7018041.91
      2820825.59      7017998.52      2821395.73      7018227.27
      2821499.60      7018347.83      2821469.04      7018555.01
      2821661.08      7018941.51      2821659.07      7019349.20
      2821870.31      7019753.76      2822006.34      7019813.29
      2821980.61      7019919.48      2822165.47      7020208.88
      2822221.75      7020246.61      2822276.11      7020180.74
      2822384.84      7020589.43      2822656.66      7020615.01
      2822904.82      7020911.14      2822998.84      7020854.21
      2823064.07      7020936.72      2823208.62      7020943.11
      2823222.69      7021026.26      2823500.26      7021177.20
      2823655.04      7021438.15      2823878.89      7021537.28
      2823970.99      7021650.49      2823880.17      7021764.33
      2823882.09      7021944.69      2824071.41      7022293.90
      2825004.82      7022575.78      2825396.01      7022606.57

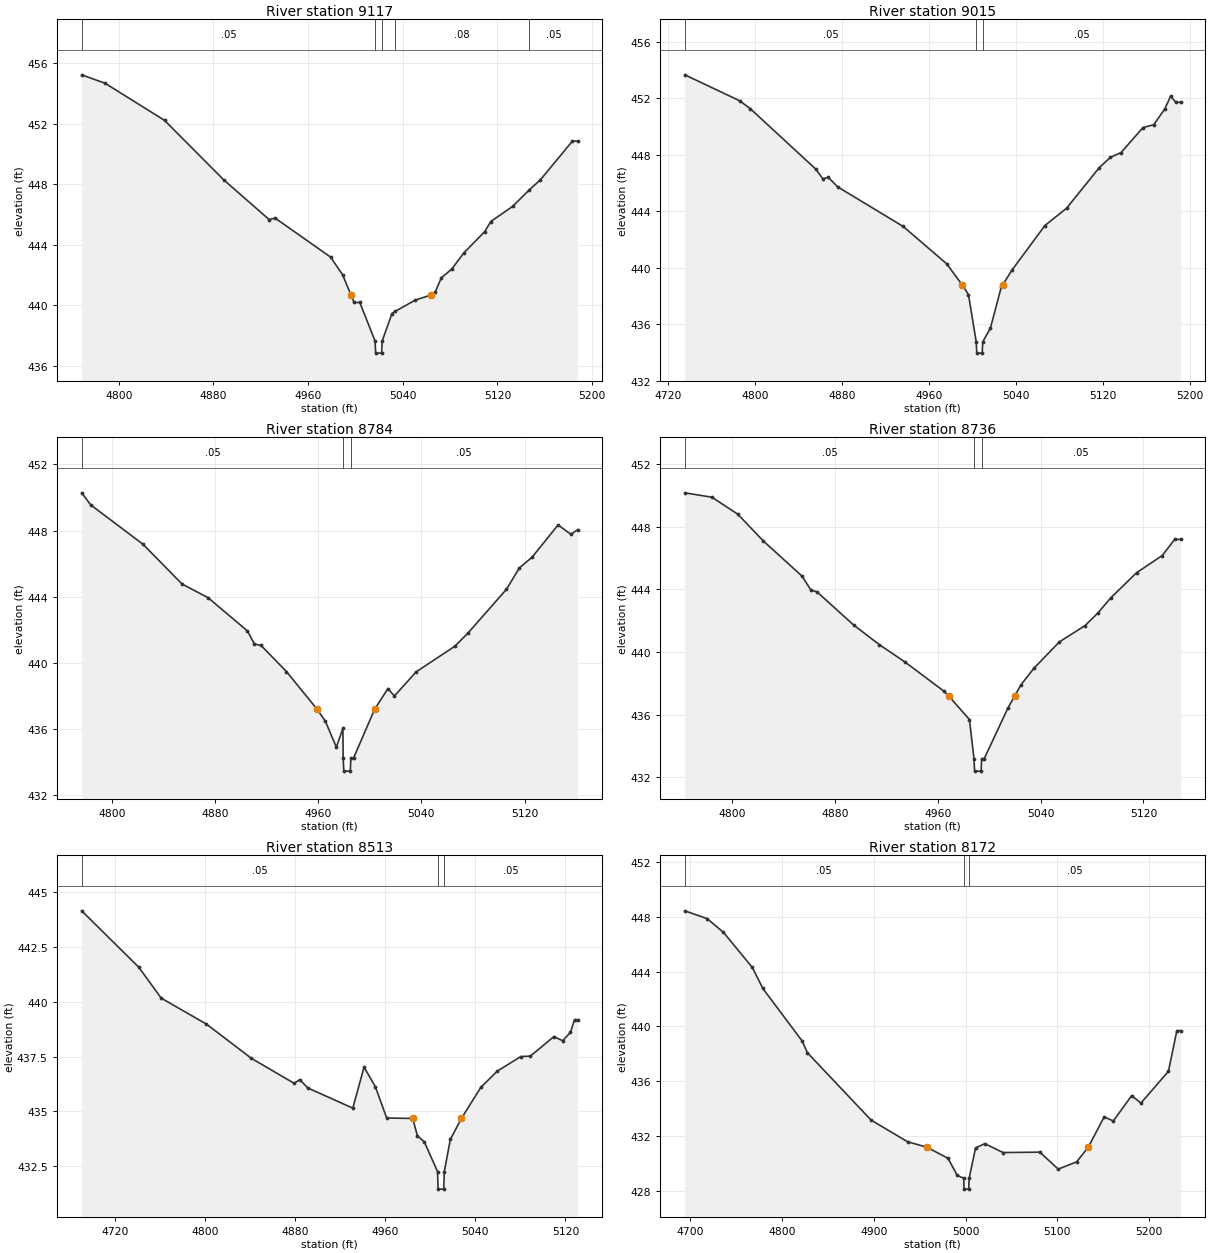
Type RM Length L Ch R = 1,9117,102,102,102
BEGIN DESCRIPTION:
UNT 175 in LFCCL Watershed 14.0
END DESCRIPTION:
XS GIS Cut Line= 3
      2820198.06      7018334.77      2820215.42      7018100.38
      2820172.03      7017921.60
#Sta/Elev= 30
  4768.7  455.24  4788.5  454.68  4838.7  452.23  4888.8  448.29  4927.1  445.67
  4932.1  445.77  4979.0  443.19  4989.1  442.03  4996.3  440.68  4998.9  440.19
  5003.7  440.19  5016.6  437.64  5017.1  436.84  5022.1  436.84  5022.6  437.64
  5030.9  439.46  5033.6  439.60  5050.4  440.34  5063.7  440.68  5067.5  440.89
  5072.6  441.82  5081.3  442.39  5091.6  443.46  5109.3  444.88  5114.4  445.54
  5132.8  446.54  5146.9  447.63  5156.2  448.29  5183.4  450.86  5187.7  450.86
#Mann=5,-1,0
  4768.7    0.05       0  5016.6    0.04       0  5022.6    0.05       0
  5033.6    0.08       0  5146.9    0.05       0
Bank Sta=4996.3,5063.7
Exp/Cntr=0.3,0.1

Type RM Length L Ch R = 1,9015,231,231,231
BEGIN DESCRIPTION:
XS4033A
END DESCRIPTION:
XS GIS Cut Line= 3
      2820270.98      7018305.20      2820290.08      7018034.41
      2820300.49      7017850.37
#Sta/Elev= 30
  4735.5  453.65  4785.8  451.82  4795.9  451.24  4856.0  446.97  4862.4  446.29
  4867.4  446.40  4876.0  445.72  4936.2  442.92  4976.3  440.27  4990.5  438.78
  4996.3  438.09  5003.4  434.75  5003.9  433.95  5008.9  433.95  5009.4  434.75
  5016.4  435.71  5026.4  438.62  5027.7  438.78  5036.4  439.84  5066.5  442.98
  5086.5  444.21  5116.5  447.08  5126.6  447.80  5136.6  448.15  5156.6  449.91
  5166.6  450.12  5176.6  451.22  5182.1  452.13  5186.9  451.71  5191.3  451.71
#Mann=3,-1,0
  4735.5    0.05       0  5003.4    0.03       0  5009.4    0.05       0
Bank Sta=4990.5,5027.7
Exp/Cntr=0.3,0.1

Type RM Length L Ch R = 1,8784,48,48,48
BEGIN DESCRIPTION:
XS4034A
END DESCRIPTION:
XS GIS Cut Line= 3
      2820489.72      7018261.88      2820520.98      7018056.98
      2820515.77      7017879.93
#Sta/Elev= 30
  4776.7  450.28  4783.7  449.55  4824.1  447.18  4854.5  444.77  4874.7  443.94
  4905.1  441.94  4910.6  441.14  4915.7  441.06  4935.4  439.48  4959.2  437.20
  4965.7  436.46  4974.1  434.91  4979.2  436.04  4979.4  434.26  4979.9  433.46
  4984.9  433.46  4985.4  434.26  4987.5  434.26  5003.8  437.20  5014.1  438.45
  5019.1  438.00  5036.0  439.46  5066.0  441.01  5076.0  441.79  5106.0  444.45
  5116.0  445.74  5126.0  446.40  5146.0  448.34  5156.0  447.77  5161.1  448.05
#Mann=3,-1,0
  4776.7    0.05       0  4979.4    0.03       0  4985.4    0.05       0
Bank Sta=4959.2,5003.8
Exp/Cntr=0.3,0.1

Type RM Length L Ch R = 1,8736,223,223,223
BEGIN DESCRIPTION:
XS4035A
END DESCRIPTION:
XS GIS Cut Line= 3
      2820553.97      7018286.10      2820567.85      7018056.98
      2820566.12      7017900.73
#Sta/Elev= 30
  4763.1  450.16  4784.2  449.88  4804.3  448.80  4824.3  447.08  4854.4  444.84
  4861.1  443.97  4866.1  443.83  4894.4  441.73  4914.5  440.47  4934.5  439.36
  4964.6  437.51  4968.6  437.18  4984.6  435.69  4988.1  433.20  4988.6  432.40
  4993.6  432.40  4994.1  433.20  4996.1  433.20  5014.6  436.44  5019.7  437.18
  5024.6  437.90  5034.6  438.95  5054.6  440.65  5074.6  441.69  5084.6  442.50
  5094.6  443.46  5114.6  445.06  5134.6  446.16  5144.3  447.19  5148.9  447.19
#Mann=3,-1,0
  4763.1    0.05       0  4988.1    0.03       0  4994.1    0.05       0
Bank Sta=4968.6,5019.7
Exp/Cntr=0.3,0.1

Type RM Length L Ch R = 1,8513,341,341,341
BEGIN DESCRIPTION:
XS4036A
END DESCRIPTION:
XS GIS Cut Line= 3
      2820809.17      7018315.66      2820795.28      7018025.73
      2820706.76      7017904.22
#Sta/Elev= 30
  4690.2  444.14  4740.9  441.57  4760.9  440.16  4801.0  438.98  4841.0  437.42
  4879.0  436.28  4884.0  436.45  4891.1  436.07  4931.1  435.15  4941.1  437.02
  4951.2  436.12  4961.2  434.70  4984.3  434.68  4988.5  433.89  4994.7  433.61
  5006.4  432.26  5006.9  431.46  5011.9  431.46  5012.4  432.26  5017.8  433.73
  5027.6  434.68  5044.9  436.10  5059.6  436.84  5080.4  437.50  5088.9  437.52
  5109.8  438.41  5117.5  438.22  5124.5  438.60  5128.1  439.18  5130.8  439.18
#Mann=3,-1,0
  4690.2    0.05       0  5006.4    0.03       0  5012.4    0.05       0
Bank Sta=4984.3,5027.6
Exp/Cntr=0.3,0.1

Type RM Length L Ch R = 1,8172,63,63,63
BEGIN DESCRIPTION:
XS4037A
END DESCRIPTION:
XS GIS Cut Line= 3
      2821001.88      7018364.28      2821095.63      7018121.22
      2821097.37      7017841.74
#Sta/Elev= 30
  4694.2  448.44  4718.5  447.87  4736.3  446.87  4767.7  444.31  4779.2  442.77
  4822.0  438.94  4827.7  438.08  4897.1  433.16  4936.8  431.58  4957.9  431.18
  4980.9  430.37  4990.9  429.12  4997.9  428.92  4998.4  428.12  5003.4  428.12
  5003.9  428.92  5010.9  431.13  5020.9  431.44  5040.9  430.79  5080.9  430.82
  5100.9  429.58  5120.9  430.11  5133.6  431.18  5150.9  433.39  5160.9  433.10
  5180.9  434.95  5190.9  434.40  5220.9  436.72  5230.1  439.69  5234.2  439.69
#Mann=3,-1,0
  4694.2    0.05       0  4997.9    0.03       0  5003.9    0.05       0
Bank Sta=4957.9,5133.6
Exp/Cntr=0.3,0.1

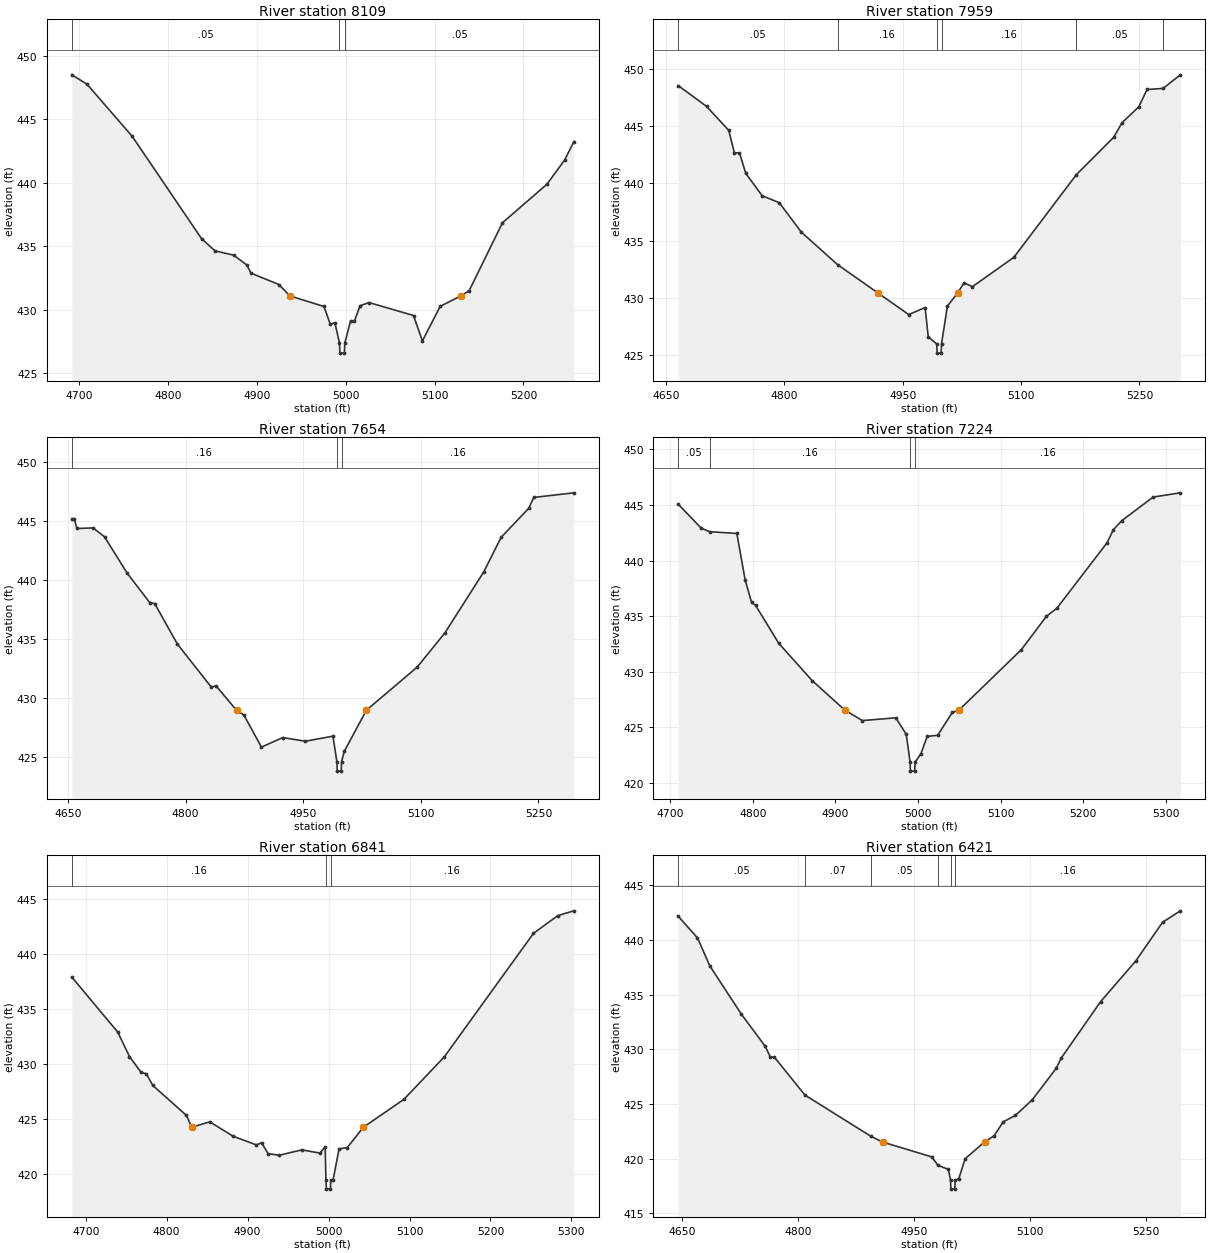
Type RM Length L Ch R = 1,8109,150,150,150
BEGIN DESCRIPTION:
XS4038A
END DESCRIPTION:
XS GIS Cut Line= 4
      2821019.26      7018362.51      2821133.83      7018192.40
      2821154.66      7018081.29      2821165.08      7017834.75
#Sta/Elev= 30
  4691.8  448.50  4709.0  447.76  4759.9  443.65  4837.9  435.60  4852.9  434.65
  4873.9  434.31  4888.9  433.53  4893.5  432.89  4924.8  432.00  4937.3  431.10
  4975.6  430.27  4982.7  428.86  4987.8  429.00  4993.0  427.40  4993.5  426.60
  4998.5  426.60  4999.0  427.40  5005.5  429.14  5009.9  429.14  5016.2  430.33
  5026.2  430.58  5076.3  429.56  5086.3  427.56  5106.3  430.28  5129.4  431.10
  5138.9  431.51  5176.4  436.86  5226.4  439.89  5246.4  441.80  5256.7  443.24
#Mann=3,-1,0
  4691.8    0.05       0  4993.0    0.03       0  4999.0    0.05       0
Bank Sta=4937.3,5129.4
Exp/Cntr=0.3,0.1

Type RM Length L Ch R = 1,7959,305,305,305
BEGIN DESCRIPTION:
UNT 175 in LFCCL Watershed 11.0
END DESCRIPTION:
XS GIS Cut Line= 3
      2821025.02      7018374.98      2821275.00      7018175.00
      2821375.01      7017874.96
#Sta/Elev= 30
  4665.4  448.53  4701.4  446.71  4729.4  444.62  4736.6  442.66  4743.0  442.66
  4751.0  440.87  4771.8  438.91  4793.4  438.31  4821.5  435.73  4867.3  432.90
  4918.4  430.43  4957.5  428.54  4978.3  429.15  4982.3  426.59  4993.1  425.97
  4993.6  425.17  4998.6  425.17  4999.1  425.97  5006.6  429.28  5019.6  430.43
  5027.7  431.31  5038.2  430.97  5090.9  433.54  5170.0  440.75  5217.4  444.02
  5228.0  445.30  5249.1  446.67  5259.6  448.19  5279.9  448.28  5301.8  449.47
#Mann=6,-1,0
  4665.4    0.05       0  4867.3    0.16       0  4993.1    0.07       0
  4999.1    0.16       0  5170.0    0.05       0  5279.9    0.16       0
Bank Sta=4918.4,5019.6
Exp/Cntr=0.3,0.1

Type RM Length L Ch R = 1,7654,430,430,430
BEGIN DESCRIPTION:
UNT 175 in LFCCL Watershed 10.0
END DESCRIPTION:
XS GIS Cut Line= 3
      2821224.98      7018554.18      2821475.00      7018354.17
      2821724.97      7018154.19
#Sta/Elev= 30
  4654.8  445.22  4658.0  445.22  4661.4  444.39  4682.2  444.44  4696.6  443.68
  4725.4  440.60  4754.2  438.10  4760.6  438.01  4789.4  434.58  4832.6  430.93
  4839.0  431.01  4864.9  428.95  4874.3  428.55  4896.7  425.82  4923.9  426.63
  4952.7  426.32  4987.9  426.75  4992.9  424.58  4993.4  423.78  4998.4  423.78
  4998.9  424.58  5002.3  425.46  5030.5  428.95  5095.2  432.61  5130.4  435.50
  5180.0  440.68  5202.4  443.64  5237.6  446.11  5244.0  447.03  5295.1  447.42
#Mann=3,-1,0
  4654.8    0.16       0  4992.9    0.07       0  4998.9    0.16       0
Bank Sta=4864.9,5030.5
Exp/Cntr=0.3,0.1

Type RM Length L Ch R = 1,7224,383,383,383
BEGIN DESCRIPTION:
UNT 175 in LFCCL Watershed 9.0
END DESCRIPTION:
XS GIS Cut Line= 3
      2821274.96      7018725.01      2821575.00      7018675.00
      2821874.98      7018625.00
#Sta/Elev= 30
  4709.5  445.06  4737.4  442.90  4747.6  442.59  4780.5  442.43  4790.6  438.25
  4798.3  436.25  4803.3  435.96  4831.2  432.57  4871.8  429.21  4911.2  426.57
  4932.6  425.62  4973.1  425.87  4985.8  424.38  4990.4  421.88  4990.9  421.08
  4995.9  421.08  4996.4  421.88  5003.5  422.64  5011.1  424.20  5023.8  424.30
  5041.6  426.35  5049.7  426.57  5125.2  431.99  5155.6  434.99  5168.3  435.72
  5229.1  441.60  5236.7  442.77  5246.9  443.58  5284.9  445.70  5317.8  446.08
#Mann=4,-1,0
  4709.5    0.05       0  4747.6    0.16       0  4990.4    0.07       0
  4996.4    0.16       0
Bank Sta=4911.2,5049.7
Exp/Cntr=0.3,0.1

Type RM Length L Ch R = 1,6841,420,420,420
BEGIN DESCRIPTION:
UNT 175 in LFCCL Watershed 8.0
END DESCRIPTION:
XS GIS Cut Line= 3
      2821424.98      7019225.02      2821675.00      7019025.00
      2821975.02      7019025.00
#Sta/Elev= 30
  4682.8  437.93  4739.7  432.91  4754.1  430.70  4768.5  429.25  4774.9  429.13
  4782.9  428.07  4824.5  425.34  4831.0  424.27  4853.3  424.76  4882.1  423.45
  4910.9  422.66  4917.3  422.86  4925.3  421.87  4939.0  421.72  4967.0  422.21
  4989.4  421.92  4995.8  422.49  4996.8  419.44  4997.3  418.64  5002.3  418.64
  5002.8  419.44  5005.5  419.44  5013.0  422.31  5023.0  422.41  5042.9  424.26
  5093.0  426.80  5143.0  430.67  5253.0  441.89  5283.0  443.51  5303.0  443.95
#Mann=3,-1,0
  4682.8    0.16       0  4996.8    0.07       0  5002.8    0.16       0
Bank Sta=4831,5042.9
Exp/Cntr=0.3,0.1

Type RM Length L Ch R = 1,6421,363,363,363
BEGIN DESCRIPTION:
UNT 175 in LFCCL Watershed 7.0
END DESCRIPTION:
XS GIS Cut Line= 3
      2821374.99      7019325.00      2821681.46      7019389.65
      2821975.02      7019224.99
#Sta/Elev= 30
  4644.8  442.17  4669.7  440.20  4685.7  437.63  4726.6  433.21  4757.2  430.30
  4764.1  429.29  4769.2  429.29  4808.8  425.82  4894.2  422.05  4909.2  421.53
  4972.8  420.17  4981.0  419.40  4994.5  419.02  4997.2  418.02  4997.7  417.22
  5002.7  417.22  5003.2  418.02  5007.9  418.18  5016.1  420.00  5041.2  421.53
  5053.8  422.11  5065.3  423.37  5081.2  423.96  5102.9  425.38  5134.1  428.28
  5140.5  429.21  5191.4  434.36  5237.2  438.11  5271.6  441.62  5294.6  442.67
#Mann=6,-1,0
  4644.8    0.05       0  4808.8    0.07       0  4894.2    0.05       0
  4981.0    0.16       0  4997.2    0.07       0  5003.2    0.16       0
Bank Sta=4909.2,5041.2
Exp/Cntr=0.3,0.1

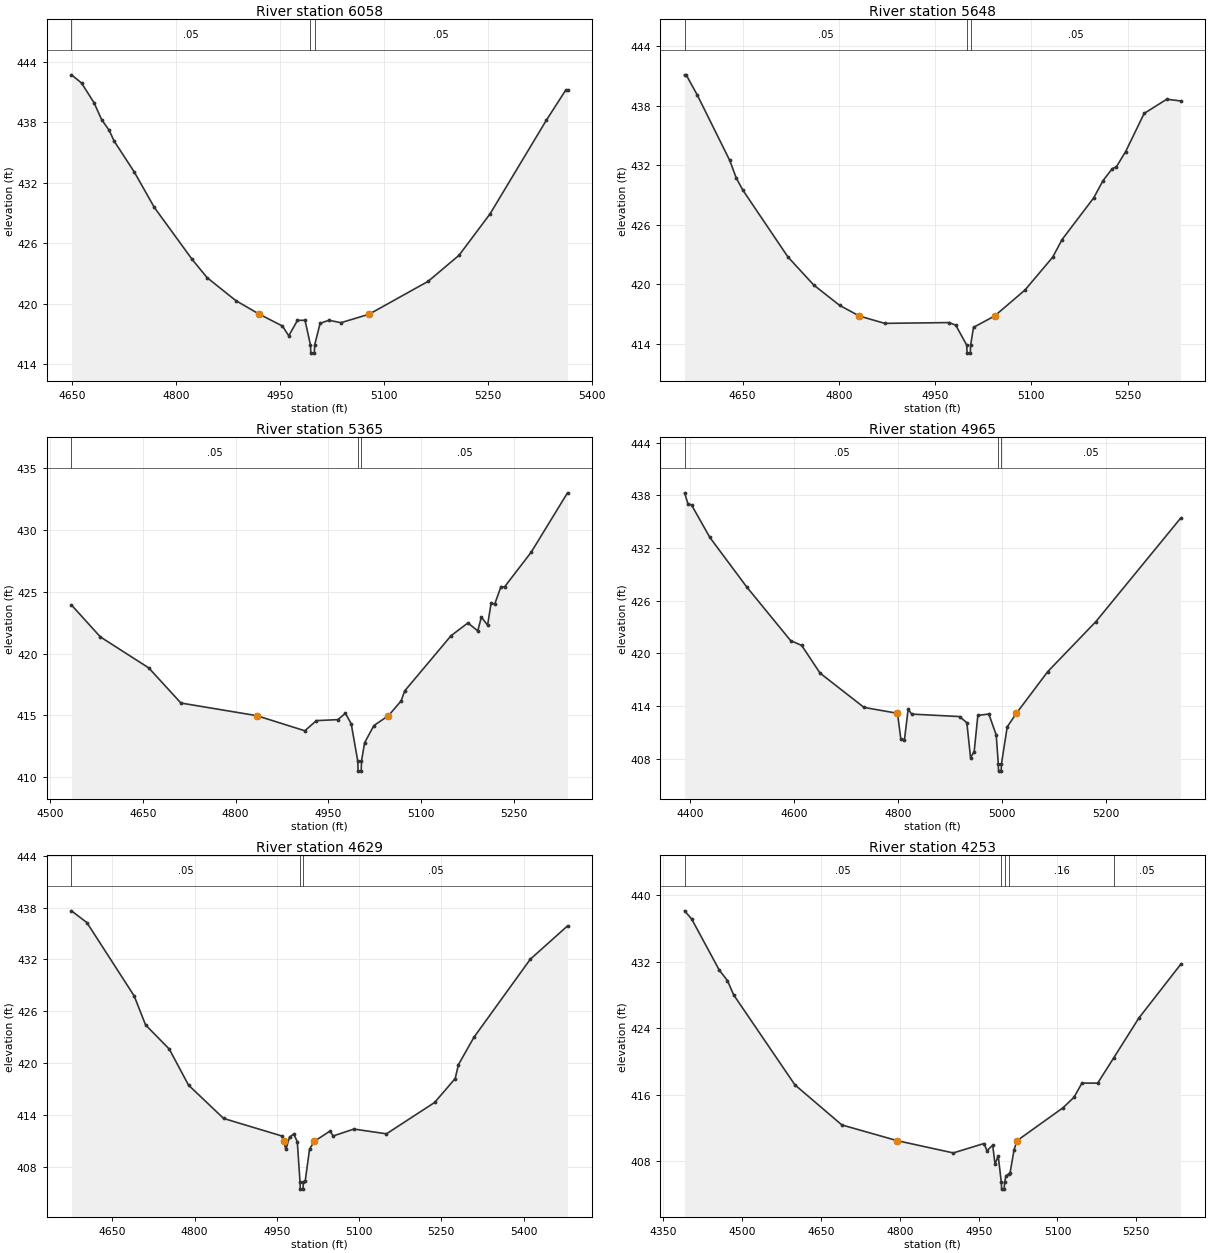
Type RM Length L Ch R = 1,6058,410,410,410
BEGIN DESCRIPTION:
UNT 175 in LFCCL Watershed 6.0
END DESCRIPTION:
XS GIS Cut Line= 3
      2821525.04      7019824.98      2821875.00      7019675.00
      2822175.04      7019524.98
#Sta/Elev= 30
  4648.7  442.69  4663.2  441.88  4681.3  439.92  4692.2  438.25  4703.1  437.19
  4710.3  436.12  4739.3  433.06  4768.3  429.54  4822.7  424.40  4844.5  422.57
  4886.2  420.28  4920.0  418.94  4953.3  417.77  4962.4  416.80  4975.0  418.33
  4985.9  418.34  4993.8  415.88  4994.3  415.08  4999.3  415.08  4999.8  415.88
  5007.7  418.04  5020.4  418.34  5037.8  418.10  5078.4  418.94  5163.6  422.20
  5208.3  424.79  5253.1  428.90  5334.1  438.16  5362.1  441.15  5364.9  441.15
#Mann=3,-1,0
  4648.7    0.05       0  4993.8    0.03       0  4999.8    0.05       0
Bank Sta=4920,5078.4
Exp/Cntr=0.3,0.1

Type RM Length L Ch R = 1,5648,283,283,283
BEGIN DESCRIPTION:
UNT 175 in LFCCL Watershed 5.0
END DESCRIPTION:
XS GIS Cut Line= 3
      2821575.02      7019925.00      2822025.00      7019975.00
      2822275.00      7019775.00
#Sta/Elev= 30
  4559.7  441.13  4562.2  441.13  4579.8  439.06  4630.1  432.50  4640.2  430.74
  4650.2  429.54  4720.7  422.78  4760.9  419.95  4801.2  417.90  4832.0  416.82
  4871.6  416.08  4972.2  416.16  4982.3  415.89  4999.4  413.88  4999.9  413.08
  5004.9  413.08  5005.4  413.88  5009.9  415.68  5042.7  416.82  5090.1  419.44
  5133.3  422.75  5147.7  424.51  5197.3  428.74  5211.7  430.47  5226.1  431.67
  5232.6  431.87  5247.0  433.40  5275.8  437.24  5311.0  438.67  5332.6  438.50
#Mann=3,-1,0
  4559.7    0.05       0  4999.4    0.03       0  5005.4    0.05       0
Bank Sta=4832,5042.7
Exp/Cntr=0.3,0.1

Type RM Length L Ch R = 1,5365,400,400,400
BEGIN DESCRIPTION:
XS4039A
END DESCRIPTION:
XS GIS Cut Line= 3
      2821678.30      7020161.67      2822077.58      7020187.71
      2822427.47      7019989.00
#Sta/Elev= 30
  4534.5  423.92  4581.3  421.34  4659.5  418.84  4711.6  416.00  4834.3  414.98
  4912.0  413.76  4930.8  414.58  4965.4  414.66  4977.7  415.17  4987.1  414.32
  4997.7  411.30  4998.2  410.50  5003.2  410.50  5003.7  411.30  5008.7  412.79
  5023.7  414.18  5047.3  414.98  5067.8  416.17  5073.6  416.98  5148.6  421.44
  5175.9  422.47  5191.8  421.83  5197.6  422.94  5207.7  422.29  5213.4  424.08
  5219.2  423.99  5229.3  425.40  5235.1  425.38  5278.3  428.19  5337.0  432.98
#Mann=3,-1,0
  4534.5    0.05       0  4997.7    0.03       0  5003.7    0.05       0
Bank Sta=4834.3,5047.3
Exp/Cntr=0.3,0.1

Type RM Length L Ch R = 1,4965,336,336,336
BEGIN DESCRIPTION:
UNT 175 in LFCCL Watershed 4.0
END DESCRIPTION:
XS GIS Cut Line= 3
      2821859.73      7020748.78      2822309.72      7020298.78
      2822558.98      7020099.38
#Sta/Elev= 30
  4388.8  438.29  4395.2  437.06  4402.3  436.90  4437.6  433.20  4508.3  427.58
  4593.2  421.44  4614.4  420.90  4649.8  417.74  4734.6  413.83  4799.0  413.16
  4805.3  410.28  4812.4  410.14  4819.5  413.62  4826.5  413.07  4918.5  412.79
  4932.6  412.09  4939.7  408.12  4946.7  408.79  4953.8  412.92  4975.0  413.08
  4989.2  410.68  4993.2  407.37  4993.7  406.57  4998.7  406.57  4999.2  407.37
  5010.4  411.62  5028.0  413.16  5088.4  417.91  5181.3  423.62  5344.4  435.40
#Mann=3,-1,0
  4388.8    0.05       0  4993.2    0.03       0  4999.2    0.05       0
Bank Sta=4799,5028
Exp/Cntr=0.3,0.1

Type RM Length L Ch R = 1,4629,376,376,376
BEGIN DESCRIPTION:
UNT 175 in LFCCL Watershed 3.0
END DESCRIPTION:
XS GIS Cut Line= 3
      2822124.97      7020925.03      2822407.44      7020573.99
      2822624.99      7020175.02
#Sta/Elev= 30
  4575.3  437.63  4603.4  436.27  4689.7  427.77  4710.5  424.41  4753.7  421.61
  4788.9  417.43  4852.9  413.57  4960.1  411.52  4962.5  410.93  4966.5  409.98
  4973.2  411.42  4980.9  411.76  4987.3  410.88  4992.3  406.18  4992.8  405.38
  4997.8  405.38  4998.3  406.18  5001.7  406.31  5009.7  410.03  5018.6  410.93
  5047.0  412.11  5052.7  411.54  5090.6  412.34  5150.0  411.79  5237.8  415.42
  5275.3  418.19  5281.4  419.82  5309.5  422.97  5412.5  432.03  5480.3  435.88
#Mann=3,-1,0
  4575.3    0.05       0  4992.3    0.03       0  4998.3    0.05       0
Bank Sta=4962.5,5018.6
Exp/Cntr=0.3,0.1

Type RM Length L Ch R = 1,4253,432,432,432
BEGIN DESCRIPTION:
UNT 175 in LFCCL Watershed 2.0
END DESCRIPTION:
XS GIS Cut Line= 3
      2822175.01      7020975.00      2822675.00      7020675.00
      2822874.98      7020375.04
#Sta/Elev= 30
  4390.6  438.09  4404.2  437.10  4456.7  430.96  4472.2  429.71  4483.9  428.00
  4600.5  417.18  4689.9  412.36  4795.3  410.47  4901.8  409.00  4960.1  410.13
  4965.9  409.27  4976.7  409.93  4981.2  407.65  4987.2  408.65  4993.2  405.45
  4993.7  404.65  4998.7  404.65  4999.2  405.45  5002.2  406.27  5007.5  406.48
  5009.7  406.57  5017.3  409.36  5023.0  410.47  5110.4  414.42  5131.4  415.69
  5146.5  417.39  5176.5  417.39  5207.3  420.46  5254.6  425.19  5334.2  431.65
#Mann=5,-1,0
  4390.6    0.05       0  4993.2    0.03       0  4999.2    0.05       0
  5007.5    0.16       0  5207.3    0.05       0
Bank Sta=4795.3,5023
Exp/Cntr=0.3,0.1

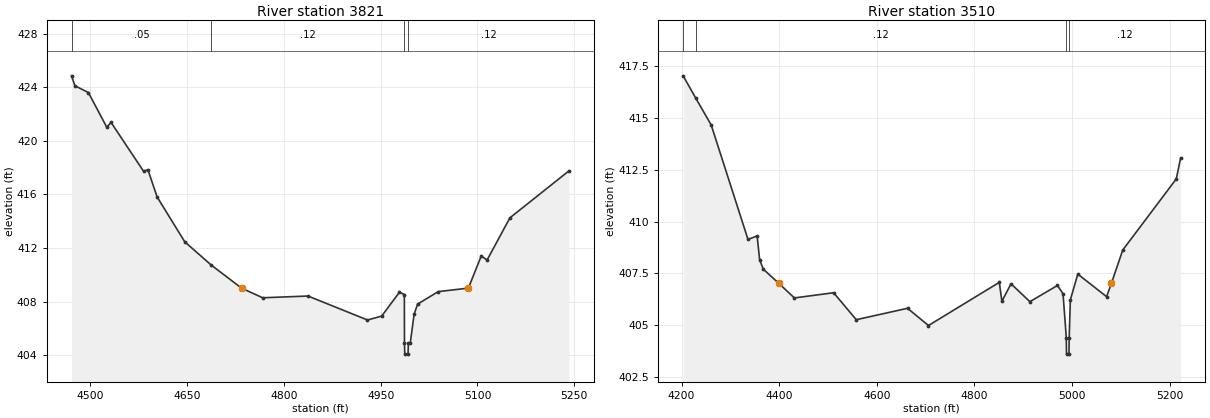
Type RM Length L Ch R = 1,3821,311,311,311
BEGIN DESCRIPTION:
XS4040A
END DESCRIPTION:
XS GIS Cut Line= 3
      2822489.91      7021246.73      2822884.87      7020908.20
      2822993.37      7020682.52
#Sta/Elev= 30
  4471.1  424.86  4476.3  424.12  4497.2  423.61  4525.7  421.02  4532.3  421.38
  4582.8  417.72  4589.4  417.85  4603.7  415.81  4646.5  412.46  4687.6  410.72
  4734.5  409.00  4767.2  408.28  4837.4  408.41  4929.6  406.62  4951.6  406.91
  4979.0  408.69  4986.7  408.52  4986.9  404.87  4987.4  404.07  4992.4  404.07
  4992.9  404.87  4995.8  404.87  5001.8  407.05  5007.3  407.81  5039.2  408.74
  5085.9  409.00  5105.8  411.40  5114.9  411.10  5150.2  414.25  5241.7  417.76
#Mann=4,-1,0
  4471.1    0.05       0  4687.6    0.12       0  4986.9    0.07       0
  4992.9    0.12       0
Bank Sta=4734.5,5085.9
Exp/Cntr=0.3,0.1

Type RM Length L Ch R = 1,3510,0,0,0
BEGIN DESCRIPTION:
UNT 175 in LFCCL Watershed 1.0
END DESCRIPTION:
XS GIS Cut Line= 3
      2822850.15      7021680.74      2823106.22      7020929.90
      2823058.64      7020709.28
#Sta/Elev= 30
  4203.2  417.03  4229.4  415.94  4260.7  414.66  4336.1  409.14  4354.8  409.31
  4360.0  408.15  4367.7  407.70  4398.9  407.03  4431.1  406.32  4511.5  406.57
  4557.9  405.27  4662.9  405.82  4705.8  404.99  4850.9  407.07  4856.2  406.16
  4874.9  407.00  4913.6  406.14  4970.0  406.92  4981.5  406.52  4988.1  404.41
  4988.6  403.61  4993.6  403.61  4994.1  404.41  4996.5  406.23  5011.7  407.47
  5070.7  406.38  5080.7  407.03  5103.8  408.63  5213.5  412.06  5222.2  413.05
#Mann=4,-1,0
  4203.2    0.16       0  4229.4    0.12       0  4988.1    0.07       0
  4994.1    0.12       0
Bank Sta=4398.9,5080.7
Exp/Cntr=0.3,0.1

Chan Stop Cuts=-1