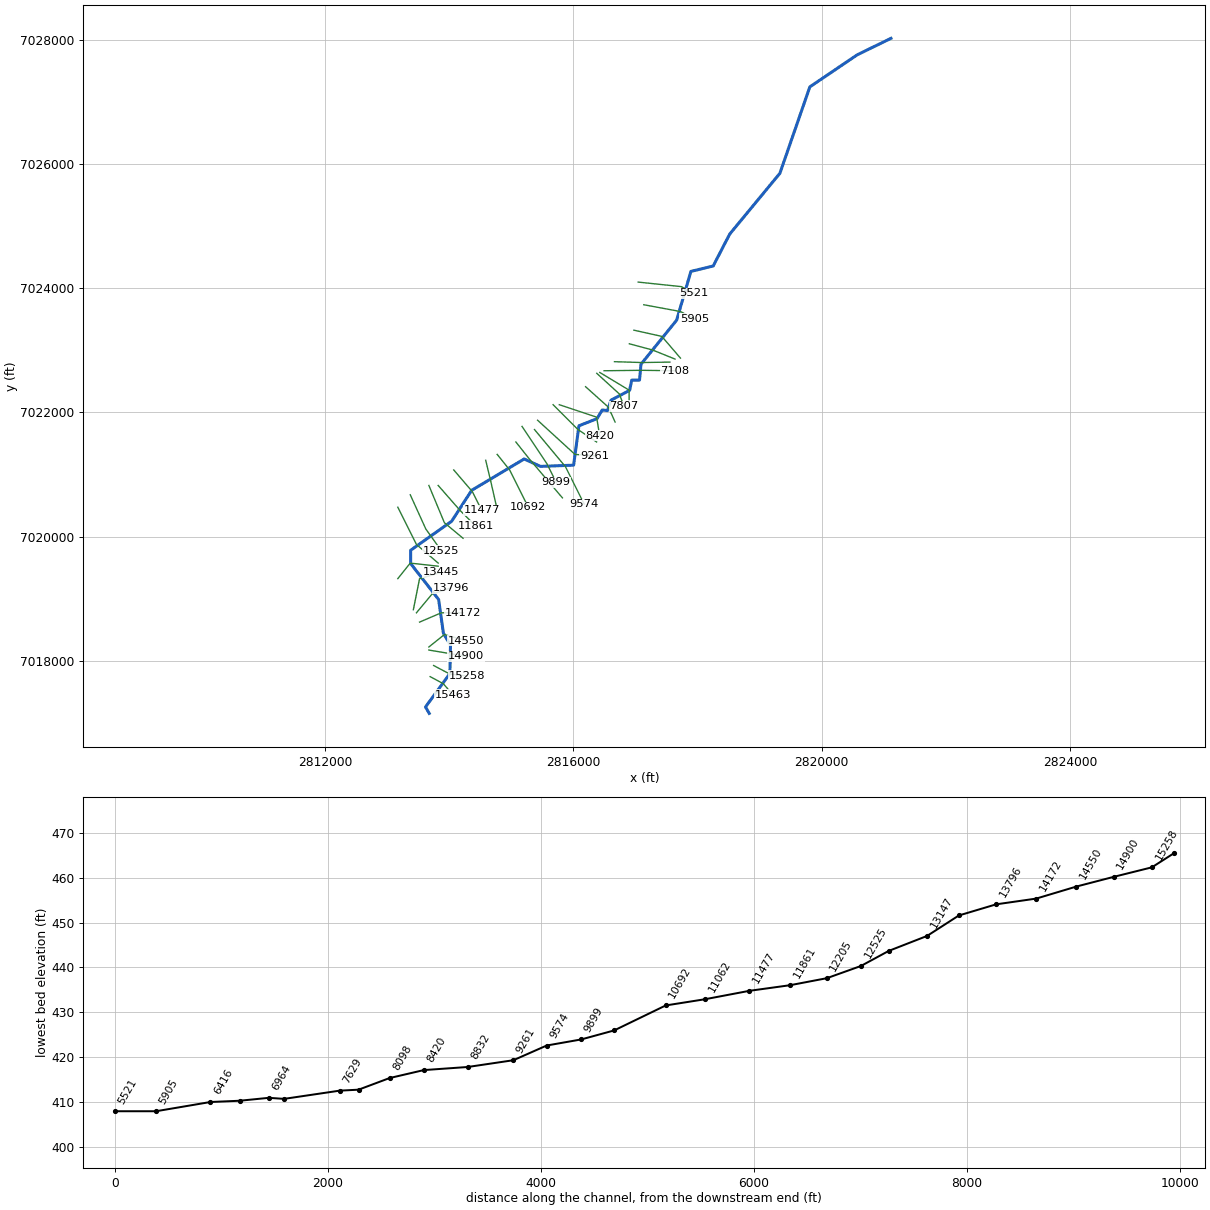
--- UNT 176 in LFCCL Watershed.prj (project) ---

Proj Title=UNT 176 in LFCCL Watershed Base Level Engineering
Current Plan=p01
Default Exp/Contr=0.3,0.1
English Units
Geom File=g01
Flow File=f01
Plan File=p01
BEGIN DESCRIPTION:
UNT 176 in LFCCL Watershed
END DESCRIPTION:

--- UNT 176 in LFCCL Watershed.p01 (plan) ---

Plan Title=Multiple Run
Short Identifier=Multiple
Geom File=g01
Flow File=f01
Subcritical Flow
K Sum by GR= 0
Std Step Tol= 0.01
Critical Tol= 0.01
Num of Std Step Trials= 20
Max Error Tol= 0.3
Flow Tol Ratio= 0.001
Split Flow NTrial= 30
Split Flow Tol= 0.02
Split Flow Ratio= 0.02
Log Output Level= 0
Friction Slope Method= 1
Unsteady Friction Slope Method= 2
Unsteady Bridges Friction Slope Method= 1
Parabolic Critical Depth
Global Vel Dist=  1 , 1 , 1
Global Log Level= 0
CheckData=True
Encroach Param= -1, 0, 0, 0
BEGIN DESCRIPTION:
Multiple Run
END DESCRIPTION:

--- UNT 176 in LFCCL Watershed.f01 (steady flow) ---

Flow Title=Multiple
Program Version=5.07
Number of Profiles= 7
Profile Names=10-year,25-year,50-year,1pct_min,100-year,1pct_plu,500-year
River Rch & RM=UNT 176 in LFCCL,Reach-1         ,15463
     310     400     472     277     553    1104     760
River Rch & RM=UNT 176 in LFCCL,Reach-1         ,12525
     618     832    1008     607    1212    2418    1753
River Rch & RM=UNT 176 in LFCCL,Reach-1         ,7108
     861    1181    1447     880    1757    3505    2595
River Rch & RM=UNT 176 in LFCCL,Reach-1         ,5023
     966    1331    1636     998    1991    3972    2956
River Rch & RM=UNT 176 in LFCCL,Reach-1         ,2167
    1479    2077    2585    1595    3183    6350    4835
Boundary for River Rch & Prof#=UNT 176 in LFCCL,Reach-1         , 1
Up Type= 0
Dn Type= 3
Dn Slope=0.005
Boundary for River Rch & Prof#=UNT 176 in LFCCL,Reach-1         , 2
Up Type= 0
Dn Type= 3
Dn Slope=0.005
Boundary for River Rch & Prof#=UNT 176 in LFCCL,Reach-1         , 3
Up Type= 0
Dn Type= 3
Dn Slope=0.005
Boundary for River Rch & Prof#=UNT 176 in LFCCL,Reach-1         , 4
Up Type= 0
Dn Type= 3
Dn Slope=0.005
Boundary for River Rch & Prof#=UNT 176 in LFCCL,Reach-1         , 5
Up Type= 0
Dn Type= 3
Dn Slope=0.005
Boundary for River Rch & Prof#=UNT 176 in LFCCL,Reach-1         , 6
Up Type= 0
Dn Type= 3
Dn Slope=0.005
Boundary for River Rch & Prof#=UNT 176 in LFCCL,Reach-1         , 7
Up Type= 0
Dn Type= 3
Dn Slope=0.005
DSS Import GetInterval= 0
DSS Import GetPeak= 0
DSS Import FillOption= 0

--- UNT 176 in LFCCL Watershed.g01 (geometry) ---

Geom Title=Existing Conditions

River Reach=UNT 176 in LFCCL,Reach-1
Reach XY= 30
      2813680.59      7017155.71      2813620.63      7017258.57
      2814013.33      7017796.74      2814022.96      7018252.15
      2813908.64      7018446.35      2813831.93      7018989.12
      2813380.92      7019568.21      2813381.69      7019781.91
      2814041.28      7020248.31      2814362.95      7020746.02
      2815209.15      7021251.44      2815470.48      7021132.22
      2816005.05      7021151.34      2816090.66      7021785.89
      2816381.79      7021900.01      2816466.02      7022040.39
      2816549.16      7022029.48      2816607.26      7022197.88
      2816906.55      7022356.01      2816940.61      7022520.98
      2817065.59      7022520.71      2817089.83      7022776.74
      2817663.38      7023485.74      2817893.38      7024271.25
      2818251.94      7024357.84      2818518.40      7024872.38
      2819325.65      7025850.28      2819808.07      7027241.63
      2820570.77      7027757.58      2821114.67      7028023.11

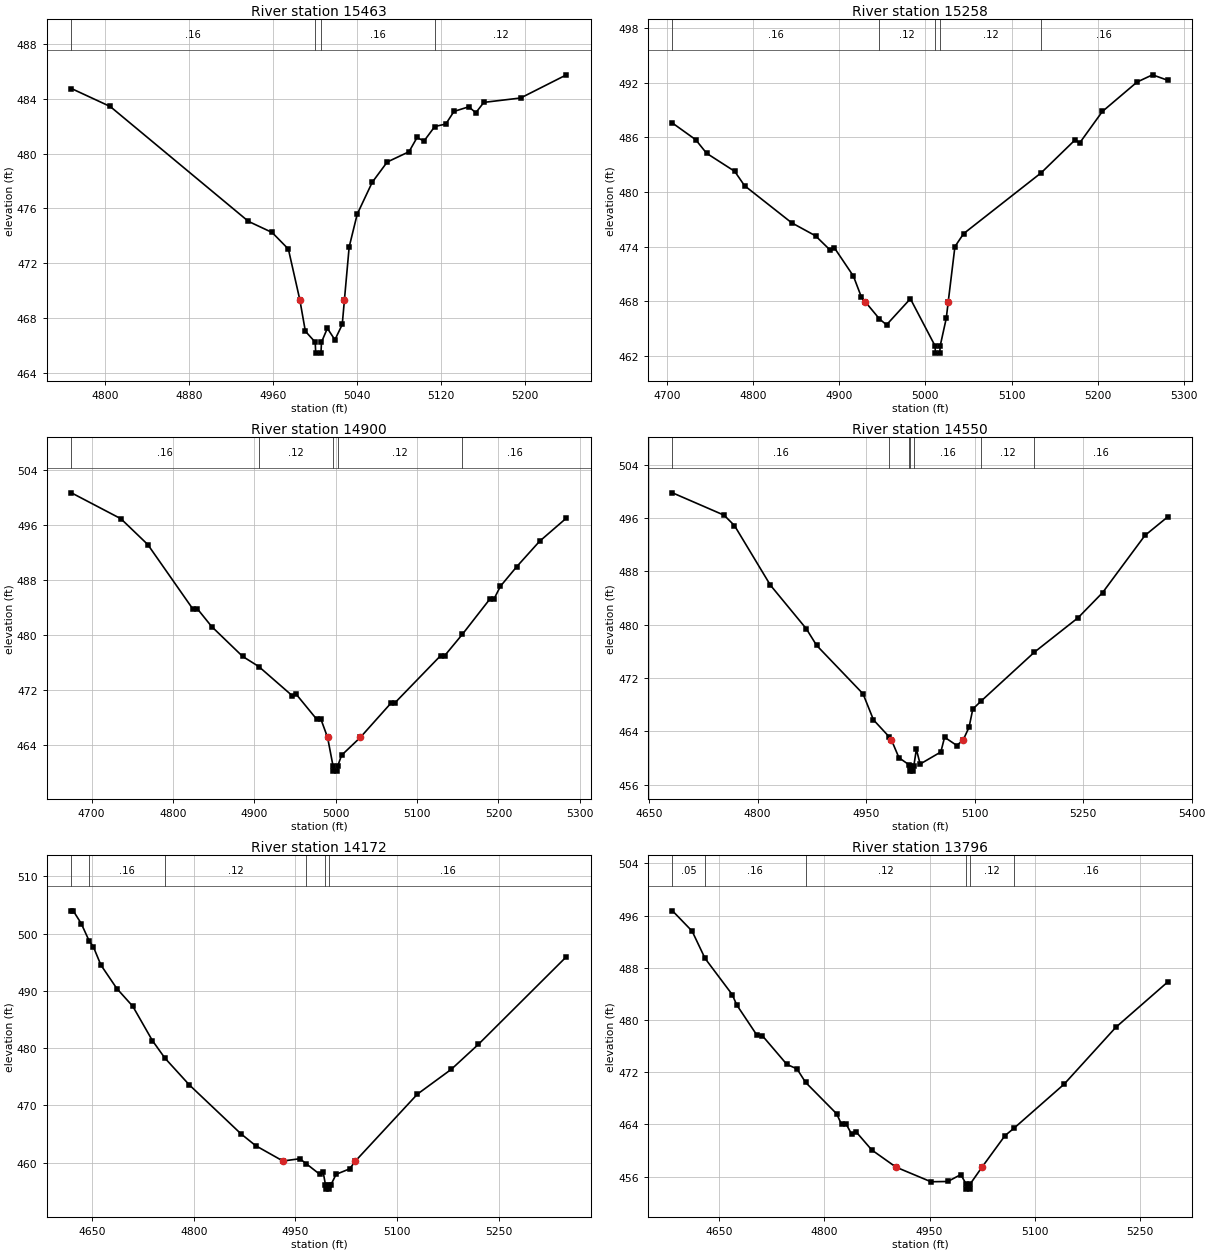
Type RM Length L Ch R = 1,15463,205,205,205
BEGIN DESCRIPTION:
UNT 176 in LFCCL Watershed 35.0
END DESCRIPTION:
XS GIS Cut Line= 3
      2813696.06      7017746.78      2813907.68      7017633.72
      2814058.43      7017456.88
#Sta/Elev= 30
  4767.5  484.75  4804.5  483.44  4936.4  475.06  4959.0  474.25  4974.5  473.04
  4985.4  469.35  4990.7  467.05  5000.1  466.25  5000.6  465.45  5005.6  465.45
  5006.1  466.25  5011.7  467.26  5018.9  466.42  5025.9  467.54  5028.0  469.35
  5032.5  473.19  5040.2  475.59  5054.5  477.91  5068.8  479.39  5089.6  480.14
  5097.3  481.18  5103.9  480.92  5114.2  481.98  5124.7  482.16  5132.5  483.08
  5146.7  483.42  5153.3  482.98  5161.0  483.74  5196.1  484.06  5239.8  485.75
#Mann=4,-1,0
  4767.5    0.16       0  5000.1    0.07       0  5006.1    0.16       0
  5114.2    0.12       0
Bank Sta=4985.4,5028
Exp/Cntr=0.3,0.1

Type RM Length L Ch R = 1,15258,358,358,358
BEGIN DESCRIPTION:
XS4041A
END DESCRIPTION:
XS GIS Cut Line= 3
      2813751.18      7017926.46      2814009.13      7017790.24
      2814290.12      7017758.37
#Sta/Elev= 30
  4706.5  487.56  4733.4  485.74  4746.1  484.25  4778.7  482.27  4790.1  480.70
  4844.8  476.63  4872.5  475.20  4888.9  473.69  4894.5  473.87  4916.5  470.78
  4925.7  468.49  4930.4  467.95  4946.7  466.09  4954.9  465.44  4982.6  468.30
  5011.2  463.14  5011.7  462.34  5016.7  462.34  5017.2  463.14  5024.2  466.14
  5026.5  467.95  5034.3  474.02  5044.4  475.44  5134.3  482.10  5174.0  485.74
  5179.0  485.37  5205.4  488.83  5245.7  492.06  5263.6  492.85  5281.0  492.26
#Mann=5,-1,0
  4706.5    0.16       0  4946.7    0.12       0  5011.2    0.07       0
  5017.2    0.12       0  5134.3    0.16       0
Bank Sta=4930.4,5026.5
Exp/Cntr=0.3,0.1

Type RM Length L Ch R = 1,14900,350,350,350
BEGIN DESCRIPTION:
UNT 176 in LFCCL Watershed 34.0
END DESCRIPTION:
XS GIS Cut Line= 3
      2813675.02      7018175.00      2813975.00      7018125.00
      2814275.05      7018074.99
#Sta/Elev= 30
  4675.3  500.71  4736.1  496.94  4769.1  493.19  4824.8  483.76  4829.9  483.86
  4847.6  481.26  4885.6  476.92  4905.5  475.44  4946.5  471.21  4951.5  471.41
  4976.9  467.74  4982.0  467.74  4990.1  465.12  4996.7  461.02  4997.2  460.22
  5002.2  460.22  5002.7  461.02  5007.3  462.53  5030.3  465.12  5068.1  470.13
  5073.2  470.20  5128.9  477.01  5134.0  477.02  5155.7  480.12  5189.8  485.30
  5194.8  485.31  5202.5  487.12  5222.7  489.99  5250.6  493.66  5283.6  497.04
#Mann=5,-1,0
  4675.3    0.16       0  4905.5    0.12       0  4996.7    0.07       0
  5002.7    0.12       0  5155.7    0.16       0
Bank Sta=4990.1,5030.3
Exp/Cntr=0.3,0.1

Type RM Length L Ch R = 1,14550,378,378,378
BEGIN DESCRIPTION:
UNT 176 in LFCCL Watershed 33.0
END DESCRIPTION:
XS GIS Cut Line= 3
      2813674.97      7018224.97      2813925.00      7018425.00
      2814275.00      7018325.00
#Sta/Elev= 30
  4682.4  499.76  4753.7  496.41  4768.1  494.85  4817.7  485.93  4867.3  479.40
  4881.7  476.89  4945.8  469.64  4960.2  465.74  4981.9  463.20  4985.0  462.74
  4995.4  460.07  5008.8  459.05  5010.0  458.86  5010.5  458.06  5015.5  458.06
  5016.0  458.86  5019.5  461.33  5024.7  459.12  5053.3  460.93  5058.5  463.14
  5075.4  461.90  5084.2  462.74  5092.3  464.63  5097.5  467.36  5109.0  468.56
  5182.7  475.89  5243.1  481.05  5276.9  484.81  5335.4  493.37  5366.6  496.13
#Mann=7,-1,0
  4682.4    0.16       0  4981.9    0.12       0  5008.8    0.16       0
  5010.0    0.07       0  5016.0    0.16       0  5109.0    0.12       0
  5182.7    0.16       0
Bank Sta=4985,5084.2
Exp/Cntr=0.3,0.1

Type RM Length L Ch R = 1,14172,376,376,376
BEGIN DESCRIPTION:
UNT 176 in LFCCL Watershed 32.0
END DESCRIPTION:
XS GIS Cut Line= 3
      2813525.03      7018625.01      2813875.00      7018775.00
      2814225.04      7018775.00
#Sta/Elev= 30
  4619.4  503.97  4622.1  503.97  4633.9  501.75  4645.5  498.74  4652.0  497.63
  4662.9  494.51  4686.5  490.39  4710.0  487.30  4739.0  481.30  4757.5  478.24
  4793.4  473.58  4869.6  465.04  4891.4  462.96  4931.7  460.28  4956.6  460.68
  4966.3  459.79  4985.7  457.99  4991.1  458.32  4994.4  456.17  4994.9  455.37
  4999.9  455.37  5000.4  456.17  5002.7  456.17  5010.2  457.96  5030.2  458.91
  5038.7  460.28  5130.2  471.96  5180.2  476.29  5220.2  480.65  5350.2  495.96
#Mann=6,-1,0
  4619.4    0.05       0  4645.5    0.16       0  4757.5    0.12       0
  4966.3    0.16       0  4994.4    0.07       0  5000.4    0.16       0
Bank Sta=4931.7,5038.7
Exp/Cntr=0.3,0.1

Type RM Length L Ch R = 1,13796,351,351,351
BEGIN DESCRIPTION:
UNT 176 in LFCCL Watershed 31.0
END DESCRIPTION:
XS GIS Cut Line= 3
      2813475.01      7018775.01      2813725.00      7019075.00
      2814024.98      7019174.99
#Sta/Elev= 30
  4583.0  496.73  4611.0  493.62  4629.5  489.44  4668.2  483.91  4674.8  482.30
  4703.4  477.70  4711.2  477.61  4746.3  473.20  4760.7  472.52  4773.0  470.45
  4817.3  465.64  4824.4  464.00  4831.0  464.05  4838.8  462.50  4845.3  462.85
  4867.4  460.10  4902.1  457.46  4952.0  455.22  4976.1  455.26  4994.6  456.32
  5002.1  454.89  5002.6  454.09  5007.6  454.09  5008.1  454.89  5024.9  457.46
  5057.8  462.30  5070.1  463.38  5142.1  470.17  5215.9  478.88  5289.7  485.80
#Mann=6,-1,0
  4583.0    0.05       0  4629.5    0.16       0  4773.0    0.12       0
  5002.1    0.07       0  5008.1    0.12       0  5070.1    0.16       0
Bank Sta=4902.1,5024.9
Exp/Cntr=0.3,0.1

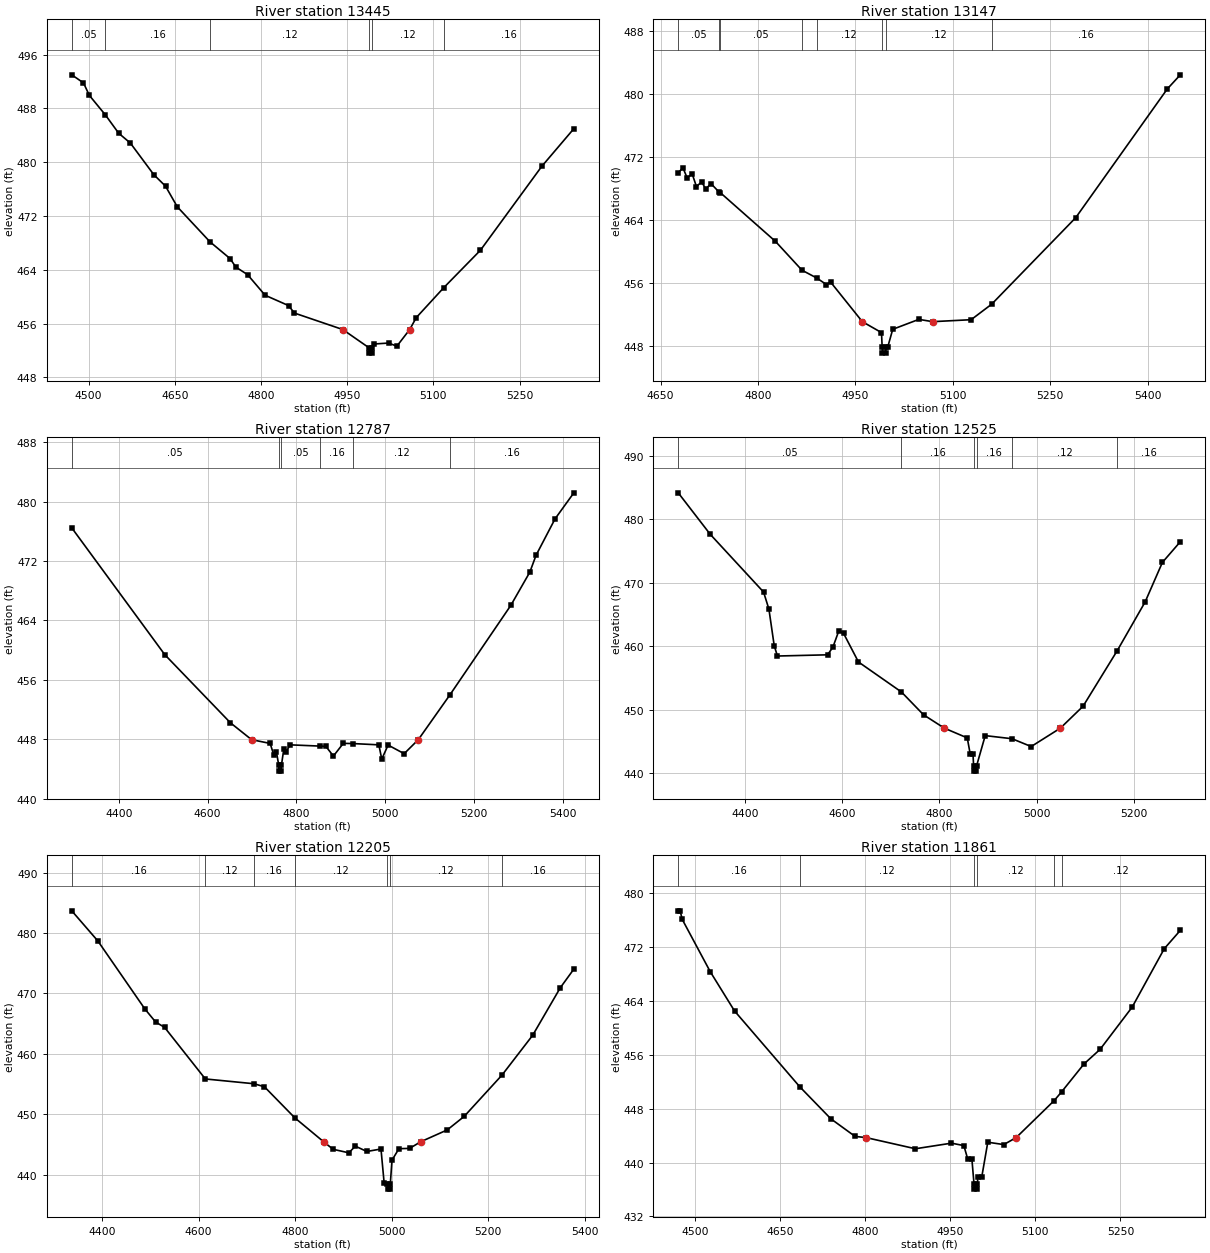
Type RM Length L Ch R = 1,13445,298,298,298
BEGIN DESCRIPTION:
UNT 176 in LFCCL Watershed 30.0
END DESCRIPTION:
XS GIS Cut Line= 3
      2813425.00      7018824.99      2813525.00      7019325.00
      2813874.98      7019424.99
#Sta/Elev= 30
  4470.6  492.99  4491.0  491.79  4501.2  489.93  4529.0  487.04  4552.2  484.31
  4572.6  482.84  4613.4  478.14  4633.8  476.43  4654.2  473.37  4711.2  468.15
  4746.0  465.67  4756.2  464.40  4776.6  463.27  4807.1  460.21  4847.9  458.67
  4858.1  457.56  4942.3  455.11  4987.9  452.40  4988.4  451.60  4993.4  451.60
  4993.9  452.40  4997.4  452.96  5022.1  453.10  5036.4  452.63  5058.8  455.11
  5070.2  456.88  5117.8  461.31  5182.0  466.91  5288.6  479.37  5344.5  484.98
#Mann=6,-1,0
  4470.6    0.05       0  4529.0    0.16       0  4711.2    0.12       0
  4987.9    0.07       0  4993.9    0.12       0  5117.8    0.16       0
Bank Sta=4942.3,5058.8
Exp/Cntr=0.3,0.1

Type RM Length L Ch R = 1,13147,360,360,360
BEGIN DESCRIPTION:
UNT 176 in LFCCL Watershed 29.0
END DESCRIPTION:
XS GIS Cut Line= 3
      2813175.03      7019325.04      2813375.00      7019575.00
      2813825.02      7019525.00
#Sta/Elev= 30
  4677.2  469.96  4684.4  470.61  4690.8  469.34  4698.8  469.80  4705.2  468.22
  4713.2  468.81  4719.6  467.91  4727.6  468.59  4740.0  467.52  4741.7  467.46
  4826.8  461.25  4867.7  457.58  4890.2  456.60  4905.3  455.76  4911.7  456.08
  4960.6  451.04  4990.1  449.65  4991.1  447.84  4991.6  447.04  4996.6  447.04
  4997.1  447.84  4999.8  447.84  5007.4  450.07  5047.6  451.33  5068.9  451.04
  5128.1  451.29  5159.7  453.26  5289.1  464.26  5430.0  480.62  5450.1  482.42
#Mann=8,-1,0
  4677.2    0.05       0  4740.0    0.16       0  4741.7    0.05       0
  4867.7    0.16       0  4890.2    0.12       0  4991.1    0.07       0
  4997.1    0.12       0  5159.7    0.16       0
Bank Sta=4960.6,5068.9
Exp/Cntr=0.3,0.1

Type RM Length L Ch R = 1,12787,262,262,262
BEGIN DESCRIPTION:
UNT 176 in LFCCL Watershed 28.0
END DESCRIPTION:
XS GIS Cut Line= 3
      2813175.00      7020475.00      2813475.00      7019875.00
      2813825.00      7019575.00
#Sta/Elev= 30
  4293.7  476.46  4503.3  459.39  4651.5  450.20  4699.0  447.94  4740.9  447.43
  4749.3  445.84  4754.9  446.32  4760.3  444.50  4760.8  443.70  4765.8  443.70
  4766.3  444.50  4771.7  446.66  4777.2  446.30  4785.6  447.24  4854.0  447.07
  4866.7  447.02  4883.5  445.73  4905.8  447.44  4928.3  447.41  4985.9  447.24
  4992.5  445.32  5006.8  447.21  5043.0  446.05  5074.9  447.94  5145.9  453.95
  5283.4  466.02  5326.2  470.49  5340.4  472.78  5383.2  477.68  5425.5  481.18
#Mann=6,-1,0
  4293.7    0.05       0  4760.3    0.07       0  4766.3    0.05       0
  4854.0    0.16       0  4928.3    0.12       0  5145.9    0.16       0
Bank Sta=4699,5074.9
Exp/Cntr=0.3,0.1

Type RM Length L Ch R = 1,12525,320,320,320
BEGIN DESCRIPTION:
UNT 176 in LFCCL Watershed 27.0
END DESCRIPTION:
XS GIS Cut Line= 3
      2813374.99      7020675.02      2813625.00      7020125.00
      2813875.00      7019774.99
#Sta/Elev= 30
  4261.8  484.14  4327.7  477.61  4437.6  468.52  4448.6  465.83  4459.5  460.09
  4466.1  458.45  4569.4  458.64  4580.4  459.84  4592.5  462.39  4602.3  462.03
  4633.1  457.51  4721.6  452.79  4767.1  449.20  4809.9  447.10  4857.2  445.56
  4863.2  443.06  4869.0  443.06  4870.3  441.13  4870.8  440.33  4875.8  440.33
  4876.3  441.13  4894.2  445.92  4949.5  445.43  4988.9  444.20  5049.1  447.10
  5095.8  450.55  5166.2  459.30  5223.6  466.96  5259.2  473.19  5296.1  476.44
#Mann=6,-1,0
  4261.8    0.05       0  4721.6    0.16       0  4870.3    0.07       0
  4876.3    0.16       0  4949.5    0.12       0  5166.2    0.16       0
Bank Sta=4809.9,5049.1
Exp/Cntr=0.3,0.1

Type RM Length L Ch R = 1,12205,344,344,344
BEGIN DESCRIPTION:
UNT 176 in LFCCL Watershed 26.0
END DESCRIPTION:
XS GIS Cut Line= 3
      2813675.01      7020824.97      2813925.00      7020225.00
      2814225.02      7019974.99
#Sta/Elev= 30
  4337.1  483.66  4391.2  478.67  4488.7  467.41  4510.9  465.26  4529.4  464.38
  4613.9  455.84  4714.6  455.05  4736.3  454.55  4799.3  449.41  4859.0  445.45
  4878.7  444.20  4911.2  443.62  4924.8  444.72  4948.6  443.84  4977.9  444.25
  4984.4  438.68  4991.2  438.41  4991.7  437.61  4996.7  437.61  4997.2  438.41
  5000.7  442.40  5015.1  444.30  5037.2  444.35  5060.3  445.45  5115.3  447.41
  5150.4  449.65  5228.8  456.49  5292.3  463.07  5349.6  470.94  5377.6  474.02
#Mann=7,-1,0
  4337.1    0.16       0  4613.9    0.12       0  4714.6    0.16       0
  4799.3    0.12       0  4991.2    0.07       0  4997.2    0.12       0
  5228.8    0.16       0
Bank Sta=4859,5060.3
Exp/Cntr=0.3,0.1

Type RM Length L Ch R = 1,11861,384,384,384
BEGIN DESCRIPTION:
UNT 176 in LFCCL Watershed 25.0
END DESCRIPTION:
XS GIS Cut Line= 3
      2813825.00      7020825.00      2814175.00      7020425.00
      2814425.03      7020174.97
#Sta/Elev= 30
  4470.4  477.34  4473.7  477.34  4477.5  476.06  4526.9  468.30  4569.6  462.49
  4684.7  451.23  4739.5  446.48  4782.2  443.87  4801.4  443.70  4888.5  442.04
  4952.1  442.87  4973.9  442.51  4980.6  440.55  4988.1  440.48  4991.8  436.85
  4992.3  436.05  4997.3  436.05  4997.8  436.85  4998.6  437.82  5005.4  437.82
  5016.1  443.01  5044.3  442.66  5066.2  443.70  5133.2  449.19  5146.3  450.49
  5185.8  454.63  5214.0  456.78  5270.6  463.05  5327.2  471.72  5355.5  474.44
#Mann=6,-1,0
  4470.4    0.16       0  4684.7    0.12       0  4991.8    0.07       0
  4997.8    0.12       0  5133.2    0.16       0  5146.3    0.12       0
Bank Sta=4801.4,5066.2
Exp/Cntr=0.3,0.1

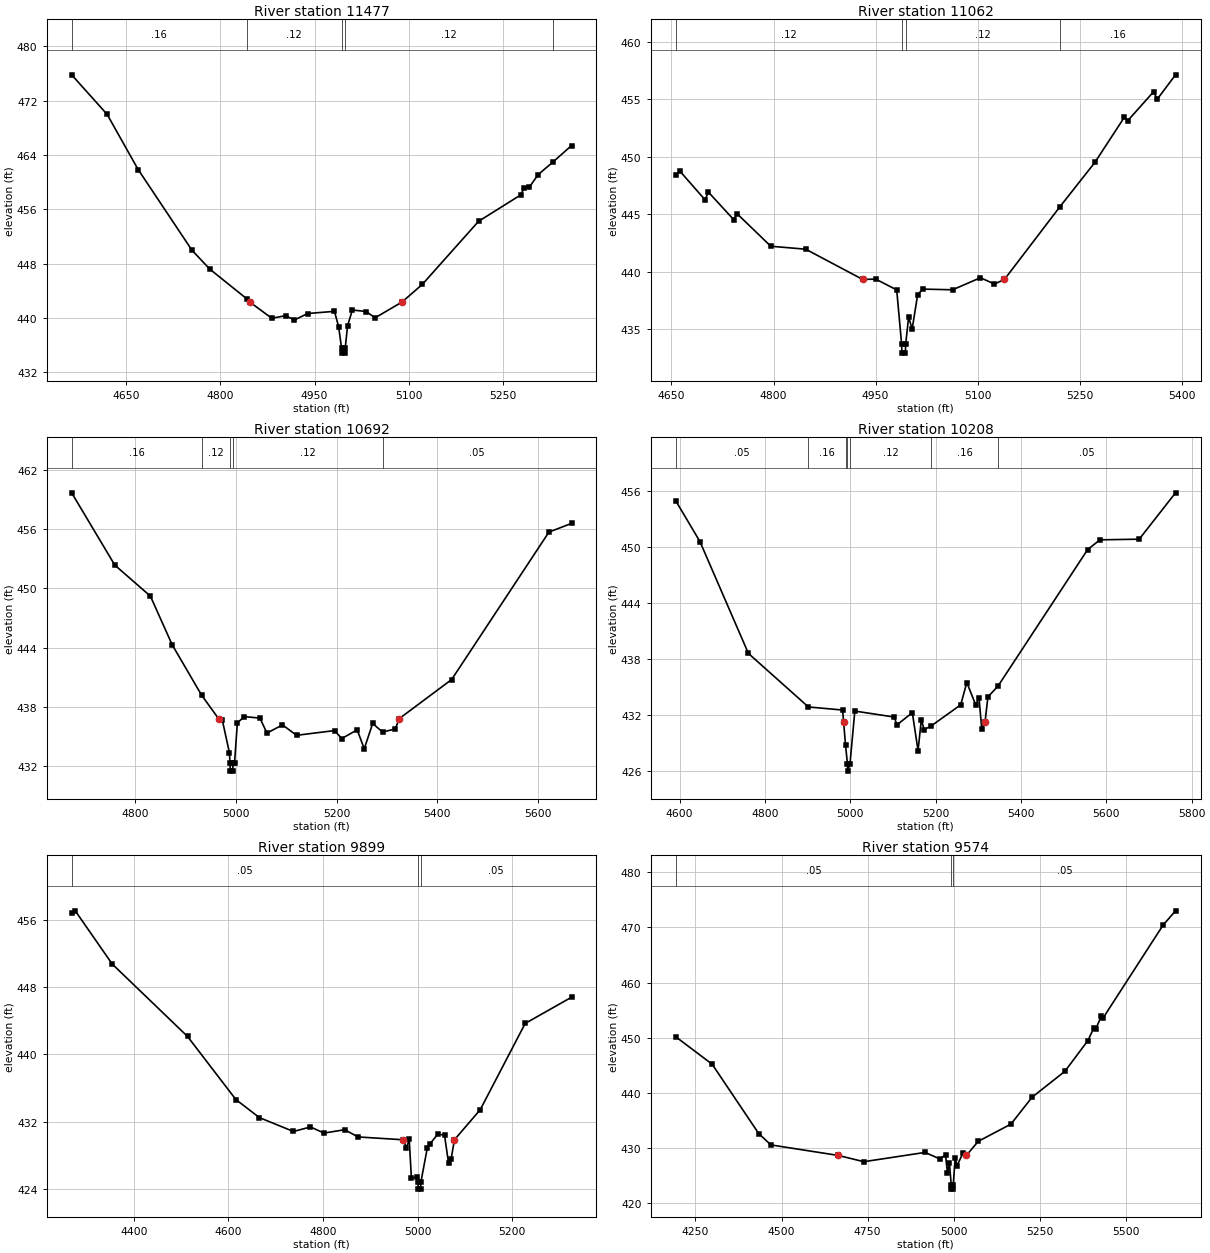
Type RM Length L Ch R = 1,11477,415,415,415
BEGIN DESCRIPTION:
UNT 176 in LFCCL Watershed 24.0
END DESCRIPTION:
XS GIS Cut Line= 3
      2814075.03      7021074.97      2814375.00      7020725.00
      2814524.98      7020425.04
#Sta/Elev= 30
  4563.0  475.82  4619.5  469.99  4668.9  461.86  4754.5  449.98  4783.0  447.18
  4841.8  442.81  4846.7  442.33  4881.8  439.93  4903.7  440.31  4918.0  439.68
  4938.9  440.63  4981.7  440.95  4988.3  438.68  4992.9  435.59  4993.4  434.79
  4998.4  434.79  4998.9  435.59  5002.5  438.81  5010.2  441.15  5032.3  440.92
  5046.3  439.99  5089.4  442.33  5121.8  444.94  5211.2  454.22  5278.3  458.11
  5283.9  459.14  5292.3  459.28  5306.2  461.11  5330.4  463.02  5359.3  465.39
#Mann=5,-1,0
  4563.0    0.16       0  4841.8    0.12       0  4992.9    0.07       0
  4998.9    0.12       0  5330.4    0.16       0
Bank Sta=4846.7,5089.4
Exp/Cntr=0.3,0.1

Type RM Length L Ch R = 1,11062,370,370,370
BEGIN DESCRIPTION:
UNT 176 in LFCCL Watershed 23.0
END DESCRIPTION:
XS GIS Cut Line= 3
      2814589.71      7021230.81      2814675.00      7020875.00
      2814756.39      7020515.49
#Sta/Elev= 30
  4656.2  448.45  4662.4  448.75  4699.3  446.26  4704.4  446.92  4741.3  444.54
  4746.4  445.05  4795.9  442.22  4847.3  441.96  4931.0  439.33  4950.1  439.36
  4981.0  438.42  4988.2  433.72  4988.7  432.92  4993.7  432.92  4994.2  433.72
  4998.5  436.05  5003.7  435.02  5011.8  438.02  5019.5  438.49  5063.1  438.43
  5104.1  439.48  5124.6  438.93  5139.3  439.33  5220.5  445.63  5272.2  449.51
  5315.4  453.43  5320.5  453.14  5358.5  455.66  5363.7  455.00  5390.7  457.13
#Mann=4,-1,0
  4656.2    0.12       0  4988.2    0.07       0  4994.2    0.12       0
  5220.5    0.16       0
Bank Sta=4931,5139.3
Exp/Cntr=0.3,0.1

Type RM Length L Ch R = 1,10692,484,484,484
BEGIN DESCRIPTION:
UNT 176 in LFCCL Watershed 22.0
END DESCRIPTION:
XS GIS Cut Line= 3
      2814775.01      7021324.98      2814975.00      7021075.00
      2815275.02      7020474.96
#Sta/Elev= 30
  4674.9  459.66  4760.5  452.35  4831.0  449.22  4874.2  444.30  4932.6  439.20
  4966.2  436.83  4973.4  436.73  4987.8  433.36  4988.8  432.33  4989.3  431.53
  4994.3  431.53  4994.8  432.33  4997.8  432.33  5003.4  436.41  5017.4  437.04
  5048.1  436.89  5062.1  435.38  5092.9  436.20  5120.8  435.15  5196.3  435.63
  5210.3  434.82  5241.0  435.70  5255.0  433.79  5271.7  436.35  5291.2  435.48
  5316.5  435.79  5324.2  436.83  5428.3  440.79  5621.1  455.69  5665.9  456.57
#Mann=5,-1,0
  4674.9    0.16       0  4932.6    0.12       0  4988.8    0.07       0
  4994.8    0.12       0  5291.2    0.05       0
Bank Sta=4966.2,5324.2
Exp/Cntr=0.3,0.1

Type RM Length L Ch R = 1,10208,309,309,309
BEGIN DESCRIPTION:
UNT 176 in LFCCL Watershed 21.0
END DESCRIPTION:
XS GIS Cut Line= 3
      2815075.03      7021524.96      2815295.14      7021248.16
      2815824.98      7020625.02
#Sta/Elev= 30
  4590.6  454.96  4647.4  450.58  4761.1  438.58  4901.7  432.84  4981.9  432.51
  4984.1  431.28  4988.8  428.72  4993.2  426.76  4993.7  425.96  4999.2  426.76
  5010.5  432.40  5102.7  431.76  5109.3  430.92  5145.3  432.23  5158.7  428.16
  5166.4  431.47  5173.0  430.41  5189.0  430.79  5258.7  433.07  5273.0  435.46
  5293.8  433.07  5301.5  433.85  5308.1  430.45  5315.9  431.28  5322.4  433.91
  5346.3  435.09  5556.3  449.72  5584.9  450.76  5677.1  450.83  5762.2  455.80
#Mann=7,-1,0
  4590.6    0.05       0  4901.7    0.16       0  4988.8    0.12       0
  4993.2    0.07       0  4999.2    0.12       0  5189.0    0.16       0
  5346.3    0.05       0
Bank Sta=4984.1,5315.9
Exp/Cntr=0.3,0.1

Type RM Length L Ch R = 1,9899,325,325,325
BEGIN DESCRIPTION:
UNT 176 in LFCCL Watershed 20.0
END DESCRIPTION:
XS GIS Cut Line= 3
      2815174.98      7021775.04      2815575.00      7021175.00
      2815725.02      7020874.97
#Sta/Elev= 30
  4268.6  456.87  4276.2  457.12  4354.3  450.78  4513.5  442.15  4615.7  434.63
  4665.3  432.48  4737.4  430.82  4773.4  431.36  4802.0  430.63  4845.5  431.03
  4874.1  430.17  4969.9  429.83  4976.2  428.85  4982.2  429.87  4986.7  425.29
  4998.1  425.35  5000.7  424.75  5001.2  423.95  5006.2  423.95  5006.7  424.75
  5020.5  428.90  5026.1  429.34  5042.9  430.54  5056.8  430.36  5065.2  427.10
  5070.8  427.57  5077.7  429.83  5132.3  433.42  5227.3  443.70  5325.2  446.82
#Mann=3,-1,0
  4268.6    0.05       0  5000.7    0.03       0  5006.7    0.05       0
Bank Sta=4969.9,5077.7
Exp/Cntr=0.3,0.1

Type RM Length L Ch R = 1,9574,313,313,313
BEGIN DESCRIPTION:
UNT 176 in LFCCL Watershed 19.0
END DESCRIPTION:
XS GIS Cut Line= 3
      2815375.03      7021724.97      2815875.00      7021125.00
      2816175.00      7020525.00
#Sta/Elev= 30
  4192.5  450.20  4298.5  445.22  4433.9  432.64  4469.1  430.60  4664.1  428.70
  4739.2  427.56  4916.9  429.24  4959.8  428.06  4976.3  428.79  4981.9  425.48
  4987.5  427.38  4992.8  423.39  4993.3  422.59  4998.3  422.59  4998.8  423.39
  5004.2  428.20  5009.8  426.84  5026.6  429.08  5036.9  428.70  5071.3  431.25
  5166.3  434.37  5227.8  439.25  5322.9  443.93  5389.9  449.51  5406.7  451.76
  5412.3  451.52  5429.1  454.00  5434.7  453.67  5608.0  470.41  5644.3  473.01
#Mann=3,-1,0
  4192.5    0.05       0  4992.8    0.03       0  4998.8    0.05       0
Bank Sta=4664.1,5036.9
Exp/Cntr=0.3,0.1

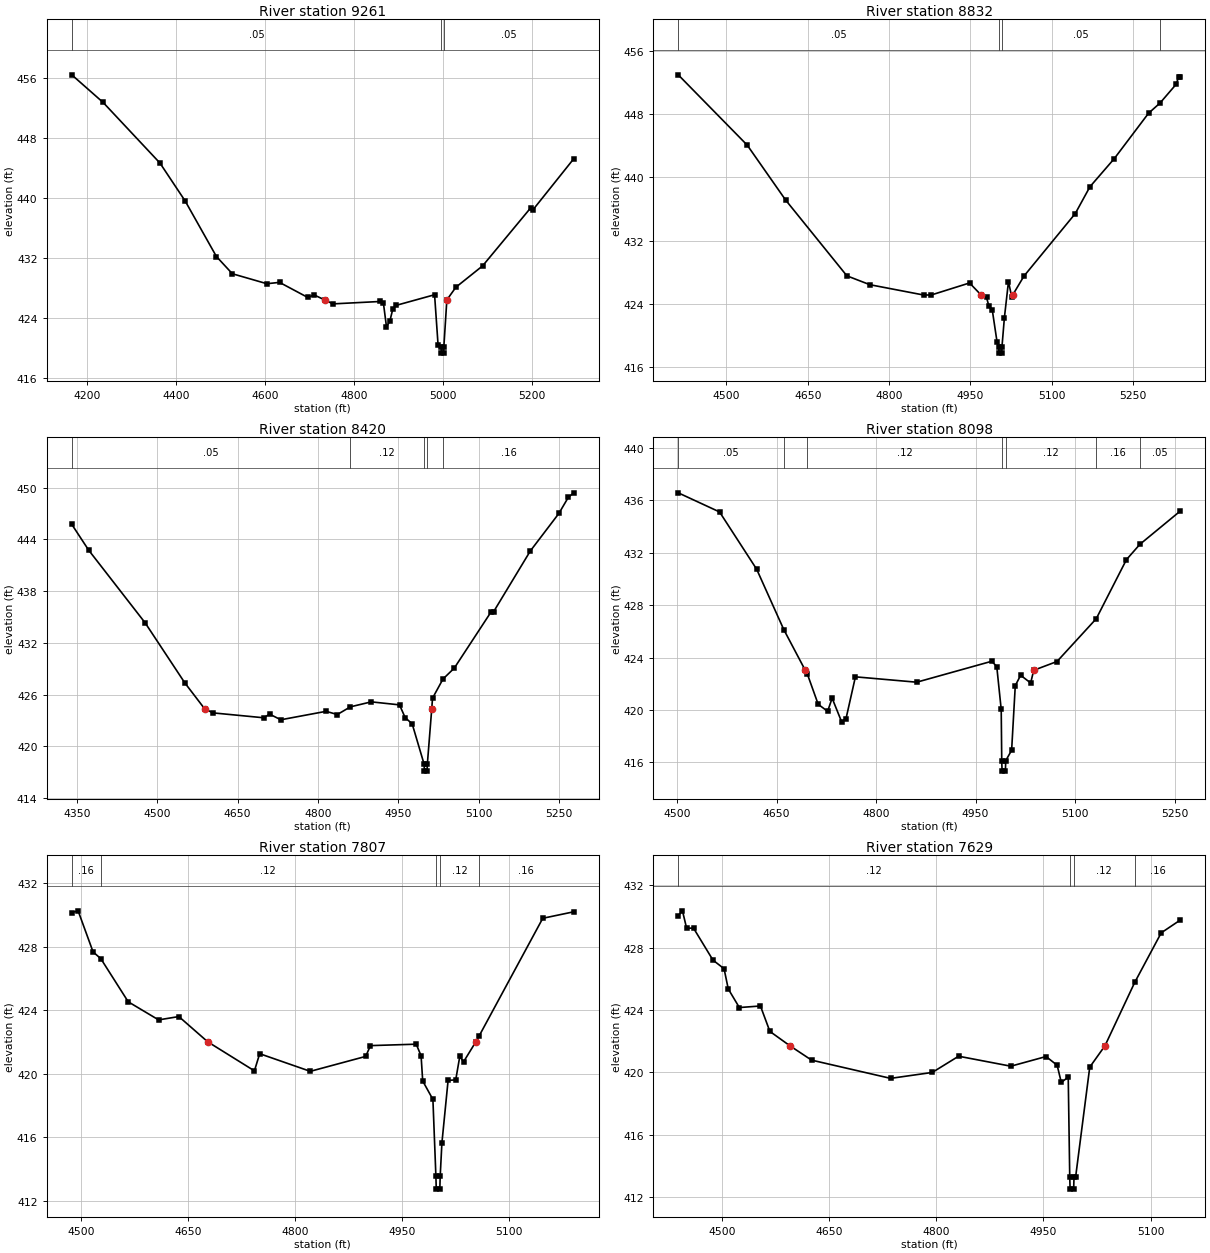
Type RM Length L Ch R = 1,9261,429,429,429
BEGIN DESCRIPTION:
UNT 176 in LFCCL Watershed 18.0
END DESCRIPTION:
XS GIS Cut Line= 3
      2815424.97      7021875.03      2816027.21      7021324.55
      2816339.70      7021303.72
#Sta/Elev= 30
  4165.1  456.44  4235.7  452.75  4363.4  444.67  4420.2  439.60  4490.4  432.20
  4526.2  429.90  4603.9  428.57  4632.3  428.75  4695.8  426.74  4710.0  427.08
  4733.8  426.41  4752.5  425.88  4858.6  426.20  4866.0  425.96  4872.8  422.84
  4880.2  423.54  4887.0  425.17  4894.4  425.68  4981.0  427.10  4988.8  420.45
  4995.8  420.11  4996.3  419.31  5001.3  419.31  5001.8  420.11  5008.6  426.41
  5028.9  428.10  5089.0  430.95  5197.0  438.68  5202.1  438.42  5294.2  445.26
#Mann=3,-1,0
  4165.1    0.05       0  4995.8    0.03       0  5001.8    0.05       0
Bank Sta=4733.8,5008.6
Exp/Cntr=0.3,0.1

Type RM Length L Ch R = 1,8832,412,412,412
BEGIN DESCRIPTION:
UNT 176 in LFCCL Watershed 17.0
END DESCRIPTION:
XS GIS Cut Line= 3
      2815675.01      7022124.99      2816075.00      7021725.00
      2816374.98      7021525.01
#Sta/Elev= 30
  4411.1  452.94  4538.4  444.06  4609.1  437.14  4722.2  427.56  4764.6  426.44
  4863.6  425.14  4877.8  425.14  4948.5  426.66  4969.8  425.14  4979.8  424.83
  4984.3  423.72  4990.3  423.30  4999.3  419.18  5002.3  418.60  5002.8  417.80
  5007.8  417.80  5008.3  418.60  5012.8  422.29  5020.3  426.83  5026.3  424.91
  5028.1  425.14  5048.9  427.53  5143.5  435.42  5170.6  438.81  5215.6  442.37
  5278.7  448.09  5299.9  449.38  5329.8  451.76  5334.3  452.72  5337.3  452.72
#Mann=4,-1,0
  4411.1    0.05       0  5002.3    0.03       0  5008.3    0.05       0
  5299.9    0.16       0
Bank Sta=4969.8,5028.1
Exp/Cntr=0.3,0.1

Type RM Length L Ch R = 1,8420,322,322,322
BEGIN DESCRIPTION:
UNT 176 in LFCCL Watershed 16.0
END DESCRIPTION:
XS GIS Cut Line= 3
      2815774.99      7022125.00      2816375.00      7021925.00
      2816425.00      7021625.01
#Sta/Elev= 30
  4340.8  445.75  4372.4  442.75  4477.8  434.31  4551.6  427.36  4588.7  424.34
  4604.3  423.87  4699.2  423.30  4709.7  423.73  4730.8  423.07  4815.2  424.05
  4836.2  423.68  4860.5  424.57  4899.5  425.15  4952.2  424.80  4962.7  423.32
  4975.8  422.60  4998.1  417.91  4998.6  417.11  5003.6  417.11  5004.1  417.91
  5012.3  424.34  5013.8  425.58  5033.3  427.80  5054.4  429.07  5122.8  435.57
  5127.9  435.63  5196.3  442.67  5249.5  447.02  5267.3  448.91  5277.4  449.41
#Mann=5,-1,0
  4340.8    0.05       0  4860.5    0.12       0  4998.1    0.07       0
  5004.1    0.12       0  5033.3    0.16       0
Bank Sta=4588.7,5012.3
Exp/Cntr=0.3,0.1

Type RM Length L Ch R = 1,8098,291,291,291
BEGIN DESCRIPTION:
UNT 176 in LFCCL Watershed 15.0
END DESCRIPTION:
XS GIS Cut Line= 3
      2816197.31      7022414.86      2816565.40      7022084.97
      2816673.03      7021845.42
#Sta/Elev= 30
  4501.8  436.58  4564.1  435.12  4620.1  430.74  4660.9  426.14  4693.3  423.03
  4696.2  422.78  4712.8  420.43  4727.0  419.90  4733.8  420.90  4748.0  419.11
  4754.7  419.33  4768.9  422.53  4861.3  422.12  4974.5  423.72  4982.0  423.31
  4988.7  420.04  4989.5  416.13  4990.0  415.33  4995.0  415.33  4995.5  416.13
  5004.4  416.92  5009.9  421.86  5018.0  422.65  5033.1  422.06  5037.7  423.03
  5072.8  423.70  5132.0  426.97  5177.5  431.48  5197.8  432.65  5258.7  435.19
#Mann=7,-1,0
  4501.8    0.05       0  4660.9    0.16       0  4696.2    0.12       0
  4989.5    0.07       0  4995.5    0.12       0  5132.0    0.16       0
  5197.8    0.05       0
Bank Sta=4693.3,5037.7
Exp/Cntr=0.3,0.1

Type RM Length L Ch R = 1,7807,178,178,178
BEGIN DESCRIPTION:
XS4044A
END DESCRIPTION:
XS GIS Cut Line= 3
      2816377.88      7022630.13      2816742.49      7022296.78
      2816815.18      7022099.47
#Sta/Elev= 30
  4486.7  430.16  4495.6  430.27  4516.6  427.68  4527.4  427.26  4565.9  424.54
  4608.5  423.40  4636.9  423.61  4677.4  422.02  4742.9  420.19  4750.3  421.27
  4821.3  420.16  4899.0  421.10  4905.7  421.78  4969.9  421.87  4976.7  421.14
  4979.0  419.55  4993.3  418.39  4997.5  413.54  4998.0  412.74  5003.0  412.74
  5003.5  413.54  5005.9  415.64  5014.6  419.59  5025.3  419.62  5031.0  421.10
  5036.3  420.76  5053.5  422.02  5057.8  422.36  5147.4  429.80  5191.0  430.21
#Mann=5,-1,0
  4486.7    0.16       0  4527.4    0.12       0  4997.5    0.07       0
  5003.5    0.12       0  5057.8    0.16       0
Bank Sta=4677.4,5053.5
Exp/Cntr=0.3,0.1

Type RM Length L Ch R = 1,7629,521,521,521
BEGIN DESCRIPTION:
XS4045A
END DESCRIPTION:
XS GIS Cut Line= 3
      2816426.53      7022643.99      2816898.74      7022359.28
      2816898.74      7022208.28
#Sta/Elev= 30
  4439.2  430.05  4445.1  430.36  4450.9  429.25  4460.6  429.25  4487.8  427.20
  4503.3  426.65  4509.2  425.35  4524.7  424.16  4554.2  424.26  4567.4  422.63
  4595.4  421.71  4625.7  420.79  4736.3  419.62  4794.6  420.00  4831.4  421.04
  4904.5  420.40  4953.8  421.02  4969.3  420.46  4975.1  419.36  4984.8  419.70
  4986.9  413.32  4987.4  412.52  4992.4  412.52  4992.9  413.32  4995.2  413.32
  5014.9  420.34  5036.2  421.71  5077.8  425.77  5114.9  428.95  5141.6  429.77
#Mann=4,-1,0
  4439.2    0.12       0  4986.9    0.07       0  4992.9    0.12       0
  5077.8    0.16       0
Bank Sta=4595.4,5036.2
Exp/Cntr=0.3,0.1

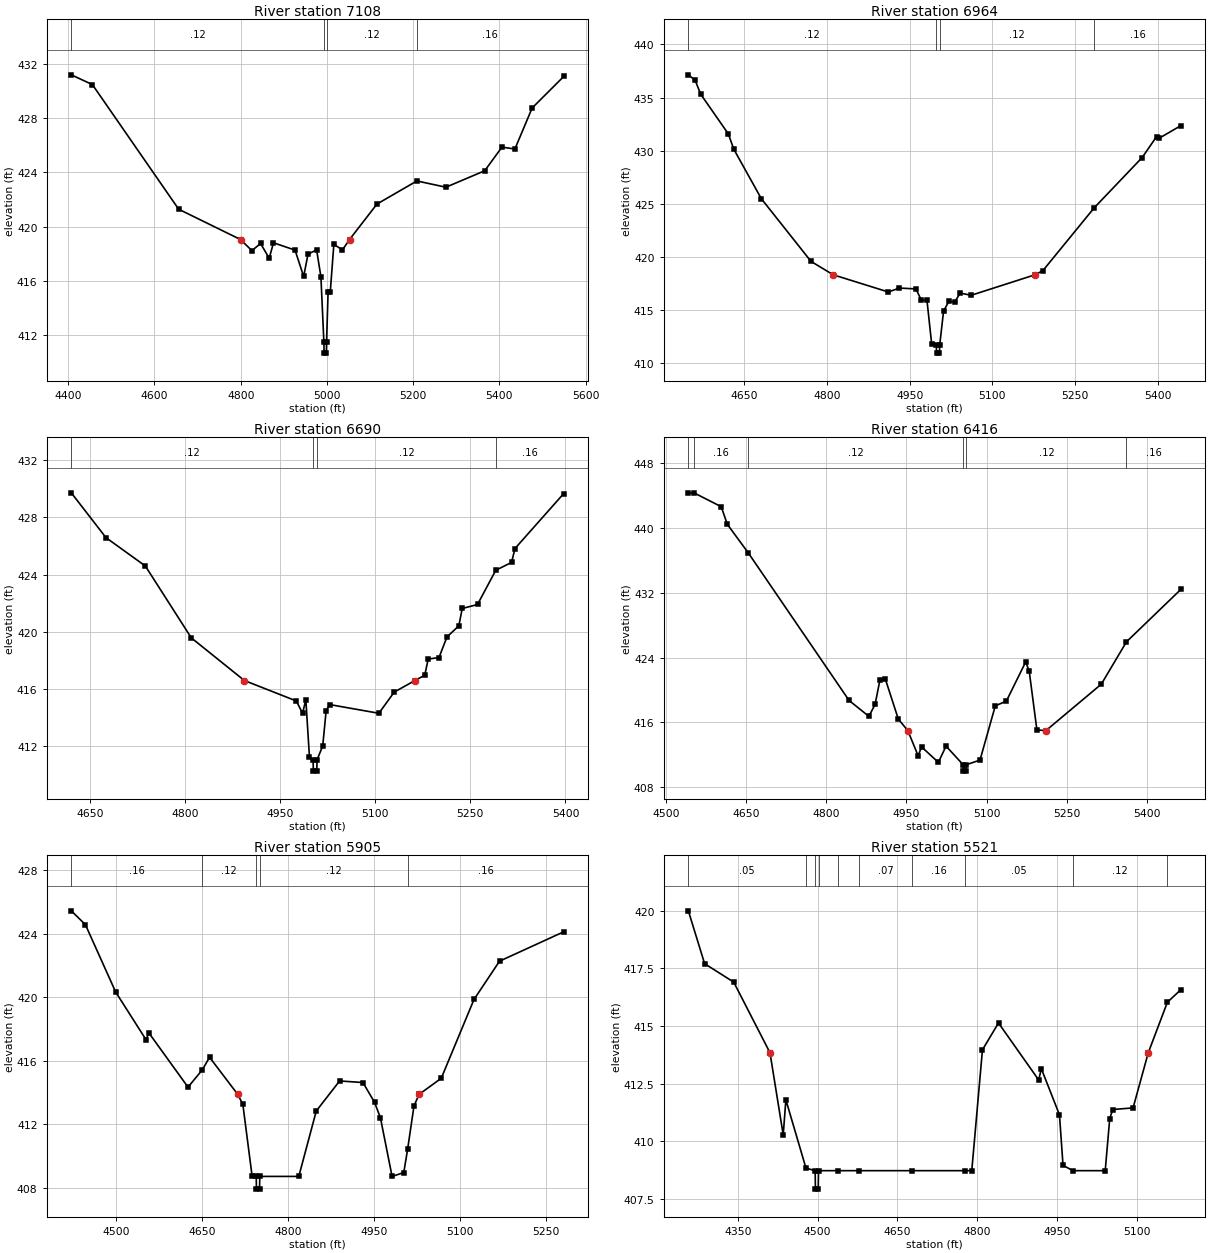
Type RM Length L Ch R = 1,7108,144,144,144
BEGIN DESCRIPTION:
XS4043A
END DESCRIPTION:
XS GIS Cut Line= 3
      2816495.97      7022671.78      2817093.18      7022678.72
      2817638.28      7022671.78
#Sta/Elev= 30
  4407.0  431.17  4456.0  430.45  4656.1  421.28  4799.6  419.05  4826.1  418.23
  4846.1  418.76  4866.1  417.67  4876.1  418.81  4926.1  418.27  4946.1  416.33
  4956.1  417.97  4976.1  418.29  4986.1  416.31  4993.0  411.49  4993.5  410.69
  4998.7  410.69  4999.2  411.49  5002.7  415.16  5007.7  415.16  5016.1  418.69
  5036.1  418.29  5052.5  419.05  5116.1  421.66  5208.7  423.36  5276.1  422.90
  5366.1  424.11  5406.1  425.85  5436.1  425.71  5476.1  428.73  5549.4  431.05
#Mann=4,-1,0
  4407.0    0.12       0  4993.0    0.07       0  4999.2    0.12       0
  5208.7    0.16       0
Bank Sta=4799.6,5052.5
Exp/Cntr=0.3,0.1

Type RM Length L Ch R = 1,6964,274,274,274
BEGIN DESCRIPTION:
XS4042A
END DESCRIPTION:
XS GIS Cut Line= 3
      2816662.66      7022817.61      2817107.07      7022803.72
      2817554.99      7022810.67
#Sta/Elev= 30
  4548.9  437.14  4561.2  436.63  4571.2  435.32  4621.3  431.58  4631.3  430.13
  4681.3  425.46  4771.3  419.56  4811.5  418.30  4911.4  416.68  4931.4  417.05
  4961.4  416.97  4971.4  415.89  4981.4  415.91  4990.0  411.75  4998.3  411.72
  4998.8  410.92  5004.1  410.92  5004.6  411.72  5011.5  414.88  5021.5  415.84
  5031.5  415.70  5041.5  416.58  5061.5  416.37  5177.2  418.30  5191.5  418.69
  5284.7  424.62  5371.5  429.35  5397.5  431.31  5402.5  431.17  5441.5  432.35
#Mann=4,-1,0
  4548.9    0.12       0  4998.3    0.07       0  5004.6    0.12       0
  5284.7    0.16       0
Bank Sta=4811.5,5177.2
Exp/Cntr=0.3,0.1

Type RM Length L Ch R = 1,6690,274,274,274
BEGIN DESCRIPTION:
XS4046A
END DESCRIPTION:
XS GIS Cut Line= 3
      2816902.19      7023105.81      2817277.21      7023005.11
      2817637.44      7022859.63
#Sta/Elev= 30
  4620.5  429.71  4675.2  426.58  4737.3  424.60  4809.8  419.58  4893.5  416.60
  4975.5  415.17  4985.3  414.31  4990.5  415.25  4996.2  411.25  5001.9  411.07
  5002.4  410.27  5007.7  410.27  5008.2  411.07  5017.1  412.02  5022.5  414.49
  5028.0  414.92  5105.7  414.31  5129.9  415.79  5162.6  416.60  5178.1  416.97
  5183.5  418.10  5200.5  418.20  5213.1  419.64  5231.8  420.42  5237.2  421.63
  5261.3  421.91  5290.1  424.30  5315.0  424.85  5320.4  425.82  5397.3  429.66
#Mann=4,-1,0
  4620.5    0.12       0  5001.9    0.07       0  5008.2    0.12       0
  5290.1    0.16       0
Bank Sta=4893.5,5162.6
Exp/Cntr=0.3,0.1

Type RM Length L Ch R = 1,6416,511,511,511
BEGIN DESCRIPTION:
UNT 176 in LFCCL Watershed 12.0
END DESCRIPTION:
XS GIS Cut Line= 3
      2816975.00      7023325.00      2817425.00      7023225.00
      2817724.97      7022875.04
#Sta/Elev= 30
  4541.8  444.29  4552.3  444.34  4603.3  442.63  4614.8  440.45  4654.3  436.90
  4842.7  418.71  4879.8  416.75  4891.4  418.23  4900.3  421.19  4910.6  421.35
  4934.9  416.41  4952.7  414.99  4972.0  411.88  4978.4  412.98  5009.9  411.07
  5024.2  413.08  5056.1  410.79  5056.6  409.99  5061.9  409.99  5062.4  410.79
  5087.8  411.35  5116.4  418.04  5137.2  418.64  5173.4  423.48  5180.0  422.29
  5194.3  415.08  5211.2  414.99  5315.0  420.73  5362.0  425.95  5463.7  432.41
#Mann=6,-1,0
  4541.8    0.12       0  4552.3    0.16       0  4654.3    0.12       0
  5056.1    0.07       0  5062.4    0.12       0  5362.0    0.16       0
Bank Sta=4952.7,5211.2
Exp/Cntr=0.3,0.1

Type RM Length L Ch R = 1,5905,384,384,384
BEGIN DESCRIPTION:
UNT 176 in LFCCL Watershed 11.0
END DESCRIPTION:
XS GIS Cut Line= 3
      2817134.83      7023734.28      2817725.00      7023625.00
      2817954.25      7023505.13
#Sta/Elev= 30
  4422.2  425.45  4446.8  424.58  4499.6  420.34  4552.5  417.34  4557.6  417.76
  4625.8  414.35  4650.5  415.43  4663.4  416.23  4712.6  413.89  4721.4  413.27
  4737.6  408.74  4744.7  408.73  4745.2  407.93  4750.5  407.93  4751.0  408.73
  4819.0  408.73  4849.5  412.85  4890.2  414.74  4930.9  414.64  4951.2  413.39
  4961.4  412.42  4981.7  408.73  5002.1  408.97  5008.8  410.44  5019.9  413.16
  5028.7  413.89  5067.5  414.91  5124.6  419.87  5169.1  422.28  5281.1  424.13
#Mann=5,-1,0
  4422.2    0.16       0  4650.5    0.12       0  4744.7    0.07       0
  4751.0    0.12       0  5008.8    0.16       0
Bank Sta=4712.6,5028.7
Exp/Cntr=0.3,0.1

Type RM Length L Ch R = 1,5521,498,498,498
BEGIN DESCRIPTION:
XS4047A
END DESCRIPTION:
XS GIS Cut Line= 3
      2817044.58      7024098.86      2817739.02      7024025.94
      2817940.40      7023918.31
#Sta/Elev= 30
  4256.7  419.99  4287.3  417.70  4342.1  416.90  4410.3  413.84  4435.2  410.28
  4440.2  411.80  4478.0  408.84  4495.3  408.73  4495.8  407.93  4501.1  407.93
  4501.6  408.73  4539.0  408.73  4577.9  408.73  4677.7  408.73  4777.6  408.73
  4790.0  408.73  4810.1  413.97  4840.3  415.13  4915.9  412.66  4920.9  413.15
  4955.0  411.15  4961.7  408.96  4980.3  408.73  5041.1  408.73  5049.6  410.99
  5055.3  411.38  5093.5  411.45  5122.1  413.84  5158.1  416.03  5183.3  416.57
#Mann=10,-1,0
  4256.7    0.05       0  4478.0    0.07       0  4495.3    0.07       0
  4501.6    0.07       0  4539.0    0.16       0  4577.9    0.07       0
  4677.7    0.16       0  4777.6    0.05       0  4980.3    0.12       0
  5158.1    0.16       0
Bank Sta=4410.3,5122.1
Exp/Cntr=0.3,0.1