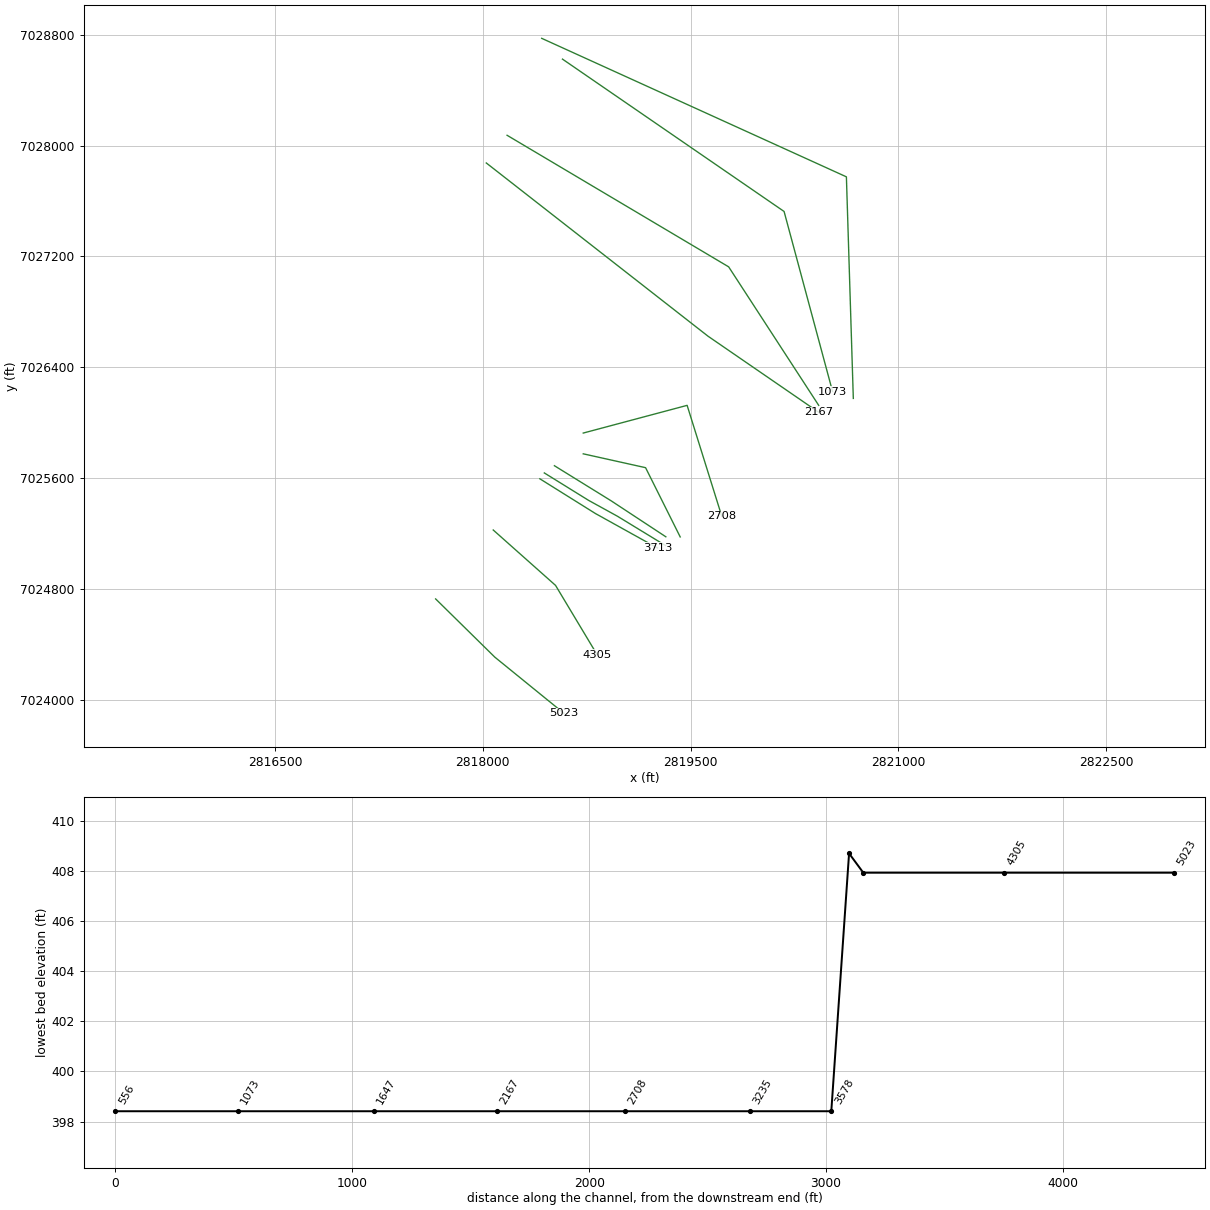
HEC-RAS study UNT 176 in LFCCL Watershed.prj: UNT 176 in LFCCL Watershed Base Level Engineering

--- UNT 176 in LFCCL Watershed.g01 (geometry) --- (continued)

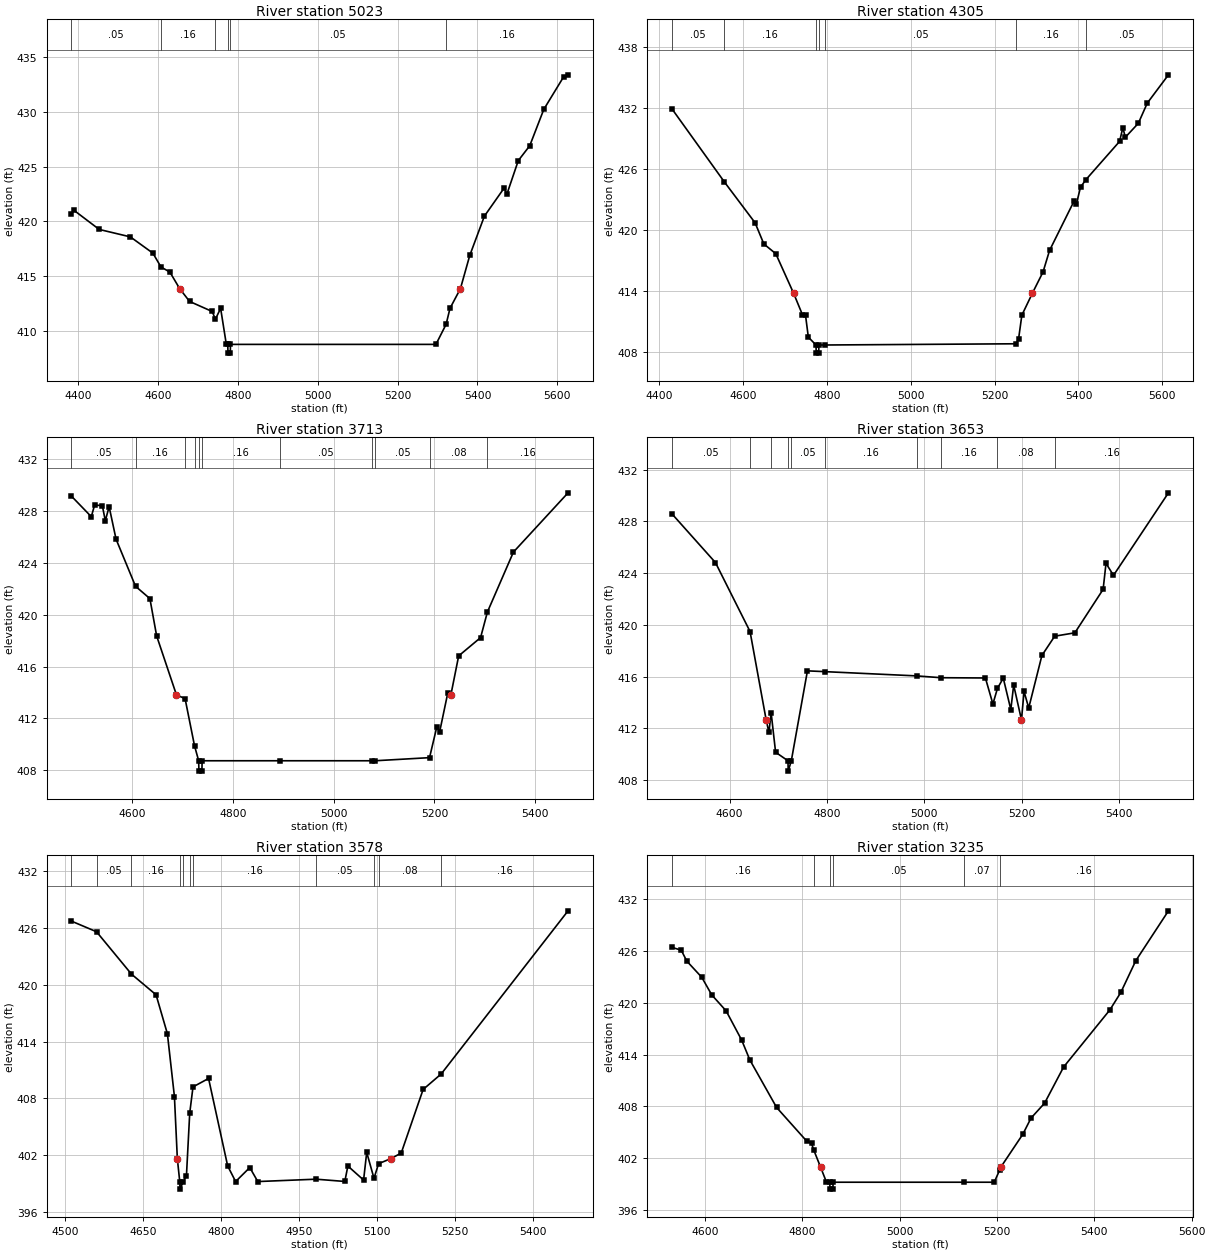
Type RM Length L Ch R = 1,5023,718,718,718
BEGIN DESCRIPTION:
XS4048A
END DESCRIPTION:
XS GIS Cut Line= 3
      2817659.15      7024727.34      2818086.24      7024307.19
      2818586.21      7023900.97
#Sta/Elev= 30
  4383.5  420.66  4389.3  421.01  4452.9  419.25  4530.8  418.57  4587.3  417.08
  4607.6  415.81  4629.8  415.35  4654.4  413.83  4679.2  412.66  4735.8  411.74
  4743.8  411.03  4756.9  412.03  4771.1  408.75  4774.8  408.73  4775.3  407.93
  4781.1  407.93  4781.6  408.73  5296.0  408.73  5321.5  410.57  5331.2  412.03
  5357.3  413.83  5380.7  416.87  5417.4  420.47  5467.0  423.05  5473.4  422.45
  5502.2  425.55  5530.9  426.91  5566.1  430.24  5615.6  433.21  5626.8  433.40
#Mann=6,-1,0
  4383.5    0.05       0  4607.6    0.16       0  4743.8    0.05       0
  4774.8   0.033       0  4781.6    0.05       0  5321.5    0.16       0
Bank Sta=4654.4,5357.3
Exp/Cntr=0.3,0.1

Type RM Length L Ch R = 1,4305,592,592,592
BEGIN DESCRIPTION:
UNT 176 in LFCCL Watershed 8.0
END DESCRIPTION:
XS GIS Cut Line= 3
      2818074.98      7025225.02      2818525.00      7024825.00
      2818825.00      7024325.00
#Sta/Elev= 30
  4429.6  431.97  4555.1  424.76  4628.2  420.75  4649.1  418.67  4677.6  417.71
  4720.1  413.82  4741.1  411.72  4748.6  411.64  4755.3  409.50  4773.6  408.73
  4774.1  407.93  4780.0  407.93  4780.5  408.73  4795.6  408.73  5251.7  408.85
  5257.2  409.36  5264.9  411.66  5290.0  413.82  5315.5  415.92  5331.0  418.03
  5389.3  422.87  5395.2  422.61  5404.9  424.26  5418.1  425.01  5498.2  428.76
  5506.0  430.12  5511.8  429.16  5542.9  430.54  5564.3  432.53  5614.8  435.31
#Mann=7,-1,0
  4429.6    0.05       0  4555.1    0.16       0  4773.6   0.033       0
  4780.5    0.16       0  4795.6    0.05       0  5251.7    0.16       0
  5418.1    0.05       0
Bank Sta=4720.1,5290
Exp/Cntr=0.3,0.1

Type RM Length L Ch R = 1,3713,60,60,60
BEGIN DESCRIPTION:
UNT 176 in LFCCL Watershed 7.0
END DESCRIPTION:
XS GIS Cut Line= 3
      2818411.67      7025594.71      2818811.63      7025344.73
      2819260.81      7025095.19
#Sta/Elev= 30
  4479.8  429.14  4519.1  427.56  4525.7  428.46  4541.0  428.41  4546.9  427.25
  4554.5  428.33  4568.2  425.83  4606.9  422.19  4635.4  421.24  4648.8  418.36
  4688.2  413.80  4705.2  413.53  4724.0  409.88  4732.2  408.73  4732.7  407.93
  4738.6  407.93  4739.1  408.73  4894.1  408.73  5075.5  408.73  5082.4  408.73
  5190.4  408.97  5204.8  411.34  5210.5  410.97  5226.5  413.94  5232.7  413.80
  5248.2  416.82  5291.7  418.23  5305.2  420.20  5356.9  424.83  5465.3  429.40
#Mann=11,-1,0
  4479.8    0.05       0  4606.9    0.16       0  4705.2    0.05       0
  4724.0    0.16       0  4732.2   0.035       0  4739.1    0.16       0
  4894.1    0.05       0  5075.5    0.16       0  5082.4    0.05       0
  5190.4    0.08       0  5305.2    0.16       0
Bank Sta=4688.2,5232.7
Exp/Cntr=0.3,0.1

Type RM Length L Ch R = 1,3653,75,75,75
BEGIN DESCRIPTION:
XS4049A
END DESCRIPTION:
XS GIS Cut Line= 4
      2818443.84      7025637.08      2818763.32      7025439.14
      2818971.65      7025324.55      2819318.86      7025112.76
#Sta/Elev= 30
  4481.6  428.59  4571.1  424.82  4642.2  419.49  4675.3  412.66  4681.0  411.69
  4685.5  413.22  4694.7  410.16  4720.1  409.50  4720.6  408.70  4727.0  409.50
  4760.1  416.45  4795.5  416.39  4984.7  416.06  5034.5  415.92  5125.8  415.90
  5141.2  413.89  5150.5  415.09  5162.5  415.89  5178.0  413.46  5183.9  415.35
  5199.9  412.66  5205.2  414.86  5214.8  413.58  5241.9  417.64  5268.2  419.13
  5309.6  419.39  5367.7  422.75  5373.6  424.76  5389.0  423.83  5501.9  430.21
#Mann=10,-1,0
  4481.6    0.05       0  4642.2    0.16       0  4685.5    0.05       0
  4720.1   0.035       0  4727.0    0.05       0  4795.5    0.16       0
  4984.7    0.05       0  5034.5    0.16       0  5150.5    0.08       0
  5268.2    0.16       0
Bank Sta=4675.3,5199.9
Exp/Cntr=0.3,0.1

Type RM Length L Ch R = 1,3578,343,343,343
BEGIN DESCRIPTION:
XS4050A
END DESCRIPTION:
XS GIS Cut Line= 3
      2818516.81      7025689.12      2818926.52      7025435.67
      2819321.20      7025176.01
#Sta/Elev= 30
  4512.5  426.72  4560.6  425.60  4627.8  421.12  4675.0  418.94  4696.8  414.82
  4710.3  408.19  4715.9  401.63  4720.5  399.21  4721.0  398.41  4727.4  399.21
  4733.4  399.83  4739.7  406.45  4746.0  409.21  4775.9  410.10  4812.6  400.86
  4827.9  399.21  4855.1  400.69  4870.5  399.21  4982.4  399.46  5037.7  399.22
  5043.6  400.85  5073.8  399.37  5079.8  402.29  5093.8  399.55  5102.6  401.10
  5126.1  401.63  5146.1  402.22  5188.2  408.94  5223.0  410.58  5466.7  427.81
#Mann=11,-1,0
  4512.5    0.12       0  4560.6    0.05       0  4627.8    0.16       0
  4720.5   0.035       0  4727.4    0.16       0  4739.7    0.05       0
  4746.0    0.16       0  4982.4    0.05       0  5093.8    0.16       0
  5102.6    0.08       0  5223.0    0.16       0
Bank Sta=4715.9,5126.1
Exp/Cntr=0.3,0.1

Type RM Length L Ch R = 1,3235,527,527,527
BEGIN DESCRIPTION:
UNT 176 in LFCCL Watershed 6.0
END DESCRIPTION:
XS GIS Cut Line= 3
      2818725.03      7025774.99      2819175.00      7025675.00
      2819425.02      7025174.96
#Sta/Elev= 30
  4532.3  426.42  4551.5  426.09  4563.0  424.82  4593.7  422.95  4614.2  420.91
  4643.7  419.06  4675.7  415.67  4692.3  413.39  4747.4  407.87  4808.9  403.99
  4819.1  403.73  4823.3  403.00  4837.7  400.96  4849.8  399.22  4856.6  399.21
  4857.1  398.41  4863.0  398.41  4863.5  399.21  5132.4  399.21  5194.5  399.21
  5205.8  400.65  5208.0  400.96  5253.2  404.77  5270.0  406.64  5297.9  408.37
  5337.0  412.56  5432.1  419.18  5454.4  421.19  5485.2  424.87  5552.3  430.65
#Mann=6,-1,0
  4532.3    0.16       0  4823.3    0.05       0  4856.6   0.033       0
  4863.5    0.05       0  5132.4    0.07       0  5205.8    0.16       0
Bank Sta=4837.7,5208
Exp/Cntr=0.3,0.1

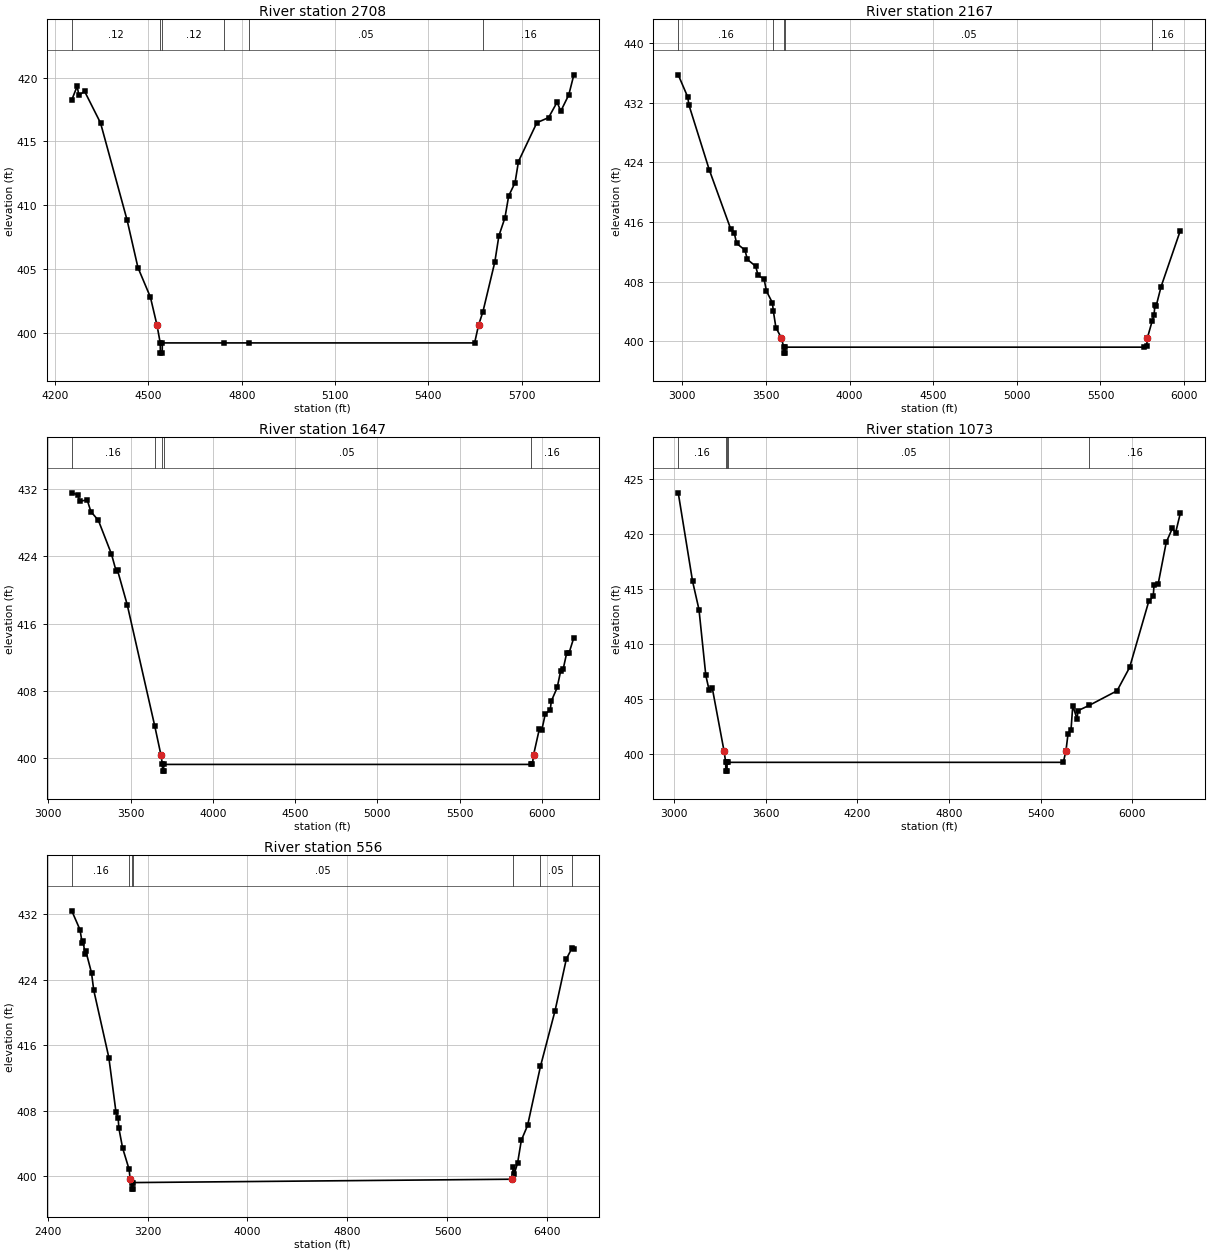
Type RM Length L Ch R = 1,2708,541,541,541
BEGIN DESCRIPTION:
UNT 176 in LFCCL Watershed 5.0
END DESCRIPTION:
XS GIS Cut Line= 3
      2818725.00      7025925.00      2819475.00      7026125.00
      2819725.01      7025324.96
#Sta/Elev= 30
  4253.3  418.25  4270.8  419.32  4275.9  418.62  4294.7  418.91  4345.8  416.44
  4431.2  408.83  4466.1  405.11  4506.2  402.79  4527.4  400.59  4537.7  399.21
  4538.2  398.41  4544.1  398.41  4544.6  399.21  4744.1  399.21  4824.2  399.21
  5548.6  399.21  5561.2  400.59  5575.5  401.67  5613.6  405.55  5626.7  407.60
  5646.1  409.01  5658.1  410.72  5678.6  411.76  5689.6  413.42  5748.8  416.46
  5786.5  416.86  5813.7  418.06  5825.8  417.37  5851.4  418.64  5867.7  420.21
#Mann=6,-1,0
  4253.3    0.12       0  4537.7   0.033       0  4544.6    0.12       0
  4744.1    0.07       0  4824.2    0.05       0  5575.5    0.16       0
Bank Sta=4527.4,5561.2
Exp/Cntr=0.3,0.1

Type RM Length L Ch R = 1,2167,520,520,520
BEGIN DESCRIPTION:
double UNT 176 in LFCCL Watershed 4.0
END DESCRIPTION:
XS GIS Cut Line= 3
      2818025.01      7027875.00      2819625.00      7026625.00
      2820424.99      7026075.01
#Sta/Elev= 30
  2976.2  435.73  3033.2  432.74  3039.6  431.72  3161.6  423.00  3290.0  415.05
  3310.8  414.55  3325.3  413.12  3375.0  412.23  3389.5  410.97  3439.2  410.06
  3453.7  408.82  3489.0  408.38  3503.5  406.73  3538.7  405.18  3545.1  404.00
  3559.9  401.84  3592.1  400.47  3606.9  399.21  3607.5  398.41  3613.9  398.41
  3614.5  399.21  5760.9  399.21  5775.8  399.35  5780.9  400.47  5808.7  402.68
  5819.7  403.48  5826.5  404.92  5832.6  404.70  5862.4  407.32  5977.4  414.84
#Mann=5,-1,0
  2976.2    0.16       0  3545.1    0.05       0  3606.9   0.033       0
  3614.5    0.05       0  5808.7    0.16       0
Bank Sta=3592.1,5780.9
Exp/Cntr=0.3,0.1

Type RM Length L Ch R = 1,1647,574,574,574
BEGIN DESCRIPTION:
double UNT 176 in LFCCL Watershed 3.0
END DESCRIPTION:
XS GIS Cut Line= 3
      2818175.04      7028074.98      2819775.00      7027125.00
      2820424.99      7026125.01
#Sta/Elev= 30
  3142.0  431.58  3177.0  431.35  3192.6  430.57  3235.5  430.75  3258.3  429.34
  3303.7  428.30  3383.6  424.27  3410.8  422.32  3420.6  422.33  3479.1  418.25
  3646.5  403.80  3683.7  400.39  3693.4  399.21  3694.1  398.41  3700.5  398.41
  3701.1  399.21  5932.7  399.21  5943.3  399.21  5950.9  400.39  5985.6  403.43
  6000.7  403.32  6021.8  405.24  6052.1  405.70  6058.0  406.74  6094.3  408.38
  6115.4  410.37  6130.5  410.57  6151.6  412.46  6166.7  412.53  6195.4  414.32
#Mann=5,-1,0
  3142.0    0.16       0  3646.5    0.05       0  3693.4   0.033       0
  3701.1    0.05       0  5932.7    0.16       0
Bank Sta=3683.7,5950.9
Exp/Cntr=0.3,0.1

Type RM Length L Ch R = 1,1073,517,517,517
BEGIN DESCRIPTION:
UNT 176 in LFCCL Watershed 2.0
END DESCRIPTION:
XS GIS Cut Line= 3
      2818575.03      7028624.98      2820175.00      7027525.00
      2820525.00      7026225.00
#Sta/Elev= 30
  3027.6  423.73  3121.6  415.67  3163.5  413.11  3208.2  407.12  3229.2  405.82
  3250.1  406.00  3327.8  400.22  3338.4  399.21  3339.3  398.41  3346.9  398.41
  3347.8  399.21  3356.4  399.21  5549.1  399.21  5566.2  400.22  5580.2  401.80
  5599.8  402.18  5611.3  404.37  5639.8  403.12  5644.9  403.91  5720.1  404.40
  5901.3  405.72  5983.7  407.85  6108.7  413.85  6138.3  414.32  6143.5  415.38
  6170.5  415.44  6223.4  419.23  6263.7  420.51  6284.4  420.08  6315.5  421.87
#Mann=5,-1,0
  3027.6    0.16       0  3338.4   0.033       0  3347.8    0.16       0
  3356.4    0.05       0  5720.1    0.16       0
Bank Sta=3327.8,5566.2
Exp/Cntr=0.3,0.1

Type RM Length L Ch R = 1,556,0,0,0
BEGIN DESCRIPTION:
UNT 176 in LFCCL Watershed 1.0
END DESCRIPTION:
XS GIS Cut Line= 3
      2818424.96      7028775.02      2820625.00      7027775.00
      2820675.00      7026175.03
#Sta/Elev= 30
  2593.9  432.41  2659.8  430.10  2677.4  428.47  2682.9  428.76  2700.5  427.19
  2706.0  427.51  2752.1  424.82  2769.7  422.71  2890.5  414.49  2947.6  407.82
  2965.2  407.08  2970.7  405.86  3000.4  403.45  3052.6  400.83  3061.1  399.62
  3072.6  399.21  3073.5  398.41  3081.1  398.41  3082.0  399.21  6114.8  399.62
  6127.3  401.12  6133.6  400.24  6161.1  401.58  6191.1  404.38  6241.1  406.19
  6344.0  413.40  6461.3  420.23  6551.3  426.53  6597.6  427.89  6611.3  427.77
#Mann=7,-1,0
  2593.9    0.16       0  3052.6    0.05       0  3072.6   0.033       0
  3082.0    0.05       0  6127.3    0.16       0  6344.0    0.05       0
  6597.6    0.16       0
Bank Sta=3061.1,6114.8
Exp/Cntr=0.3,0.1

Chan Stop Cuts=-1