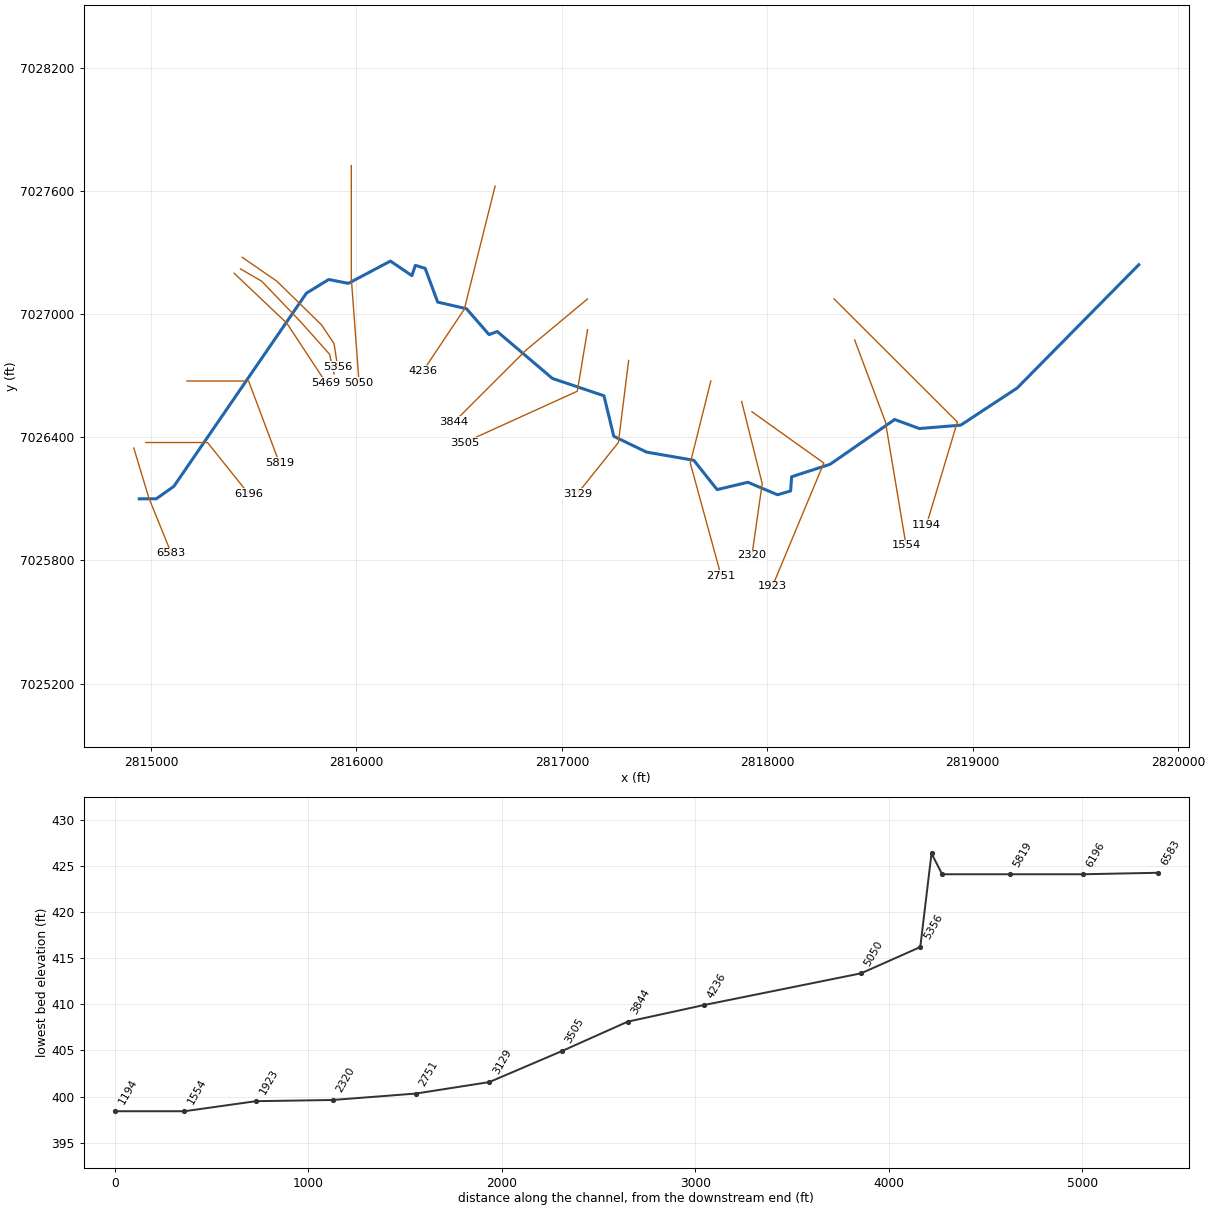
--- UNT 177 in LFCCL Watershed.prj (project) ---

Proj Title=UNT 177 in LFCCL Watershed Base Level Engineering
Current Plan=p01
Default Exp/Contr=0.3,0.1
English Units
Geom File=g01
Flow File=f01
Plan File=p01
BEGIN DESCRIPTION:
UNT 177 in LFCCL Watershed
END DESCRIPTION:

--- UNT 177 in LFCCL Watershed.p01 (plan) ---

Plan Title=Multiple Run
Short Identifier=Multiple
Geom File=g01
Flow File=f01
Subcritical Flow
K Sum by GR= 0
Std Step Tol= 0.01
Critical Tol= 0.01
Num of Std Step Trials= 20
Max Error Tol= 0.3
Flow Tol Ratio= 0.001
Split Flow NTrial= 30
Split Flow Tol= 0.02
Split Flow Ratio= 0.02
Log Output Level= 0
Friction Slope Method= 1
Unsteady Friction Slope Method= 2
Unsteady Bridges Friction Slope Method= 1
Parabolic Critical Depth
Global Vel Dist=  1 , 1 , 1
Global Log Level= 0
CheckData=True
Encroach Param= -1, 0, 0, 0
BEGIN DESCRIPTION:
Multiple Run
END DESCRIPTION:

--- UNT 177 in LFCCL Watershed.f01 (steady flow) ---

Flow Title=Multiple
Number of Profiles=7
Profile Names=10-year,25-year,50-year,1pct_min,100-year,1pct_plu,500-year
River Rch & RM= UNT 177 in LFCCL,Reach-1,6583
     450     594     709     421     840    1677    1183
River Rch & RM= UNT 177 in LFCCL,Reach-1,1554
     565     754     907     543    1083    2161    1546
Boundary for River Rch & Prof#=UNT 177 in LFCCL,Reach-1,1
Up Type=0
Dn Type=3
Dn Slope=0.005
Boundary for River Rch & Prof#=UNT 177 in LFCCL,Reach-1,2
Up Type=0
Dn Type=3
Dn Slope=0.005
Boundary for River Rch & Prof#=UNT 177 in LFCCL,Reach-1,3
Up Type=0
Dn Type=3
Dn Slope=0.005
Boundary for River Rch & Prof#=UNT 177 in LFCCL,Reach-1,4
Up Type=0
Dn Type=3
Dn Slope=0.005
Boundary for River Rch & Prof#=UNT 177 in LFCCL,Reach-1,5
Up Type=0
Dn Type=3
Dn Slope=0.005
Boundary for River Rch & Prof#=UNT 177 in LFCCL,Reach-1,6
Up Type=0
Dn Type=3
Dn Slope=0.005
Boundary for River Rch & Prof#=UNT 177 in LFCCL,Reach-1,7
Up Type=0
Dn Type=3
Dn Slope=0.005

--- UNT 177 in LFCCL Watershed.g01 (geometry) ---

Geom Title=Existing Conditions

River Reach=UNT 177 in LFCCL,Reach-1
Reach XY= 30
      2814942.90      7026100.43      2815025.59      7026100.71
      2815111.25      7026161.43      2815756.30      7027102.91
      2815864.85      7027169.71      2815960.88      7027150.93
      2816165.46      7027259.48      2816269.84      7027188.50
      2816286.54      7027238.60      2816334.55      7027223.99
      2816395.38      7027059.61      2816535.72      7027027.04
      2816645.36      7026901.11      2816685.45      7026916.14
      2816953.60      7026687.47      2817204.83      7026602.89
      2817252.44      7026405.54      2817411.58      7026328.48
      2817642.13      7026288.38      2817755.53      7026145.54
      2817905.26      7026181.25      2818049.36      7026120.48
      2818113.27      7026138.65      2818118.28      7026208.19
      2818305.60      7026268.96      2818619.88      7026487.24
      2818739.87      7026443.17      2818941.25      7026459.64
      2819215.85      7026640.44      2819808.07      7027241.63

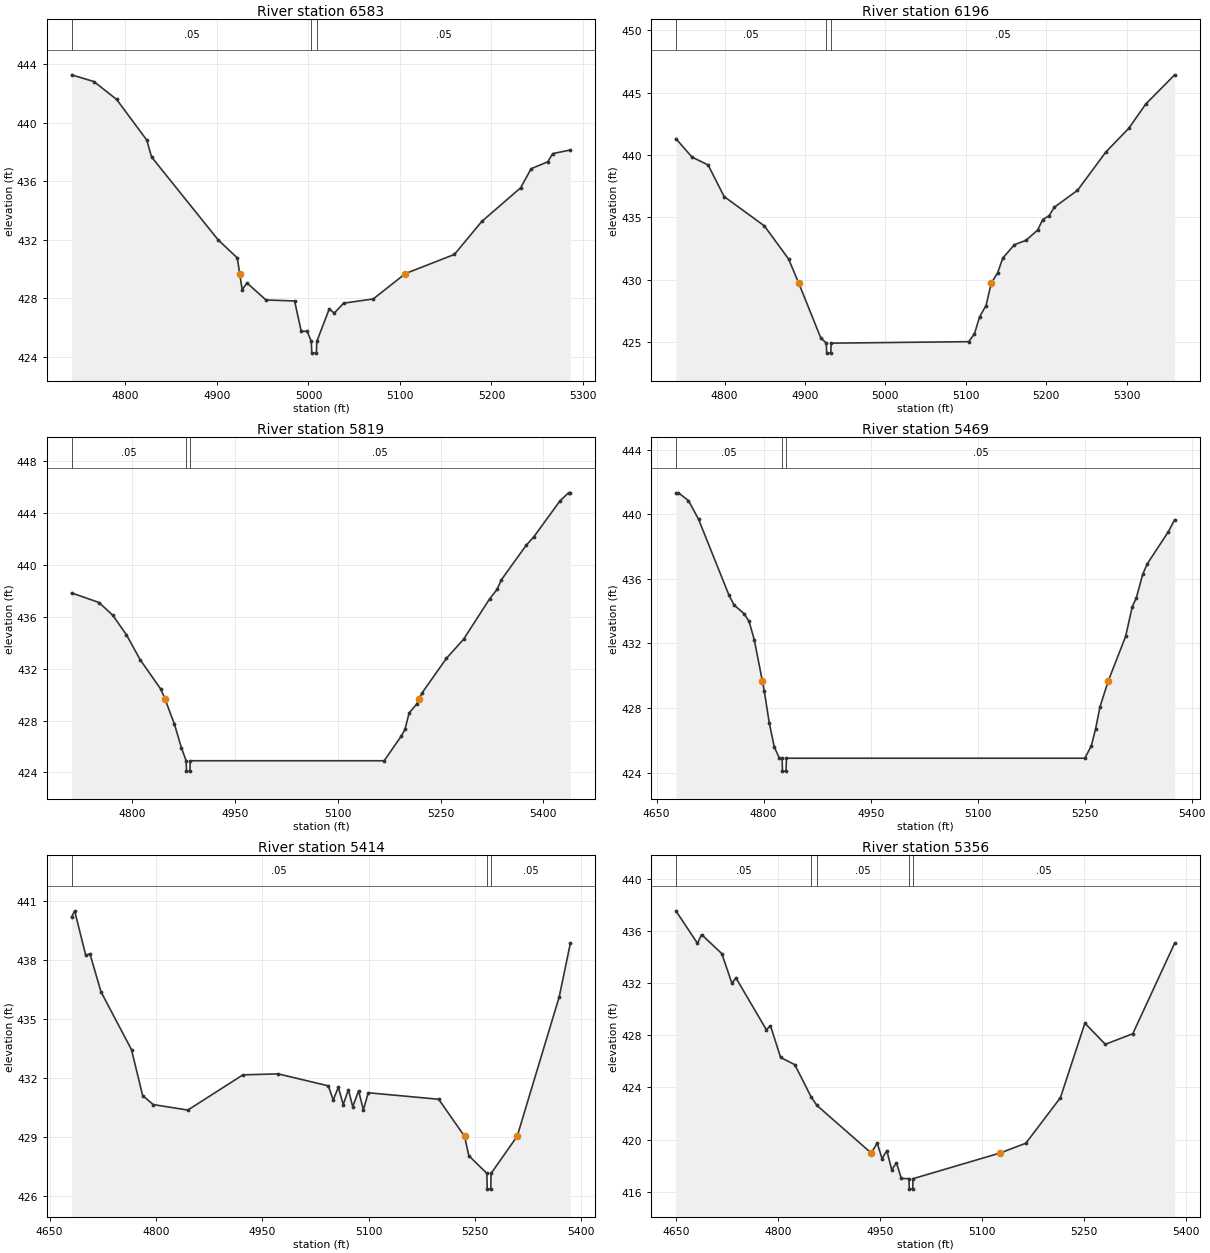
Type RM Length L Ch R = 1,6583,387,387,387
BEGIN DESCRIPTION:
UNT 177 in LFCCL Watershed 15.0
END DESCRIPTION:
XS GIS Cut Line= 3
      2814916.20      7026348.37      2814989.13      7026106.14
      2815098.52      7025835.26
#Sta/Elev= 30
  4741.1  443.26  4765.5  442.80  4790.3  441.58  4823.3  438.80  4828.5  437.65
  4901.3  431.99  4922.2  430.76  4924.8  429.69  4927.5  428.59  4932.8  429.05
  4953.5  427.89  4984.8  427.82  4992.1  425.75  4998.5  425.75  5003.1  425.06
  5003.6  424.26  5008.6  424.26  5009.1  425.06  5022.7  427.28  5028.1  426.99
  5038.4  427.67  5070.8  427.96  5105.9  429.69  5159.5  431.00  5189.4  433.25
  5231.9  435.55  5243.3  436.85  5261.5  437.32  5266.9  437.88  5286.2  438.13
#Mann=3,-1,0
  4741.1    0.05       0  5003.1    0.03       0  5009.1    0.05       0
Bank Sta=4924.8,5105.9
Exp/Cntr=0.3,0.1

Type RM Length L Ch R = 1,6196,377,377,377
BEGIN DESCRIPTION:
UNT 177 in LFCCL Watershed 14.0
END DESCRIPTION:
XS GIS Cut Line= 3
      2814975.01      7026375.00      2815275.00      7026375.00
      2815474.97      7026125.04
#Sta/Elev= 30
  4739.5  441.31  4759.5  439.83  4779.5  439.20  4799.5  436.66  4849.5  434.31
  4879.5  431.66  4892.4  429.69  4919.5  425.34  4926.5  424.90  4927.0  424.10
  4932.0  424.10  4932.5  424.90  5103.5  425.02  5110.7  425.65  5117.1  427.02
  5125.1  427.92  5131.5  429.70  5139.5  430.54  5145.9  431.72  5160.3  432.80
  5174.8  433.15  5189.2  433.97  5195.6  434.82  5203.6  435.13  5210.0  435.81
  5238.8  437.16  5274.0  440.23  5302.8  442.16  5323.6  444.08  5359.6  446.43
#Mann=3,-1,0
  4739.5    0.05       0  4926.5   0.033       0  4932.5    0.05       0
Bank Sta=4892.4,5131.5
Exp/Cntr=0.3,0.1

Type RM Length L Ch R = 1,5819,350,350,350
BEGIN DESCRIPTION:
UNT 177 in LFCCL Watershed 13.0
END DESCRIPTION:
XS GIS Cut Line= 3
      2815175.01      7026675.00      2815475.00      7026675.00
      2815625.00      7026274.99
#Sta/Elev= 30
  4712.1  437.83  4752.1  437.09  4772.1  436.11  4792.1  434.60  4812.1  432.68
  4842.1  430.42  4848.1  429.68  4862.1  427.71  4872.1  425.92  4879.1  424.90
  4879.6  424.10  4884.6  424.10  4885.1  424.90  5167.8  424.90  5192.8  426.80
  5198.1  427.31  5204.3  428.59  5215.0  429.25  5219.0  429.68  5223.0  430.12
  5258.6  432.79  5283.5  434.25  5321.8  437.39  5332.5  438.10  5338.7  438.84
  5375.2  441.52  5385.9  442.14  5424.2  444.92  5436.6  445.54  5439.3  445.54
#Mann=3,-1,0
  4712.1    0.05       0  4879.1   0.033       0  4885.1    0.05       0
Bank Sta=4848.1,5219
Exp/Cntr=0.3,0.1

Type RM Length L Ch R = 1,5469,55,55,55
BEGIN DESCRIPTION:
XS4051A
END DESCRIPTION:
XS GIS Cut Line= 3
      2815404.90      7027199.92      2815661.01      7026956.83
      2815850.99      7026667.55
#Sta/Elev= 30
  4677.0  441.32  4680.5  441.32  4694.6  440.84  4708.8  439.68  4751.2  435.01
  4758.5  434.38  4772.7  433.84  4779.6  433.36  4786.8  432.24  4798.2  429.68
  4801.0  429.03  4807.9  427.08  4815.0  425.58  4822.0  424.91  4825.9  424.90
  4826.4  424.10  4831.4  424.10  4831.9  424.90  5250.3  424.90  5259.4  425.67
  5265.3  426.70  5271.6  428.09  5283.1  429.68  5307.5  432.44  5316.6  434.25
  5322.6  434.84  5331.4  436.28  5337.7  436.92  5367.3  438.91  5376.2  439.66
#Mann=3,-1,0
  4677.0    0.05       0  4825.9    0.03       0  4831.9    0.05       0
Bank Sta=4798.2,5283.1
Exp/Cntr=0.3,0.1

Type RM Length L Ch R = 1,5414,58,58,58
BEGIN DESCRIPTION:
XS4052A
END DESCRIPTION:
XS GIS Cut Line= 5
      2815435.29      7027221.61      2815539.48      7027160.83
      2815730.45      7026961.17      2815869.34      7026804.92
      2815890.98      7026709.71
#Sta/Elev= 30
  4681.1  440.20  4685.4  440.51  4701.1  438.24  4706.9  438.33  4722.6  436.39
  4765.6  433.45  4781.3  431.12  4796.2  430.66  4845.1  430.38  4922.8  432.17
  4972.5  432.22  5043.3  431.61  5050.2  430.89  5057.4  431.54  5064.3  430.66
  5071.6  431.42  5077.7  430.55  5086.0  431.36  5092.7  430.39  5099.6  431.26
  5198.9  430.93  5235.4  429.05  5241.5  428.06  5266.9  427.16  5267.4  426.36
  5272.4  426.36  5272.9  427.16  5309.7  429.05  5369.0  436.14  5384.7  438.86
#Mann=3,-1,0
  4681.1    0.05       0  5266.9    0.03       0  5272.9    0.05       0
Bank Sta=5235.4,5309.7
Exp/Cntr=0.3,0.1

Type RM Length L Ch R = 1,5356,306,306,306
BEGIN DESCRIPTION:
XS4053A
END DESCRIPTION:
XS GIS Cut Line= 5
      2815443.97      7027278.03      2815613.26      7027160.83
      2815830.28      7026948.15      2815891.04      7026857.01
      2815908.41      7026744.14
#Sta/Elev= 30
  4650.0  437.54  4681.7  435.05  4687.8  435.72  4717.5  434.26  4732.3  432.00
  4738.4  432.39  4783.0  428.43  4789.1  428.73  4804.0  426.30  4824.9  425.75
  4848.7  423.29  4857.3  422.63  4937.2  418.98  4946.1  419.74  4953.2  418.54
  4960.2  419.16  4967.4  417.69  4974.4  418.22  4981.5  417.03  4992.7  417.01
  4993.2  416.21  4998.2  416.21  4998.7  417.01  5126.8  418.98  5164.7  419.73
  5215.5  423.22  5251.5  428.93  5281.5  427.31  5321.9  428.12  5383.5  435.06
#Mann=5,-1,0
  4650.0    0.05       0  4848.7    0.12       0  4857.3    0.05       0
  4992.7    0.03       0  4998.7    0.05       0
Bank Sta=4937.2,5126.8
Exp/Cntr=0.3,0.1

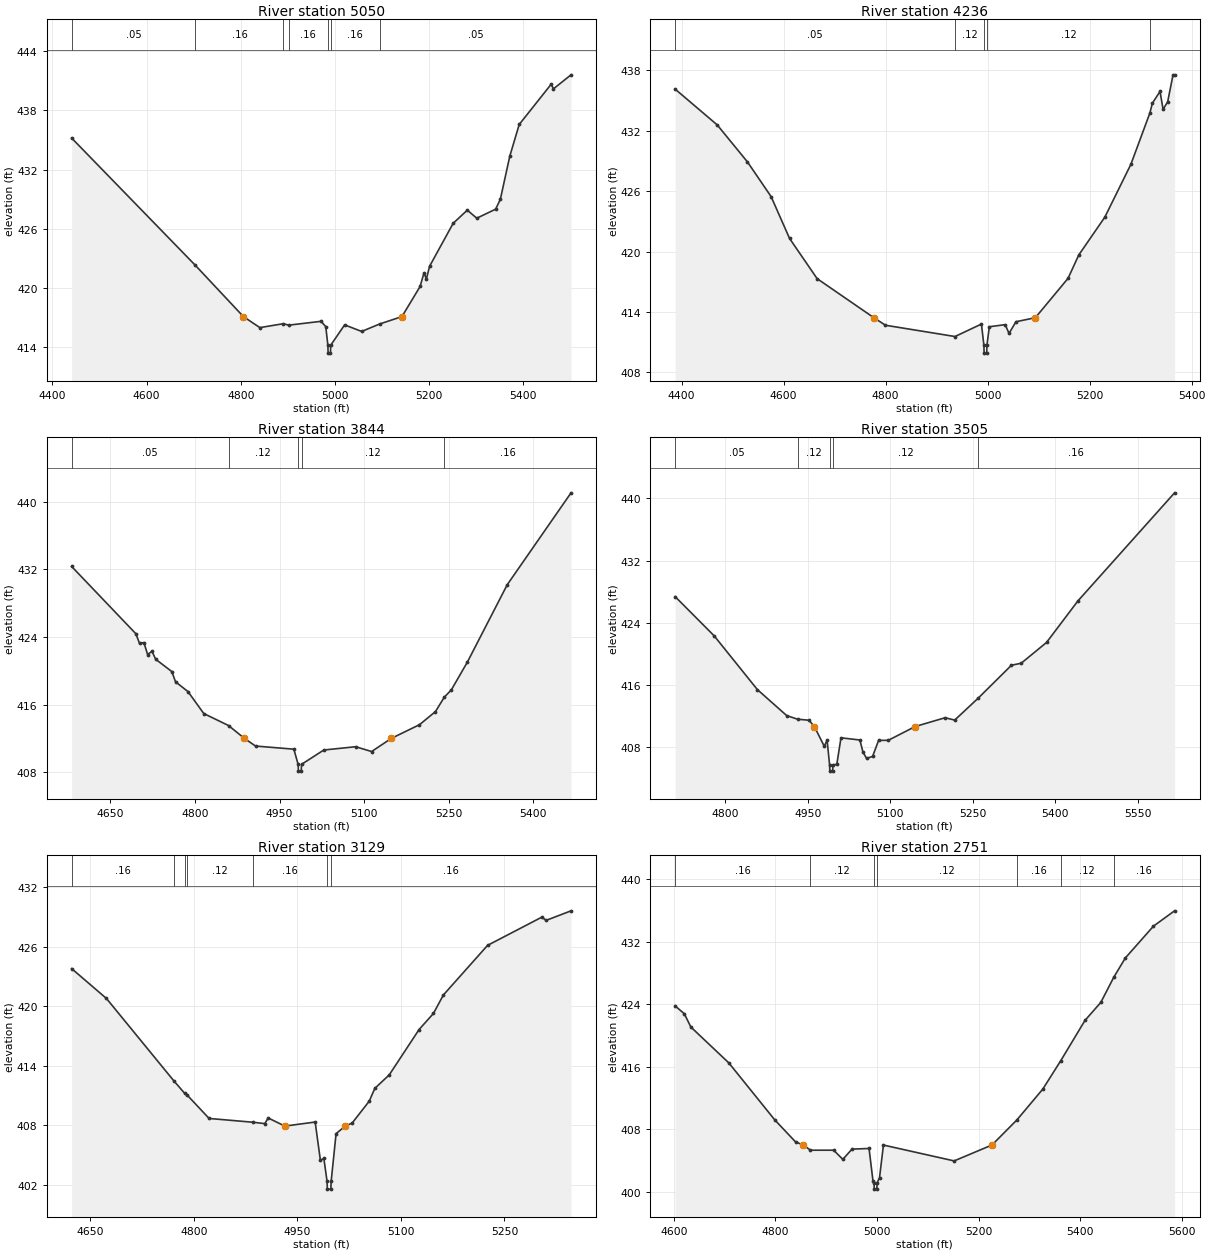
Type RM Length L Ch R = 1,5050,814,814,814
BEGIN DESCRIPTION:
UNT 177 in LFCCL Watershed 11.0
END DESCRIPTION:
XS GIS Cut Line= 3
      2815975.00      7027725.01      2815975.00      7027175.00
      2816012.95      7026665.22
#Sta/Elev= 30
  4440.7  435.20  4703.9  422.26  4805.7  417.07  4840.7  415.95  4890.6  416.35
  4901.9  416.20  4970.7  416.59  4980.7  416.05  4985.2  414.16  4985.7  413.36
  4990.7  413.36  4991.2  414.16  5020.8  416.23  5057.0  415.56  5095.3  416.32
  5142.6  417.07  5181.2  420.13  5189.5  421.52  5194.5  420.88  5201.3  422.18
  5251.4  426.54  5281.5  427.88  5301.6  427.06  5341.7  427.98  5351.7  428.98
  5371.8  433.37  5391.8  436.58  5459.6  440.66  5464.6  440.20  5501.9  441.62
#Mann=7,-1,0
  4440.7    0.05       0  4703.9    0.16       0  4890.6    0.12       0
  4901.9    0.16       0  4985.2    0.07       0  4991.2    0.16       0
  5095.3    0.05       0
Bank Sta=4805.7,5142.6
Exp/Cntr=0.3,0.1

Type RM Length L Ch R = 1,4236,392,392,392
BEGIN DESCRIPTION:
UNT 177 in LFCCL Watershed 9.0
END DESCRIPTION:
XS GIS Cut Line= 3
      2816675.00      7027625.01      2816525.00      7027025.00
      2816325.02      7026725.03
#Sta/Elev= 30
  4387.5  436.14  4470.0  432.58  4529.2  428.91  4575.6  425.46  4611.7  421.31
  4665.8  417.31  4777.0  413.43  4799.8  412.68  4936.1  411.56  4987.9  412.80
  4992.7  410.71  4993.2  409.91  4998.2  409.91  4998.7  410.71  5003.4  412.53
  5034.5  412.74  5042.0  411.87  5055.6  413.03  5093.6  413.43  5157.7  417.34
  5178.7  419.66  5229.8  423.42  5280.9  428.67  5318.2  433.78  5323.0  434.74
  5338.0  435.91  5344.0  434.13  5353.0  434.88  5363.5  437.56  5366.5  437.56
#Mann=5,-1,0
  4387.5    0.05       0  4936.1    0.12       0  4992.7    0.07       0
  4998.7    0.12       0  5318.2    0.16       0
Bank Sta=4777,5093.6
Exp/Cntr=0.3,0.1

Type RM Length L Ch R = 1,3844,339,339,339
BEGIN DESCRIPTION:
UNT 177 in LFCCL Watershed 8.0
END DESCRIPTION:
XS GIS Cut Line= 3
      2817124.99      7027074.99      2816825.00      7026825.00
      2816474.98      7026474.98
#Sta/Elev= 30
  4581.4  432.36  4695.3  424.39  4701.8  423.24  4709.6  423.34  4716.1  421.93
  4723.9  422.31  4730.4  421.37  4759.1  419.91  4765.6  418.70  4787.7  417.54
  4815.7  414.94  4859.6  413.52  4887.9  411.99  4907.5  411.09  4975.4  410.72
  4983.0  408.92  4983.5  408.12  4988.5  408.12  4989.0  408.92  5028.5  410.62
  5085.0  411.01  5113.3  410.44  5148.1  411.99  5198.2  413.62  5226.5  415.17
  5242.2  416.88  5254.7  417.75  5283.0  421.02  5353.7  430.19  5466.9  441.08
#Mann=5,-1,0
  4581.4    0.05       0  4859.6    0.12       0  4983.0    0.07       0
  4989.0    0.12       0  5242.2    0.16       0
Bank Sta=4887.9,5148.1
Exp/Cntr=0.3,0.1

Type RM Length L Ch R = 1,3505,376,376,376
BEGIN DESCRIPTION:
UNT 177 in LFCCL Watershed 7.0
END DESCRIPTION:
XS GIS Cut Line= 3
      2817125.00      7026925.00      2817075.00      7026625.00
      2816524.99      7026375.00
#Sta/Elev= 30
  4708.6  427.36  4779.6  422.32  4858.1  415.42  4911.4  412.08  4931.2  411.61
  4951.9  411.48  4961.8  410.67  4979.8  408.13  4984.9  408.92  4989.5  405.74
  4990.0  404.94  4995.0  404.94  4995.5  405.74  5002.6  405.81  5010.2  409.22
  5044.6  408.94  5050.1  407.40  5056.7  406.58  5067.7  406.83  5078.6  408.89
  5096.2  408.90  5145.1  410.67  5199.5  411.80  5217.1  411.50  5259.5  414.30
  5320.3  418.55  5337.9  418.80  5384.0  421.47  5441.1  426.81  5616.9  440.70
#Mann=5,-1,0
  4708.6    0.05       0  4931.2    0.12       0  4989.5    0.07       0
  4995.5    0.12       0  5259.5    0.16       0
Bank Sta=4961.8,5145.1
Exp/Cntr=0.3,0.1

Type RM Length L Ch R = 1,3129,378,378,378
BEGIN DESCRIPTION:
UNT 177 in LFCCL Watershed 6.0
END DESCRIPTION:
XS GIS Cut Line= 3
      2817325.00      7026775.02      2817275.00      7026375.00
      2817074.99      7026124.99
#Sta/Elev= 30
  4623.1  423.79  4673.5  420.78  4771.0  412.49  4786.7  411.23  4790.5  411.04
  4822.2  408.69  4885.6  408.31  4902.8  408.17  4907.8  408.74  4931.9  407.92
  4975.8  408.33  4983.4  404.47  4988.4  404.67  4993.0  402.37  4993.5  401.57
  4998.5  401.57  4999.0  402.37  5006.1  407.16  5019.3  407.92  5029.4  408.23
  5054.2  410.44  5062.2  411.72  5083.1  413.08  5126.3  417.65  5147.1  419.27
  5161.5  421.13  5225.5  426.13  5304.0  428.97  5310.4  428.65  5346.4  429.61
#Mann=7,-1,0
  4623.1    0.16       0  4771.0    0.05       0  4786.7    0.16       0
  4790.5    0.12       0  4885.6    0.16       0  4993.0    0.07       0
  4999.0    0.16       0
Bank Sta=4931.9,5019.3
Exp/Cntr=0.3,0.1

Type RM Length L Ch R = 1,2751,431,431,431
BEGIN DESCRIPTION:
UNT 177 in LFCCL Watershed 5.0
END DESCRIPTION:
XS GIS Cut Line= 3
      2817724.99      7026674.97      2817625.00      7026275.00
      2817775.01      7025724.97
#Sta/Elev= 30
  4602.9  423.77  4620.9  422.77  4633.8  421.07  4708.5  416.48  4798.7  409.20
  4839.9  406.36  4855.0  405.98  4869.1  405.31  4914.7  405.31  4932.7  404.14
  4950.8  405.45  4984.3  405.53  4992.0  401.40  4994.1  401.13  4994.6  400.33
  4999.6  400.33  5000.1  401.13  5004.9  401.78  5012.6  405.97  5151.7  403.94
  5226.2  405.98  5274.8  409.16  5326.1  413.13  5361.5  416.77  5409.1  421.92
  5440.2  424.22  5465.8  427.45  5488.5  429.91  5543.8  433.98  5585.3  435.94
#Mann=7,-1,0
  4602.9    0.16       0  4869.1    0.12       0  4994.1    0.07       0
  5000.1    0.12       0  5274.8    0.16       0  5361.5    0.12       0
  5465.8    0.16       0
Bank Sta=4855,5226.2
Exp/Cntr=0.3,0.1

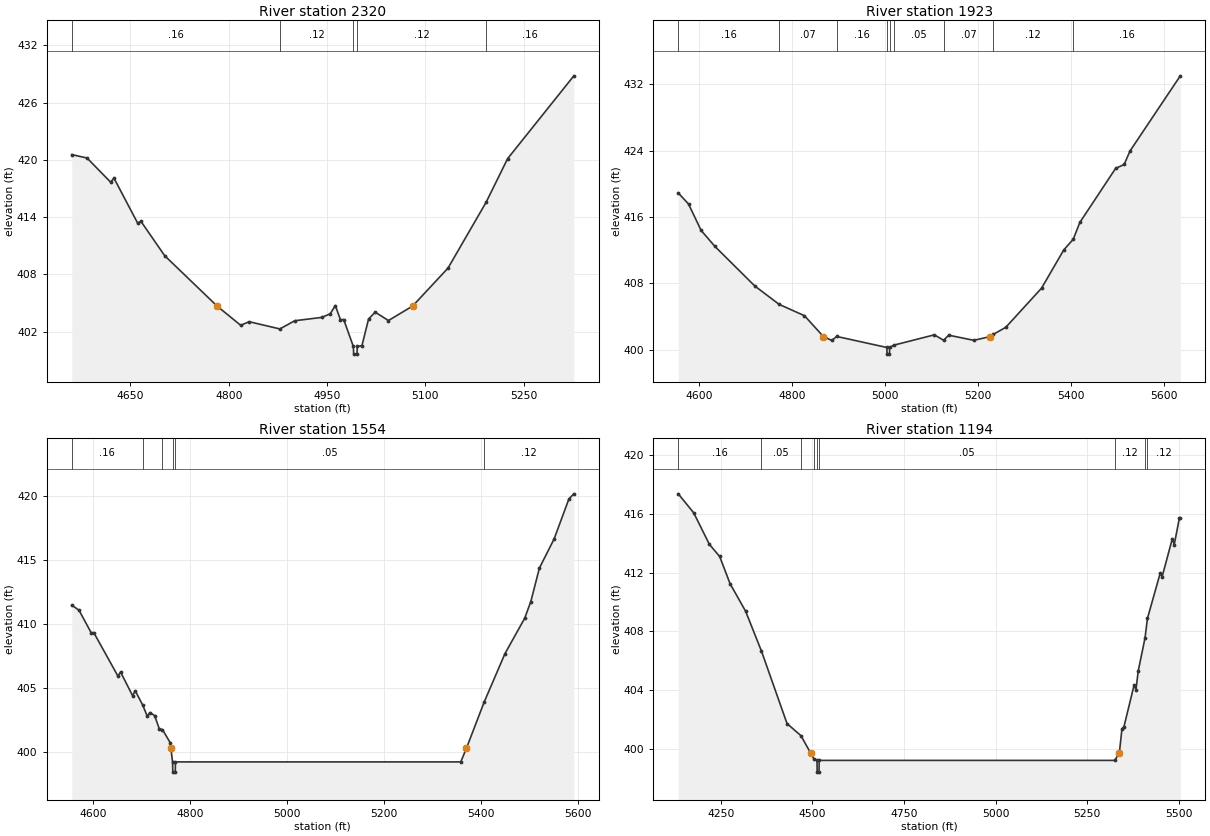
Type RM Length L Ch R = 1,2320,397,397,397
BEGIN DESCRIPTION:
UNT 177 in LFCCL Watershed 4.0
END DESCRIPTION:
XS GIS Cut Line= 3
      2817875.01      7026574.97      2817975.00      7026175.00
      2817925.00      7025825.03
#Sta/Elev= 30
  4560.6  420.54  4583.8  420.19  4619.8  417.66  4625.0  418.07  4661.1  413.36
  4666.2  413.54  4702.3  409.95  4782.2  404.67  4818.3  402.65  4831.1  403.03
  4878.0  402.27  4900.7  403.13  4942.0  403.48  4954.8  403.86  4962.6  404.72
  4970.3  403.25  4975.4  403.25  4990.1  400.43  4990.6  399.63  4995.6  399.63
  4996.1  400.43  5003.2  400.52  5013.3  403.31  5023.4  404.03  5043.6  403.15
  5080.5  404.67  5134.5  408.65  5192.6  415.55  5225.4  420.12  5326.4  428.80
#Mann=5,-1,0
  4560.6    0.16       0  4878.0    0.12       0  4990.1    0.07       0
  4996.1    0.12       0  5192.6    0.16       0
Bank Sta=4782.2,5080.5
Exp/Cntr=0.3,0.1

Type RM Length L Ch R = 1,1923,369,369,369
BEGIN DESCRIPTION:
UNT 177 in LFCCL Watershed 3.0
END DESCRIPTION:
XS GIS Cut Line= 3
      2817925.01      7026525.00      2818275.00      7026275.00
      2818025.00      7025675.01
#Sta/Elev= 30
  4554.7  418.90  4576.8  417.57  4603.8  414.40  4633.3  412.48  4719.4  407.70
  4771.7  405.49  4826.3  404.12  4866.9  401.62  4885.3  401.14  4895.4  401.63
  5003.5  400.30  5004.0  399.50  5009.0  399.50  5009.5  400.30  5018.5  400.58
  5105.6  401.82  5125.6  401.17  5136.5  401.78  5190.6  401.16  5226.2  401.62
  5232.6  401.88  5259.4  402.73  5336.3  407.44  5384.0  412.03  5404.5  413.33
  5418.7  415.35  5495.6  421.85  5514.0  422.32  5526.5  423.94  5634.8  432.99
#Mann=9,-1,0
  4554.7    0.16       0  4771.7    0.07       0  4895.4    0.16       0
  5003.5    0.07       0  5009.5    0.16       0  5018.5    0.05       0
  5125.6    0.07       0  5232.6    0.12       0  5404.5    0.16       0
Bank Sta=4866.9,5226.2
Exp/Cntr=0.3,0.1

Type RM Length L Ch R = 1,1554,360,360,360
BEGIN DESCRIPTION:
double UNT 177 in LFCCL Watershed 2.0
END DESCRIPTION:
XS GIS Cut Line= 3
      2818425.00      7026875.00      2818575.00      7026475.00
      2818675.00      7025874.97
#Sta/Elev= 30
  4555.6  411.47  4570.7  411.06  4595.6  409.31  4601.0  409.32  4650.8  405.92
  4656.2  406.24  4681.1  404.38  4686.4  404.78  4701.8  403.66  4711.3  402.78
  4716.7  403.07  4726.5  402.83  4736.3  401.77  4742.6  401.74  4758.5  400.72
  4759.9  400.29  4763.5  399.21  4764.0  398.41  4769.0  398.41  4769.5  399.21
  5357.9  399.21  5369.7  400.29  5406.4  403.91  5449.1  407.68  5489.7  410.44
  5502.4  411.75  5520.1  414.37  5550.5  416.65  5580.9  419.77  5591.1  420.17
#Mann=6,-1,0
  4555.6    0.16       0  4701.8    0.07       0  4742.6    0.05       0
  4763.5   0.033       0  4769.5    0.05       0  5406.4    0.12       0
Bank Sta=4759.9,5369.7
Exp/Cntr=0.3,0.1

Type RM Length L Ch R = 1,1194,0,0,0
BEGIN DESCRIPTION:
UNT 177 in LFCCL Watershed 1.0
END DESCRIPTION:
XS GIS Cut Line= 3
      2818324.99      7027075.01      2818925.00      7026475.00
      2818774.99      7025974.96
#Sta/Elev= 30
  4133.6  417.38  4176.0  416.08  4218.5  413.94  4246.7  413.11  4275.0  411.26
  4317.5  409.38  4360.8  406.66  4430.6  401.72  4468.8  400.89  4495.0  399.71
  4504.2  399.30  4512.4  399.21  4512.9  398.41  4517.9  398.41  4518.4  399.21
  5325.0  399.21  5337.8  399.71  5344.9  401.37  5350.2  401.49  5378.0  404.34
  5383.2  404.04  5389.3  405.30  5407.9  407.56  5414.5  408.89  5449.3  411.97
  5454.6  411.73  5482.4  414.32  5487.6  413.92  5501.5  415.70  5504.2  415.70
#Mann=9,-1,0
  4133.6    0.16       0  4360.8    0.05       0  4468.8    0.16       0
  4504.2    0.05       0  4512.4   0.033       0  4518.4    0.05       0
  5325.0    0.12       0  5407.9    0.05       0  5414.5    0.12       0
Bank Sta=4495,5337.8
Exp/Cntr=0.3,0.1

Chan Stop Cuts=-1