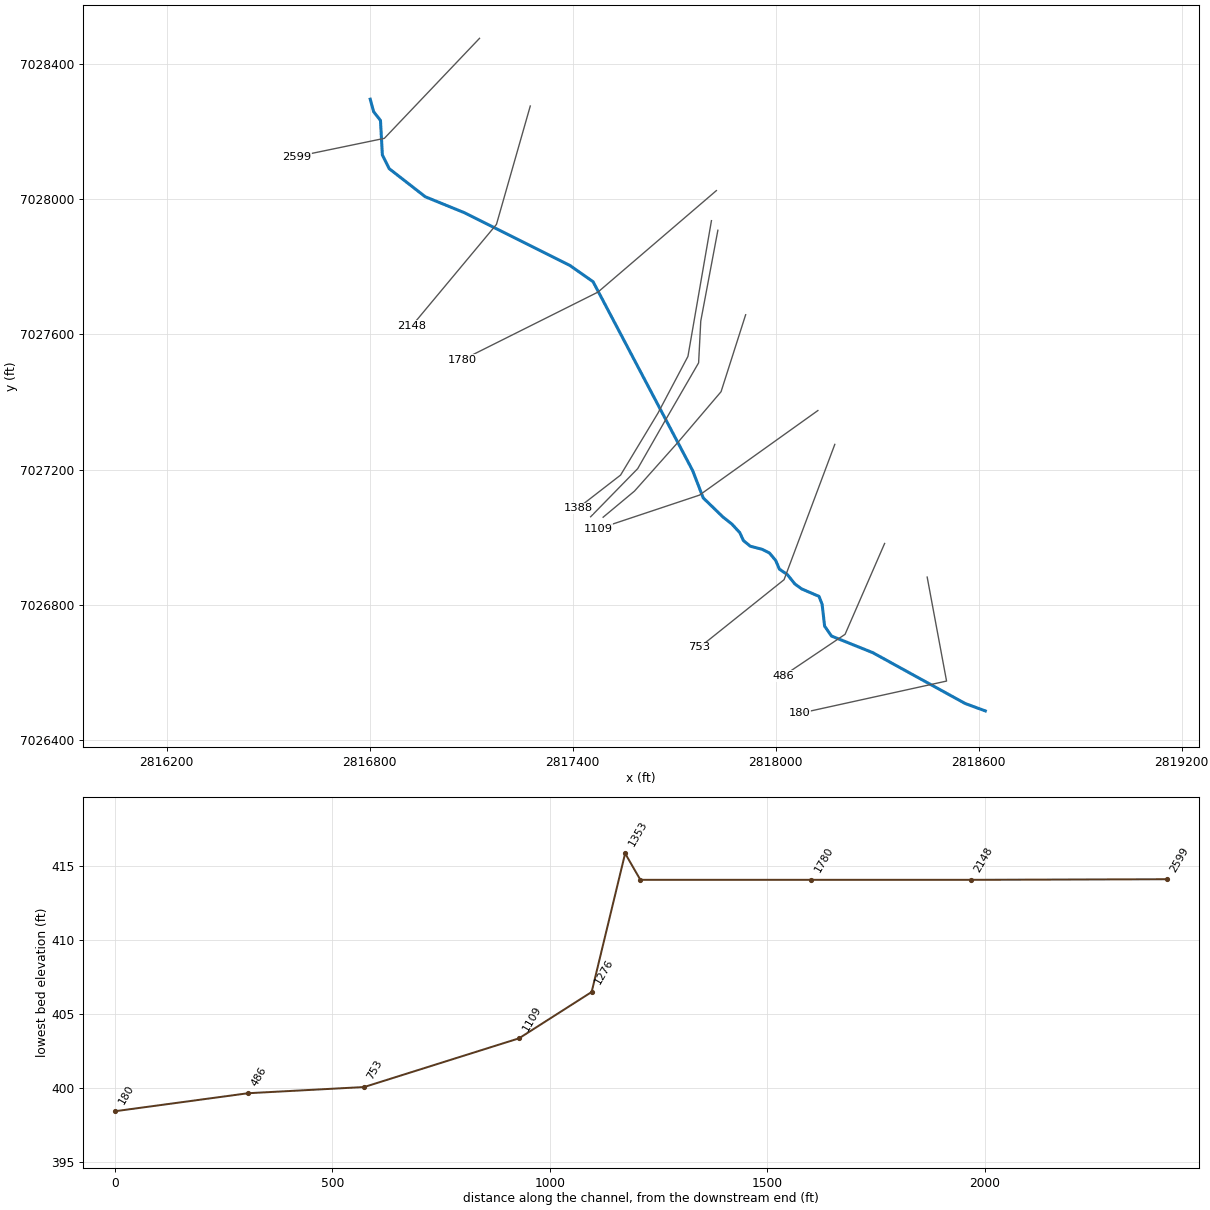
--- UNT 178 in LFCCL Watershed.prj (project) ---

Proj Title=UNT 178 in LFCCL Watershed Base Level Engineering
Current Plan=p01
Default Exp/Contr=0.3,0.1
English Units
Geom File=g01
Flow File=f01
Plan File=p01
BEGIN DESCRIPTION:
UNT 178 in LFCCL Watershed
END DESCRIPTION:

--- UNT 178 in LFCCL Watershed.p01 (plan) ---

Plan Title=Multiple Run
Short Identifier=Multiple
Geom File=g01
Flow File=f01
Subcritical Flow
K Sum by GR= 0
Std Step Tol= 0.01
Critical Tol= 0.01
Num of Std Step Trials= 20
Max Error Tol= 0.3
Flow Tol Ratio= 0.001
Split Flow NTrial= 30
Split Flow Tol= 0.02
Split Flow Ratio= 0.02
Log Output Level= 0
Friction Slope Method= 1
Unsteady Friction Slope Method= 2
Unsteady Bridges Friction Slope Method= 1
Parabolic Critical Depth
Global Vel Dist=  1 , 1 , 1
Global Log Level= 0
CheckData=True
Encroach Param= -1, 0, 0, 0
BEGIN DESCRIPTION:
Multiple Run
END DESCRIPTION:

--- UNT 178 in LFCCL Watershed.f01 (steady flow) ---

Flow Title=Multiple
Number of Profiles=7
Profile Names=10-year,25-year,50-year,1pct_min,100-year,1pct_plu,500-year
River Rch & RM= UNT 178 in LFCCL,Reach-1,2599
     157     191     217     123     246     490     313
Boundary for River Rch & Prof#=UNT 178 in LFCCL,Reach-1,1
Up Type=0
Dn Type=3
Dn Slope=0.005
Boundary for River Rch & Prof#=UNT 178 in LFCCL,Reach-1,2
Up Type=0
Dn Type=3
Dn Slope=0.005
Boundary for River Rch & Prof#=UNT 178 in LFCCL,Reach-1,3
Up Type=0
Dn Type=3
Dn Slope=0.005
Boundary for River Rch & Prof#=UNT 178 in LFCCL,Reach-1,4
Up Type=0
Dn Type=3
Dn Slope=0.005
Boundary for River Rch & Prof#=UNT 178 in LFCCL,Reach-1,5
Up Type=0
Dn Type=3
Dn Slope=0.005
Boundary for River Rch & Prof#=UNT 178 in LFCCL,Reach-1,6
Up Type=0
Dn Type=3
Dn Slope=0.005
Boundary for River Rch & Prof#=UNT 178 in LFCCL,Reach-1,7
Up Type=0
Dn Type=3
Dn Slope=0.005

--- UNT 178 in LFCCL Watershed.g01 (geometry) ---

Geom Title=Existing Conditions

River Reach=UNT 178 in LFCCL,Reach-1
Reach XY= 30
      2816801.96      7028295.21      2816812.06      7028258.18
      2816832.26      7028232.37      2816837.87      7028130.25
      2816858.07      7028089.85      2816964.68      7028006.81
      2817080.26      7027959.68      2817392.23      7027803.69
      2817460.59      7027755.71      2817754.90      7027197.45
      2817786.02      7027116.90      2817844.61      7027060.14
      2817870.24      7027040.00      2817894.04      7027014.37
      2817905.02      7026990.57      2817925.16      7026974.10
      2817959.95      7026964.94      2817981.92      7026953.96
      2818000.23      7026931.99      2818011.21      7026906.36
      2818035.01      7026889.88      2818056.98      7026862.42
      2818077.12      7026847.77      2818128.38      7026825.80
      2818137.54      7026802.00      2818144.86      7026737.92
      2818165.00      7026708.63      2818287.66      7026659.20
      2818560.45      7026509.07      2818619.88      7026487.24

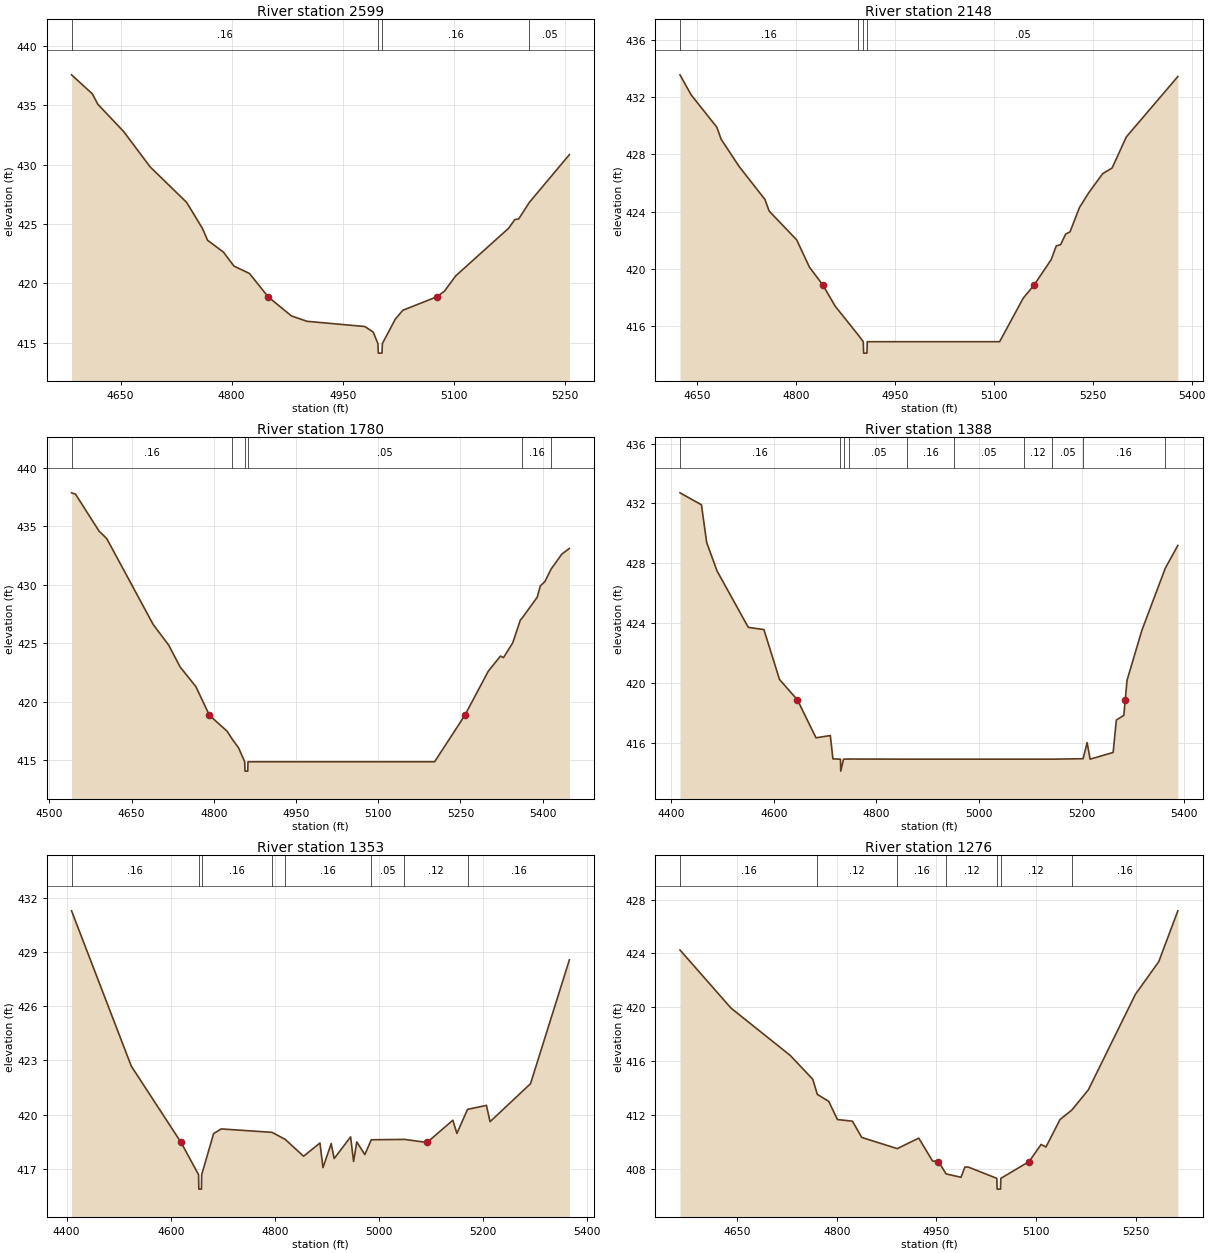
Type RM Length L Ch R = 1,2599,451,451,451
BEGIN DESCRIPTION:
UNT 178 in LFCCL Watershed 7.0
END DESCRIPTION:
XS GIS Cut Line= 3
      2817125.00      7028475.00      2816843.75      7028179.42
      2816584.66      7028125.71
#Sta/Elev= 30
  4583.7  437.56  4611.8  435.96  4619.1  435.09  4654.3  432.77  4689.9  429.81
  4739.2  426.82  4760.6  424.62  4767.5  423.63  4789.0  422.63  4803.1  421.46
  4824.2  420.83  4849.3  418.87  4880.8  417.26  4901.8  416.81  4979.9  416.37
  4991.3  415.90  4997.6  414.93  4998.1  414.13  5003.1  414.13  5003.6  414.93
  5021.1  416.99  5031.3  417.74  5077.1  418.87  5087.4  419.34  5102.8  420.64
  5174.3  424.65  5182.6  425.38  5187.7  425.42  5202.3  426.83  5256.3  430.84
#Mann=4,-1,0
  4583.7    0.16       0  4997.6    0.07       0  5003.6    0.16       0
  5202.3    0.05       0
Bank Sta=4849.3,5077.1
Exp/Cntr=0.3,0.1

Type RM Length L Ch R = 1,2148,368,368,368
BEGIN DESCRIPTION:
UNT 178 in LFCCL Watershed 6.0
END DESCRIPTION:
XS GIS Cut Line= 3
      2817274.99      7028274.97      2817175.00      7027925.00
      2816924.99      7027624.99
#Sta/Elev= 30
  4624.6  433.57  4641.5  432.17  4680.5  429.90  4687.0  429.06  4714.3  427.15
  4753.3  424.85  4759.8  424.03  4801.4  422.02  4820.9  420.10  4841.1  418.86
  4859.9  417.37  4894.9  415.35  4902.4  414.89  4902.9  414.09  4907.9  414.09
  4908.4  414.89  5109.0  414.89  5144.8  417.94  5161.3  418.86  5187.1  420.63
  5194.9  421.60  5201.4  421.68  5209.2  422.43  5215.7  422.58  5230.0  424.28
  5244.4  425.34  5265.2  426.65  5279.5  427.05  5301.0  429.22  5379.1  433.45
#Mann=4,-1,0
  4624.6    0.16       0  4894.9    0.05       0  4902.4   0.033       0
  4908.4    0.05       0
Bank Sta=4841.1,5161.3
Exp/Cntr=0.3,0.1

Type RM Length L Ch R = 1,1780,392,392,392
BEGIN DESCRIPTION:
UNT 178 in LFCCL Watershed 5.0
END DESCRIPTION:
XS GIS Cut Line= 3
      2817825.03      7028025.02      2817475.00      7027725.00
      2817075.02      7027525.01
#Sta/Elev= 30
  4540.6  437.87  4547.8  437.76  4590.6  434.61  4604.8  433.96  4689.4  426.63
  4717.9  424.85  4738.7  422.99  4767.3  421.32  4792.1  418.86  4824.4  417.50
  4834.2  416.79  4845.2  416.09  4856.5  414.89  4857.0  414.09  4862.0  414.09
  4862.5  414.89  5202.9  414.89  5258.1  418.86  5300.7  422.62  5323.0  423.92
  5328.6  423.79  5345.4  425.05  5359.4  427.01  5362.6  427.17  5390.1  428.95
  5395.7  429.91  5404.1  430.29  5415.4  431.35  5434.9  432.63  5448.8  433.12
#Mann=6,-1,0
  4540.6    0.16       0  4834.2    0.05       0  4856.5   0.033       0
  4862.5    0.05       0  5362.6    0.16       0  5415.4    0.05       0
Bank Sta=4792.1,5258.1
Exp/Cntr=0.3,0.1

Type RM Length L Ch R = 1,1388,35,35,35
BEGIN DESCRIPTION:
XS4054A
END DESCRIPTION:
XS GIS Cut Line= 5
      2817810.44      7027936.20      2817740.93      7027534.97
      2817652.48      7027367.53      2817541.91      7027184.30
      2817415.58      7027086.40
#Sta/Elev= 30
  4417.1  432.71  4458.9  431.91  4469.1  429.39  4489.4  427.48  4550.2  423.71
  4580.7  423.56  4611.1  420.22  4646.0  418.86  4682.2  416.32  4710.1  416.47
  4715.2  414.91  4729.9  414.89  4730.4  414.09  4735.9  414.89  4747.4  414.90
  4860.4  414.89  4951.9  414.89  5086.9  414.89  5142.1  414.89  5202.8  414.92
  5210.7  416.00  5216.5  414.89  5261.4  415.34  5267.7  417.51  5282.2  417.82
  5285.0  418.86  5288.5  420.17  5317.5  423.52  5363.1  427.67  5387.5  429.19
#Mann=10,-1,0
  4417.1    0.16       0  4729.9   0.035       0  4735.9    0.16       0
  4747.4    0.05       0  4860.4    0.16       0  4951.9    0.05       0
  5086.9    0.12       0  5142.1    0.05       0  5202.8    0.16       0
  5363.1    0.05       0
Bank Sta=4646,5285
Exp/Cntr=0.3,0.1

Type RM Length L Ch R = 1,1353,77,77,77
BEGIN DESCRIPTION:
XS4055A
END DESCRIPTION:
XS GIS Cut Line= 6
      2817829.40      7027907.78      2817778.84      7027639.22
      2817772.52      7027516.01      2817668.27      7027335.94
      2817592.45      7027203.26      2817453.43      7027061.07
#Sta/Elev= 30
  4409.5  431.27  4524.3  422.68  4619.9  418.46  4653.5  416.68  4654.0  415.88
  4659.0  415.88  4659.5  416.68  4682.4  418.95  4697.0  419.21  4794.6  419.02
  4820.0  418.63  4855.2  417.70  4886.7  418.43  4892.5  417.07  4908.3  418.40
  4914.0  417.57  4945.6  418.77  4951.3  417.41  4957.5  418.49  4972.9  417.79
  4985.3  418.61  5049.1  418.63  5092.4  418.46  5142.0  419.69  5149.8  418.96
  5170.2  420.29  5206.5  420.51  5213.5  419.61  5291.2  421.71  5365.9  428.56
#Mann=8,-1,0
  4409.5    0.16       0  4653.5   0.035       0  4659.5    0.16       0
  4794.6    0.05       0  4820.0    0.16       0  4985.3    0.05       0
  5049.1    0.12       0  5170.2    0.16       0
Bank Sta=4619.9,5092.4
Exp/Cntr=0.3,0.1

Type RM Length L Ch R = 1,1276,167,167,167
BEGIN DESCRIPTION:
XS4056A
END DESCRIPTION:
XS GIS Cut Line= 5
      2817911.52      7027658.15      2817838.87      7027430.71
      2817712.50      7027282.24      2817582.98      7027136.92
      2817490.32      7027059.71
#Sta/Elev= 30
  4564.1  424.26  4640.9  419.94  4730.1  416.42  4763.9  414.65  4770.7  413.53
  4787.9  413.01  4801.0  411.66  4823.5  411.54  4837.6  410.33  4891.0  409.50
  4923.3  410.28  4944.1  408.58  4952.9  408.54  4964.5  407.62  4986.9  407.37
  4992.7  408.13  4997.8  408.13  5040.8  407.29  5041.3  406.49  5046.3  406.49
  5046.8  407.29  5089.4  408.54  5107.4  409.81  5114.7  409.62  5135.8  411.66
  5153.5  412.36  5178.5  413.87  5249.3  420.97  5284.4  423.39  5313.1  427.17
#Mann=7,-1,0
  4564.1    0.16       0  4770.7    0.12       0  4891.0    0.16       0
  4964.5    0.12       0  5040.8    0.07       0  5046.8    0.12       0
  5153.5    0.16       0
Bank Sta=4952.9,5089.4
Exp/Cntr=0.3,0.1

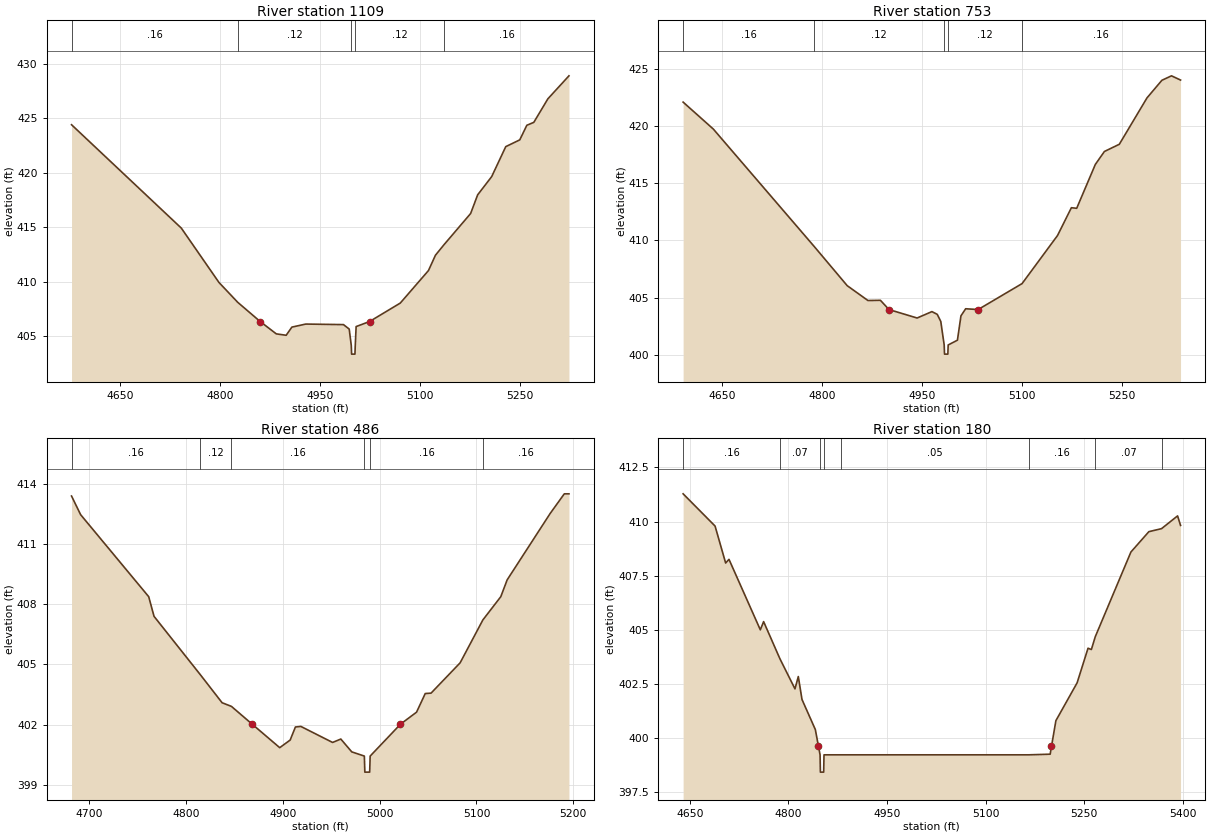
Type RM Length L Ch R = 1,1109,356,356,356
BEGIN DESCRIPTION:
UNT 178 in LFCCL Watershed 3.0
END DESCRIPTION:
XS GIS Cut Line= 3
      2818124.99      7027374.99      2817775.00      7027125.00
      2817475.03      7027025.01
#Sta/Elev= 30
  4577.2  424.41  4741.9  414.92  4798.4  409.93  4826.5  408.11  4860.3  406.34
  4884.4  405.21  4899.2  405.08  4907.8  405.83  4928.6  406.11  4985.2  406.06
  4993.8  405.65  4996.9  404.15  4997.4  403.35  5002.4  403.35  5002.9  404.15
  5004.2  405.88  5024.3  406.34  5070.5  408.04  5112.7  411.02  5123.2  412.43
  5136.1  413.40  5176.0  416.26  5186.5  417.97  5207.6  419.65  5228.7  422.40
  5249.7  423.02  5260.3  424.36  5270.8  424.63  5291.9  426.79  5323.5  428.90
#Mann=5,-1,0
  4577.2    0.16       0  4826.5    0.12       0  4996.9    0.07       0
  5002.9    0.12       0  5136.1    0.16       0
Bank Sta=4860.3,5024.3
Exp/Cntr=0.3,0.1

Type RM Length L Ch R = 1,753,267,267,267
BEGIN DESCRIPTION:
UNT 178 in LFCCL Watershed 2.0
END DESCRIPTION:
XS GIS Cut Line= 3
      2818175.00      7027274.99      2818025.00      7026875.00
      2817775.04      7026675.03
#Sta/Elev= 30
  4591.3  422.10  4636.7  419.74  4788.5  409.45  4837.8  406.04  4869.0  404.74
  4887.7  404.76  4900.6  403.95  4942.8  403.21  4965.1  403.77  4973.1  403.53
  4978.4  402.91  4983.5  400.85  4984.0  400.05  4989.0  400.05  4989.5  400.85
  5003.4  401.27  5008.7  403.40  5015.8  404.02  5034.5  403.95  5100.5  406.22
  5153.8  410.43  5174.6  412.86  5182.6  412.81  5210.6  416.65  5224.2  417.78
  5246.6  418.41  5288.2  422.47  5310.6  424.01  5325.0  424.40  5338.6  424.03
#Mann=5,-1,0
  4591.3    0.16       0  4788.5    0.12       0  4983.5    0.07       0
  4989.5    0.12       0  5100.5    0.16       0
Bank Sta=4900.6,5034.5
Exp/Cntr=0.3,0.1

Type RM Length L Ch R = 1,486,306,306,306
BEGIN DESCRIPTION:
XS4057A
END DESCRIPTION:
XS GIS Cut Line= 3
      2818322.22      7026982.15      2818205.32      7026713.60
      2818022.09      7026590.39
#Sta/Elev= 30
  4681.8  413.40  4691.2  412.47  4761.5  408.38  4767.0  407.40  4814.8  404.49
  4837.3  403.09  4846.9  402.91  4868.4  402.02  4896.8  400.85  4907.6  401.23
  4913.0  401.88  4918.6  401.91  4951.4  401.11  4959.9  401.28  4971.2  400.64
  4984.2  400.43  4984.7  399.63  4989.7  399.63  4990.2  400.43  5021.5  402.02
  5038.1  402.62  5047.1  403.55  5053.1  403.57  5083.1  405.08  5106.6  407.22
  5125.1  408.38  5131.7  409.22  5176.1  412.53  5190.7  413.51  5195.5  413.51
#Mann=6,-1,0
  4681.8    0.16       0  4814.8    0.12       0  4846.9    0.16       0
  4984.2    0.07       0  4990.2    0.16       0  5106.6    0.16       0
Bank Sta=4868.4,5021.5
Exp/Cntr=0.3,0.1

Type RM Length L Ch R = 1,180,0,0,0
BEGIN DESCRIPTION:
UNT 178 in LFCCL Watershed 1.0
END DESCRIPTION:
XS GIS Cut Line= 3
      2818447.98      7026882.81      2818505.27      7026575.48
      2818071.27      7026480.00
#Sta/Elev= 30
  4639.7  411.28  4688.3  409.79  4704.4  408.08  4709.5  408.25  4757.2  404.99
  4762.2  405.37  4786.9  403.66  4809.9  402.26  4815.0  402.83  4820.6  401.77
  4840.9  400.38  4845.7  399.60  4848.1  399.21  4848.6  398.41  4853.6  398.41
  4854.1  399.21  4879.4  399.21  5166.0  399.21  5198.3  399.24  5200.3  399.60
  5207.0  400.79  5239.3  402.54  5255.9  404.14  5261.0  404.08  5266.9  404.67
  5321.2  408.59  5348.5  409.53  5367.8  409.67  5392.2  410.26  5396.7  409.82
#Mann=8,-1,0
  4639.7    0.16       0  4786.9    0.07       0  4848.1   0.033       0
  4854.1    0.07       0  4879.4    0.05       0  5166.0    0.16       0
  5266.9    0.07       0  5367.8    0.16       0
Bank Sta=4845.7,5200.3
Exp/Cntr=0.3,0.1

Chan Stop Cuts=-1