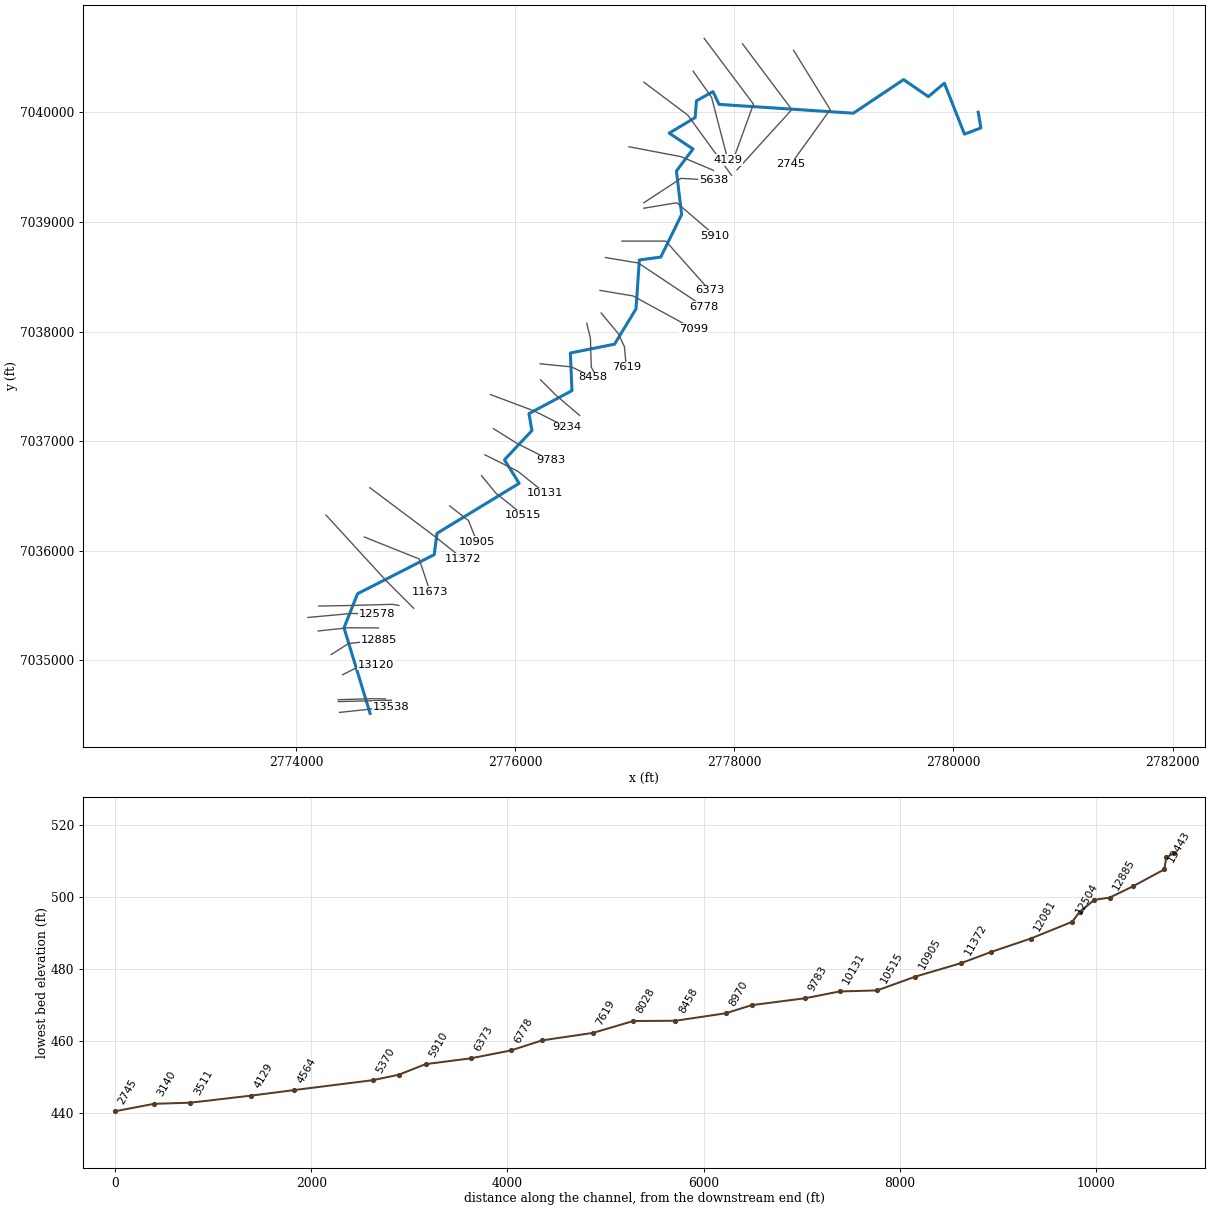
--- UNT 181 in LFCCL Watershed.prj (project) ---

Proj Title=UNT 181 in LFCCL Watershed Base Level Engineering
Current Plan=p01
Default Exp/Contr=0.3,0.1
English Units
Geom File=g01
Flow File=f01
Plan File=p01
Y Axis Title=Elevation
X Axis Title(PF)=Main Channel Distance
X Axis Title(XS)=Station
BEGIN DESCRIPTION:
UNT 181 in LFCCL Watershed
END DESCRIPTION:
DSS Export Rating Curves= 0
DSS Export Rating Curve Sorted= 0
DSS Export Volume Flow Curves= 0
DXF OffsetX= 0
DXF OffsetY= 0
DXF ScaleX= 1
DXF ScaleY= 10

--- UNT 181 in LFCCL Watershed.p01 (plan) ---

Plan Title=Multiple Run
Short Identifier=Multiple
Geom File=g01
Flow File=f01
Subcritical Flow
K Sum by GR= 0
Std Step Tol= 0.01
Critical Tol= 0.01
Num of Std Step Trials= 20
Max Error Tol= 0.3
Flow Tol Ratio= 0.001
Split Flow NTrial= 30
Split Flow Tol= 0.02
Split Flow Ratio= 0.02
Log Output Level= 0
Friction Slope Method= 1
Unsteady Friction Slope Method= 2
Unsteady Bridges Friction Slope Method= 1
Parabolic Critical Depth
Global Vel Dist=  1 , 1 , 1
Global Log Level= 0
CheckData=True
Encroach Param= -1, 0, 0, 0
BEGIN DESCRIPTION:
Multiple Run
END DESCRIPTION:

--- UNT 181 in LFCCL Watershed.f01 (steady flow) ---

Flow Title=Multiple
Number of Profiles=7
Profile Names=10-year,25-year,50-year,1pct_min,100-year,1pct_plu,500-year
River Rch & RM= UNT 181 in LFCCL,Reach-1,13538
     316     407     478     279     557    1112     760
River Rch & RM= UNT 181 in LFCCL,Reach-1,5370
     535     712     854     510    1017    2029    1444
Boundary for River Rch & Prof#=UNT 181 in LFCCL,Reach-1,1
Up Type=0
Dn Type=3
Dn Slope=0.005
Boundary for River Rch & Prof#=UNT 181 in LFCCL,Reach-1,2
Up Type=0
Dn Type=3
Dn Slope=0.005
Boundary for River Rch & Prof#=UNT 181 in LFCCL,Reach-1,3
Up Type=0
Dn Type=3
Dn Slope=0.005
Boundary for River Rch & Prof#=UNT 181 in LFCCL,Reach-1,4
Up Type=0
Dn Type=3
Dn Slope=0.005
Boundary for River Rch & Prof#=UNT 181 in LFCCL,Reach-1,5
Up Type=0
Dn Type=3
Dn Slope=0.005
Boundary for River Rch & Prof#=UNT 181 in LFCCL,Reach-1,6
Up Type=0
Dn Type=3
Dn Slope=0.005
Boundary for River Rch & Prof#=UNT 181 in LFCCL,Reach-1,7
Up Type=0
Dn Type=3
Dn Slope=0.005

--- UNT 181 in LFCCL Watershed.g01 (geometry) ---

Geom Title=Existing Conditions
Program Version=5.07

River Reach=UNT 181 in LFCCL,Reach-1
Reach XY= 30
      2774677.22        7034516.      2774439.15      7035295.95
      2774562.61      7035607.38      2775262.23      7035964.31
      2775287.54      7036158.44      2776037.26      7036615.01
      2775903.04      7036829.73      2776153.83      7037096.06
      2776126.67       7037251.1      2776518.94      7037460.45
      2776504.59      7037803.91      2776907.64      7037884.48
      2777103.29      7038206.92      2777133.78      7038652.76
      2777329.64       7038679.5      2777519.71      7039067.81
      2777471.83      7039464.57      2777623.31       7039665.3
      2777406.27      7039810.07      2777643.17        7039952.
        2777655.      7040105.02      2777805.57      7040188.84
      2777860.87       7040072.5      2779086.07      7039991.81
      2779544.85      7040298.33      2779770.69      7040143.15
      2779916.69      7040265.96      2780100.36      7039800.71
      2780249.91      7039857.65      2780225.59      7040000.71

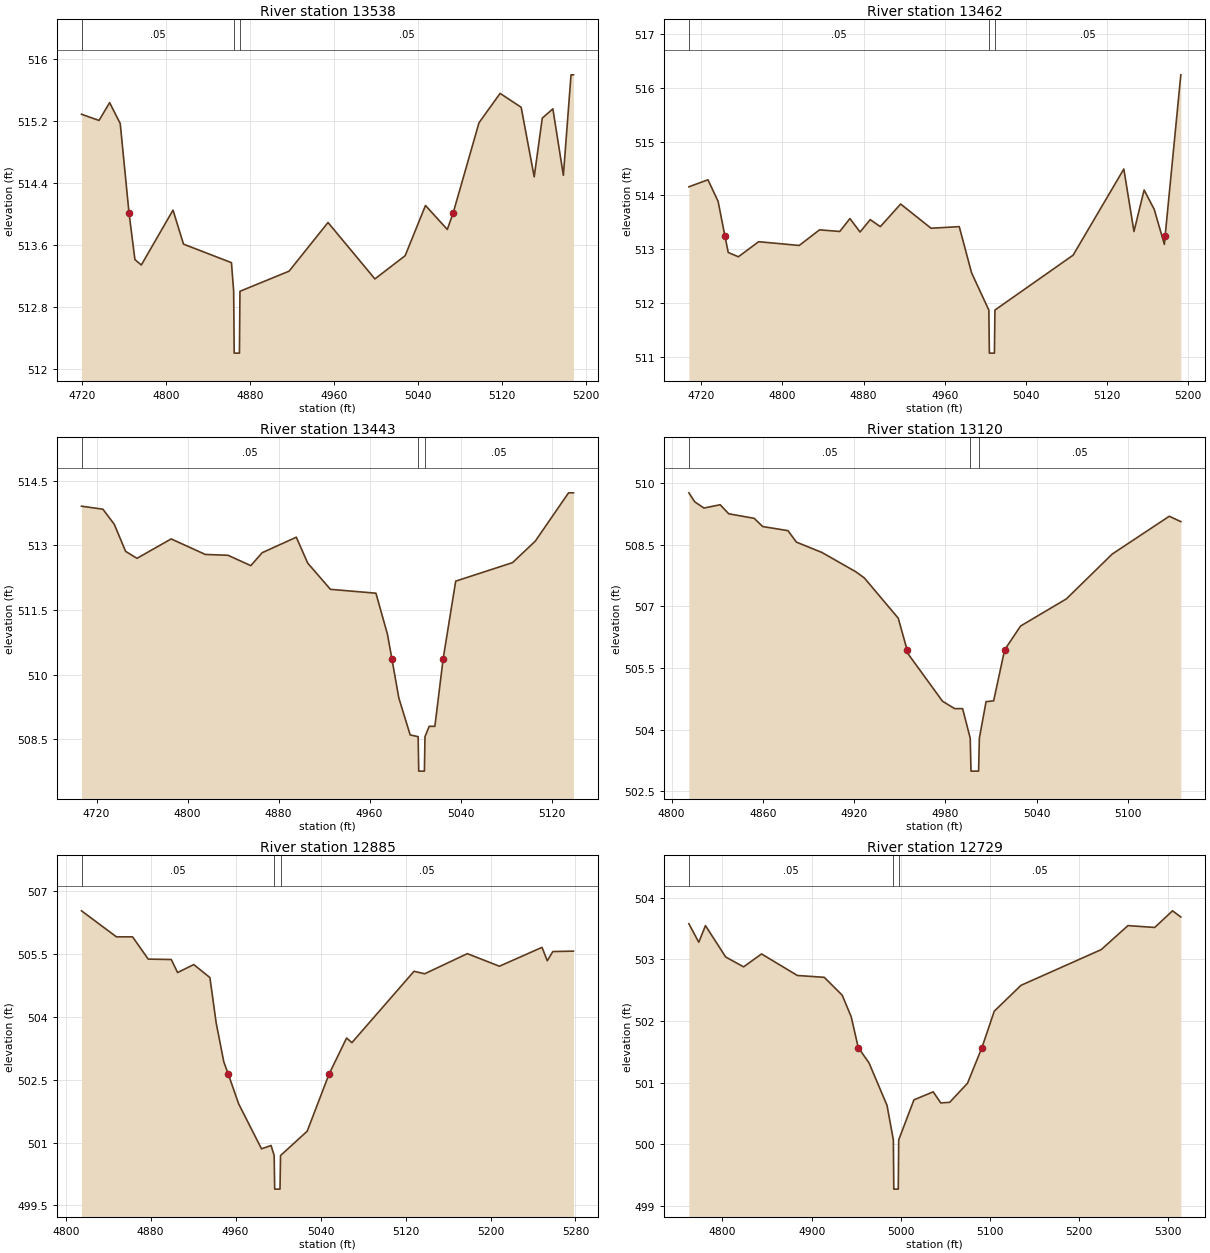
Type RM Length L Ch R = 1 ,13538   ,76,76,76
BEGIN DESCRIPTION:
UNT 181 in LFCCL Watershed 23.0
END DESCRIPTION:
XS GIS Cut Line= 3
      2774398.35      7034524.66      2774672.69      7034554.18
      2774864.53      7034574.14
#Sta/Elev= 30
  4719.1  515.29  4735.8  515.21  4745.9  515.44    4756  515.17  4764.4  514.01
    4770  513.41  4776.1  513.34  4806.3  514.05  4816.3  513.61    4862  513.37
  4864.1     513  4864.6   512.2  4869.6   512.2  4870.1     513  4916.9  513.26
    4954  513.89  4998.7  513.16  5027.5  513.46  5046.9  514.11  5067.7   513.8
  5073.2  514.01  5097.9  515.18    5118  515.56  5138.1  515.38  5150.5  514.48
  5158.2  515.24  5168.3  515.36  5178.3   514.5  5185.6   515.8  5187.9   515.8
#Mann= 3 ,-1 , 0
  4719.1     .05       0  4864.1     .03       0  4870.1     .05       0
Bank Sta=4764.4,5073.2
XS Rating Curve= 0 ,0
Exp/Cntr=0.3,0.1

Type RM Length L Ch R = 1 ,13462   ,19,19,19
BEGIN DESCRIPTION:
XS4058A
END DESCRIPTION:
XS GIS Cut Line= 3
      2774386.24      7034623.62      2774679.64      7034630.57
      2774871.19      7034635.75
#Sta/Elev= 30
  4707.7  514.16  4726.5  514.29  4736.5  513.89  4743.3  513.24  4746.5  512.94
  4756.5  512.86  4776.5  513.14  4816.5  513.07  4836.5  513.36  4856.5  513.33
  4866.5  513.57  4876.5  513.32  4886.5  513.55  4896.5  513.42  4916.5  513.84
  4946.5  513.39  4974.3  513.42  4986.5  512.56  5003.5  511.87    5004  511.07
    5009  511.07  5009.5  511.87  5086.6  512.89  5136.6  514.49  5146.6  513.33
  5156.6   514.1  5166.6  513.74  5176.6  513.09  5177.3  513.24  5192.8  516.24
#Mann= 3 ,-1 , 0
  4707.7     .05       0  5003.5     .03       0  5009.5     .05       0
Bank Sta=4743.3,5177.3
XS Rating Curve= 0 ,0
Exp/Cntr=0.3,0.1

Type RM Length L Ch R = 1 ,13443   ,323,323,323
BEGIN DESCRIPTION:
XS4061A
END DESCRIPTION:
XS GIS Cut Line= 3
      2774386.25      7034640.99      2774693.53      7034649.67
      2774818.52      7034647.93
#Sta/Elev= 30
  4706.8  513.91  4725.6  513.84  4735.6  513.49  4745.6  512.86  4755.6   512.7
  4785.6  513.15  4815.6  512.79  4835.6  512.77  4855.6  512.53  4865.6  512.83
  4895.6  513.19  4905.6  512.59  4925.6  511.98  4965.6  511.89  4975.7  510.94
  4979.6  510.37  4985.7  509.46  4995.7   508.6  5002.7  508.56  5003.2  507.76
  5008.2  507.76  5008.7  508.56  5012.4   508.8  5017.4   508.8  5024.7  510.37
  5035.7  512.17  5085.7   512.6  5105.7   513.1  5134.9  514.22  5139.2  514.22
#Mann= 3 ,-1 , 0
  4706.8     .05       0  5002.7     .03       0  5008.7     .05       0
Bank Sta=4979.6,5024.7
XS Rating Curve= 0 ,0
Exp/Cntr=0.3,0.1

Type RM Length L Ch R = 1 ,13120   ,235,235,235
BEGIN DESCRIPTION:
XS4063A
END DESCRIPTION:
XS GIS Cut Line= 3
      2774426.19      7034868.43      2774584.15      7034948.28
      2774729.95      7034960.43
#Sta/Elev= 30
  4811.4  509.76  4815.3  509.54  4821.3  509.39    4832  509.47  4837.6  509.25
  4854.3  509.14  4859.9  508.94  4876.5  508.84  4882.1  508.56  4898.8  508.31
  4921.1  507.84  4926.7  507.69    4949  506.71  4954.8  505.94  4955.7  505.83
  4978.1  504.69  4986.1  504.51  4991.3  504.51  4996.3  503.79  4996.8  502.99
  5001.8  502.99  5002.3  503.79  5006.7  504.68  5011.7   504.7  5018.9  505.94
  5029.4  506.52  5059.5  507.18  5089.6  508.27  5127.1  509.19  5134.7  509.06
#Mann= 3 ,-1 , 0
  4811.4     .05       0  4996.3     .03       0  5002.3     .05       0
Bank Sta=4954.8,5018.9
XS Rating Curve= 0 ,0
Exp/Cntr=0.3,0.1

Type RM Length L Ch R = 1 ,12885   ,156,156,156
BEGIN DESCRIPTION:
XS4064A
END DESCRIPTION:
XS GIS Cut Line= 3
      2774322.03      7035052.46      2774479.99      7035153.14
      2774754.29      7035182.65
#Sta/Elev= 30
  4814.9  506.52  4847.8   505.9    4863   505.9  4877.7  505.37  4899.4  505.36
  4905.4  505.05  4920.6  505.24  4935.8  504.93  4941.7  503.85  4948.9  502.92
  4953.1  502.63  4962.9  501.92  4984.4  500.85  4993.4  500.93  4996.3  500.69
  4996.8  499.89  5001.8  499.89  5002.3  500.69  5027.4  501.27    5048  502.63
  5064.5  503.49  5069.5  503.38    5128  505.08    5138  505.02  5178.2   505.5
  5208.4   505.2  5248.5  505.65  5253.5  505.33  5258.7  505.55  5278.1  505.56
#Mann= 3 ,-1 , 0
  4814.9     .05       0  4996.3     .03       0  5002.3     .05       0
Bank Sta=4953.1,5048
XS Rating Curve= 0 ,0
Exp/Cntr=0.3,0.1

Type RM Length L Ch R = 1 ,12729   ,151,151,151
BEGIN DESCRIPTION:
XS4065A
END DESCRIPTION:
XS GIS Cut Line= 3
      2774203.96      7035267.72      2774476.51      7035297.24
      2774754.27       7035295.5
#Sta/Elev= 30
  4762.3  503.58  4773.4  503.28  4780.9  503.55  4803.6  503.04  4823.7  502.88
  4843.8  503.09    4884  502.74  4914.2  502.71  4934.3  502.42  4944.4  502.07
  4952.3  501.57  4964.4  501.32  4984.6  500.63  4991.7  500.07  4992.2  499.27
  4997.2  499.27  4997.7  500.07  5014.8  500.72  5036.4  500.85  5044.9  500.67
  5054.9  500.68  5074.9  500.99  5091.1  501.57  5104.9  502.16  5134.9  502.58
  5224.9  503.16  5254.9  503.55  5284.9  503.52  5304.9  503.79  5314.2  503.69
#Mann= 3 ,-1 , 0
  4762.3     .05       0  4991.7     .03       0  4997.7     .05       0
Bank Sta=4952.3,5091.1
XS Rating Curve= 0 ,0
Exp/Cntr=0.3,0.1

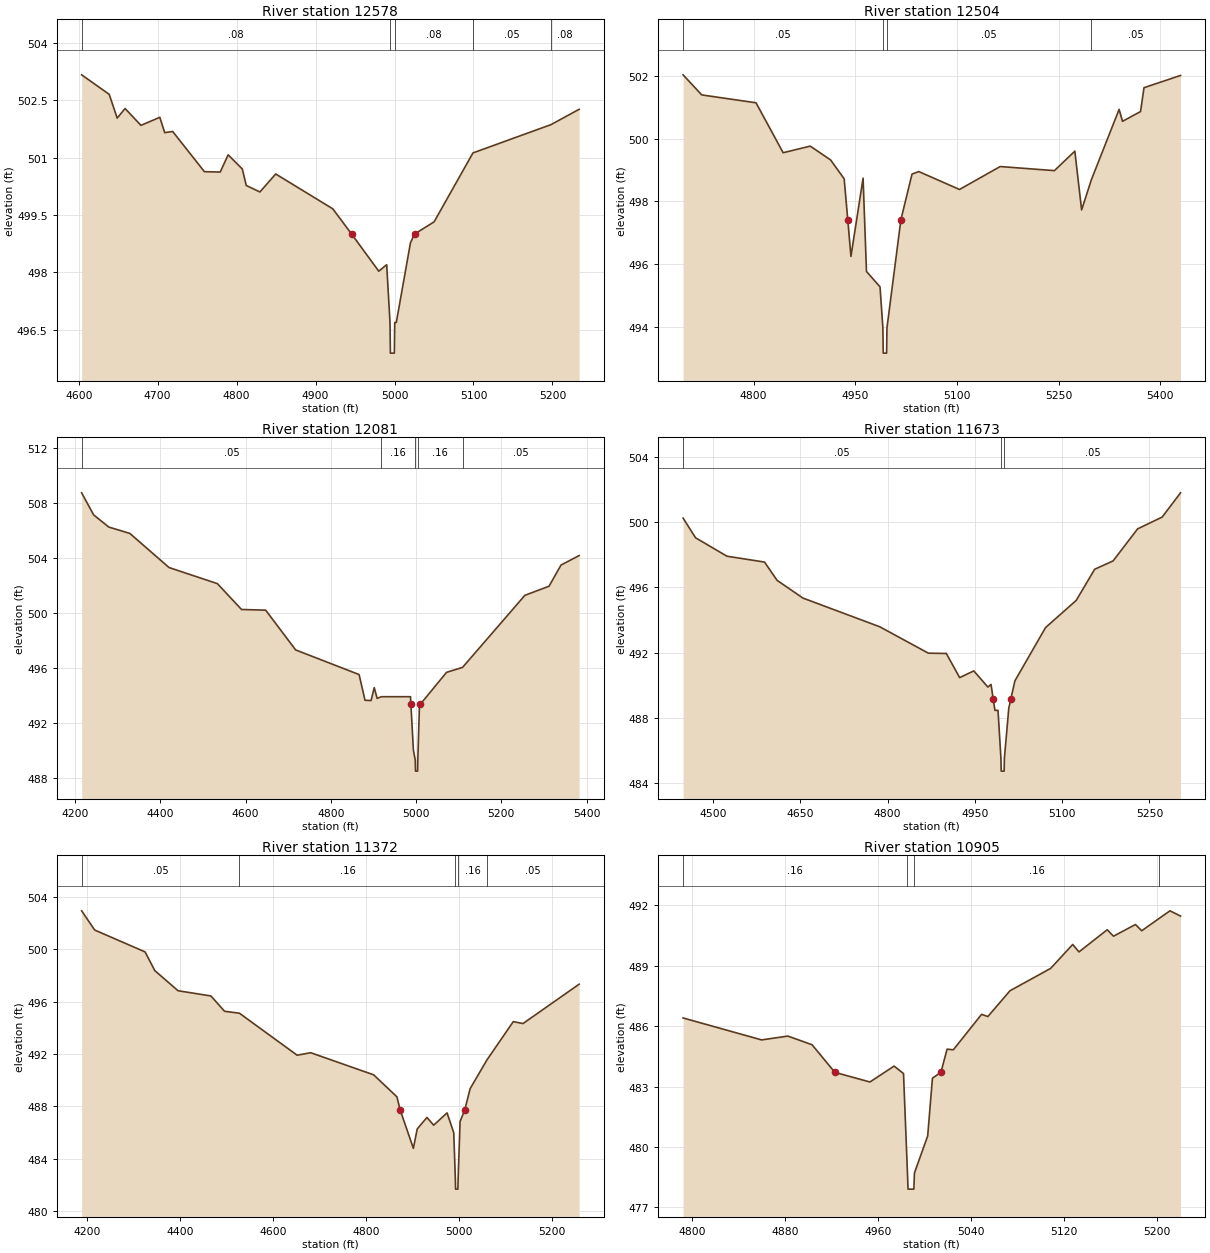
Type RM Length L Ch R = 1 ,12578   ,74,74,74
BEGIN DESCRIPTION:
XS4066A
END DESCRIPTION:
XS GIS Cut Line= 3
      2774110.21      7035390.99      2774504.29      7035427.44
       2774738.7      7035423.97
#Sta/Elev= 30
  4603.7  503.16  4638.6  502.65  4648.7  502.03  4658.7  502.28  4678.8  501.84
  4702.7  502.05  4708.9  501.65    4719  501.68  4759.2  500.63  4779.2  500.62
  4789.3  501.07  4807.2   500.7  4812.2  500.27  4829.5   500.1  4849.5  500.57
  4921.8  499.66  4945.7     499  4980.1  498.03  4990.1   498.2  4994.3  496.69
  4994.8  495.89  4999.8  495.89  5000.3  496.69  5002.3  496.69  5020.2  498.77
  5025.4     499  5050.2  499.32  5099.4  501.12  5198.4  501.86  5233.9  502.26
#Mann= 5 ,-1 , 0
  4603.7     .08       0  4994.3     .07       0  5000.3     .08       0
  5099.4     .05       0  5198.4     .08       0
Bank Sta=4945.7,5025.4
XS Rating Curve= 0 ,0
Exp/Cntr=0.3,0.1

Type RM Length L Ch R = 1 ,12504   ,423,423,423
BEGIN DESCRIPTION:
XS4067A
END DESCRIPTION:
XS GIS Cut Line= 4
       2774207.4      7035495.15      2774495.61      7035500.36
      2774879.29      7035510.78      2774940.02      7035500.37
#Sta/Elev= 30
    4696  502.03  4723.6  501.39  4803.6  501.14  4843.6  499.55  4883.6  499.76
  4913.6  499.32  4933.6  498.72  4938.9  497.42  4943.6  496.25  4961.5  498.74
  4966.5  495.77  4986.5  495.28  4990.7  493.97  4991.2  493.17  4996.2  493.17
  4996.7  493.97  5017.3  497.42  5033.7  498.87  5043.7  498.95  5103.7  498.38
  5163.7  499.11  5243.7  498.98  5273.8   499.6  5283.8  497.73  5298.2  498.69
  5339.1  500.93  5344.1  500.55  5370.7  500.86  5375.8  501.62  5429.7  502.01
#Mann= 4 ,-1 , 0
    4696     .05       0  4990.7     .07       0  4996.7     .05       0
  5298.2     .05       0
Bank Sta=4938.9,5017.3
XS Rating Curve= 0 ,0
Exp/Cntr=0.3,0.1

Type RM Length L Ch R = 1 ,12081   ,408,408,408
BEGIN DESCRIPTION:
UNT 181 in LFCCL Watershed 21.0
END DESCRIPTION:
XS GIS Cut Line= 3
      2774275.02      7036324.98        2774825.        7035725.
      2775075.03      7035474.97
#Sta/Elev= 30
  4215.2  508.73  4243.2  507.13    4279  506.24  4328.3  505.78  4420.2   503.3
  4533.7  502.13  4590.4  500.25  4647.1   500.2  4717.4  497.31  4866.3  495.52
  4880.2  493.65  4894.4  493.63  4901.8  494.57  4908.6  493.79  4918.8  493.91
  4986.9  493.91  4987.9  493.36  4993.7  490.04  4998.1   489.3  4998.6   488.5
  5003.6   488.5  5004.1   489.3  5007.8  493.13    5010  493.36  5071.5  495.68
  5109.1  496.04  5255.4  501.28    5312  501.94  5340.2  503.48  5382.7  504.17
#Mann= 5 ,-1 , 0
  4215.2     .05       0  4918.8     .16       0  4998.1     .07       0
  5004.1     .16       0  5109.1     .05       0
Bank Sta=4987.9,5010
XS Rating Curve= 0 ,0
Exp/Cntr=0.3,0.1

Type RM Length L Ch R = 1 ,11673   ,301,301,301
BEGIN DESCRIPTION:
UNT 181 in LFCCL Watershed 20.0
END DESCRIPTION:
XS GIS Cut Line= 3
      2774625.01        7036125.        2775125.        7035925.
      2775224.99      7035625.04
#Sta/Elev= 30
  4448.7  500.26  4470.2  499.05  4524.1  497.92  4588.7  497.56  4610.2  496.44
  4654.7  495.35  4786.6  493.59  4870.1  491.97    4901  491.95  4923.9  490.47
  4948.2  490.88  4972.4  489.89  4977.8  490.05  4981.7  489.13  4984.5  488.46
  4989.8  488.46  4994.8  485.53  4995.3  484.73  5000.3  484.73  5000.8  485.53
  5008.3  488.59  5011.7  489.13  5018.8  490.27  5071.5  493.54  5124.2  495.21
  5155.9  497.12  5187.5  497.63  5229.7   499.6  5271.8  500.32  5303.4  501.81
#Mann= 3 ,-1 , 0
  4448.7     .05       0  4994.8     .03       0  5000.8     .05       0
Bank Sta=4981.7,5011.7
XS Rating Curve= 0 ,0
Exp/Cntr=0.3,0.1

Type RM Length L Ch R = 1 ,11372   ,467,467,467
BEGIN DESCRIPTION:
UNT 181 in LFCCL Watershed 19.0
END DESCRIPTION:
XS GIS Cut Line= 3
      2774675.02      7036574.98        2775275.        7036125.
      2775524.98      7035925.02
#Sta/Elev= 30
  4188.7  502.94  4216.8  501.47  4325.1   499.8    4346  498.37    4396  496.83
  4466.8  496.43    4496  495.26  4528.1  495.11  4652.2   491.9  4681.4  492.09
  4816.8   490.4  4866.8  488.72  4873.7  487.73  4902.2  484.78  4910.5  486.26
  4931.4  487.14  4945.9  486.55  4974.7  487.49  4989.1  485.97  4992.5  482.46
    4993  481.66    4998  481.66  4998.5  482.46  5002.7  486.83  5012.9  487.73
  5024.3  489.34  5060.3  491.53  5117.2  494.47    5138  494.32  5258.8  497.33
#Mann= 5 ,-1 , 0
  4188.7     .05       0  4528.1     .16       0  4992.5     .07       0
  4998.5     .16       0  5060.3     .05       0
Bank Sta=4873.7,5012.9
XS Rating Curve= 0 ,0
Exp/Cntr=0.3,0.1

Type RM Length L Ch R = 1 ,10905   ,390,390,390
BEGIN DESCRIPTION:
UNT 181 in LFCCL Watershed 18.0
END DESCRIPTION:
XS GIS Cut Line= 3
      2775403.17      7036408.78        2775575.        7036275.
      2775652.51      7036079.47
#Sta/Elev= 30
    4792  486.41  4859.6  485.32  4882.2  485.51    4903  485.08  4922.6  483.71
  4952.8  483.23  4973.6  484.02  4981.7  483.65  4985.1  478.71  4985.6  477.91
  4990.6  477.91  4991.1  478.71  5002.5  480.55  5006.6  483.42  5013.9  483.71
  5019.2  484.86  5024.6  484.83  5048.9  486.59  5054.3  486.48  5073.3  487.76
  5108.3  488.87  5127.3  490.06  5132.7  489.69    5157  490.79  5162.4  490.47
  5181.3  491.05  5186.7  490.74  5201.6  491.35    5211  491.73  5220.1  491.47
#Mann= 4 ,-1 , 0
    4792     .16       0  4985.1     .07       0  4991.1     .16       0
  5201.6     .05       0
Bank Sta=4922.6,5013.9
XS Rating Curve= 0 ,0
Exp/Cntr=0.3,0.1

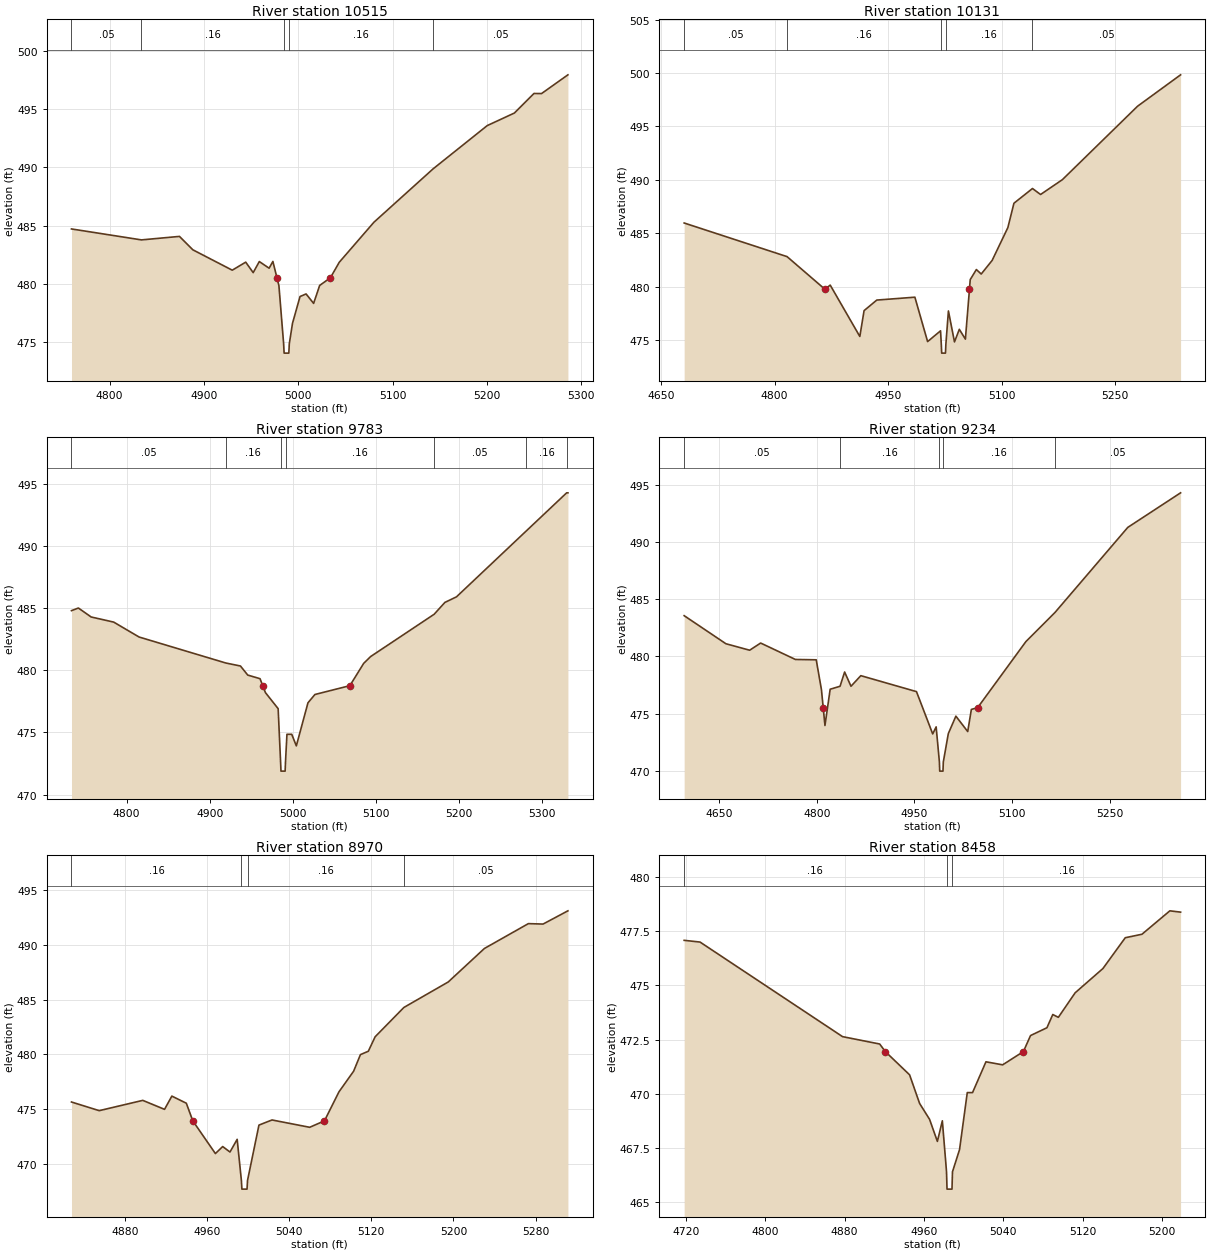
Type RM Length L Ch R = 1 ,10515   ,384,384,384
BEGIN DESCRIPTION:
UNT 181 in LFCCL Watershed 17.0
END DESCRIPTION:
XS GIS Cut Line= 3
      2775693.96       7036684.4        2775825.        7036525.
        2776075.        7036325.
#Sta/Elev= 30
  4759.5  484.72  4833.7  483.78    4874  484.08  4888.2  482.93    4930  481.18
  4944.3  481.87  4952.2  480.97  4958.7  481.92  4969.1  481.35  4973.1  481.93
  4977.4  480.53  4979.5  479.85  4984.5  474.86    4985  474.06    4990  474.06
  4990.5  474.86  4993.9  476.62  5001.9  478.92  5008.3  479.14  5016.3  478.33
  5022.7  479.87  5034.1  480.53  5043.5  481.86  5080.3   485.3  5142.9  489.87
  5200.4  493.59  5229.2  494.67    5250  496.35    5258  496.34    5286  497.95
#Mann= 5 ,-1 , 0
  4759.5     .05       0  4833.7     .16       0  4984.5     .07       0
  4990.5     .16       0  5142.9     .05       0
Bank Sta=4977.4,5034.1
XS Rating Curve= 0 ,0
Exp/Cntr=0.3,0.1

Type RM Length L Ch R = 1 ,10131   ,348,348,348
BEGIN DESCRIPTION:
UNT 181 in LFCCL Watershed 16.0
END DESCRIPTION:
XS GIS Cut Line= 3
      2775724.99      7036875.01        2776025.        7036725.
      2776275.01      7036524.99
#Sta/Elev= 30
  4680.6  485.95  4816.5   482.8  4866.4  479.75  4873.5  480.13  4912.6  475.32
  4918.2  477.74    4935  478.73  4985.3     479  5002.1  474.84  5019.2  475.85
  5020.2  474.56  5020.7  473.76  5025.7  473.76  5026.2  474.56  5029.6  477.71
  5037.6  474.81    5044  475.99    5052  475.07  5057.4  479.75  5058.4  480.65
  5066.5  481.59  5072.9  481.17  5087.3  482.44  5108.1  485.52  5116.1   487.8
  5140.6  489.18  5151.3  488.62  5180.1  490.01  5279.4  496.89  5336.2  499.83
#Mann= 5 ,-1 , 0
  4680.6     .05       0  4816.5     .16       0  5020.2     .07       0
  5026.2     .16       0  5140.6     .05       0
Bank Sta=4866.4,5057.4
XS Rating Curve= 0 ,0
Exp/Cntr=0.3,0.1

Type RM Length L Ch R = 1 ,9783    ,549,549,549
BEGIN DESCRIPTION:
UNT 181 in LFCCL Watershed 15.0
END DESCRIPTION:
XS GIS Cut Line= 3
      2775802.43       7037114.1        2776025.        7036975.
      2776325.02      7036824.99
#Sta/Elev= 30
  4733.6  484.79  4741.9     485  4757.3  484.28  4784.4  483.87    4815  482.67
  4919.5  480.58  4937.1  480.34  4945.9  479.61  4960.7  479.32  4963.9  478.76
  4967.2   478.2  4982.5  476.91  4985.4  472.69  4985.9  471.89  4990.9  471.89
  4991.4  472.69  4993.1  474.85  4998.9  474.85  5004.4  473.92  5018.4  477.38
  5026.8  478.05  5068.9  478.76  5085.5  480.55  5093.9   481.1  5170.4   484.5
  5183.3  485.45  5197.3   485.9  5281.4   491.2    5330  494.26  5331.5  494.26
#Mann= 7 ,-1 , 0
  4733.6     .05       0  4919.5     .16       0  4985.4     .07       0
  4991.4     .16       0  5170.4     .05       0  5281.4     .16       0
    5330     .05       0
Bank Sta=4963.9,5068.9
XS Rating Curve= 0 ,0
Exp/Cntr=0.3,0.1

Type RM Length L Ch R = 1 ,9234    ,264,264,264
BEGIN DESCRIPTION:
UNT 181 in LFCCL Watershed 14.0
END DESCRIPTION:
XS GIS Cut Line= 3
      2775775.02      7037424.99        2776175.        7037275.
      2776475.01        7037125.
#Sta/Elev= 30
  4596.3  483.58  4660.4  481.12  4696.9  480.55  4713.8  481.18  4767.2  479.74
  4799.2  479.71  4807.2  477.09  4809.9  475.52  4812.6  473.95  4820.6  477.13
  4835.8  477.39  4842.8  478.64  4852.6  477.39  4867.7  478.32  4953.2  476.92
  4978.1  473.21  4983.4  473.83  4988.4  470.75  4988.9  469.95  4993.9  469.95
  4994.4  470.75  5002.1  473.24  5013.7  474.77  5031.9  473.42  5037.5  475.36
  5047.2  475.52  5121.3  481.31  5166.1  483.87  5277.8  491.32  5358.9  494.35
#Mann= 5 ,-1 , 0
  4596.3     .05       0  4835.8     .16       0  4988.4     .07       0
  4994.4     .16       0  5166.1     .05       0
Bank Sta=4809.9,5047.2
XS Rating Curve= 0 ,0
Exp/Cntr=0.3,0.1

Type RM Length L Ch R = 1 ,8970    ,512,512,512
BEGIN DESCRIPTION:
UNT 181 in LFCCL Watershed 13.0
END DESCRIPTION:
XS GIS Cut Line= 3
       2776231.7      7037559.84      2776369.74       7037421.8
      2776588.47      7037234.32
#Sta/Elev= 30
  4828.1  475.65  4855.1  474.86  4897.5   475.8  4918.7  474.98  4925.8  476.19
  4939.9  475.54  4946.2  473.93  4968.2  470.94  4975.3  471.58  4982.4  471.08
  4989.4  472.24  4993.5  468.49    4994  467.69    4999  467.69  4999.5  468.49
  5010.6  473.54  5023.3  474.01    5060  473.34  5074.4  473.93  5088.5  476.58
  5102.8  478.47  5109.4  479.98  5117.1  480.29  5123.7  481.61  5151.7  484.29
  5194.9  486.62  5230.1  489.68  5272.9  491.95  5287.2  491.91  5311.4  493.12
#Mann= 4 ,-1 , 0
  4828.1     .16       0  4993.5     .07       0  4999.5     .16       0
  5151.7     .05       0
Bank Sta=4946.2,5074.4
XS Rating Curve= 0 ,0
Exp/Cntr=0.3,0.1

Type RM Length L Ch R = 1 ,8458    ,430,430,430
BEGIN DESCRIPTION:
XS4068A
END DESCRIPTION:
XS GIS Cut Line= 3
      2776229.11      7037705.66      2776515.58      7037677.01
      2776705.72      7037583.24
#Sta/Elev= 30
  4718.5  477.08  4734.5     477    4878  472.64  4915.4   472.3  4921.1  471.95
  4945.5  470.88  4955.6  469.56  4965.6  468.83  4973.5  467.81  4978.5  468.76
  4982.7  466.41  4983.2  465.61  4988.2  465.61  4988.7  466.41  4995.8  467.43
  5003.6  470.06  5008.9  470.06  5022.4  471.48  5039.2  471.34  5060.1  471.95
  5067.3  472.69  5083.8  473.05  5089.7  473.66  5095.3  473.53  5112.2  474.66
  5140.2  475.78  5162.7   477.2  5179.5  477.36  5207.6  478.44  5218.4  478.38
#Mann= 3 ,-1 , 0
  4718.5     .16       0  4982.7     .07       0  4988.7     .16       0
Bank Sta=4921.1,5060.1
XS Rating Curve= 0 ,0
Exp/Cntr=0.3,0.1

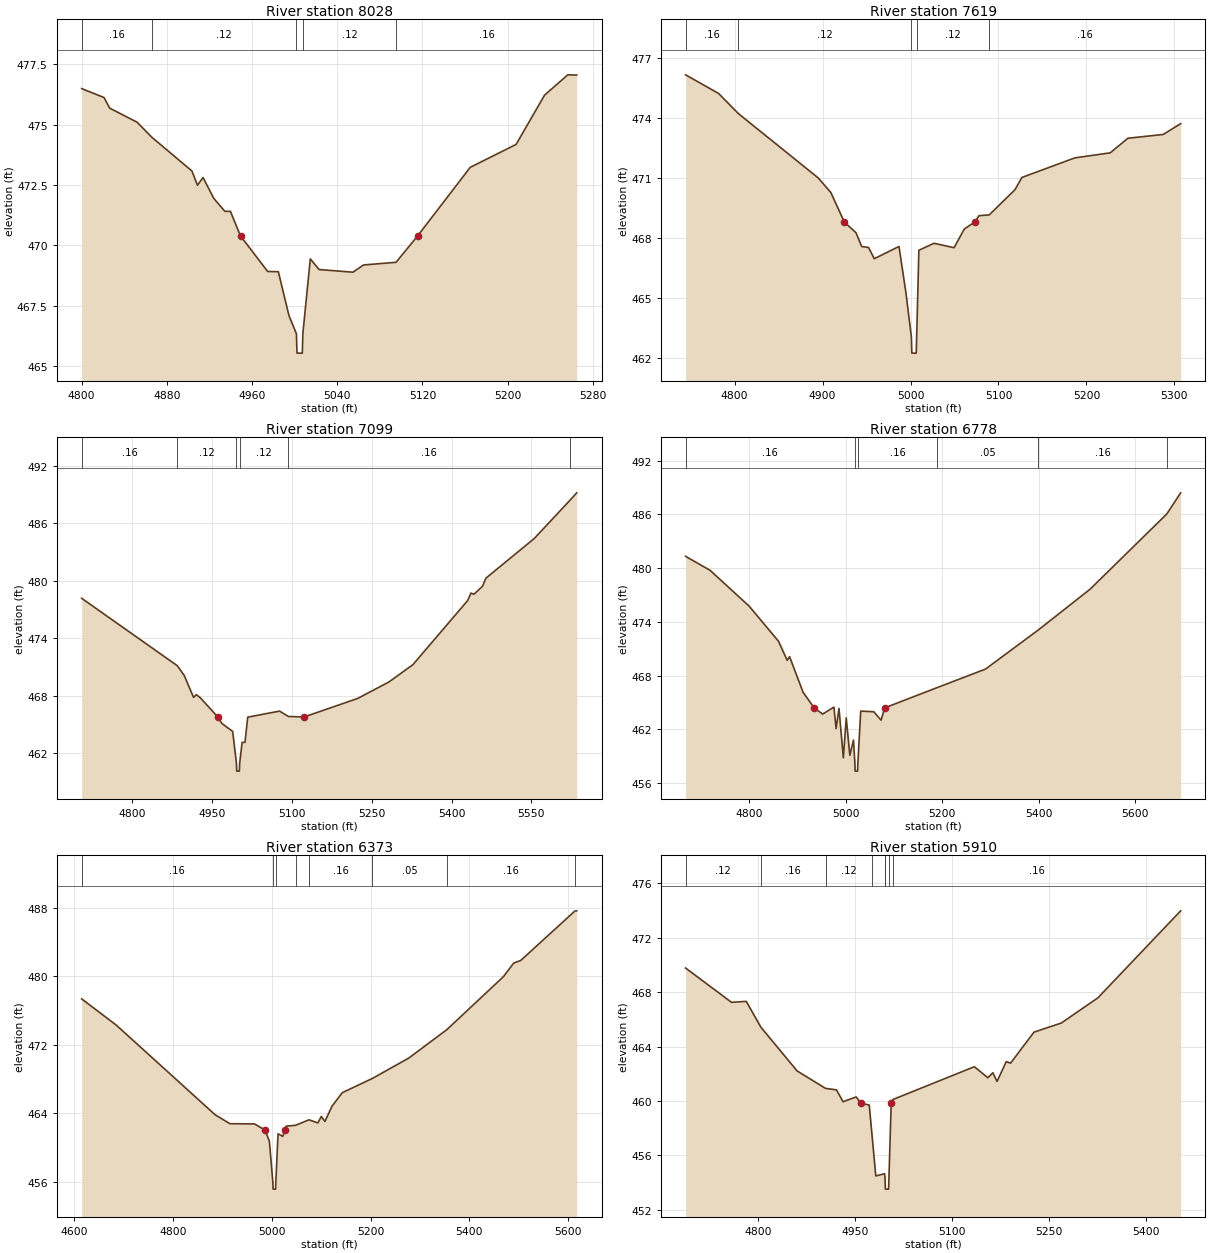
Type RM Length L Ch R = 1 ,8028    ,409,409,409
BEGIN DESCRIPTION:
XS4069A
END DESCRIPTION:
XS GIS Cut Line= 4
      2776653.61      7038075.42      2776687.45      7037940.03
      2776695.26      7037674.41      2776723.89      7037622.35
#Sta/Elev= 30
  4800.1  476.49  4821.1  476.12  4826.4  475.68  4852.1   475.1  4866.1  474.47
  4903.6  473.08  4908.8  472.49    4914  472.81  4924.2  471.94  4934.5  471.41
  4939.7  471.41  4949.2  470.39  4974.7  468.92  4984.7  468.91  4994.7  467.09
  5001.7  466.34  5002.2  465.54  5007.2  465.54  5007.7  466.34  5014.7  469.44
    5023     469  5054.7  468.89  5064.7  469.19  5095.2   469.3  5115.4  470.39
  5164.8  473.23  5207.9  474.18  5234.6  476.22  5256.4  477.06  5264.8  477.05
#Mann= 5 ,-1 , 0
  4800.1     .16       0  4866.1     .12       0  5001.7     .07       0
  5007.7     .12       0  5095.2     .16       0
Bank Sta=4949.2,5115.4
XS Rating Curve= 0 ,0
Exp/Cntr=0.3,0.1

Type RM Length L Ch R = 1 ,7619    ,520,520,520
BEGIN DESCRIPTION:
XS4070A
END DESCRIPTION:
XS GIS Cut Line= 4
      2776785.57       7038168.3      2776941.79      7037980.83
      2776997.35      7037862.77      2777014.71      7037675.28
#Sta/Elev= 30
  4744.3  476.15  4781.8  475.22  4804.4  474.21    4895     471  4909.4  470.27
  4924.8  468.79    4938  468.26  4944.5  467.57  4952.3  467.52  4958.8  466.96
  4986.9  467.57  4994.8  465.26    5001  463.04  5001.5  462.24  5006.5  462.24
    5007  463.04  5009.5  467.38  5026.7  467.73  5049.5  467.51  5061.1  468.44
  5072.9  468.79  5077.9  469.11  5089.5  469.15  5118.8  470.41  5126.6  471.02
  5186.9     472    5227  472.25  5247.1  472.98  5287.3  473.17  5307.1  473.71
#Mann= 5 ,-1 , 0
  4744.3     .16       0  4804.4     .12       0    5001     .07       0
    5007     .12       0  5089.5     .16       0
Bank Sta=4924.8,5072.9
XS Rating Curve= 0 ,0
Exp/Cntr=0.3,0.1

Type RM Length L Ch R = 1 ,7099    ,321,321,321
BEGIN DESCRIPTION:
UNT 181 in LFCCL Watershed 10.0
END DESCRIPTION:
XS GIS Cut Line= 3
      2776774.97      7038375.01        2777075.        7038325.
      2777625.03      7038024.99
#Sta/Elev= 30
  4704.6  478.18  4884.3  471.15  4897.3  470.14    4915  467.84  4920.1  468.13
  4927.7   467.8  4960.5   465.8  4968.2  465.12  4988.5  464.29  4995.6  460.95
  4996.1  460.15  5001.1  460.15  5001.6  460.95  5006.2  463.15  5011.6  463.15
  5016.8  465.78  5076.6  466.41  5093.3  465.85  5122.8   465.8  5223.8  467.74
  5282.2  469.45  5327.2  471.25  5430.2  477.94  5436.4  478.72  5442.1   478.6
  5458.2  479.44  5464.4  480.27  5555.5  484.42  5621.8  488.36  5635.3  489.18
#Mann= 6 ,-1 , 0
  4704.6     .16       0  4884.3     .12       0  4995.6     .07       0
  5001.6     .12       0  5093.3     .16       0  5621.8     .05       0
Bank Sta=4960.5,5122.8
XS Rating Curve= 0 ,0
Exp/Cntr=0.3,0.1

Type RM Length L Ch R = 1 ,6778    ,405,405,405
BEGIN DESCRIPTION:
UNT 181 in LFCCL Watershed 9.0
END DESCRIPTION:
XS GIS Cut Line= 3
      2776824.99        7038675.        2777125.        7038625.
      2777725.04      7038224.98
#Sta/Elev= 30
  4668.8  481.31  4719.5  479.75  4800.6  475.74  4861.4  471.82  4879.2   469.7
  4884.2  470.11  4912.1  466.14  4935.3  464.38  4952.7   463.7    4976  464.48
  4980.5  462.07  4986.5  464.33  4995.5  458.82  5001.5  463.28    5009   459.1
  5016.5   460.8  5019.5  458.13    5020  457.33    5025  457.33  5025.5  458.13
  5031.5  464.03  5058.6  463.96  5073.6  463.02  5081.1  464.39  5190.1  466.66
  5289.9  468.72  5398.6  473.06  5506.3  477.63  5665.4  486.04  5694.1   488.4
#Mann= 6 ,-1 , 0
  4668.8     .16       0  5019.5     .07       0  5025.5     .16       0
  5190.1     .05       0  5398.6     .16       0  5665.4     .05       0
Bank Sta=4935.3,5081.1
XS Rating Curve= 0 ,0
Exp/Cntr=0.3,0.1

Type RM Length L Ch R = 1 ,6373    ,463,463,463
BEGIN DESCRIPTION:
UNT 181 in LFCCL Watershed 8.0
END DESCRIPTION:
XS GIS Cut Line= 3
      2776975.02        7038825.        2777375.        7038825.
      2777775.03      7038374.97
#Sta/Elev= 30
  4615.2  477.37  4685.2  474.31  4885.2  463.85  4915.2   462.8  4965.2  462.77
  4986.5  462.05  4995.2  460.73  5002.2  455.96  5002.7  455.16  5007.7  455.16
  5008.2  455.96  5012.7  461.62  5022.3  461.32  5026.4  462.05    5029  462.51
  5048.1  462.61  5075.4  463.25  5093.4  462.89  5100.1  463.64  5107.6  463.06
  5121.8  464.83  5142.7  466.42  5203.6  468.08  5277.3  470.46  5354.4  473.78
  5468.8  479.96  5489.7  481.55    5504  481.86  5613.6  487.63  5617.3  487.65
#Mann= 8 ,-1 , 0
  4615.2     .16       0  5002.2     .07       0  5008.2     .16       0
  5048.1     .12       0  5075.4     .16       0  5203.6     .05       0
  5354.4     .16       0  5613.6     .05       0
Bank Sta=4986.5,5026.4
XS Rating Curve= 0 ,0
Exp/Cntr=0.3,0.1

Type RM Length L Ch R = 1 ,5910    ,272,272,272
BEGIN DESCRIPTION:
UNT 181 in LFCCL Watershed 7.0
END DESCRIPTION:
XS GIS Cut Line= 3
      2777174.96      7039124.99        2777475.        7039175.
      2777825.03      7038874.97
#Sta/Elev= 30
  4688.5  469.77  4759.5  467.25  4782.3  467.32  4804.8  465.43  4860.9  462.21
  4904.8  460.93  4921.7  460.82  4931.9  459.95  4952.1   460.3  4959.5  459.85
  4972.4   459.7  4976.7  457.49  4982.5   454.5  4996.1  454.66  4996.8  454.33
  4997.3  453.53  5002.3  453.53  5002.8  454.33  5006.3  459.85  5008.9  460.11
  5134.8  462.52  5155.7  461.71  5163.4  462.08  5169.9  461.44  5184.2   462.9
  5190.8  462.78    5227  465.06  5269.3  465.73  5325.8  467.58  5453.7  473.97
#Mann= 8 ,-1 , 0
  4688.5     .12       0  4804.8     .16       0  4904.8     .12       0
  4976.7     .16       0  4996.1     .12       0  4996.8     .07       0
  5002.8     .12       0  5008.9     .16       0
Bank Sta=4959.5,5006.3
XS Rating Curve= 0 ,0
Exp/Cntr=0.3,0.1

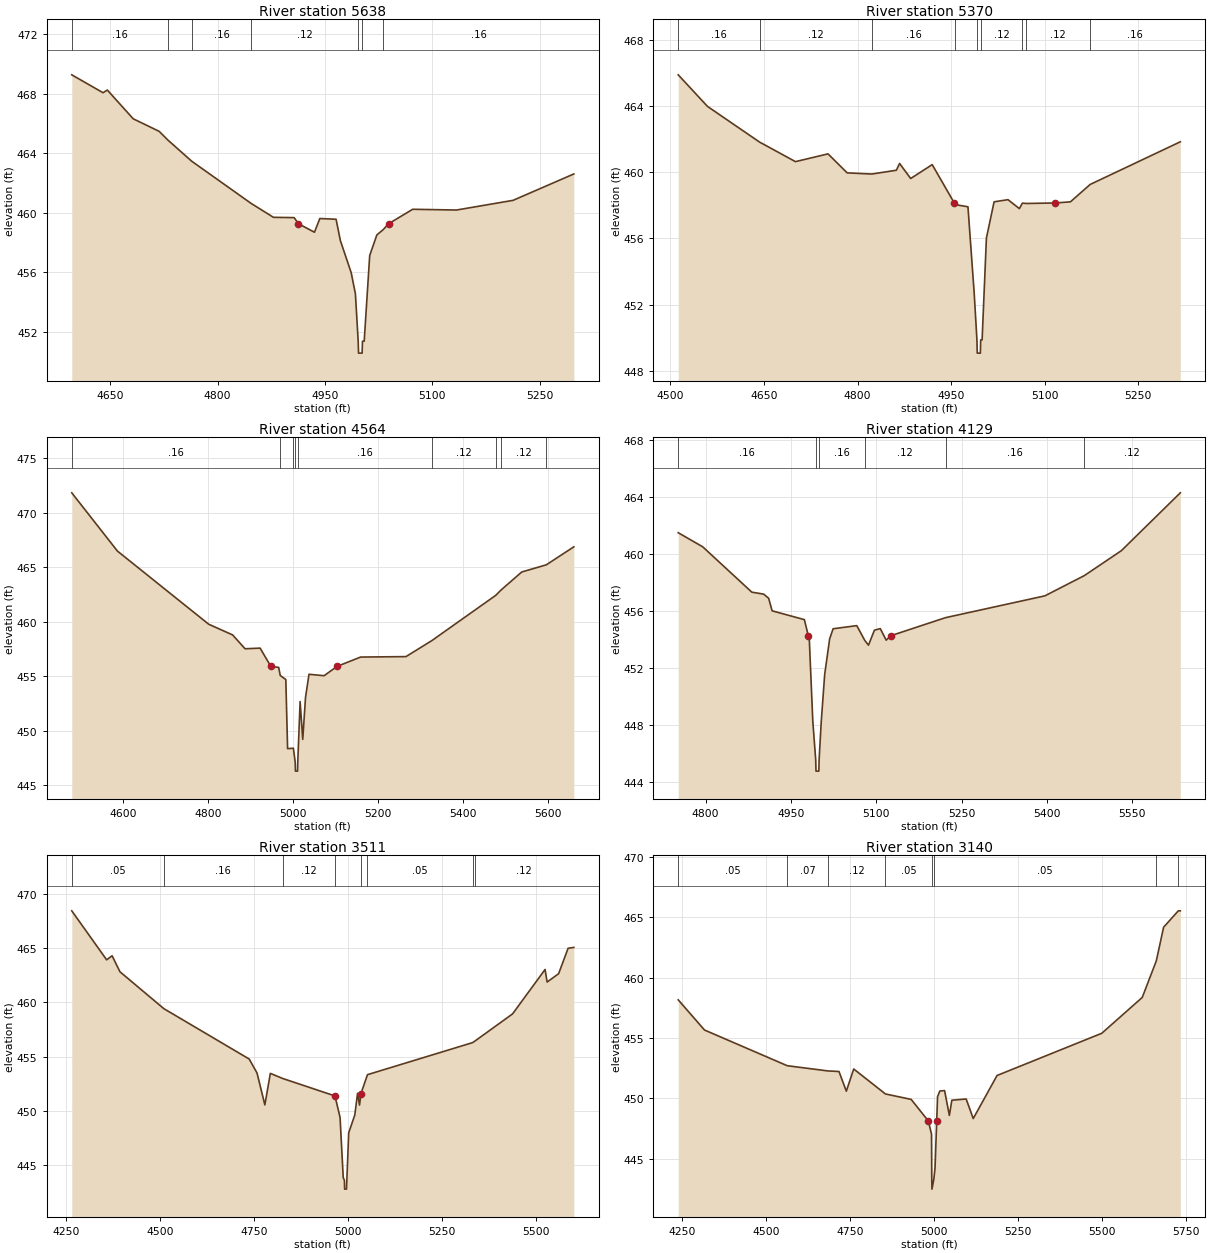
Type RM Length L Ch R = 1 ,5638    ,268,268,268
BEGIN DESCRIPTION:
UNT 181 in LFCCL Watershed 6.0
END DESCRIPTION:
XS GIS Cut Line= 3
      2777174.99      7039174.99      2777514.71       7039397.5
       2777809.8      7039380.14
#Sta/Elev= 30
  4596.1  469.26  4639.8  468.06  4645.8  468.24    4682  466.31  4718.2  465.47
  4730.3  464.89  4763.6  463.47  4846.9  460.63    4878   459.7  4906.9  459.68
  4912.9  459.27  4935.3   458.7  4942.8  459.62  4965.5  459.57  4971.5  458.14
  4986.6  455.99  4992.5  454.58  4996.4  451.39  4996.9  450.59  5001.9  450.59
  5002.4  451.39  5004.8  451.39  5012.5  457.14  5022.5  458.52  5031.5  458.88
  5038.9  459.27  5072.6  460.24  5133.8  460.19  5212.9  460.84  5297.8  462.61
#Mann= 7 ,-1 , 0
  4596.1     .16       0  4730.3     .12       0  4763.6     .16       0
  4846.9     .12       0  4996.4     .07       0  5002.4     .12       0
  5031.5     .16       0
Bank Sta=4912.9,5038.9
XS Rating Curve= 0 ,0
Exp/Cntr=0.3,0.1

Type RM Length L Ch R = 1 ,5370    ,806,806,806
BEGIN DESCRIPTION:
XS4071A
END DESCRIPTION:
XS GIS Cut Line= 3
      2777038.97       7039685.7      2777514.71      7039595.41
      2777809.89      7039470.39
#Sta/Elev= 30
  4512.6  465.89  4559.5  463.98  4643.1  461.82  4700.5  460.64  4752.7  461.11
  4783.4  459.96  4822.7  459.89  4862.3  460.12  4867.4  460.53  4885.2  459.62
  4919.7  460.46  4955.1  458.14  4956.8  458.04    4977  457.91    4987  452.69
  4991.4  449.86  4991.9  449.06  4996.9  449.06  4997.4  449.86  4999.7  449.86
  5006.6  456.02  5018.9  458.21  5041.2  458.34  5059.4   457.8  5064.3  458.13
  5070.7  458.11    5117  458.14  5141.3  458.21  5172.9  459.26  5317.4  461.84
#Mann= 9 ,-1 , 0
  4512.6     .16       0  4643.1     .12       0  4822.7     .16       0
  4956.8     .12       0  4991.4     .07       0  4997.4     .12       0
  5064.3     .16       0  5070.7     .12       0  5172.9     .16       0
Bank Sta=4955.1,5117
XS Rating Curve= 0 ,0
Exp/Cntr=0.3,0.1

Type RM Length L Ch R = 1 ,4564    ,435,435,435
BEGIN DESCRIPTION:
UNT 181 in LFCCL Watershed 5.0
END DESCRIPTION:
XS GIS Cut Line= 3
      2777175.02      7040274.99        2777575.        7039975.
      2777975.03      7039424.96
#Sta/Elev= 30
  4479.7  471.81    4587  466.47  4801.6  459.76  4857.8  458.78    4887  457.51
  4922.4  457.57  4947.7  455.89  4966.1   455.8  4969.7  455.06  4982.8  454.69
    4987  448.35  5000.6  448.39  5004.9  447.09  5005.4  446.29  5010.4  446.29
  5010.9  447.09  5016.4  452.67  5022.6   449.2  5029.1  453.04  5037.3  455.17
  5072.8  455.04  5103.1  455.89  5158.6  456.75  5265.2  456.79  5325.7  458.25
  5476.3  462.41  5488.2  462.88  5537.3  464.55  5595.2  465.21  5659.8  466.86
#Mann= 9 ,-1 , 0
  4479.7     .16       0  4969.7     .12       0  5000.6     .16       0
  5004.9     .07       0  5010.9     .16       0  5325.7     .12       0
  5476.3     .16       0  5488.2     .12       0  5595.2     .05       0
Bank Sta=4947.7,5103.1
XS Rating Curve= 0 ,0
Exp/Cntr=0.3,0.1

Type RM Length L Ch R = 1 ,4129    ,618,618,618
BEGIN DESCRIPTION:
UNT 181 in LFCCL Watershed 4.0
END DESCRIPTION:
XS GIS Cut Line= 3
      2777625.01      7040374.98      2777792.49      7040137.08
      2777941.58      7039564.72
#Sta/Elev= 30
  4751.9  461.49    4795   460.5  4881.2  457.32  4902.1  457.18  4910.8  456.89
  4916.9  456.01  4973.6  455.39  4980.5  454.26  4982.3  453.97  4988.4  448.27
  4993.5  445.56    4994  444.76    4999  444.76  4999.5  445.56  5003.2  448.21
  5009.3  451.55    5018  454.04  5024.1  454.75  5065.7  454.97  5079.8  453.93
  5086.3   453.6  5096.7  454.65    5107  454.76  5117.4  453.95  5125.3  454.26
  5221.7  455.53  5396.3  457.06  5465.6  458.48  5530.7  460.23  5634.3  464.29
#Mann= 6 ,-1 , 0
  4751.9     .16       0  4993.5     .07       0  4999.5     .16       0
  5079.8     .12       0  5221.7     .16       0  5465.6     .12       0
Bank Sta=4980.5,5125.3
XS Rating Curve= 0 ,0
Exp/Cntr=0.3,0.1

Type RM Length L Ch R = 1 ,3511    ,371,371,371
BEGIN DESCRIPTION:
UNT 181 in LFCCL Watershed 3.0
END DESCRIPTION:
XS GIS Cut Line= 3
        2777725.        7040675.        2778175.        7040075.
      2777975.01      7039525.03
#Sta/Elev= 30
  4265.9  468.43  4358.6  463.92  4373.2  464.29    4394  462.82  4510.8  459.42
  4737.8  454.78  4758.6  453.49  4779.4  450.56    4794  453.46  4826.9  452.99
  4965.9  451.38  4979.4   449.4  4987.8  443.87    4991   443.6  4991.5   442.8
  4996.5   442.8  5002.4  447.99  5018.6  449.63  5025.9  451.62  5031.2  450.54
  5034.9  451.59  5052.3  453.34  5331.6  456.29    5337  456.41  5438.2  458.94
  5524.6  463.03    5530  461.87  5560.6  462.64  5585.8  464.98  5601.1  465.06
#Mann= 8 ,-1 , 0
  4265.9     .05       0  4510.8     .16       0  4826.9     .12       0
  4965.9     .07       0  5034.9     .12       0  5052.3     .05       0
  5331.6     .16       0    5337     .12       0
Bank Sta=4965.9,5034.9
XS Rating Curve= 0 ,0
Exp/Cntr=0.3,0.1

Type RM Length L Ch R = 1 ,3140    ,395,395,395
BEGIN DESCRIPTION:
UNT 181 in LFCCL Watershed 2.0
END DESCRIPTION:
XS GIS Cut Line= 3
      2778075.01      7040624.99        2778525.        7040025.
      2778024.99      7039474.99
#Sta/Elev= 30
  4239.6  458.17  4317.7  455.67  4563.9  452.71  4684.1  452.28  4717.7  452.23
  4739.6   450.6  4761.5  452.44  4855.8  450.37  4932.3  449.92  4983.3  448.14
    4993  447.04  4993.7  443.28  4994.2  442.48  4999.7  443.28  5003.4  444.23
  5008.4  448.14  5010.9  450.15  5017.6  450.61  5031.8  450.65    5046  448.59
  5053.4  449.85    5096  449.95    5117  448.33  5187.9   451.9  5499.4   455.4
  5619.7  458.37  5661.5   461.4  5683.2  464.19    5727  465.55  5732.9  465.55
#Mann= 8 ,-1 , 0
  4239.6     .05       0  4563.9     .07       0  4684.1     .12       0
  4855.8     .05       0  4993.7     .03       0  4999.7     .05       0
  5661.5     .12       0    5727     .05       0
Bank Sta=4983.3,5008.4
XS Rating Curve= 0 ,0
Exp/Cntr=0.3,0.1

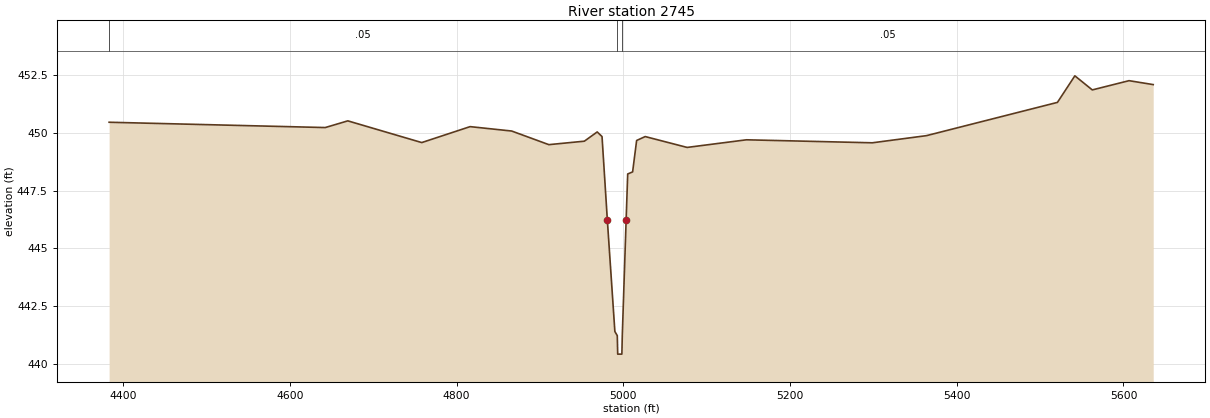
Type RM Length L Ch R = 1 ,2745    ,0,0,0
BEGIN DESCRIPTION:
UNT 181 in LFCCL Watershed 1.0
END DESCRIPTION:
XS GIS Cut Line= 3
      2778540.77      7040565.86        2778875.        7040025.
      2778514.71      7039524.24
#Sta/Elev= 30
    4383  450.46  4642.3  450.23  4669.4  450.52  4758.1  449.58  4816.1  450.27
    4866  450.08  4910.6  449.49  4953.2  449.64  4968.6  450.04  4974.4  449.84
  4980.8  446.21  4989.8   441.4  4992.7  441.22  4993.2  440.42  4998.2  440.42
  4998.7  441.22  5003.3  446.21  5005.2  448.22  5011.1  448.31  5015.9  449.67
  5026.2  449.84  5076.5  449.37  5147.7   449.7  5298.7  449.57  5363.7  449.88
  5520.8  451.32  5541.7  452.47  5562.6  451.86  5606.7  452.26  5635.7  452.09
#Mann= 3 ,-1 , 0
    4383     .05       0  4992.7     .03       0  4998.7     .05       0
Bank Sta=4980.8,5003.3
XS Rating Curve= 0 ,0
Exp/Cntr=0.3,0.1
LCMann Table=0

Chan Stop Cuts=-1
Use User Specified Reach Order=0
Composite Channel Slope=5