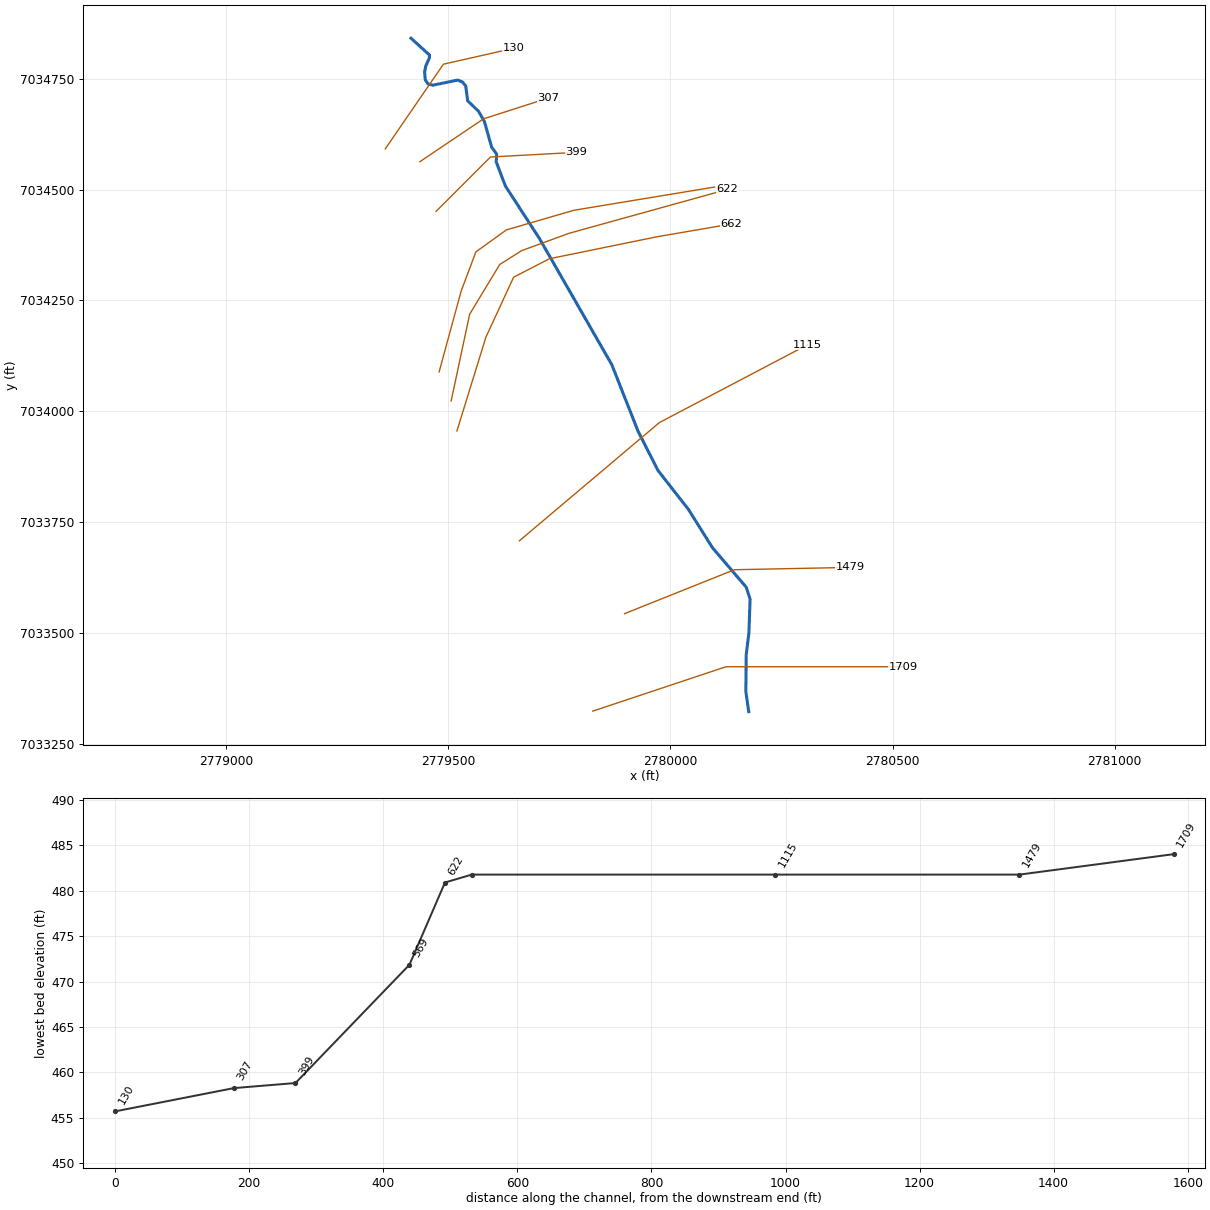
--- UNT 183 in LFCCL Watershed.prj (project) ---

Proj Title=UNT 183 in LFCCL Watershed Base Level Engineering
Current Plan=p01
Default Exp/Contr=0.3,0.1
English Units
Geom File=g01
Flow File=f01
Plan File=p01
BEGIN DESCRIPTION:
UNT 183 in LFCCL Watershed
END DESCRIPTION:

--- UNT 183 in LFCCL Watershed.p01 (plan) ---

Plan Title=Multiple Run
Short Identifier=Multiple
Geom File=g01
Flow File=f01
Subcritical Flow
K Sum by GR= 0
Std Step Tol= 0.01
Critical Tol= 0.01
Num of Std Step Trials= 20
Max Error Tol= 0.3
Flow Tol Ratio= 0.001
Split Flow NTrial= 30
Split Flow Tol= 0.02
Split Flow Ratio= 0.02
Log Output Level= 0
Friction Slope Method= 1
Unsteady Friction Slope Method= 2
Unsteady Bridges Friction Slope Method= 1
Parabolic Critical Depth
Global Vel Dist=  1 , 1 , 1
Global Log Level= 0
CheckData=True
Encroach Param= -1, 0, 0, 0
BEGIN DESCRIPTION:
Multiple Run
END DESCRIPTION:

--- UNT 183 in LFCCL Watershed.f01 (steady flow) ---

Flow Title=Multiple
Number of Profiles=7
Profile Names=10-year,25-year,50-year,1pct_min,100-year,1pct_plu,500-year
River Rch & RM= UNT 183 in LFCCL,Reach-1,1709
     158     196     225     130     259     517     340
Boundary for River Rch & Prof#=UNT 183 in LFCCL,Reach-1,1
Up Type=0
Dn Type=3
Dn Slope=0.005
Boundary for River Rch & Prof#=UNT 183 in LFCCL,Reach-1,2
Up Type=0
Dn Type=3
Dn Slope=0.005
Boundary for River Rch & Prof#=UNT 183 in LFCCL,Reach-1,3
Up Type=0
Dn Type=3
Dn Slope=0.005
Boundary for River Rch & Prof#=UNT 183 in LFCCL,Reach-1,4
Up Type=0
Dn Type=3
Dn Slope=0.005
Boundary for River Rch & Prof#=UNT 183 in LFCCL,Reach-1,5
Up Type=0
Dn Type=3
Dn Slope=0.005
Boundary for River Rch & Prof#=UNT 183 in LFCCL,Reach-1,6
Up Type=0
Dn Type=3
Dn Slope=0.005
Boundary for River Rch & Prof#=UNT 183 in LFCCL,Reach-1,7
Up Type=0
Dn Type=3
Dn Slope=0.005

--- UNT 183 in LFCCL Watershed.g01 (geometry) ---

Geom Title=Existing Conditions

River Reach=UNT 183 in LFCCL,Reach-1
Reach XY= 30
      2780176.20      7033323.76      2780169.69      7033368.90
      2780170.56      7033452.23      2780176.64      7033501.71
      2780179.24      7033577.23      2780170.56      7033604.14
      2780094.17      7033693.55      2780040.35      7033779.49
      2779971.78      7033867.16      2779926.74      7033956.02
      2779867.79      7034105.41      2779705.03      7034389.27
      2779628.21      7034507.76      2779607.38      7034562.45
      2779608.58      7034579.66      2779597.17      7034595.42
      2779580.76      7034653.44      2779567.45      7034676.54
      2779543.19      7034699.74      2779538.82      7034733.48
      2779531.28      7034742.17      2779520.62      7034746.48
      2779464.65      7034734.98      2779453.98      7034737.63
      2779447.69      7034746.77      2779446.21      7034764.73
      2779448.87      7034778.51      2779457.17      7034796.79
      2779457.11      7034803.07      2779415.59      7034840.71

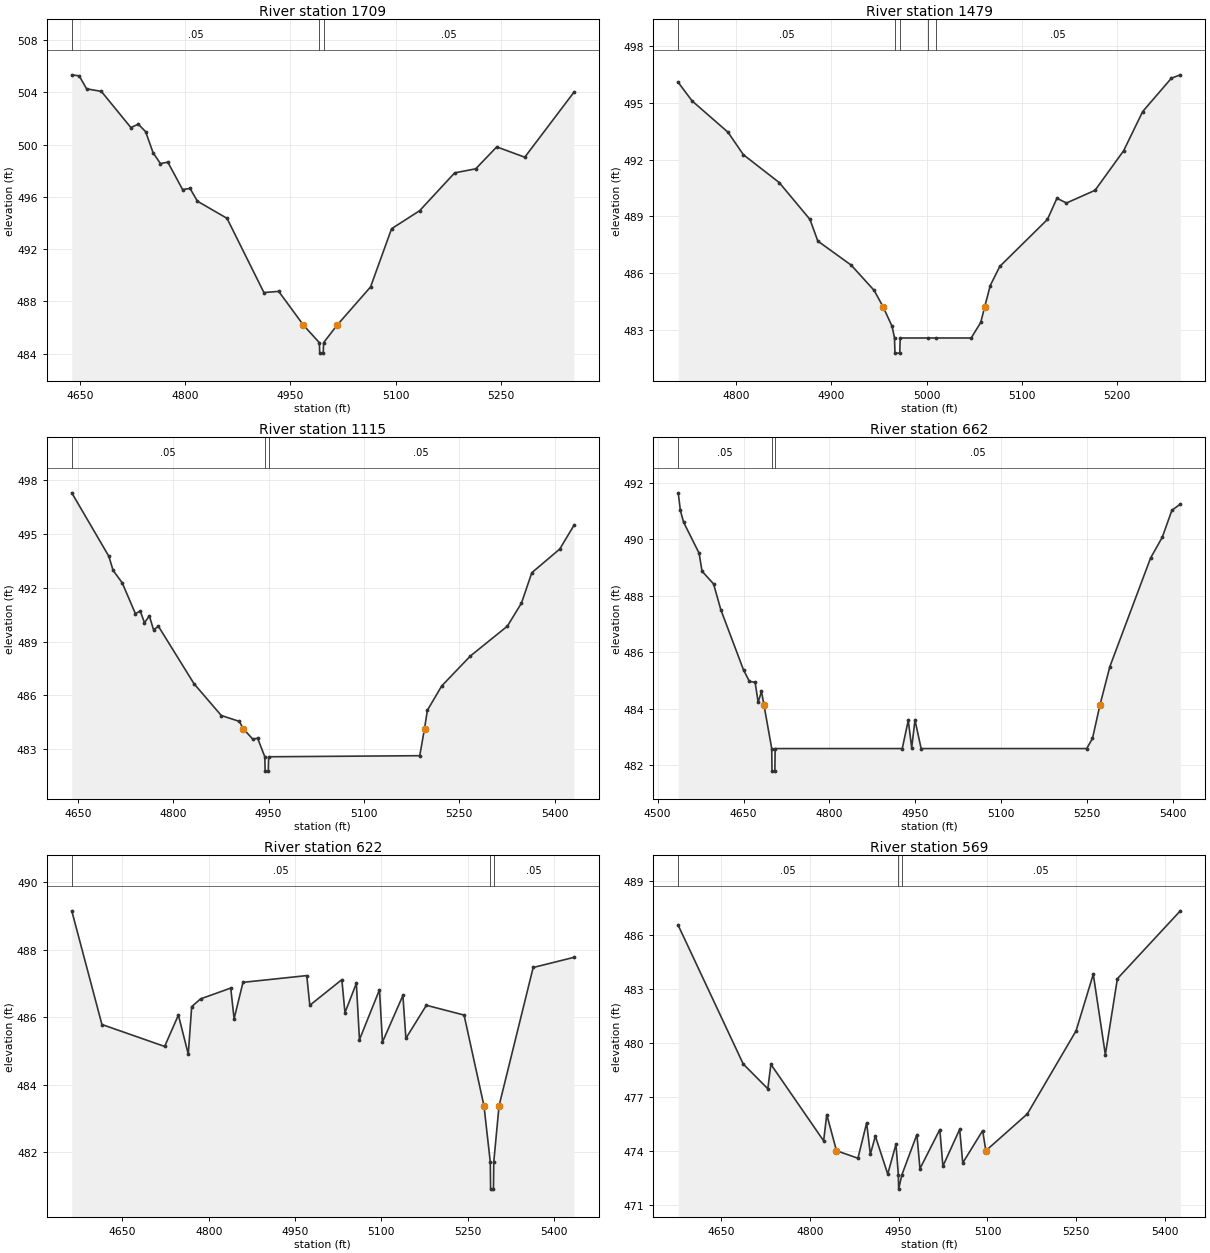
Type RM Length L Ch R = 1,1709,230,230,230
BEGIN DESCRIPTION:
UNT 183 in LFCCL Watershed 3.0
END DESCRIPTION:
XS GIS Cut Line= 3
      2779824.99      7033325.00      2780125.00      7033425.00
      2780524.96      7033425.00
#Sta/Elev= 30
  4638.2  505.35  4648.8  505.27  4659.3  504.28  4680.4  504.08  4722.5  501.31
  4733.1  501.57  4743.6  500.99  4754.2  499.38  4764.7  498.55  4775.2  498.66
  4796.3  496.56  4806.9  496.65  4817.4  495.67  4859.6  494.36  4912.3  488.67
  4933.4  488.76  4968.6  486.18  4991.4  484.83  4991.9  484.03  4996.9  484.03
  4997.4  484.83  5016.8  486.18  5064.4  489.10  5094.4  493.56  5134.4  494.94
  5184.4  497.84  5214.4  498.15  5244.4  499.83  5284.4  499.04  5354.4  504.01
#Mann=3,-1,0
  4638.2    0.05       0  4991.4    0.03       0  4997.4    0.05       0
Bank Sta=4968.6,5016.8
Exp/Cntr=0.3,0.1

Type RM Length L Ch R = 1,1479,364,364,364
BEGIN DESCRIPTION:
XS4077A
END DESCRIPTION:
XS GIS Cut Line= 3
      2779896.56      7033544.57      2780144.00      7033643.55
      2780404.45      7033648.75
#Sta/Elev= 30
  4739.2  496.08  4753.8  495.10  4791.4  493.45  4807.6  492.26  4845.2  490.79
  4877.5  488.84  4885.7  487.70  4920.7  486.43  4944.9  485.09  4954.4  484.21
  4963.7  483.19  4966.2  482.58  4966.7  481.78  4971.7  481.78  4972.2  482.58
  5001.1  482.58  5009.9  482.58  5046.7  482.58  5056.7  483.40  5060.8  484.21
  5066.7  485.35  5076.7  486.36  5126.7  488.84  5136.7  489.96  5146.7  489.71
  5176.7  490.38  5206.7  492.47  5226.7  494.54  5256.8  496.30  5266.2  496.48
#Mann=5,-1,0
  4739.2    0.05       0  4966.2    0.03       0  4972.2    0.05       0
  5001.1     0.1       0  5009.9    0.05       0
Bank Sta=4954.4,5060.8
Exp/Cntr=0.3,0.1

Type RM Length L Ch R = 1,1115,453,453,453
BEGIN DESCRIPTION:
UNT 183 in LFCCL Watershed 2.0
END DESCRIPTION:
XS GIS Cut Line= 3
      2779659.66      7033708.68      2779975.00      7033975.00
      2780309.05      7034150.51
#Sta/Elev= 30
  4640.3  497.29  4698.7  493.75  4705.3  492.97  4719.6  492.28  4740.4  490.56
  4748.1  490.70  4754.7  490.05  4762.4  490.43  4769.0  489.66  4776.7  489.85
  4832.7  486.65  4875.6  484.88  4904.2  484.55  4909.9  484.15  4925.0  483.57
  4932.8  483.61  4944.1  482.58  4944.6  481.78  4949.6  481.78  4950.1  482.58
  5187.9  482.64  5195.4  484.15  5199.9  485.17  5222.5  486.53  5267.7  488.20
  5325.8  489.86  5347.9  491.14  5364.3  492.84  5408.3  494.16  5430.4  495.47
#Mann=3,-1,0
  4640.3    0.05       0  4944.1   0.033       0  4950.1    0.05       0
Bank Sta=4909.9,5195.4
Exp/Cntr=0.3,0.1

Type RM Length L Ch R = 1,662,40,40,40
BEGIN DESCRIPTION:
XS4076A
END DESCRIPTION:
XS GIS Cut Line= 6
      2779519.01      7033956.09      2779584.10      7034166.98
      2779646.60      7034302.40      2779727.33      7034344.07
      2779969.52      7034393.55      2780136.18      7034422.19
#Sta/Elev= 30
  4536.0  491.65  4539.7  491.03  4545.3  490.61  4572.4  489.51  4577.6  488.87
  4597.7  488.42  4610.3  487.51  4650.0  485.37  4660.4  484.96  4670.3  484.93
  4675.6  484.22  4681.4  484.61  4685.7  484.13  4699.3  482.58  4699.8  481.78
  4704.8  481.78  4705.3  482.58  4927.3  482.58  4937.8  483.58  4943.8  482.61
  4949.5  483.59  4960.3  482.58  5249.5  482.58  5259.6  482.94  5272.7  484.13
  5290.0  485.49  5361.1  489.34  5381.4  490.07  5398.3  491.03  5413.0  491.25
#Mann=3,-1,0
  4536.0    0.05       0  4699.3    0.03       0  4705.3    0.05       0
Bank Sta=4685.7,5272.7
Exp/Cntr=0.3,0.1

Type RM Length L Ch R = 1,622,53,53,53
BEGIN DESCRIPTION:
XS4075A
END DESCRIPTION:
XS GIS Cut Line= 6
      2779505.98      7034023.74      2779547.65      7034219.07
      2779615.35      7034331.05      2779664.83      7034362.30
      2779771.60      7034401.36      2780127.89      7034500.17
#Sta/Elev= 30
  4561.9  489.16  4614.3  485.79  4723.3  485.14  4747.2  486.07  4764.4  484.91
  4770.3  486.32  4785.8  486.55  4838.2  486.87  4844.0  485.96  4859.5  487.04
  4970.3  487.24  4975.6  486.36  5031.3  487.12  5036.7  486.14  5056.5  487.01
  5061.9  485.34  5096.7  486.82  5101.9  485.27  5137.4  486.65  5142.6  485.38
  5178.2  486.36  5243.7  486.07  5278.3  483.38  5289.3  481.71  5289.8  480.91
  5294.8  480.91  5295.3  481.71  5304.5  483.38  5363.8  487.48  5434.5  487.78
#Mann=3,-1,0
  4561.9    0.05       0  5289.3    0.03       0  5295.3    0.05       0
Bank Sta=5278.3,5304.5
Exp/Cntr=0.3,0.1

Type RM Length L Ch R = 1,569,170,170,170
BEGIN DESCRIPTION:
Mapping XS 78f43607
END DESCRIPTION:
XS GIS Cut Line= 6
      2779478.86      7034089.15      2779528.50      7034271.16
      2779561.60      7034359.42      2779630.55      7034409.07
      2779782.25      7034453.20      2780099.38      7034505.59
#Sta/Elev= 30
  4578.1  486.55  4687.8  478.83  4729.3  477.45  4734.5  478.81  4823.5  474.55
  4828.8  476.01  4845.2  474.00  4881.4  473.58  4896.1  475.55  4902.3  473.80
  4910.8  474.81  4931.7  472.70  4945.6  474.36  4949.6  472.66  4950.1  471.86
  4955.6  472.66  4980.9  474.90  4986.1  473.00  5019.6  475.18  5024.8  473.14
  5053.1  475.19  5058.3  473.32  5091.9  475.12  5097.3  474.00  5167.3  476.05
  5249.6  480.68  5278.6  483.83  5299.0  479.35  5319.3  483.58  5425.5  487.36
#Mann=3,-1,0
  4578.1    0.05       0  4949.6    0.03       0  4955.6    0.05       0
Bank Sta=4845.2,5097.3
Exp/Cntr=0.3,0.1

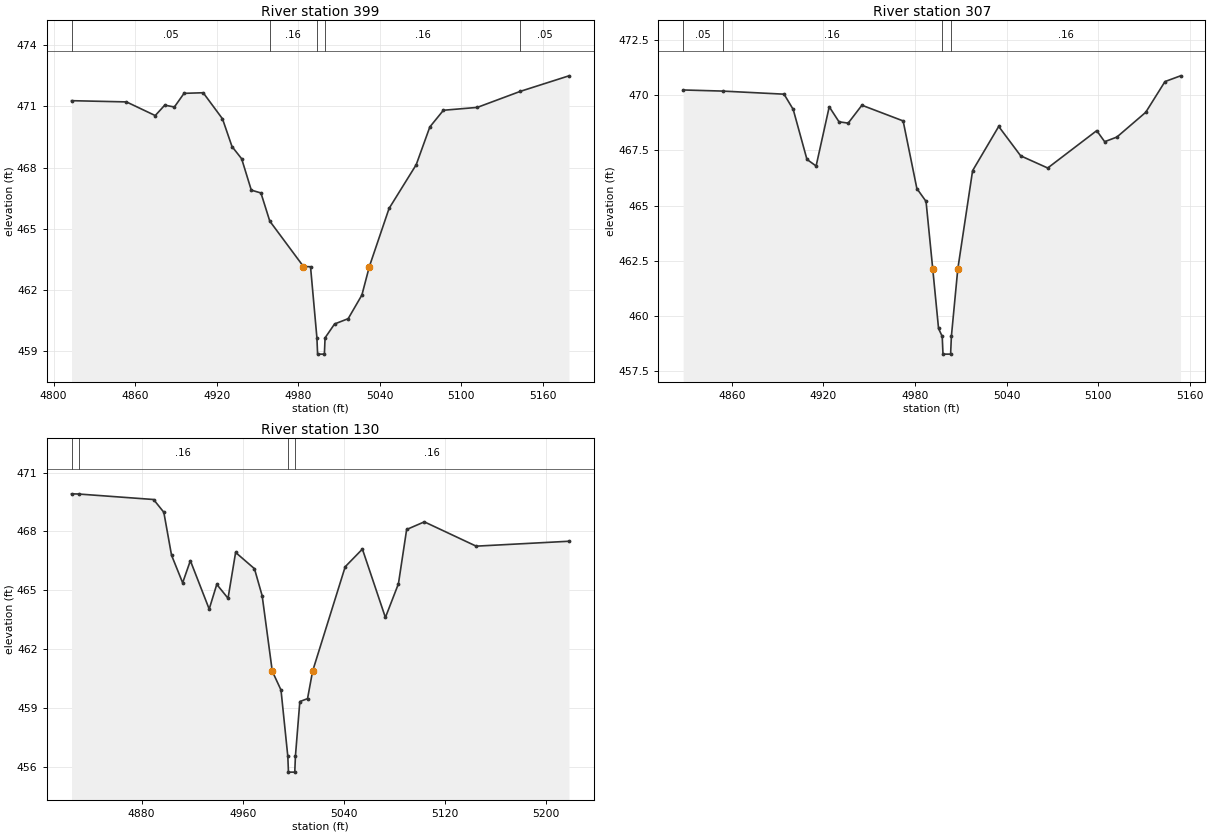
Type RM Length L Ch R = 1,399,92,92,92
BEGIN DESCRIPTION:
XS4074A
END DESCRIPTION:
XS GIS Cut Line= 3
      2779472.11      7034450.82      2779594.52      7034573.23
      2779787.22      7034583.65
#Sta/Elev= 30
  4813.2  471.28  4853.6  471.22  4874.8  470.55  4881.8  471.06  4888.9  470.97
  4896.0  471.64  4910.1  471.67  4924.3  470.39  4931.3  469.03  4938.4  468.43
  4945.5  466.89  4952.6  466.75  4959.1  465.37  4983.9  463.14  4989.1  463.13
  4993.8  459.64  4994.3  458.84  4999.3  458.84  4999.8  459.64  5006.8  460.32
  5016.8  460.58  5026.9  461.74  5032.4  463.14  5046.9  465.99  5066.9  468.14
  5076.9  469.99  5086.9  470.81  5111.8  470.95  5143.6  471.74  5179.3  472.50
#Mann=5,-1,0
  4813.2    0.05       0  4959.1    0.16       0  4993.8    0.07       0
  4999.8    0.16       0  5143.6    0.05       0
Bank Sta=4983.9,5032.4
Exp/Cntr=0.3,0.1

Type RM Length L Ch R = 1,307,177,177,177
BEGIN DESCRIPTION:
XS4072A
END DESCRIPTION:
XS GIS Cut Line= 3
      2779435.63      7034562.79      2779578.90      7034659.17
      2779724.69      7034706.03
#Sta/Elev= 30
  4828.1  470.23  4853.9  470.18  4894.2  470.04  4900.2  469.35  4909.2  467.09
  4915.2  466.79  4923.8  469.47  4930.2  468.79  4936.2  468.73  4945.2  469.54
  4972.2  468.83  4981.2  465.77  4987.2  465.19  4991.6  462.13  4995.4  459.44
  4997.8  459.08  4998.3  458.28  5003.3  458.28  5003.8  459.08  5008.0  462.13
  5017.7  466.58  5034.8  468.58  5049.2  467.25  5066.9  466.70  5099.0  468.39
  5104.2  467.89  5112.2  468.10  5131.1  469.22  5143.7  470.61  5153.9  470.87
#Mann=4,-1,0
  4828.1    0.05       0  4853.9    0.16       0  4997.8    0.07       0
  5003.8    0.16       0
Bank Sta=4991.6,5008
Exp/Cntr=0.3,0.1

Type RM Length L Ch R = 1,130,0,0,0
BEGIN DESCRIPTION:
UNT 183 in LFCCL Watershed 1.0
END DESCRIPTION:
XS GIS Cut Line= 3
      2779357.55      7034591.47      2779488.54      7034782.29
      2779646.59      7034818.02
#Sta/Elev= 30
  4824.6  469.92  4830.3  469.91  4889.5  469.63  4897.6  468.98  4903.7  466.79
  4912.5  465.38  4918.6  466.51  4933.5  464.04  4939.5  465.30  4948.4  464.59
  4954.4  466.93  4969.3  466.10  4975.4  464.72  4983.4  460.87  4990.3  459.91
  4995.7  456.52  4996.2  455.72  5001.2  455.72  5001.7  456.52  5005.2  459.32
  5011.3  459.47  5015.3  460.87  5041.1  466.20  5054.7  467.10  5072.9  463.61
  5083.2  465.33  5089.7  468.10  5103.7  468.49  5144.7  467.25  5218.1  467.50
#Mann=4,-1,0
  4824.6    0.05       0  4830.3    0.16       0  4995.7    0.07       0
  5001.7    0.16       0
Bank Sta=4983.4,5015.3
Exp/Cntr=0.3,0.1

Chan Stop Cuts=-1