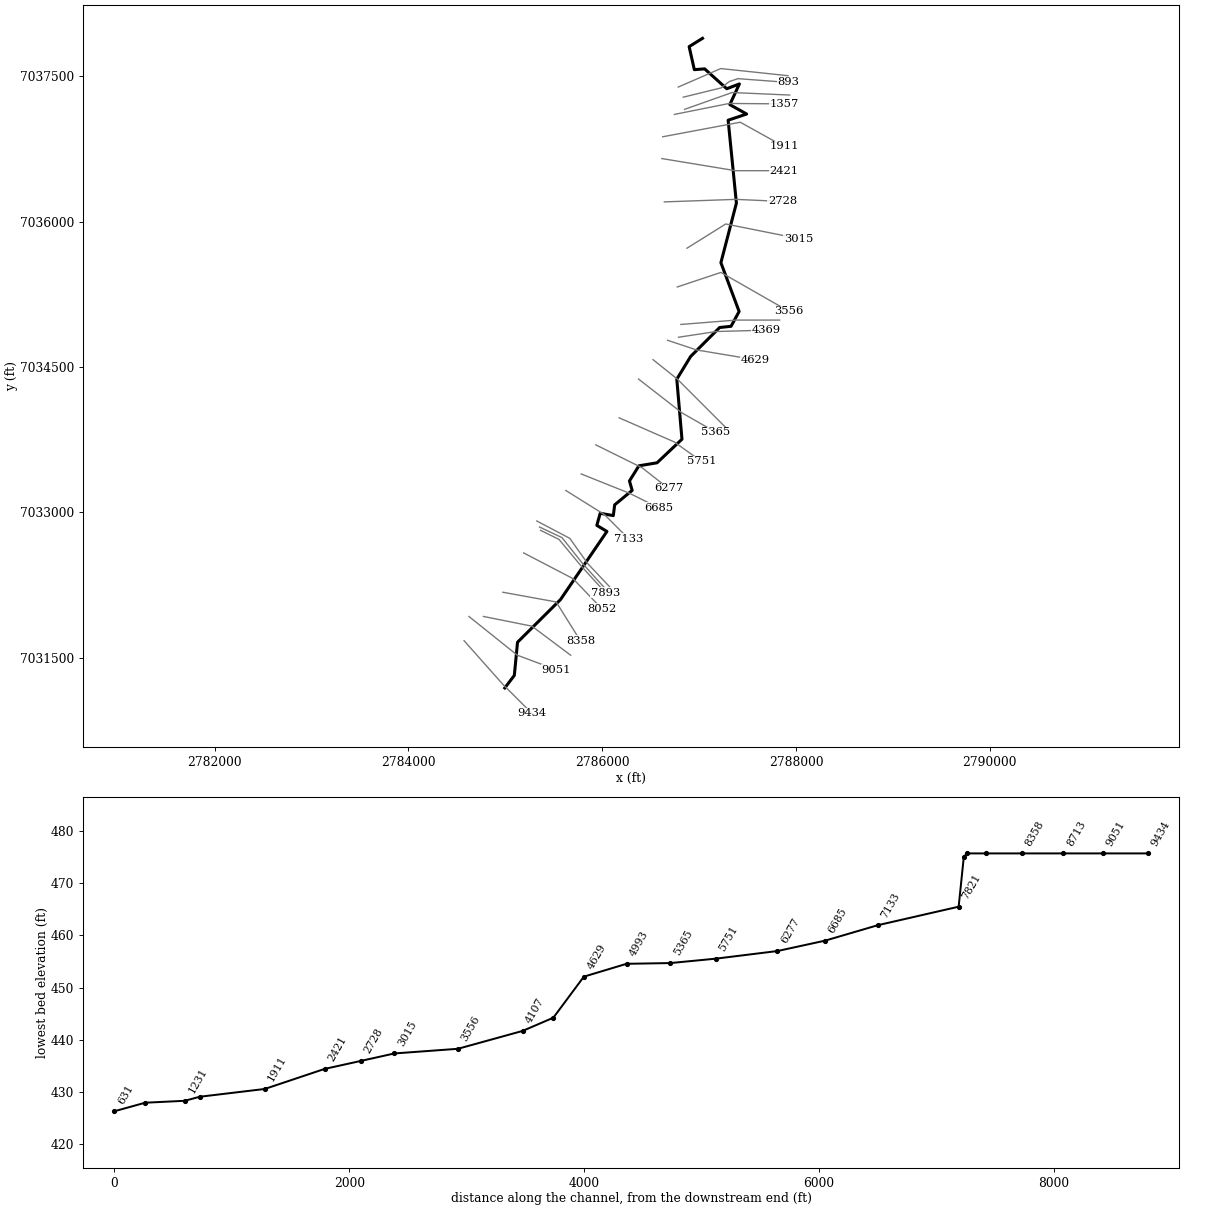
--- UNT 184 in LFCCL Watershed.prj (project) ---

Proj Title=UNT 184 in LFCCL Watershed Base Level Engineering
Current Plan=p01
Default Exp/Contr=0.3,0.1
English Units
Geom File=g01
Flow File=f01
Plan File=p01
BEGIN DESCRIPTION:
UNT 184 in LFCCL Watershed
END DESCRIPTION:

--- UNT 184 in LFCCL Watershed.p01 (plan) ---

Plan Title=Multiple Run
Short Identifier=Multiple
Geom File=g01
Flow File=f01
Subcritical Flow
K Sum by GR= 0
Std Step Tol= 0.01
Critical Tol= 0.01
Num of Std Step Trials= 20
Max Error Tol= 0.3
Flow Tol Ratio= 0.001
Split Flow NTrial= 30
Split Flow Tol= 0.02
Split Flow Ratio= 0.02
Log Output Level= 0
Friction Slope Method= 1
Unsteady Friction Slope Method= 2
Unsteady Bridges Friction Slope Method= 1
Parabolic Critical Depth
Global Vel Dist=  1 , 1 , 1
Global Log Level= 0
CheckData=True
Encroach Param= -1, 0, 0, 0
BEGIN DESCRIPTION:
Multiple Run
END DESCRIPTION:

--- UNT 184 in LFCCL Watershed.f01 (steady flow) ---

Flow Title=Multiple
Number of Profiles=7
Profile Names=10-year,25-year,50-year,1pct_min,100-year,1pct_plu,500-year
River Rch & RM= UNT 184 in LFCCL,Reach-1,9434
     469     618     736     437     871    1738    1221
River Rch & RM= UNT 184 in LFCCL,Reach-1,6685
     752    1018    1236     745    1486    2964    2153
Boundary for River Rch & Prof#=UNT 184 in LFCCL,Reach-1,1
Up Type=0
Dn Type=3
Dn Slope=0.005
Boundary for River Rch & Prof#=UNT 184 in LFCCL,Reach-1,2
Up Type=0
Dn Type=3
Dn Slope=0.005
Boundary for River Rch & Prof#=UNT 184 in LFCCL,Reach-1,3
Up Type=0
Dn Type=3
Dn Slope=0.005
Boundary for River Rch & Prof#=UNT 184 in LFCCL,Reach-1,4
Up Type=0
Dn Type=3
Dn Slope=0.005
Boundary for River Rch & Prof#=UNT 184 in LFCCL,Reach-1,5
Up Type=0
Dn Type=3
Dn Slope=0.005
Boundary for River Rch & Prof#=UNT 184 in LFCCL,Reach-1,6
Up Type=0
Dn Type=3
Dn Slope=0.005
Boundary for River Rch & Prof#=UNT 184 in LFCCL,Reach-1,7
Up Type=0
Dn Type=3
Dn Slope=0.005

--- UNT 184 in LFCCL Watershed.g01 (geometry) ---

Geom Title=Existing Conditions

River Reach=UNT 184 in LFCCL,Reach-1
Reach XY= 30
      2784995.10      7031187.34      2785093.55      7031316.41
      2785126.62      7031659.02      2785570.20      7032099.35
      2786049.13      7032802.46      2785944.96      7032864.96
      2785979.69      7032989.96      2786115.10      7032965.66
      2786128.99      7033076.77      2786309.55      7033226.07
      2786281.77      7033323.30      2786378.99      7033479.55
      2786566.49      7033510.80      2786823.44      7033753.85
      2786770.14      7034373.54      2786913.17      7034608.17
      2787212.16      7034906.70      2787330.02      7034919.23
      2787413.24      7035072.02      2787225.23      7035575.72
      2787385.26      7036190.24      2787299.99      7037045.89
      2787491.01      7037109.56      2787317.17      7037206.59
      2787416.13      7037420.14      2787285.59      7037370.71
      2787057.70      7037575.52      2786951.09      7037567.44
      2786897.51      7037805.15      2787035.59      7037890.71

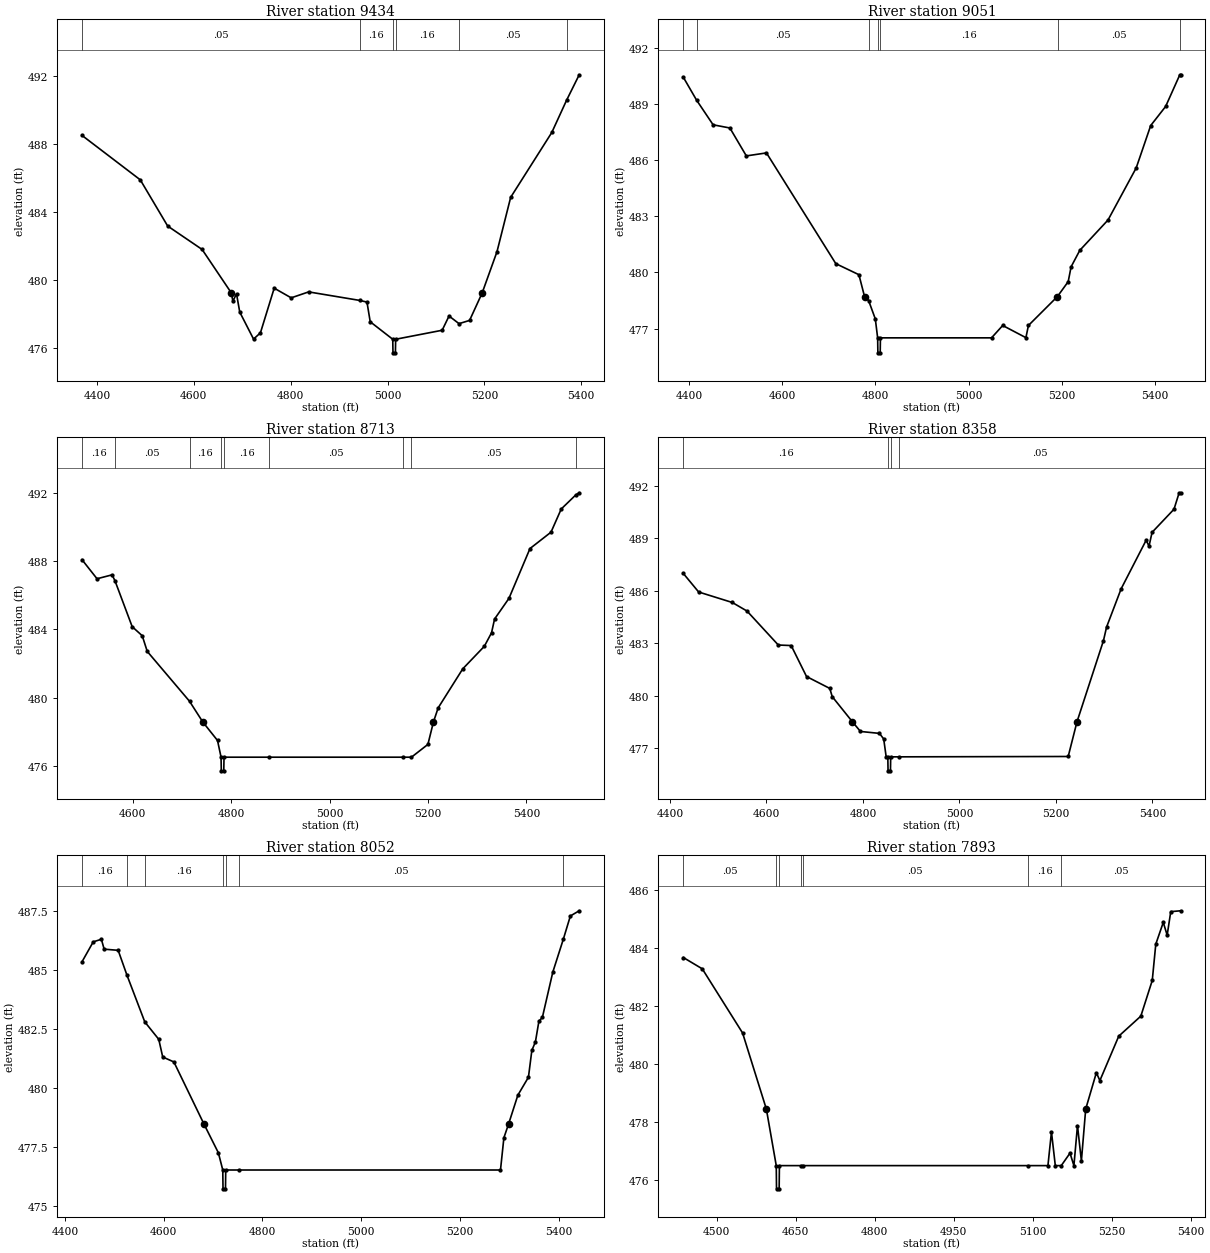
Type RM Length L Ch R = 1,9434,383,383,383
BEGIN DESCRIPTION:
UNT 184 in LFCCL Watershed 19.0
END DESCRIPTION:
XS GIS Cut Line= 3
      2784574.99      7031675.01      2784975.00      7031225.00
      2785275.03      7030924.97
#Sta/Elev= 30
  4369.3  488.52  4489.7  485.90  4546.2  483.18  4617.3  481.80  4677.6  479.24
  4680.8  478.75  4688.3  479.19  4695.0  478.11  4723.5  476.52  4737.7  476.89
  4766.1  479.52  4801.2  478.95  4837.2  479.30  4942.2  478.80  4957.6  478.70
  4964.3  477.54  5010.8  476.51  5011.3  475.71  5016.3  475.71  5016.8  476.51
  5112.8  477.04  5127.0  477.88  5147.6  477.43  5169.4  477.62  5195.4  479.24
  5226.0  481.67  5254.2  484.87  5339.1  488.69  5369.8  490.60  5395.7  492.09
#Mann=6,-1,0
  4369.3    0.05       0  4942.2    0.16       0  5010.8    0.07       0
  5016.8    0.16       0  5147.6    0.05       0  5369.8    0.08       0
Bank Sta=4677.6,5195.4
Exp/Cntr=0.3,0.1

Type RM Length L Ch R = 1,9051,338,338,338
BEGIN DESCRIPTION:
UNT 184 in LFCCL Watershed 18.0
END DESCRIPTION:
XS GIS Cut Line= 3
      2784625.01      7031924.99      2785125.00      7031525.00
      2785525.00      7031375.00
#Sta/Elev= 30
  4387.5  490.42  4415.9  489.20  4451.5  487.88  4487.5  487.71  4522.8  486.22
  4566.0  486.38  4714.9  480.47  4764.5  479.88  4776.6  478.71  4785.3  478.50
  4799.7  477.52  4804.7  476.51  4805.2  475.71  4810.2  475.71  4810.7  476.51
  5049.2  476.51  5073.2  477.17  5123.0  476.52  5128.4  477.17  5190.5  478.71
  5191.4  478.74  5213.8  479.51  5220.0  480.30  5238.7  481.18  5299.3  482.80
  5359.8  485.58  5390.9  487.84  5423.0  488.86  5453.4  490.55  5455.0  490.55
#Mann=7,-1,0
  4387.5    0.16       0  4415.9    0.05       0  4785.3    0.16       0
  4804.7    0.07       0  4810.7    0.16       0  5191.4    0.05       0
  5453.4    0.08       0
Bank Sta=4776.6,5190.5
Exp/Cntr=0.3,0.1

Type RM Length L Ch R = 1,8713,355,355,355
BEGIN DESCRIPTION:
UNT 184 in LFCCL Watershed 17.0
END DESCRIPTION:
XS GIS Cut Line= 3
      2784775.00      7031925.00      2785275.00      7031825.00
      2785675.00      7031525.00
#Sta/Elev= 30
  4497.2  488.09  4527.8  486.97  4558.4  487.20  4564.4  486.84  4599.2  484.16
  4619.6  483.63  4629.8  482.71  4715.6  479.79  4742.7  478.57  4772.5  477.49
  4779.7  476.51  4780.2  475.71  4785.2  475.71  4785.7  476.51  4877.1  476.51
  5149.3  476.51  5166.4  476.51  5199.8  477.26  5211.0  478.57  5220.6  479.40
  5270.6  481.69  5314.4  483.01  5329.0  483.80  5335.2  484.61  5364.4  485.82
  5407.1  488.74  5449.8  489.70  5470.6  491.06  5500.0  491.88  5507.1  492.01
#Mann=9,-1,0
  4497.2    0.16       0  4564.4    0.05       0  4715.6    0.16       0
  4779.7   0.033       0  4785.7    0.16       0  4877.1    0.05       0
  5149.3    0.16       0  5166.4    0.05       0  5500.0    0.08       0
Bank Sta=4742.7,5211
Exp/Cntr=0.3,0.1

Type RM Length L Ch R = 1,8358,306,306,306
BEGIN DESCRIPTION:
UNT 184 in LFCCL Watershed 16.0
END DESCRIPTION:
XS GIS Cut Line= 3
      2784975.01      7032175.00      2785525.00      7032075.00
      2785774.99      7031675.01
#Sta/Elev= 30
  4427.7  486.99  4459.5  485.93  4529.3  485.33  4559.8  484.84  4624.6  482.90
  4651.3  482.87  4683.1  481.10  4731.3  480.42  4736.4  479.95  4778.3  478.51
  4794.9  477.96  4834.3  477.85  4843.1  477.53  4848.2  476.51  4851.6  476.51
  4852.1  475.71  4857.1  475.71  4857.6  476.51  4875.8  476.51  5225.5  476.53
  5243.7  478.51  5298.6  483.15  5305.1  483.93  5335.2  486.11  5387.1  488.89
  5393.0  488.55  5399.4  489.34  5444.8  490.66  5455.5  491.60  5458.4  491.60
#Mann=4,-1,0
  4427.7    0.16       0  4851.6   0.033       0  4857.6    0.16       0
  4875.8    0.05       0
Bank Sta=4778.3,5243.7
Exp/Cntr=0.3,0.1

Type RM Length L Ch R = 1,8052,159,159,159
BEGIN DESCRIPTION:
XS4078A
END DESCRIPTION:
XS GIS Cut Line= 3
      2785189.94      7032580.65      2785697.41      7032316.60
      2785998.57      7032003.06
#Sta/Elev= 30
  4434.6  485.35  4457.4  486.20  4473.9  486.31  4479.5  485.89  4507.9  485.84
  4525.8  484.78  4561.8  482.80  4590.1  482.06  4598.1  481.31  4620.7  481.10
  4681.4  478.47  4710.8  477.24  4719.7  476.51  4720.2  475.71  4725.2  475.71
  4725.7  476.51  4751.9  476.51  5282.0  476.51  5288.9  477.88  5298.5  478.47
  5317.2  479.69  5338.6  480.45  5345.5  481.59  5352.7  481.95  5359.7  482.82
  5366.9  483.00  5388.0  484.92  5409.2  486.31  5423.5  487.30  5441.4  487.52
#Mann=7,-1,0
  4434.6    0.16       0  4525.8    0.12       0  4561.8    0.16       0
  4719.7   0.033       0  4725.7    0.16       0  4751.9    0.05       0
  5409.2    0.08       0
Bank Sta=4681.4,5298.5
Exp/Cntr=0.3,0.1

Type RM Length L Ch R = 1,7893,28,28,28
BEGIN DESCRIPTION:
XS4079A
END DESCRIPTION:
XS GIS Cut Line= 4
      2785364.10      7032814.13      2785554.23      7032720.37
      2785772.98      7032457.35      2786035.19      7032169.18
#Sta/Elev= 30
  4436.9  483.68  4472.9  483.29  4549.4  481.08  4594.5  478.46  4613.3  476.51
  4613.8  475.71  4618.8  475.71  4619.3  476.51  4660.4  476.51  4664.1  476.51
  5090.5  476.51  5128.9  476.51  5135.6  477.67  5142.9  476.51  5154.2  476.51
  5170.8  476.94  5178.2  476.51  5185.0  477.89  5192.4  476.67  5200.6  478.46
  5220.8  479.71  5227.5  479.44  5263.3  480.97  5305.2  481.66  5326.9  482.89
  5333.6  484.14  5347.8  484.89  5355.2  484.45  5362.0  485.26  5380.6  485.29
#Mann=7,-1,0
  4436.9    0.05       0  4613.3   0.033       0  4619.3    0.05       0
  4660.4    0.16       0  4664.1    0.05       0  5090.5    0.16       0
  5154.2    0.05       0
Bank Sta=4594.5,5200.6
Exp/Cntr=0.3,0.1

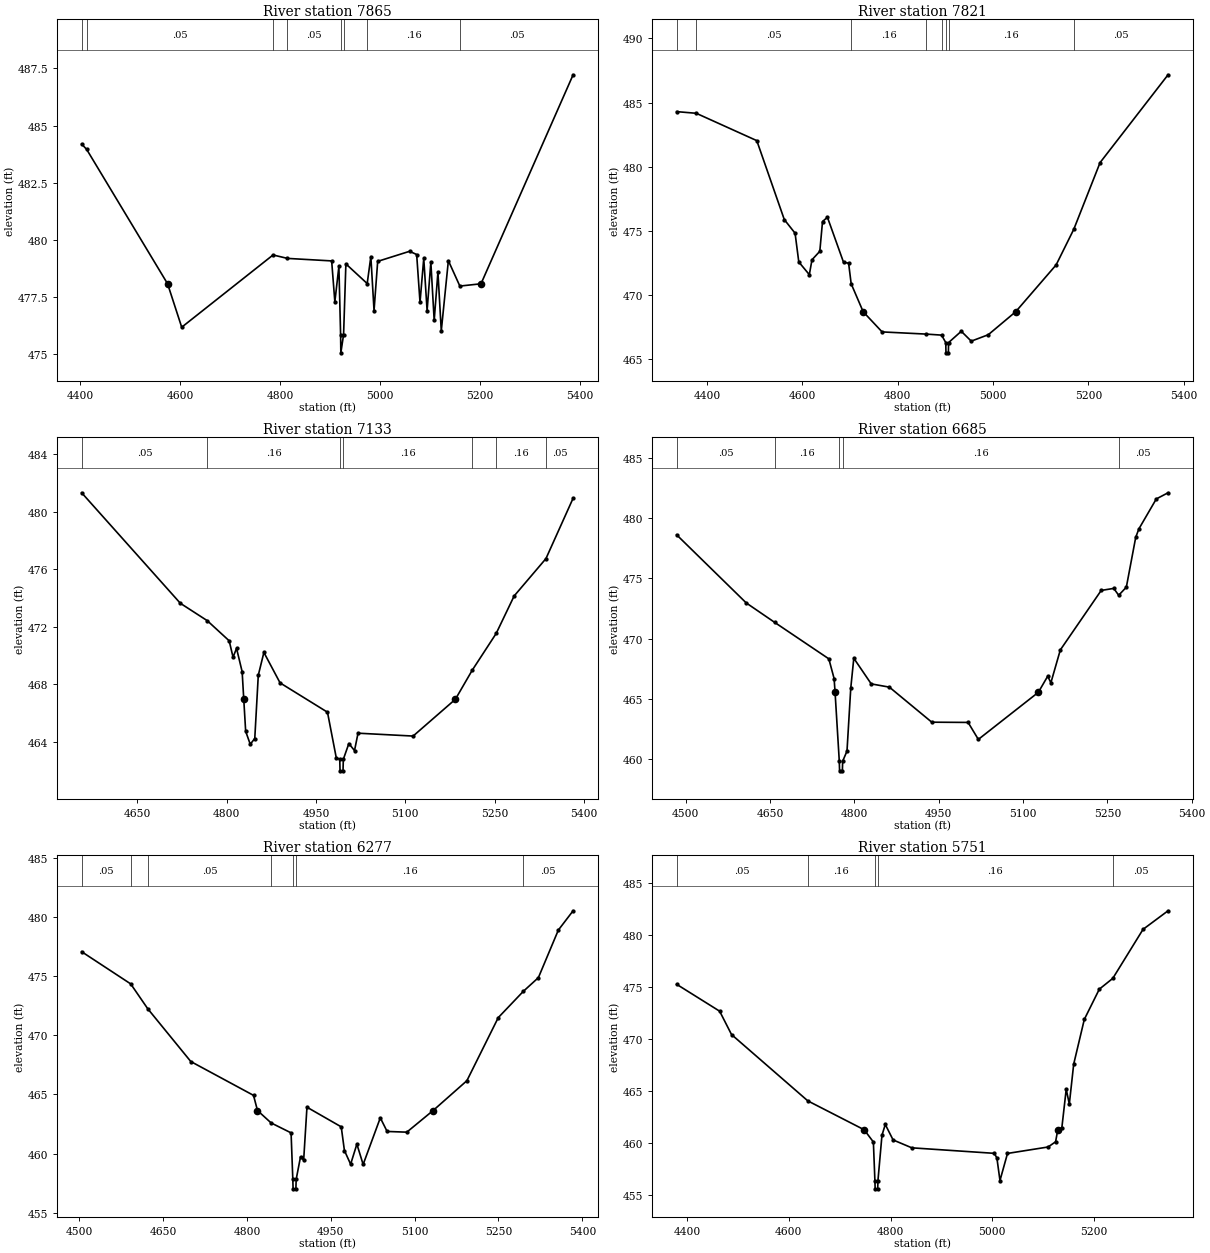
Type RM Length L Ch R = 1,7865,44,44,44
BEGIN DESCRIPTION:
XS4080A
END DESCRIPTION:
XS GIS Cut Line= 4
      2785353.73      7032847.97      2785585.48      7032738.60
      2785799.02      7032470.37      2786056.83      7032183.92
#Sta/Elev= 30
  4402.4  484.19  4412.3  483.96  4574.5  478.08  4602.8  476.18  4785.8  479.34
  4814.7  479.19  4903.2  479.08  4909.6  477.29  4917.7  478.84  4921.1  475.86
  4921.6  475.06  4927.1  475.86  4931.7  478.95  4974.4  478.09  4981.7  479.27
  4988.1  476.91  4995.4  479.06  5059.3  479.50  5073.5  479.36  5080.2  477.27
  5087.7  479.19  5094.4  476.91  5101.9  479.02  5108.6  476.48  5116.1  478.59
  5122.8  476.02  5137.0  479.09  5160.0  477.98  5202.4  478.08  5386.9  487.22
#Mann=8,-1,0
  4402.4    0.16       0  4412.3    0.05       0  4785.8    0.16       0
  4814.7    0.05       0  4921.1    0.07       0  4927.1    0.05       0
  4974.4    0.16       0  5160.0    0.05       0
Bank Sta=4574.5,5202.4
Exp/Cntr=0.3,0.1

Type RM Length L Ch R = 1,7821,688,688,688
BEGIN DESCRIPTION:
XS4081A
END DESCRIPTION:
XS GIS Cut Line= 4
      2785325.10      7032910.46      2785666.21      7032730.79
      2785851.10      7032470.37      2786075.08      7032233.38
#Sta/Elev= 30
  4336.0  484.30  4377.2  484.17  4504.2  482.04  4561.9  475.89  4584.5  474.83
  4592.3  472.59  4614.4  471.60  4620.0  472.76  4636.4  473.42  4642.1  475.74
  4652.4  476.07  4686.3  472.55  4696.8  472.50  4702.2  470.89  4727.4  468.71
  4767.1  467.14  4859.8  466.97  4891.9  466.89  4900.6  466.31  4901.1  465.51
  4906.1  465.51  4906.6  466.31  4933.2  467.19  4954.1  466.42  4989.8  466.92
  5047.3  468.71  5132.2  472.36  5169.3  475.14  5224.4  480.33  5367.0  487.17
#Mann=8,-1,0
  4336.0    0.16       0  4377.2    0.05       0  4702.2    0.16       0
  4859.8    0.05       0  4891.9    0.16       0  4900.6    0.07       0
  4906.6    0.16       0  5169.3    0.05       0
Bank Sta=4727.4,5047.3
Exp/Cntr=0.3,0.1

Type RM Length L Ch R = 1,7133,448,448,448
BEGIN DESCRIPTION:
UNT 184 in LFCCL Watershed 13.0
END DESCRIPTION:
XS GIS Cut Line= 3
      2785624.97      7033225.02      2786025.00      7032975.00
      2786275.01      7032724.99
#Sta/Elev= 30
  4556.5  481.32  4722.2  473.63  4767.4  472.42  4804.2  471.02  4810.7  469.88
  4816.6  470.49  4826.0  468.87  4828.7  466.95  4831.9  464.72  4839.6  463.82
  4847.2  464.22  4853.1  468.62  4862.5  470.21  4889.7  468.09  4969.3  466.05
  4984.0  462.89  4989.9  462.77  4990.4  461.97  4995.4  461.97  4995.9  462.77
  5005.2  463.87  5014.7  463.38  5020.6  464.59  5113.1  464.39  5184.1  466.95
  5212.2  468.96  5252.6  471.53  5282.8  474.14  5336.2  476.74  5381.8  480.94
#Mann=7,-1,0
  4556.5    0.05       0  4767.4    0.16       0  4989.9    0.07       0
  4995.9    0.16       0  5212.2    0.05       0  5252.6    0.16       0
  5336.2    0.05       0
Bank Sta=4828.7,5184.1
Exp/Cntr=0.3,0.1

Type RM Length L Ch R = 1,6685,408,408,408
BEGIN DESCRIPTION:
UNT 184 in LFCCL Watershed 12.0
END DESCRIPTION:
XS GIS Cut Line= 3
      2785783.65      7033395.50      2786283.68      7033195.49
      2786583.72      7033045.47
#Sta/Elev= 30
  4483.9  478.62  4607.8  472.96  4658.2  471.35  4754.6  468.32  4764.0  466.68
  4765.7  465.54  4773.2  459.82  4773.7  459.02  4778.7  459.02  4779.2  459.82
  4786.9  460.66  4793.6  465.89  4799.0  468.37  4830.0  466.24  4862.3  465.97
  4937.7  463.06  5002.3  463.04  5020.5  461.63  5127.2  465.54  5143.9  466.88
  5149.5  466.33  5166.3  469.06  5239.0  474.00  5261.3  474.17  5270.1  473.60
  5283.7  474.27  5300.4  478.41  5306.0  479.11  5337.0  481.60  5357.9  482.11
#Mann=5,-1,0
  4483.9    0.05       0  4658.2    0.16       0  4773.2    0.07       0
  4779.2    0.16       0  5270.1    0.05       0
Bank Sta=4765.7,5127.2
Exp/Cntr=0.3,0.1

Type RM Length L Ch R = 1,6277,526,526,526
BEGIN DESCRIPTION:
UNT 184 in LFCCL Watershed 11.0
END DESCRIPTION:
XS GIS Cut Line= 3
      2785933.85      7033696.07      2786414.65      7033457.93
      2786683.84      7033246.08
#Sta/Elev= 30
  4504.4  477.06  4592.1  474.34  4622.6  472.24  4699.6  467.78  4811.8  464.92
  4818.9  463.64  4843.3  462.59  4879.0  461.75  4882.1  457.82  4882.6  457.02
  4887.6  457.02  4888.1  457.82  4895.9  459.73  4901.5  459.45  4907.4  463.92
  4968.7  462.26  4974.4  460.26  4985.5  459.10  4996.7  460.80  5007.9  459.08
  5038.6  463.02  5050.8  461.87  5086.0  461.81  5133.1  463.64  5193.5  466.16
  5249.6  471.49  5294.2  473.70  5321.4  474.87  5357.1  478.89  5383.5  480.52
#Mann=7,-1,0
  4504.4    0.05       0  4592.1    0.16       0  4622.6    0.05       0
  4843.3    0.16       0  4882.1    0.07       0  4888.1    0.16       0
  5294.2    0.05       0
Bank Sta=4818.9,5133.1
Exp/Cntr=0.3,0.1

Type RM Length L Ch R = 1,5751,386,386,386
BEGIN DESCRIPTION:
UNT 184 in LFCCL Watershed 10.0
END DESCRIPTION:
XS GIS Cut Line= 3
      2786174.98      7033975.01      2786743.58      7033726.07
      2787025.02      7033524.99
#Sta/Elev= 30
  4379.3  475.26  4463.9  472.67  4487.3  470.42  4637.4  464.03  4748.2  461.25
  4766.3  460.07  4769.3  456.36  4769.8  455.56  4774.8  455.56  4775.3  456.36
  4783.2  460.72  4789.7  461.76  4805.1  460.27  4841.9  459.51  5003.9  458.98
  5009.2  458.55  5015.3  456.36  5030.1  458.97  5109.9  459.59  5124.7  460.09
  5129.0  461.25  5137.0  461.44  5145.6  465.15  5151.7  463.73  5160.3  467.57
  5181.2  471.88  5210.7  474.79  5237.2  475.83  5296.7  480.55  5345.9  482.34
#Mann=5,-1,0
  4379.3    0.05       0  4637.4    0.16       0  4769.3    0.07       0
  4775.3    0.16       0  5237.2    0.05       0
Bank Sta=4748.2,5129
Exp/Cntr=0.3,0.1

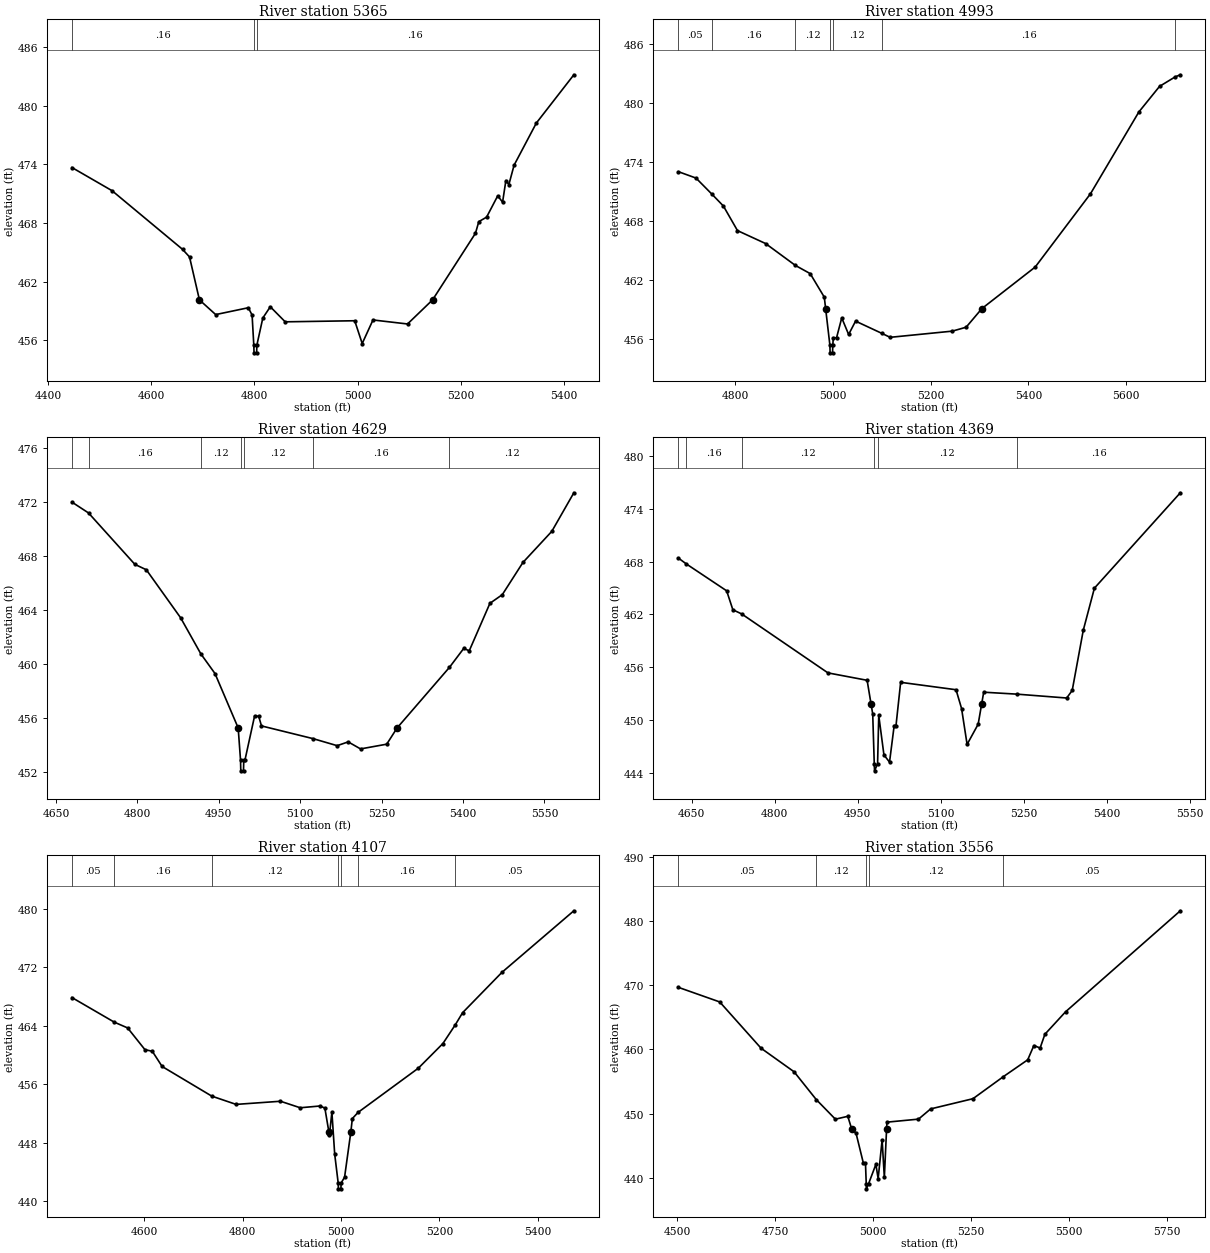
Type RM Length L Ch R = 1,5365,372,372,372
BEGIN DESCRIPTION:
UNT 184 in LFCCL Watershed 9.0
END DESCRIPTION:
XS GIS Cut Line= 3
      2786375.02      7034374.99      2786825.00      7034025.00
      2787175.02      7033824.99
#Sta/Elev= 30
  4446.2  473.66  4524.0  471.29  4660.6  465.30  4674.2  464.52  4693.4  460.13
  4724.9  458.63  4788.2  459.33  4795.5  458.58  4798.8  455.52  4799.3  454.72
  4804.3  454.72  4804.8  455.52  4816.3  458.28  4830.8  459.43  4859.7  457.89
  4994.5  458.00  5009.0  455.67  5029.9  458.08  5096.9  457.67  5145.4  460.13
  5228.6  466.94  5235.1  468.13  5250.2  468.59  5271.8  470.77  5281.2  470.12
  5287.6  472.33  5293.4  471.92  5303.5  473.90  5346.7  478.21  5419.4  483.14
#Mann=3,-1,0
  4446.2    0.16       0  4798.8    0.07       0  4804.8    0.16       0
Bank Sta=4693.4,5145.4
Exp/Cntr=0.3,0.1

Type RM Length L Ch R = 1,4993,364,364,364
BEGIN DESCRIPTION:
UNT 184 in LFCCL Watershed 8.0
END DESCRIPTION:
XS GIS Cut Line= 3
      2786524.99      7034575.00      2786775.00      7034375.00
      2787275.02      7033874.98
#Sta/Elev= 30
  4683.7  473.03  4719.7  472.38  4752.7  470.72  4775.8  469.53  4804.6  467.03
  4862.2  465.71  4923.2  463.48  4953.4  462.65  4982.3  460.25  4985.0  459.09
  4993.7  455.38  4994.2  454.58  4999.2  454.58  4999.7  455.38  5000.7  456.12
  5007.4  456.12  5018.0  458.14  5032.1  456.45  5046.3  457.81  5099.8  456.57
  5117.0  456.16  5244.3  456.79  5272.6  457.19  5304.9  459.09  5414.0  463.32
  5527.1  470.78  5626.1  479.11  5668.5  481.72  5700.6  482.69  5711.0  482.90
#Mann=7,-1,0
  4683.7    0.05       0  4752.7    0.16       0  4923.2    0.12       0
  4993.7    0.07       0  4999.7    0.12       0  5099.8    0.16       0
  5700.6    0.05       0
Bank Sta=4985,5304.9
Exp/Cntr=0.3,0.1

Type RM Length L Ch R = 1,4629,260,260,260
BEGIN DESCRIPTION:
UNT 184 in LFCCL Watershed 7.0
END DESCRIPTION:
XS GIS Cut Line= 3
      2786675.05      7034774.98      2786975.00      7034675.00
      2787575.04      7034574.99
#Sta/Elev= 30
  4679.6  471.98  4710.1  471.18  4795.5  467.38  4816.6  466.98  4879.8  463.43
  4917.1  460.76  4943.1  459.31  4985.8  455.29  4990.1  452.92  4990.6  452.12
  4995.6  452.12  4996.1  452.92  4998.3  452.92  5016.1  456.19  5023.7  456.14
  5028.7  455.44  5123.7  454.50  5168.1  453.98  5188.4  454.26  5211.2  453.74
  5259.4  454.09  5278.5  455.29  5375.0  459.77  5401.3  461.17  5411.4  460.99
  5449.5  464.50  5472.3  465.14  5510.3  467.52  5563.5  469.82  5604.1  472.67
#Mann=7,-1,0
  4679.6    0.05       0  4710.1    0.16       0  4917.1    0.12       0
  4990.1    0.07       0  4996.1    0.12       0  5123.7    0.16       0
  5375.0    0.12       0
Bank Sta=4985.8,5278.5
Exp/Cntr=0.3,0.1

Type RM Length L Ch R = 1,4369,262,262,262
BEGIN DESCRIPTION:
XS4082A
END DESCRIPTION:
XS GIS Cut Line= 3
      2786787.73      7034806.31      2787176.62      7034865.34
      2787690.29      7034879.22
#Sta/Elev= 30
  4626.2  468.39  4640.7  467.72  4713.4  464.68  4724.6  462.53  4740.5  462.06
  4896.5  455.37  4967.3  454.53  4974.5  451.80  4977.4  450.71  4980.2  445.06
  4980.7  444.26  4986.2  445.06  4988.3  450.55  4997.7  446.06  5007.8  445.25
  5016.2  449.40  5019.5  449.40  5027.9  454.30  5128.0  453.46  5138.0  451.33
  5148.0  447.26  5168.0  449.55  5174.2  451.80  5178.0  453.18  5237.9  452.96
  5328.0  452.52  5338.0  453.38  5358.0  460.21  5378.1  464.98  5533.4  475.80
#Mann=6,-1,0
  4626.2    0.05       0  4640.7    0.16       0  4740.5    0.12       0
  4980.2    0.07       0  4986.2    0.12       0  5237.9    0.16       0
Bank Sta=4974.5,5174.2
Exp/Cntr=0.3,0.1

Type RM Length L Ch R = 1,4107,551,551,551
BEGIN DESCRIPTION:
UNT 184 in LFCCL Watershed 6.0
END DESCRIPTION:
XS GIS Cut Line= 3
      2786812.03      7034938.26      2787381.48      7034983.40
      2787831.45      7034983.40
#Sta/Elev= 30
  4452.4  467.87  4538.5  464.51  4565.7  463.72  4600.9  460.75  4615.9  460.53
  4635.9  458.45  4736.9  454.40  4786.4  453.27  4876.7  453.70  4916.8  452.81
  4956.9  453.05  4967.0  452.77  4975.2  449.49  4976.3  449.05  4981.3  452.22
  4987.0  446.47  4994.1  442.53  4994.6  441.73  4999.6  441.73  5000.1  442.53
  5007.1  443.32  5019.8  449.49  5022.9  451.33  5034.4  452.17  5157.2  458.22
  5207.2  461.59  5232.5  464.16  5247.2  465.80  5327.2  471.31  5473.6  479.73
#Mann=7,-1,0
  4452.4    0.05       0  4538.5    0.16       0  4736.9    0.12       0
  4994.1    0.07       0  5000.1    0.12       0  5034.4    0.16       0
  5232.5    0.05       0
Bank Sta=4975.2,5019.8
Exp/Cntr=0.3,0.1

Type RM Length L Ch R = 1,3556,541,541,541
BEGIN DESCRIPTION:
UNT 184 in LFCCL Watershed 5.0
END DESCRIPTION:
XS GIS Cut Line= 3
      2786775.03      7035325.01      2787225.00      7035475.00
      2787924.97      7035075.02
#Sta/Elev= 30
  4503.3  469.67  4608.7  467.40  4714.1  460.20  4798.4  456.53  4854.9  452.21
  4903.8  449.15  4935.4  449.60  4945.4  447.62  4956.5  446.96  4975.0  442.35
  4980.5  442.35  4982.5  439.11  4983.0  438.31  4988.5  439.11  5007.1  442.12
  5012.9  439.90  5023.0  445.93  5028.7  440.08  5034.4  447.62  5035.2  448.69
  5115.8  449.16  5146.8  450.75  5254.8  452.34  5332.5  455.78  5394.4  458.39
  5410.2  460.62  5426.1  460.23  5438.3  462.37  5490.9  465.86  5783.8  481.59
#Mann=5,-1,0
  4503.3    0.05       0  4854.9    0.12       0  4982.5    0.07       0
  4988.5    0.12       0  5332.5    0.05       0
Bank Sta=4945.4,5034.4
Exp/Cntr=0.3,0.1

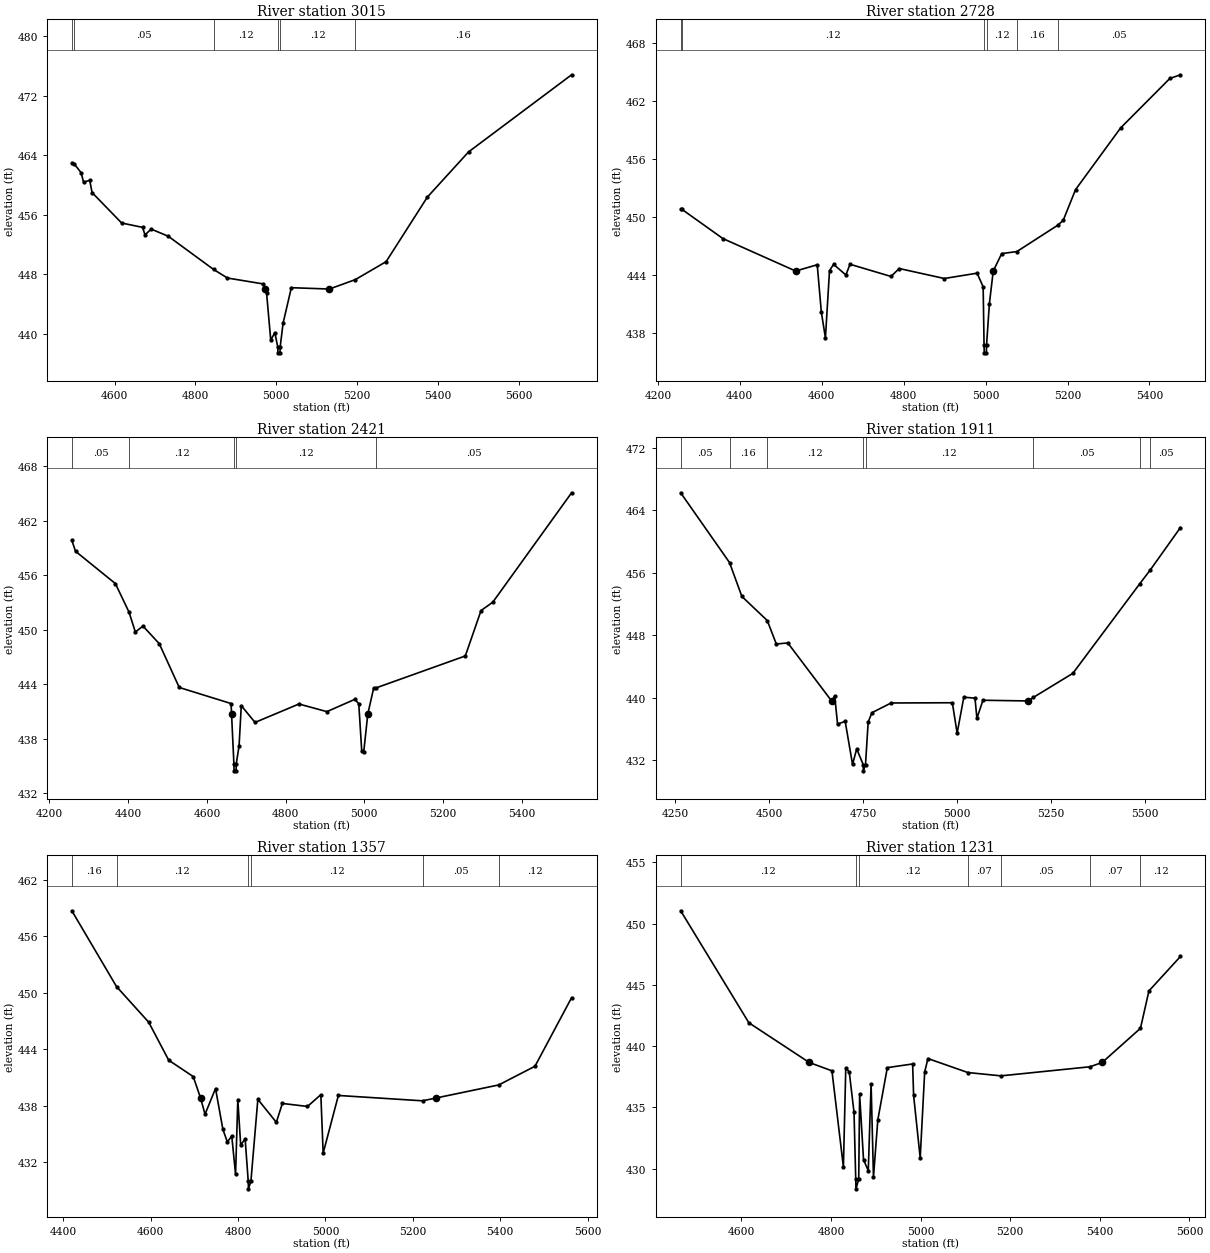
Type RM Length L Ch R = 1,3015,287,287,287
BEGIN DESCRIPTION:
UNT 184 in LFCCL Watershed 4.0
END DESCRIPTION:
XS GIS Cut Line= 3
      2786875.02      7035725.01      2787275.00      7035975.00
      2788024.97      7035825.01
#Sta/Elev= 30
  4494.4  462.97  4500.3  462.82  4517.4  461.64  4523.3  460.37  4538.6  460.62
  4544.5  458.97  4617.6  454.88  4669.5  454.29  4675.4  453.28  4690.7  454.06
  4733.2  453.09  4844.9  448.64  4879.4  447.48  4968.6  446.68  4972.7  446.00
  4976.3  445.42  4986.5  439.14  4996.7  440.13  5003.8  438.22  5004.3  437.42
  5009.4  437.42  5009.9  438.22  5017.1  441.42  5037.5  446.18  5131.5  446.00
  5195.6  447.26  5272.0  449.68  5374.0  458.36  5476.0  464.44  5730.9  474.81
#Mann=6,-1,0
  4494.4    0.12       0  4500.3    0.05       0  4844.9    0.12       0
  5003.8    0.07       0  5009.9    0.12       0  5195.6    0.16       0
Bank Sta=4972.7,5131.5
Exp/Cntr=0.3,0.1

Type RM Length L Ch R = 1,2728,307,307,307
BEGIN DESCRIPTION:
XS4083A
END DESCRIPTION:
XS GIS Cut Line= 3
      2786641.93      7036203.01      2787379.75      7036229.06
      2787860.79      7036207.39
#Sta/Elev= 30
  4255.7  450.77  4259.3  450.77  4358.8  447.77  4536.4  444.42  4589.0  445.07
  4599.0  440.19  4609.0  437.52  4619.0  444.47  4629.0  445.11  4659.0  444.01
  4669.0  445.12  4769.1  443.86  4789.1  444.68  4899.2  443.65  4979.2  444.20
  4994.0  442.79  4996.2  436.78  4996.7  435.98  5001.8  435.98  5002.3  436.78
  5009.2  441.05  5018.6  444.42  5039.3  446.22  5076.3  446.43  5175.5  449.13
  5189.4  449.65  5219.5  452.82  5329.6  459.19  5449.7  464.29  5475.5  464.67
#Mann=6,-1,0
  4255.7    0.16       0  4259.3    0.12       0  4996.2    0.07       0
  5002.3    0.12       0  5076.3    0.16       0  5175.5    0.05       0
Bank Sta=4536.4,5018.6
Exp/Cntr=0.3,0.1

Type RM Length L Ch R = 1,2421,510,510,510
BEGIN DESCRIPTION:
UNT 184 in LFCCL Watershed 3.0
END DESCRIPTION:
XS GIS Cut Line= 3
      2786615.86      7036650.06      2787375.00      7036525.00
      2787875.03      7036525.00
#Sta/Elev= 30
  4257.0  459.84  4266.3  458.64  4367.6  455.08  4402.2  451.94  4418.3  449.75
  4437.7  450.40  4479.1  448.46  4529.8  443.64  4661.5  441.87  4662.7  440.71
  4668.6  435.26  4669.1  434.46  4674.2  434.46  4674.7  435.26  4681.8  437.22
  4687.4  441.64  4722.3  439.79  4833.8  441.82  4904.8  440.98  4975.7  442.33
  4985.8  441.86  4993.3  436.67  4998.3  436.49  5008.7  440.71  5023.8  443.60
  5029.5  443.59  5256.4  447.11  5296.4  452.11  5326.4  453.04  5526.4  465.08
#Mann=5,-1,0
  4257.0    0.05       0  4402.2    0.12       0  4668.6    0.07       0
  4674.7    0.12       0  5029.5    0.05       0
Bank Sta=4662.7,5008.7
Exp/Cntr=0.3,0.1

Type RM Length L Ch R = 1,1911,554,554,554
BEGIN DESCRIPTION:
UNT 184 in LFCCL Watershed 2.0
END DESCRIPTION:
XS GIS Cut Line= 3
      2786625.05      7036875.01      2787425.00      7037025.00
      2787875.02      7036774.99
#Sta/Elev= 30
  4264.7  466.27  4394.6  457.32  4427.4  452.98  4494.9  449.89  4519.0  446.88
  4549.5  447.02  4666.0  439.58  4674.2  440.22  4681.8  436.62  4702.1  436.96
  4721.6  431.45  4732.7  433.43  4750.0  431.42  4750.5  430.62  4756.1  431.42
  4763.2  436.89  4773.4  438.08  4824.2  439.32  4987.0  439.35  4999.7  435.45
  5017.5  440.06  5047.2  439.94  5052.3  437.36  5068.4  439.67  5189.4  439.58
  5202.2  440.03  5307.4  443.12  5484.7  454.57  5513.6  456.40  5593.4  461.81
#Mann=8,-1,0
  4264.7    0.05       0  4394.6    0.16       0  4494.9    0.12       0
  4750.0    0.07       0  4756.1    0.12       0  5202.2    0.05       0
  5484.7    0.16       0  5513.6    0.05       0
Bank Sta=4666,5189.4
Exp/Cntr=0.3,0.1

Type RM Length L Ch R = 1,1357,126,126,126
BEGIN DESCRIPTION:
XS4084A
END DESCRIPTION:
XS GIS Cut Line= 3
      2786746.03      7037105.78      2787310.30      7037218.64
      2787878.84      7037214.30
#Sta/Elev= 30
  4419.5  458.73  4521.8  450.66  4595.4  446.87  4641.3  442.82  4697.4  441.08
  4714.2  438.79  4724.4  437.07  4748.4  439.81  4765.2  435.48  4775.4  434.12
  4785.6  434.75  4794.3  430.66  4799.4  438.64  4806.0  433.79  4816.2  434.44
  4823.3  429.93  4823.8  429.13  4829.4  429.93  4845.3  438.66  4887.6  436.21
  4901.4  438.22  4958.9  437.90  4989.5  439.15  4994.8  432.93  5029.6  439.07
  5222.3  438.50  5252.2  438.79  5396.7  440.19  5479.7  442.18  5563.5  449.48
#Mann=6,-1,0
  4419.5    0.16       0  4521.8    0.12       0  4823.3    0.07       0
  4829.4    0.12       0  5222.3    0.05       0  5396.7    0.12       0
Bank Sta=4714.2,5252.2
Exp/Cntr=0.3,0.1

Type RM Length L Ch R = 1,1231,338,338,338
BEGIN DESCRIPTION:
XS4085A
END DESCRIPTION:
XS GIS Cut Line= 3
      2786850.26      7037157.88      2787340.69      7037331.49
      2787935.27      7037305.45
#Sta/Elev= 30
  4464.5  451.05  4616.7  441.91  4751.5  438.67  4802.1  437.99  4827.7  430.14
  4833.0  438.24  4840.8  437.89  4851.4  434.59  4855.2  429.16  4855.7  428.36
  4861.9  429.16  4863.9  436.06  4872.6  430.74  4883.2  429.84  4889.5  436.93
  4894.8  429.32  4904.5  433.99  4925.7  438.25  4982.2  438.55  4984.4  435.98
  4999.1  430.88  5009.1  437.90  5016.4  438.99  5105.5  437.85  5179.3  437.58
  5377.8  438.32  5405.2  438.67  5490.7  441.46  5509.6  444.51  5579.9  447.32
#Mann=7,-1,0
  4464.5    0.12       0  4855.2    0.07       0  4861.9    0.12       0
  5105.5    0.07       0  5179.3    0.05       0  5377.8    0.07       0
  5490.7    0.12       0
Bank Sta=4751.5,5405.2
Exp/Cntr=0.3,0.1

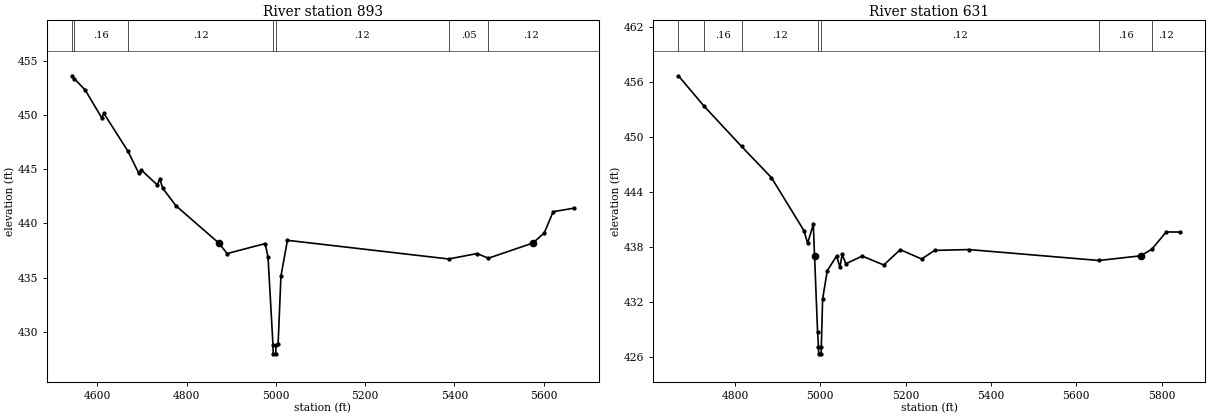
Type RM Length L Ch R = 1,893,262,262,262
BEGIN DESCRIPTION:
XS4086A
END DESCRIPTION:
XS GIS Cut Line= 5
      2786837.24      7037283.75      2787227.84      7037379.23
      2787310.30      7037444.33      2787401.45      7037474.71
      2787921.15      7037435.74
#Sta/Elev= 30
  4543.1  453.61  4548.6  453.33  4573.1  452.28  4609.6  449.75  4614.8  450.14
  4668.6  446.65  4692.9  444.62  4698.1  444.94  4734.6  443.54  4739.7  444.11
  4746.7  443.23  4776.2  441.63  4872.0  438.20  4890.8  437.23  4976.1  438.15
  4982.4  436.87  4993.5  428.79  4994.0  427.99  4999.7  427.99  5000.2  428.79
  5005.0  428.94  5011.3  435.15  5025.8  438.45  5387.0  436.73  5450.7  437.23
  5476.0  436.80  5575.7  438.20  5601.2  439.13  5621.2  441.09  5667.5  441.41
#Mann=7,-1,0
  4543.1    0.05       0  4548.6    0.16       0  4668.6    0.12       0
  4993.5    0.07       0  5000.2    0.12       0  5387.0    0.05       0
  5476.0    0.12       0
Bank Sta=4872,5575.7
Exp/Cntr=0.3,0.1

Type RM Length L Ch R = 1,631,0,0,0
BEGIN DESCRIPTION:
UNT 184 in LFCCL Watershed 1.0
END DESCRIPTION:
XS GIS Cut Line= 3
      2786785.12      7037387.91      2787223.50      7037578.88
      2787917.92      7037505.10
#Sta/Elev= 30
  4667.5  456.68  4727.0  453.40  4815.4  448.98  4885.5  445.58  4961.9  439.78
  4970.3  438.41  4983.7  440.49  4986.6  437.05  4993.7  428.75  4995.8  427.16
  4996.3  426.36  5002.0  426.36  5002.5  427.16  5005.5  432.33  5016.4  435.42
  5038.2  437.03  5046.0  435.82  5051.5  437.20  5060.0  436.18  5098.3  437.02
  5148.9  436.05  5187.4  437.72  5237.7  436.70  5267.9  437.64  5348.3  437.73
  5653.4  436.54  5751.3  437.05  5777.3  437.77  5810.9  439.65  5844.0  439.64
#Mann=7,-1,0
  4667.5    0.05       0  4727.0    0.16       0  4815.4    0.12       0
  4995.8    0.07       0  5002.5    0.12       0  5653.4    0.16       0
  5777.3    0.12       0
Bank Sta=4986.6,5751.3
Exp/Cntr=0.3,0.1

Chan Stop Cuts=-1