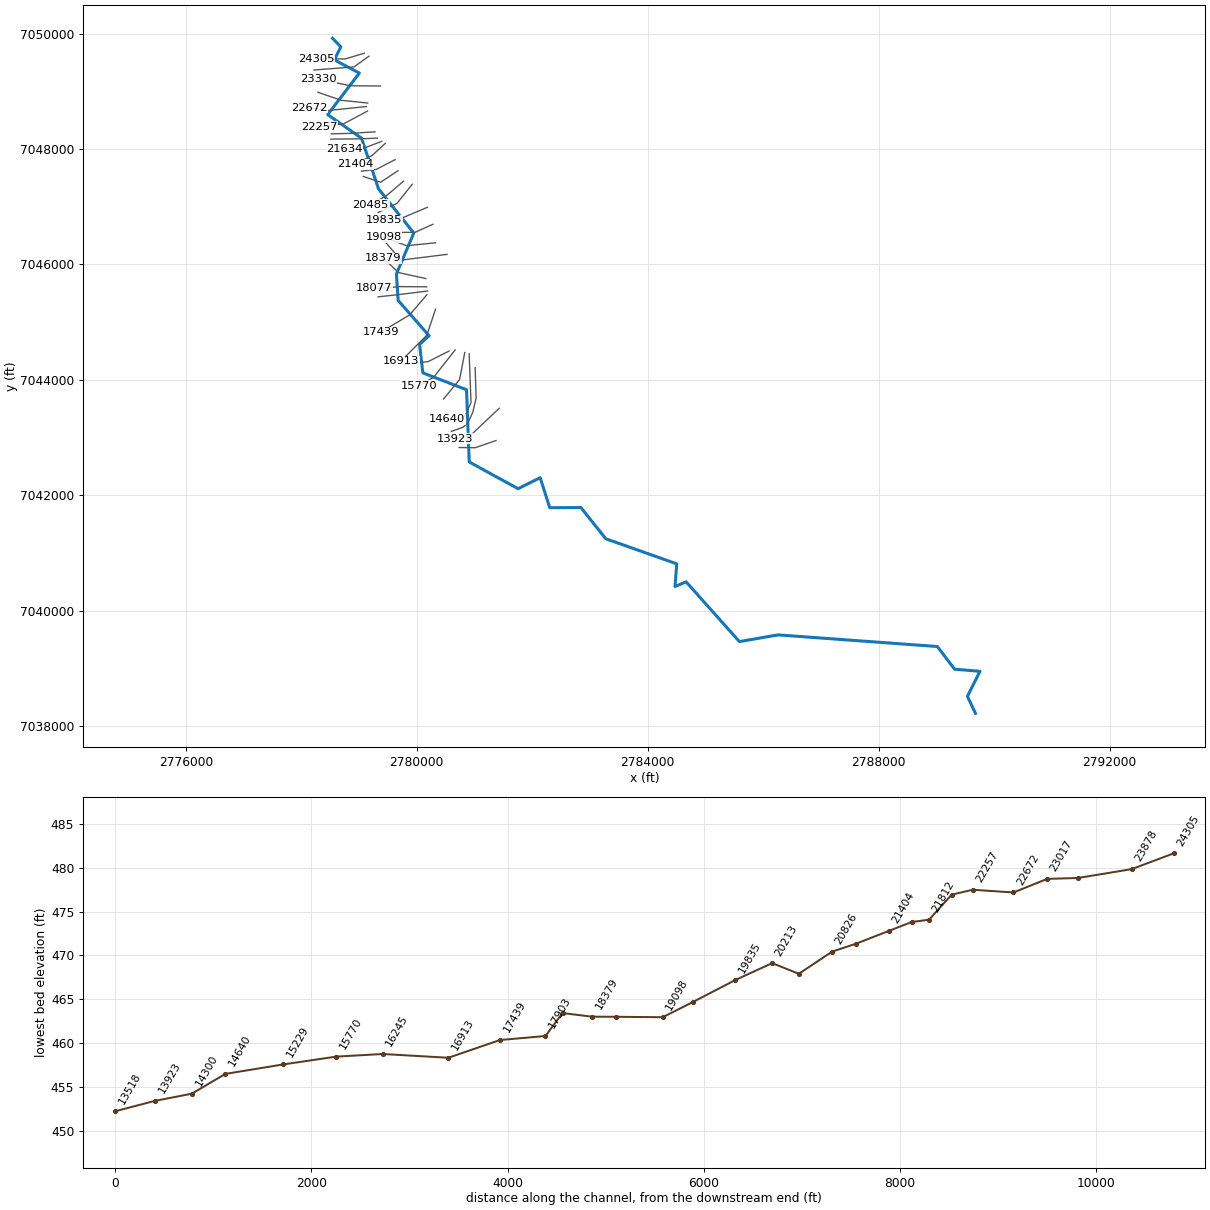
--- UNT 185 in LFCCL Watershed.prj (project) ---

Proj Title=UNT 185 in LFCCL Watershed Base Level Engineering
Current Plan=p01
Default Exp/Contr=0.3,0.1
English Units
Geom File=g01
Flow File=f01
Plan File=p01
BEGIN DESCRIPTION:
UNT 185 in LFCCL Watershed
END DESCRIPTION:

--- UNT 185 in LFCCL Watershed.p01 (plan) ---

Plan Title=Multiple Run
Short Identifier=Multiple
Geom File=g01
Flow File=f01
Subcritical Flow
K Sum by GR= 0
Std Step Tol= 0.01
Critical Tol= 0.01
Num of Std Step Trials= 20
Max Error Tol= 0.3
Flow Tol Ratio= 0.001
Split Flow NTrial= 30
Split Flow Tol= 0.02
Split Flow Ratio= 0.02
Log Output Level= 0
Friction Slope Method= 1
Unsteady Friction Slope Method= 2
Unsteady Bridges Friction Slope Method= 1
Parabolic Critical Depth
Global Vel Dist=  1 , 1 , 1
Global Log Level= 0
CheckData=True
Encroach Param= -1, 0, 0, 0
BEGIN DESCRIPTION:
Multiple Run
END DESCRIPTION:

--- UNT 185 in LFCCL Watershed.f01 (steady flow) ---

Flow Title=Multiple
Number of Profiles=7
Profile Names=10-year,25-year,50-year,1pct_min,100-year,1pct_plu,500-year
River Rch & RM= UNT 185 in LFCCL,Reach-1,24305
     344     443     521     305     608    1213     829
River Rch & RM= UNT 185 in LFCCL,Reach-1,21072
     574     760     908     539    1075    2146    1511
River Rch & RM= UNT 185 in LFCCL,Reach-1,10546
     770    1034    1247     746    1489    2971    2128
Boundary for River Rch & Prof#=UNT 185 in LFCCL,Reach-1,1
Up Type=0
Dn Type=3
Dn Slope=0.005
Boundary for River Rch & Prof#=UNT 185 in LFCCL,Reach-1,2
Up Type=0
Dn Type=3
Dn Slope=0.005
Boundary for River Rch & Prof#=UNT 185 in LFCCL,Reach-1,3
Up Type=0
Dn Type=3
Dn Slope=0.005
Boundary for River Rch & Prof#=UNT 185 in LFCCL,Reach-1,4
Up Type=0
Dn Type=3
Dn Slope=0.005
Boundary for River Rch & Prof#=UNT 185 in LFCCL,Reach-1,5
Up Type=0
Dn Type=3
Dn Slope=0.005
Boundary for River Rch & Prof#=UNT 185 in LFCCL,Reach-1,6
Up Type=0
Dn Type=3
Dn Slope=0.005
Boundary for River Rch & Prof#=UNT 185 in LFCCL,Reach-1,7
Up Type=0
Dn Type=3
Dn Slope=0.005

--- UNT 185 in LFCCL Watershed.g01 (geometry) ---

Geom Title=Existing Conditions

River Reach=UNT 185 in LFCCL,Reach-1
Reach XY= 30
      2778541.43      7049918.51      2778683.98      7049770.84
      2778573.72      7049544.94      2779005.69      7049316.11
      2778457.66      7048596.40      2779043.12      7048188.79
      2779337.20      7047311.45      2779948.14      7046544.31
      2779647.61      7045834.70      2779677.81      7045377.19
      2780213.70      7044764.30      2780048.30      7044615.47
      2780105.52      7044121.31      2780861.80      7043828.96
      2780908.49      7042577.53      2781753.77      7042114.40
      2782136.90      7042304.41      2782302.63      7041784.67
      2782843.07      7041787.46      2783272.15      7041247.11
      2784502.18      7040811.91      2784471.86      7040419.71
      2784664.71      7040500.15      2785587.05      7039464.22
      2786255.51      7039580.84      2789015.04      7039379.26
      2789313.31      7038985.99      2789753.50      7038949.90
      2789535.90      7038515.38      2789675.59      7038220.71

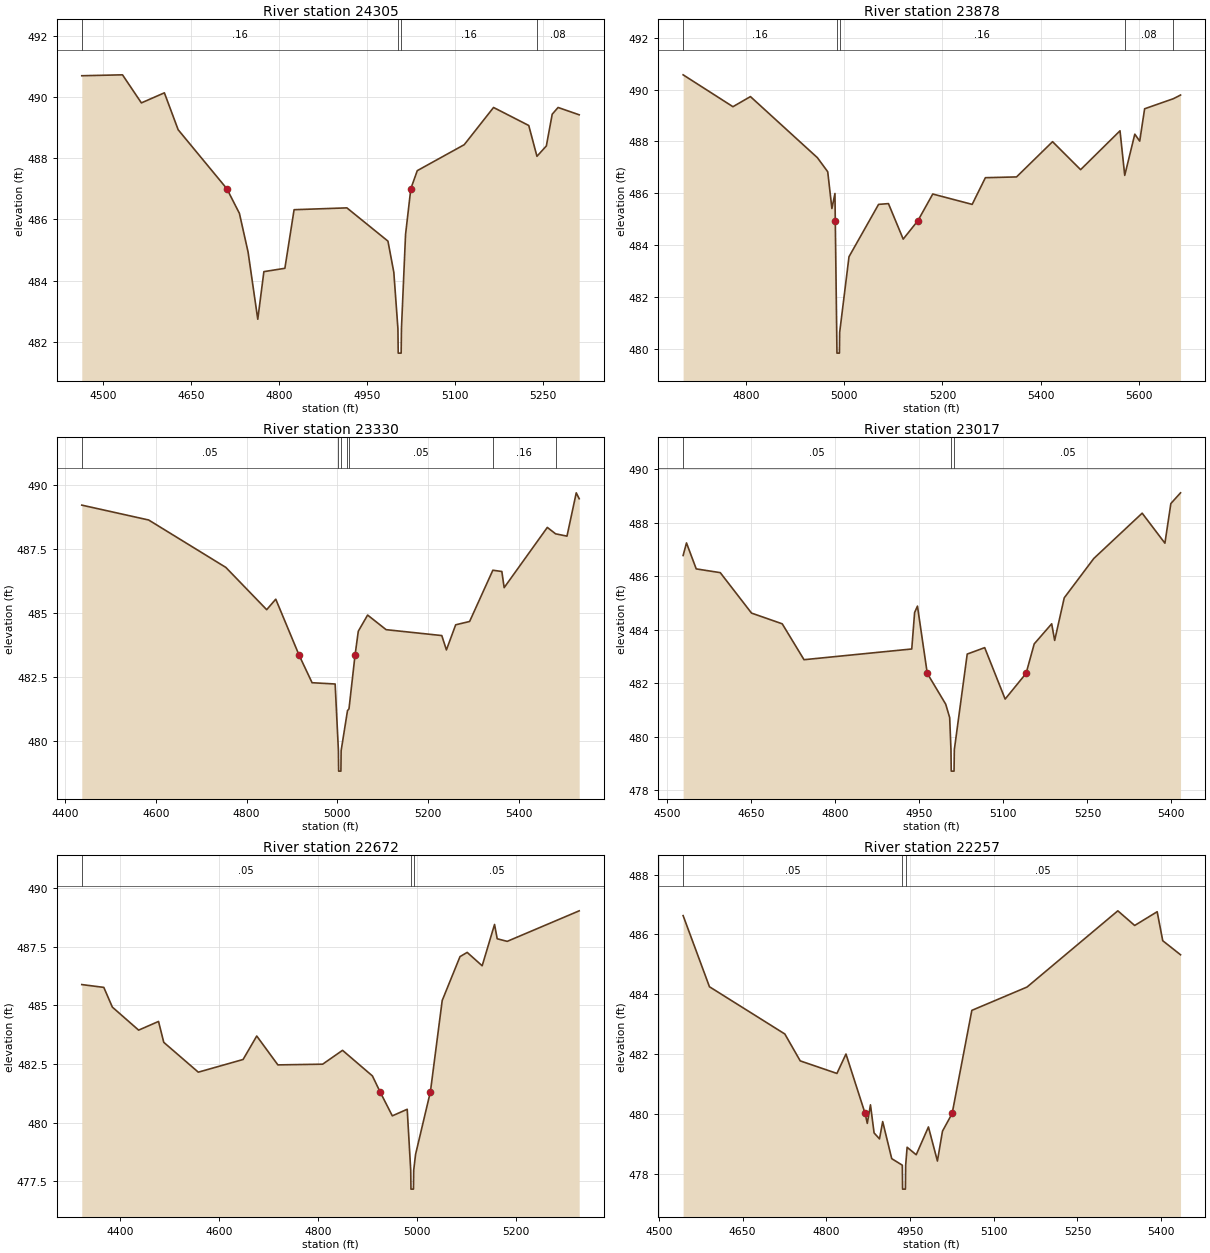
Type RM Length L Ch R = 1,24305,427,427,427
BEGIN DESCRIPTION:
UNT 185 in LFCCL Watershed 39.0
END DESCRIPTION:
XS GIS Cut Line= 3
      2779092.33      7049661.21      2778760.78      7049561.74
      2778259.03      7049561.74
#Sta/Elev= 30
  4464.1  490.71  4533.5  490.74  4565.7  489.82  4604.9  490.15  4628.4  488.94
  4711.3  487.01  4732.8  486.20  4747.6  484.93  4764.1  482.73  4774.5  484.29
  4810.3  484.40  4826.0  486.32  4916.0  486.38  4986.0  485.29  4996.0  484.27
  5003.0  482.42  5003.5  481.62  5008.5  481.62  5009.0  482.42  5016.0  485.51
  5025.0  487.01  5036.0  487.60  5116.0  488.45  5166.0  489.67  5226.0  489.08
  5240.0  488.07  5256.0  488.41  5266.0  489.45  5276.0  489.67  5312.0  489.43
#Mann=4,-1,0
  4464.1    0.16       0  5003.0    0.07       0  5009.0    0.16       0
  5240.0    0.08       0
Bank Sta=4711.3,5025
Exp/Cntr=0.3,0.1

Type RM Length L Ch R = 1,23878,548,548,548
BEGIN DESCRIPTION:
XS4087A
END DESCRIPTION:
XS GIS Cut Line= 3
      2779172.62      7049608.93      2778912.24      7049422.33
      2778222.15      7049370.25
#Sta/Elev= 30
  4672.3  490.57  4773.7  489.34  4809.3  489.73  4945.7  487.37  4966.6  486.83
  4975.1  485.41  4981.3  485.99  4982.0  484.94  4984.9  480.63  4985.4  479.83
  4990.4  479.83  4990.9  480.63  5009.9  483.55  5070.1  485.57  5090.2  485.60
  5120.2  484.23  5150.1  484.94  5180.4  485.97  5260.6  485.57  5287.5  486.60
  5350.9  486.63  5424.2  487.99  5481.3  486.91  5561.5  488.41  5571.1  486.69
  5591.6  488.28  5601.6  488.01  5611.6  489.26  5670.3  489.65  5684.7  489.79
#Mann=5,-1,0
  4672.3    0.16       0  4984.9    0.07       0  4990.9    0.16       0
  5571.1    0.08       0  5670.3    0.05       0
Bank Sta=4982,5150.1
Exp/Cntr=0.3,0.1

Type RM Length L Ch R = 1,23330,313,313,313
BEGIN DESCRIPTION:
XS4088A
END DESCRIPTION:
XS GIS Cut Line= 3
      2779372.29      7049092.47      2778851.48      7049096.81
      2778288.62      7049213.71
#Sta/Elev= 30
  4437.0  489.20  4584.3  488.62  4754.3  486.77  4844.3  485.12  4864.3  485.53
  4915.8  483.34  4944.3  482.27  4995.1  482.22  5002.3  479.62  5002.8  478.82
  5007.8  478.82  5008.3  479.62  5022.3  481.18  5025.6  481.25  5038.9  483.34
  5046.1  484.28  5066.6  484.91  5107.4  484.34  5230.0  484.11  5240.2  483.55
  5260.6  484.53  5291.3  484.66  5342.5  486.66  5362.3  486.61  5367.4  485.98
  5462.5  488.33  5480.7  488.08  5505.8  487.99  5526.2  489.68  5532.7  489.45
#Mann=7,-1,0
  4437.0    0.05       0  5002.3    0.03       0  5008.3    0.05       0
  5022.3    0.16       0  5025.6    0.05       0  5342.5    0.16       0
  5480.7    0.08       0
Bank Sta=4915.8,5038.9
Exp/Cntr=0.3,0.1

Type RM Length L Ch R = 1,23017,345,345,345
BEGIN DESCRIPTION:
XS4089A
END DESCRIPTION:
XS GIS Cut Line= 3
      2779150.93      7048797.33      2778690.89      7048845.07
      2778288.65      7048983.48
#Sta/Elev= 30
  4528.4  486.77  4534.4  487.24  4551.8  486.27  4594.7  486.13  4650.5  484.62
  4705.3  484.22  4744.2  482.88  4936.5  483.28  4941.6  484.64  4946.7  484.88
  4964.2  482.37  4997.1  481.22  5004.2  480.72  5006.5  479.52  5007.0  478.72
  5012.0  478.72  5012.5  479.52  5035.5  483.09  5066.7  483.33  5103.2  481.41
  5140.6  482.37  5155.1  483.47  5186.3  484.22  5191.6  483.60  5208.7  485.19
  5261.5  486.66  5347.8  488.35  5388.4  487.23  5399.0  488.71  5416.3  489.11
#Mann=3,-1,0
  4528.4    0.05       0  5006.5    0.03       0  5012.5    0.05       0
Bank Sta=4964.2,5140.6
Exp/Cntr=0.3,0.1

Type RM Length L Ch R = 1,22672,415,415,415
BEGIN DESCRIPTION:
XS4090A
END DESCRIPTION:
XS GIS Cut Line= 3
      2779129.25      7048736.57      2778456.52      7048667.12
      2778131.01      7048714.86
#Sta/Elev= 30
  4322.2  485.88  4366.7  485.76  4384.0  484.92  4437.1  483.94  4477.3  484.31
  4487.9  483.42  4557.7  482.15  4648.2  482.69  4675.8  483.69  4718.5  482.46
  4809.0  482.49  4849.2  483.08  4909.6  481.99  4924.9  481.32  4949.8  480.29
  4979.9  480.57  4987.0  477.97  4987.5  477.17  4992.5  477.17  4993.0  477.97
  4996.8  478.65  5026.8  481.32  5050.6  485.20  5086.6  487.07  5101.1  487.25
  5131.4  486.68  5156.4  488.44  5161.8  487.83  5182.0  487.72  5327.5  489.02
#Mann=3,-1,0
  4322.2    0.05       0  4987.0    0.03       0  4993.0    0.05       0
Bank Sta=4924.9,5026.8
Exp/Cntr=0.3,0.1

Type RM Length L Ch R = 1,22257,214,214,214
BEGIN DESCRIPTION:
XS4091A
END DESCRIPTION:
XS GIS Cut Line= 3
      2779146.58      7048658.42      2778734.29      7048437.09
      2778313.33      7048389.35
#Sta/Elev= 30
  4543.3  486.63  4590.5  484.25  4725.6  482.67  4753.2  481.77  4819.0  481.35
  4835.2  482.00  4869.5  480.01  4873.4  479.68  4879.1  480.30  4885.6  479.36
  4895.3  479.16  4901.0  479.74  4917.2  478.50  4936.2  478.28  4936.7  477.48
  4941.7  477.48  4942.2  478.28  4944.8  478.88  4961.1  478.63  4983.0  479.56
  4999.1  478.42  5008.2  479.42  5025.5  480.01  5060.8  483.46  5159.7  484.24
  5322.5  486.79  5352.7  486.30  5393.0  486.76  5403.0  485.79  5434.9  485.32
#Mann=3,-1,0
  4543.3    0.05       0  4936.2    0.03       0  4942.2    0.05       0
Bank Sta=4869.5,5025.5
Exp/Cntr=0.3,0.1

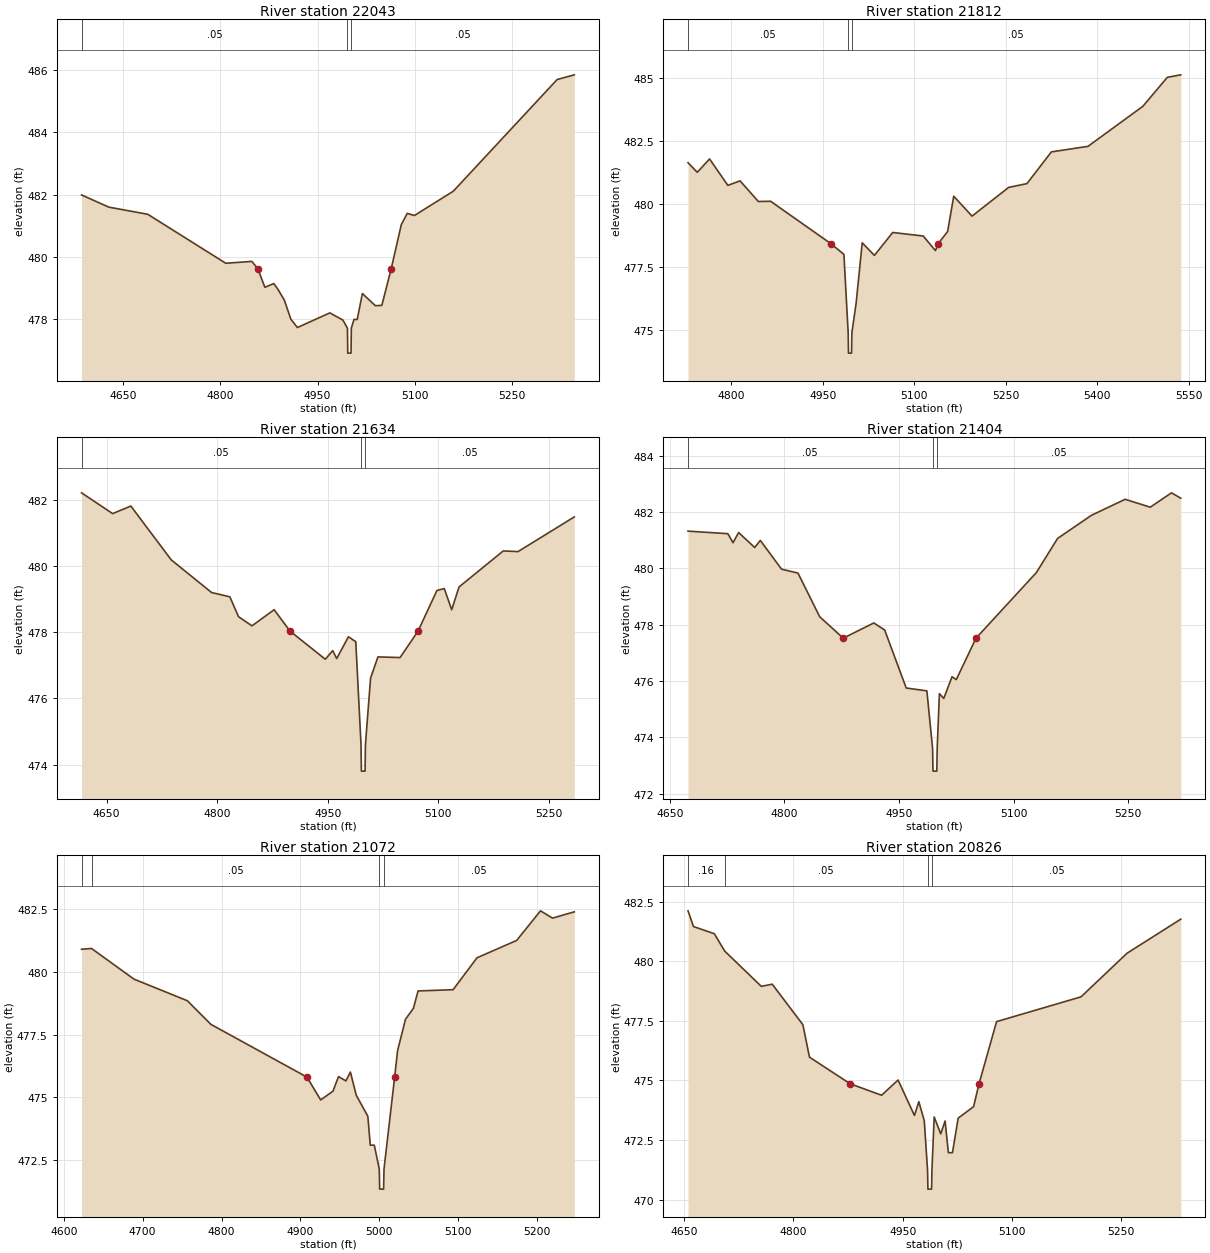
Type RM Length L Ch R = 1,22043,231,231,231
BEGIN DESCRIPTION:
XS4092A
END DESCRIPTION:
XS GIS Cut Line= 3
      2779276.82      7048298.20      2778855.82      7048272.16
      2778518.63      7048263.51
#Sta/Elev= 30
  4586.5  481.99  4628.4  481.60  4688.5  481.37  4808.7  479.80  4848.8  479.86
  4857.9  479.63  4868.9  479.03  4882.6  479.15  4888.9  478.97  4898.9  478.62
  4908.9  478.01  4919.0  477.74  4969.0  478.21  4989.1  477.98  4996.1  477.72
  4996.6  476.92  5001.6  476.92  5002.1  477.72  5006.2  478.00  5011.2  478.00
  5019.1  478.83  5039.1  478.44  5049.1  478.45  5063.6  479.63  5079.1  481.04
  5088.3  481.40  5099.2  481.33  5159.2  482.11  5319.2  485.69  5345.6  485.84
#Mann=3,-1,0
  4586.5    0.05       0  4996.1    0.03       0  5002.1    0.05       0
Bank Sta=4857.9,5063.6
Exp/Cntr=0.3,0.1

Type RM Length L Ch R = 1,21812,178,178,178
BEGIN DESCRIPTION:
XS4093A
END DESCRIPTION:
XS GIS Cut Line= 3
      2779320.22      7048189.69      2779029.43      7048176.67
      2778512.93      7048172.33
#Sta/Elev= 30
  4729.3  481.63  4744.5  481.25  4764.6  481.78  4794.6  480.73  4814.6  480.91
  4844.6  480.09  4864.7  480.10  4963.8  478.41  4984.8  477.99  4991.8  474.87
  4992.3  474.07  4997.3  474.07  4997.8  474.87  5004.8  476.05  5014.8  478.45
  5034.8  477.95  5064.8  478.86  5114.8  478.72  5134.8  478.14  5139.1  478.41
  5154.8  478.90  5164.8  480.30  5194.8  479.51  5254.8  480.65  5284.8  480.80
  5324.8  482.06  5384.8  482.28  5474.8  483.87  5514.8  485.02  5536.9  485.12
#Mann=3,-1,0
  4729.3    0.05       0  4991.8    0.03       0  4997.8    0.05       0
Bank Sta=4963.8,5139.1
Exp/Cntr=0.3,0.1

Type RM Length L Ch R = 1,21634,230,230,230
BEGIN DESCRIPTION:
XS4094A
END DESCRIPTION:
XS GIS Cut Line= 3
      2779394.03      7048133.27      2779064.15      7048007.40
      2778748.69      7047994.44
#Sta/Elev= 30
  4616.0  482.23  4658.2  481.60  4682.9  481.83  4737.7  480.20  4792.5  479.21
  4817.3  479.08  4829.0  478.48  4847.3  478.20  4877.4  478.69  4899.0  478.04
  4946.8  477.19  4956.9  477.45  4962.3  477.21  4978.2  477.87  4988.2  477.72
  4995.3  474.60  4995.8  473.80  5000.8  473.80  5001.3  474.60  5008.3  476.62
  5018.3  477.26  5048.3  477.24  5072.7  478.04  5098.3  479.27  5108.3  479.33
  5118.4  478.69  5128.4  479.38  5188.4  480.47  5208.4  480.45  5284.8  481.50
#Mann=3,-1,0
  4616.0    0.05       0  4995.3    0.03       0  5001.3    0.05       0
Bank Sta=4899,5072.7
Exp/Cntr=0.3,0.1

Type RM Length L Ch R = 1,21404,332,332,332
BEGIN DESCRIPTION:
XS4095A
END DESCRIPTION:
XS GIS Cut Line= 3
      2779454.76      7048098.53      2779229.08      7047890.21
      2778929.79      7047734.06
#Sta/Elev= 30
  4673.9  481.32  4726.0  481.23  4732.8  480.91  4740.1  481.27  4761.1  480.74
  4768.5  480.99  4796.3  479.97  4817.8  479.83  4846.2  478.28  4877.0  477.52
  4917.0  478.06  4931.2  477.81  4959.4  475.75  4986.4  475.65  4993.9  473.60
  4994.4  472.80  4999.4  472.80  4999.9  473.60  5002.8  475.55  5008.5  475.38
  5019.3  476.15  5024.9  476.05  5050.7  477.52  5129.7  479.85  5157.4  481.06
  5201.6  481.88  5245.8  482.45  5278.7  482.17  5306.4  482.68  5318.6  482.49
#Mann=3,-1,0
  4673.9    0.05       0  4993.9    0.03       0  4999.9    0.05       0
Bank Sta=4877,5050.7
Exp/Cntr=0.3,0.1

Type RM Length L Ch R = 1,21072,246,246,246
BEGIN DESCRIPTION:
XS4096A
END DESCRIPTION:
XS GIS Cut Line= 3
      2779624.04      7047816.43      2779298.53      7047647.16
      2779042.42      7047616.77
#Sta/Elev= 30
  4622.5  480.90  4635.2  480.93  4689.0  479.71  4756.7  478.85  4786.5  477.91
  4908.3  475.81  4925.7  474.90  4941.3  475.25  4948.3  475.83  4957.7  475.66
  4963.4  476.01  4970.8  475.09  4985.5  474.25  4988.6  473.10  4993.7  473.10
  5000.0  472.15  5000.5  471.35  5005.5  471.35  5006.0  472.15  5019.5  475.81
  5023.2  476.86  5033.2  478.11  5043.3  478.55  5049.2  479.24  5093.6  479.29
  5123.9  480.56  5174.2  481.25  5204.4  482.43  5219.7  482.14  5247.3  482.39
#Mann=4,-1,0
  4622.5    0.16       0  4635.2    0.05       0  5000.0    0.03       0
  5006.0    0.05       0
Bank Sta=4908.3,5019.5
Exp/Cntr=0.3,0.1

Type RM Length L Ch R = 1,20826,341,341,341
BEGIN DESCRIPTION:
UNT 185 in LFCCL Watershed 34.0
END DESCRIPTION:
XS GIS Cut Line= 3
      2779675.03      7047625.02      2779375.00      7047425.00
      2779075.01      7047525.00
#Sta/Elev= 30
  4655.2  482.12  4662.7  481.46  4691.3  481.16  4705.6  480.43  4755.9  478.95
  4770.9  479.04  4813.0  477.34  4822.0  475.98  4878.0  474.86  4921.1  474.38
  4943.7  475.02  4966.2  473.53  4972.2  474.11  4979.7  473.31  4984.2  471.24
  4984.7  470.44  4989.7  470.44  4990.2  471.24  4993.3  473.47  5002.3  472.76
  5008.3  473.30  5012.8  471.97  5018.4  471.97  5026.3  473.42  5047.4  473.90
  5054.9  474.86  5079.0  477.47  5195.0  478.51  5258.2  480.34  5332.0  481.77
#Mann=4,-1,0
  4655.2    0.16       0  4705.6    0.05       0  4984.2    0.03       0
  4990.2    0.05       0
Bank Sta=4878,5054.9
Exp/Cntr=0.3,0.1

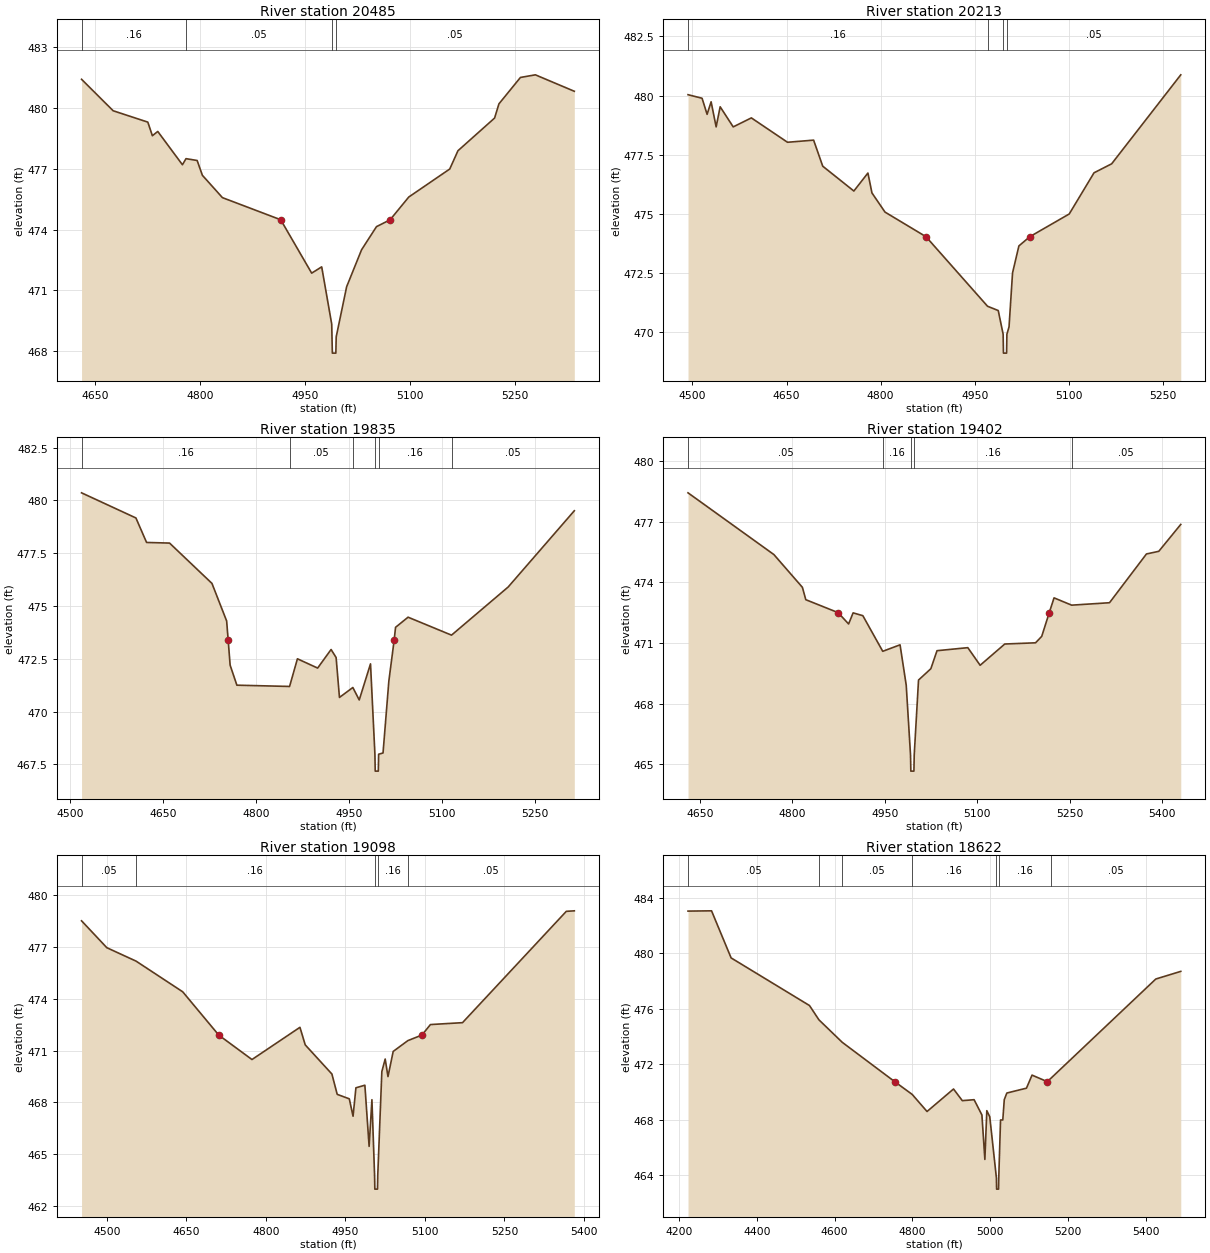
Type RM Length L Ch R = 1,20485,272,272,272
BEGIN DESCRIPTION:
UNT 185 in LFCCL Watershed 33.0
END DESCRIPTION:
XS GIS Cut Line= 3
      2779770.77      7047442.31      2779494.71      7047207.92
      2779203.00      7047030.82
#Sta/Elev= 30
  4631.1  481.40  4676.2  479.85  4725.7  479.29  4732.2  478.62  4739.9  478.83
  4775.1  477.19  4780.2  477.49  4796.1  477.40  4803.6  476.67  4832.2  475.57
  4915.4  474.48  4959.6  471.85  4973.9  472.16  4988.2  469.34  4988.6  468.71
  4989.1  467.91  4994.1  467.91  4994.6  468.71  5009.5  471.18  5030.8  473.00
  5052.1  474.14  5071.6  474.48  5098.2  475.60  5156.7  476.98  5168.4  477.88
  5220.7  479.49  5226.9  480.19  5257.6  481.49  5278.9  481.62  5334.5  480.81
#Mann=4,-1,0
  4631.1    0.16       0  4780.2    0.05       0  4988.6    0.03       0
  4994.6    0.05       0
Bank Sta=4915.4,5071.6
Exp/Cntr=0.3,0.1

Type RM Length L Ch R = 1,20213,378,378,378
BEGIN DESCRIPTION:
XS4097A
END DESCRIPTION:
XS GIS Cut Line= 4
      2779921.79      7047390.21      2779656.17      7047056.88
      2779557.21      7047010.01      2779333.21      7046900.61
#Sta/Elev= 30
  4493.1  480.04  4515.5  479.89  4523.5  479.21  4529.9  479.74  4537.9  478.68
  4544.3  479.53  4565.1  478.68  4594.0  479.06  4651.6  478.03  4693.2  478.12
  4707.7  477.02  4757.3  475.97  4779.7  476.73  4786.1  475.89  4806.9  475.08
  4872.2  474.04  4970.3  471.10  4987.3  470.92  4995.1  469.92  4995.6  469.12
  5000.6  469.12  5001.1  469.92  5004.5  470.23  5010.1  472.51  5020.2  473.65
  5037.6  474.04  5100.4  475.00  5139.9  476.74  5168.0  477.12  5278.1  480.88
#Mann=4,-1,0
  4493.1    0.16       0  4970.3    0.05       0  4995.1    0.03       0
  5001.1    0.05       0
Bank Sta=4872.2,5037.6
Exp/Cntr=0.3,0.1

Type RM Length L Ch R = 1,19835,433,433,433
BEGIN DESCRIPTION:
XS4098A
END DESCRIPTION:
XS GIS Cut Line= 3
      2780185.72      7046991.27      2779775.96      7046817.64
      2779429.36      7046769.12
#Sta/Elev= 30
  4518.5  480.36  4606.2  479.17  4623.4  478.01  4660.5  477.98  4728.9  476.07
  4752.6  474.29  4755.1  473.37  4758.2  472.20  4769.1  471.25  4854.1  471.19
  4866.8  472.50  4899.4  472.06  4921.1  472.94  4929.2  472.56  4934.6  470.67
  4956.2  471.14  4966.5  470.55  4984.7  472.26  4991.8  467.98  4992.3  467.18
  4997.3  467.18  4997.8  467.98  5004.9  468.04  5014.3  471.45  5022.8  473.37
  5025.1  473.99  5045.3  474.47  5115.4  473.62  5206.8  475.90  5313.5  479.51
#Mann=6,-1,0
  4518.5    0.16       0  4854.1    0.05       0  4956.2    0.16       0
  4991.8    0.07       0  4997.8    0.16       0  5115.4    0.05       0
Bank Sta=4755.1,5022.8
Exp/Cntr=0.3,0.1

Type RM Length L Ch R = 1,19402,304,304,304
BEGIN DESCRIPTION:
XS4099A
END DESCRIPTION:
XS GIS Cut Line= 3
      2780279.42      7046696.11      2779970.40      7046557.23
      2779509.30      7046553.76
#Sta/Elev= 30
  4630.7  478.42  4770.1  475.37  4816.4  473.75  4821.9  473.14  4874.4  472.50
  4891.4  471.94  4898.7  472.49  4914.5  472.35  4946.8  470.59  4974.9  470.91
  4984.9  468.92  4991.9  465.47  4992.4  464.67  4997.4  464.67  4997.9  465.47
  5004.9  469.17  5024.9  469.73  5034.9  470.62  5084.9  470.77  5104.9  469.90
  5144.9  470.95  5194.9  471.01  5204.9  471.33  5217.1  472.50  5224.9  473.23
  5253.5  472.87  5314.9  472.99  5374.9  475.40  5394.9  475.53  5430.6  476.86
#Mann=5,-1,0
  4630.7    0.05       0  4946.8    0.16       0  4991.9    0.07       0
  4997.9    0.16       0  5253.5    0.05       0
Bank Sta=4874.4,5217.1
Exp/Cntr=0.3,0.1

Type RM Length L Ch R = 1,19098,476,476,476
BEGIN DESCRIPTION:
UNT 185 in LFCCL Watershed 30.0
END DESCRIPTION:
XS GIS Cut Line= 3
      2780324.95      7046375.00      2779825.00      7046325.00
      2779425.04      7046474.98
#Sta/Elev= 30
  4452.2  478.53  4499.9  476.97  4555.1  476.19  4643.1  474.41  4711.0  471.90
  4773.7  470.48  4864.2  472.35  4874.2  471.33  4924.5  469.64  4934.5  468.46
  4957.3  468.20  4964.4  467.19  4969.8  468.84  4986.7  468.99  4994.7  465.44
  5000.0  468.15  5005.0  463.76  5005.5  462.96  5010.5  462.96  5011.0  463.76
  5018.7  469.78  5025.0  470.51  5030.3  469.49  5040.1  470.95  5067.9  471.58
  5094.3  471.90  5110.4  472.51  5170.9  472.62  5366.7  479.08  5381.8  479.11
#Mann=5,-1,0
  4452.2    0.05       0  4555.1    0.16       0  5005.0    0.07       0
  5011.0    0.16       0  5067.9    0.05       0
Bank Sta=4711,5094.3
Exp/Cntr=0.3,0.1

Type RM Length L Ch R = 1,18622,243,243,243
BEGIN DESCRIPTION:
UNT 185 in LFCCL Watershed 29.0
END DESCRIPTION:
XS GIS Cut Line= 3
      2780524.99      7046175.00      2779725.00      7046075.00
      2779424.99      7046425.01
#Sta/Elev= 30
  4223.0  483.03  4283.5  483.05  4333.8  479.66  4535.4  476.23  4559.7  475.20
  4619.7  473.58  4754.5  470.75  4799.5  469.83  4837.7  468.60  4905.8  470.22
  4928.4  469.38  4958.7  469.45  4978.8  468.35  4986.4  465.15  4991.4  468.66
  4999.0  468.22  5016.1  463.81  5016.6  463.01  5021.6  463.01  5022.1  463.81
  5026.7  467.99  5032.5  467.99  5036.3  469.45  5042.9  469.93  5093.4  470.28
  5107.7  471.22  5146.7  470.75  5156.5  471.00  5426.0  478.14  5490.2  478.69
#Mann=7,-1,0
  4223.0    0.05       0  4559.7    0.16       0  4619.7    0.05       0
  4799.5    0.16       0  5016.1    0.07       0  5022.1    0.16       0
  5156.5    0.05       0
Bank Sta=4754.5,5146.7
Exp/Cntr=0.3,0.1

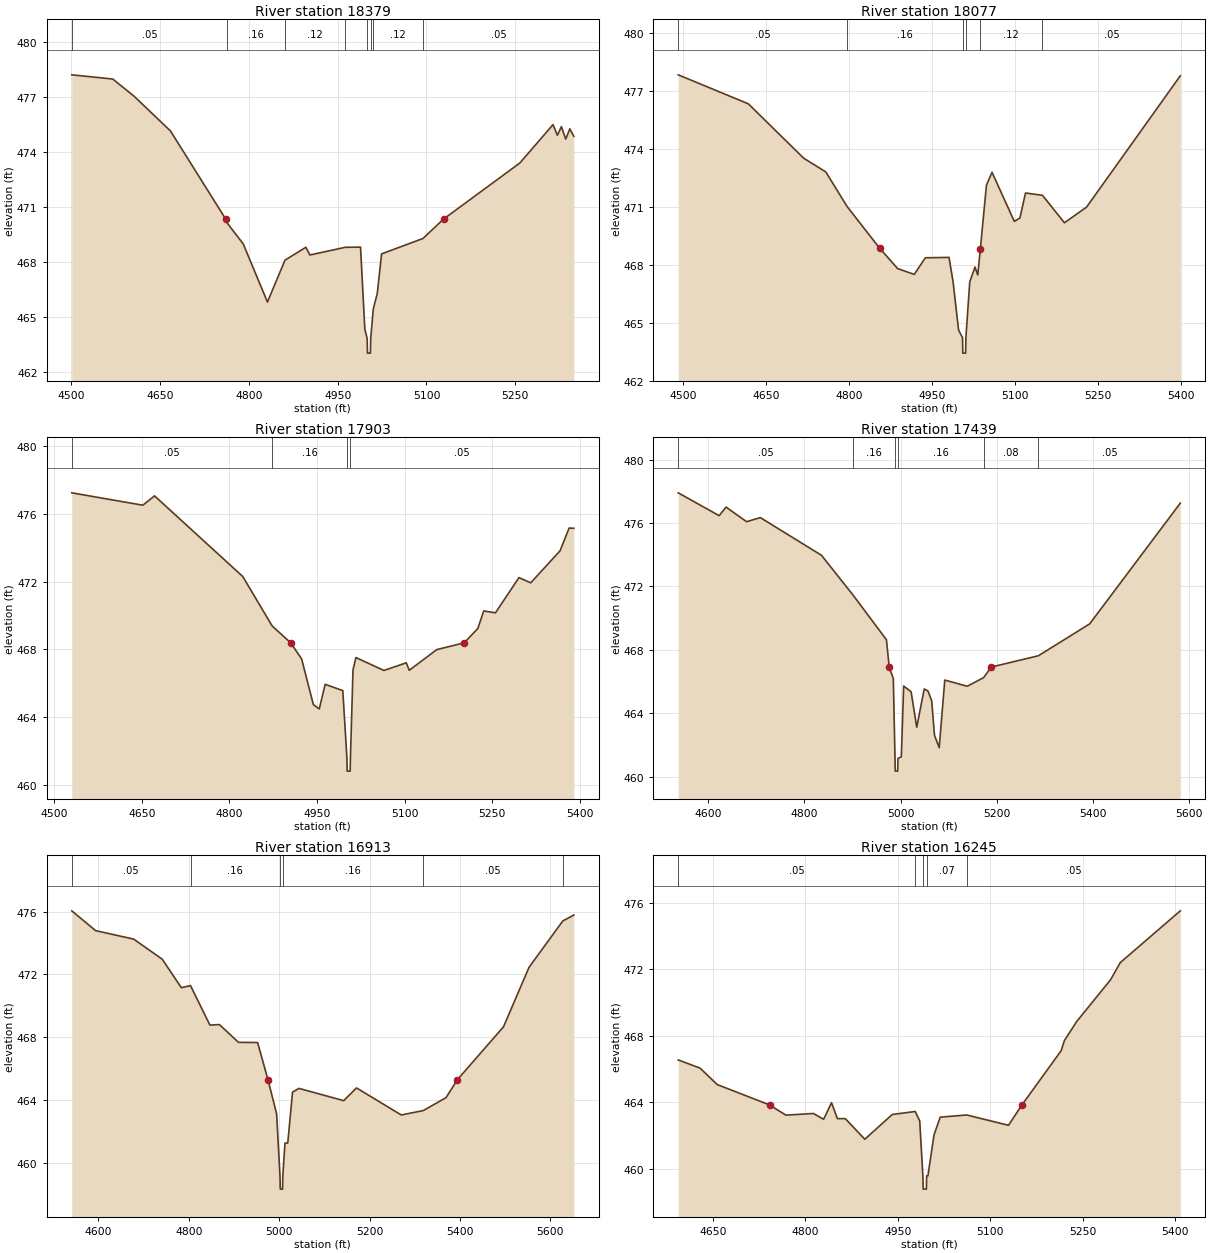
Type RM Length L Ch R = 1,18379,302,302,302
BEGIN DESCRIPTION:
XS4100A
END DESCRIPTION:
XS GIS Cut Line= 3
      2780157.93      7045755.14      2779685.68      7045859.31
      2779419.15      7046108.54
#Sta/Elev= 30
  4500.6  478.22  4569.9  477.99  4606.0  477.05  4667.5  475.15  4760.8  470.34
  4763.6  470.11  4790.3  468.99  4831.3  465.81  4861.0  468.10  4896.2  468.80
  4903.0  468.38  4962.9  468.80  4988.6  468.81  4995.9  464.33  4999.8  463.82
  5000.3  463.02  5005.3  463.02  5005.8  463.82  5010.2  465.44  5016.9  466.28
  5024.2  468.44  5094.0  469.28  5128.9  470.34  5257.7  473.40  5313.9  475.50
  5321.3  474.92  5328.1  475.39  5335.4  474.71  5342.3  475.27  5349.1  474.86
#Mann=8,-1,0
  4500.6    0.05       0  4763.6    0.16       0  4861.0    0.12       0
  4962.9    0.16       0  4999.8    0.07       0  5005.8    0.16       0
  5010.2    0.12       0  5094.0    0.05       0
Bank Sta=4760.8,5128.9
Exp/Cntr=0.3,0.1

Type RM Length L Ch R = 1,18077,174,174,174
BEGIN DESCRIPTION:
XS4101A
END DESCRIPTION:
XS GIS Cut Line= 4
      2780171.79      7045612.78      2779682.21      7045616.26
      2779484.29      7045591.95      2779265.51      7045588.48
#Sta/Elev= 30
  4490.8  477.82  4617.6  476.32  4717.6  473.51  4757.6  472.80  4796.4  471.00
  4855.4  468.84  4887.6  467.80  4917.6  467.50  4937.6  468.36  4980.4  468.38
  4987.7  467.13  4997.7  464.62  5004.8  464.23  5005.3  463.43  5010.4  463.43
  5010.9  464.23  5017.9  467.11  5027.3  467.88  5032.4  467.47  5036.3  468.60
  5037.1  468.83  5048.1  472.12  5058.2  472.78  5098.5  470.24  5108.6  470.42
  5118.7  471.71  5149.4  471.59  5189.1  470.17  5229.1  470.98  5398.6  477.77
#Mann=6,-1,0
  4490.8    0.05       0  4796.4    0.16       0  5004.8    0.07       0
  5010.9    0.16       0  5036.3    0.12       0  5149.4    0.05       0
Bank Sta=4855.4,5037.1
Exp/Cntr=0.3,0.1

Type RM Length L Ch R = 1,17903,464,464,464
BEGIN DESCRIPTION:
XS4102A
END DESCRIPTION:
XS GIS Cut Line= 3
      2780185.70      7045539.87      2779744.71      7045484.31
      2779331.54      7045439.18
#Sta/Elev= 30
  4529.9  477.24  4651.6  476.51  4671.7  477.06  4822.9  472.30  4873.1  469.39
  4904.9  468.39  4923.7  467.44  4943.8  464.74  4953.9  464.49  4964.0  465.94
  4994.2  465.57  5001.2  461.62  5001.7  460.82  5006.8  460.82  5007.3  461.62
  5011.7  466.80  5016.7  467.52  5064.6  466.76  5103.0  467.21  5108.0  466.77
  5155.2  467.99  5202.3  468.39  5225.6  469.24  5235.6  470.27  5255.7  470.16
  5296.0  472.24  5316.1  471.93  5366.4  473.82  5381.9  475.16  5390.0  475.15
#Mann=4,-1,0
  4529.9    0.05       0  4873.1    0.16       0  5001.2    0.07       0
  5007.3    0.05       0
Bank Sta=4904.9,5202.3
Exp/Cntr=0.3,0.1

Type RM Length L Ch R = 1,17439,526,526,526
BEGIN DESCRIPTION:
UNT 185 in LFCCL Watershed 27.0
END DESCRIPTION:
XS GIS Cut Line= 3
      2780175.03      7045475.04      2779875.00      7045125.00
      2779375.02      7044825.01
#Sta/Elev= 30
  4537.5  477.90  4622.6  476.46  4636.9  477.00  4679.7  476.08  4708.2  476.34
  4835.5  473.96  4900.4  471.48  4970.5  468.64  4976.2  466.92  4984.8  466.19
  4988.3  461.16  4988.8  460.36  4993.9  460.36  4994.4  461.16  5001.4  461.26
  5006.3  465.72  5021.8  465.36  5033.5  463.13  5049.1  465.54  5056.8  465.41
  5064.6  464.79  5070.4  462.62  5080.2  461.84  5091.8  466.10  5138.5  465.71
  5172.5  466.25  5188.6  466.92  5286.4  467.63  5393.1  469.64  5581.6  477.25
#Mann=6,-1,0
  4537.5    0.05       0  4900.4    0.16       0  4988.3    0.07       0
  4994.4    0.16       0  5172.5    0.08       0  5286.4    0.05       0
Bank Sta=4976.2,5188.6
Exp/Cntr=0.3,0.1

Type RM Length L Ch R = 1,16913,668,668,668
BEGIN DESCRIPTION:
UNT 185 in LFCCL Watershed 26.0
END DESCRIPTION:
XS GIS Cut Line= 3
      2780324.99      7045224.96      2780175.00      7044775.00
      2779725.00      7044325.00
#Sta/Elev= 30
  4541.3  476.05  4594.0  474.79  4678.3  474.25  4741.5  472.97  4783.7  471.16
  4804.0  471.29  4846.9  468.78  4868.0  468.81  4910.2  467.68  4952.4  467.67
  4975.3  465.31  4994.5  463.13  5002.0  459.14  5002.5  458.34  5007.6  458.34
  5008.1  459.14  5013.0  461.27  5019.1  461.27  5029.7  464.51  5043.9  464.75
  5142.9  463.97  5171.2  464.78  5270.2  463.06  5319.0  463.34  5369.2  464.16
  5394.6  465.31  5496.4  468.67  5553.0  472.46  5627.7  475.41  5652.0  475.78
#Mann=6,-1,0
  4541.3    0.05       0  4804.0    0.16       0  5002.0    0.07       0
  5008.1    0.16       0  5319.0    0.05       0  5627.7    0.08       0
Bank Sta=4975.3,5394.6
Exp/Cntr=0.3,0.1

Type RM Length L Ch R = 1,16245,475,475,475
BEGIN DESCRIPTION:
XS4103A
END DESCRIPTION:
XS GIS Cut Line= 3
      2780557.17      7044498.18      2780199.57      7044317.64
      2779788.21      7044265.79
#Sta/Elev= 30
  4593.5  466.54  4628.9  466.05  4656.8  465.06  4742.0  463.83  4768.3  463.22
  4812.9  463.32  4829.6  462.97  4842.4  463.97  4851.9  463.01  4864.8  463.01
  4896.4  461.77  4941.0  463.26  4978.3  463.44  4985.6  462.87  4990.7  459.57
  4991.2  458.77  4996.4  458.77  4996.9  459.57  4998.9  459.57  5008.8  462.03
  5018.9  463.10  5061.9  463.23  5129.7  462.61  5151.5  463.83  5215.3  467.10
  5220.4  467.70  5240.6  468.86  5295.6  471.37  5311.1  472.39  5408.7  475.51
#Mann=5,-1,0
  4593.5    0.05       0  4978.3    0.07       0  4990.7    0.07       0
  4996.9    0.07       0  5061.9    0.05       0
Bank Sta=4742,5151.5
Exp/Cntr=0.3,0.1

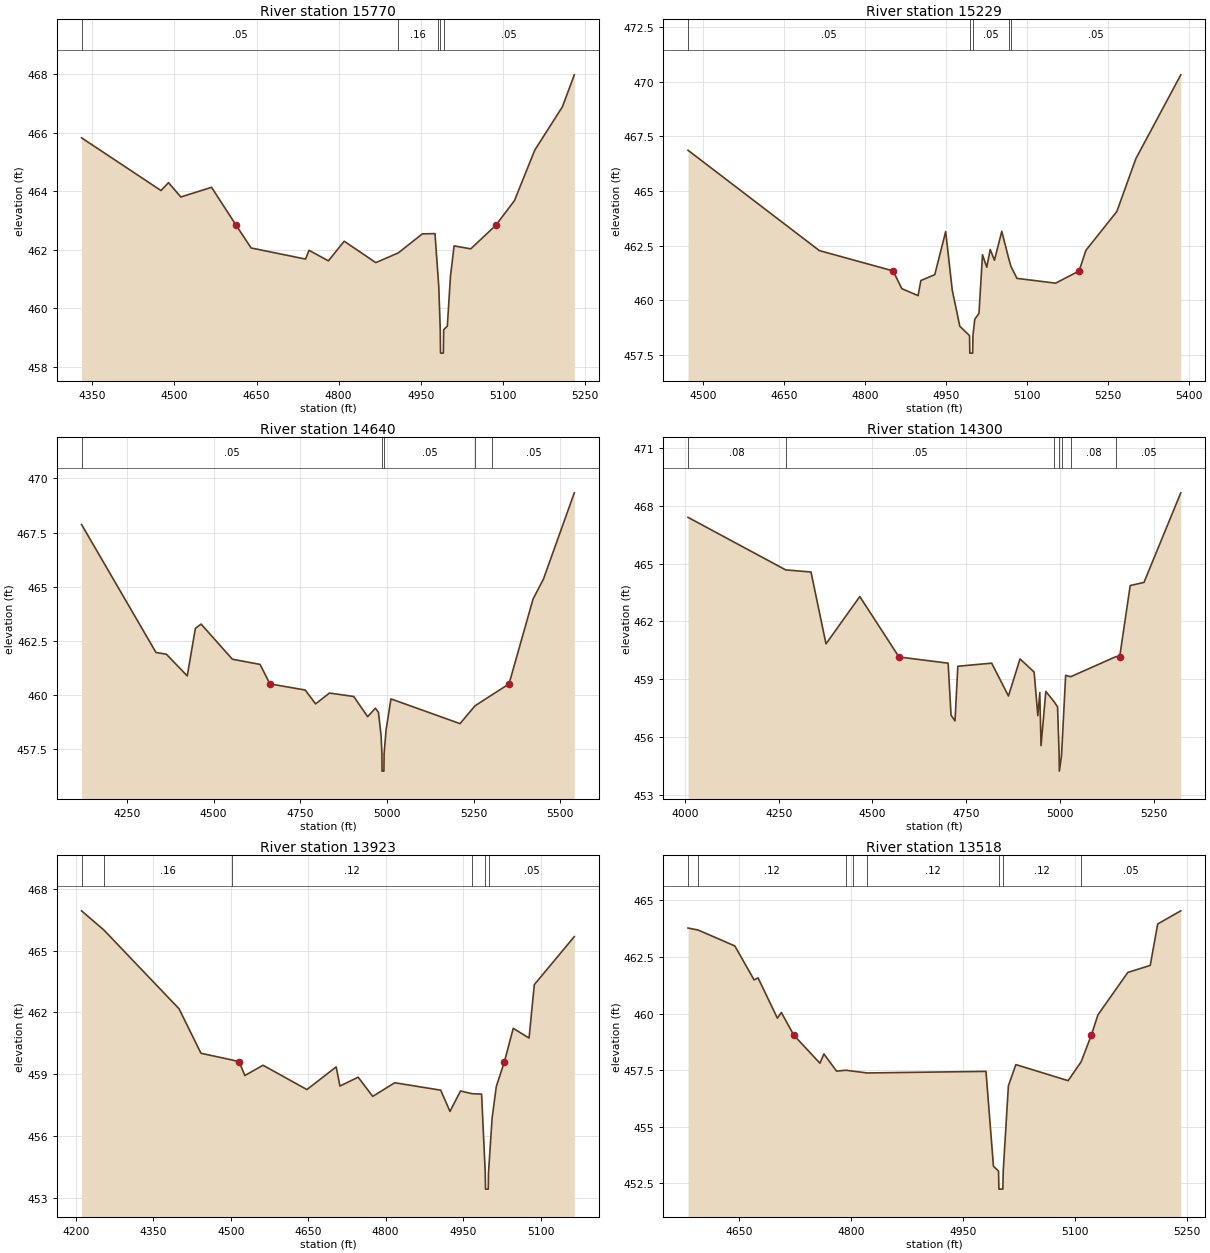
Type RM Length L Ch R = 1,15770,541,541,541
BEGIN DESCRIPTION:
XS4104A
END DESCRIPTION:
XS GIS Cut Line= 3
      2780664.84      7044519.03      2780293.32      7044046.81
      2780036.36      7043894.02
#Sta/Elev= 30
  4330.5  465.82  4475.6  464.02  4489.3  464.29  4511.8  463.80  4567.9  464.13
  4612.6  462.84  4640.1  462.06  4739.5  461.68  4745.9  461.98  4781.2  461.62
  4810.1  462.29  4867.8  461.56  4908.8  461.89  4952.7  462.54  4975.9  462.55
  4981.1  461.19  4982.8  460.75  4985.5  459.27  4986.0  458.47  4991.2  458.47
  4991.7  459.27  4998.4  459.39  5004.2  461.10  5010.8  462.13  5041.2  462.03
  5087.3  462.84  5121.1  463.68  5158.1  465.40  5208.6  466.88  5230.3  467.97
#Mann=5,-1,0
  4330.5    0.05       0  4908.8    0.16       0  4981.1    0.05       0
  4985.5    0.03       0  4991.7    0.05       0
Bank Sta=4612.6,5087.3
Exp/Cntr=0.3,0.1

Type RM Length L Ch R = 1,15229,589,589,589
BEGIN DESCRIPTION:
XS4105A
END DESCRIPTION:
XS GIS Cut Line= 3
      2780831.51      7044473.88      2780741.24      7044005.14
      2780464.17      7043669.20
#Sta/Elev= 30
  4471.8  466.86  4715.1  462.27  4851.8  461.34  4867.8  460.53  4898.0  460.21
  4903.1  460.90  4928.9  461.17  4949.1  463.14  4961.3  460.46  4975.3  458.81
  4993.3  458.38  4993.8  457.58  4999.1  457.58  4999.6  458.38  5003.0  459.13
  5010.8  459.40  5017.3  462.08  5025.2  461.51  5031.6  462.32  5039.5  461.83
  5053.0  463.15  5066.6  461.84  5070.0  461.55  5081.1  461.00  5152.8  460.78
  5196.3  461.34  5208.8  462.28  5266.2  464.06  5301.3  466.47  5384.6  470.31
#Mann=5,-1,0
  4471.8    0.05       0  4993.3    0.03       0  4999.6    0.05       0
  5066.6    0.16       0  5070.0    0.05       0
Bank Sta=4851.8,5196.3
Exp/Cntr=0.3,0.1

Type RM Length L Ch R = 1,14640,340,340,340
BEGIN DESCRIPTION:
XS4106A
END DESCRIPTION:
XS GIS Cut Line= 6
      2780907.90      7044449.58      2780939.15      7043605.84
      2780894.02      7043508.62      2780845.40      7043390.56
      2780727.35      7043314.17      2780525.94      7043314.17
#Sta/Elev= 30
  4119.2  467.87  4333.9  461.97  4363.9  461.89  4424.0  460.89  4447.5  463.08
  4464.0  463.28  4554.1  461.66  4634.1  461.42  4662.5  460.52  4764.2  460.24
  4794.2  459.60  4834.3  460.10  4904.3  459.94  4944.3  459.01  4966.7  459.40
  4975.5  459.21  4983.1  458.15  4985.5  457.30  4986.0  456.50  4991.3  456.50
  4991.8  457.30  4997.5  458.40  5011.5  459.83  5210.8  458.69  5254.0  459.51
  5304.2  460.03  5352.1  460.52  5421.3  464.43  5451.3  465.35  5540.4  469.33
#Mann=5,-1,0
  4119.2    0.05       0  4985.5    0.04       0  4991.8    0.05       0
  5254.0    0.08       0  5304.2    0.05       0
Bank Sta=4662.5,5352.1
Exp/Cntr=0.3,0.1

Type RM Length L Ch R = 1,14300,377,377,377
BEGIN DESCRIPTION:
XS4107A
END DESCRIPTION:
XS GIS Cut Line= 6
      2781011.06      7044212.64      2781028.42      7043687.44
      2780969.83      7043437.87      2780887.36      7043259.92
      2780800.55      7043179.62      2780598.25      7043106.45
#Sta/Elev= 30
  4008.4  467.39  4268.7  464.67  4336.2  464.56  4376.2  460.84  4466.3  463.29
  4570.8  460.16  4701.8  459.84  4709.5  457.15  4720.1  456.85  4727.6  459.68
  4817.8  459.84  4862.6  458.14  4893.4  460.06  4931.0  459.38  4940.9  457.12
  4946.1  458.32  4949.4  455.57  4962.2  458.38  4983.6  457.86  4993.5  457.58
  4997.7  455.05  4998.2  454.25  5004.0  455.05  5015.0  459.21  5028.6  459.14
  5149.3  460.18  5159.0  460.16  5187.1  463.86  5223.8  464.02  5321.9  468.66
#Mann=7,-1,0
  4008.4    0.08       0  4268.7    0.05       0  4983.6    0.16       0
  4997.7    0.07       0  5004.0    0.16       0  5028.6    0.08       0
  5149.3    0.05       0
Bank Sta=4570.8,5159
Exp/Cntr=0.3,0.1

Type RM Length L Ch R = 1,13923,405,405,405
BEGIN DESCRIPTION:
XS4108A
END DESCRIPTION:
XS GIS Cut Line= 3
      2781428.62      7043508.21      2780925.12      7043032.49
      2780669.12      7042980.60
#Sta/Elev= 30
  4211.3  466.93  4254.5  466.00  4400.0  462.18  4442.5  460.02  4501.9  459.70
  4516.5  459.61  4527.4  458.94  4562.6  459.44  4647.6  458.26  4704.2  459.36
  4711.5  458.43  4746.7  458.86  4775.0  457.93  4817.5  458.59  4906.6  458.23
  4924.5  457.20  4944.9  458.19  4967.3  458.06  4985.7  458.04  4992.8  454.23
  4993.3  453.43  4998.6  453.43  4999.1  454.23  5006.1  456.88  5014.2  458.41
  5029.9  459.61  5047.0  461.23  5077.6  460.76  5087.8  463.35  5165.2  465.68
#Mann=6,-1,0
  4211.3    0.05       0  4254.5    0.16       0  4501.9    0.12       0
  4967.3    0.05       0  4992.8    0.04       0  4999.1    0.05       0
Bank Sta=4516.5,5029.9
Exp/Cntr=0.3,0.1

Type RM Length L Ch R = 1,13518,470,470,470
BEGIN DESCRIPTION:
XS4109A
END DESCRIPTION:
XS GIS Cut Line= 3
      2781373.07      7042949.17      2781011.93      7042824.15
      2780734.11      7042827.63
#Sta/Elev= 30
  4581.9  463.78  4595.6  463.69  4644.6  462.99  4670.4  461.49  4675.7  461.58
  4701.6  459.80  4706.9  460.05  4723.6  459.05  4758.6  457.81  4763.9  458.22
  4780.9  457.46  4793.2  457.50  4802.7  457.46  4822.0  457.38  4981.0  457.45
  4991.0  453.26  4997.8  453.05  4998.3  452.25  5003.6  452.25  5004.1  453.05
  5011.0  456.81  5021.0  457.75  5091.0  457.04  5108.4  457.87  5122.1  459.05
  5131.0  459.95  5171.0  461.82  5201.0  462.13  5211.0  463.96  5241.9  464.54
#Mann=8,-1,0
  4581.9    0.16       0  4595.6    0.12       0  4793.2    0.05       0
  4802.7    0.16       0  4822.0    0.12       0  4997.8    0.07       0
  5004.1    0.12       0  5108.4    0.05       0
Bank Sta=4723.6,5122.1
Exp/Cntr=0.3,0.1