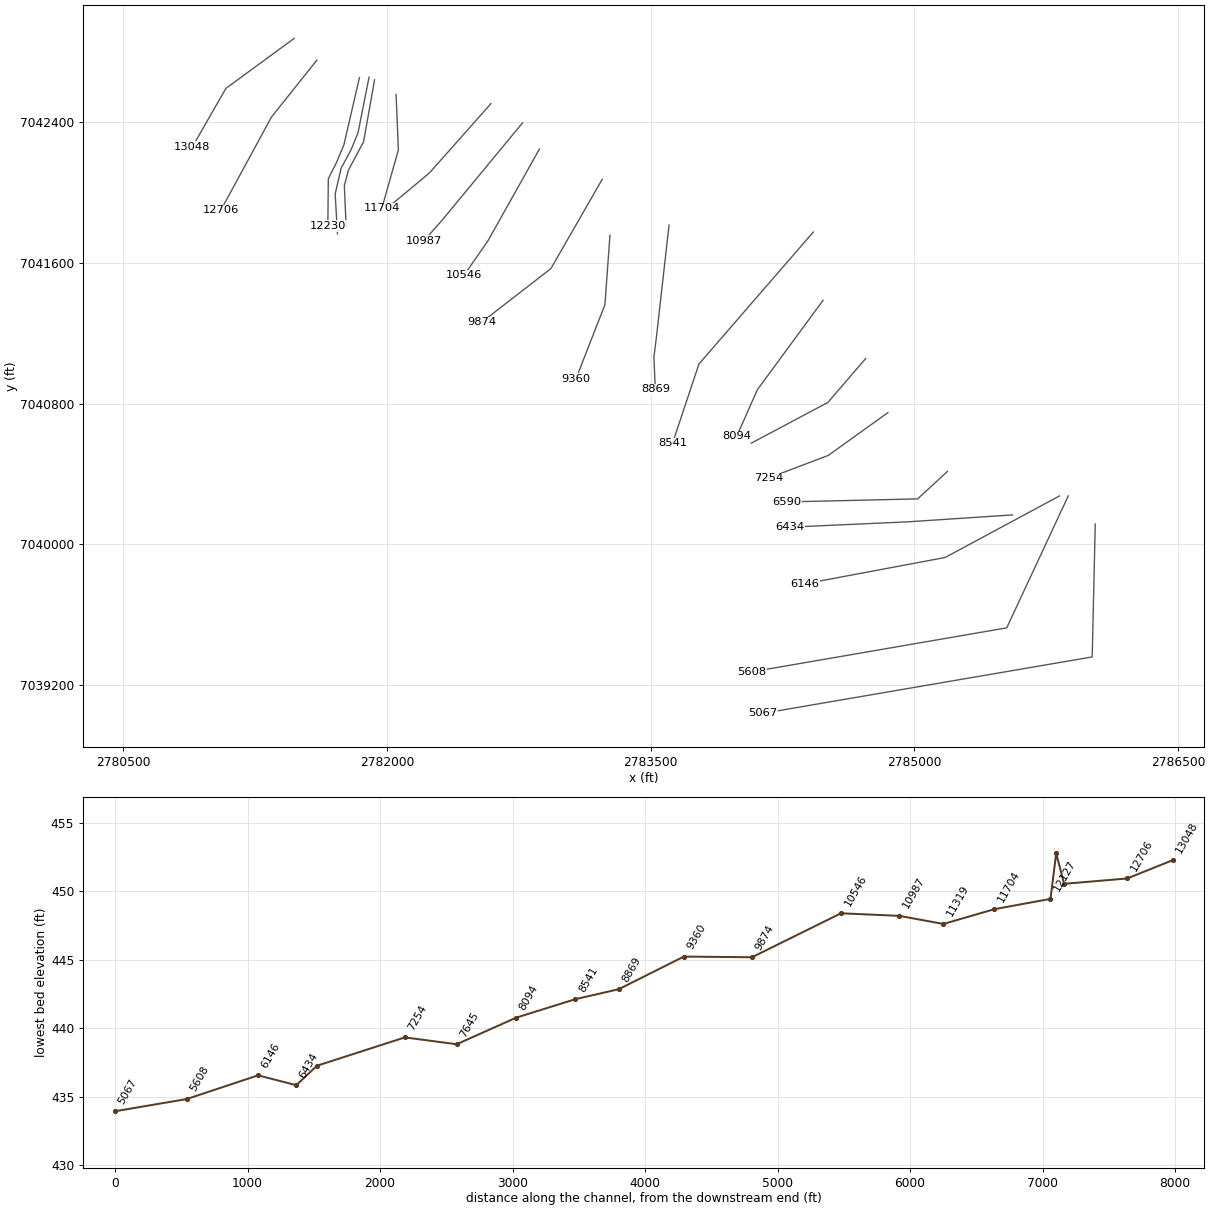
HEC-RAS study UNT 185 in LFCCL Watershed.prj: UNT 185 in LFCCL Watershed Base Level Engineering

--- UNT 185 in LFCCL Watershed.g01 (geometry) --- (continued)

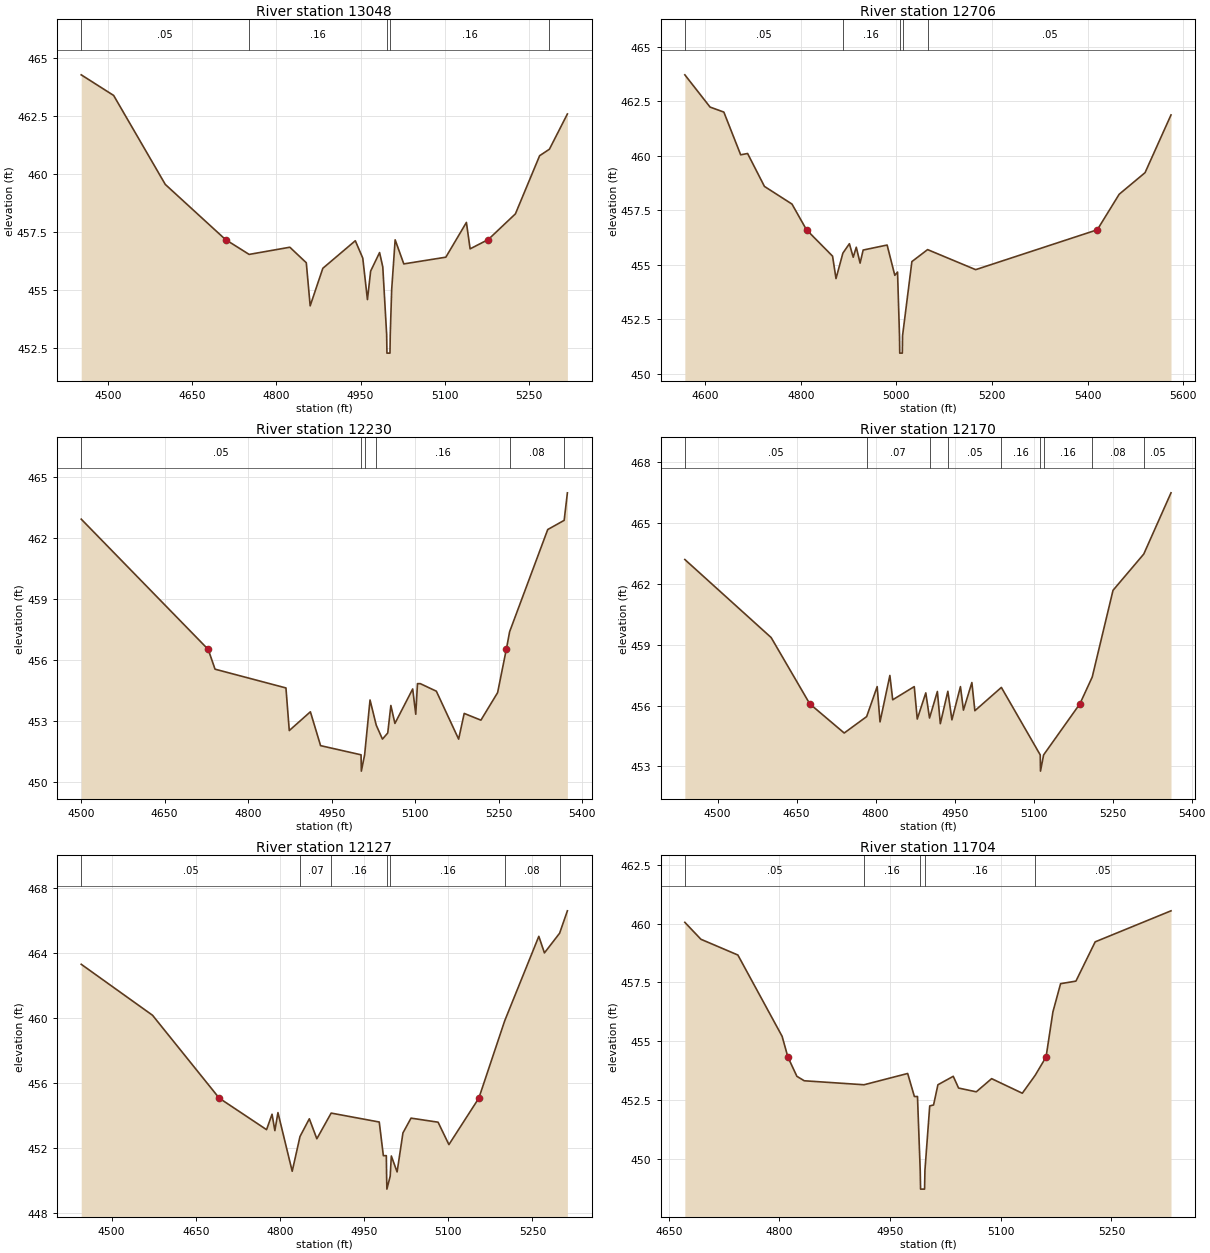
Type RM Length L Ch R = 1,13048,342,342,342
BEGIN DESCRIPTION:
XS4110A
END DESCRIPTION:
XS GIS Cut Line= 3
      2781473.71      7042876.22      2781084.84      7042591.52
      2780894.37      7042259.06
#Sta/Elev= 30
  4452.9  464.28  4510.6  463.39  4602.5  459.55  4709.7  457.17  4751.7  456.53
  4824.1  456.84  4853.4  456.17  4860.3  454.31  4882.8  455.93  4940.6  457.12
  4953.9  456.37  4962.2  454.58  4967.9  455.81  4983.8  456.61  4989.5  455.99
  4996.4  453.07  4996.9  452.27  5002.3  452.27  5002.8  453.07  5005.3  455.00
  5011.5  457.16  5026.9  456.12  5101.7  456.41  5138.3  457.91  5144.9  456.77
  5177.1  457.17  5225.5  458.28  5268.6  460.79  5286.0  461.07  5318.0  462.59
#Mann=5,-1,0
  4452.9    0.05       0  4751.7    0.16       0  4996.4    0.07       0
  5002.8    0.16       0  5286.0    0.05       0
Bank Sta=4709.7,5177.1
Exp/Cntr=0.3,0.1

Type RM Length L Ch R = 1,12706,476,476,476
BEGIN DESCRIPTION:
XS4111A
END DESCRIPTION:
XS GIS Cut Line= 3
      2781602.23      7042752.14      2781344.39      7042429.19
      2781055.88      7041898.96
#Sta/Elev= 30
  4557.6  463.71  4610.4  462.23  4639.2  462.00  4674.4  460.04  4688.9  460.10
  4724.1  458.59  4781.7  457.78  4812.1  456.60  4866.6  455.39  4873.8  454.36
  4888.2  455.53  4901.8  455.96  4909.8  455.34  4916.2  455.80  4924.2  455.07
  4930.6  455.67  4980.7  455.90  4996.8  454.51  5002.5  454.66  5006.6  451.74
  5007.1  450.94  5012.5  450.94  5013.0  451.74  5032.5  455.14  5065.4  455.69
  5165.9  454.77  5420.3  456.60  5466.1  458.23  5520.2  459.22  5574.5  461.87
#Mann=5,-1,0
  4557.6    0.05       0  4888.2    0.16       0  5006.6    0.07       0
  5013.0    0.16       0  5065.4    0.05       0
Bank Sta=4812.1,5420.3
Exp/Cntr=0.3,0.1

Type RM Length L Ch R = 1,12230,60,60,60
BEGIN DESCRIPTION:
XS4112A
END DESCRIPTION:
XS GIS Cut Line= 5
      2781844.39      7042653.12      2781755.85      7042270.34
      2781714.18      7042171.38      2781667.31      7042077.63
      2781664.71      7041809.72
#Sta/Elev= 30
  4500.2  462.91  4728.2  456.52  4740.5  455.55  4867.8  454.63  4873.8  452.54
  4911.7  453.46  4930.0  451.80  5002.7  451.35  5003.2  450.55  5009.1  451.35
  5018.8  454.04  5030.0  452.80  5041.1  452.12  5050.6  452.42  5056.2  453.77
  5063.5  452.89  5095.4  454.58  5100.9  453.34  5104.0  454.84  5109.1  454.84
  5137.9  454.47  5177.9  452.12  5187.9  453.38  5217.9  453.05  5247.9  454.40
  5263.5  456.52  5269.5  457.39  5337.9  462.40  5367.4  462.85  5373.2  464.20
#Mann=6,-1,0
  4500.2    0.05       0  5002.7    0.03       0  5009.1    0.05       0
  5030.0    0.16       0  5269.5    0.08       0  5367.4    0.05       0
Bank Sta=4728.2,5263.5
Exp/Cntr=0.3,0.1

Type RM Length L Ch R = 1,12170,43,43,43
BEGIN DESCRIPTION:
XS4113A
END DESCRIPTION:
XS GIS Cut Line= 6
      2781899.08      7042655.76      2781836.58      7042340.65
      2781797.52      7042244.29      2781740.22      7042137.52
      2781706.37      7041991.69      2781719.39      7041765.11
#Sta/Elev= 30
  4437.7  463.21  4601.6  459.36  4674.9  456.09  4740.3  454.65  4782.9  455.46
  4802.9  456.94  4808.3  455.20  4827.0  457.49  4832.4  456.29  4873.3  456.94
  4879.0  455.34  4895.2  456.63  4902.3  455.39  4917.2  456.70  4922.8  455.11
  4937.1  456.71  4944.8  455.30  4961.0  456.94  4966.7  455.78  4982.7  457.14
  4988.4  455.75  5038.7  456.90  5112.5  453.57  5113.0  452.77  5118.9  453.57
  5187.8  456.09  5211.2  457.41  5250.7  461.69  5309.1  463.48  5360.8  466.50
#Mann=9,-1,0
  4437.7    0.05       0  4782.9    0.07       0  4902.3    0.16       0
  4937.1    0.05       0  5038.7    0.16       0  5112.5    0.03       0
  5118.9    0.16       0  5211.2    0.08       0  5309.1    0.05       0
Bank Sta=4674.9,5187.8
Exp/Cntr=0.3,0.1

Type RM Length L Ch R = 1,12127,423,423,423
BEGIN DESCRIPTION:
XS4114A
END DESCRIPTION:
XS GIS Cut Line= 5
      2781930.32      7042640.10      2781867.83      7042288.56
      2781781.89      7042127.11      2781758.45      7042038.56
      2781768.87      7041804.14
#Sta/Elev= 30
  4446.0  463.29  4573.1  460.15  4691.9  455.05  4776.2  453.11  4786.0  454.06
  4791.0  453.05  4796.5  454.16  4821.9  450.55  4835.8  452.69  4852.4  453.78
  4865.8  452.55  4891.3  454.13  4977.0  453.58  4984.3  451.51  4989.6  451.51
  4990.1  450.25  4990.6  449.45  4996.5  450.25  4998.5  451.49  5008.8  450.51
  5019.2  452.91  5033.6  453.82  5081.8  453.57  5101.1  452.19  5154.4  455.05
  5200.5  459.81  5261.3  465.01  5271.3  463.99  5298.3  465.20  5312.2  466.58
#Mann=7,-1,0
  4446.0    0.05       0  4835.8    0.07       0  4891.3    0.16       0
  4990.1    0.07       0  4996.5    0.16       0  5200.5    0.08       0
  5298.3    0.05       0
Bank Sta=4691.9,5154.4
Exp/Cntr=0.3,0.1

Type RM Length L Ch R = 1,11704,385,385,385
BEGIN DESCRIPTION:
XS4115A
END DESCRIPTION:
XS GIS Cut Line= 3
      2782052.72      7042556.80      2782065.75      7042241.69
      2781972.01      7041911.00
#Sta/Elev= 30
  4671.7  460.05  4693.5  459.33  4743.6  458.66  4803.6  455.20  4811.4  454.32
  4823.6  453.50  4833.6  453.31  4914.6  453.14  4973.8  453.62  4982.9  452.64
  4987.1  452.64  4990.8  449.50  4991.3  448.70  4996.7  448.70  4997.2  449.50
  5003.7  452.24  5008.9  452.28  5014.8  453.14  5035.6  453.50  5042.8  453.00
  5066.8  452.84  5087.6  453.40  5129.2  452.78  5146.6  453.54  5161.4  454.32
  5170.7  456.24  5181.1  457.44  5201.9  457.55  5228.0  459.22  5330.8  460.54
#Mann=5,-1,0
  4671.7    0.05       0  4914.6    0.16       0  4990.8    0.07       0
  4997.2    0.16       0  5146.6    0.05       0
Bank Sta=4811.4,5161.4
Exp/Cntr=0.3,0.1

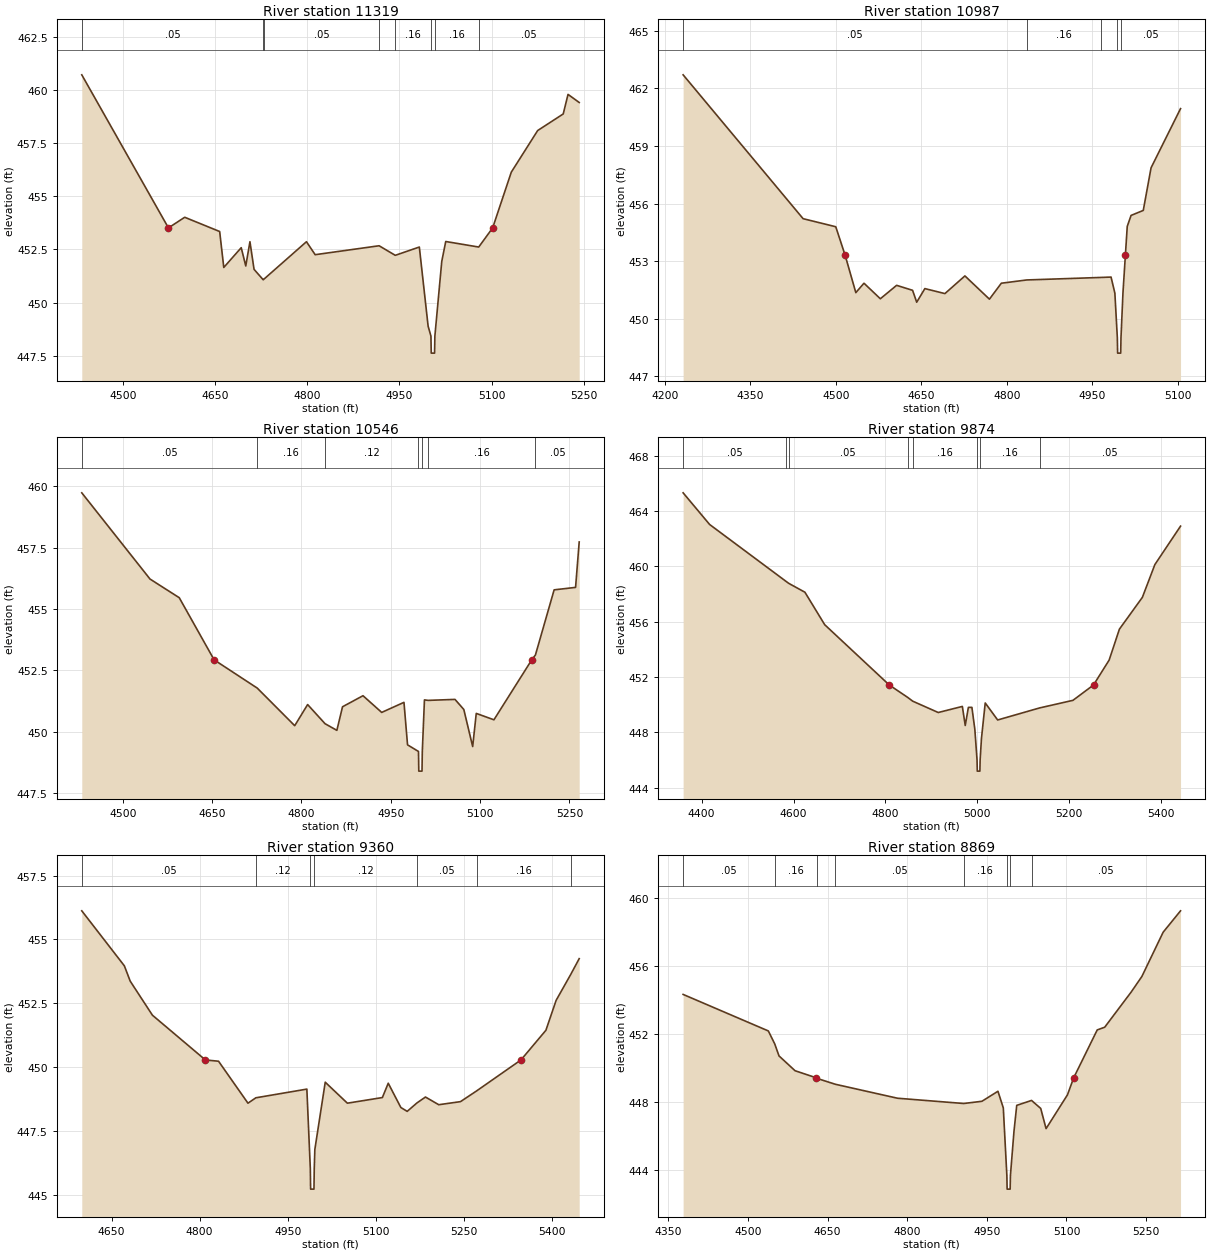
Type RM Length L Ch R = 1,11319,332,332,332
BEGIN DESCRIPTION:
XS4116A
END DESCRIPTION:
XS GIS Cut Line= 3
      2782591.81      7042504.74      2782242.83      7042111.48
      2782024.56      7041929.59
#Sta/Elev= 30
  4432.9  460.71  4574.0  453.51  4600.5  454.01  4657.4  453.34  4664.1  451.65
  4692.5  452.58  4699.9  451.72  4706.7  452.86  4713.4  451.56  4728.3  451.07
  4729.5  451.10  4798.7  452.86  4812.9  452.25  4917.0  452.67  4943.3  452.22
  4982.5  452.61  4996.8  448.89  5001.4  448.42  5001.9  447.62  5007.3  447.62
  5007.8  448.42  5019.0  451.93  5025.5  452.87  5079.2  452.61  5101.9  453.51
  5132.2  456.13  5175.2  458.09  5216.8  458.87  5224.6  459.79  5242.8  459.41
#Mann=8,-1,0
  4432.9    0.05       0  4728.3    0.16       0  4729.5    0.05       0
  4917.0    0.07       0  4943.3    0.16       0  5001.4    0.07       0
  5007.8    0.16       0  5079.2    0.05       0
Bank Sta=4574,5101.9
Exp/Cntr=0.3,0.1

Type RM Length L Ch R = 1,10987,441,441,441
BEGIN DESCRIPTION:
XS4117A
END DESCRIPTION:
XS GIS Cut Line= 3
      2782771.48      7042395.34      2782313.14      7041840.65
      2782211.56      7041726.04
#Sta/Elev= 30
  4231.9  462.70  4442.4  455.21  4499.7  454.79  4516.2  453.30  4534.9  451.36
  4549.2  451.85  4577.9  451.04  4606.5  451.74  4634.5  451.48  4641.7  450.86
  4656.0  451.57  4691.2  451.31  4726.3  452.23  4769.3  451.02  4790.2  451.85
  4834.9  452.02  4964.8  452.15  4982.7  452.17  4989.4  451.33  4993.7  449.01
  4994.2  448.21  4999.6  448.21  5000.1  449.01  5003.6  451.36  5007.8  453.30
  5011.1  454.81  5017.8  455.38  5039.2  455.64  5052.9  457.86  5104.6  460.94
#Mann=5,-1,0
  4231.9    0.05       0  4834.9    0.16       0  4964.8    0.05       0
  4993.7    0.04       0  5000.1    0.05       0
Bank Sta=4516.2,5007.8
Exp/Cntr=0.3,0.1

Type RM Length L Ch R = 1,10546,672,672,672
BEGIN DESCRIPTION:
UNT 185 in LFCCL Watershed 16.0
END DESCRIPTION:
XS GIS Cut Line= 3
      2782867.81      7042246.87      2782575.00      7041725.00
      2782439.71      7041530.41
#Sta/Elev= 30
  4431.0  459.73  4545.6  456.22  4594.7  455.46  4653.3  452.93  4725.7  451.78
  4788.6  450.25  4810.3  451.11  4839.6  450.33  4859.4  450.06  4868.9  451.02
  4903.3  451.47  4934.7  450.79  4972.1  451.20  4978.1  449.47  4996.5  449.20
  4997.0  448.40  5002.4  448.40  5002.9  449.20  5006.5  451.30  5012.8  451.28
  5057.8  451.32  5072.6  450.91  5087.5  449.40  5093.5  450.75  5123.2  450.49
  5186.7  452.93  5192.9  453.13  5224.3  455.78  5260.3  455.88  5266.4  457.73
#Mann=7,-1,0
  4431.0    0.05       0  4725.7    0.16       0  4839.6    0.12       0
  4996.5    0.07       0  5002.9    0.12       0  5012.8    0.16       0
  5192.9    0.05       0
Bank Sta=4653.3,5186.7
Exp/Cntr=0.3,0.1

Type RM Length L Ch R = 1,9874,514,514,514
BEGIN DESCRIPTION:
UNT 185 in LFCCL Watershed 15.0
END DESCRIPTION:
XS GIS Cut Line= 3
      2783225.00      7042074.99      2782932.93      7041567.21
      2782539.81      7041262.61
#Sta/Elev= 30
  4359.6  465.32  4417.3  463.03  4583.5  458.92  4589.7  458.77  4624.8  458.13
  4667.9  455.78  4808.5  451.42  4848.7  450.52  4859.5  450.25  4915.1  449.43
  4967.6  449.87  4973.9  448.49  4980.7  449.80  4988.4  449.80  4994.8  448.21
  4999.6  445.99  5000.1  445.19  5005.8  445.19  5006.3  445.99  5009.2  447.55
  5017.4  450.12  5044.5  448.89  5135.7  449.76  5208.4  450.31  5253.2  451.42
  5287.2  453.22  5309.6  455.46  5359.6  457.76  5386.8  460.13  5442.7  462.91
#Mann=8,-1,0
  4359.6    0.05       0  4583.5    0.16       0  4589.7    0.05       0
  4848.7    0.07       0  4859.5    0.16       0  4999.6    0.07       0
  5006.3    0.16       0  5135.7    0.05       0
Bank Sta=4808.5,5253.2
Exp/Cntr=0.3,0.1

Type RM Length L Ch R = 1,9360,491,491,491
BEGIN DESCRIPTION:
XS4118A
END DESCRIPTION:
XS GIS Cut Line= 3
      2783268.87      7041757.31      2783240.22      7041361.48
      2783076.16      7040942.20
#Sta/Elev= 30
  4599.3  456.12  4671.8  453.97  4681.8  453.37  4719.6  452.04  4809.8  450.29
  4832.2  450.24  4882.3  448.60  4895.7  448.81  4982.6  449.15  4988.5  446.04
  4989.0  445.24  4994.7  445.24  4995.2  446.04  4996.2  446.79  5013.9  449.42
  5051.6  448.60  5111.2  448.82  5121.2  449.38  5142.7  448.43  5153.5  448.28
  5170.1  448.61  5184.6  448.84  5207.2  448.54  5244.2  448.66  5271.7  449.08
  5347.2  450.29  5389.7  451.45  5407.1  452.62  5431.9  453.63  5446.4  454.25
#Mann=7,-1,0
  4599.3    0.05       0  4895.7    0.12       0  4988.5    0.07       0
  4995.2    0.12       0  5170.1    0.05       0  5271.7    0.16       0
  5431.9    0.05       0
Bank Sta=4809.8,5347.2
Exp/Cntr=0.3,0.1

Type RM Length L Ch R = 1,8869,328,328,328
BEGIN DESCRIPTION:
XS4119A
END DESCRIPTION:
XS GIS Cut Line= 4
      2783604.81      7041814.60      2783534.50      7041189.61
      2783518.87      7041064.61      2783526.68      7040882.28
#Sta/Elev= 30
  4377.6  454.32  4538.2  452.17  4550.2  451.41  4558.3  450.70  4588.5  449.83
  4628.8  449.41  4629.6  449.38  4664.7  449.03  4781.6  448.21  4906.4  447.90
  4940.7  448.03  4970.9  448.62  4981.0  447.64  4987.7  443.66  4988.2  442.86
  4993.9  442.86  4994.4  443.66  5001.1  446.26  5006.3  447.79  5034.2  448.08
  5051.5  447.61  5061.6  446.42  5101.9  448.41  5113.6  449.41  5158.0  452.23
  5172.1  452.39  5222.2  454.47  5242.2  455.38  5282.2  457.98  5315.0  459.24
#Mann=8,-1,0
  4377.6    0.05       0  4550.2    0.16       0  4629.6    0.12       0
  4664.7    0.05       0  4906.4    0.16       0  4987.7    0.07       0
  4994.4    0.16       0  5034.2    0.05       0
Bank Sta=4628.8,5113.6
Exp/Cntr=0.3,0.1

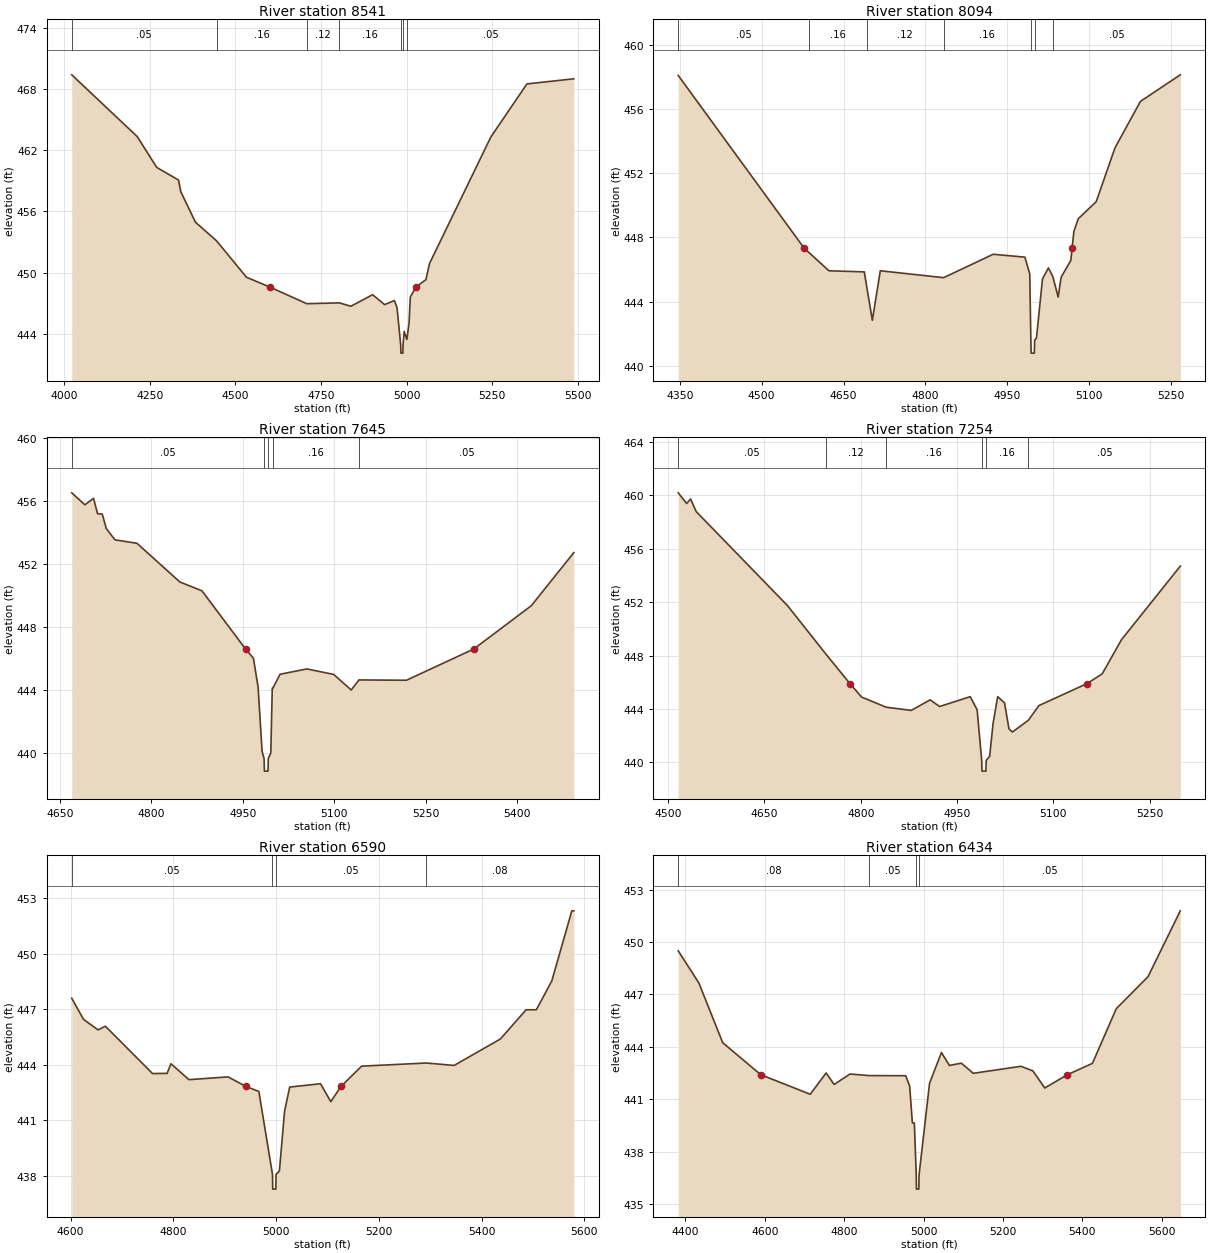
Type RM Length L Ch R = 1,8541,447,447,447
BEGIN DESCRIPTION:
UNT 185 in LFCCL Watershed 13.0
END DESCRIPTION:
XS GIS Cut Line= 3
      2784424.97      7041774.97      2783775.00      7041025.00
      2783624.99      7040574.97
#Sta/Elev= 30
  4021.7  469.38  4213.0  463.33  4270.0  460.31  4333.6  459.08  4340.3  457.93
  4383.0  454.95  4444.6  453.13  4532.1  449.56  4599.7  448.61  4708.2  446.97
  4803.8  447.05  4837.0  446.72  4900.6  447.85  4935.7  446.88  4964.2  447.28
  4971.9  446.59  4982.7  442.93  4983.2  442.13  4989.1  442.13  4989.6  442.93
  4992.8  444.25  5000.8  443.47  5007.0  445.07  5010.8  447.62  5027.2  448.61
  5056.3  449.32  5066.8  450.90  5246.0  463.29  5351.4  468.49  5488.5  468.99
#Mann=7,-1,0
  4021.7    0.05       0  4444.6    0.16       0  4708.2    0.12       0
  4803.8    0.16       0  4982.7    0.07       0  4989.6    0.16       0
  5000.8    0.05       0
Bank Sta=4599.7,5027.2
Exp/Cntr=0.3,0.1

Type RM Length L Ch R = 1,8094,449,449,449
BEGIN DESCRIPTION:
XS4120A
END DESCRIPTION:
XS GIS Cut Line= 3
      2784480.48      7041386.68      2784107.20      7040878.84
      2783990.01      7040614.08
#Sta/Elev= 30
  4347.2  458.11  4577.7  447.34  4586.3  447.07  4623.3  445.92  4688.1  445.85
  4692.4  444.95  4702.8  442.83  4717.4  445.92  4833.4  445.49  4924.2  446.95
  4982.3  446.77  4991.2  445.72  4993.2  441.58  4993.7  440.78  4999.6  440.78
  5000.1  441.58  5003.5  441.73  5014.5  445.41  5025.4  446.10  5033.4  445.56
  5043.2  444.28  5048.7  445.52  5066.5  446.57  5068.8  447.34  5072.0  448.37
  5080.1  449.17  5112.9  450.23  5147.3  453.59  5193.9  456.49  5267.0  458.15
#Mann=7,-1,0
  4347.2    0.05       0  4586.3    0.16       0  4692.4    0.12       0
  4833.4    0.16       0  4993.2    0.07       0  5000.1    0.16       0
  5033.4    0.05       0
Bank Sta=4577.7,5068.8
Exp/Cntr=0.3,0.1

Type RM Length L Ch R = 1,7645,391,391,391
BEGIN DESCRIPTION:
XS4121A
END DESCRIPTION:
XS GIS Cut Line= 3
      2784723.54      7041056.82      2784508.07      7040806.34
      2784072.48      7040575.03
#Sta/Elev= 30
  4669.6  456.54  4691.1  455.78  4705.3  456.19  4711.9  455.21  4719.6  455.19
  4726.2  454.27  4740.5  453.55  4776.6  453.33  4846.9  450.87  4883.1  450.31
  4954.6  446.61  4967.6  446.02  4975.3  444.17  4981.8  440.09  4985.1  439.64
  4985.6  438.84  4991.5  438.84  4992.0  439.64  4996.1  440.00  4998.5  444.12
  4999.5  444.12  5011.3  445.00  5055.3  445.34  5099.3  444.99  5128.0  444.00
  5140.7  444.64  5218.6  444.62  5329.2  446.61  5423.4  449.36  5493.2  452.74
#Mann=5,-1,0
  4669.6    0.05       0  4985.1    0.07       0  4992.0    0.05       0
  4999.5    0.16       0  5140.7    0.05       0
Bank Sta=4954.6,5329.2
Exp/Cntr=0.3,0.1

Type RM Length L Ch R = 1,7254,664,664,664
BEGIN DESCRIPTION:
XS4122A
END DESCRIPTION:
XS GIS Cut Line= 3
      2784849.35      7040748.61      2784510.84      7040505.58
      2784168.97      7040375.76
#Sta/Elev= 30
  4515.6  460.19  4528.7  459.39  4534.9  459.73  4543.5  458.79  4685.9  451.74
  4745.2  448.14  4783.3  445.89  4801.3  444.89  4839.6  444.13  4878.7  443.89
  4908.2  444.68  4922.9  444.18  4970.7  444.92  4981.4  443.93  4988.5  440.14
  4989.0  439.34  4995.0  439.34  4995.5  440.14  5000.9  440.45  5006.2  442.90
  5013.4  444.92  5024.1  444.45  5031.0  442.51  5036.4  442.27  5061.2  443.15
  5077.6  444.25  5152.3  445.89  5176.3  446.63  5206.4  449.19  5298.0  454.70
#Mann=6,-1,0
  4515.6    0.05       0  4745.2    0.12       0  4839.6    0.16       0
  4988.5    0.07       0  4995.5    0.16       0  5061.2    0.05       0
Bank Sta=4783.3,5152.3
Exp/Cntr=0.3,0.1

Type RM Length L Ch R = 1,6590,156,156,156
BEGIN DESCRIPTION:
XS4123A
END DESCRIPTION:
XS GIS Cut Line= 3
      2785187.94      7040414.45      2785018.65      7040258.18
      2784272.14      7040240.82
#Sta/Elev= 30
  4602.4  447.59  4625.3  446.45  4653.6  445.88  4667.8  446.08  4759.6  443.52
  4788.0  443.53  4795.4  444.05  4830.5  443.19  4906.5  443.34  4940.9  442.83
  4966.5  442.55  4993.0  438.07  4993.5  437.27  4999.5  437.27  5000.0  438.07
  5006.5  438.25  5016.5  441.48  5026.5  442.79  5086.5  442.97  5106.5  442.00
  5126.6  442.83  5166.5  443.92  5292.3  444.09  5346.6  443.96  5436.6  445.39
  5486.6  446.97  5506.6  446.97  5536.6  448.53  5575.6  452.32  5579.5  452.32
#Mann=4,-1,0
  4602.4    0.05       0  4993.0    0.03       0  5000.0    0.05       0
  5292.3    0.08       0
Bank Sta=4940.9,5126.6
Exp/Cntr=0.3,0.1

Type RM Length L Ch R = 1,6434,288,288,288
BEGIN DESCRIPTION:
XS4124A
END DESCRIPTION:
XS GIS Cut Line= 3
      2785556.85      7040167.04      2784966.57      7040127.97
      2784293.83      7040097.59
#Sta/Elev= 30
  4381.9  449.49  4433.9  447.65  4494.0  444.23  4589.8  442.40  4714.5  441.28
  4754.6  442.50  4774.6  441.84  4814.7  442.44  4861.6  442.35  4955.0  442.34
  4965.0  441.75  4971.8  439.64  4976.8  439.64  4981.6  436.65  4982.1  435.85
  4988.1  435.85  4988.6  436.65  5015.1  441.91  5045.1  443.67  5065.1  442.93
  5095.2  443.06  5125.2  442.48  5245.3  442.88  5275.4  442.62  5305.4  441.64
  5362.5  442.40  5425.5  443.05  5485.6  446.18  5565.6  448.01  5646.9  451.78
#Mann=4,-1,0
  4381.9    0.08       0  4861.6    0.05       0  4981.6    0.03       0
  4988.6    0.05       0
Bank Sta=4589.8,5362.5
Exp/Cntr=0.3,0.1

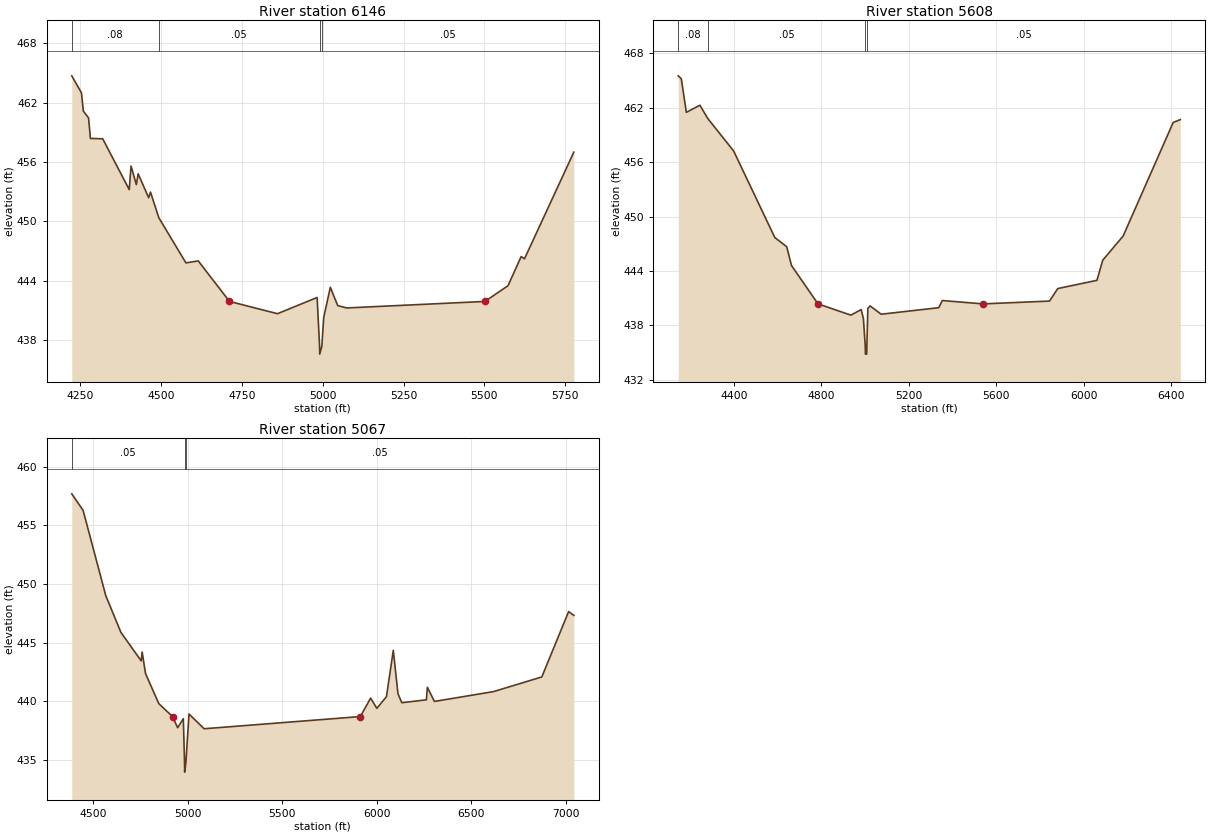
Type RM Length L Ch R = 1,6146,538,538,538
BEGIN DESCRIPTION:
UNT 185 in LFCCL Watershed 9.0
END DESCRIPTION:
XS GIS Cut Line= 3
      2785825.00      7040275.00      2785175.00      7039925.00
      2784374.99      7039775.00
#Sta/Elev= 30
  4224.3  464.72  4254.3  463.00  4260.0  461.16  4276.2  460.46  4281.9  458.39
  4320.0  458.35  4402.0  453.21  4407.6  455.59  4423.9  453.72  4429.6  454.81
  4462.0  452.39  4467.7  452.96  4493.4  450.37  4577.2  445.80  4615.3  446.00
  4711.9  441.90  4860.3  440.66  4982.9  442.30  4990.4  437.37  4990.9  436.57
  4997.4  437.37  5003.2  440.27  5023.6  443.33  5046.5  441.48  5074.5  441.24
  5501.7  441.90  5573.0  443.49  5613.7  446.44  5623.9  446.21  5776.5  457.00
#Mann=4,-1,0
  4224.3    0.08       0  4493.4    0.05       0  4990.4    0.03       0
  4997.4    0.05       0
Bank Sta=4711.9,5501.7
Exp/Cntr=0.3,0.1

Type RM Length L Ch R = 1,5608,541,541,541
BEGIN DESCRIPTION:
UNT 185 in LFCCL Watershed 8.0
END DESCRIPTION:
XS GIS Cut Line= 3
      2785875.01      7040275.02      2785525.00      7039525.00
      2784074.96      7039274.99
#Sta/Elev= 30
  4144.0  465.53  4158.2  465.20  4181.1  461.50  4243.3  462.29  4278.8  460.84
  4397.8  457.24  4586.2  447.70  4640.6  446.69  4662.7  444.61  4784.1  440.38
  4934.6  439.14  4981.8  439.75  4992.0  438.75  5000.6  435.64  5001.1  434.84
  5007.1  434.84  5007.6  435.64  5012.3  439.87  5022.4  440.16  5073.1  439.24
  5337.0  439.96  5353.2  440.75  5539.9  440.38  5844.4  440.69  5881.9  442.07
  6061.5  442.98  6087.9  445.20  6181.3  447.86  6410.6  460.39  6443.1  460.70
#Mann=4,-1,0
  4144.0    0.08       0  4278.8    0.05       0  5000.6    0.03       0
  5007.6    0.05       0
Bank Sta=4784.1,5539.9
Exp/Cntr=0.3,0.1

Type RM Length L Ch R = 1,5067,0,0,0
BEGIN DESCRIPTION:
UNT 185 in LFCCL Watershed 7.0
END DESCRIPTION:
XS GIS Cut Line= 3
      2786028.49      7040114.95      2786011.13      7039359.75
      2784138.02      7039038.89
#Sta/Elev= 30
  4387.1  457.69  4447.1  456.28  4567.1  449.00  4647.1  445.87  4754.4  443.44
  4759.4  444.20  4777.2  442.36  4847.2  439.80  4920.0  438.69  4947.2  437.74
  4977.2  438.51  4983.7  434.75  4984.2  433.95  4990.7  434.75  5007.2  438.91
  5087.2  437.65  5913.6  438.69  5967.8  440.26  6001.0  439.39  6051.7  440.39
  6087.9  444.34  6112.6  440.64  6132.9  439.87  6263.0  440.12  6268.1  441.19
  6305.3  439.98  6618.2  440.82  6873.5  442.07  7015.5  447.65  7042.9  447.32
#Mann=3,-1,0
  4387.1    0.05       0  4983.7    0.03       0  4990.7    0.05       0
Bank Sta=4920,5913.6
Exp/Cntr=0.3,0.1

Chan Stop Cuts=-1