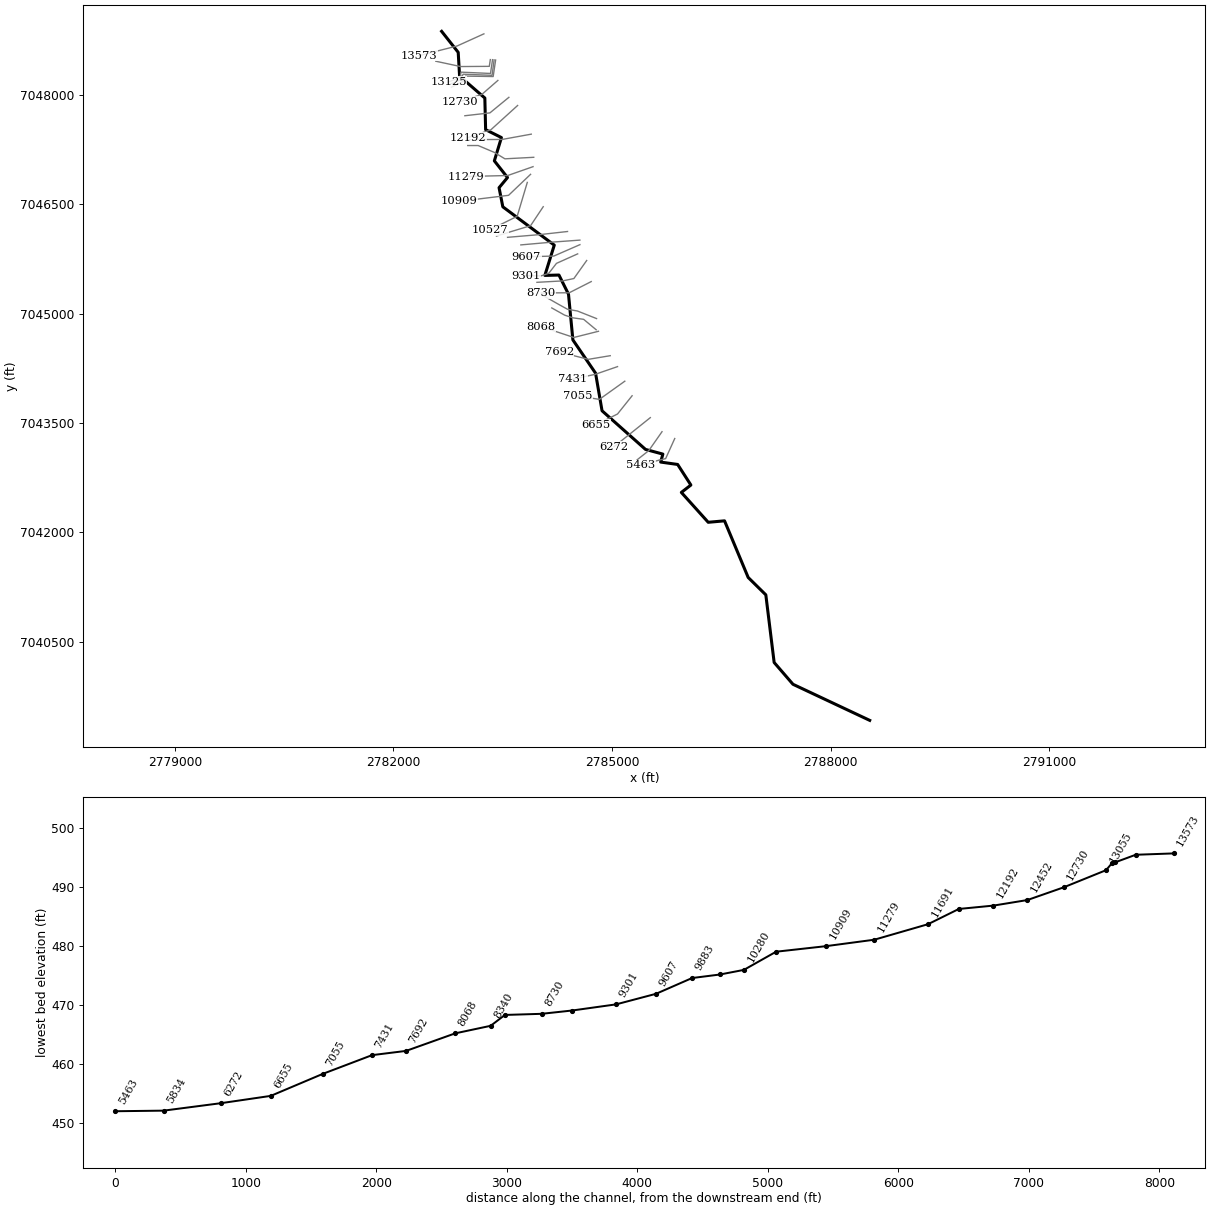
--- UNT 186 in LFCCL Watershed.prj (project) ---

Proj Title=UNT 186 in LFCCL Watershed Base Level Engineering
Current Plan=p01
Default Exp/Contr=0.3,0.1
English Units
Geom File=g01
Flow File=f01
Plan File=p01
BEGIN DESCRIPTION:
UNT 186 in LFCCL Watershed
END DESCRIPTION:

--- UNT 186 in LFCCL Watershed.p01 (plan) ---

Plan Title=Multiple Run
Short Identifier=Multiple
Geom File=g01
Flow File=f01
Subcritical Flow
K Sum by GR= 0
Std Step Tol= 0.01
Critical Tol= 0.01
Num of Std Step Trials= 20
Max Error Tol= 0.3
Flow Tol Ratio= 0.001
Split Flow NTrial= 30
Split Flow Tol= 0.02
Split Flow Ratio= 0.02
Log Output Level= 0
Friction Slope Method= 1
Unsteady Friction Slope Method= 2
Unsteady Bridges Friction Slope Method= 1
Parabolic Critical Depth
Global Vel Dist=  1 , 1 , 1
Global Log Level= 0
CheckData=True
Encroach Param= -1, 0, 0, 0
BEGIN DESCRIPTION:
Multiple Run
END DESCRIPTION:

--- UNT 186 in LFCCL Watershed.f01 (steady flow) ---

Flow Title=Multiple
Number of Profiles=7
Profile Names=10-year,25-year,50-year,1pct_min,100-year,1pct_plu,500-year
River Rch & RM= UNT 186 in LFCCL,Reach-1,13573
     206     257     296     170     338     675     443
River Rch & RM= UNT 186 in LFCCL,Reach-1,7692
     387     503     593     349     696    1388     957
Boundary for River Rch & Prof#=UNT 186 in LFCCL,Reach-1,1
Up Type=0
Dn Type=3
Dn Slope=0.005
Boundary for River Rch & Prof#=UNT 186 in LFCCL,Reach-1,2
Up Type=0
Dn Type=3
Dn Slope=0.005
Boundary for River Rch & Prof#=UNT 186 in LFCCL,Reach-1,3
Up Type=0
Dn Type=3
Dn Slope=0.005
Boundary for River Rch & Prof#=UNT 186 in LFCCL,Reach-1,4
Up Type=0
Dn Type=3
Dn Slope=0.005
Boundary for River Rch & Prof#=UNT 186 in LFCCL,Reach-1,5
Up Type=0
Dn Type=3
Dn Slope=0.005
Boundary for River Rch & Prof#=UNT 186 in LFCCL,Reach-1,6
Up Type=0
Dn Type=3
Dn Slope=0.005
Boundary for River Rch & Prof#=UNT 186 in LFCCL,Reach-1,7
Up Type=0
Dn Type=3
Dn Slope=0.005

--- UNT 186 in LFCCL Watershed.g01 (geometry) ---

Geom Title=Existing Conditions

River Reach=UNT 186 in LFCCL,Reach-1
Reach XY= 30
      2782661.21      7048875.80      2782888.64      7048587.61
      2782907.74      7048261.22      2783254.10      7047960.68
      2783264.95      7047526.66      2783481.96      7047418.15
      2783384.71      7047098.57      2783565.17      7046869.68
      2783449.41      7046730.13      2783500.83      7046467.99
      2784207.00      7045942.27      2784077.65      7045526.57
      2784271.05      7045531.58      2784402.05      7045269.26
      2784462.44      7044641.15      2784773.60      7044184.73
      2784862.48      7043669.11      2785458.76      7043138.89
      2785697.03      7043074.67      2785667.18      7042965.10
      2785900.03      7042932.43      2786081.63      7042650.05
      2785950.76      7042548.71      2786319.47      7042138.82
      2786543.35      7042158.80      2786867.93      7041381.52
      2787109.95      7041143.19      2787224.26      7040215.01
      2787482.52      7039915.97      2788535.59      7039420.71

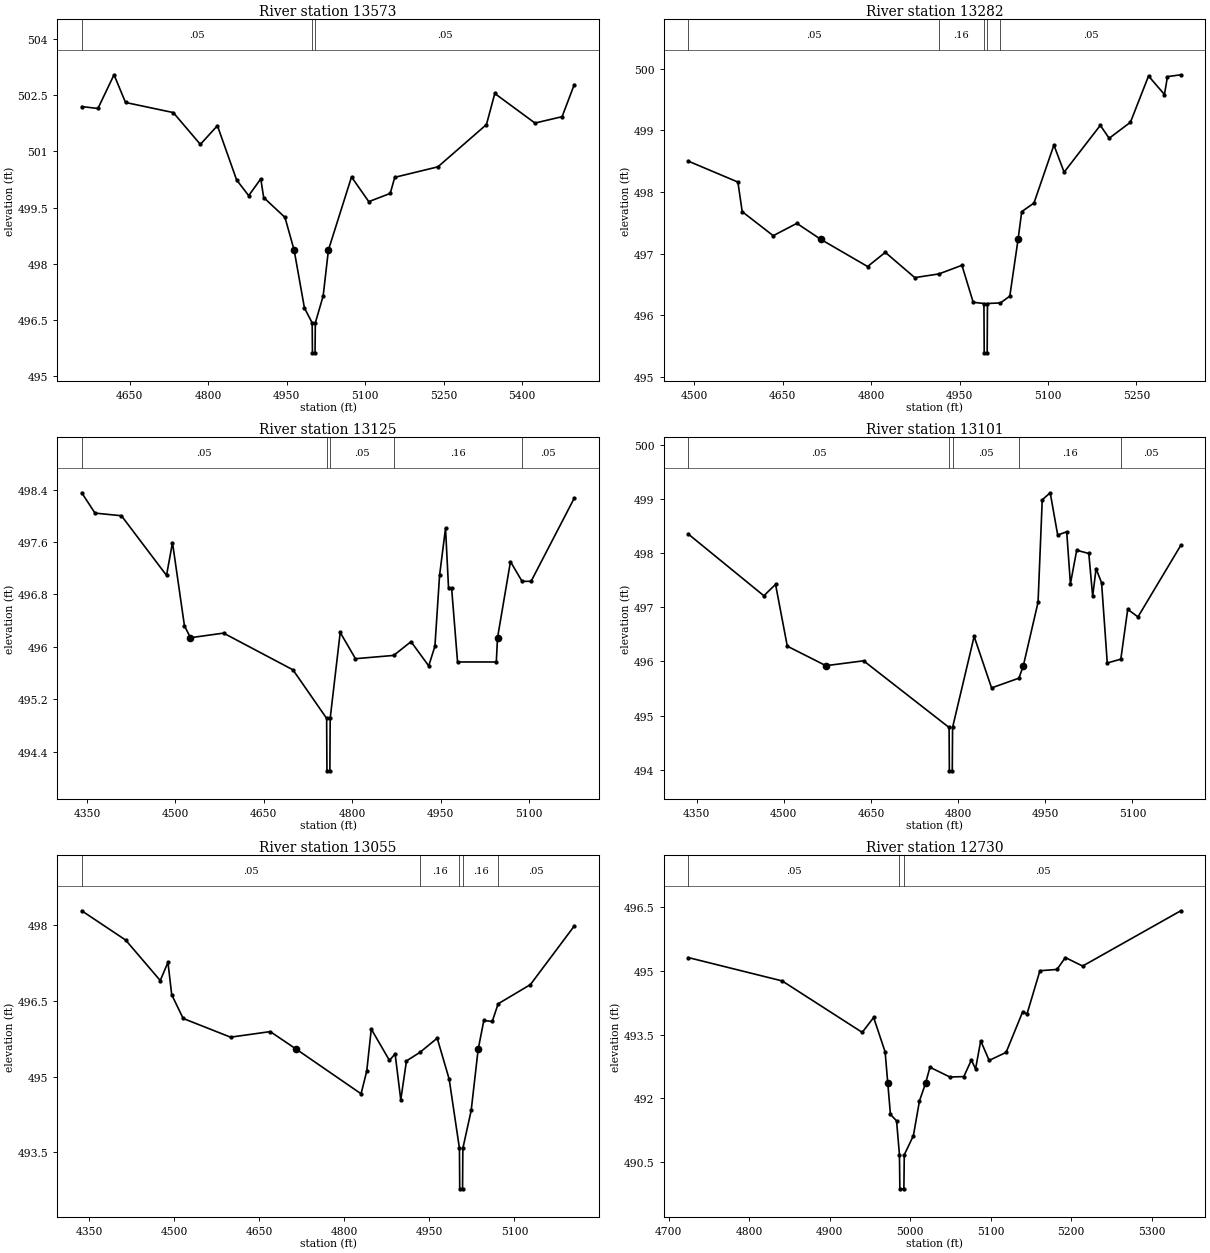
Type RM Length L Ch R = 1,13573,291,291,291
BEGIN DESCRIPTION:
UNT 186 in LFCCL Watershed 22.0
END DESCRIPTION:
XS GIS Cut Line= 3
      2783241.25      7048841.39      2782873.16      7048674.71
      2782352.28      7048542.75
#Sta/Elev= 30
  4558.3  502.20  4589.3  502.15  4620.0  503.05  4642.0  502.31  4733.3  502.04
  4785.0  501.19  4817.6  501.69  4854.3  500.24  4877.4  499.82  4900.5  500.27
  4906.0  499.77  4946.7  499.24  4964.3  498.36  4983.9  496.82  4998.7  496.42
  4999.2  495.62  5004.2  495.62  5004.7  496.42  5019.7  497.14  5029.8  498.37
  5073.9  500.32  5106.9  499.66  5147.9  499.88  5156.5  500.31  5239.0  500.59
  5331.8  501.72  5347.7  502.55  5424.5  501.76  5476.3  501.93  5499.7  502.79
#Mann=3,-1,0
  4558.3    0.05       0  4998.7    0.03       0  5004.7    0.05       0
Bank Sta=4964.3,5029.8
Exp/Cntr=0.3,0.1

Type RM Length L Ch R = 1,13282,157,157,157
BEGIN DESCRIPTION:
XS4125A
END DESCRIPTION:
XS GIS Cut Line= 4
      2783329.41      7048488.35      2783315.32      7048395.48
      2782921.77      7048392.59      2782581.48      7048465.51
#Sta/Elev= 30
  4489.7  498.50  4574.0  498.16  4581.3  497.68  4633.9  497.29  4674.0  497.49
  4714.7  497.23  4794.0  496.79  4824.0  497.02  4874.0  496.61  4915.0  496.67
  4954.0  496.81  4973.1  496.21  4991.3  496.19  4991.8  495.39  4996.8  495.39
  4997.3  496.19  5019.4  496.20  5035.2  496.31  5049.2  497.23  5055.4  497.68
  5076.2  497.82  5110.0  498.76  5127.3  498.32  5188.7  499.08  5203.7  498.87
  5239.8  499.13  5270.5  499.88  5297.5  499.58  5302.6  499.87  5325.2  499.90
#Mann=5,-1,0
  4489.7    0.05       0  4915.0    0.16       0  4991.3    0.07       0
  4997.3    0.16       0  5019.4    0.05       0
Bank Sta=4714.7,5049.2
Exp/Cntr=0.3,0.1

Type RM Length L Ch R = 1,13125,24,24,24
BEGIN DESCRIPTION:
XS4128A
END DESCRIPTION:
XS GIS Cut Line= 6
      2783359.79      7048487.27      2783331.65      7048297.96
      2782927.41      7048315.76      2782916.56      7048255.00
      2782875.33      7048228.96      2782755.94      7048181.20
#Sta/Elev= 30
  4341.2  498.35  4363.7  498.04  4408.5  498.00  4485.0  497.09  4495.1  497.59
  4515.4  496.32  4525.6  496.14  4581.7  496.21  4699.4  495.65  4756.5  494.91
  4757.0  494.11  4762.0  494.11  4762.5  494.91  4779.5  496.22  4805.4  495.82
  4870.2  495.87  4899.6  496.08  4929.6  495.71  4940.1  496.01  4948.0  497.09
  4958.1  497.81  4963.2  496.90  4968.4  496.90  4978.5  495.77  5044.2  495.77
  5046.3  496.14  5068.2  497.30  5087.9  497.00  5103.2  497.00  5176.5  498.27
#Mann=5,-1,0
  4341.2    0.05       0  4756.5    0.07       0  4762.5    0.05       0
  4870.2    0.16       0  5087.9    0.05       0
Bank Sta=4525.6,5046.3
Exp/Cntr=0.3,0.1

Type RM Length L Ch R = 1,13101,46,46,46
BEGIN DESCRIPTION:
XS4126A
END DESCRIPTION:
XS GIS Cut Line= 6
      2783381.49      7048484.01      2783353.19      7048272.33
      2782955.63      7048287.55      2782929.58      7048226.79
      2782912.22      7048207.26      2782779.92      7048150.87
#Sta/Elev= 30
  4335.6  498.35  4465.8  497.21  4485.9  497.42  4506.1  496.28  4572.6  495.92
  4637.4  496.01  4784.5  494.78  4785.0  493.98  4790.0  493.98  4790.5  494.78
  4827.6  496.46  4857.6  495.51  4904.7  495.69  4912.3  495.92  4937.6  497.09
  4944.8  498.98  4958.5  499.11  4971.4  498.33  4986.9  498.39  4993.3  497.43
  5004.1  498.05  5024.9  497.99  5031.6  497.20  5037.4  497.71  5046.9  497.45
  5056.7  495.97  5080.0  496.04  5091.9  496.96  5109.5  496.82  5183.2  498.14
#Mann=5,-1,0
  4335.6    0.05       0  4784.5    0.07       0  4790.5    0.05       0
  4904.7    0.16       0  5080.0    0.05       0
Bank Sta=4572.6,4912.3
Exp/Cntr=0.3,0.1

Type RM Length L Ch R = 1,13055,325,325,325
BEGIN DESCRIPTION:
XS4127A
END DESCRIPTION:
XS GIS Cut Line= 6
      2783402.11      7048481.87      2783368.48      7048255.51
      2782988.18      7048261.51      2782968.65      7048202.92
      2782951.29      7048187.73      2782795.43      7048109.79
#Sta/Elev= 30
  4337.2  498.28  4414.7  497.70  4475.6  496.90  4489.2  497.26  4495.8  496.62
  4516.0  496.15  4599.5  495.78  4669.5  495.89  4715.7  495.54  4829.6  494.66
  4839.6  495.11  4847.6  495.94  4879.6  495.32  4889.6  495.45  4899.6  494.54
  4909.6  495.31  4933.4  495.48  4963.8  495.76  4984.9  494.95  5003.0  493.58
  5003.5  492.78  5008.5  492.78  5009.0  493.58  5023.7  494.33  5036.0  495.54
  5046.0  496.11  5060.8  496.09  5071.2  496.44  5128.1  496.82  5205.5  497.98
#Mann=5,-1,0
  4337.2    0.05       0  4933.4    0.16       0  5003.0    0.07       0
  5009.0    0.16       0  5071.2    0.05       0
Bank Sta=4715.7,5036
Exp/Cntr=0.3,0.1

Type RM Length L Ch R = 1,12730,278,278,278
BEGIN DESCRIPTION:
XS4129A
END DESCRIPTION:
XS GIS Cut Line= 3
      2783433.06      7048202.05      2783211.70      7048009.34
      2782908.48      7047910.86
#Sta/Elev= 30
  4724.1  495.31  4840.9  494.76  4940.4  493.55  4954.6  493.90  4968.9  493.09
  4972.2  492.35  4975.5  491.62  4983.1  491.47  4986.7  490.67  4987.2  489.87
  4992.2  489.87  4992.7  490.67  5004.0  491.12  5011.6  491.94  5019.1  492.35
  5024.6  492.73  5049.4  492.50  5066.7  492.51  5076.1  492.90  5081.3  492.69
  5087.7  493.35  5098.2  492.89  5119.3  493.08  5140.0  494.04  5145.2  493.98
  5161.3  495.00  5182.5  495.03  5192.9  495.31  5214.4  495.11  5336.4  496.41
#Mann=3,-1,0
  4724.1    0.05       0  4986.7    0.03       0  4992.7    0.05       0
Bank Sta=4972.2,5019.1
Exp/Cntr=0.3,0.1

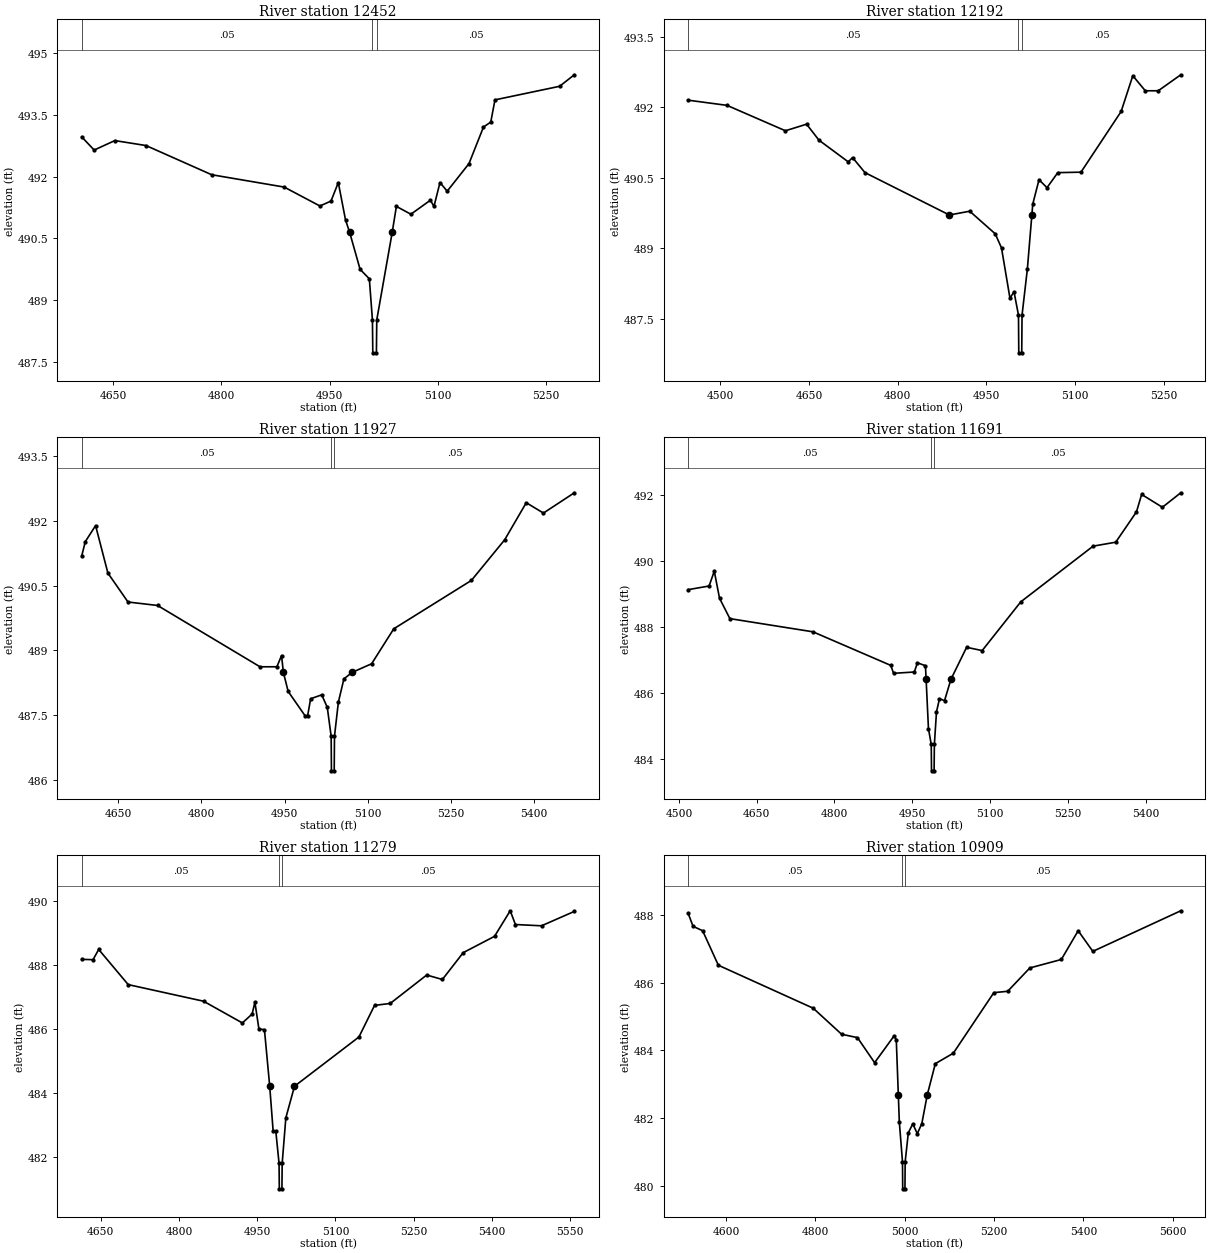
Type RM Length L Ch R = 1,12452,260,260,260
BEGIN DESCRIPTION:
XS4130A
END DESCRIPTION:
XS GIS Cut Line= 3
      2783584.08      7047970.27      2783323.68      7047756.74
      2782979.95      7047717.68
#Sta/Elev= 30
  4606.6  492.97  4623.8  492.65  4652.5  492.88  4695.6  492.76  4786.7  492.05
  4887.2  491.75  4936.7  491.29  4952.1  491.41  4962.2  491.86  4972.2  490.95
  4977.9  490.65  4992.4  489.75  5005.2  489.52  5009.5  488.52  5010.0  487.72
  5015.0  487.72  5015.5  488.52  5036.9  490.65  5042.7  491.28  5062.8  491.09
  5089.8  491.43  5094.8  491.28  5103.1  491.86  5113.1  491.65  5143.3  492.32
  5163.4  493.21  5173.5  493.33  5179.3  493.87  5268.9  494.20  5289.3  494.48
#Mann=3,-1,0
  4606.6    0.05       0  5009.5    0.03       0  5015.5    0.05       0
Bank Sta=4977.9,5036.9
Exp/Cntr=0.3,0.1

Type RM Length L Ch R = 1,12192,265,265,265
BEGIN DESCRIPTION:
XS4131A
END DESCRIPTION:
XS GIS Cut Line= 3
      2783703.93      7047858.33      2783336.70      7047524.97
      2783018.23      7047416.22
#Sta/Elev= 30
  4446.0  492.15  4511.6  492.04  4610.3  491.50  4646.1  491.64  4667.0  491.30
  4716.4  490.84  4723.8  490.93  4744.8  490.61  4887.4  489.71  4921.8  489.79
  4964.9  489.31  4975.5  489.01  4989.8  487.94  4996.6  488.08  5004.2  487.58
  5004.7  486.78  5009.7  486.78  5010.2  487.58  5019.2  488.56  5026.8  489.71
  5028.3  489.94  5038.9  490.46  5052.4  490.29  5070.6  490.61  5109.8  490.62
  5177.7  491.91  5197.4  492.67  5218.5  492.35  5240.4  492.35  5278.5  492.69
#Mann=3,-1,0
  4446.0    0.05       0  5004.2    0.03       0  5010.2    0.05       0
Bank Sta=4887.4,5026.8
Exp/Cntr=0.3,0.1

Type RM Length L Ch R = 1,11927,236,236,236
BEGIN DESCRIPTION:
XS4132A
END DESCRIPTION:
XS GIS Cut Line= 3
      2783891.39      7047465.07      2783490.35      7047392.15
      2783009.27      7047389.55
#Sta/Elev= 30
  4584.0  491.19  4590.5  491.52  4609.0  491.89  4631.2  490.79  4667.5  490.12
  4720.8  490.04  4905.6  488.62  4936.1  488.62  4944.5  488.88  4947.8  488.49
  4956.4  488.05  4986.7  487.49  4991.6  487.49  4997.0  487.88  5017.0  487.97
  5027.0  487.68  5034.0  487.01  5034.5  486.21  5039.5  486.21  5040.0  487.01
  5047.0  487.80  5057.0  488.34  5071.8  488.49  5107.0  488.69  5147.0  489.50
  5287.0  490.62  5347.0  491.56  5386.0  492.42  5417.0  492.18  5472.7  492.65
#Mann=3,-1,0
  4584.0    0.05       0  5034.0    0.03       0  5040.0    0.05       0
Bank Sta=4947.8,5071.8
Exp/Cntr=0.3,0.1

Type RM Length L Ch R = 1,11691,412,412,412
BEGIN DESCRIPTION:
XS4133A
END DESCRIPTION:
XS GIS Cut Line= 5
      2783925.28      7047147.36      2783529.41      7047126.53
      2783383.58      7047215.07      2783162.22      7047308.82
      2783019.53      7047308.82
#Sta/Elev= 30
  4517.9  489.13  4558.2  489.24  4568.2  489.69  4578.3  488.87  4598.3  488.25
  4758.5  487.85  4908.7  486.83  4914.0  486.59  4954.1  486.63  4960.0  486.91
  4975.5  486.82  4976.8  486.41  4981.3  484.91  4986.7  484.43  4987.2  483.63
  4992.2  483.63  4992.7  484.43  4996.8  485.42  5002.6  485.82  5012.3  485.76
  5024.7  486.41  5054.9  487.38  5084.9  487.28  5159.4  488.76  5298.9  490.45
  5342.5  490.57  5382.5  491.49  5392.5  492.02  5432.5  491.63  5468.0  492.07
#Mann=3,-1,0
  4517.9    0.05       0  4986.7    0.03       0  4992.7    0.05       0
Bank Sta=4976.8,5024.7
Exp/Cntr=0.3,0.1

Type RM Length L Ch R = 1,11279,370,370,370
BEGIN DESCRIPTION:
XS4134A
END DESCRIPTION:
XS GIS Cut Line= 3
      2783915.67      7047018.88      2783568.47      7046897.36
      2782992.09      7046883.47
#Sta/Elev= 30
  4613.7  488.18  4635.4  488.17  4646.2  488.49  4702.8  487.39  4847.3  486.87
  4921.7  486.19  4940.4  486.47  4945.7  486.84  4953.4  486.00  4964.0  485.98
  4974.1  484.21  4980.7  482.80  4985.8  482.80  4992.0  481.80  4992.5  481.00
  4997.5  481.00  4998.0  481.80  5005.0  483.22  5021.6  484.21  5145.1  485.75
  5175.1  486.74  5205.1  486.80  5275.1  487.69  5305.1  487.55  5345.1  488.39
  5405.1  488.90  5435.2  489.70  5445.2  489.27  5495.2  489.23  5558.1  489.68
#Mann=3,-1,0
  4613.7    0.05       0  4992.0    0.03       0  4998.0    0.05       0
Bank Sta=4974.1,5021.6
Exp/Cntr=0.3,0.1

Type RM Length L Ch R = 1,10909,382,382,382
BEGIN DESCRIPTION:
XS4135A
END DESCRIPTION:
XS GIS Cut Line= 3
      2783881.81      7046913.82      2783579.76      7046625.66
      2782899.59      7046542.38
#Sta/Elev= 30
  4515.4  488.05  4526.3  487.67  4547.7  487.54  4582.9  486.52  4795.2  485.25
  4858.8  484.48  4894.3  484.38  4932.7  483.64  4976.2  484.43  4981.2  484.32
  4985.8  482.69  4988.0  481.89  4995.1  480.71  4995.6  479.91  5000.6  479.91
  5001.1  480.71  5008.2  481.57  5018.2  481.83  5028.3  481.54  5038.4  481.84
  5050.6  482.69  5068.6  483.61  5108.9  483.92  5199.6  485.71  5230.6  485.75
  5280.2  486.44  5350.7  486.69  5388.4  487.54  5421.2  486.93  5618.1  488.13
#Mann=3,-1,0
  4515.4    0.05       0  4995.1    0.03       0  5001.1    0.05       0
Bank Sta=4985.8,5050.6
Exp/Cntr=0.3,0.1

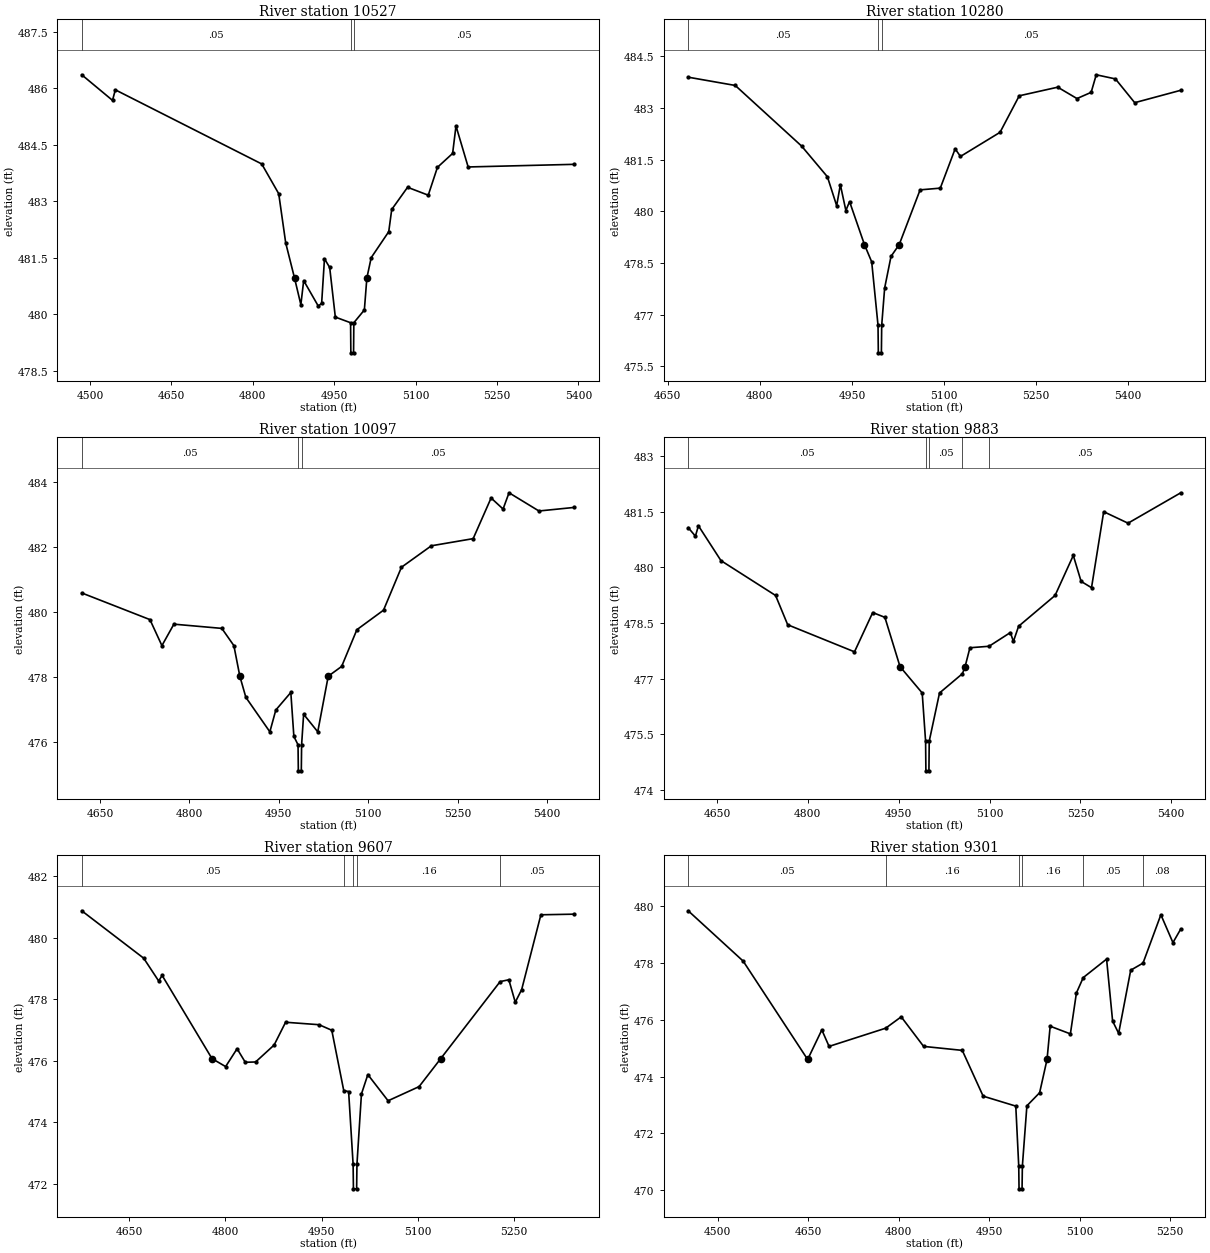
Type RM Length L Ch R = 1,10527,247,247,247
BEGIN DESCRIPTION:
XS4136A
END DESCRIPTION:
XS GIS Cut Line= 3
      2783836.69      7046802.71      2783697.81      7046337.47
      2783319.70      7046150.14
#Sta/Elev= 30
  4484.9  486.36  4541.6  485.68  4546.8  485.96  4816.5  483.99  4847.8  483.20
  4860.7  481.89  4876.9  480.96  4888.6  480.25  4893.8  480.89  4920.8  480.21
  4926.9  480.29  4932.1  481.47  4941.7  481.24  4952.1  479.92  4980.2  479.77
  4980.7  478.97  4985.7  478.97  4986.2  479.77  5005.6  480.11  5010.2  480.96
  5018.2  481.50  5050.5  482.19  5056.0  482.78  5085.2  483.37  5123.3  483.16
  5140.2  483.90  5168.2  484.27  5174.4  485.00  5196.8  483.91  5392.4  483.98
#Mann=3,-1,0
  4484.9    0.05       0  4980.2    0.03       0  4986.2    0.05       0
Bank Sta=4876.9,5010.2
Exp/Cntr=0.3,0.1

Type RM Length L Ch R = 1,10280,183,183,183
BEGIN DESCRIPTION:
XS4137A
END DESCRIPTION:
XS GIS Cut Line= 3
      2784055.47      7046469.44      2783881.84      7046208.99
      2783413.10      7046066.64
#Sta/Elev= 30
  4683.2  483.89  4759.9  483.65  4868.1  481.89  4910.1  481.00  4925.2  480.16
  4931.2  480.77  4940.2  480.02  4946.2  480.28  4970.5  479.03  4982.3  478.53
  4992.6  476.69  4993.1  475.89  4998.1  475.89  4998.6  476.69  5003.4  477.77
  5013.8  478.69  5027.1  479.03  5061.2  480.62  5094.1  480.67  5118.3  481.81
  5127.0  481.59  5191.5  482.29  5222.8  483.35  5285.5  483.60  5316.9  483.27
  5340.0  483.45  5348.3  483.96  5379.6  483.84  5411.0  483.15  5486.1  483.51
#Mann=3,-1,0
  4683.2    0.05       0  4992.6    0.03       0  4998.6    0.05       0
Bank Sta=4970.5,5027.1
Exp/Cntr=0.3,0.1

Type RM Length L Ch R = 1,10097,214,214,214
BEGIN DESCRIPTION:
XS4138A
END DESCRIPTION:
XS GIS Cut Line= 3
      2784388.78      7046129.13      2784017.26      7046087.47
      2783565.83      7046049.27
#Sta/Elev= 30
  4619.1  480.58  4733.6  479.76  4753.7  478.96  4773.8  479.62  4854.3  479.49
  4874.5  478.96  4884.5  478.02  4894.6  477.37  4934.9  476.31  4944.9  476.98
  4970.1  477.52  4975.2  476.17  4982.2  475.91  4982.7  475.11  4987.7  475.11
  4988.2  475.91  4991.6  476.85  5015.3  476.31  5032.9  478.02  5055.4  478.32
  5081.0  479.45  5125.7  480.05  5155.8  481.37  5206.0  482.03  5276.2  482.25
  5306.3  483.50  5326.4  483.16  5336.4  483.66  5386.6  483.10  5446.0  483.21
#Mann=3,-1,0
  4619.1    0.05       0  4982.2    0.03       0  4988.2    0.05       0
Bank Sta=4884.5,5032.9
Exp/Cntr=0.3,0.1

Type RM Length L Ch R = 1,9883,276,276,276
BEGIN DESCRIPTION:
XS4139A
END DESCRIPTION:
XS GIS Cut Line= 3
      2784558.91      7046011.08      2784176.98      7045983.30
      2783748.20      7045945.26
#Sta/Elev= 30
  4602.4  481.07  4614.3  480.84  4619.3  481.12  4656.5  480.18  4746.7  479.24
  4766.7  478.45  4877.0  477.72  4907.1  478.78  4927.2  478.65  4952.2  477.32
  4988.8  476.61  4994.4  475.31  4994.9  474.51  4999.9  474.51  5000.4  475.31
  5017.4  476.61  5055.2  477.13  5059.6  477.32  5067.6  477.83  5099.2  477.87
  5134.4  478.24  5139.4  478.00  5148.0  478.41  5208.2  479.24  5238.3  480.32
  5251.2  479.62  5268.4  479.45  5288.5  481.50  5328.7  481.19  5415.8  482.01
#Mann=5,-1,0
  4602.4    0.05       0  4994.4    0.03       0  5000.4    0.05       0
  5055.2    0.16       0  5099.2    0.05       0
Bank Sta=4952.2,5059.6
Exp/Cntr=0.3,0.1

Type RM Length L Ch R = 1,9607,306,306,306
BEGIN DESCRIPTION:
XS4140A
END DESCRIPTION:
XS GIS Cut Line= 3
      2784558.91      7045948.57      2784201.29      7045792.33
      2783822.79      7045781.91
#Sta/Elev= 30
  4575.6  480.87  4672.3  479.33  4695.7  478.59  4701.1  478.77  4778.9  476.07
  4800.2  475.81  4818.1  476.39  4830.9  475.95  4847.0  475.96  4875.9  476.51
  4893.8  477.25  4946.1  477.17  4965.9  476.99  4984.6  475.03  4992.2  475.00
  4999.2  472.64  4999.7  471.84  5004.7  471.84  5005.2  472.64  5012.2  474.92
  5022.2  475.55  5053.8  474.70  5102.2  475.16  5136.0  476.07  5228.7  478.57
  5242.3  478.63  5252.3  477.90  5262.3  478.31  5292.3  480.74  5344.5  480.76
#Mann=5,-1,0
  4575.6    0.05       0  4984.6    0.16       0  4999.2    0.07       0
  5005.2    0.16       0  5228.7    0.05       0
Bank Sta=4778.9,5136
Exp/Cntr=0.3,0.1

Type RM Length L Ch R = 1,9301,337,337,337
BEGIN DESCRIPTION:
XS4142A
END DESCRIPTION:
XS GIS Cut Line= 5
      2784528.13      7045822.29      2784237.31      7045692.07
      2784130.97      7045555.35      2784026.81      7045520.63
      2783811.97      7045522.80
#Sta/Elev= 30
  4450.9  479.83  4542.0  478.06  4648.9  474.60  4672.4  475.64  4684.4  475.06
  4778.2  475.70  4804.0  476.10  4841.1  475.06  4905.2  474.92  4939.8  473.31
  4993.9  472.96  4998.8  470.85  4999.3  470.05  5004.3  470.05  5004.8  470.85
  5012.3  472.97  5033.4  473.43  5045.7  474.60  5050.9  475.77  5084.4  475.50
  5094.4  476.94  5105.7  477.48  5144.4  478.13  5154.4  475.95  5164.4  475.52
  5184.4  477.74  5204.8  477.99  5234.4  479.69  5254.4  478.71  5267.4  479.19
#Mann=6,-1,0
  4450.9    0.05       0  4778.2    0.16       0  4998.8    0.07       0
  5004.8    0.16       0  5105.7    0.05       0  5204.8    0.08       0
Bank Sta=4648.9,5045.7
Exp/Cntr=0.3,0.1

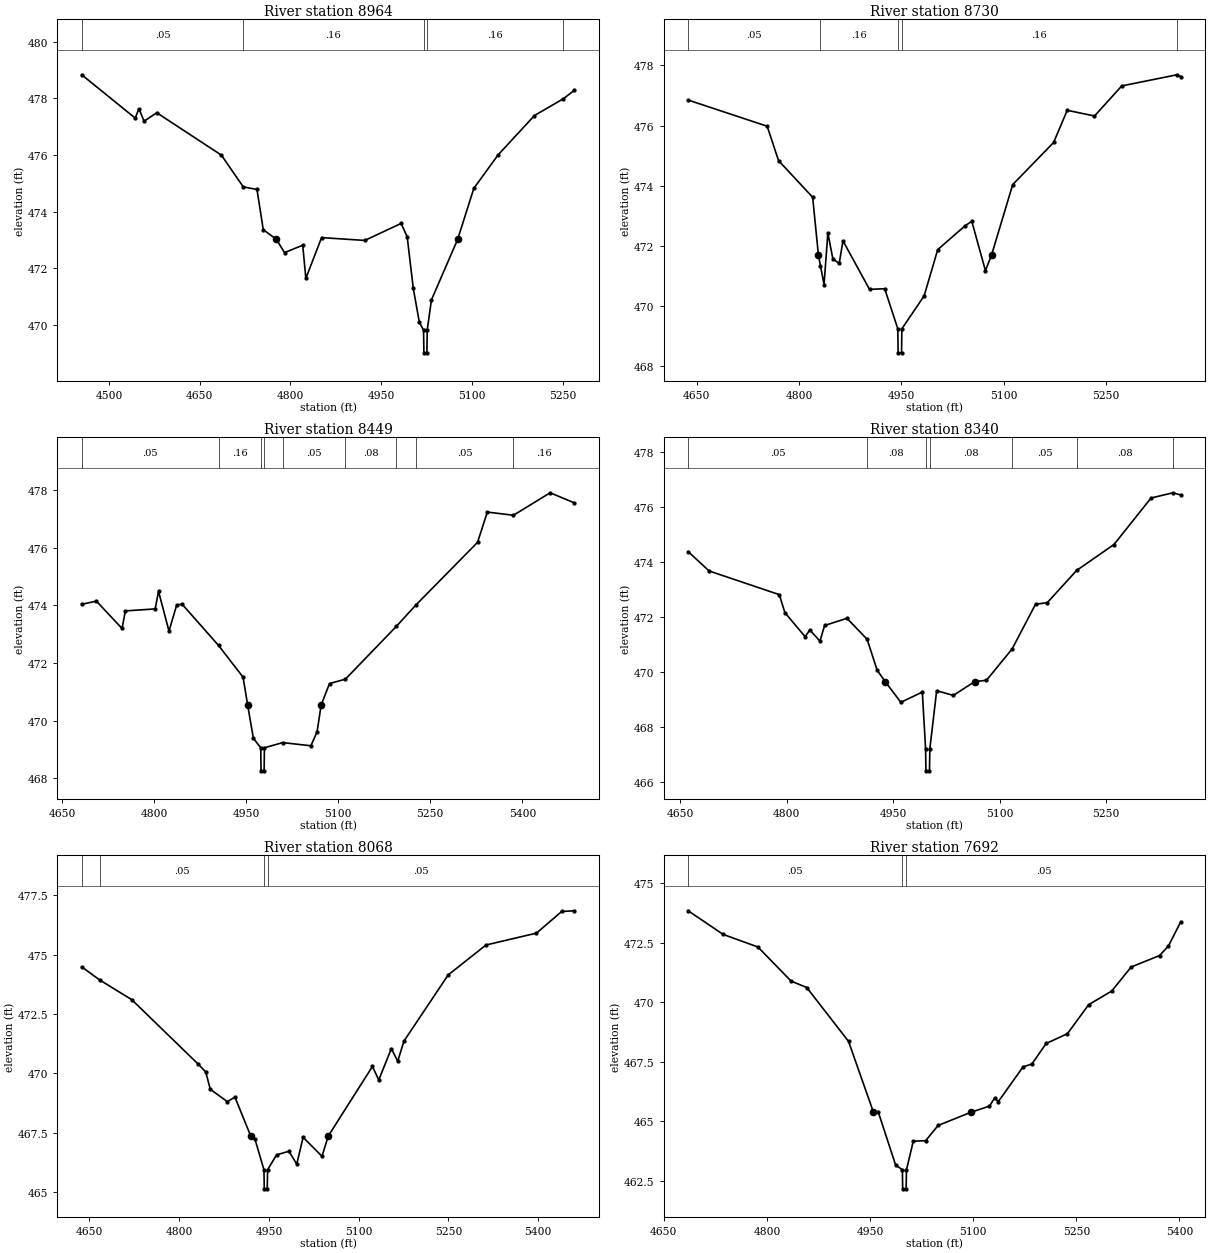
Type RM Length L Ch R = 1,8964,234,234,234
BEGIN DESCRIPTION:
XS4141A
END DESCRIPTION:
XS GIS Cut Line= 4
      2784651.81      7045731.13      2784476.02      7045483.73
      2784321.94      7045451.18      2783969.15      7045431.70
#Sta/Elev= 30
  4455.1  478.83  4543.5  477.30  4549.6  477.63  4558.2  477.19  4579.1  477.49
  4686.1  475.99  4722.1  474.87  4744.8  474.78  4755.2  473.36  4776.8  473.02
  4790.3  472.55  4820.4  472.81  4825.6  471.64  4851.6  473.08  4923.0  472.98
  4983.1  473.58  4993.1  473.11  5003.1  471.30  5013.2  470.09  5020.2  469.81
  5020.7  469.01  5025.7  469.01  5026.2  469.81  5033.2  470.88  5076.6  473.02
  5103.3  474.82  5143.4  476.00  5203.5  477.39  5251.0  477.98  5269.4  478.28
#Mann=5,-1,0
  4455.1    0.05       0  4722.1    0.16       0  5020.2    0.07       0
  5026.2    0.16       0  5251.0    0.05       0
Bank Sta=4776.8,5076.6
Exp/Cntr=0.3,0.1

Type RM Length L Ch R = 1,8730,281,281,281
BEGIN DESCRIPTION:
XS4143A
END DESCRIPTION:
XS GIS Cut Line= 3
      2784714.27      7045442.05      2784412.22      7045288.42
      2784028.41      7045285.83
#Sta/Elev= 30
  4637.4  476.85  4753.3  475.98  4769.9  474.84  4820.0  473.62  4828.4  471.71
  4831.4  471.35  4836.7  470.72  4842.3  472.43  4849.7  471.57  4858.9  471.42
  4864.5  472.17  4903.4  470.56  4925.7  470.58  4944.9  469.25  4945.4  468.45
  4950.4  468.45  4950.9  469.25  4983.5  470.34  5003.5  471.88  5043.5  472.67
  5053.5  472.82  5073.5  471.18  5082.6  471.71  5113.5  474.04  5173.5  475.44
  5193.5  476.51  5233.5  476.32  5273.5  477.32  5354.5  477.69  5360.1  477.63
#Mann=5,-1,0
  4637.4    0.05       0  4831.4    0.16       0  4944.9    0.07       0
  4950.9    0.16       0  5354.5    0.05       0
Bank Sta=4828.4,5082.6
Exp/Cntr=0.3,0.1

Type RM Length L Ch R = 1,8449,109,109,109
BEGIN DESCRIPTION:
XS4144A
END DESCRIPTION:
XS GIS Cut Line= 5
      2784787.19      7044934.27      2784524.20      7045038.42
      2784388.79      7045061.86      2784266.39      7045129.57
      2784055.49      7045249.34
#Sta/Elev= 30
  4682.0  474.04  4705.9  474.15  4747.7  473.20  4753.1  473.81  4801.7  473.88
  4807.1  474.49  4824.2  473.11  4836.8  474.02  4845.7  474.04  4905.0  472.61
  4944.9  471.51  4952.4  470.54  4961.7  469.39  4973.7  469.06  4974.2  468.26
  4979.2  468.26  4979.7  469.06  5009.5  469.24  5055.4  469.13  5065.5  469.61
  5072.1  470.54  5085.8  471.29  5111.6  471.44  5194.5  473.27  5226.3  474.01
  5327.0  476.19  5342.9  477.24  5385.5  477.13  5445.3  477.91  5484.7  477.56
#Mann=9,-1,0
  4682.0    0.05       0  4905.0    0.16       0  4973.7    0.07       0
  4979.7    0.16       0  5009.5    0.05       0  5111.6    0.08       0
  5194.5    0.16       0  5226.3    0.05       0  5385.5    0.16       0
Bank Sta=4952.4,5072.1
Exp/Cntr=0.3,0.1

Type RM Length L Ch R = 1,8340,272,272,272
BEGIN DESCRIPTION:
XS4145A
END DESCRIPTION:
XS GIS Cut Line= 5
      2784782.00      7044780.62      2784610.14      7044923.84
      2784461.70      7044944.67      2784349.72      7044981.13
      2784172.76      7045080.02
#Sta/Elev= 30
  4661.0  474.38  4690.5  473.68  4789.4  472.82  4797.2  472.17  4825.8  471.29
  4832.3  471.54  4846.7  471.13  4853.2  471.70  4884.7  471.96  4913.1  471.20
  4927.2  470.08  4938.6  469.66  4960.6  468.91  4990.9  469.28  4995.5  467.22
  4996.0  466.42  5001.0  466.42  5001.5  467.22  5011.1  469.33  5034.6  469.16
  5064.6  469.66  5081.3  469.71  5117.5  470.85  5150.4  472.47  5167.0  472.53
  5208.4  473.70  5260.9  474.64  5313.2  476.33  5344.1  476.52  5355.1  476.44
#Mann=7,-1,0
  4661.0    0.05       0  4913.1    0.08       0  4995.5    0.07       0
  5001.5    0.08       0  5117.5    0.05       0  5208.4    0.08       0
  5344.1    0.05       0
Bank Sta=4938.6,5064.6
Exp/Cntr=0.3,0.1

Type RM Length L Ch R = 1,8068,376,376,376
BEGIN DESCRIPTION:
UNT 186 in LFCCL Watershed 16.0
END DESCRIPTION:
XS GIS Cut Line= 3
      2784813.31      7044759.79      2784475.00      7044675.00
      2784025.01      7044825.00
#Sta/Elev= 30
  4637.2  474.48  4667.1  473.93  4720.8  473.10  4831.3  470.40  4844.4  470.06
  4852.0  469.33  4880.4  468.81  4893.2  469.00  4919.6  467.36  4926.8  467.22
  4941.7  465.94  4942.2  465.14  4947.2  465.14  4947.7  465.94  4962.8  466.57
  4983.4  466.72  4996.5  466.18  5007.1  467.31  5038.7  466.51  5049.1  467.36
  5123.0  470.29  5133.5  469.72  5154.6  471.04  5165.2  470.51  5175.7  471.36
  5249.5  474.14  5312.7  475.40  5397.1  475.90  5439.2  476.81  5460.3  476.84
#Mann=4,-1,0
  4637.2    0.08       0  4667.1    0.05       0  4941.7    0.03       0
  4947.7    0.05       0
Bank Sta=4919.6,5049.1
Exp/Cntr=0.3,0.1

Type RM Length L Ch R = 1,7692,261,261,261
BEGIN DESCRIPTION:
UNT 186 in LFCCL Watershed 15.0
END DESCRIPTION:
XS GIS Cut Line= 3
      2784975.05      7044425.01      2784675.00      7044375.00
      2784275.00      7044475.00
#Sta/Elev= 30
  4685.4  473.84  4736.1  472.85  4786.8  472.32  4835.0  470.89  4857.8  470.62
  4918.6  468.36  4954.8  465.39  4961.7  465.41  4987.1  463.17  4996.9  462.97
  4997.4  462.17  5002.4  462.17  5002.9  462.97  5012.8  464.17  5030.8  464.19
  5048.9  464.83  5097.2  465.39  5123.6  465.64  5131.3  465.99  5136.5  465.83
  5172.5  467.29  5185.4  467.41  5206.0  468.27  5237.0  468.68  5267.9  469.90
  5301.4  470.47  5329.7  471.48  5371.0  471.96  5383.9  472.36  5401.9  473.38
#Mann=3,-1,0
  4685.4    0.05       0  4996.9    0.03       0  5002.9    0.05       0
Bank Sta=4954.8,5097.2
Exp/Cntr=0.3,0.1

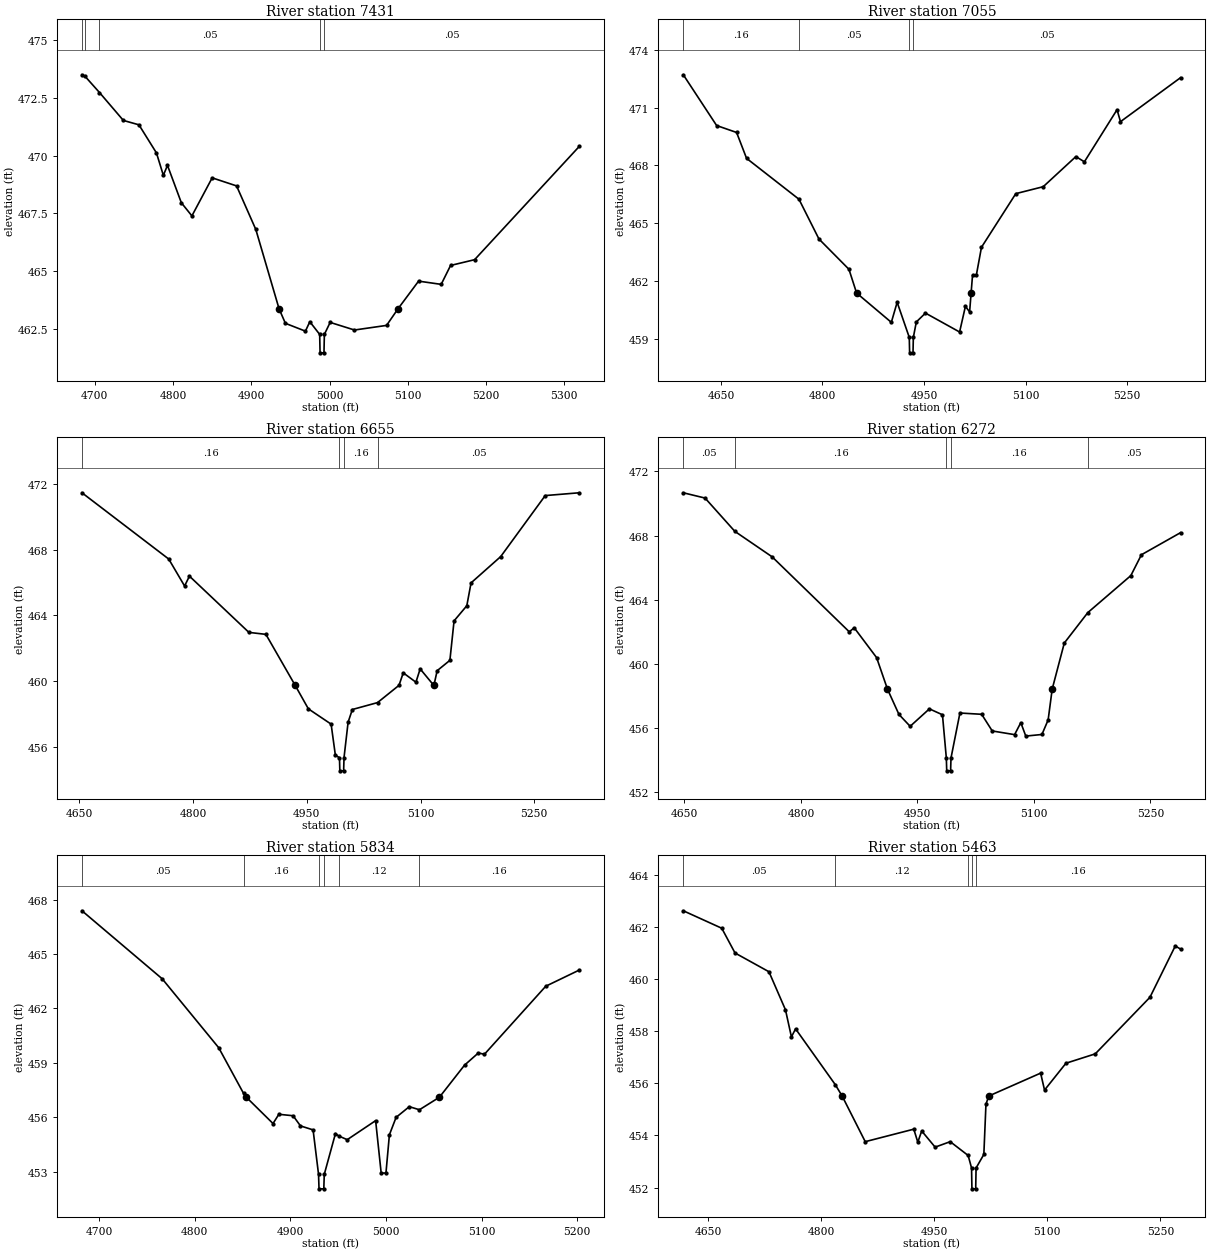
Type RM Length L Ch R = 1,7431,376,376,376
BEGIN DESCRIPTION:
UNT 186 in LFCCL Watershed 14.0
END DESCRIPTION:
XS GIS Cut Line= 3
      2785075.04      7044275.01      2784766.39      7044168.63
      2784464.29      7044103.52
#Sta/Elev= 30
  4683.6  473.51  4687.6  473.44  4706.0  472.74  4736.5  471.53  4756.4  471.34
  4778.8  470.12  4787.6  469.15  4792.9  469.58  4810.6  467.96  4824.1  467.39
  4850.0  469.04  4881.2  468.69  4905.8  466.80  4935.5  463.36  4943.6  462.73
  4969.2  462.39  4974.8  462.80  4987.4  462.25  4987.9  461.45  4992.9  461.45
  4993.4  462.25  5000.8  462.77  5031.9  462.44  5072.9  462.64  5087.5  463.36
  5113.8  464.56  5142.7  464.42  5154.7  465.24  5185.4  465.49  5319.1  470.40
#Mann=5,-1,0
  4683.6    0.05       0  4687.6    0.16       0  4706.0    0.05       0
  4987.4    0.03       0  4993.4    0.05       0
Bank Sta=4935.5,5087.5
Exp/Cntr=0.3,0.1

Type RM Length L Ch R = 1,7055,400,400,400
BEGIN DESCRIPTION:
UNT 186 in LFCCL Watershed 13.0
END DESCRIPTION:
XS GIS Cut Line= 3
      2785175.02      7044075.01      2784825.00      7043825.00
      2784524.97      7043875.00
#Sta/Elev= 30
  4594.5  472.70  4643.7  470.07  4673.2  469.71  4687.9  468.37  4765.3  466.25
  4794.8  464.19  4839.1  462.62  4850.4  461.39  4901.7  459.87  4910.3  460.91
  4928.2  459.09  4928.7  458.29  4933.7  458.29  4934.2  459.09  4938.6  459.89
  4952.1  460.35  5002.5  459.37  5011.1  460.70  5017.3  460.41  5019.5  461.39
  5021.6  462.31  5027.2  462.31  5034.8  463.76  5085.5  466.54  5126.0  466.90
  5174.2  468.46  5186.8  468.19  5235.0  470.89  5240.1  470.27  5328.8  472.55
#Mann=4,-1,0
  4594.5    0.16       0  4765.3    0.05       0  4928.2    0.03       0
  4934.2    0.05       0
Bank Sta=4850.4,5019.5
Exp/Cntr=0.3,0.1

Type RM Length L Ch R = 1,6655,383,383,383
BEGIN DESCRIPTION:
UNT 186 in LFCCL Watershed 12.0
END DESCRIPTION:
XS GIS Cut Line= 3
      2785274.99      7043874.99      2785075.00      7043625.00
      2784774.96      7043474.98
#Sta/Elev= 30
  4653.6  471.46  4768.0  467.43  4788.9  465.79  4795.3  466.39  4873.7  462.97
  4896.1  462.85  4934.8  459.74  4952.1  458.32  4982.1  457.39  4987.7  455.50
  4993.1  455.35  4993.6  454.55  4998.6  454.55  4999.1  455.35  5004.5  457.51
  5010.1  458.28  5043.3  458.70  5071.6  459.75  5077.2  460.51  5093.9  459.94
  5099.5  460.75  5117.6  459.74  5121.9  460.64  5138.7  461.27  5144.2  463.67
  5161.0  464.59  5166.6  465.98  5205.7  467.58  5264.4  471.29  5309.2  471.46
#Mann=4,-1,0
  4653.6    0.16       0  4993.1    0.07       0  4999.1    0.16       0
  5043.3    0.05       0
Bank Sta=4934.8,5117.6
Exp/Cntr=0.3,0.1

Type RM Length L Ch R = 1,6272,438,438,438
BEGIN DESCRIPTION:
UNT 186 in LFCCL Watershed 11.0
END DESCRIPTION:
XS GIS Cut Line= 3
      2785524.98      7043574.99      2785275.00      7043375.00
      2785024.99      7043174.99
#Sta/Elev= 30
  4648.5  470.67  4676.5  470.34  4714.9  468.26  4762.9  466.67  4862.2  461.99
  4868.6  462.24  4897.4  460.38  4911.4  458.41  4926.2  456.83  4940.6  456.09
  4965.4  457.18  4982.2  456.81  4987.2  454.11  4987.7  453.31  4992.7  453.31
  4993.2  454.11  5004.7  456.92  5032.7  456.84  5046.3  455.80  5075.1  455.57
  5083.1  456.32  5089.5  455.48  5110.3  455.58  5118.3  456.49  5123.5  458.41
  5139.1  461.29  5169.4  463.19  5224.8  465.50  5238.4  466.80  5288.8  468.18
#Mann=5,-1,0
  4648.5    0.05       0  4714.9    0.16       0  4987.2    0.07       0
  4993.2    0.16       0  5169.4    0.05       0
Bank Sta=4911.4,5123.5
Exp/Cntr=0.3,0.1

Type RM Length L Ch R = 1,5834,371,371,371
BEGIN DESCRIPTION:
XS4146A
END DESCRIPTION:
XS GIS Cut Line= 3
      2785685.67      7043382.18      2785503.37      7043121.75
      2785344.54      7042996.77
#Sta/Elev= 30
  4682.0  467.38  4765.9  463.63  4825.0  459.83  4851.0  457.31  4853.9  457.10
  4881.8  455.65  4887.9  456.16  4902.8  456.08  4910.5  455.52  4923.7  455.30
  4929.4  452.85  4929.9  452.05  4934.9  452.05  4935.4  452.85  4947.1  455.10
  4950.3  454.97  4959.4  454.76  4989.1  455.81  4994.9  452.92  4999.9  452.92
  5003.5  455.03  5010.5  455.99  5024.3  456.58  5034.9  456.41  5055.8  457.10
  5082.1  458.87  5096.5  459.54  5102.9  459.47  5167.0  463.22  5202.0  464.11
#Mann=6,-1,0
  4682.0    0.05       0  4851.0    0.16       0  4929.4    0.07       0
  4935.4    0.16       0  4950.3    0.12       0  5034.9    0.16       0
Bank Sta=4853.9,5055.8
Exp/Cntr=0.3,0.1

Type RM Length L Ch R = 1,5463,271,271,271
BEGIN DESCRIPTION:
XS4148A
END DESCRIPTION:
XS GIS Cut Line= 4
      2785860.15      7043288.45      2785735.14      7043012.38
      2785643.99      7042991.55      2785391.36      7042918.62
#Sta/Elev= 30
  4617.2  462.62  4668.2  461.95  4685.8  461.00  4730.8  460.28  4752.7  458.82
  4760.6  457.78  4766.1  458.09  4818.7  455.95  4827.9  455.51  4858.5  453.76
  4922.9  454.24  4928.2  453.74  4933.4  454.17  4951.2  453.55  4971.2  453.76
  4995.0  453.23  4999.5  452.75  5000.0  451.95  5005.0  451.95  5005.5  452.75
  5015.8  453.27  5018.6  455.19  5022.2  455.51  5091.1  456.39  5096.3  455.74
  5124.7  456.77  5163.6  457.13  5236.1  459.30  5269.7  461.27  5276.7  461.15
#Mann=5,-1,0
  4617.2    0.05       0  4818.7    0.12       0  4995.0    0.16       0
  4999.5    0.07       0  5005.5    0.16       0
Bank Sta=4827.9,5022.2
Exp/Cntr=0.3,0.1