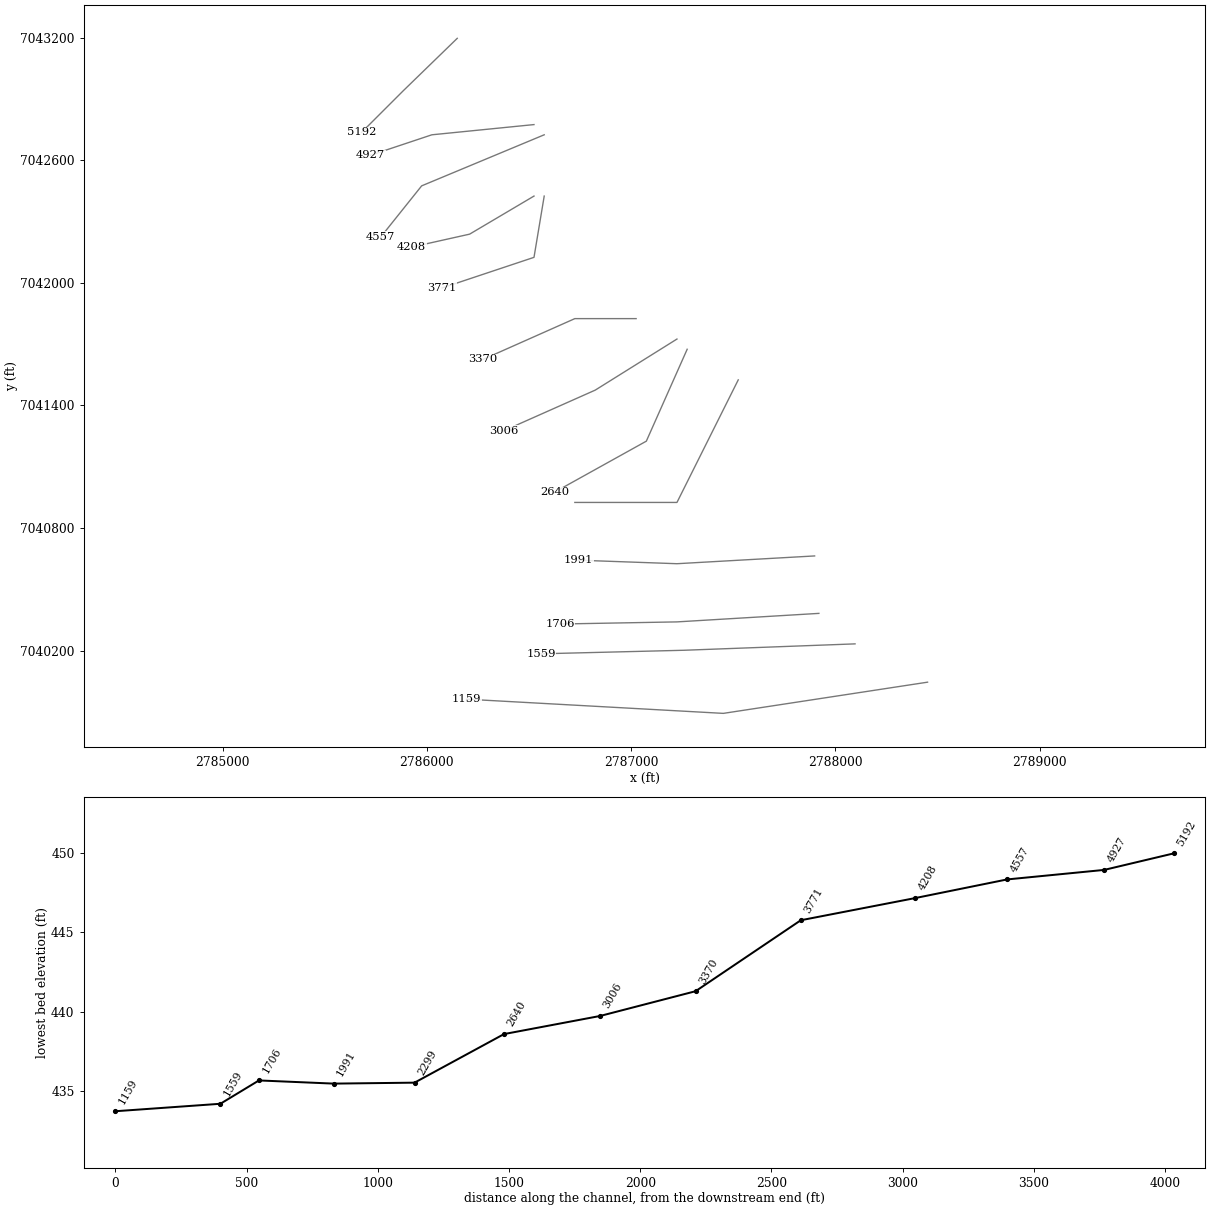
HEC-RAS study UNT 186 in LFCCL Watershed.prj: UNT 186 in LFCCL Watershed Base Level Engineering

--- UNT 186 in LFCCL Watershed.g01 (geometry) --- (continued)

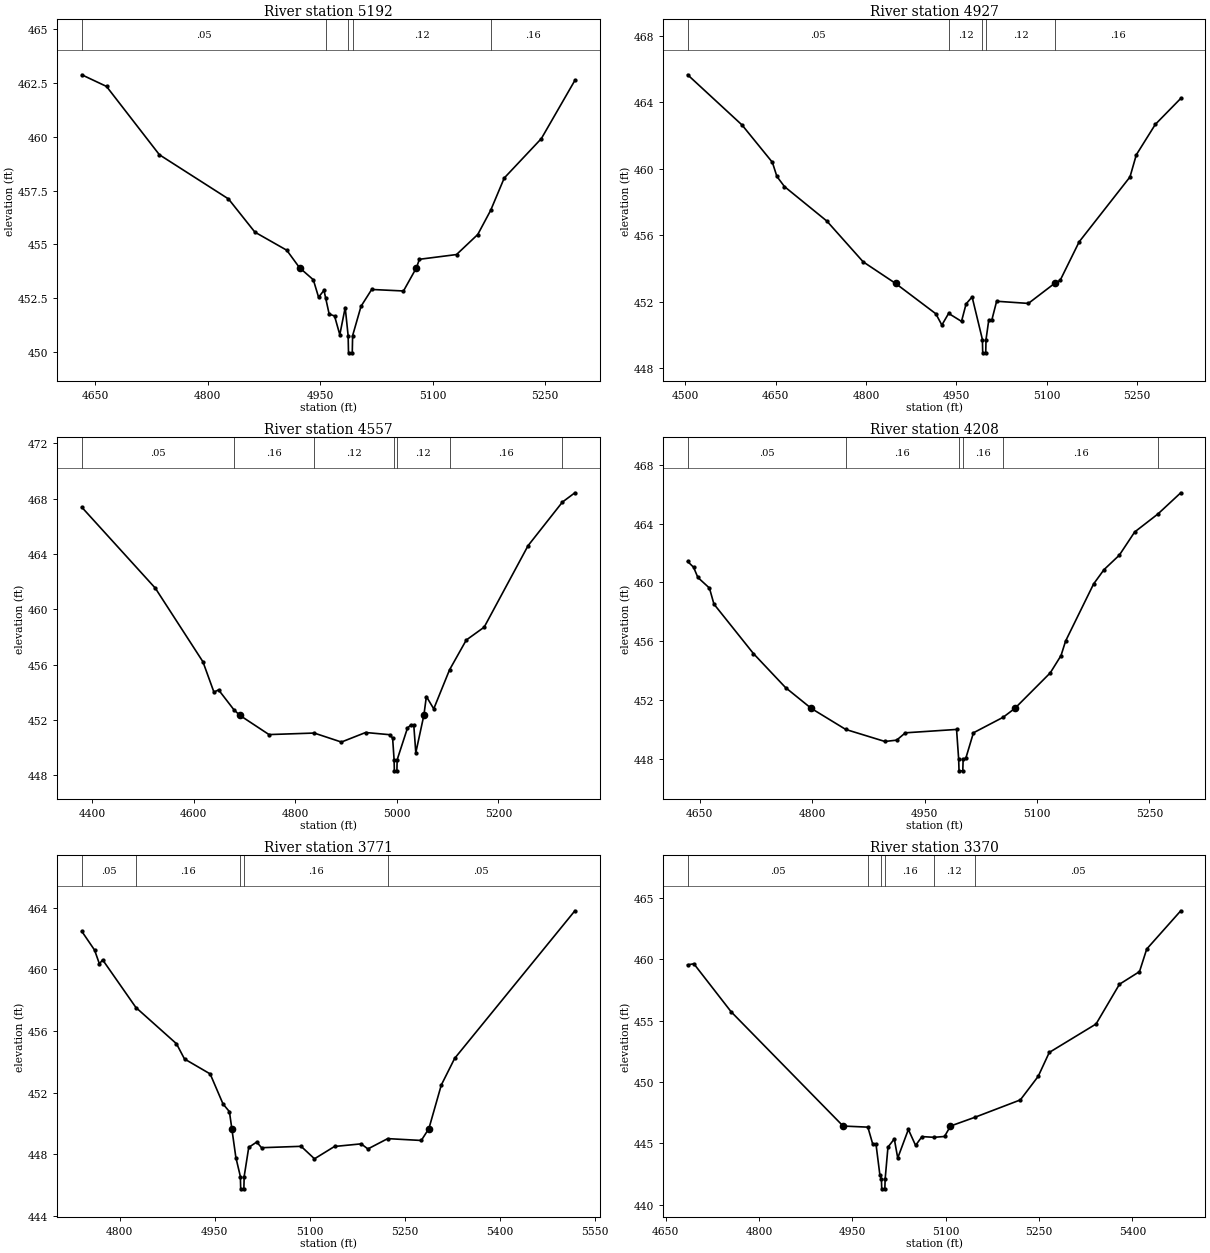
Type RM Length L Ch R = 1,5192,265,265,265
BEGIN DESCRIPTION:
XS4147A
END DESCRIPTION:
XS GIS Cut Line= 3
      2786149.21      7043197.28      2785885.33      7042941.07
      2785680.48      7042736.36
#Sta/Elev= 30
  4632.2  462.87  4665.2  462.33  4735.7  459.16  4827.8  457.11  4863.0  455.57
  4905.5  454.73  4922.5  453.92  4940.9  453.36  4947.9  452.55  4955.1  452.87
  4957.3  452.52  4962.0  451.77  4969.2  451.68  4976.2  450.81  4983.4  452.07
  4987.3  450.77  4987.8  449.97  4992.8  449.97  4993.3  450.77  5004.5  452.13
  5018.7  452.91  5061.1  452.84  5078.4  453.92  5082.3  454.31  5131.8  454.53
  5160.1  455.46  5177.3  456.58  5195.4  458.08  5244.9  459.91  5289.6  462.61
#Mann=5,-1,0
  4632.2    0.05       0  4957.3    0.12       0  4987.3    0.07       0
  4993.3    0.12       0  5177.3    0.16       0
Bank Sta=4922.5,5078.4
Exp/Cntr=0.3,0.1

Type RM Length L Ch R = 1,4927,370,370,370
BEGIN DESCRIPTION:
UNT 186 in LFCCL Watershed 10.0
END DESCRIPTION:
XS GIS Cut Line= 3
      2786524.98      7042775.00      2786025.00      7042725.00
      2785725.00      7042625.00
#Sta/Elev= 30
  4503.7  465.64  4594.1  462.62  4644.4  460.38  4651.9  459.53  4664.5  458.92
  4734.8  456.85  4795.1  454.40  4849.0  453.10  4915.7  451.28  4925.8  450.60
  4937.0  451.30  4958.4  450.82  4966.0  451.87  4976.0  452.29  4993.1  449.73
  4993.6  448.93  4998.6  448.93  4999.1  449.73  5003.7  450.91  5008.8  450.91
  5016.7  452.03  5069.4  451.90  5112.8  453.10  5114.2  453.13  5122.1  453.28
  5153.7  455.60  5238.1  459.50  5248.6  460.83  5280.2  462.66  5322.4  464.22
#Mann=5,-1,0
  4503.7    0.05       0  4937.0    0.12       0  4993.1    0.07       0
  4999.1    0.12       0  5114.2    0.16       0
Bank Sta=4849,5112.8
Exp/Cntr=0.3,0.1

Type RM Length L Ch R = 1,4557,349,349,349
BEGIN DESCRIPTION:
UNT 186 in LFCCL Watershed 9.0
END DESCRIPTION:
XS GIS Cut Line= 3
      2786575.03      7042725.01      2785975.00      7042475.00
      2785774.99      7042224.99
#Sta/Elev= 30
  4380.1  467.38  4524.8  461.53  4618.5  456.21  4640.1  454.02  4649.3  454.18
  4679.1  452.76  4690.7  452.35  4748.5  450.95  4837.4  451.06  4890.9  450.41
  4938.6  451.10  4986.3  450.94  4991.7  450.69  4994.6  449.13  4995.1  448.33
  5000.1  448.33  5000.6  449.13  5020.9  451.42  5027.4  451.64  5033.3  451.64
  5037.3  449.64  5053.2  452.35  5058.1  453.70  5072.6  452.81  5103.7  455.63
  5136.6  457.78  5171.8  458.71  5258.2  464.60  5325.8  467.75  5350.3  468.42
#Mann=7,-1,0
  4380.1    0.05       0  4679.1    0.16       0  4837.4    0.12       0
  4994.6    0.07       0  5000.6    0.12       0  5103.7    0.16       0
  5325.8    0.05       0
Bank Sta=4690.7,5053.2
Exp/Cntr=0.3,0.1

Type RM Length L Ch R = 1,4208,437,437,437
BEGIN DESCRIPTION:
UNT 186 in LFCCL Watershed 8.0
END DESCRIPTION:
XS GIS Cut Line= 3
      2786525.03      7042425.02      2786209.85      7042238.57
      2785924.96      7042174.99
#Sta/Elev= 30
  4633.8  461.42  4641.7  461.03  4647.5  460.33  4662.9  459.61  4668.9  458.52
  4721.6  455.15  4764.5  452.83  4798.9  451.41  4844.8  449.98  4897.1  449.16
  4912.7  449.25  4924.4  449.75  4992.7  449.98  4995.5  447.96  4996.0  447.16
  5001.0  447.16  5001.5  447.96  5005.0  448.01  5015.2  449.75  5054.9  450.81
  5070.4  451.41  5117.7  453.83  5132.1  455.01  5138.2  456.00  5175.6  459.89
  5189.4  460.86  5209.9  461.85  5230.4  463.43  5261.3  464.65  5291.9  466.10
#Mann=6,-1,0
  4633.8    0.05       0  4844.8    0.16       0  4995.5    0.07       0
  5001.5    0.16       0  5054.9    0.16       0  5261.3    0.05       0
Bank Sta=4798.9,5070.4
Exp/Cntr=0.3,0.1

Type RM Length L Ch R = 1,3771,401,401,401
BEGIN DESCRIPTION:
UNT 186 in LFCCL Watershed 7.0
END DESCRIPTION:
XS GIS Cut Line= 3
      2786575.00      7042424.97      2786525.00      7042125.00
      2786074.96      7041974.99
#Sta/Elev= 30
  4740.0  462.48  4760.2  461.26  4767.9  460.36  4772.9  460.63  4825.5  457.53
  4889.5  455.18  4902.2  454.19  4942.7  453.22  4963.0  451.27  4973.1  450.77
  4976.9  449.67  4983.3  447.79  4990.4  446.56  4990.9  445.76  4995.9  445.76
  4996.4  446.56  5003.6  448.45  5016.2  448.80  5023.8  448.43  5086.3  448.52
  5107.4  447.71  5139.0  448.51  5181.1  448.68  5191.7  448.35  5223.0  449.02
  5276.0  448.90  5288.0  449.67  5307.6  452.50  5328.7  454.23  5518.5  463.81
#Mann=5,-1,0
  4740.0    0.05       0  4825.5    0.16       0  4990.4    0.07       0
  4996.4    0.16       0  5223.0    0.05       0
Bank Sta=4976.9,5288
Exp/Cntr=0.3,0.1

Type RM Length L Ch R = 1,3370,364,364,364
BEGIN DESCRIPTION:
UNT 186 in LFCCL Watershed 6.0
END DESCRIPTION:
XS GIS Cut Line= 3
      2787024.99      7041825.00      2786725.00      7041825.00
      2786275.03      7041625.01
#Sta/Elev= 30
  4685.4  459.55  4695.4  459.64  4755.4  455.72  4935.2  446.41  4975.0  446.32
  4982.9  444.93  4988.1  444.93  4994.3  442.43  4996.8  442.09  4997.3  441.29
  5002.3  441.29  5002.8  442.09  5007.3  444.69  5017.5  445.36  5023.0  443.80
  5040.1  446.13  5051.7  444.83  5062.0  445.55  5081.4  445.49  5098.2  445.56
  5107.8  446.41  5146.8  447.12  5220.0  448.54  5248.7  450.46  5266.5  452.41
  5341.7  454.73  5379.3  457.97  5411.5  459.00  5423.1  460.84  5477.8  463.96
#Mann=6,-1,0
  4685.4    0.05       0  4975.0    0.16       0  4996.8    0.07       0
  5002.8    0.16       0  5081.4    0.12       0  5146.8    0.05       0
Bank Sta=4935.2,5107.8
Exp/Cntr=0.3,0.1

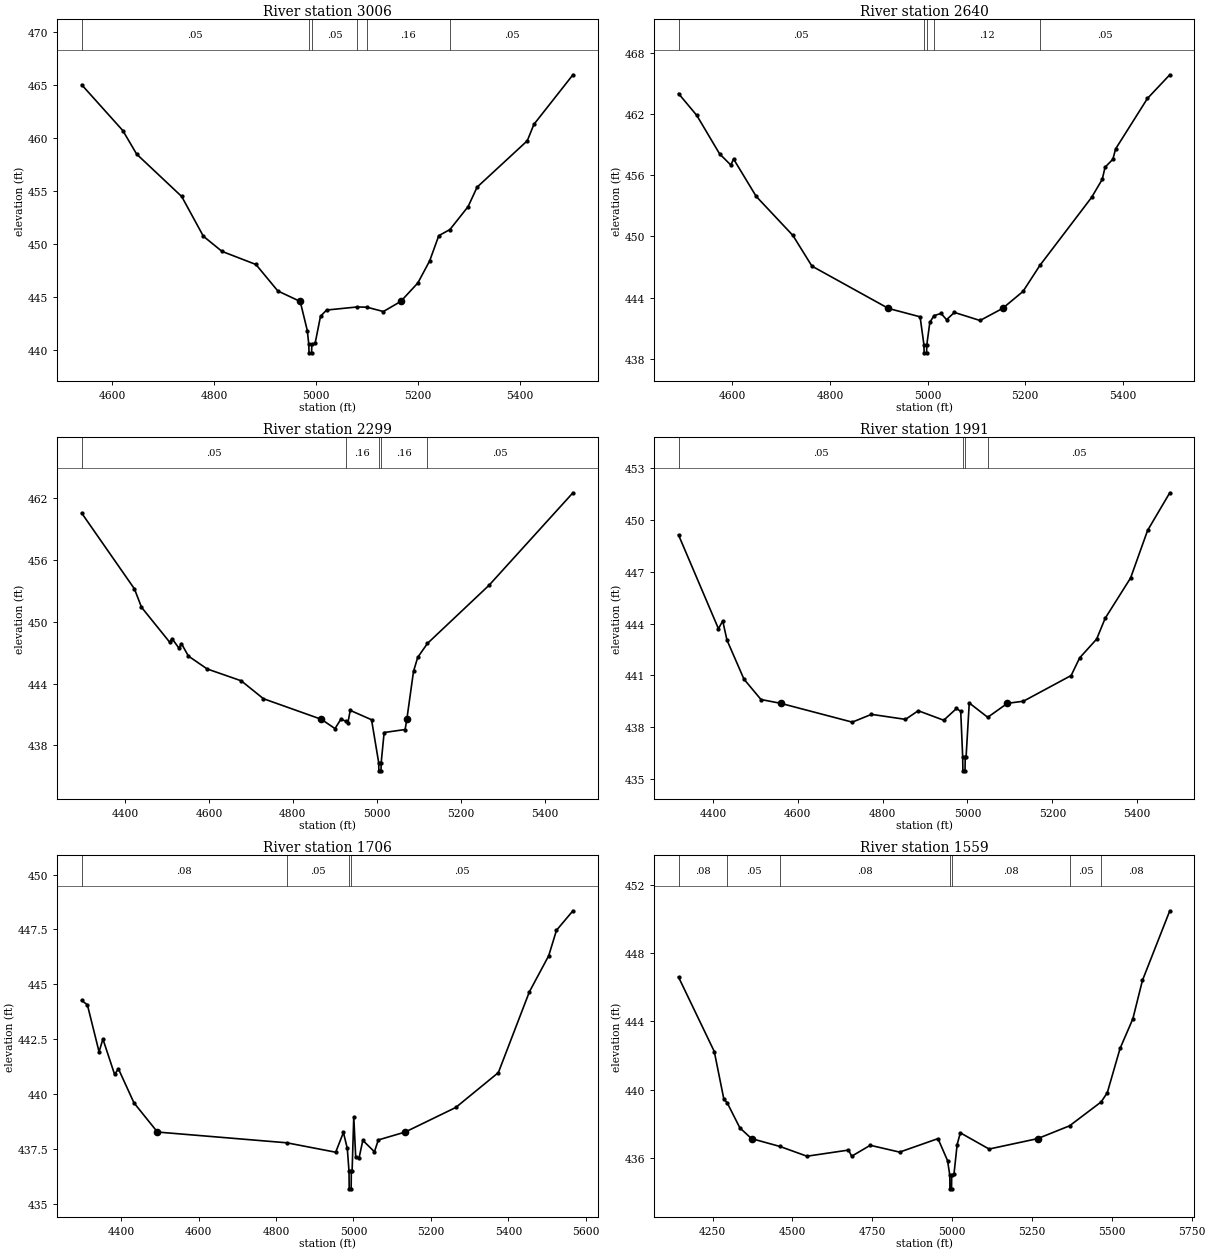
Type RM Length L Ch R = 1,3006,366,366,366
BEGIN DESCRIPTION:
UNT 186 in LFCCL Watershed 5.0
END DESCRIPTION:
XS GIS Cut Line= 3
      2787224.98      7041724.99      2786825.00      7041475.00
      2786375.02      7041275.01
#Sta/Elev= 30
  4540.1  465.04  4620.9  460.71  4648.0  458.49  4736.4  454.49  4778.9  450.74
  4815.4  449.31  4882.1  448.07  4925.1  445.57  4969.0  444.58  4982.9  441.83
  4985.8  440.53  4986.3  439.73  4991.3  439.73  4991.8  440.53  4998.2  440.62
  5008.8  443.18  5020.7  443.77  5080.7  444.06  5099.8  444.04  5132.2  443.63
  5166.2  444.58  5199.9  446.33  5223.1  448.42  5240.9  450.79  5262.8  451.37
  5298.4  453.53  5316.1  455.37  5414.6  459.75  5427.6  461.30  5504.2  465.98
#Mann=6,-1,0
  4540.1    0.05       0  4985.8    0.07       0  4991.8    0.05       0
  5080.7    0.12       0  5099.8    0.16       0  5262.8    0.05       0
Bank Sta=4969,5166.2
Exp/Cntr=0.3,0.1

Type RM Length L Ch R = 1,2640,341,341,341
BEGIN DESCRIPTION:
UNT 186 in LFCCL Watershed 4.0
END DESCRIPTION:
XS GIS Cut Line= 3
      2787274.99      7041674.97      2787075.00      7041225.00
      2786624.99      7040975.00
#Sta/Elev= 30
  4489.5  464.00  4527.1  461.85  4573.6  458.10  4596.8  456.99  4602.3  457.59
  4648.8  453.92  4724.1  450.09  4763.0  447.09  4920.0  442.94  4984.8  442.12
  4992.6  439.39  4993.1  438.59  4998.1  438.59  4998.6  439.39  5004.8  441.59
  5013.5  442.24  5027.7  442.45  5039.1  441.84  5055.1  442.55  5107.7  441.76
  5153.8  442.94  5195.8  444.61  5230.4  447.16  5336.5  453.83  5358.3  455.60
  5364.0  456.78  5380.0  457.56  5385.7  458.58  5450.9  463.52  5496.7  465.84
#Mann=5,-1,0
  4489.5    0.05       0  4992.6    0.03       0  4998.6    0.05       0
  5013.5    0.12       0  5230.4    0.05       0
Bank Sta=4920,5153.8
Exp/Cntr=0.3,0.1

Type RM Length L Ch R = 1,2299,308,308,308
BEGIN DESCRIPTION:
UNT 186 in LFCCL Watershed 3.0
END DESCRIPTION:
XS GIS Cut Line= 3
      2787525.02      7041525.04      2787225.00      7040925.00
      2786724.96      7040925.00
#Sta/Elev= 30
  4296.7  460.55  4422.5  453.19  4439.3  451.41  4506.4  448.02  4512.0  448.37
  4528.7  447.43  4534.3  447.89  4551.1  446.67  4595.8  445.42  4676.9  444.27
  4730.0  442.53  4868.1  440.53  4900.5  439.63  4914.5  440.54  4925.8  440.36
  4931.2  440.19  4936.8  441.40  4987.6  440.49  5004.6  436.33  5005.1  435.53
  5010.1  435.53  5010.6  436.33  5017.6  439.25  5067.6  439.54  5071.7  440.53
  5087.6  445.18  5097.6  446.54  5120.9  447.90  5267.6  453.54  5467.6  462.52
#Mann=5,-1,0
  4296.7    0.05       0  4925.8    0.16       0  5004.6    0.07       0
  5010.6    0.16       0  5120.9    0.05       0
Bank Sta=4868.1,5071.7
Exp/Cntr=0.3,0.1

Type RM Length L Ch R = 1,1991,285,285,285
BEGIN DESCRIPTION:
UNT 186 in LFCCL Watershed 2.0
END DESCRIPTION:
XS GIS Cut Line= 3
      2787898.99      7040663.07      2787225.00      7040625.00
      2786742.77      7040642.24
#Sta/Elev= 30
  4319.1  449.13  4413.2  443.70  4423.3  444.15  4433.3  443.04  4473.3  440.78
  4513.4  439.60  4559.7  439.38  4728.5  438.29  4773.8  438.74  4853.9  438.45
  4884.0  438.95  4944.1  438.40  4974.1  439.08  4984.1  438.91  4988.7  436.27
  4989.2  435.47  4994.2  435.47  4994.7  436.27  4996.7  436.27  5004.2  439.40
  5047.7  438.57  5094.1  439.38  5131.7  439.50  5244.3  440.99  5264.3  442.01
  5304.4  443.10  5324.4  444.30  5384.4  446.64  5424.4  449.39  5476.7  451.57
#Mann=4,-1,0
  4319.1    0.05       0  4988.7    0.07       0  4994.7    0.05       0
  5047.7    0.05       0
Bank Sta=4559.7,5094.1
Exp/Cntr=0.3,0.1

Type RM Length L Ch R = 1,1706,147,147,147
BEGIN DESCRIPTION:
XS4150A
END DESCRIPTION:
XS GIS Cut Line= 3
      2787919.82      7040381.82      2787225.42      7040340.16
      2786652.46      7040329.74
#Sta/Elev= 30
  4298.1  444.26  4312.9  444.06  4343.0  441.92  4353.0  442.50  4383.1  440.89
  4393.1  441.14  4433.2  439.59  4493.8  438.26  4827.7  437.77  4954.1  437.34
  4974.1  438.24  4984.1  437.51  4988.5  436.47  4989.0  435.67  4994.0  435.67
  4994.5  436.47  4996.5  436.47  5000.8  438.96  5005.8  437.12  5014.2  437.06
  5024.2  437.88  5054.2  437.36  5064.2  437.90  5133.6  438.26  5264.2  439.38
  5374.2  440.97  5454.2  444.65  5504.2  446.30  5524.3  447.46  5566.8  448.35
#Mann=4,-1,0
  4298.1    0.08       0  4827.7    0.05       0  4988.5    0.03       0
  4994.5    0.05       0
Bank Sta=4493.8,5133.6
Exp/Cntr=0.3,0.1

Type RM Length L Ch R = 1,1559,400,400,400
BEGIN DESCRIPTION:
XS4149A
END DESCRIPTION:
XS GIS Cut Line= 3
      2788096.93      7040232.52      2787260.14      7040201.27
      2786559.33      7040183.92
#Sta/Elev= 30
  4143.1  446.60  4255.1  442.24  4285.1  439.45  4295.5  439.24  4335.2  437.77
  4371.7  437.14  4460.9  436.68  4545.3  436.11  4675.4  436.47  4685.4  436.11
  4743.5  436.75  4835.5  436.35  4955.6  437.14  4985.6  435.85  4992.6  435.00
  4993.1  434.20  4998.1  434.20  4998.6  435.00  5005.6  435.04  5015.6  436.79
  5025.6  437.48  5115.7  436.53  5267.7  437.14  5367.7  437.89  5466.7  439.29
  5485.8  439.83  5525.8  442.42  5565.8  444.15  5595.8  446.40  5681.5  450.48
#Mann=7,-1,0
  4143.1    0.08       0  4295.5    0.05       0  4460.9    0.08       0
  4992.6    0.07       0  4998.6    0.08       0  5367.7    0.05       0
  5466.7    0.08       0
Bank Sta=4371.7,5267.7
Exp/Cntr=0.3,0.1

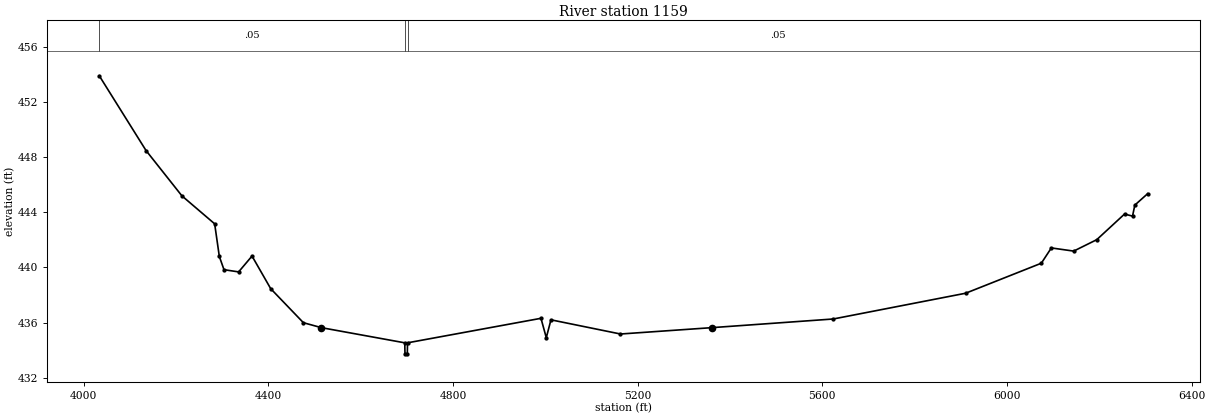
Type RM Length L Ch R = 1,1159,0,0,0
BEGIN DESCRIPTION:
UNT 186 in LFCCL Watershed 1.0
END DESCRIPTION:
XS GIS Cut Line= 3
      2788452.00      7040045.02      2787451.98      7039892.24
      2786195.02      7039961.69
#Sta/Elev= 30
  4034.1  453.92  4135.4  448.49  4213.1  445.20  4284.0  443.17  4294.1  440.80
  4304.2  439.84  4335.9  439.68  4364.9  440.83  4405.4  438.46  4476.2  435.99
  4515.3  435.63  4695.7  434.53  4696.2  433.73  4701.2  433.73  4701.7  434.53
  4990.7  436.31  5002.2  434.90  5012.3  436.20  5162.9  435.17  5360.1  435.63
  5623.6  436.26  5910.3  438.13  6074.3  440.31  6096.0  441.42  6144.4  441.19
  6194.4  442.02  6254.5  443.88  6271.8  443.73  6276.8  444.53  6304.6  445.36
#Mann=3,-1,0
  4034.1    0.05       0  4695.7    0.03       0  4701.7    0.05       0
Bank Sta=4515.3,5360.1
Exp/Cntr=0.3,0.1

Chan Stop Cuts=-1