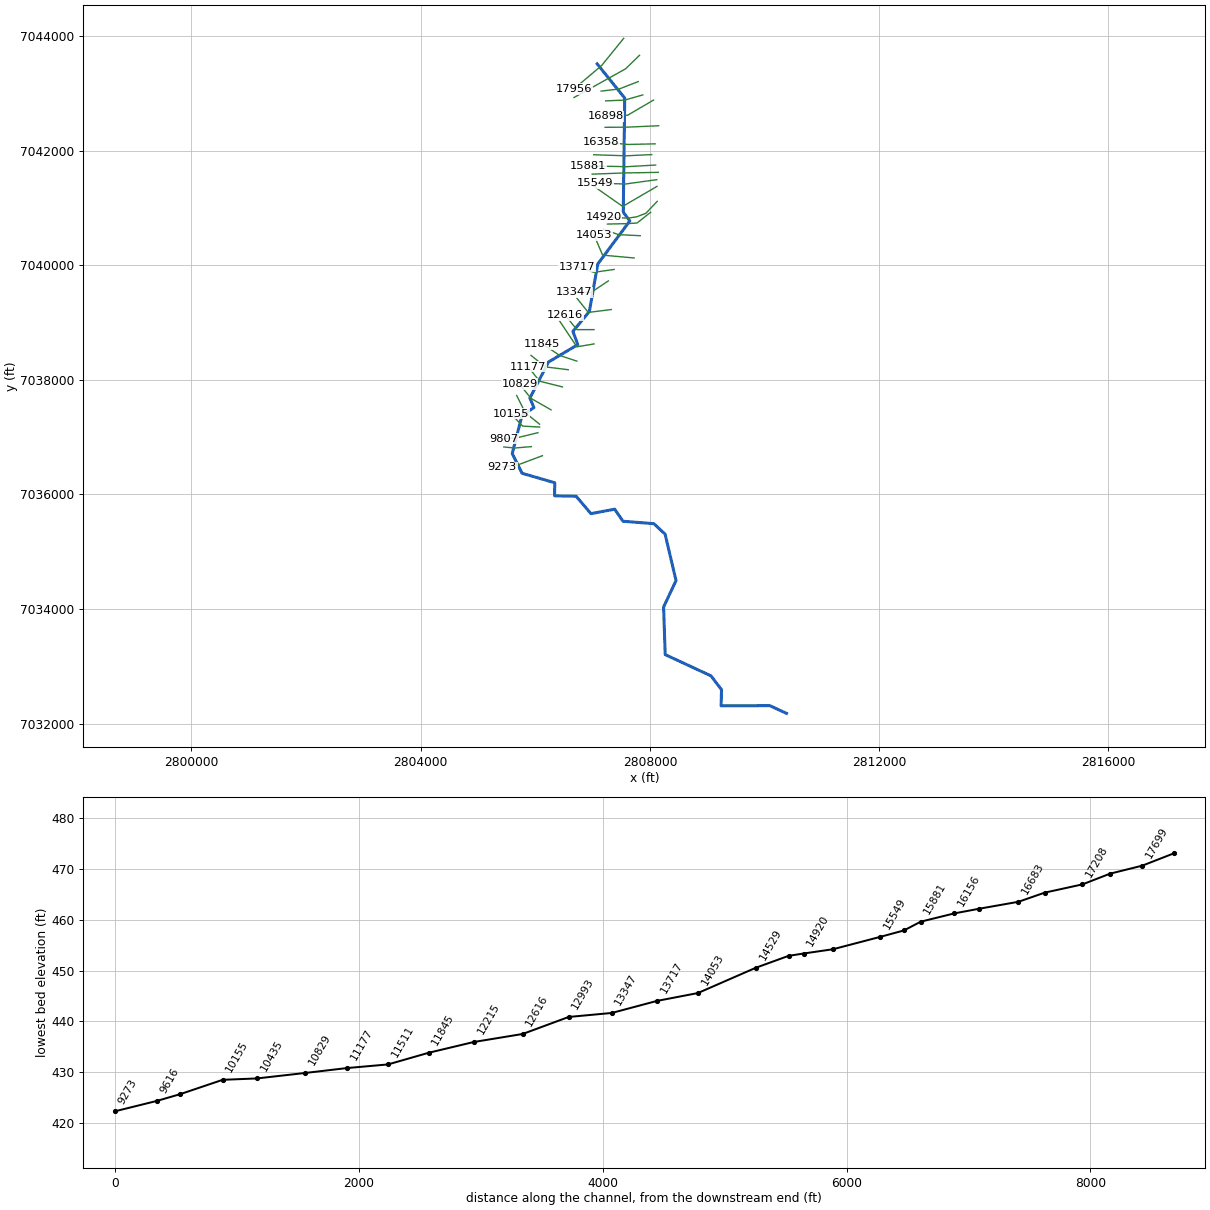
--- UNT 187 in LFCCL Watershed.prj (project) ---

Proj Title=UNT 187 in LFCCL Watershed Base Level Engineering
Current Plan=p01
Default Exp/Contr=0.3,0.1
English Units
Geom File=g01
Flow File=f01
Plan File=p01
BEGIN DESCRIPTION:
UNT 187 in LFCCL Watershed
END DESCRIPTION:

--- UNT 187 in LFCCL Watershed.p01 (plan) ---

Plan Title=Multiple Run
Short Identifier=Multiple
Geom File=g01
Flow File=f01
Subcritical Flow
K Sum by GR= 0
Std Step Tol= 0.01
Critical Tol= 0.01
Num of Std Step Trials= 20
Max Error Tol= 0.3
Flow Tol Ratio= 0.001
Split Flow NTrial= 30
Split Flow Tol= 0.02
Split Flow Ratio= 0.02
Log Output Level= 0
Friction Slope Method= 1
Unsteady Friction Slope Method= 2
Unsteady Bridges Friction Slope Method= 1
Parabolic Critical Depth
Global Vel Dist=  1 , 1 , 1
Global Log Level= 0
CheckData=True
Encroach Param= -1, 0, 0, 0
BEGIN DESCRIPTION:
Multiple Run
END DESCRIPTION:

--- UNT 187 in LFCCL Watershed.f01 (steady flow) ---

Flow Title=Multiple
Number of Profiles=7
Profile Names=10-year,25-year,50-year,1pct_min,100-year,1pct_plu,500-year
River Rch & RM= UNT 187 in LFCCL,Reach-1,17956
     172     212     242     138     275     548     355
River Rch & RM= UNT 187 in LFCCL,Reach-1,14529
     518     684     816     485     967    1930    1359
River Rch & RM= UNT 187 in LFCCL,Reach-1,5266
     627     836    1005     600    1198    2390    1703
Boundary for River Rch & Prof#=UNT 187 in LFCCL,Reach-1,1
Up Type=0
Dn Type=3
Dn Slope=0.005
Boundary for River Rch & Prof#=UNT 187 in LFCCL,Reach-1,2
Up Type=0
Dn Type=3
Dn Slope=0.005
Boundary for River Rch & Prof#=UNT 187 in LFCCL,Reach-1,3
Up Type=0
Dn Type=3
Dn Slope=0.005
Boundary for River Rch & Prof#=UNT 187 in LFCCL,Reach-1,4
Up Type=0
Dn Type=3
Dn Slope=0.005
Boundary for River Rch & Prof#=UNT 187 in LFCCL,Reach-1,5
Up Type=0
Dn Type=3
Dn Slope=0.005
Boundary for River Rch & Prof#=UNT 187 in LFCCL,Reach-1,6
Up Type=0
Dn Type=3
Dn Slope=0.005
Boundary for River Rch & Prof#=UNT 187 in LFCCL,Reach-1,7
Up Type=0
Dn Type=3
Dn Slope=0.005

--- UNT 187 in LFCCL Watershed.g01 (geometry) ---

Geom Title=Existing Conditions

River Reach=UNT 187 in LFCCL,Reach-1
Reach XY= 30
      2807079.17      7043512.97      2807560.94      7042915.31
      2807535.29      7040925.59      2807649.25      7040770.97
      2807090.45      7040019.54      2806943.45      7039191.54
      2806657.38      7038845.02      2806741.59      7038612.92
      2806229.64      7038308.76      2805905.97      7037680.12
      2805976.40      7037513.91      2805768.95      7037379.36
      2805598.07      7036712.19      2805768.89      7036368.27
      2806340.17      7036202.28      2806337.09      7035974.92
      2806713.86      7035966.52      2806971.05      7035663.65
      2807385.68      7035741.39      2807529.88      7035530.74
      2808068.81      7035488.59      2808265.51      7035305.47
      2808456.23      7034495.73      2808239.12      7034034.47
      2808267.00      7033204.02      2809067.39      7032832.17
      2809249.76      7032591.27      2809242.96      7032310.91
      2810094.94      7032312.27      2810383.89      7032178.18

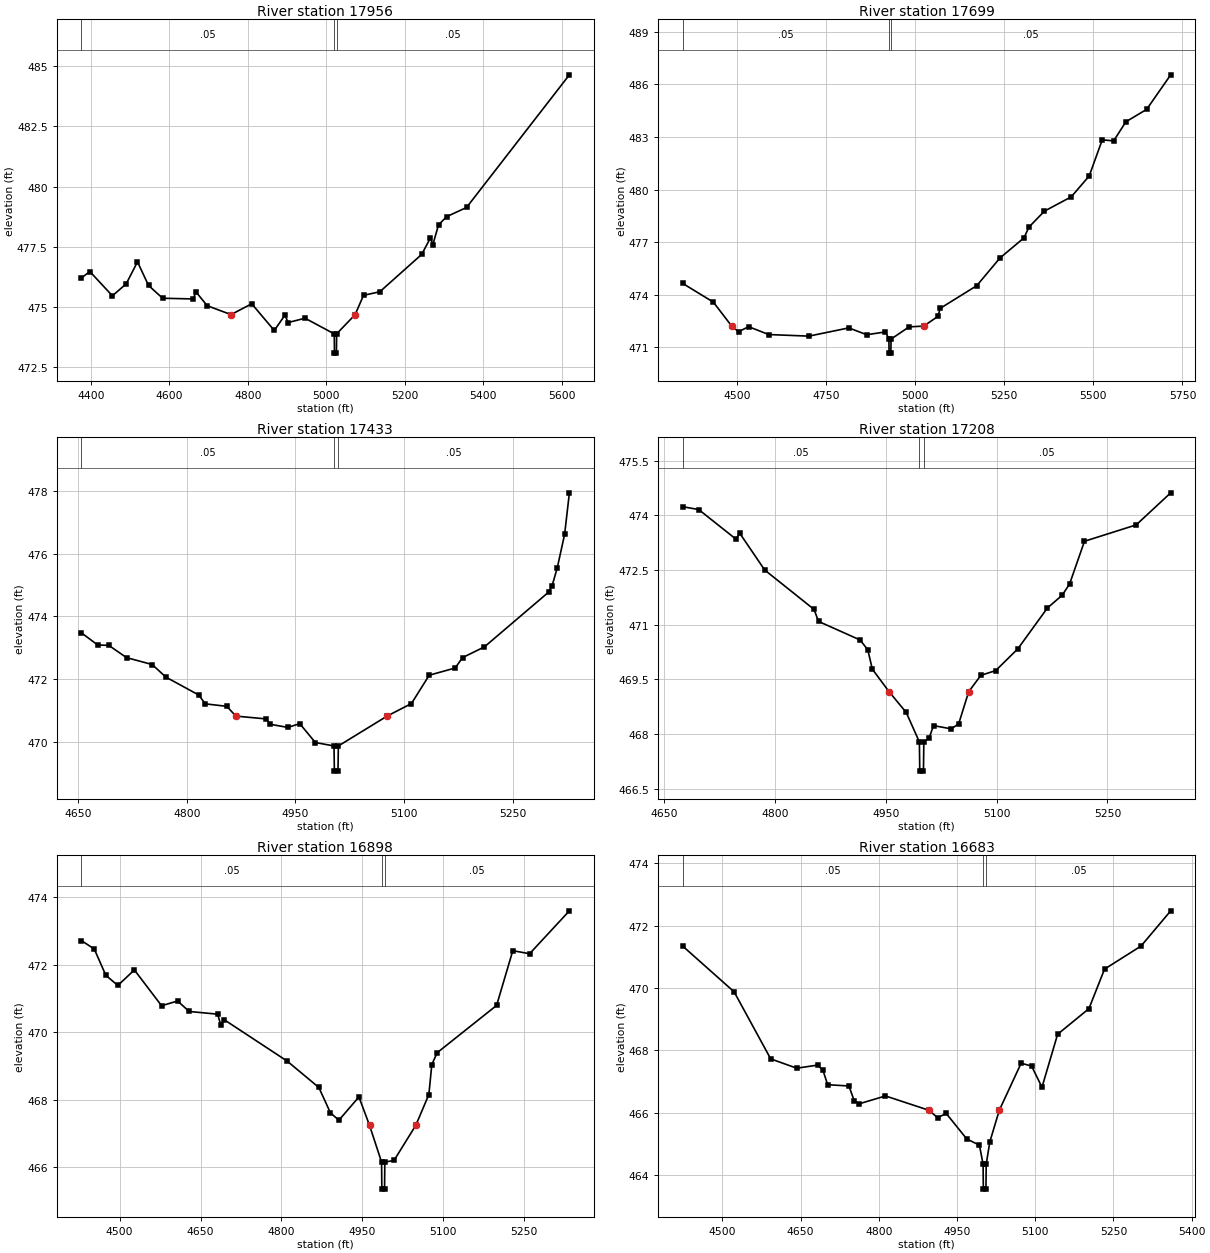
Type RM Length L Ch R = 1,17956,257,257,257
BEGIN DESCRIPTION:
UNT 187 in LFCCL Watershed 34.0
END DESCRIPTION:
XS GIS Cut Line= 3
      2807542.66      7043958.06      2807158.68      7043484.31
      2806675.03      7043075.03
#Sta/Elev= 30
  4375.7  476.20  4397.4  476.47  4454.9  475.46  4490.1  475.96  4518.8  476.87
  4547.0  475.89  4582.8  475.36  4661.1  475.33  4667.5  475.63  4696.3  475.05
  4757.1  474.68  4809.8  475.13  4867.3  474.02  4894.5  474.66  4902.5  474.35
  4945.6  474.53  5020.1  473.88  5020.6  473.08  5025.6  473.08  5026.1  473.88
  5073.3  474.68  5094.6  475.48  5136.2  475.63  5242.8  477.18  5264.9  477.86
  5271.4  477.59  5285.7  478.41  5306.5  478.75  5357.1  479.13  5619.1  484.64
#Mann=3,-1,0
  4375.7    0.05       0  5020.1    0.03       0  5026.1    0.05       0
Bank Sta=4757.1,5073.3
Exp/Cntr=0.3,0.1

Type RM Length L Ch R = 1,17699,266,266,266
BEGIN DESCRIPTION:
UNT 187 in LFCCL Watershed 33.0
END DESCRIPTION:
XS GIS Cut Line= 3
      2807819.27      7043662.56      2807575.00      7043425.00
      2806675.00      7042925.00
#Sta/Elev= 30
  4346.7  474.65  4432.9  473.58  4484.6  472.21  4503.6  471.89  4531.9  472.18
  4588.5  471.73  4701.2  471.64  4813.3  472.11  4863.6  471.72  4916.2  471.88
  4925.8  471.47  4926.3  470.67  4931.3  470.67  4931.8  471.47  4982.6  472.17
  5023.3  472.21  5063.8  472.77  5069.5  473.22  5172.5  474.52  5237.7  476.10
  5305.2  477.25  5318.9  477.86  5362.4  478.77  5437.9  479.59  5488.2  480.78
  5524.8  482.84  5556.8  482.78  5591.2  483.87  5649.5  484.58  5717.0  486.55
#Mann=3,-1,0
  4346.7    0.05       0  4925.8    0.03       0  4931.8    0.05       0
Bank Sta=4484.6,5023.3
Exp/Cntr=0.3,0.1

Type RM Length L Ch R = 1,17433,225,225,225
BEGIN DESCRIPTION:
XS4151A
END DESCRIPTION:
XS GIS Cut Line= 3
      2807796.13      7043203.42      2807466.26      7043074.94
      2807148.43      7043036.94
#Sta/Elev= 30
  4654.3  473.48  4677.0  473.09  4692.2  473.08  4716.7  472.69  4752.1  472.47
  4771.1  472.07  4816.5  471.50  4825.5  471.22  4855.3  471.14  4867.7  470.83
  4909.7  470.74  4915.1  470.57  4939.6  470.47  4956.0  470.59  4977.5  469.99
  5003.3  469.88  5003.8  469.08  5008.8  469.08  5009.3  469.88  5076.6  470.83
  5110.3  471.23  5134.8  472.13  5170.7  472.36  5180.8  472.69  5211.0  473.03
  5299.6  474.77  5304.6  474.98  5311.7  475.55  5321.8  476.61  5328.4  477.93
#Mann=3,-1,0
  4654.3    0.05       0  5003.3    0.03       0  5009.3    0.05       0
Bank Sta=4867.7,5076.6
Exp/Cntr=0.3,0.1

Type RM Length L Ch R = 1,17208,310,310,310
BEGIN DESCRIPTION:
XS4152A
END DESCRIPTION:
XS GIS Cut Line= 3
      2807875.94      7042970.76      2807560.01      7042880.49
      2807228.37      7042866.68
#Sta/Elev= 30
  4675.1  474.24  4696.9  474.16  4747.2  473.35  4752.4  473.51  4786.2  472.50
  4852.9  471.42  4859.0  471.09  4915.3  470.58  4925.7  470.31  4931.8  469.78
  4954.5  469.16  4977.7  468.59  4995.5  467.78  4996.0  466.98  5001.0  466.98
  5001.5  467.78  5008.7  467.89  5014.6  468.23  5038.7  468.14  5048.7  468.28
  5062.2  469.16  5078.7  469.61  5098.8  469.74  5128.8  470.34  5168.8  471.46
  5188.8  471.81  5198.8  472.12  5218.9  473.29  5288.9  473.74  5335.6  474.62
#Mann=3,-1,0
  4675.1    0.05       0  4995.5    0.03       0  5001.5    0.05       0
Bank Sta=4954.5,5062.2
Exp/Cntr=0.3,0.1

Type RM Length L Ch R = 1,16898,215,215,215
BEGIN DESCRIPTION:
XS4153A
END DESCRIPTION:
XS GIS Cut Line= 3
      2808063.50      7042880.51      2807612.09      7042616.61
      2807230.15      7042595.77
#Sta/Elev= 30
  4428.9  472.71  4452.9  472.46  4474.4  471.68  4496.7  471.38  4527.3  471.84
  4577.8  470.78  4607.5  470.92  4629.0  470.61  4681.8  470.53  4687.6  470.21
  4693.6  470.37  4810.8  469.14  4869.5  468.36  4891.0  467.61  4906.7  467.39
  4943.9  468.08  4963.5  467.24  4985.9  466.15  4986.4  465.35  4991.4  465.35
  4991.9  466.15  5009.0  466.20  5049.4  467.24  5073.6  468.15  5079.1  469.04
  5089.1  469.39  5199.3  470.79  5229.3  472.41  5260.5  472.32  5334.3  473.59
#Mann=3,-1,0
  4428.9    0.05       0  4985.9    0.03       0  4991.9    0.05       0
Bank Sta=4963.5,5049.4
Exp/Cntr=0.3,0.1

Type RM Length L Ch R = 1,16683,325,325,325
BEGIN DESCRIPTION:
XS4154A
END DESCRIPTION:
XS GIS Cut Line= 3
      2808153.72      7042432.58      2807608.62      7042408.27
      2807218.08      7042404.82
#Sta/Elev= 30
  4423.6  471.35  4522.4  469.88  4592.5  467.73  4642.5  467.43  4682.6  467.53
  4692.6  467.37  4701.8  466.90  4742.6  466.86  4752.6  466.39  4762.7  466.29
  4812.7  466.54  4896.1  466.08  4912.8  465.84  4929.1  465.98  4968.6  465.16
  4992.9  464.96  4999.9  464.35  5000.4  463.55  5005.4  463.55  5005.9  464.35
  5012.9  465.07  5031.0  466.08  5072.9  467.59  5092.9  467.50  5112.9  466.82
  5142.9  468.52  5202.9  469.34  5232.9  470.61  5302.9  471.35  5359.8  472.48
#Mann=3,-1,0
  4423.6    0.05       0  4999.9    0.03       0  5005.9    0.05       0
Bank Sta=4896.1,5031
Exp/Cntr=0.3,0.1

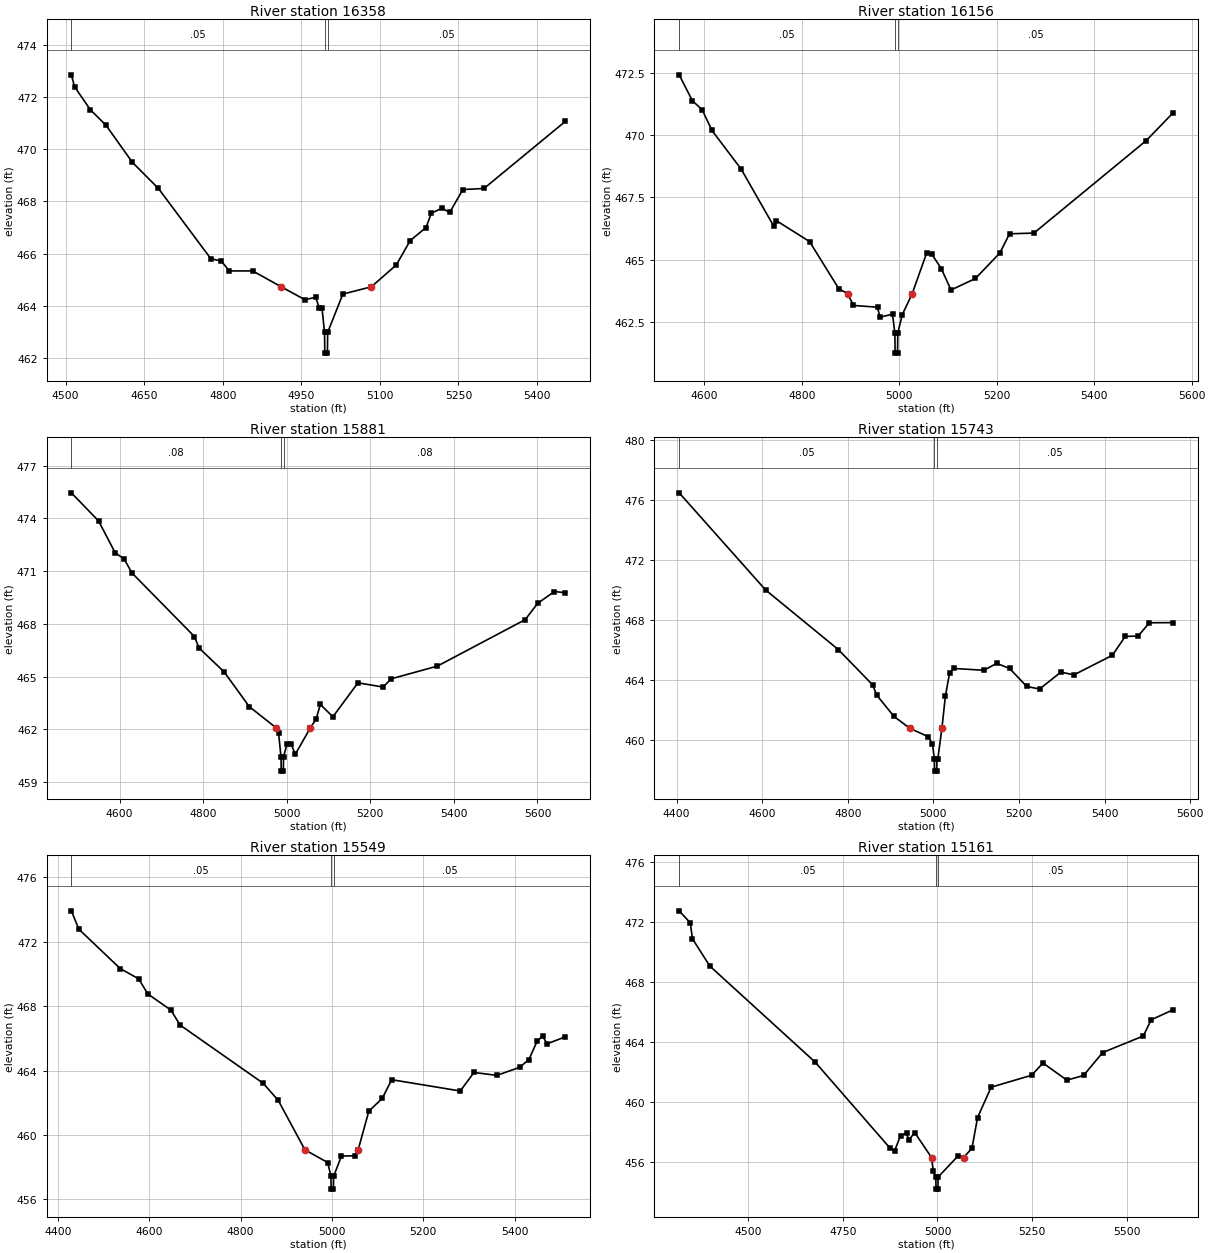
Type RM Length L Ch R = 1,16358,202,202,202
BEGIN DESCRIPTION:
XS4155A
END DESCRIPTION:
XS GIS Cut Line= 3
      2808091.22      7042116.61      2807615.56      7042106.19
      2807150.32      7042151.32
#Sta/Elev= 30
  4511.0  472.87  4517.2  472.41  4547.2  471.53  4577.2  470.93  4627.3  469.51
  4677.3  468.50  4777.3  465.80  4797.3  465.71  4812.5  465.33  4857.3  465.33
  4911.7  464.72  4957.3  464.22  4977.3  464.32  4984.6  463.90  4989.6  463.90
  4994.4  462.97  4994.9  462.17  4999.9  462.17  5000.4  462.97  5029.4  464.44
  5083.8  464.72  5131.4  465.56  5158.1  466.50  5188.3  467.00  5198.3  467.55
  5218.4  467.74  5233.4  467.58  5258.6  468.46  5298.8  468.50  5454.2  471.08
#Mann=3,-1,0
  4511.0    0.05       0  4994.4    0.03       0  5000.4    0.05       0
Bank Sta=4911.7,5083.8
Exp/Cntr=0.3,0.1

Type RM Length L Ch R = 1,16156,275,275,275
BEGIN DESCRIPTION:
XS4156A
END DESCRIPTION:
XS GIS Cut Line= 3
      2808032.19      7041929.10      2807584.31      7041908.27
      2807019.57      7041926.49
#Sta/Elev= 30
  4548.6  472.41  4575.8  471.37  4595.8  471.01  4615.9  470.18  4675.9  468.63
  4742.8  466.34  4747.8  466.57  4816.1  465.73  4876.1  463.84  4894.2  463.64
  4906.2  463.17  4955.5  463.10  4960.5  462.70  4986.3  462.82  4991.1  462.06
  4991.6  461.26  4996.6  461.26  4997.1  462.06  5006.3  462.80  5026.6  463.64
  5056.3  465.27  5066.3  465.24  5086.3  464.65  5106.3  463.79  5156.4  464.25
  5206.4  465.27  5226.4  466.04  5276.4  466.07  5506.5  469.77  5562.0  470.89
#Mann=3,-1,0
  4548.6    0.05       0  4991.1    0.03       0  4997.1    0.05       0
Bank Sta=4894.2,5026.6
Exp/Cntr=0.3,0.1

Type RM Length L Ch R = 1,15881,138,138,138
BEGIN DESCRIPTION:
XS4157A
END DESCRIPTION:
XS GIS Cut Line= 4
      2808099.97      7041746.82      2807592.12      7041718.17
      2807360.35      7041723.38      2806918.87      7041728.57
#Sta/Elev= 30
  4484.7  475.45  4549.8  473.85  4589.8  472.03  4610.3  471.71  4629.9  470.89
  4779.2  467.28  4790.2  466.63  4850.3  465.27  4910.3  463.30  4974.7  462.09
  4980.5  461.79  4986.4  460.43  4986.9  459.63  4991.9  459.63  4992.4  460.43
  5000.5  461.16  5010.5  461.17  5020.5  460.59  5056.6  462.09  5070.2  462.58
  5080.5  463.42  5110.5  462.72  5170.5  464.65  5230.5  464.41  5250.5  464.88
  5360.5  465.60  5570.6  468.24  5600.6  469.17  5640.6  469.84  5666.7  469.77
#Mann=3,-1,0
  4484.7    0.08       0  4986.4    0.07       0  4992.4    0.08       0
Bank Sta=4974.7,5056.6
Exp/Cntr=0.3,0.1

Type RM Length L Ch R = 1,15743,194,194,194
BEGIN DESCRIPTION:
XS4158A
END DESCRIPTION:
XS GIS Cut Line= 3
      2808146.86      7041619.21      2807545.25      7041608.79
      2806993.14      7041587.96
#Sta/Elev= 30
  4406.0  476.47  4607.9  469.99  4777.9  466.01  4857.9  463.66  4867.9  462.96
  4907.9  461.55  4945.3  460.75  4987.9  460.20  4997.9  459.71  5002.3  458.70
  5002.8  457.90  5007.8  457.90  5008.3  458.70  5010.3  458.70  5019.9  460.75
  5028.0  462.89  5038.0  464.47  5048.0  464.75  5118.0  464.63  5148.0  465.09
  5178.1  464.75  5218.1  463.55  5248.1  463.38  5298.2  464.51  5328.2  464.32
  5418.2  465.63  5448.3  466.89  5478.3  466.91  5504.7  467.80  5560.2  467.81
#Mann=3,-1,0
  4406.0    0.05       0  5002.3    0.03       0  5008.3    0.05       0
Bank Sta=4945.3,5019.9
Exp/Cntr=0.3,0.1

Type RM Length L Ch R = 1,15549,388,388,388
BEGIN DESCRIPTION:
XS4159A
END DESCRIPTION:
XS GIS Cut Line= 3
      2808120.79      7041491.61      2807573.90      7041416.09
      2807045.21      7041431.71
#Sta/Elev= 30
  4429.7  473.91  4446.1  472.77  4536.5  470.33  4576.9  469.69  4597.1  468.75
  4647.5  467.75  4667.7  466.82  4849.4  463.21  4882.4  462.15  4940.8  459.08
  4990.7  458.29  4997.7  457.44  4998.2  456.64  5003.2  456.64  5003.7  457.44
  5020.7  458.69  5050.7  458.71  5057.3  459.08  5080.7  461.48  5110.0  462.27
  5130.7  463.43  5280.8  462.73  5310.8  463.88  5360.8  463.70  5410.9  464.20
  5430.9  464.68  5449.3  465.84  5460.9  466.13  5470.9  465.66  5510.7  466.09
#Mann=3,-1,0
  4429.7    0.05       0  4997.7    0.03       0  5003.7    0.05       0
Bank Sta=4940.8,5057.3
Exp/Cntr=0.3,0.1

Type RM Length L Ch R = 1,15161,241,241,241
BEGIN DESCRIPTION:
UNT 187 in LFCCL Watershed 26.0
END DESCRIPTION:
XS GIS Cut Line= 3
      2808124.98      7041374.99      2807525.00      7041025.00
      2807025.02      7041374.98
#Sta/Elev= 30
  4317.6  472.74  4346.9  471.94  4352.7  470.88  4398.6  469.06  4676.5  462.67
  4873.3  456.97  4886.9  456.77  4902.6  457.77  4918.3  457.93  4924.1  457.46
  4939.8  457.97  4984.4  456.30  4989.0  455.38  4995.6  455.00  4996.1  454.20
  5001.1  454.20  5001.6  455.00  5055.4  456.44  5069.0  456.30  5091.1  456.93
  5105.9  458.97  5141.7  460.99  5248.9  461.79  5278.6  462.60  5341.8  461.46
  5385.8  461.77  5436.4  463.30  5543.6  464.40  5564.5  465.48  5622.5  466.15
#Mann=3,-1,0
  4317.6    0.05       0  4995.6    0.03       0  5001.6    0.05       0
Bank Sta=4984.4,5069
Exp/Cntr=0.3,0.1

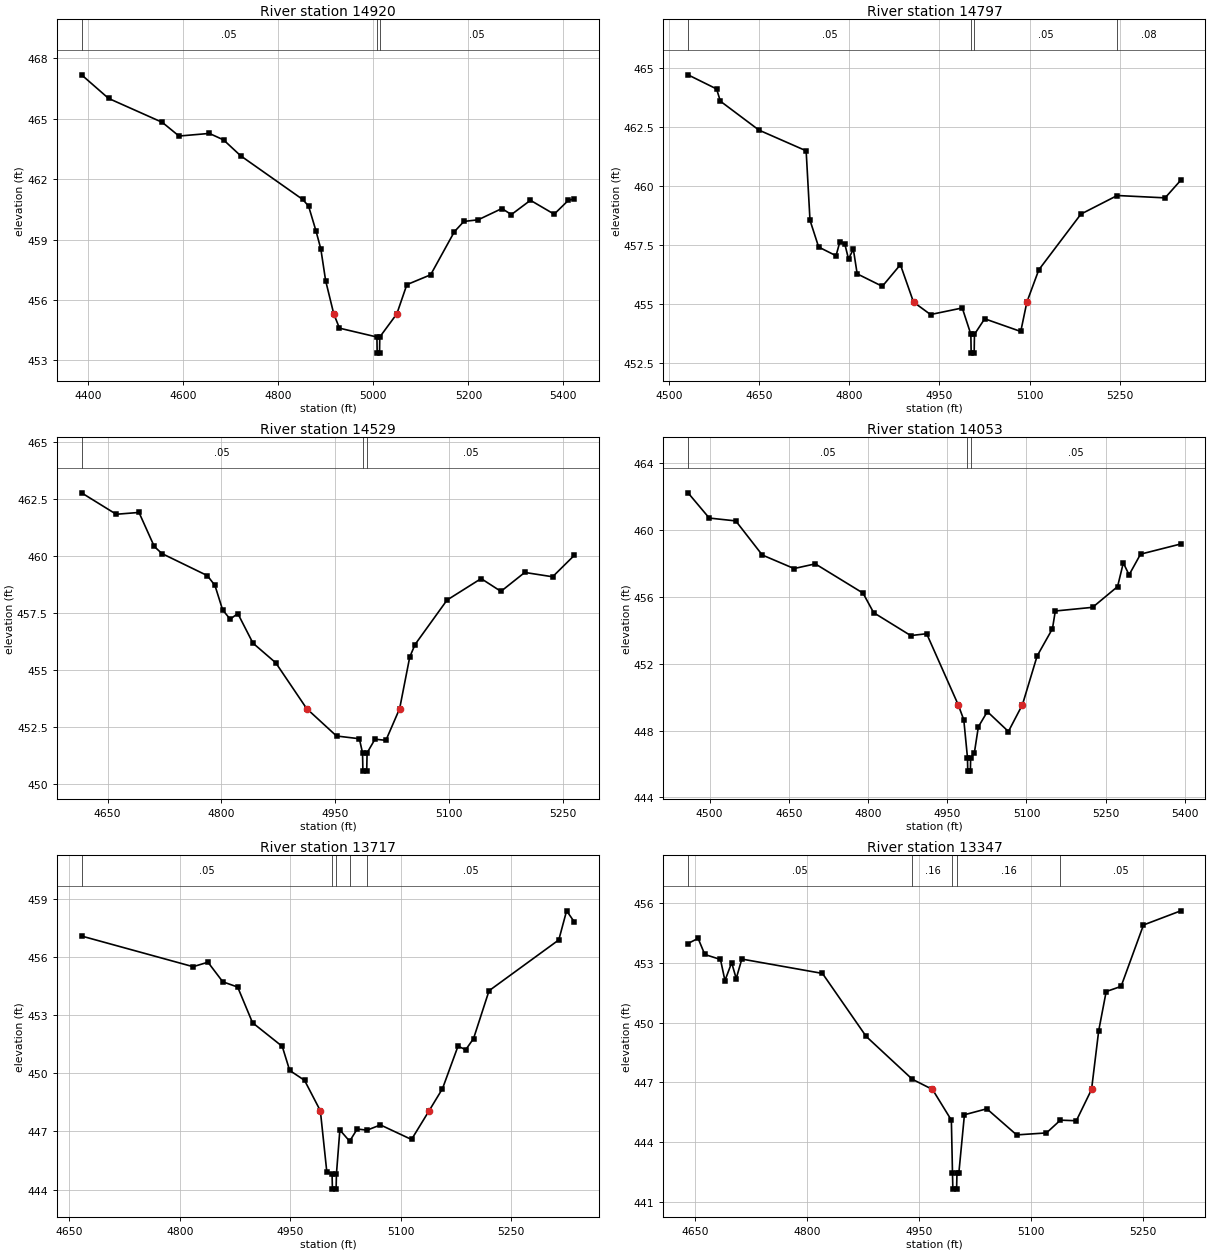
Type RM Length L Ch R = 1,14920,123,123,123
BEGIN DESCRIPTION:
XS4160A
END DESCRIPTION:
XS GIS Cut Line= 5
      2808127.47      7041112.88      2807929.58      7040904.58
      2807765.52      7040842.08      2807622.29      7040821.25
      2807192.60      7040834.27
#Sta/Elev= 30
  4385.5  467.18  4442.3  466.01  4555.5  464.82  4590.7  464.14  4654.6  464.27
  4684.4  463.95  4720.5  463.16  4851.2  460.99  4863.5  460.66  4879.2  459.42
  4889.3  458.53  4899.4  456.96  4916.5  455.31  4928.5  454.60  5007.4  454.16
  5007.9  453.36  5012.9  453.36  5013.4  454.16  5049.3  455.31  5070.4  456.76
  5120.5  457.25  5170.5  459.39  5190.5  459.90  5220.5  459.98  5270.5  460.54
  5290.5  460.24  5330.6  460.95  5380.6  460.26  5410.6  460.95  5423.0  461.02
#Mann=3,-1,0
  4385.5    0.05       0  5007.4    0.04       0  5013.4    0.05       0
Bank Sta=4916.5,5049.3
Exp/Cntr=0.3,0.1

Type RM Length L Ch R = 1,14797,268,268,268
BEGIN DESCRIPTION:
XS4161A
END DESCRIPTION:
XS GIS Cut Line= 4
      2808012.94      7040922.84      2807775.94      7040735.31
      2807622.29      7040724.90      2807258.89      7040717.11
#Sta/Elev= 30
  4531.8  464.73  4579.3  464.13  4585.6  463.61  4649.8  462.38  4728.3  461.50
  4734.7  458.55  4749.1  457.41  4778.0  457.04  4784.4  457.63  4792.4  457.56
  4798.8  456.90  4806.8  457.32  4813.2  456.27  4855.0  455.74  4885.1  456.66
  4906.9  455.07  4935.2  454.54  4988.0  454.82  5002.3  453.70  5002.8  452.90
  5007.8  452.90  5008.3  453.70  5025.3  454.36  5085.3  453.82  5095.5  455.07
  5115.3  456.44  5185.4  458.81  5245.8  459.60  5325.4  459.50  5351.5  460.25
#Mann=4,-1,0
  4531.8    0.05       0  5002.3    0.03       0  5008.3    0.05       0
  5245.8    0.08       0
Bank Sta=4906.9,5095.5
Exp/Cntr=0.3,0.1

Type RM Length L Ch R = 1,14529,476,476,476
BEGIN DESCRIPTION:
XS4162A
END DESCRIPTION:
XS GIS Cut Line= 3
      2807830.64      7040513.96      2807455.62      7040532.19
      2807196.26      7040620.37
#Sta/Elev= 30
  4615.6  462.76  4661.3  461.82  4691.3  461.90  4711.4  460.41  4721.4  460.10
  4781.4  459.13  4791.4  458.70  4801.5  457.63  4811.5  457.22  4821.5  457.47
  4841.5  456.17  4871.5  455.31  4912.3  453.30  4951.6  452.10  4981.7  451.98
  4985.9  451.36  4986.4  450.56  4991.4  450.56  4991.9  451.36  5002.3  451.96
  5016.7  451.91  5034.8  453.30  5048.1  455.56  5055.1  456.11  5097.3  458.06
  5142.2  459.00  5168.3  458.44  5199.7  459.27  5236.4  459.08  5265.0  460.02
#Mann=3,-1,0
  4615.6    0.05       0  4985.9    0.03       0  4991.9    0.05       0
Bank Sta=4912.3,5034.8
Exp/Cntr=0.3,0.1

Type RM Length L Ch R = 1,14053,336,336,336
BEGIN DESCRIPTION:
UNT 187 in LFCCL Watershed 23.0
END DESCRIPTION:
XS GIS Cut Line= 3
      2807725.01      7040125.00      2807175.00      7040175.00
      2807024.99      7040525.03
#Sta/Elev= 30
  4459.1  462.22  4499.3  460.71  4549.5  460.54  4599.7  458.50  4659.9  457.69
  4700.1  457.97  4790.5  456.22  4810.6  455.05  4880.8  453.68  4911.0  453.79
  4970.6  449.55  4981.3  448.64  4988.3  446.37  4988.8  445.57  4993.8  445.57
  4994.3  446.37  5001.3  446.66  5008.9  448.22  5025.9  449.13  5065.8  447.94
  5092.4  449.55  5120.2  452.46  5149.2  454.09  5154.6  455.15  5225.3  455.37
  5272.5  456.61  5283.4  458.03  5294.3  457.31  5316.0  458.55  5392.2  459.16
#Mann=3,-1,0
  4459.1    0.05       0  4988.3    0.03       0  4994.3    0.05       0
Bank Sta=4970.6,5092.4
Exp/Cntr=0.3,0.1

Type RM Length L Ch R = 1,13717,370,370,370
BEGIN DESCRIPTION:
UNT 187 in LFCCL Watershed 22.0
END DESCRIPTION:
XS GIS Cut Line= 3
      2807375.03      7039925.00      2807025.00      7039875.00
      2806725.01      7039975.00
#Sta/Elev= 30
  4666.4  457.07  4818.0  455.49  4838.2  455.72  4858.4  454.71  4878.6  454.44
  4898.8  452.60  4939.2  451.38  4949.3  450.14  4969.5  449.63  4991.0  448.06
  4999.8  444.90  5006.9  444.82  5007.4  444.02  5012.4  444.02  5012.9  444.82
  5017.5  447.07  5030.8  446.49  5041.1  447.12  5054.4  447.06  5072.7  447.33
  5114.9  446.58  5138.8  448.06  5157.0  449.20  5178.1  451.39  5188.6  451.21
  5199.2  451.78  5220.3  454.25  5315.1  456.87  5325.7  458.37  5336.2  457.80
#Mann=5,-1,0
  4666.4    0.05       0  5006.9    0.03       0  5012.9    0.05       0
  5030.8    0.16       0  5054.4    0.05       0
Bank Sta=4991,5138.8
Exp/Cntr=0.3,0.1

Type RM Length L Ch R = 1,13347,354,354,354
BEGIN DESCRIPTION:
UNT 187 in LFCCL Watershed 21.0
END DESCRIPTION:
XS GIS Cut Line= 3
      2807274.96      7039724.98      2806975.00      7039525.00
      2806675.01      7039525.00
#Sta/Elev= 30
  4640.3  453.97  4653.8  454.23  4662.8  453.42  4683.8  453.17  4689.8  452.11
  4698.8  453.01  4704.9  452.21  4712.4  453.19  4820.5  452.47  4879.1  449.31
  4941.0  447.16  4968.0  446.65  4993.3  445.11  4994.8  442.45  4995.3  441.65
  5000.3  441.65  5000.8  442.45  5003.3  442.45  5010.8  445.38  5040.8  445.68
  5080.8  444.37  5120.8  444.47  5139.4  445.11  5160.8  445.08  5181.2  446.65
  5190.8  449.60  5200.8  451.56  5220.8  451.82  5250.8  454.90  5300.8  455.61
#Mann=5,-1,0
  4640.3    0.05       0  4941.0    0.16       0  4994.8    0.07       0
  5000.8    0.16       0  5139.4    0.05       0
Bank Sta=4968,5181.2
Exp/Cntr=0.3,0.1

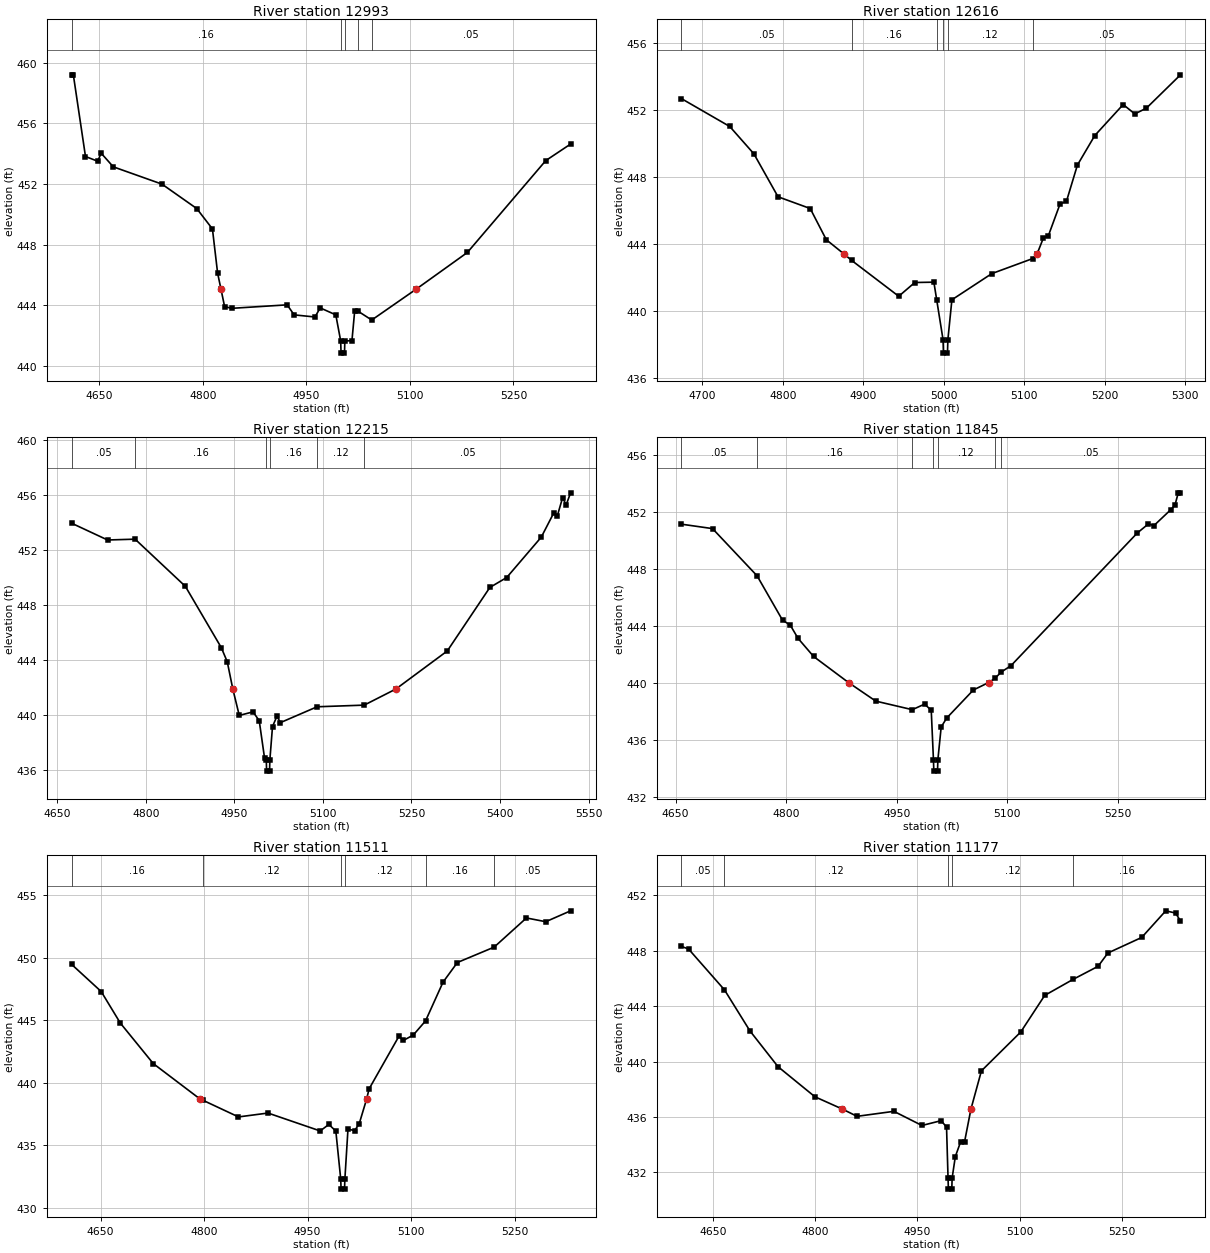
Type RM Length L Ch R = 1,12993,377,377,377
BEGIN DESCRIPTION:
UNT 187 in LFCCL Watershed 20.0
END DESCRIPTION:
XS GIS Cut Line= 3
      2807324.98      7039225.00      2806925.00      7039175.00
      2806725.03      7039424.96
#Sta/Elev= 30
  4609.7  459.19  4612.2  459.19  4629.8  453.81  4647.5  453.50  4652.5  454.03
  4670.1  453.13  4740.7  451.99  4791.1  450.38  4813.8  449.04  4821.3  446.13
  4826.2  445.07  4831.4  443.93  4841.5  443.81  4922.1  444.04  4932.2  443.38
  4962.4  443.24  4970.0  443.84  4992.6  443.38  4999.7  441.66  5000.2  440.86
  5005.2  440.86  5005.7  441.66  5016.0  441.68  5020.0  443.65  5024.2  443.64
  5044.7  443.04  5109.0  445.07  5183.3  447.49  5296.9  453.54  5332.9  454.63
#Mann=5,-1,0
  4609.7    0.16       0  4999.7    0.07       0  5005.7    0.16       0
  5024.2    0.12       0  5044.7    0.05       0
Bank Sta=4826.2,5109
Exp/Cntr=0.3,0.1

Type RM Length L Ch R = 1,12616,401,401,401
BEGIN DESCRIPTION:
UNT 187 in LFCCL Watershed 19.0
END DESCRIPTION:
XS GIS Cut Line= 3
      2807025.04      7038875.00      2806725.00      7038875.00
      2806525.00      7039125.00
#Sta/Elev= 30
  4674.0  452.68  4734.0  451.02  4764.0  449.39  4794.0  446.83  4834.0  446.13
  4854.0  444.27  4876.5  443.40  4885.4  443.04  4944.0  440.90  4964.0  441.72
  4987.7  441.74  4991.2  440.69  4999.1  438.31  4999.6  437.51  5004.6  437.51
  5005.1  438.31  5010.1  440.69  5059.7  442.25  5110.7  443.15  5115.7  443.39
  5123.7  444.36  5130.1  444.52  5144.5  446.40  5152.5  446.56  5166.1  448.72
  5187.7  450.48  5223.0  452.33  5237.4  451.77  5251.8  452.11  5294.2  454.10
#Mann=6,-1,0
  4674.0    0.05       0  4885.4    0.16       0  4991.2    0.12       0
  4999.1    0.07       0  5005.1    0.12       0  5110.7    0.05       0
Bank Sta=4876.5,5115.7
Exp/Cntr=0.3,0.1

Type RM Length L Ch R = 1,12215,370,370,370
BEGIN DESCRIPTION:
UNT 187 in LFCCL Watershed 18.0
END DESCRIPTION:
XS GIS Cut Line= 3
      2807025.02      7038625.00      2806725.00      7038575.00
      2806425.00      7039025.01
#Sta/Elev= 30
  4674.5  453.96  4735.4  452.74  4782.0  452.80  4867.1  449.37  4928.0  444.91
  4938.1  443.88  4947.5  441.90  4958.4  439.98  4981.7  440.24  4992.2  439.60
  5001.2  436.89  5004.2  436.73  5004.7  435.93  5009.7  435.93  5010.2  436.73
  5014.7  439.17  5022.2  439.92  5028.2  439.46  5090.2  440.61  5170.0  440.73
  5223.6  441.90  5310.7  444.67  5382.8  449.29  5411.3  450.01  5469.9  452.95
  5490.9  454.70  5497.0  454.49  5506.0  455.82  5512.0  455.29  5519.5  456.17
#Mann=6,-1,0
  4674.5    0.05       0  4782.0    0.16       0  5004.2    0.07       0
  5010.2    0.16       0  5090.2    0.12       0  5170.0    0.05       0
Bank Sta=4947.5,5223.6
Exp/Cntr=0.3,0.1

Type RM Length L Ch R = 1,11845,334,334,334
BEGIN DESCRIPTION:
UNT 187 in LFCCL Watershed 17.0
END DESCRIPTION:
XS GIS Cut Line= 3
      2806724.96      7038325.01      2806425.00      7038425.00
      2806125.03      7038624.98
#Sta/Elev= 30
  4658.1  451.13  4700.2  450.82  4760.6  447.51  4795.1  444.40  4805.6  444.05
  4816.2  443.12  4837.3  441.85  4884.7  440.02  4921.6  438.72  4971.1  438.12
  4987.8  438.51  4996.8  438.08  4999.8  434.61  5000.3  433.81  5005.3  433.81
  5005.8  434.61  5010.3  436.91  5017.9  437.54  5053.9  439.50  5074.5  440.02
  5083.1  440.31  5091.5  440.75  5105.0  441.21  5276.2  450.51  5291.3  451.15
  5298.8  451.03  5321.3  452.13  5327.3  452.46  5331.8  453.33  5334.8  453.33
#Mann=7,-1,0
  4658.1    0.05       0  4760.6    0.16       0  4971.1    0.12       0
  4999.8    0.07       0  5005.8    0.12       0  5083.1    0.16       0
  5091.5    0.05       0
Bank Sta=4884.7,5074.5
Exp/Cntr=0.3,0.1

Type RM Length L Ch R = 1,11511,334,334,334
BEGIN DESCRIPTION:
UNT 187 in LFCCL Watershed 16.0
END DESCRIPTION:
XS GIS Cut Line= 3
      2806575.03      7038175.00      2806175.00      7038225.00
      2805925.00      7038425.00
#Sta/Elev= 30
  4608.0  449.47  4650.9  447.30  4678.6  444.78  4726.4  441.54  4794.4  438.70
  4798.4  438.61  4849.9  437.28  4892.7  437.59  4968.3  436.16  4980.9  436.68
  4991.0  436.15  4998.1  432.31  4998.6  431.51  5003.6  431.51  5004.1  432.31
  5008.6  436.30  5018.3  436.19  5024.8  436.72  5035.6  438.70  5039.2  439.52
  5082.4  443.72  5088.8  443.39  5103.2  443.82  5121.0  444.95  5146.4  448.05
  5167.2  449.62  5220.5  450.85  5267.3  453.18  5295.3  452.88  5331.3  453.75
#Mann=6,-1,0
  4608.0    0.16       0  4798.4    0.12       0  4998.1    0.07       0
  5004.1    0.12       0  5121.0    0.16       0  5220.5    0.05       0
Bank Sta=4794.4,5035.6
Exp/Cntr=0.3,0.1

Type RM Length L Ch R = 1,11177,348,348,348
BEGIN DESCRIPTION:
UNT 187 in LFCCL Watershed 15.0
END DESCRIPTION:
XS GIS Cut Line= 3
      2806475.01      7037875.00      2806075.00      7037975.00
      2805874.98      7038225.02
#Sta/Elev= 30
  4603.8  448.30  4614.1  448.12  4666.9  445.17  4704.3  442.21  4745.5  439.63
  4799.7  437.46  4840.1  436.57  4861.5  436.05  4915.6  436.41  4956.8  435.39
  4985.2  435.74  4992.9  435.26  4995.1  431.60  4995.6  430.80  5000.6  430.80
  5001.1  431.60  5005.8  433.15  5013.5  434.20  5019.3  434.20  5028.7  436.57
  5044.1  439.33  5101.8  442.13  5137.0  444.77  5178.8  445.93  5215.4  446.87
  5229.8  447.83  5279.4  448.95  5314.7  450.87  5329.1  450.71  5336.3  450.14
#Mann=5,-1,0
  4603.8    0.05       0  4666.9    0.12       0  4995.1    0.07       0
  5001.1    0.12       0  5178.8    0.16       0
Bank Sta=4840.1,5028.7
Exp/Cntr=0.3,0.1

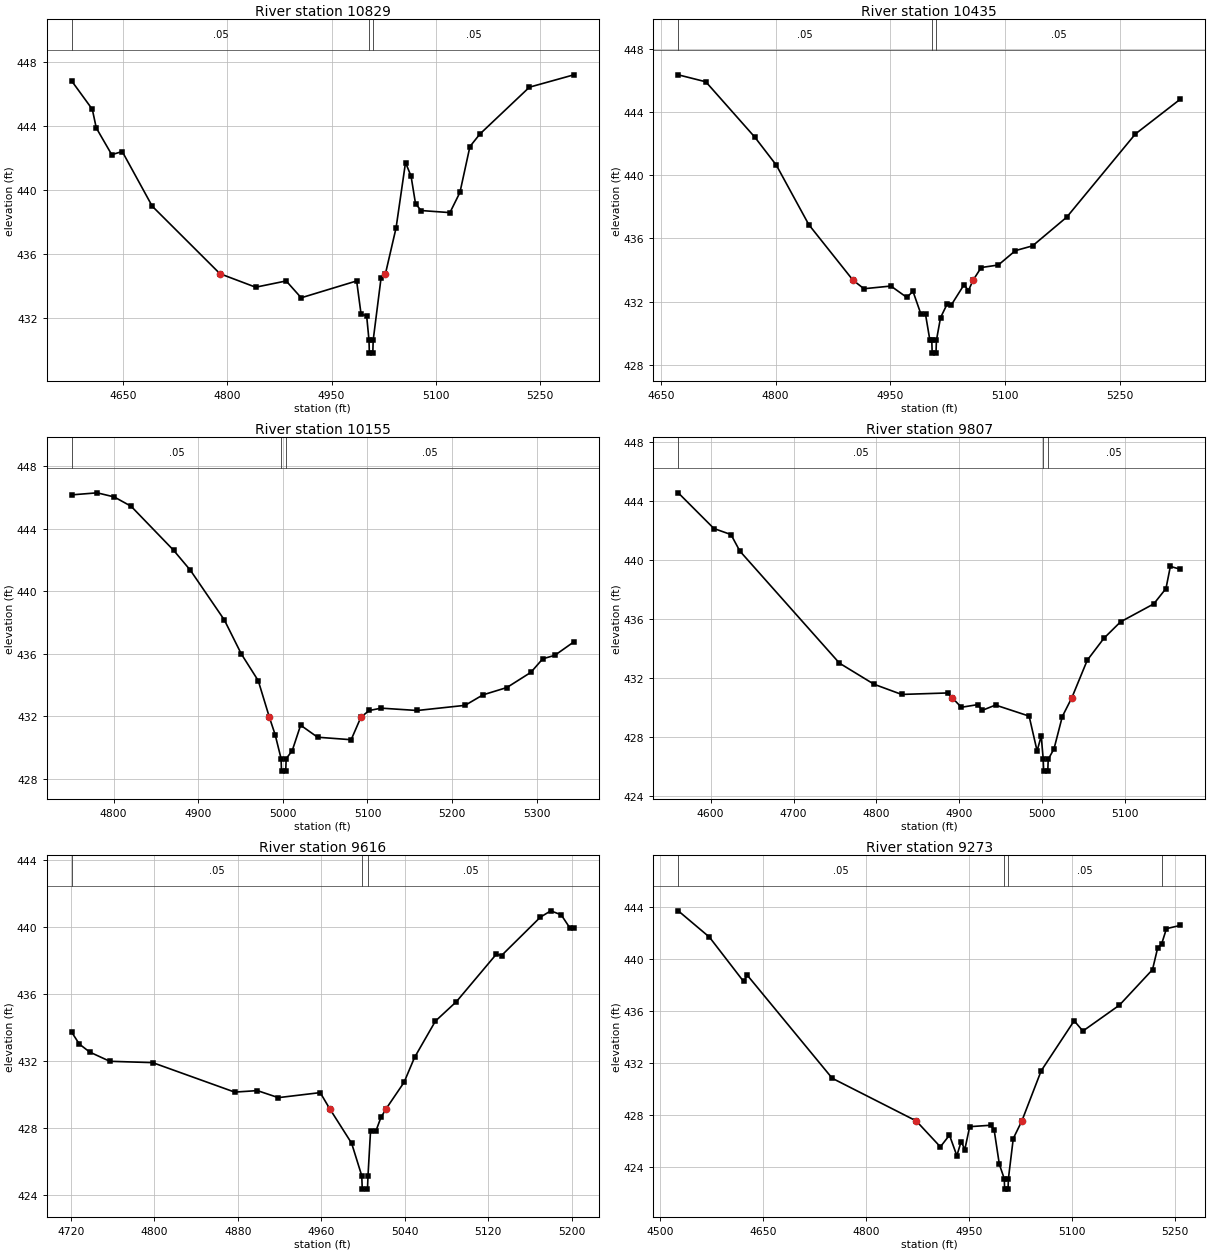
Type RM Length L Ch R = 1,10829,394,394,394
BEGIN DESCRIPTION:
UNT 187 in LFCCL Watershed 14.0
END DESCRIPTION:
XS GIS Cut Line= 3
      2806275.04      7037474.98      2805925.00      7037675.00
      2805725.01      7037924.99
#Sta/Elev= 30
  4575.7  446.78  4605.3  445.02  4611.0  443.86  4633.3  442.19  4648.4  442.39
  4691.6  438.98  4789.2  434.77  4840.6  433.93  4884.6  434.32  4906.2  433.27
  4986.1  434.32  4992.5  432.24  5000.5  432.15  5003.9  430.62  5004.4  429.82
  5009.4  429.82  5009.9  430.62  5021.3  434.52  5027.6  434.77  5042.9  437.63
  5056.5  441.70  5064.5  440.85  5070.9  439.14  5078.9  438.71  5120.5  438.58
  5134.9  439.84  5149.3  442.70  5163.7  443.48  5235.0  446.40  5299.0  447.17
#Mann=3,-1,0
  4575.7    0.05       0  5003.9    0.03       0  5009.9    0.05       0
Bank Sta=4789.2,5027.6
Exp/Cntr=0.3,0.1

Type RM Length L Ch R = 1,10435,280,280,280
BEGIN DESCRIPTION:
UNT 187 in LFCCL Watershed 13.0
END DESCRIPTION:
XS GIS Cut Line= 3
      2806075.00      7037225.00      2805825.00      7037425.00
      2805674.98      7037725.03
#Sta/Elev= 30
  4672.9  446.34  4708.9  445.90  4772.9  442.40  4801.0  440.63  4843.4  436.87
  4901.1  433.36  4915.4  432.82  4950.6  432.99  4971.4  432.27  4979.4  432.66
  4989.9  431.20  4995.8  431.20  5001.4  429.59  5004.0  429.55  5004.5  428.75
  5009.5  428.75  5010.0  429.55  5015.4  430.99  5023.8  431.83  5029.4  431.79
  5046.2  433.08  5051.8  432.70  5057.9  433.36  5068.5  434.16  5090.9  434.32
  5113.2  435.23  5135.6  435.53  5180.3  437.35  5269.8  442.60  5328.5  444.80
#Mann=3,-1,0
  4672.9    0.05       0  5004.0    0.03       0  5010.0    0.05       0
Bank Sta=4901.1,5057.9
Exp/Cntr=0.3,0.1

Type RM Length L Ch R = 1,10155,348,348,348
BEGIN DESCRIPTION:
UNT 187 in LFCCL Watershed 12.0
END DESCRIPTION:
XS GIS Cut Line= 3
      2806074.97      7037175.00      2805779.41      7037191.04
      2805574.53      7037406.34
#Sta/Elev= 30
  4750.6  446.16  4780.6  446.29  4800.6  446.03  4820.7  445.43  4870.8  442.62
  4890.8  441.33  4930.8  438.16  4950.9  435.98  4970.9  434.27  4984.0  431.94
  4990.9  430.81  4997.9  429.28  4998.4  428.48  5003.4  428.48  5003.9  429.28
  5011.0  429.78  5021.0  431.42  5041.0  430.65  5080.7  430.49  5092.3  431.94
  5102.1  432.36  5116.2  432.51  5158.7  432.36  5215.3  432.69  5236.4  433.36
  5264.7  433.83  5293.0  434.80  5307.1  435.67  5321.3  435.89  5343.8  436.75
#Mann=3,-1,0
  4750.6    0.05       0  4997.9    0.03       0  5003.9    0.05       0
Bank Sta=4984,5092.3
Exp/Cntr=0.3,0.1

Type RM Length L Ch R = 1,9807,191,191,191
BEGIN DESCRIPTION:
XS4163A
END DESCRIPTION:
XS GIS Cut Line= 3
      2806046.76      7037076.46      2805661.35      7036982.71
      2805453.06      7036968.82
#Sta/Elev= 30
  4561.0  444.53  4604.0  442.11  4624.6  441.70  4635.3  440.58  4755.4  432.98
  4797.1  431.55  4830.4  430.86  4885.7  430.96  4891.0  430.65  4902.4  429.99
  4922.3  430.17  4927.5  429.78  4943.6  430.14  4984.1  429.39  4993.7  427.03
  4998.7  428.04  5001.1  426.46  5001.6  425.66  5006.6  425.66  5007.1  426.46
  5014.1  427.17  5024.1  429.36  5035.7  430.65  5054.2  433.18  5074.3  434.67
  5094.3  435.78  5134.4  437.00  5149.1  438.04  5154.4  439.54  5166.4  439.35
#Mann=3,-1,0
  4561.0    0.05       0  5001.1    0.03       0  5007.1    0.05       0
Bank Sta=4891,5035.7
Exp/Cntr=0.3,0.1

Type RM Length L Ch R = 1,9616,343,343,343
BEGIN DESCRIPTION:
XS4164A
END DESCRIPTION:
XS GIS Cut Line= 3
      2805932.18      7036833.40      2805643.99      7036809.10
      2805452.99      7036826.46
#Sta/Elev= 30
  4721.0  433.69  4728.2  432.99  4738.2  432.51  4757.4  431.96  4798.5  431.88
  4877.1  430.12  4898.8  430.21  4918.9  429.79  4959.0  430.09  4968.0  429.14
  4989.1  427.07  4998.8  425.13  4999.3  424.33  5004.3  424.33  5004.8  425.13
  5007.2  427.77  5012.2  427.77  5017.2  428.61  5022.3  429.14  5039.3  430.70
  5049.4  432.19  5069.4  434.36  5089.5  435.52  5127.7  438.35  5132.7  438.27
  5169.9  440.56  5179.9  440.94  5189.9  440.70  5198.5  439.89  5202.0  439.89
#Mann=3,-1,0
  4721.0    0.05       0  4998.8    0.03       0  5004.8    0.05       0
Bank Sta=4968,5022.3
Exp/Cntr=0.3,0.1

Type RM Length L Ch R = 1,9273,411,411,411
BEGIN DESCRIPTION:
UNT 187 in LFCCL Watershed 10.0
END DESCRIPTION:
XS GIS Cut Line= 3
      2806124.99      7036675.00      2805725.00      7036525.00
      2805425.03      7036475.00
#Sta/Elev= 30
  4525.9  443.68  4571.3  441.66  4621.1  438.25  4626.5  438.73  4750.2  430.81
  4872.6  427.53  4907.7  425.54  4921.0  426.44  4931.7  424.86  4938.0  425.95
  4943.3  425.33  4950.4  427.09  4981.0  427.20  4986.0  426.85  4993.6  424.20
  5000.8  423.09  5001.3  422.29  5006.3  422.29  5006.8  423.09  5013.9  426.18
  5026.4  427.53  5054.5  431.38  5102.6  435.23  5115.3  434.44  5168.5  436.43
  5216.7  439.16  5224.3  440.85  5229.8  441.10  5237.0  442.31  5257.2  442.56
#Mann=4,-1,0
  4525.9    0.05       0  5000.8    0.03       0  5006.8    0.05       0
  5229.8    0.08       0
Bank Sta=4872.6,5026.4
Exp/Cntr=0.3,0.1