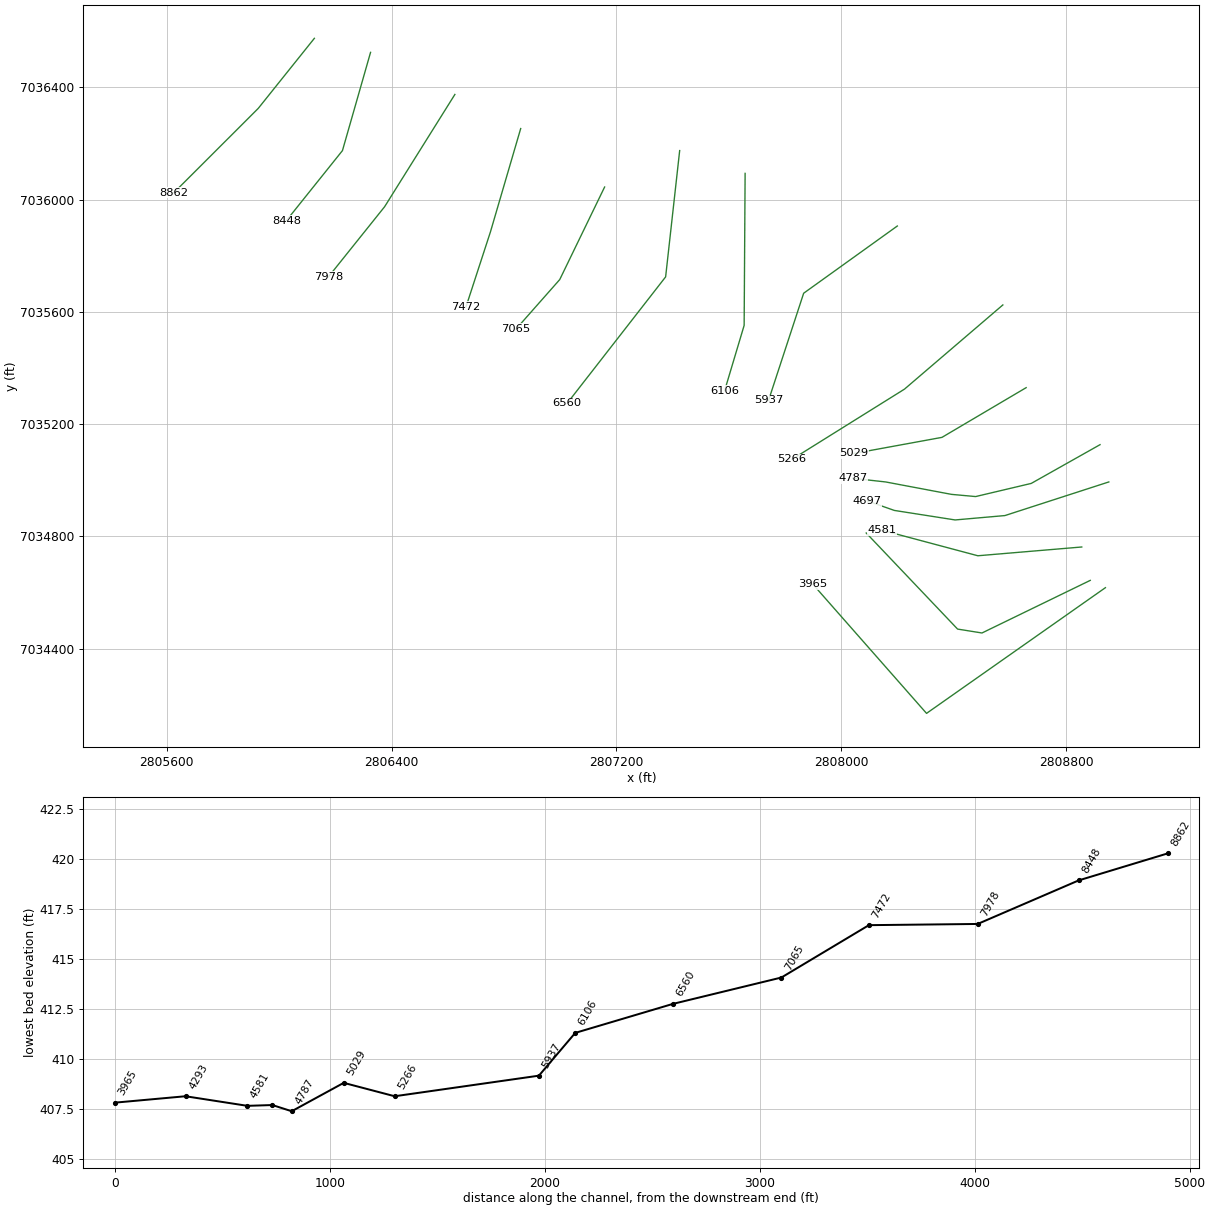
HEC-RAS study UNT 187 in LFCCL Watershed.prj: UNT 187 in LFCCL Watershed Base Level Engineering

--- UNT 187 in LFCCL Watershed.g01 (geometry) --- (continued)

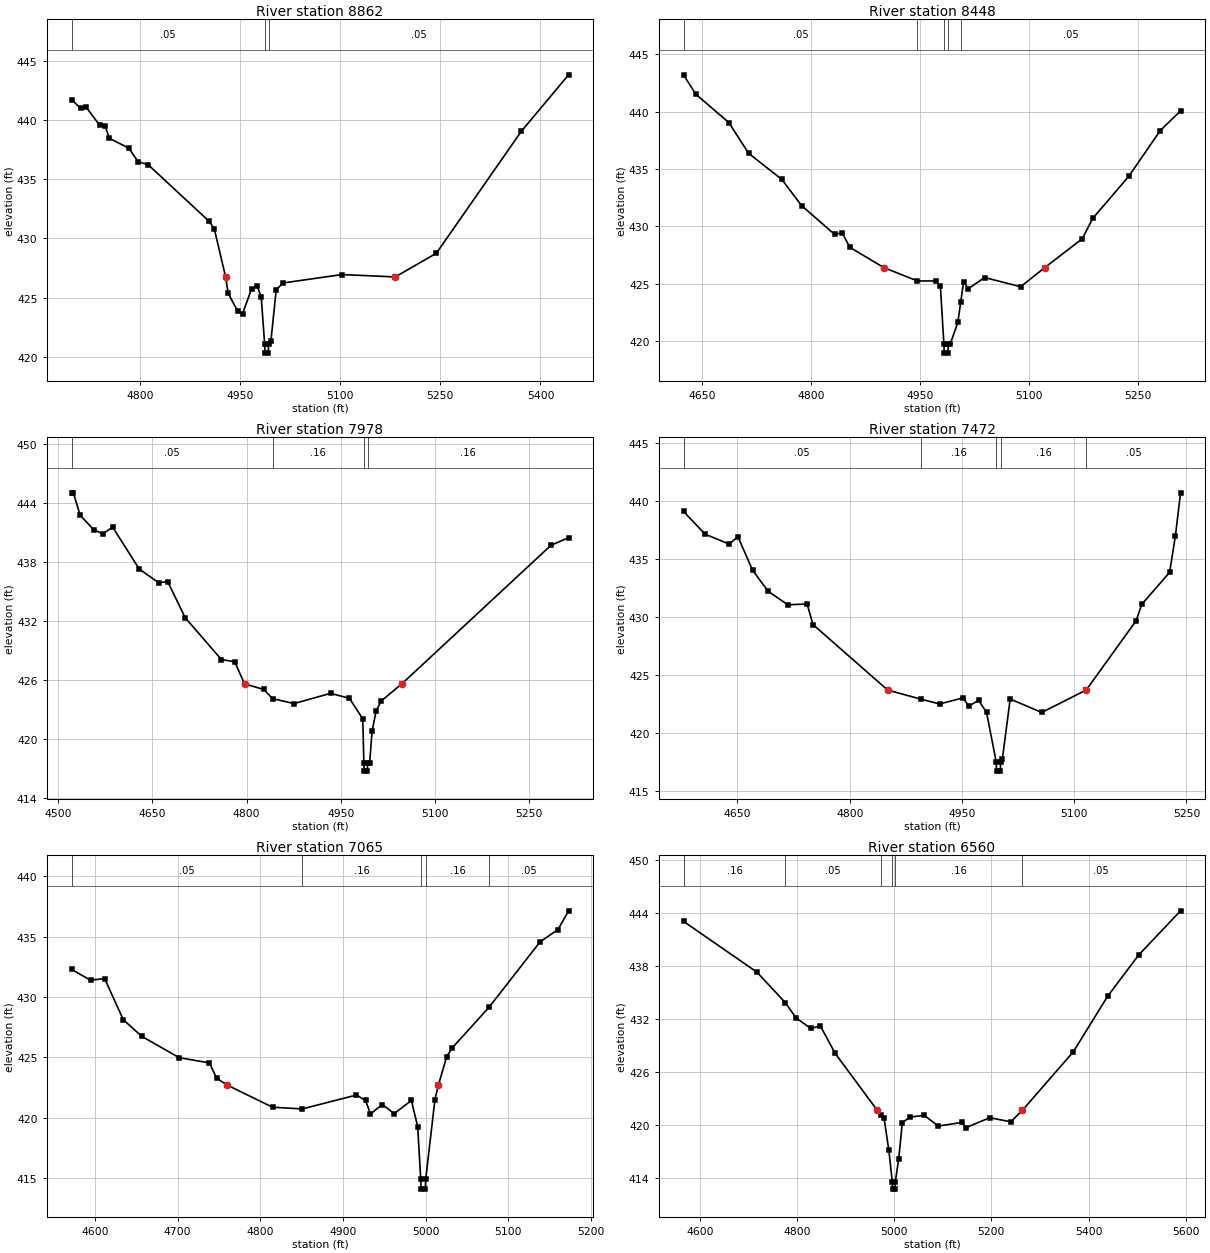
Type RM Length L Ch R = 1,8862,414,414,414
BEGIN DESCRIPTION:
UNT 187 in LFCCL Watershed 9.0
END DESCRIPTION:
XS GIS Cut Line= 3
      2806125.00      7036575.01      2805925.00      7036325.00
      2805625.02      7036025.02
#Sta/Elev= 30
  4697.7  441.73  4711.3  440.99  4719.3  441.11  4740.1  439.54  4748.1  439.46
  4754.5  438.45  4783.3  437.63  4797.8  436.46  4812.2  436.24  4903.4  431.46
  4911.4  430.83  4928.5  426.74  4932.2  425.37  4946.6  423.84  4953.8  423.62
  4967.4  425.74  4975.4  425.99  4981.8  425.06  4986.9  421.10  4987.4  420.30
  4992.4  420.30  4992.9  421.10  4996.3  421.31  5004.3  425.67  5014.7  426.23
  5102.7  426.94  5182.5  426.74  5244.1  428.74  5371.4  439.05  5442.1  443.82
#Mann=3,-1,0
  4697.7    0.05       0  4986.9    0.03       0  4992.9    0.05       0
Bank Sta=4928.5,5182.5
Exp/Cntr=0.3,0.1

Type RM Length L Ch R = 1,8448,470,470,470
BEGIN DESCRIPTION:
UNT 187 in LFCCL Watershed 8.0
END DESCRIPTION:
XS GIS Cut Line= 3
      2806325.00      7036525.01      2806225.00      7036175.00
      2806024.98      7035924.97
#Sta/Elev= 30
  4624.0  443.21  4640.9  441.52  4686.4  439.05  4713.7  436.36  4759.2  434.10
  4786.5  431.81  4832.0  429.30  4842.4  429.44  4852.8  428.18  4899.6  426.41
  4946.0  425.24  4971.1  425.24  4977.6  424.78  4982.4  419.75  4982.9  418.95
  4987.9  418.95  4988.4  419.75  4991.2  419.75  5001.6  421.63  5005.7  423.45
  5009.6  425.18  5016.0  424.56  5038.4  425.54  5088.1  424.74  5121.4  426.41
  5172.9  428.92  5187.3  430.70  5236.9  434.36  5280.2  438.35  5308.2  440.07
#Mann=5,-1,0
  4624.0    0.05       0  4946.0    0.07       0  4982.4    0.07       0
  4988.4    0.07       0  5005.7    0.05       0
Bank Sta=4899.6,5121.4
Exp/Cntr=0.3,0.1

Type RM Length L Ch R = 1,7978,506,506,506
BEGIN DESCRIPTION:
UNT 187 in LFCCL Watershed 7.0
END DESCRIPTION:
XS GIS Cut Line= 3
      2806625.01      7036375.01      2806375.00      7035975.00
      2806174.98      7035724.97
#Sta/Elev= 30
  4521.0  445.00  4524.0  445.00  4534.6  442.74  4556.4  441.25  4571.1  440.85
  4586.5  441.52  4628.9  437.27  4659.6  435.89  4674.3  435.99  4702.0  432.34
  4759.8  428.09  4781.0  427.86  4796.6  425.62  4827.0  425.06  4841.6  424.12
  4875.4  423.62  4933.7  424.66  4963.8  424.16  4985.0  422.07  4986.8  417.57
  4987.3  416.77  4992.3  416.77  4992.8  417.57  4995.9  417.57  4999.9  420.84
  5006.3  422.86  5014.3  423.88  5047.2  425.62  5284.9  439.68  5312.9  440.45
#Mann=4,-1,0
  4521.0    0.05       0  4841.6    0.16       0  4986.8    0.07       0
  4992.8    0.16       0
Bank Sta=4796.6,5047.2
Exp/Cntr=0.3,0.1

Type RM Length L Ch R = 1,7472,407,407,407
BEGIN DESCRIPTION:
UNT 187 in LFCCL Watershed 6.0
END DESCRIPTION:
XS GIS Cut Line= 3
      2806859.28      7036253.57      2806751.63      7035885.49
      2806664.69      7035618.48
#Sta/Elev= 30
  4577.9  439.07  4606.7  437.11  4638.9  436.26  4650.6  436.89  4670.2  434.01
  4691.0  432.19  4717.4  431.03  4743.1  431.10  4750.9  429.33  4850.7  423.69
  4895.0  422.91  4920.2  422.49  4951.5  423.02  4959.0  422.31  4972.4  422.80
  4982.9  421.76  4995.8  417.51  4996.3  416.71  5001.3  416.71  5001.8  417.51
  5004.1  417.79  5014.5  422.92  5056.6  421.76  5116.0  423.69  5116.2  423.70
  5182.8  429.66  5190.4  431.07  5227.6  433.83  5235.3  436.97  5242.2  440.67
#Mann=5,-1,0
  4577.9    0.05       0  4895.0    0.16       0  4995.8    0.07       0
  5001.8    0.16       0  5116.2    0.05       0
Bank Sta=4850.7,5116
Exp/Cntr=0.3,0.1

Type RM Length L Ch R = 1,7065,505,505,505
BEGIN DESCRIPTION:
XS4165A
END DESCRIPTION:
XS GIS Cut Line= 3
      2807157.88      7036045.21      2806998.16      7035715.35
      2806842.68      7035539.13
#Sta/Elev= 30
  4571.6  432.28  4594.6  431.39  4611.7  431.52  4634.3  428.11  4656.8  426.73
  4702.0  424.97  4738.5  424.54  4747.2  423.27  4759.8  422.71  4814.9  420.87
  4850.8  420.73  4916.4  421.88  4927.4  421.43  4933.4  420.32  4947.8  421.09
  4962.1  420.34  4982.9  421.43  4990.5  419.27  4994.2  414.89  4994.7  414.09
  4999.7  414.09  5000.2  414.89  5011.4  421.51  5015.6  422.71  5025.6  425.06
  5032.3  425.78  5076.9  429.15  5138.6  434.56  5160.3  435.58  5173.1  437.13
#Mann=5,-1,0
  4571.6    0.05       0  4850.8    0.16       0  4994.2    0.07       0
  5000.2    0.16       0  5076.9    0.05       0
Bank Sta=4759.8,5015.6
Exp/Cntr=0.3,0.1

Type RM Length L Ch R = 1,6560,454,454,454
BEGIN DESCRIPTION:
UNT 187 in LFCCL Watershed 4.0
END DESCRIPTION:
XS GIS Cut Line= 3
      2807425.00      7036175.04      2807375.00      7035725.00
      2807025.00      7035275.00
#Sta/Elev= 30
  4566.5  443.04  4717.5  437.30  4775.9  433.86  4798.0  432.13  4828.1  430.95
  4848.3  431.20  4878.5  428.12  4965.4  421.66  4973.3  421.11  4979.1  420.83
  4989.1  417.14  4996.2  413.57  4996.7  412.77  5001.7  412.77  5002.2  413.57
  5009.3  416.15  5016.8  420.29  5032.9  420.92  5061.8  421.11  5090.8  419.90
  5140.6  420.32  5146.9  419.70  5196.7  420.84  5240.1  420.38  5262.3  421.60
  5263.7  421.67  5368.6  428.29  5439.2  434.56  5503.4  439.25  5589.4  444.23
#Mann=6,-1,0
  4566.5    0.16       0  4775.9    0.05       0  4973.3    0.16       0
  4996.2    0.07       0  5002.2    0.16       0  5262.3    0.05       0
Bank Sta=4965.4,5263.7
Exp/Cntr=0.3,0.1

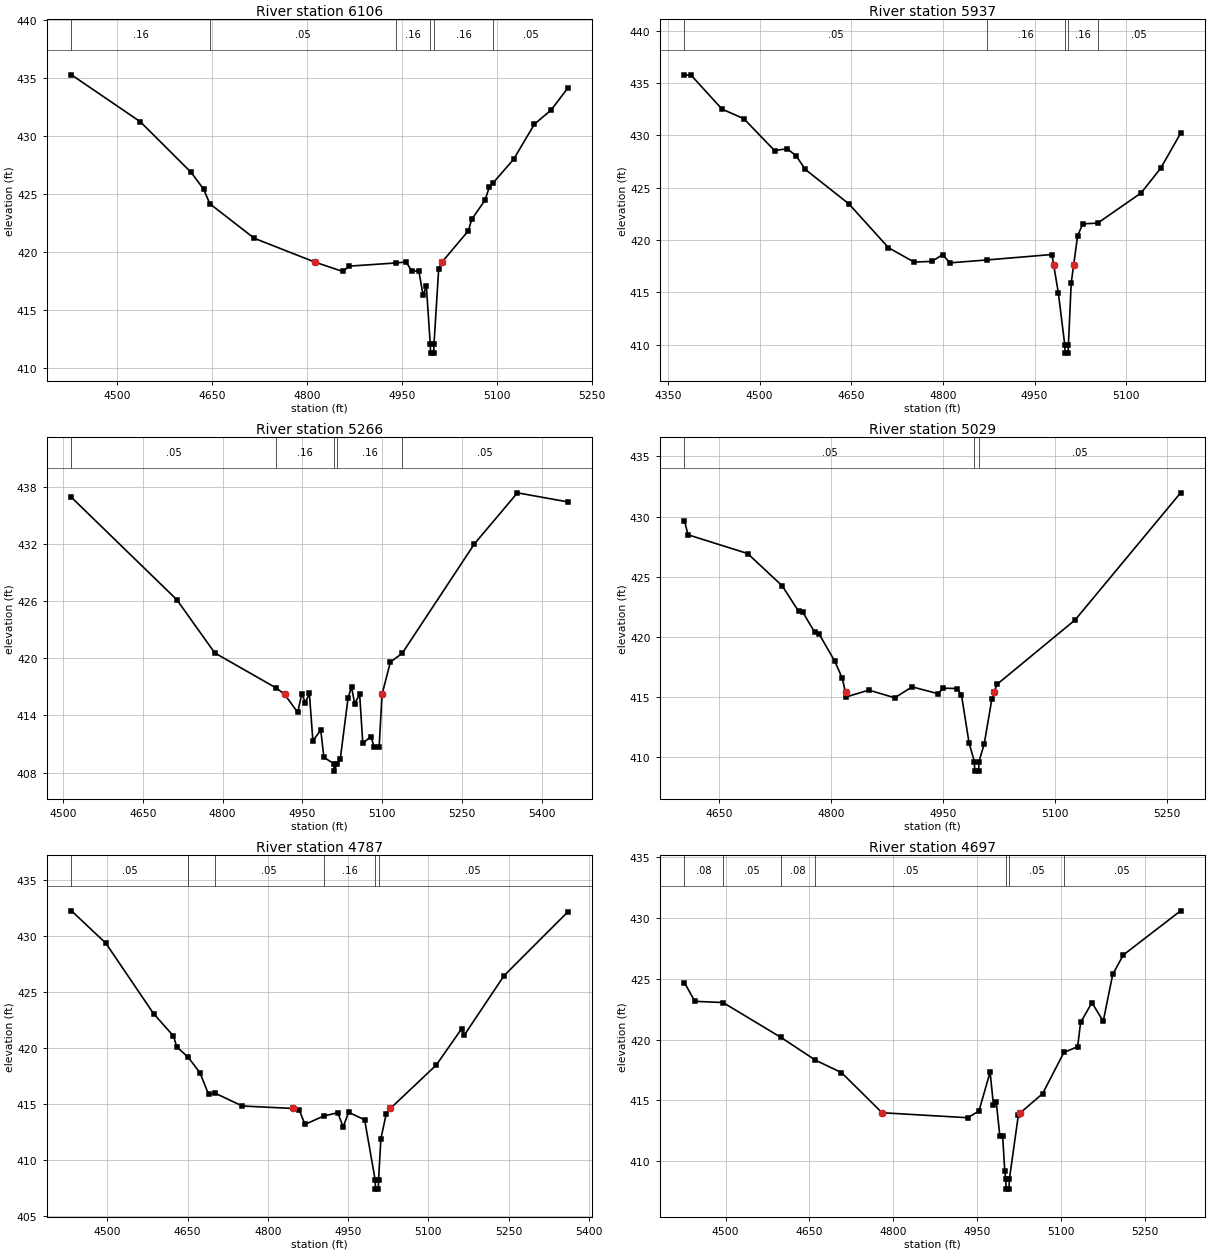
Type RM Length L Ch R = 1,6106,169,169,169
BEGIN DESCRIPTION:
XS4166A
END DESCRIPTION:
XS GIS Cut Line= 3
      2807657.88      7036093.81      2807654.41      7035552.15
      2807585.03      7035319.75
#Sta/Elev= 30
  4427.7  435.28  4536.5  431.24  4616.5  426.90  4636.5  425.44  4646.4  424.18
  4716.5  421.21  4813.2  419.14  4856.5  418.35  4866.5  418.81  4940.0  419.08
  4956.5  419.17  4965.4  418.40  4976.8  418.38  4983.4  416.29  4988.6  417.09
  4994.7  412.12  4995.2  411.32  5000.2  411.32  5000.7  412.12  5008.1  418.60
  5013.0  419.14  5054.9  421.85  5060.3  422.84  5081.2  424.48  5088.0  425.59
  5094.4  426.00  5126.4  428.00  5159.5  431.04  5185.6  432.24  5211.9  434.12
#Mann=6,-1,0
  4427.7    0.16       0  4646.4    0.05       0  4940.0    0.16       0
  4994.7    0.07       0  5000.7    0.16       0  5094.4    0.05       0
Bank Sta=4813.2,5013
Exp/Cntr=0.3,0.1

Type RM Length L Ch R = 1,5937,671,671,671
BEGIN DESCRIPTION:
XS4167A
END DESCRIPTION:
XS GIS Cut Line= 3
      2808199.52      7035906.30      2807866.21      7035666.74
      2807741.20      7035284.75
#Sta/Elev= 30
  4376.8  435.79  4388.1  435.73  4438.4  432.51  4474.0  431.60  4524.3  428.55
  4545.2  428.72  4559.9  428.03  4574.7  426.74  4645.9  423.46  4710.9  419.26
  4752.7  417.89  4782.1  417.95  4799.6  418.60  4811.3  417.81  4872.3  418.09
  4978.5  418.61  4981.5  417.57  4989.0  414.95  4999.5  409.98  5000.0  409.18
  5005.0  409.18  5005.5  409.98  5010.1  415.90  5014.0  417.57  5020.6  420.41
  5029.1  421.54  5053.4  421.61  5124.6  424.50  5156.5  426.85  5189.2  430.20
#Mann=5,-1,0
  4376.8    0.05       0  4872.3    0.16       0  4999.5    0.07       0
  5005.5    0.16       0  5053.4    0.05       0
Bank Sta=4981.5,5014
Exp/Cntr=0.3,0.1

Type RM Length L Ch R = 1,5266,237,237,237
BEGIN DESCRIPTION:
UNT 187 in LFCCL Watershed 2.0
END DESCRIPTION:
XS GIS Cut Line= 3
      2808574.99      7035624.99      2808225.00      7035325.00
      2807824.97      7035074.98
#Sta/Elev= 30
  4515.8  436.87  4713.9  426.13  4785.2  420.55  4900.7  416.87  4916.4  416.21
  4941.1  414.31  4948.8  416.29  4955.4  415.34  4963.0  416.30  4969.6  411.34
  4984.4  412.45  4990.3  409.58  5009.0  408.95  5009.5  408.15  5015.2  408.95
  5021.0  409.39  5035.7  415.81  5042.2  417.01  5048.1  415.23  5057.5  416.21
  5063.4  411.09  5078.8  411.77  5084.7  410.69  5094.1  410.67  5099.6  416.21
  5115.3  419.59  5137.6  420.52  5273.3  432.00  5354.1  437.35  5448.5  436.40
#Mann=5,-1,0
  4515.8    0.05       0  4900.7    0.16       0  5009.0    0.07       0
  5015.2    0.16       0  5137.6    0.05       0
Bank Sta=4916.4,5099.6
Exp/Cntr=0.3,0.1

Type RM Length L Ch R = 1,5029,242,242,242
BEGIN DESCRIPTION:
XS4172A
END DESCRIPTION:
XS GIS Cut Line= 3
      2808657.91      7035330.24      2808358.40      7035153.14
      2808045.87      7035095.84
#Sta/Elev= 30
  4603.1  429.66  4607.9  428.48  4687.9  426.92  4734.3  424.23  4756.2  422.12
  4762.0  422.03  4777.7  420.39  4783.5  420.26  4804.9  417.95  4814.7  416.57
  4819.2  415.37  4820.5  415.00  4850.5  415.56  4885.3  414.92  4908.5  415.83
  4943.4  415.26  4950.1  415.72  4969.1  415.69  4974.8  415.16  4985.0  411.16
  4992.1  409.62  4992.6  408.82  4997.8  408.82  4998.3  409.62  5005.3  411.08
  5015.5  414.79  5018.7  415.37  5022.3  416.03  5127.3  421.40  5268.8  431.97
#Mann=3,-1,0
  4603.1    0.05       0  4992.1    0.03       0  4998.3    0.05       0
Bank Sta=4819.2,5018.7
Exp/Cntr=0.3,0.1

Type RM Length L Ch R = 1,4787,90,90,90
BEGIN DESCRIPTION:
XS4171A
END DESCRIPTION:
XS GIS Cut Line= 6
      2808920.88      7035127.08      2808676.11      7034989.07
      2808478.19      7034942.20      2808392.26      7034950.01
      2808157.88      7034994.28      2808040.70      7035007.30
#Sta/Elev= 30
  4433.2  432.21  4497.3  429.33  4586.8  423.03  4623.6  421.06  4630.1  420.07
  4651.4  419.15  4673.4  417.76  4689.4  415.84  4700.7  415.97  4752.4  414.81
  4847.5  414.59  4859.2  414.41  4869.5  413.17  4904.5  413.92  4930.8  414.21
  4940.9  412.94  4950.9  414.25  4981.0  413.58  5000.7  408.20  5001.2  407.40
  5006.5  407.40  5007.0  408.20  5011.3  411.89  5021.4  414.12  5029.0  414.59
  5114.8  418.46  5162.1  421.69  5167.2  421.13  5241.3  426.42  5360.3  432.10
#Mann=6,-1,0
  4433.2    0.05       0  4651.4    0.08       0  4700.7    0.05       0
  4904.5    0.16       0  5000.7    0.07       0  5007.0    0.05       0
Bank Sta=4847.5,5029
Exp/Cntr=0.3,0.1

Type RM Length L Ch R = 1,4697,116,116,116
BEGIN DESCRIPTION:
XS4170A
END DESCRIPTION:
XS GIS Cut Line= 5
      2808952.20      7034994.30      2808582.36      7034874.49
      2808405.28      7034858.87      2808189.13      7034892.72
      2808092.81      7034926.56
#Sta/Elev= 30
  4426.5  424.69  4445.1  423.15  4495.6  423.05  4598.9  420.19  4660.9  418.31
  4707.4  417.29  4780.0  413.99  4933.1  413.58  4953.2  414.13  4973.2  417.33
  4979.2  414.62  4984.2  414.87  4990.7  412.04  4995.7  412.04  4999.4  409.18
  5001.3  408.51  5001.8  407.71  5007.1  407.71  5007.6  408.51  5023.7  413.79
  5027.4  413.99  5067.1  415.56  5105.2  418.95  5129.8  419.42  5135.0  421.41
  5155.3  423.04  5175.5  421.51  5192.5  425.37  5211.4  426.96  5313.9  430.59
#Mann=7,-1,0
  4426.5    0.08       0  4495.6    0.05       0  4598.9    0.08       0
  4660.9    0.05       0  5001.3    0.04       0  5007.6    0.05       0
  5105.2    0.05       0
Bank Sta=4780,5027.4
Exp/Cntr=0.3,0.1

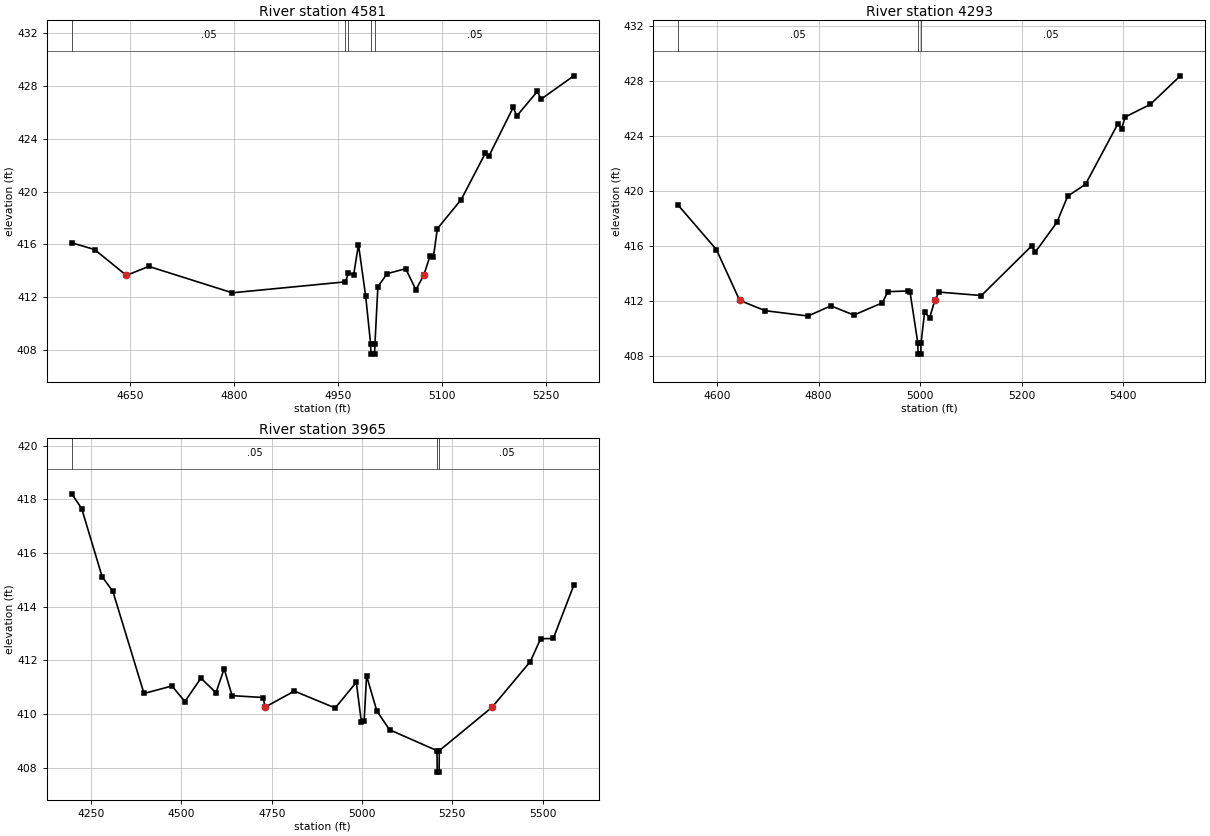
Type RM Length L Ch R = 1,4581,288,288,288
BEGIN DESCRIPTION:
XS4169A
END DESCRIPTION:
XS GIS Cut Line= 3
      2808855.83      7034762.51      2808486.01      7034731.26
      2808144.81      7034822.42
#Sta/Elev= 30
  4565.9  416.11  4598.8  415.60  4644.7  413.64  4677.1  414.32  4797.5  412.32
  4960.7  413.15  4965.1  413.83  4972.6  413.69  4979.5  415.98  4989.8  412.10
  4997.0  408.47  4997.5  407.67  5002.8  407.67  5003.3  408.47  5007.5  412.79
  5020.9  413.77  5047.6  414.15  5062.3  412.55  5073.6  413.64  5082.5  415.08
  5087.6  415.04  5093.3  417.18  5127.7  419.39  5162.6  422.91  5167.8  422.70
  5202.7  426.37  5207.9  425.73  5237.6  427.59  5242.8  427.00  5290.2  428.77
#Mann=5,-1,0
  4565.9    0.05       0  4960.7    0.16       0  4965.1    0.05       0
  4997.0    0.03       0  5003.3    0.05       0
Bank Sta=4644.7,5073.6
Exp/Cntr=0.3,0.1

Type RM Length L Ch R = 1,4293,328,328,328
BEGIN DESCRIPTION:
XS4168A
END DESCRIPTION:
XS GIS Cut Line= 4
      2808886.16      7034643.58      2808500.76      7034456.09
      2808413.96      7034469.98      2808088.81      7034812.42
#Sta/Elev= 30
  4523.5  418.97  4598.7  415.75  4644.4  412.06  4694.4  411.31  4779.1  410.92
  4824.2  411.66  4869.3  410.99  4925.5  411.88  4936.2  412.69  4975.0  412.74
  4980.0  412.66  4995.3  408.95  4995.8  408.15  5001.1  408.15  5001.6  408.95
  5008.6  411.18  5018.7  410.81  5028.8  412.06  5036.9  412.66  5120.6  412.41
  5219.6  416.02  5226.5  415.56  5269.0  417.72  5290.4  419.63  5325.6  420.50
  5389.5  424.91  5396.4  424.52  5403.7  425.39  5453.0  426.30  5512.2  428.38
#Mann=3,-1,0
  4523.5    0.05       0  4995.3    0.03       0  5001.6    0.05       0
Bank Sta=4644.4,5028.8
Exp/Cntr=0.3,0.1

Type RM Length L Ch R = 1,3965,0,0,0
BEGIN DESCRIPTION:
UNT 187 in LFCCL Watershed 1.0
END DESCRIPTION:
XS GIS Cut Line= 3
      2808940.02      7034617.56      2808303.47      7034169.62
      2807899.42      7034629.33
#Sta/Elev= 30
  4196.3  418.20  4223.8  417.65  4280.4  415.11  4310.0  414.57  4396.3  410.76
  4473.8  411.04  4509.5  410.46  4553.9  411.33  4595.8  410.79  4618.2  411.68
  4640.2  410.68  4726.4  410.61  4731.3  410.25  4812.7  410.85  4925.9  410.22
  4984.2  411.18  4998.4  409.69  5006.0  409.74  5012.7  411.42  5041.1  410.11
  5076.2  409.41  5207.8  408.63  5208.3  407.83  5213.6  407.83  5214.1  408.63
  5360.4  410.25  5466.2  411.95  5494.7  412.80  5529.8  412.81  5586.7  414.80
#Mann=3,-1,0
  4196.3    0.05       0  5207.8    0.03       0  5214.1    0.05       0
Bank Sta=4731.3,5360.4
Exp/Cntr=0.3,0.1

Chan Stop Cuts=-1