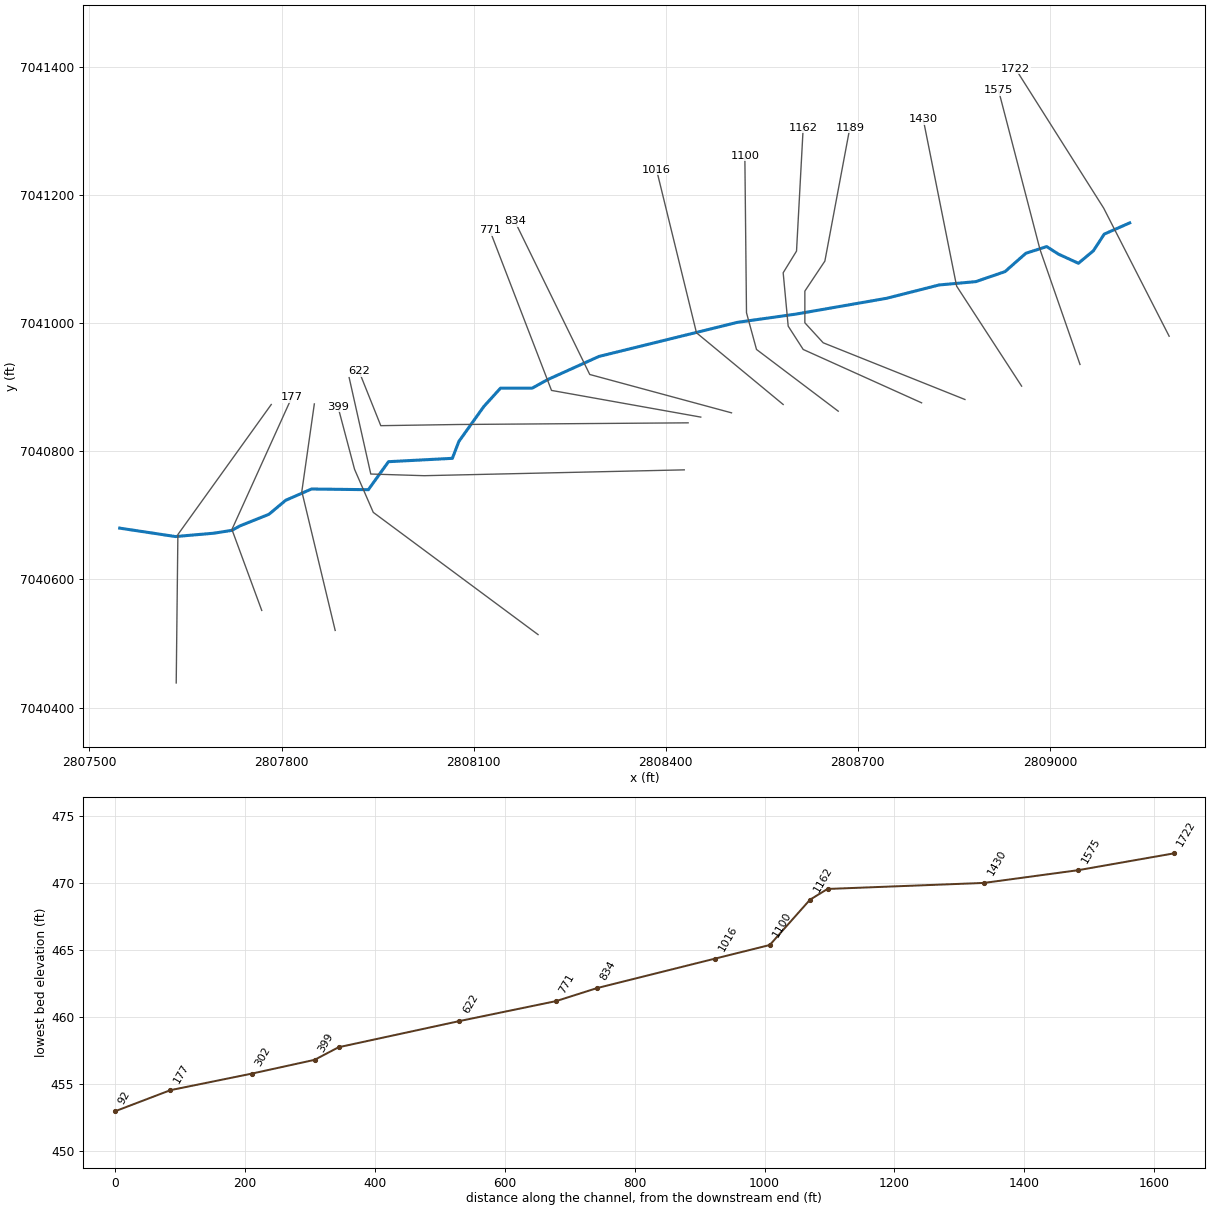
--- UNT 188 in LFCCL Watershed.prj (project) ---

Proj Title=UNT 188 in LFCCL Watershed Base Level Engineering
Current Plan=p01
Default Exp/Contr=0.3,0.1
English Units
Geom File=g01
Flow File=f01
Plan File=p01
BEGIN DESCRIPTION:
UNT 188 in LFCCL Watershed
END DESCRIPTION:

--- UNT 188 in LFCCL Watershed.p01 (plan) ---

Plan Title=Multiple Run
Short Identifier=Multiple
Geom File=g01
Flow File=f01
Subcritical Flow
K Sum by GR= 0
Std Step Tol= 0.01
Critical Tol= 0.01
Num of Std Step Trials= 20
Max Error Tol= 0.3
Flow Tol Ratio= 0.001
Split Flow NTrial= 30
Split Flow Tol= 0.02
Split Flow Ratio= 0.02
Log Output Level= 0
Friction Slope Method= 1
Unsteady Friction Slope Method= 2
Unsteady Bridges Friction Slope Method= 1
Parabolic Critical Depth
Global Vel Dist=  1 , 1 , 1
Global Log Level= 0
CheckData=True
Encroach Param= -1, 0, 0, 0
BEGIN DESCRIPTION:
Multiple Run
END DESCRIPTION:

--- UNT 188 in LFCCL Watershed.f01 (steady flow) ---

Flow Title=Multiple
Number of Profiles=7
Profile Names=10-year,25-year,50-year,1pct_min,100-year,1pct_plu,500-year
River Rch & RM= UNT 188 in LFCCL,Reach-1,1722
      77      89      97      54     107     213     128
Boundary for River Rch & Prof#=UNT 188 in LFCCL,Reach-1,1
Up Type=0
Dn Type=3
Dn Slope=0.005
Boundary for River Rch & Prof#=UNT 188 in LFCCL,Reach-1,2
Up Type=0
Dn Type=3
Dn Slope=0.005
Boundary for River Rch & Prof#=UNT 188 in LFCCL,Reach-1,3
Up Type=0
Dn Type=3
Dn Slope=0.005
Boundary for River Rch & Prof#=UNT 188 in LFCCL,Reach-1,4
Up Type=0
Dn Type=3
Dn Slope=0.005
Boundary for River Rch & Prof#=UNT 188 in LFCCL,Reach-1,5
Up Type=0
Dn Type=3
Dn Slope=0.005
Boundary for River Rch & Prof#=UNT 188 in LFCCL,Reach-1,6
Up Type=0
Dn Type=3
Dn Slope=0.005
Boundary for River Rch & Prof#=UNT 188 in LFCCL,Reach-1,7
Up Type=0
Dn Type=3
Dn Slope=0.005

--- UNT 188 in LFCCL Watershed.g01 (geometry) ---

Geom Title=Existing Conditions

River Reach=UNT 188 in LFCCL,Reach-1
Reach XY= 30
      2809124.57      7041156.87      2809084.86      7041139.40
      2809067.93      7041113.36      2809044.49      7041093.82
      2809013.24      7041108.15      2808995.01      7041119.87
      2808962.46      7041109.45      2808929.91      7041080.80
      2808884.34      7041065.18      2808827.04      7041059.97
      2808745.01      7041039.14      2808603.09      7041014.40
      2808511.71      7041001.52      2808295.66      7040948.30
      2808214.93      7040911.84      2808191.49      7040898.82
      2808142.01      7040898.82      2808115.97      7040870.17
      2808076.91      7040815.48      2808066.76      7040789.18
      2807967.03      7040783.95      2807935.58      7040740.22
      2807846.84      7040741.29      2807806.45      7040723.63
      2807780.17      7040701.71      2807735.03      7040683.65
      2807722.53      7040676.71      2807694.10      7040672.25
      2807634.20      7040667.05      2807547.24      7040680.19

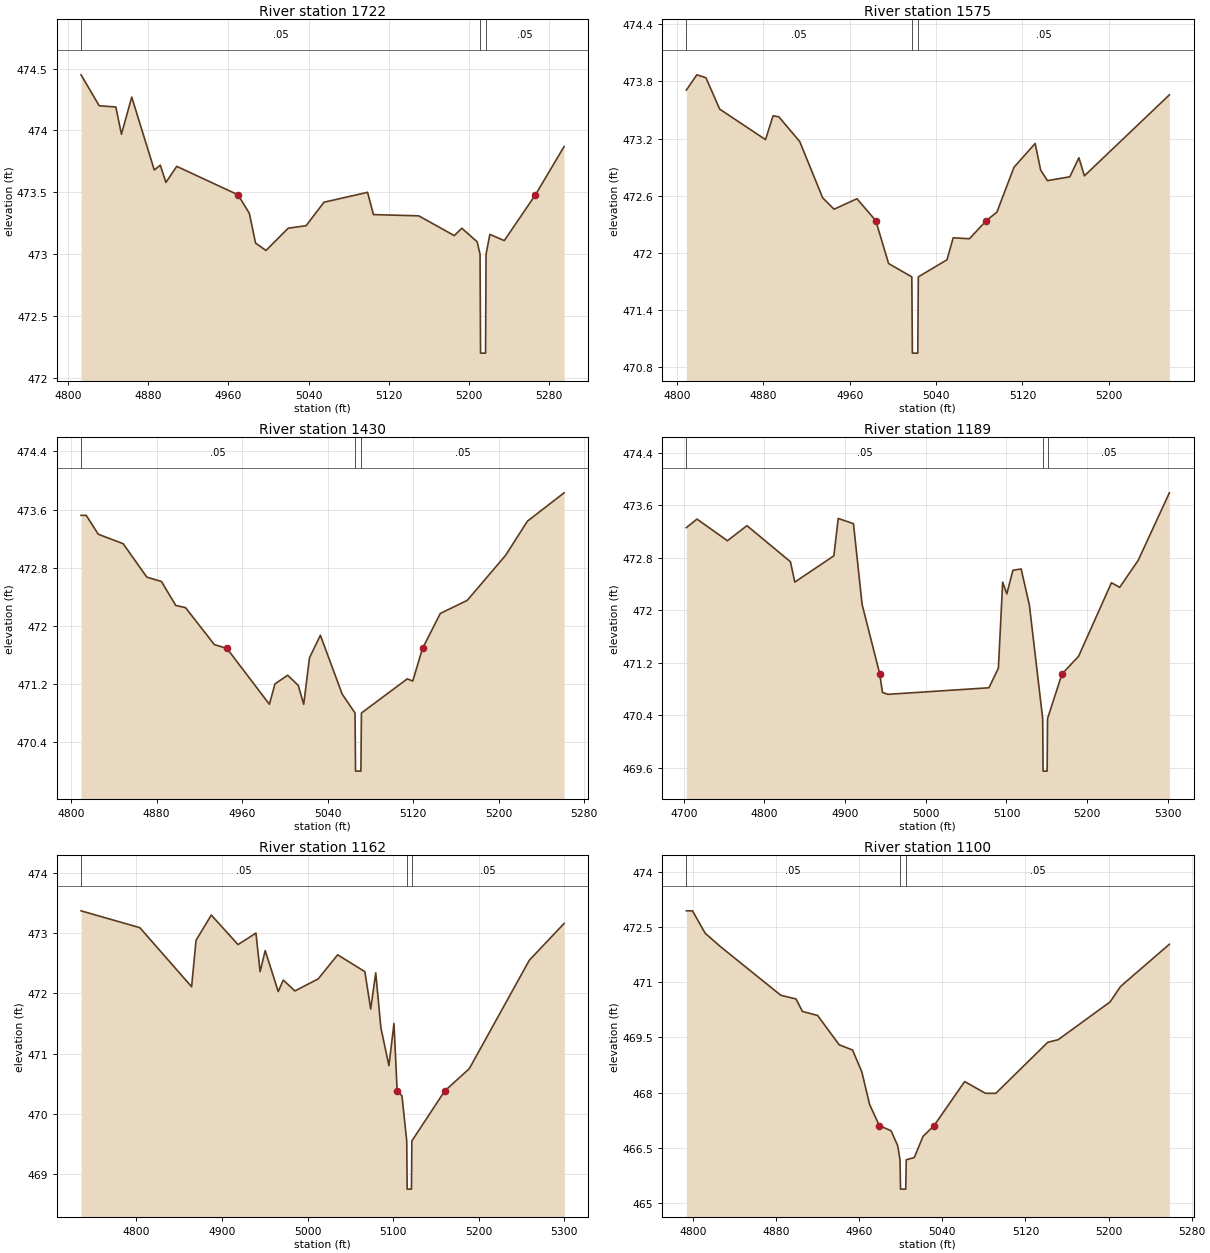
Type RM Length L Ch R = 1,1722,147,147,147
BEGIN DESCRIPTION:
XS4173A
END DESCRIPTION:
XS GIS Cut Line= 3
      2809186.20      7040979.92      2809084.00      7041179.87
      2808946.26      7041397.60
#Sta/Elev= 30
  4812.9  474.45  4831.0  474.20  4847.6  474.19  4853.2  473.97  4863.5  474.27
  4886.0  473.68  4892.0  473.72  4897.6  473.58  4908.4  473.71  4969.6  473.48
  4980.9  473.33  4987.1  473.09  4997.5  473.03  5019.7  473.21  5037.5  473.23
  5055.4  473.42  5098.9  473.50  5104.8  473.32  5150.0  473.31  5185.5  473.15
  5193.0  473.21  5208.3  473.10  5211.2  473.00  5211.7  472.20  5216.7  472.20
  5217.2  473.00  5221.0  473.16  5235.4  473.11  5266.5  473.48  5295.1  473.87
#Mann=3,-1,0
  4812.9    0.05       0  5211.2    0.03       0  5217.2    0.05       0
Bank Sta=4969.6,5266.5
Exp/Cntr=0.3,0.1

Type RM Length L Ch R = 1,1575,145,145,145
BEGIN DESCRIPTION:
XS4174A
END DESCRIPTION:
XS GIS Cut Line= 3
      2809046.97      7040935.80      2808984.47      7041115.47
      2808919.69      7041364.25
#Sta/Elev= 30
  4808.8  473.71  4818.5  473.87  4826.9  473.84  4839.7  473.51  4882.1  473.19
  4889.1  473.44  4894.4  473.43  4913.8  473.17  4935.0  472.58  4945.6  472.46
  4966.8  472.57  4984.2  472.34  4996.1  471.89  5017.6  471.75  5018.1  470.95
  5023.1  470.95  5023.6  471.75  5050.2  471.93  5055.9  472.16  5070.9  472.15
  5086.6  472.34  5096.4  472.43  5112.2  472.90  5131.8  473.15  5136.9  472.87
  5143.2  472.76  5163.9  472.80  5172.3  473.00  5177.4  472.81  5256.1  473.66
#Mann=3,-1,0
  4808.8    0.05       0  5017.6    0.03       0  5023.6    0.05       0
Bank Sta=4984.2,5086.6
Exp/Cntr=0.3,0.1

Type RM Length L Ch R = 1,1430,241,241,241
BEGIN DESCRIPTION:
XS4178A
END DESCRIPTION:
XS GIS Cut Line= 3
      2808955.81      7040901.95      2808854.27      7041058.18
      2808802.18      7041318.59
#Sta/Elev= 30
  4809.4  473.52  4814.2  473.52  4825.5  473.26  4848.8  473.13  4870.9  472.67
  4884.6  472.61  4898.0  472.28  4907.1  472.25  4934.2  471.74  4945.8  471.69
  4985.6  470.92  4990.8  471.20  5002.7  471.32  5012.6  471.18  5017.7  470.92
  5023.1  471.56  5033.3  471.87  5053.7  471.06  5065.7  470.80  5066.2  470.00
  5071.2  470.00  5071.7  470.80  5114.6  471.27  5119.7  471.24  5128.9  471.69
  5145.5  472.17  5170.7  472.35  5206.6  472.97  5227.0  473.44  5261.3  473.83
#Mann=3,-1,0
  4809.4    0.05       0  5065.7    0.03       0  5071.7    0.05       0
Bank Sta=4945.8,5128.9
Exp/Cntr=0.3,0.1

Type RM Length L Ch R = 1,1189,27,27,27
BEGIN DESCRIPTION:
XS4177A
END DESCRIPTION:
XS GIS Cut Line= 6
      2808867.26      7040881.10      2808645.93      7040969.63
      2808617.29      7041000.88      2808617.29      7041050.36
      2808648.54      7041097.24      2808687.59      7041305.54
#Sta/Elev= 30
  4703.3  473.26  4716.5  473.39  4754.2  473.06  4778.4  473.29  4832.3  472.74
  4837.7  472.43  4886.1  472.83  4891.5  473.40  4910.4  473.32  4921.1  472.09
  4943.0  471.03  4946.3  470.75  4953.1  470.72  5078.3  470.82  5090.0  471.12
  5095.3  472.43  5100.4  472.25  5108.0  472.61  5118.2  472.63  5128.4  472.08
  5144.9  470.35  5145.4  469.55  5150.4  469.55  5150.9  470.35  5168.8  471.03
  5189.4  471.30  5230.1  472.42  5240.3  472.35  5263.2  472.76  5301.9  473.79
#Mann=3,-1,0
  4703.3    0.05       0  5144.9    0.03       0  5150.9    0.05       0
Bank Sta=4943,5168.8
Exp/Cntr=0.3,0.1

Type RM Length L Ch R = 1,1162,62,62,62
BEGIN DESCRIPTION:
XS4176A
END DESCRIPTION:
XS GIS Cut Line= 6
      2808799.59      7040875.88      2808614.68      7040959.22
      2808591.24      7040995.68      2808583.43      7041079.01
      2808604.27      7041112.86      2808614.68      7041305.56
#Sta/Elev= 30
  4735.4  473.37  4804.1  473.09  4864.5  472.11  4869.7  472.88  4887.5  473.30
  4918.7  472.81  4939.7  473.00  4944.5  472.36  4950.5  472.71  4965.7  472.03
  4971.6  472.22  4985.2  472.04  5012.4  472.24  5035.1  472.64  5066.9  472.36
  5073.7  471.74  5079.6  472.34  5085.6  471.43  5095.0  470.80  5100.9  471.50
  5104.6  470.38  5110.2  470.30  5115.8  469.55  5116.3  468.75  5121.3  468.75
  5121.8  469.55  5160.2  470.38  5188.9  470.75  5259.0  472.55  5299.6  473.16
#Mann=3,-1,0
  4735.4    0.05       0  5115.8    0.03       0  5121.8    0.05       0
Bank Sta=5104.6,5160.2
Exp/Cntr=0.3,0.1

Type RM Length L Ch R = 1,1100,84,84,84
BEGIN DESCRIPTION:
XS4175A
END DESCRIPTION:
XS GIS Cut Line= 4
      2808669.39      7040862.85      2808541.77      7040959.22
      2808526.14      7041016.51      2808523.56      7041261.99
#Sta/Elev= 30
  4793.7  472.95  4799.6  472.95  4811.8  472.34  4826.3  471.98  4884.6  470.65
  4899.2  470.55  4905.4  470.21  4920.0  470.10  4940.8  469.30  4953.6  469.16
  4962.6  468.56  4970.0  467.68  4979.4  467.10  4990.7  466.96  4997.1  466.55
  4999.3  466.17  4999.8  465.37  5004.8  465.37  5005.3  466.17  5013.0  466.23
  5021.5  466.81  5032.1  467.10  5061.5  468.30  5081.5  467.98  5091.5  467.98
  5141.5  469.37  5151.5  469.44  5201.5  470.47  5211.5  470.89  5258.5  472.04
#Mann=3,-1,0
  4793.7    0.05       0  4999.3    0.03       0  5005.3    0.05       0
Bank Sta=4979.4,5032.1
Exp/Cntr=0.3,0.1

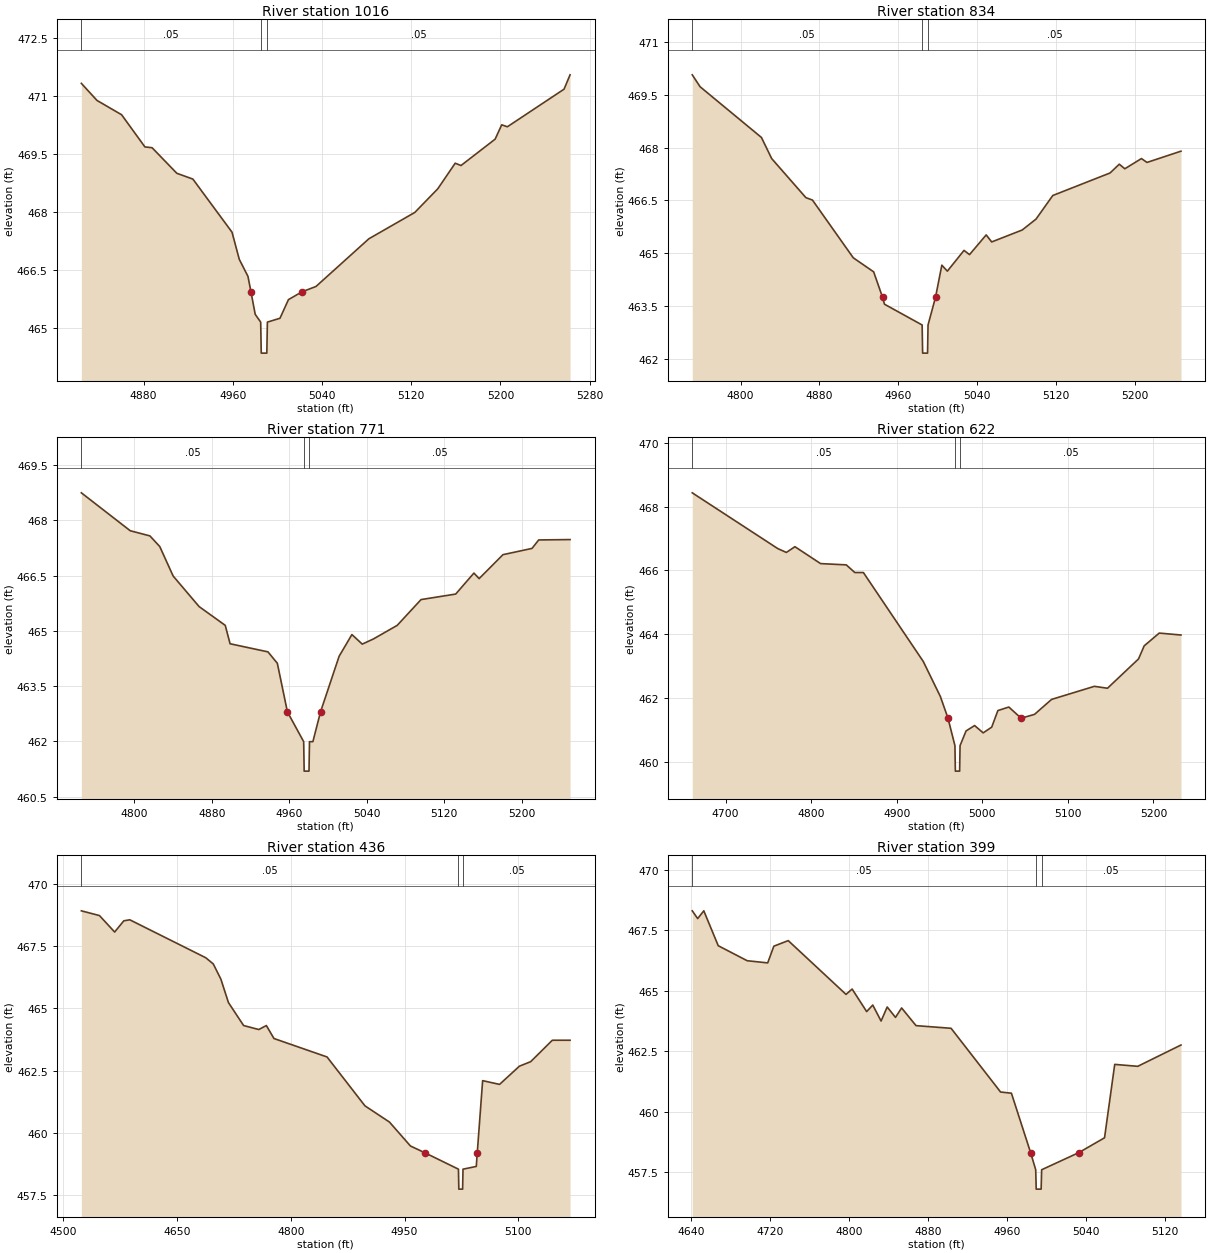
Type RM Length L Ch R = 1,1016,182,182,182
BEGIN DESCRIPTION:
XS4181A
END DESCRIPTION:
XS GIS Cut Line= 3
      2808583.41      7040873.30      2808448.02      7040985.26
      2808385.57      7041240.24
#Sta/Elev= 30
  4824.2  471.32  4838.2  470.88  4860.3  470.51  4881.2  469.68  4887.6  469.66
  4909.8  469.00  4924.2  468.85  4959.3  467.48  4965.8  466.78  4973.6  466.34
  4976.3  465.94  4980.1  465.36  4985.0  465.16  4985.5  464.36  4990.5  464.36
  4991.0  465.16  5002.3  465.26  5009.9  465.74  5021.9  465.94  5034.6  466.08
  5082.0  467.31  5123.2  467.99  5143.8  468.60  5159.4  469.26  5164.6  469.20
  5195.2  469.88  5201.1  470.25  5206.2  470.20  5257.0  471.17  5262.4  471.54
#Mann=3,-1,0
  4824.2    0.05       0  4985.0    0.03       0  4991.0    0.05       0
Bank Sta=4976.3,5021.9
Exp/Cntr=0.3,0.1

Type RM Length L Ch R = 1,834,63,63,63
BEGIN DESCRIPTION:
XS4180A
END DESCRIPTION:
XS GIS Cut Line= 3
      2808502.72      7040860.25      2808281.35      7040920.15
      2808164.18      7041159.70
#Sta/Elev= 30
  4750.9  470.07  4758.9  469.73  4821.1  468.29  4831.5  467.69  4866.2  466.58
  4872.9  466.51  4914.3  464.87  4935.0  464.47  4944.0  463.75  4946.0  463.55
  4984.2  462.96  4984.7  462.16  4989.7  462.16  4990.2  462.96  4997.8  463.75
  5004.2  464.66  5009.8  464.49  5026.7  465.08  5032.3  464.96  5049.2  465.52
  5054.8  465.32  5085.8  465.66  5099.8  465.97  5116.8  466.64  5174.9  467.28
  5184.3  467.53  5189.9  467.40  5206.8  467.69  5212.4  467.58  5246.9  467.90
#Mann=3,-1,0
  4750.9    0.05       0  4984.2    0.03       0  4990.2    0.05       0
Bank Sta=4944,4997.8
Exp/Cntr=0.3,0.1

Type RM Length L Ch R = 1,771,149,149,149
BEGIN DESCRIPTION:
Mapping XS 0f90d967
END DESCRIPTION:
XS GIS Cut Line= 3
      2808454.73      7040853.58      2808221.62      7040895.26
      2808125.28      7041145.23
#Sta/Elev= 30
  4745.3  468.75  4795.8  467.72  4816.1  467.58  4826.3  467.29  4840.1  466.49
  4866.9  465.66  4893.9  465.15  4898.9  464.65  4938.0  464.43  4947.7  464.12
  4958.1  462.80  4974.9  461.99  4975.4  461.19  4980.4  461.19  4980.9  461.99
  4984.4  461.99  4992.3  462.80  5011.5  464.31  5024.7  464.90  5035.4  464.64
  5046.9  464.78  5071.5  465.15  5096.1  465.85  5131.9  466.00  5150.7  466.57
  5156.1  466.42  5180.7  467.07  5210.7  467.24  5217.6  467.47  5250.0  467.48
#Mann=3,-1,0
  4745.3    0.05       0  4974.9    0.03       0  4980.9    0.05       0
Bank Sta=4958.1,4992.3
Exp/Cntr=0.3,0.1

Type RM Length L Ch R = 1,622,186,186,186
BEGIN DESCRIPTION:
XS4179A
END DESCRIPTION:
XS GIS Cut Line= 4
      2808434.97      7040844.63      2808075.62      7040842.03
      2807954.99      7040840.20      2807921.12      7040924.88
#Sta/Elev= 30
  4661.0  468.43  4761.0  466.68  4771.0  466.56  4781.0  466.74  4811.0  466.21
  4841.0  466.17  4851.0  465.93  4861.0  465.93  4931.0  463.14  4951.0  462.04
  4959.9  461.36  4968.0  460.50  4968.5  459.70  4973.5  459.70  4974.0  460.50
  4981.0  460.96  4991.0  461.13  5001.0  460.90  5011.0  461.08  5018.2  461.60
  5031.0  461.71  5045.4  461.36  5061.0  461.48  5081.0  461.95  5131.0  462.36
  5146.3  462.30  5182.6  463.22  5189.2  463.63  5206.8  464.03  5232.2  463.97
#Mann=3,-1,0
  4661.0    0.05       0  4968.0    0.04       0  4974.0    0.05       0
Bank Sta=4959.9,5045.4
Exp/Cntr=0.3,0.1

Type RM Length L Ch R = 1,436,37,37,37
BEGIN DESCRIPTION:
Mapping XS d2ca65b6
END DESCRIPTION:
XS GIS Cut Line= 4
      2808428.93      7040771.19      2808022.70      7040762.08
      2807939.37      7040764.68      2807905.51      7040915.73
#Sta/Elev= 30
  4523.8  468.91  4547.7  468.72  4567.7  468.06  4579.8  468.51  4587.7  468.55
  4687.8  467.03  4697.8  466.78  4707.8  466.17  4717.8  465.23  4737.8  464.31
  4757.8  464.15  4767.8  464.31  4777.8  463.79  4847.8  463.05  4897.8  461.09
  4930.1  460.44  4957.8  459.48  4977.4  459.20  5021.1  458.55  5021.6  457.75
  5026.6  457.75  5027.1  458.55  5044.6  458.66  5045.9  459.20  5053.0  462.10
  5075.3  461.95  5101.5  462.68  5116.3  462.86  5144.9  463.72  5168.3  463.72
#Mann=3,-1,0
  4523.8    0.05       0  5021.1    0.03       0  5027.1    0.05       0
Bank Sta=4977.4,5045.9
Exp/Cntr=0.3,0.1

Type RM Length L Ch R = 1,399,97,97,97
BEGIN DESCRIPTION:
XS4182A
END DESCRIPTION:
XS GIS Cut Line= 4
      2808200.60      7040513.92      2807943.27      7040704.79
      2807914.06      7040771.99      2807888.11      7040869.85
#Sta/Elev= 30
  4641.0  468.30  4646.5  467.98  4652.7  468.30  4667.3  466.86  4696.6  466.24
  4717.4  466.15  4723.6  466.84  4738.2  467.07  4796.7  464.85  4802.9  465.07
  4817.6  464.14  4823.8  464.41  4832.2  463.75  4838.4  464.33  4846.8  463.90
  4853.0  464.29  4867.6  463.56  4903.1  463.45  4953.2  460.82  4964.2  460.77
  4983.6  458.32  4988.8  457.61  4989.3  456.81  4994.3  456.81  4994.8  457.61
  5032.6  458.32  5058.5  458.93  5068.8  461.96  5092.1  461.88  5135.9  462.76
#Mann=3,-1,0
  4641.0    0.05       0  4988.8    0.03       0  4994.8    0.05       0
Bank Sta=4983.6,5032.6
Exp/Cntr=0.3,0.1

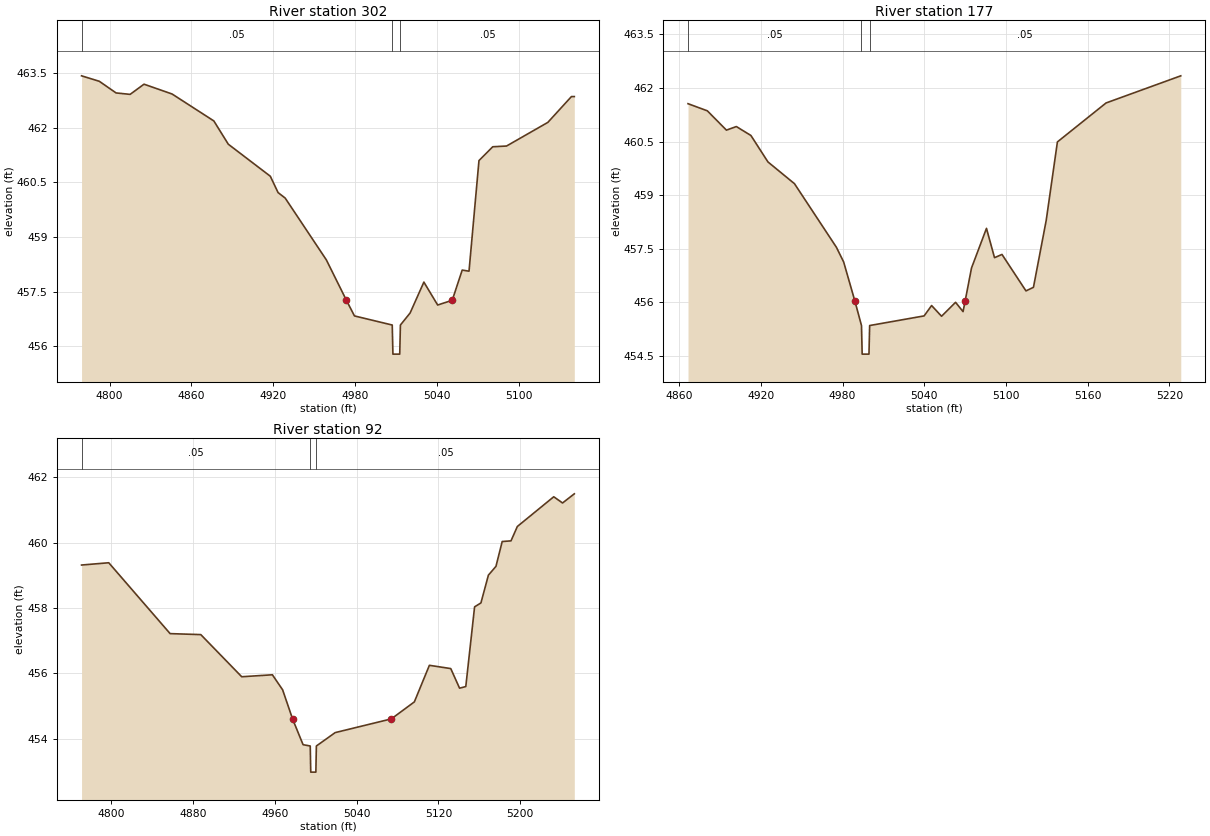
Type RM Length L Ch R = 1,302,125,125,125
BEGIN DESCRIPTION:
XS4183A
END DESCRIPTION:
XS GIS Cut Line= 3
      2807883.78      7040520.42      2807831.70      7040737.43
      2807851.23      7040874.17
#Sta/Elev= 30
  4779.4  463.43  4792.4  463.28  4804.7  462.96  4815.0  462.92  4825.2  463.20
  4845.8  462.93  4876.4  462.19  4887.0  461.55  4917.8  460.67  4923.5  460.22
  4928.7  460.07  4958.9  458.37  4973.6  457.26  4979.5  456.83  5007.2  456.58
  5007.7  455.78  5012.7  455.78  5013.2  456.58  5020.3  456.91  5030.4  457.76
  5040.5  457.13  5051.2  457.26  5058.5  458.09  5063.5  458.06  5070.8  461.10
  5080.9  461.48  5091.0  461.50  5121.3  462.15  5138.6  462.86  5140.7  462.86
#Mann=3,-1,0
  4779.4    0.05       0  5007.2    0.03       0  5013.2    0.05       0
Bank Sta=4973.6,5051.2
Exp/Cntr=0.3,0.1

Type RM Length L Ch R = 1,177,85,85,85
BEGIN DESCRIPTION:
Mapping XS b409b0b8
END DESCRIPTION:
XS GIS Cut Line= 3
      2807769.08      7040551.66      2807722.53      7040678.09
      2807816.28      7040885.02
#Sta/Elev= 30
  4866.5  461.56  4880.7  461.36  4894.7  460.82  4902.0  460.92  4912.7  460.67
  4925.2  459.93  4944.7  459.32  4975.5  457.54  4980.8  457.13  4989.1  456.03
  4993.9  455.35  4994.4  454.55  4999.4  454.55  4999.9  455.35  5039.9  455.62
  5045.4  455.91  5052.7  455.61  5063.0  456.00  5068.5  455.74  5070.0  456.03
  5074.7  456.96  5085.7  458.07  5091.6  457.25  5097.1  457.34  5114.7  456.32
  5120.2  456.42  5129.6  458.30  5137.8  460.49  5173.5  461.58  5228.4  462.34
#Mann=3,-1,0
  4866.5    0.05       0  4993.9    0.03       0  4999.9    0.05       0
Bank Sta=4989.1,5070
Exp/Cntr=0.3,0.1

Type RM Length L Ch R = 1,92,0,0,0
BEGIN DESCRIPTION:
UNT 188 in LFCCL Watershed 1.0
END DESCRIPTION:
XS GIS Cut Line= 3
      2807635.52      7040438.40      2807638.12      7040670.15
      2807783.94      7040873.26
#Sta/Elev= 30
  4771.0  459.32  4797.6  459.39  4857.6  457.22  4887.6  457.19  4927.6  455.90
  4957.6  455.96  4967.6  455.50  4977.3  454.61  4987.6  453.82  4994.6  453.78
  4995.1  452.98  5000.1  452.98  5000.6  453.78  5019.0  454.19  5073.9  454.61
  5096.4  455.13  5111.1  456.25  5132.0  456.15  5140.6  455.55  5146.7  455.60
  5155.3  458.04  5161.5  458.16  5168.8  459.01  5176.2  459.28  5182.3  460.04
  5190.9  460.06  5197.1  460.50  5232.7  461.41  5241.3  461.22  5252.8  461.50
#Mann=3,-1,0
  4771.0    0.05       0  4994.6    0.03       0  5000.6    0.05       0
Bank Sta=4977.3,5073.9
Exp/Cntr=0.3,0.1

Chan Stop Cuts=-1