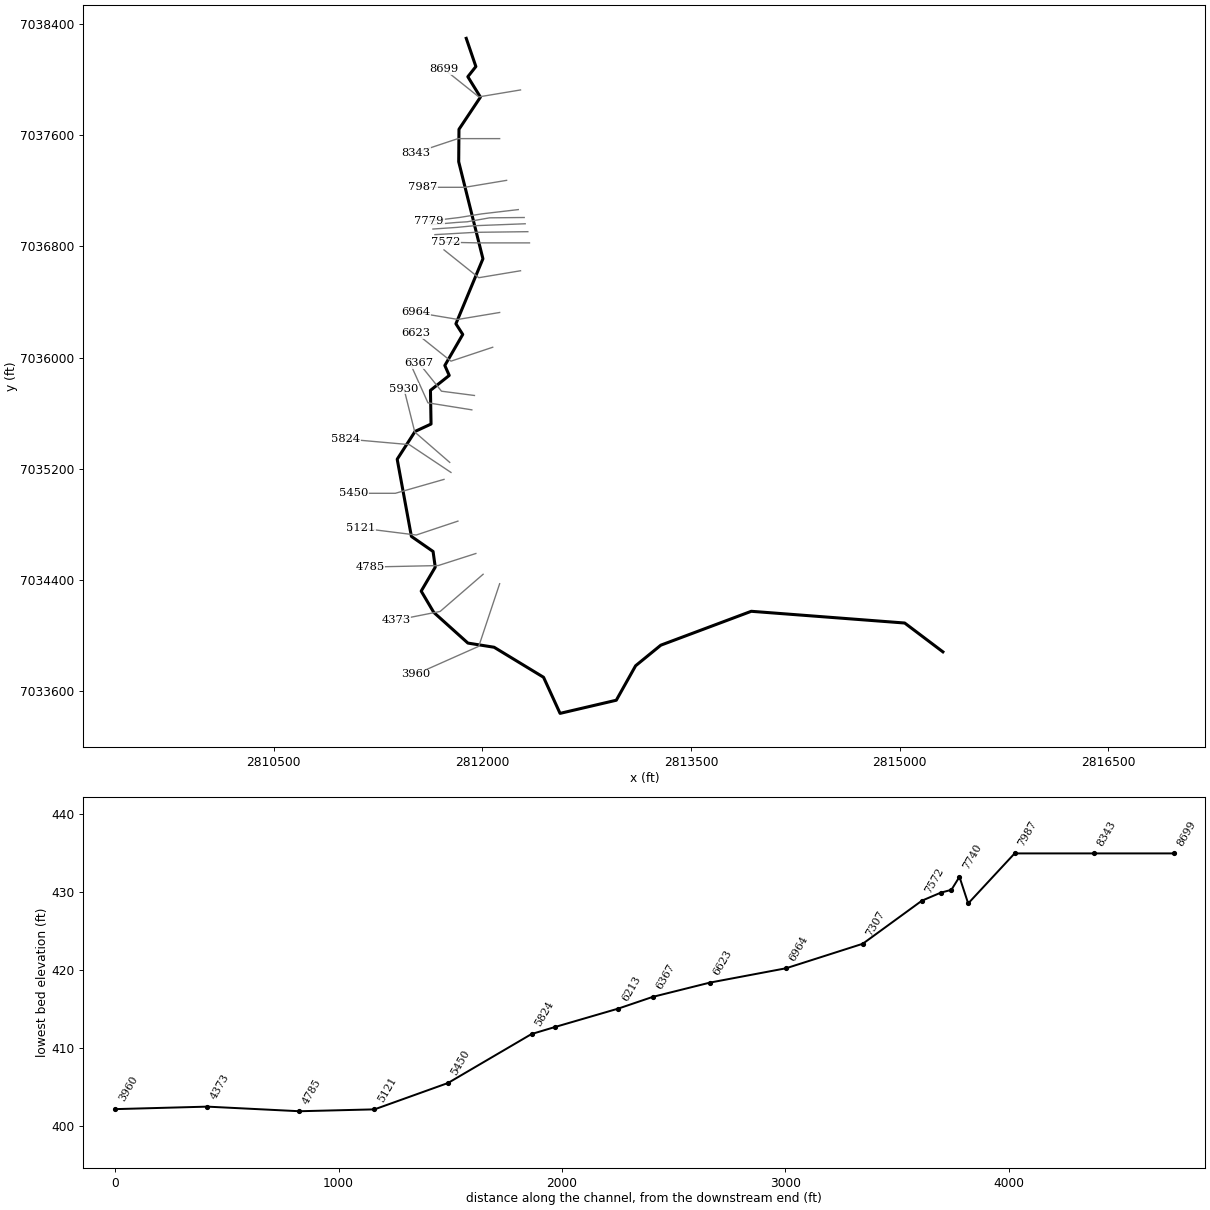
--- UNT 189 in LFCCL Watershed.prj (project) ---

Proj Title=UNT 189 in LFCCL Watershed Base Level Engineering
Current Plan=p01
Default Exp/Contr=0.3,0.1
English Units
Geom File=g01
Flow File=f01
Plan File=p01
BEGIN DESCRIPTION:
UNT 189 in LFCCL Watershed
END DESCRIPTION:

--- UNT 189 in LFCCL Watershed.p01 (plan) ---

Plan Title=Multiple Run
Short Identifier=Multiple
Geom File=g01
Flow File=f01
Subcritical Flow
K Sum by GR= 0
Std Step Tol= 0.01
Critical Tol= 0.01
Num of Std Step Trials= 20
Max Error Tol= 0.3
Flow Tol Ratio= 0.001
Split Flow NTrial= 30
Split Flow Tol= 0.02
Split Flow Ratio= 0.02
Log Output Level= 0
Friction Slope Method= 1
Unsteady Friction Slope Method= 2
Unsteady Bridges Friction Slope Method= 1
Parabolic Critical Depth
Global Vel Dist=  1 , 1 , 1
Global Log Level= 0
CheckData=True
Encroach Param= -1, 0, 0, 0
BEGIN DESCRIPTION:
Multiple Run
END DESCRIPTION:

--- UNT 189 in LFCCL Watershed.f01 (steady flow) ---

Flow Title=Multiple
Program Version=5.07
Number of Profiles= 7
Profile Names=10-year,25-year,50-year,1pct_min,100-year,1pct_plu,500-year
River Rch & RM=UNT 189 in LFCCL,Reach-1         ,8699
     260     330     384     223     445     888     596
River Rch & RM=UNT 189 in LFCCL,Reach-1         ,5824
     533     708     849     506    1009    2013    1429
Boundary for River Rch & Prof#=UNT 189 in LFCCL,Reach-1         , 1
Up Type= 0
Dn Type= 3
Dn Slope=0.005
Boundary for River Rch & Prof#=UNT 189 in LFCCL,Reach-1         , 2
Up Type= 0
Dn Type= 3
Dn Slope=0.005
Boundary for River Rch & Prof#=UNT 189 in LFCCL,Reach-1         , 3
Up Type= 0
Dn Type= 3
Dn Slope=0.005
Boundary for River Rch & Prof#=UNT 189 in LFCCL,Reach-1         , 4
Up Type= 0
Dn Type= 3
Dn Slope=0.005
Boundary for River Rch & Prof#=UNT 189 in LFCCL,Reach-1         , 5
Up Type= 0
Dn Type= 3
Dn Slope=0.005
Boundary for River Rch & Prof#=UNT 189 in LFCCL,Reach-1         , 6
Up Type= 0
Dn Type= 3
Dn Slope=0.005
Boundary for River Rch & Prof#=UNT 189 in LFCCL,Reach-1         , 7
Up Type= 0
Dn Type= 3
Dn Slope=0.005
DSS Import GetInterval= 0
DSS Import GetPeak= 0
DSS Import FillOption= 0

--- UNT 189 in LFCCL Watershed.g01 (geometry) ---

Geom Title=Existing Conditions

River Reach=UNT 189 in LFCCL,Reach-1
Reach XY= 30
      2811884.78      7038296.03      2811954.02      7038093.29
      2811896.16      7038019.99      2811986.81      7037873.40
      2811832.50      7037641.93      2811830.57      7037408.53
      2812004.80      7036711.23      2811810.49      7036243.74
      2811859.69      7036167.08      2811730.82      7035943.90
      2811762.52      7035872.35      2811627.52      7035765.04
      2811631.74      7035522.93      2811516.91      7035469.71
      2811388.34      7035269.92      2811490.46      7034715.00
      2811646.31      7034606.74      2811661.96      7034493.93
      2811560.89      7034321.77      2811651.53      7034168.52
      2811896.73      7033948.10      2812085.19      7033918.10
      2812440.60      7033702.25      2812559.28      7033442.71
      2812963.60      7033537.27      2813102.50      7033785.07
      2813283.79      7033933.10      2813934.09      7034176.66
      2815037.08      7034092.35      2815311.80      7033885.09

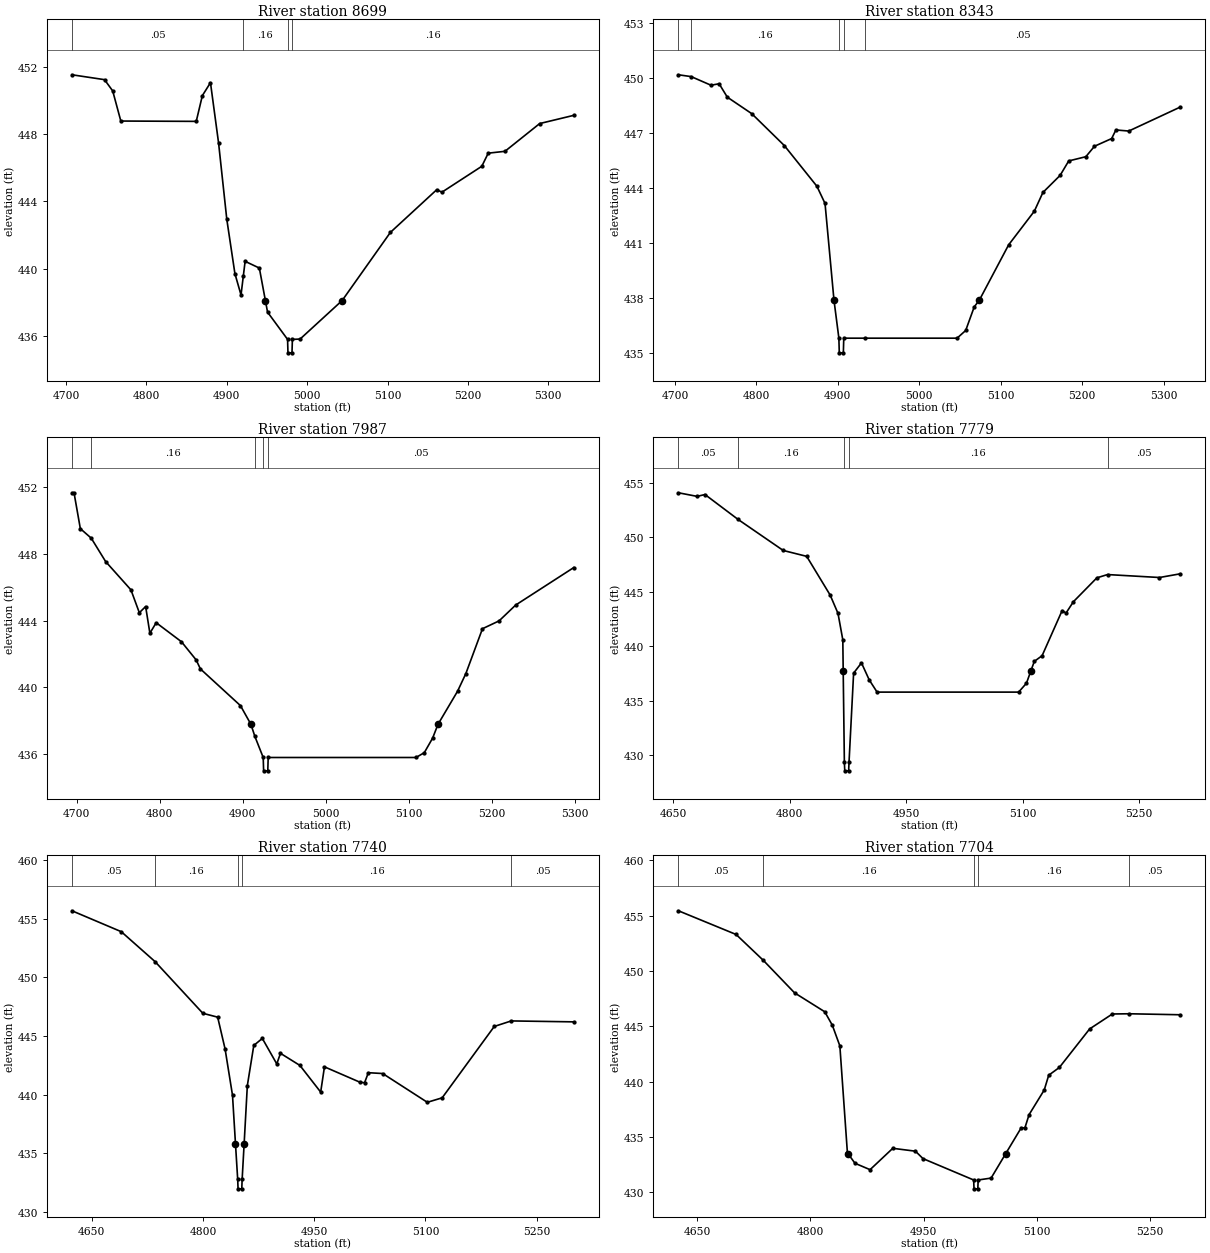
Type RM Length L Ch R = 1,8699,356,356,356
BEGIN DESCRIPTION:
UNT 189 in LFCCL Watershed 19.0
END DESCRIPTION:
XS GIS Cut Line= 3
      2812274.97      7037924.99      2811975.00      7037875.00
      2811724.97      7038075.02
#Sta/Elev= 30
  4707.4  451.52  4747.9  451.23  4758.1  450.56  4768.2  448.77  4862.0  448.75
  4869.6  450.28  4879.7  451.05  4889.8  447.46  4900.0  442.93  4910.1  439.70
  4917.7  438.43  4920.5  439.53  4922.8  440.43  4940.5  440.03  4948.0  438.10
  4950.7  437.41  4975.6  435.79  4976.1  434.99  4981.1  434.99  4981.6  435.79
  4991.2  435.81  5043.5  438.10  5103.5  442.15  5161.2  444.69  5167.6  444.54
  5217.2  446.08  5225.2  446.86  5246.0  446.97  5289.2  448.62  5331.7  449.11
#Mann=4,-1,0
  4707.4    0.05       0  4920.5    0.16       0  4975.6    0.07       0
  4981.6    0.16       0
Bank Sta=4948,5043.5
Exp/Cntr=0.3,0.1

Type RM Length L Ch R = 1,8343,356,356,356
BEGIN DESCRIPTION:
UNT 189 in LFCCL Watershed 18.0
END DESCRIPTION:
XS GIS Cut Line= 3
      2812124.96      7037575.00      2811825.00      7037575.00
      2811524.99      7037475.00
#Sta/Elev= 30
  4704.3  450.16  4720.0  450.06  4744.3  449.59  4754.3  449.67  4764.3  448.94
  4794.3  448.04  4834.3  446.30  4874.3  444.08  4884.3  443.14  4895.3  437.86
  4901.3  435.79  4901.8  434.99  4906.8  434.99  4907.3  435.79  4933.4  435.79
  5046.4  435.79  5057.0  436.21  5067.5  437.50  5073.7  437.86  5109.7  440.88
  5141.3  442.72  5151.8  443.74  5172.9  444.67  5183.5  445.46  5204.5  445.69
  5215.1  446.26  5236.2  446.68  5241.4  447.15  5257.2  447.09  5320.5  448.40
#Mann=5,-1,0
  4704.3    0.05       0  4720.0    0.16       0  4901.3   0.033       0
  4907.3    0.16       0  4933.4    0.05       0
Bank Sta=4895.3,5073.7
Exp/Cntr=0.3,0.1

Type RM Length L Ch R = 1,7987,208,208,208
BEGIN DESCRIPTION:
UNT 189 in LFCCL Watershed 17.0
END DESCRIPTION:
XS GIS Cut Line= 3
      2812174.99      7037275.00      2811875.00      7037225.00
      2811575.03      7037225.00
#Sta/Elev= 30
  4694.3  451.66  4696.8  451.66  4704.4  449.51  4717.5  448.94  4734.8  447.54
  4765.3  445.84  4775.4  444.47  4783.0  444.84  4788.1  443.24  4795.7  443.87
  4826.1  442.73  4843.8  441.64  4848.9  441.10  4897.1  438.90  4909.7  437.78
  4914.5  437.05  4924.5  435.79  4925.0  434.99  4930.0  434.99  4930.5  435.79
  5108.4  435.79  5118.4  436.08  5128.4  436.95  5134.9  437.78  5158.4  439.76
  5168.4  440.82  5188.4  443.51  5208.4  443.98  5228.4  444.93  5298.4  447.18
#Mann=5,-1,0
  4694.3    0.05       0  4717.5    0.16       0  4914.5    0.05       0
  4924.5   0.033       0  4930.5    0.05       0
Bank Sta=4909.7,5134.9
Exp/Cntr=0.3,0.1

Type RM Length L Ch R = 1,7779,39,39,39
BEGIN DESCRIPTION:
XS4184A
END DESCRIPTION:
XS GIS Cut Line= 4
      2812258.96      7037064.75      2811995.89      7037033.94
      2811834.75      7037007.87      2811618.40      7036982.00
#Sta/Elev= 30
  4656.9  454.07  4681.0  453.74  4691.1  453.91  4733.8  451.62  4791.8  448.78
  4822.0  448.24  4852.2  444.69  4862.3  443.01  4868.5  440.58  4869.0  437.69
  4870.5  429.37  4871.0  428.57  4876.0  428.57  4876.5  429.37  4882.4  437.53
  4892.5  438.47  4902.5  436.91  4912.6  435.79  5094.8  435.79  5104.9  436.61
  5110.3  437.69  5115.0  438.61  5125.0  439.13  5150.8  443.27  5155.8  443.04
  5165.3  444.08  5195.5  446.27  5209.2  446.57  5276.1  446.30  5302.9  446.64
#Mann=5,-1,0
  4656.9    0.05       0  4733.8    0.16       0  4870.5    0.07       0
  4876.5    0.16       0  5209.2    0.05       0
Bank Sta=4869,5110.3
Exp/Cntr=0.3,0.1

Type RM Length L Ch R = 1,7740,36,36,36
BEGIN DESCRIPTION:
XS4185A
END DESCRIPTION:
XS GIS Cut Line= 5
      2812301.52      7037007.87      2812052.76      7037005.50
      2811891.62      7036977.07      2811815.80      7036972.33
      2811628.09      7036955.90
#Sta/Elev= 30
  4623.3  455.67  4689.8  453.89  4735.4  451.34  4799.8  446.94  4819.8  446.61
  4829.8  443.90  4839.8  439.96  4843.8  435.84  4846.8  432.79  4847.3  431.99
  4852.3  431.99  4852.8  432.79  4855.5  435.84  4859.8  440.78  4868.5  444.20
  4880.0  444.80  4899.5  442.63  4904.5  443.53  4930.7  442.50  4958.7  440.23
  4963.8  442.38  5012.0  441.06  5017.9  441.03  5023.0  441.88  5042.3  441.81
  5102.5  439.36  5122.5  439.74  5192.8  445.82  5215.7  446.29  5300.1  446.21
#Mann=5,-1,0
  4623.3    0.05       0  4735.4    0.16       0  4846.8    0.07       0
  4852.8    0.16       0  5215.7    0.05       0
Bank Sta=4843.8,4855.5
Exp/Cntr=0.3,0.1

Type RM Length L Ch R = 1,7704,48,48,48
BEGIN DESCRIPTION:
XS4186A
END DESCRIPTION:
XS GIS Cut Line= 4
      2812308.64      7036962.85      2811939.02      7036948.63
      2811818.17      7036936.79      2811645.20      7036924.94
#Sta/Elev= 30
  4625.3  455.43  4701.7  453.29  4737.8  450.95  4779.1  448.02  4819.1  446.31
  4829.1  445.10  4839.1  443.23  4849.1  433.57  4850.2  433.47  4859.1  432.63
  4879.1  432.05  4909.2  433.98  4939.2  433.72  4949.2  433.05  5016.3  431.12
  5016.8  430.32  5021.8  430.32  5022.3  431.12  5039.4  431.29  5058.5  433.47
  5079.1  435.81  5084.2  435.83  5089.7  437.02  5109.8  439.25  5115.7  440.58
  5129.8  441.28  5169.9  444.76  5200.0  446.11  5222.1  446.13  5290.0  446.04
#Mann=5,-1,0
  4625.3    0.05       0  4737.8    0.16       0  5016.3    0.07       0
  5022.3    0.16       0  5222.1    0.05       0
Bank Sta=4850.2,5058.5
Exp/Cntr=0.3,0.1

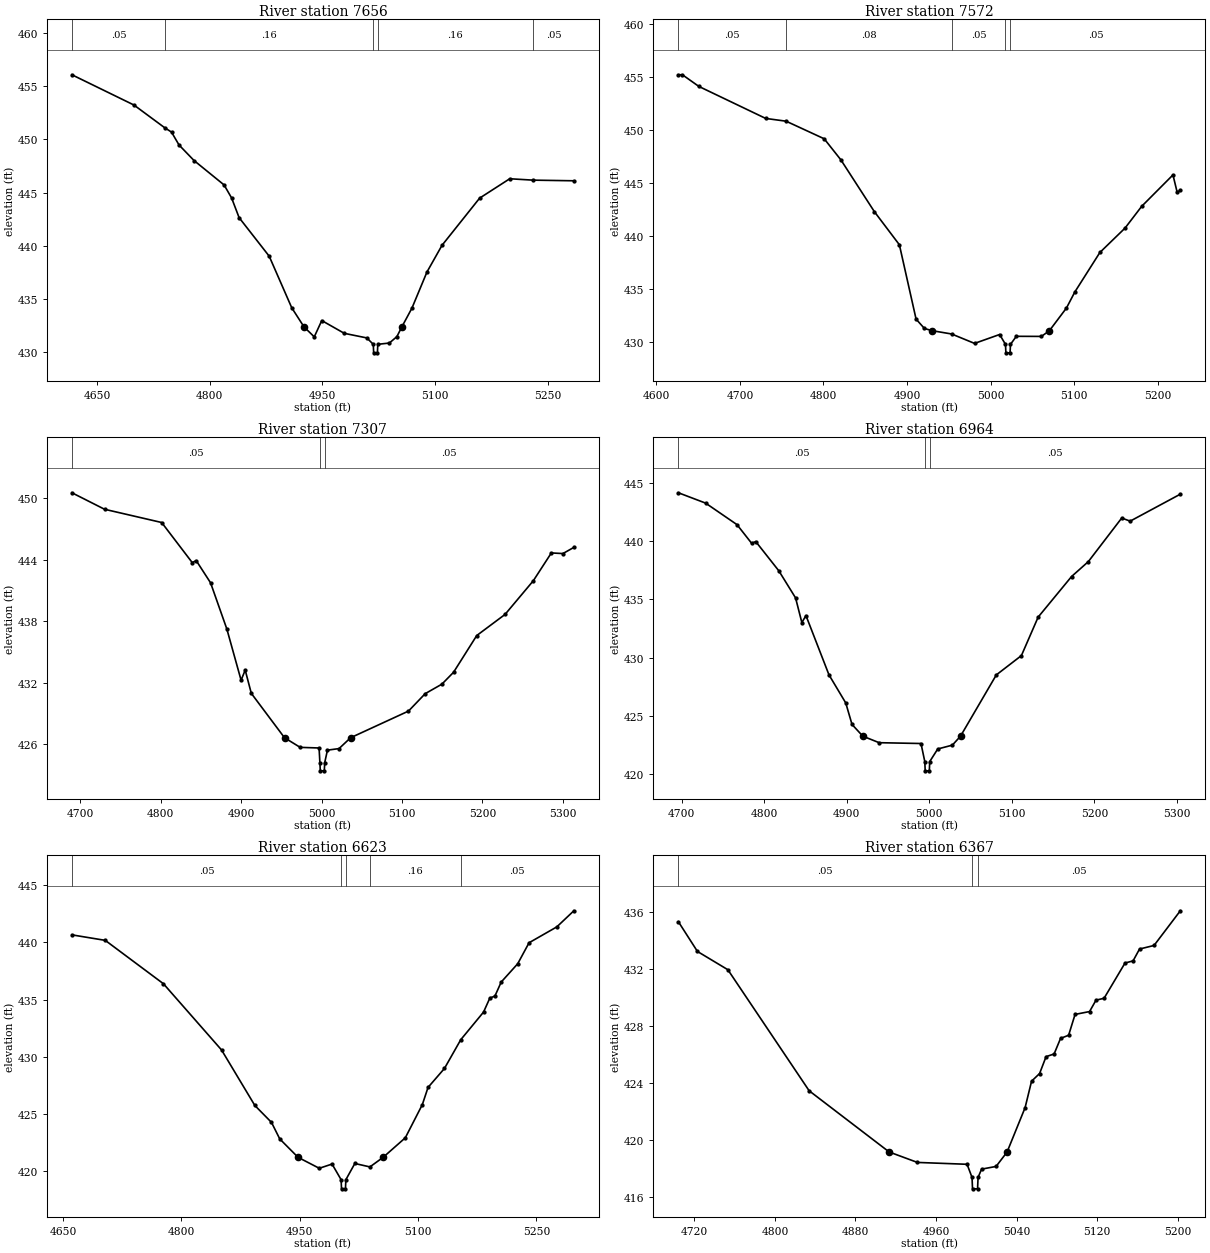
Type RM Length L Ch R = 1,7656,84,84,84
BEGIN DESCRIPTION:
XS4187A
END DESCRIPTION:
XS GIS Cut Line= 3
      2812327.63      7036905.98      2811948.50      7036901.24
      2811659.73      7036884.67
#Sta/Elev= 30
  4616.6  456.05  4699.2  453.21  4740.3  451.07  4749.2  450.67  4759.2  449.46
  4779.2  448.00  4819.2  445.71  4829.2  444.49  4839.2  442.64  4879.3  439.02
  4909.3  434.18  4925.7  432.38  4939.3  431.45  4949.3  432.98  4979.3  431.78
  5009.3  431.35  5017.9  430.75  5018.4  429.95  5023.4  429.95  5023.9  430.75
  5039.3  430.87  5049.3  431.47  5055.9  432.38  5069.4  434.15  5089.4  437.54
  5109.4  440.04  5159.5  444.47  5199.6  446.29  5230.7  446.16  5285.0  446.10
#Mann=5,-1,0
  4616.6    0.05       0  4740.3    0.16       0  5017.9    0.07       0
  5023.9    0.16       0  5230.7    0.05       0
Bank Sta=4925.7,5055.9
Exp/Cntr=0.3,0.1

Type RM Length L Ch R = 1,7572,265,265,265
BEGIN DESCRIPTION:
XS4188A
END DESCRIPTION:
XS GIS Cut Line= 3
      2812339.52      7036825.41      2811969.82      7036825.41
      2811738.77      7036830.13
#Sta/Elev= 30
  4626.4  455.17  4631.2  455.17  4650.9  454.07  4730.9  451.05  4755.3  450.79
  4800.9  449.13  4820.9  447.14  4860.9  442.26  4890.9  439.13  4910.9  432.11
  4920.9  431.23  4930.1  431.02  4953.4  430.71  4980.9  429.82  5010.9  430.66
  5017.9  429.73  5018.4  428.93  5023.4  428.93  5023.9  429.73  5030.9  430.49
  5060.9  430.48  5070.5  431.02  5090.9  433.16  5100.9  434.67  5130.9  438.40
  5161.0  440.70  5181.0  442.76  5218.4  445.72  5223.4  444.09  5227.2  444.25
#Mann=5,-1,0
  4626.4    0.05       0  4755.3    0.08       0  4953.4    0.05       0
  5017.9    0.03       0  5023.9    0.05       0
Bank Sta=4930.1,5070.5
Exp/Cntr=0.3,0.1

Type RM Length L Ch R = 1,7307,343,343,343
BEGIN DESCRIPTION:
UNT 189 in LFCCL Watershed 15.0
END DESCRIPTION:
XS GIS Cut Line= 3
      2812275.03      7036625.01      2811975.00      7036575.00
      2811725.02      7036774.98
#Sta/Elev= 30
  4689.4  450.53  4730.0  448.92  4801.0  447.63  4839.0  443.72  4844.0  443.91
  4861.8  441.75  4882.1  437.23  4899.8  432.24  4904.9  433.23  4912.5  430.96
  4953.8  426.63  4973.3  425.69  4996.8  425.63  4997.8  424.20  4998.3  423.40
  5003.3  423.40  5003.8  424.20  5007.2  425.42  5021.6  425.57  5036.0  426.63
  5108.0  429.23  5128.8  430.93  5149.6  431.86  5164.1  433.02  5192.9  436.60
  5228.1  438.66  5263.3  441.95  5285.7  444.66  5300.1  444.60  5313.7  445.20
#Mann=3,-1,0
  4689.4    0.05       0  4997.8    0.03       0  5003.8    0.05       0
Bank Sta=4953.8,5036
Exp/Cntr=0.3,0.1

Type RM Length L Ch R = 1,6964,341,341,341
BEGIN DESCRIPTION:
UNT 189 in LFCCL Watershed 14.0
END DESCRIPTION:
XS GIS Cut Line= 3
      2812125.02      7036325.00      2811825.00      7036275.00
      2811525.00      7036325.00
#Sta/Elev= 30
  4695.9  444.17  4728.9  443.28  4766.9  441.43  4784.6  439.83  4789.7  439.97
  4817.6  437.46  4837.9  435.13  4845.5  433.01  4850.5  433.61  4878.4  428.51
  4898.7  426.10  4906.3  424.25  4919.4  423.24  4939.2  422.68  4989.9  422.61
  4994.5  421.06  4995.0  420.26  5000.0  420.26  5000.5  421.06  5010.2  422.14
  5027.9  422.47  5037.8  423.24  5081.2  428.51  5111.6  430.17  5131.9  433.48
  5172.4  436.97  5192.7  438.25  5233.2  442.00  5243.4  441.73  5304.2  444.05
#Mann=3,-1,0
  4695.9    0.05       0  4994.5    0.03       0  5000.5    0.05       0
Bank Sta=4919.4,5037.8
Exp/Cntr=0.3,0.1

Type RM Length L Ch R = 1,6623,256,256,256
BEGIN DESCRIPTION:
UNT 189 in LFCCL Watershed 13.0
END DESCRIPTION:
XS GIS Cut Line= 3
      2812075.01      7036075.00      2811775.00      7035975.00
      2811525.00      7036175.00
#Sta/Elev= 30
  4661.1  440.66  4703.3  440.18  4777.1  436.38  4850.8  430.58  4893.0  425.72
  4914.1  424.24  4924.6  422.79  4947.8  421.18  4974.7  420.22  4990.9  420.59
  5002.4  419.22  5002.9  418.42  5007.9  418.42  5008.4  419.22  5019.8  420.64
  5038.9  420.34  5055.7  421.18  5083.8  422.89  5105.4  425.80  5112.6  427.30
  5133.4  428.96  5154.1  431.48  5183.0  433.90  5191.0  435.13  5197.4  435.30
  5205.4  436.53  5226.3  438.13  5240.7  439.97  5275.9  441.36  5297.5  442.77
#Mann=5,-1,0
  4661.1    0.05       0  5002.4    0.03       0  5008.4    0.05       0
  5038.9    0.16       0  5154.1    0.05       0
Bank Sta=4947.8,5055.7
Exp/Cntr=0.3,0.1

Type RM Length L Ch R = 1,6367,154,154,154
BEGIN DESCRIPTION:
XS4190A
END DESCRIPTION:
XS GIS Cut Line= 3
      2811943.72      7035728.29      2811706.79      7035759.09
      2811544.48      7035961.40
#Sta/Elev= 30
  4704.2  435.30  4723.1  433.22  4753.3  431.94  4834.0  423.46  4913.5  419.17
  4941.5  418.44  4990.8  418.31  4995.7  417.39  4996.2  416.59  5001.2  416.59
  5001.7  417.39  5005.2  417.97  5019.6  418.16  5030.5  419.17  5048.4  422.28
  5054.8  424.13  5062.8  424.67  5069.2  425.85  5077.2  426.04  5083.6  427.13
  5091.6  427.35  5098.0  428.81  5112.4  429.01  5118.8  429.81  5126.8  429.94
  5147.6  432.41  5155.6  432.56  5162.0  433.39  5176.4  433.64  5202.5  436.07
#Mann=3,-1,0
  4704.2    0.05       0  4995.7    0.03       0  5001.7    0.05       0
Bank Sta=4913.5,5030.5
Exp/Cntr=0.3,0.1

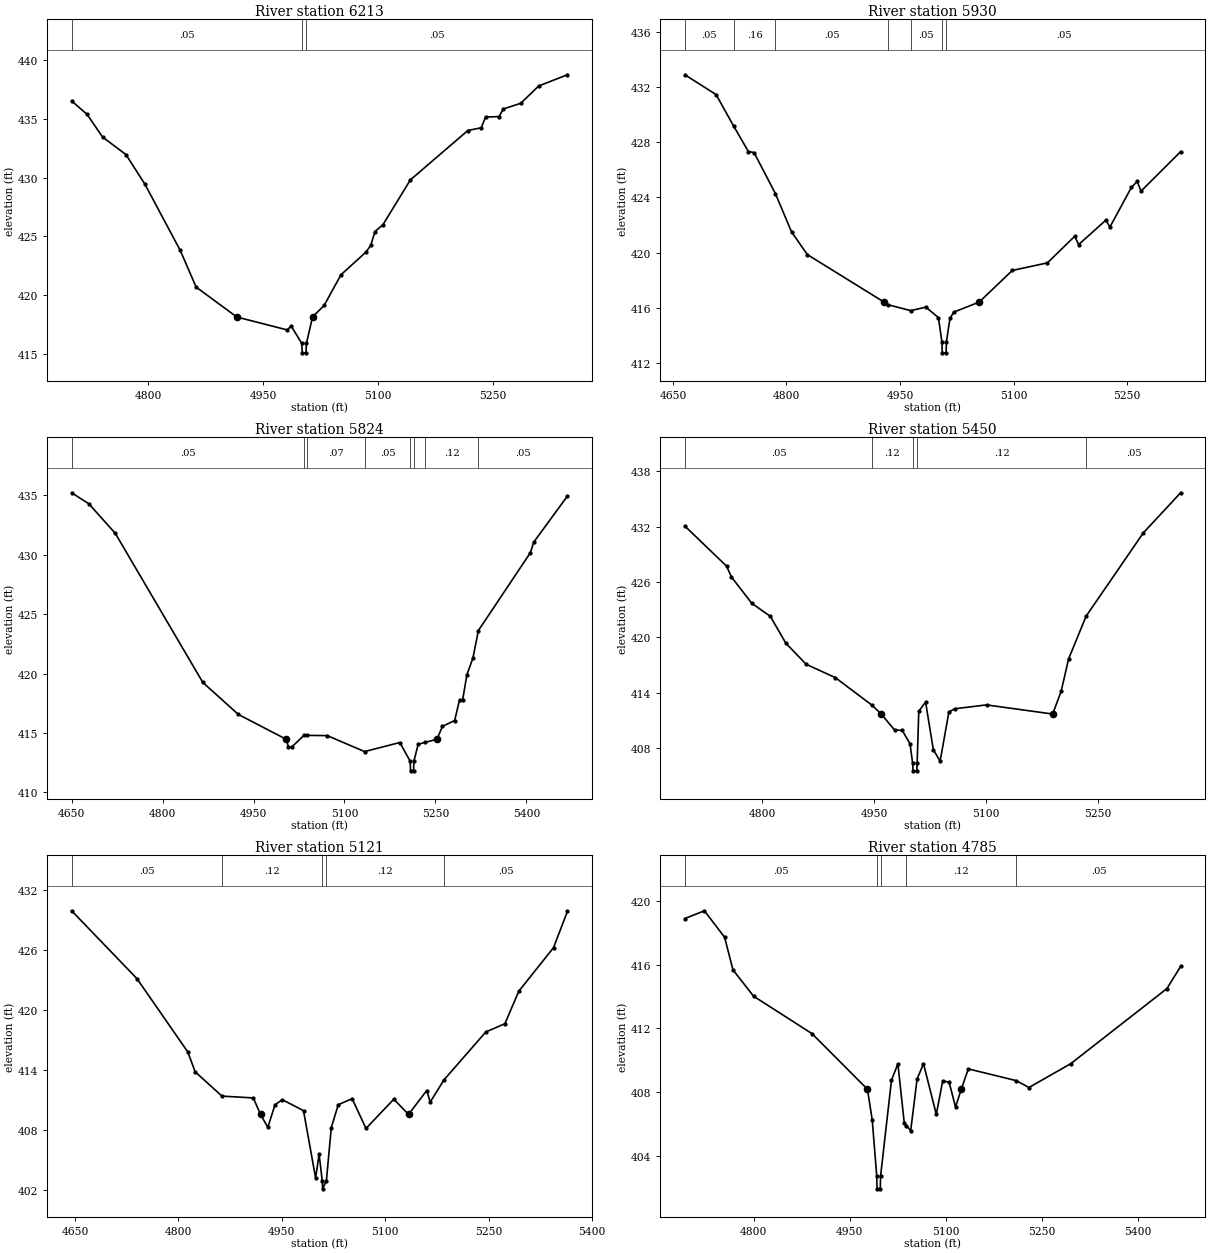
Type RM Length L Ch R = 1,6213,283,283,283
BEGIN DESCRIPTION:
UNT 189 in LFCCL Watershed 12.0
END DESCRIPTION:
XS GIS Cut Line= 3
      2811925.02      7035625.00      2811609.47      7035675.45
      2811475.00      7035974.99
#Sta/Elev= 30
  4699.7  436.54  4720.0  435.39  4740.2  433.46  4770.6  431.98  4795.3  429.47
  4841.5  423.83  4862.4  420.69  4915.6  418.14  4981.5  417.04  4986.5  417.38
  5000.5  415.89  5001.0  415.09  5006.0  415.09  5006.5  415.89  5014.5  418.14
  5029.7  419.13  5051.7  421.74  5084.5  423.68  5090.6  424.24  5096.1  425.42
  5106.5  426.00  5142.4  429.82  5217.4  434.02  5235.1  434.26  5240.6  435.17
  5258.3  435.21  5263.8  435.86  5286.6  436.34  5310.1  437.82  5347.6  438.77
#Mann=3,-1,0
  4699.7    0.05       0  5000.5    0.03       0  5006.5    0.05       0
Bank Sta=4915.6,5014.5
Exp/Cntr=0.3,0.1

Type RM Length L Ch R = 1,5930,106,106,106
BEGIN DESCRIPTION:
XS4189A
END DESCRIPTION:
XS GIS Cut Line= 3
      2811766.01      7035247.28      2811514.86      7035465.26
      2811436.65      7035778.08
#Sta/Elev= 30
  4665.8  432.88  4707.0  431.45  4730.4  429.15  4749.7  427.32  4757.3  427.24
  4785.4  424.27  4806.7  421.50  4827.6  419.85  4928.9  416.41  4934.5  416.21
  4964.2  415.79  4984.3  416.04  5000.8  415.28  5005.4  413.53  5005.9  412.73
  5010.9  412.73  5011.4  413.53  5016.0  415.22  5021.1  415.68  5054.7  416.41
  5098.4  418.70  5144.8  419.25  5180.9  421.18  5186.0  420.57  5222.1  422.35
  5227.3  421.84  5255.8  424.72  5263.3  425.15  5268.5  424.45  5320.8  427.31
#Mann=7,-1,0
  4665.8    0.05       0  4730.4    0.16       0  4785.4    0.05       0
  4934.5    0.12       0  4964.2    0.05       0  5005.4    0.03       0
  5011.4    0.05       0
Bank Sta=4928.9,5054.7
Exp/Cntr=0.3,0.1

Type RM Length L Ch R = 1,5824,374,374,374
BEGIN DESCRIPTION:
double UNT 189 in LFCCL Watershed 11.0
END DESCRIPTION:
XS GIS Cut Line= 3
      2811774.98      7035175.01      2811475.00      7035375.00
      2811019.83      7035415.47
#Sta/Elev= 30
  4650.1  435.19  4678.6  434.26  4722.2  431.77  4866.4  419.25  4925.0  416.56
  5004.0  414.47  5007.6  413.83  5013.1  413.83  5033.4  414.81  5038.8  414.80
  5071.5  414.78  5133.1  413.44  5191.3  414.20  5208.4  412.62  5208.9  411.82
  5213.9  411.82  5214.4  412.62  5221.5  414.05  5232.7  414.21  5252.4  414.47
  5261.6  415.56  5281.7  416.05  5289.8  417.80  5294.8  417.77  5301.8  419.88
  5311.8  421.30  5320.8  423.61  5406.5  430.15  5412.2  431.05  5467.6  434.91
#Mann=8,-1,0
  4650.1    0.05       0  5033.4    0.12       0  5038.8    0.07       0
  5133.1    0.05       0  5208.4    0.03       0  5214.4    0.05       0
  5232.7    0.12       0  5320.8    0.05       0
Bank Sta=5004,5252.4
Exp/Cntr=0.3,0.1

Type RM Length L Ch R = 1,5450,329,329,329
BEGIN DESCRIPTION:
double UNT 189 in LFCCL Watershed 10.0
END DESCRIPTION:
XS GIS Cut Line= 3
      2811724.99      7035125.00      2811375.00      7035025.00
      2811074.99      7035025.00
#Sta/Elev= 30
  4696.3  432.08  4752.2  427.73  4758.7  426.56  4786.0  423.70  4810.7  422.30
  4831.5  419.39  4858.8  417.09  4897.8  415.65  4946.9  412.66  4959.3  411.70
  4977.1  409.98  4987.5  409.92  4997.9  408.47  5001.4  406.34  5001.9  405.54
  5006.9  405.54  5007.4  406.34  5009.6  412.00  5018.7  413.00  5029.1  407.83
  5038.2  406.59  5049.9  411.91  5057.7  412.27  5100.3  412.69  5188.9  411.70
  5200.3  414.17  5210.3  417.69  5233.8  422.32  5310.3  431.34  5360.3  435.69
#Mann=5,-1,0
  4696.3    0.05       0  4946.9    0.12       0  5001.4    0.07       0
  5007.4    0.12       0  5233.8    0.05       0
Bank Sta=4959.3,5188.9
Exp/Cntr=0.3,0.1

Type RM Length L Ch R = 1,5121,336,336,336
BEGIN DESCRIPTION:
UNT 189 in LFCCL Watershed 9.0
END DESCRIPTION:
XS GIS Cut Line= 3
      2811824.98      7034824.99      2811525.00      7034725.00
      2811125.02      7034775.00
#Sta/Elev= 30
  4645.0  429.93  4739.8  423.15  4813.6  415.82  4824.2  413.85  4863.1  411.42
  4908.5  411.24  4919.1  409.59  4929.6  408.30  4940.1  410.56  4950.7  411.06
  4981.4  409.97  4999.0  403.23  5004.0  405.63  5008.6  402.96  5009.1  402.16
  5014.6  402.96  5021.7  408.27  5031.8  410.56  5051.9  411.17  5072.1  408.19
  5112.4  411.11  5133.8  409.59  5160.2  411.98  5165.3  410.83  5185.2  413.04
  5245.9  417.83  5273.6  418.65  5293.8  421.90  5344.2  426.25  5364.3  429.87
#Mann=5,-1,0
  4645.0    0.05       0  4863.1    0.12       0  5008.6    0.07       0
  5014.6    0.12       0  5185.2    0.05       0
Bank Sta=4919.1,5133.8
Exp/Cntr=0.3,0.1

Type RM Length L Ch R = 1,4785,412,412,412
BEGIN DESCRIPTION:
XS4191A
END DESCRIPTION:
XS GIS Cut Line= 3
      2811954.00      7034592.17      2811683.21      7034505.37
      2811193.58      7034494.96
#Sta/Elev= 30
  4692.5  418.91  4723.0  419.40  4754.5  417.74  4767.7  415.68  4799.8  414.03
  4890.9  411.68  4977.6  408.18  4985.1  406.24  4992.1  402.72  4992.6  401.92
  4997.6  401.92  4998.1  402.72  5015.1  408.74  5025.1  409.78  5035.1  406.06
  5038.4  405.90  5045.1  405.57  5055.1  408.82  5065.1  409.79  5085.1  406.60
  5095.1  408.70  5105.1  408.63  5115.1  407.06  5124.1  408.18  5135.1  409.46
  5210.1  408.72  5229.8  408.29  5295.1  409.79  5445.2  414.51  5466.6  415.90
#Mann=5,-1,0
  4692.5    0.05       0  4992.1    0.03       0  4998.1    0.05       0
  5038.4    0.12       0  5210.1    0.05       0
Bank Sta=4977.6,5124.1
Exp/Cntr=0.3,0.1

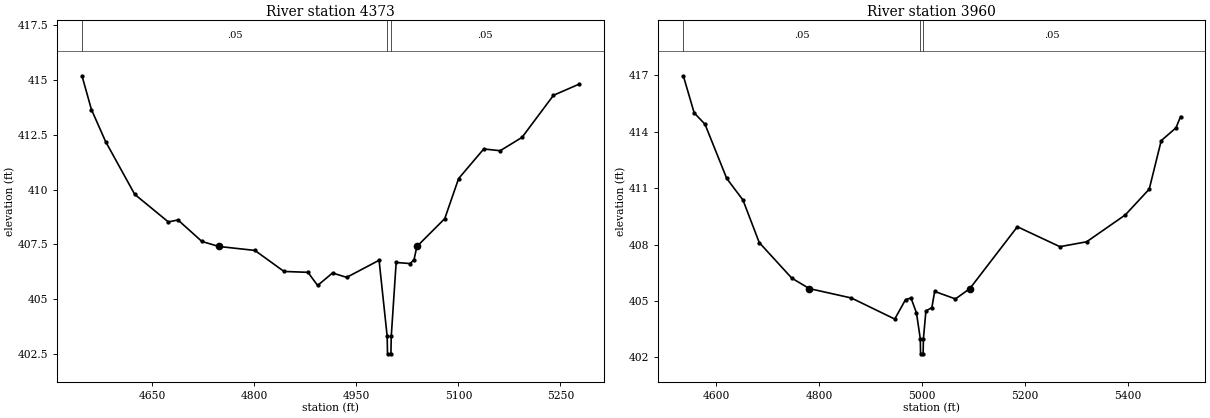
Type RM Length L Ch R = 1,4373,413,413,413
BEGIN DESCRIPTION:
UNT 189 in LFCCL Watershed 8.0
END DESCRIPTION:
XS GIS Cut Line= 3
      2812006.12      7034442.86      2811697.10      7034175.51
      2811381.14      7034113.02
#Sta/Elev= 30
  4546.8  415.20  4560.7  413.66  4581.5  412.20  4624.3  409.79  4673.7  408.53
  4687.9  408.62  4723.0  407.64  4747.9  407.41  4800.9  407.23  4843.7  406.27
  4878.9  406.23  4893.1  405.63  4915.0  406.20  4935.8  406.00  4983.4  406.78
  4995.3  403.31  4995.8  402.51  5000.8  402.51  5001.3  403.31  5008.5  406.68
  5028.9  406.63  5034.7  406.80  5039.0  407.41  5079.9  408.68  5100.3  410.51
  5137.2  411.86  5161.4  411.78  5193.5  412.39  5239.7  414.31  5277.5  414.82
#Mann=3,-1,0
  4546.8    0.05       0  4995.3    0.07       0  5001.3    0.05       0
Bank Sta=4747.9,5039
Exp/Cntr=0.3,0.1

Type RM Length L Ch R = 1,3960,0,0,0
BEGIN DESCRIPTION:
UNT 189 in LFCCL Watershed 7.0
END DESCRIPTION:
XS GIS Cut Line= 3
      2812125.01      7034375.02      2811975.00      7033925.00
      2811525.01      7033725.00
#Sta/Elev= 30
  4535.9  416.98  4557.0  415.01  4578.1  414.40  4620.3  411.52  4651.9  410.37
  4683.5  408.11  4746.7  406.22  4780.9  405.66  4862.7  405.16  4947.0  404.04
  4968.1  405.08  4978.6  405.16  4989.2  404.37  4996.7  402.99  4997.2  402.19
  5002.2  402.19  5002.7  402.99  5007.6  404.47  5019.2  404.65  5024.6  405.51
  5065.0  405.11  5093.0  405.66  5185.4  408.95  5268.1  407.89  5320.1  408.15
  5395.3  409.58  5441.8  410.95  5465.1  413.53  5493.8  414.21  5502.7  414.81
#Mann=3,-1,0
  4535.9    0.05       0  4996.7    0.03       0  5002.7    0.05       0
Bank Sta=4780.9,5093
Exp/Cntr=0.3,0.1

Chan Stop Cuts=-1