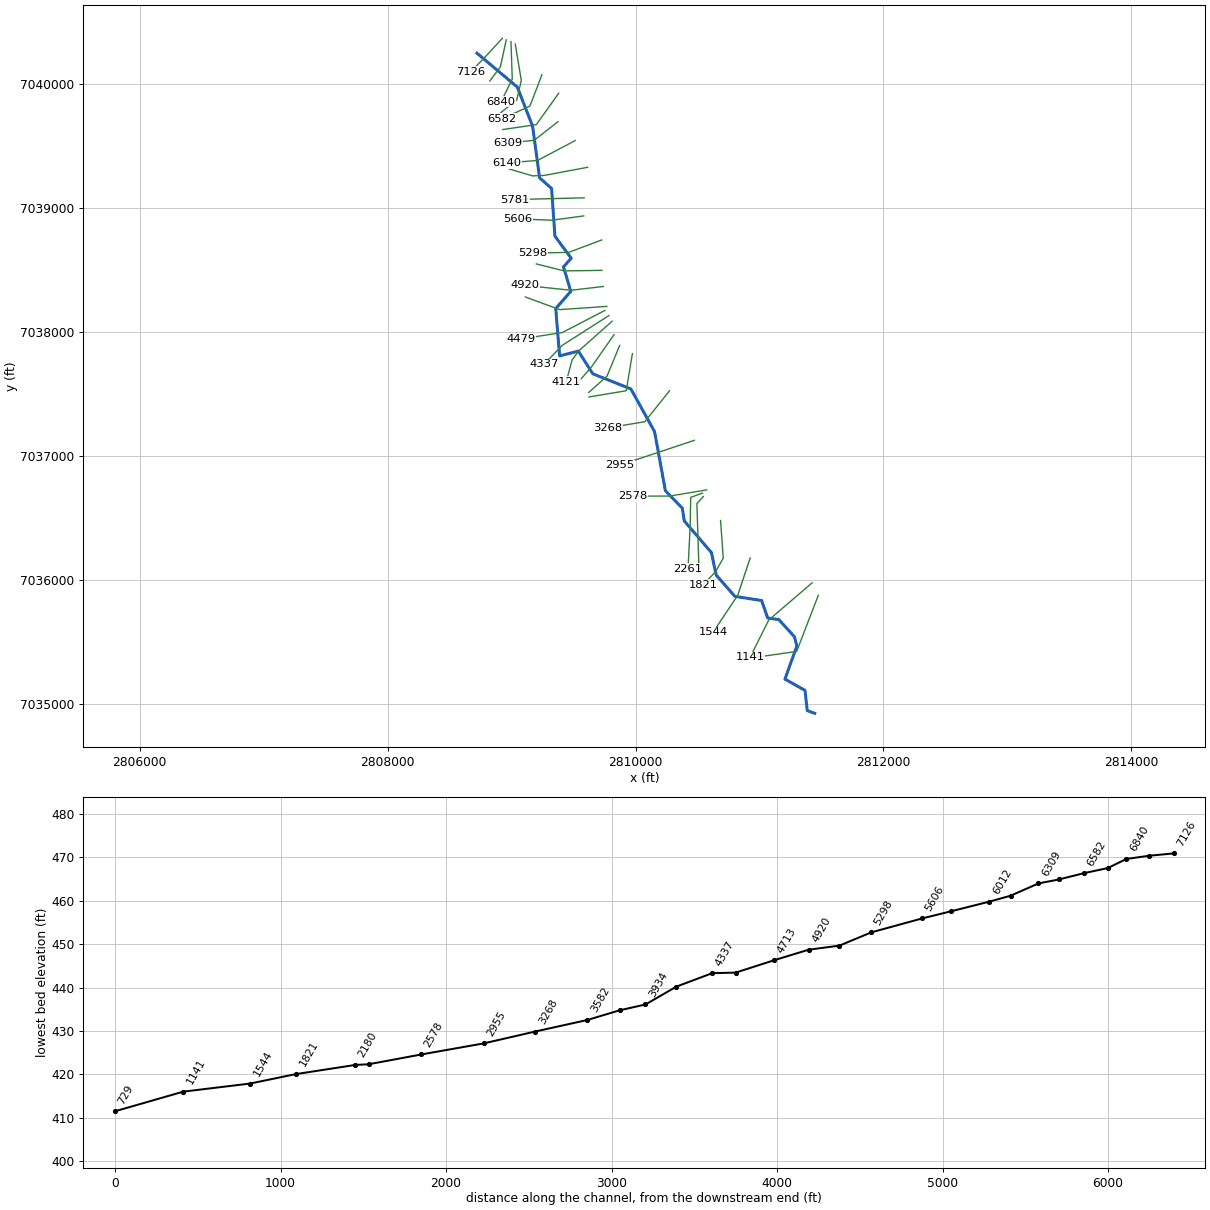
--- UNT 190 in LFCCL Watershed.prj (project) ---

Proj Title=UNT 190 in LFCCL Watershed Base Level Engineering
Current Plan=p01
Default Exp/Contr=0.3,0.1
English Units
Geom File=g01
Flow File=f01
Plan File=p01
BEGIN DESCRIPTION:
UNT 190 in LFCCL Watershed
END DESCRIPTION:

--- UNT 190 in LFCCL Watershed.p01 (plan) ---

Plan Title=Multiple Run
Short Identifier=Multiple
Geom File=g01
Flow File=f01
Subcritical Flow
K Sum by GR= 0
Std Step Tol= 0.01
Critical Tol= 0.01
Num of Std Step Trials= 20
Max Error Tol= 0.3
Flow Tol Ratio= 0.001
Split Flow NTrial= 30
Split Flow Tol= 0.02
Split Flow Ratio= 0.02
Log Output Level= 0
Friction Slope Method= 1
Unsteady Friction Slope Method= 2
Unsteady Bridges Friction Slope Method= 1
Parabolic Critical Depth
Global Vel Dist=  1 , 1 , 1
Global Log Level= 0
CheckData=True
Encroach Param= -1, 0, 0, 0
BEGIN DESCRIPTION:
Multiple Run
END DESCRIPTION:

--- UNT 190 in LFCCL Watershed.f01 (steady flow) ---

Flow Title=Multiple
Number of Profiles=7
Profile Names=10-year,25-year,50-year,1pct_min,100-year,1pct_plu,500-year
River Rch & RM= UNT 190 in LFCCL,Reach-1,7126
      77      89      97      54     107     213     128
River Rch & RM= UNT 190 in LFCCL,Reach-1,6977
     118     141     158      89     178     354     222
River Rch & RM= UNT 190 in LFCCL,Reach-1,3582
     275     352     411     240     478     954     646
Boundary for River Rch & Prof#=UNT 190 in LFCCL,Reach-1,1
Up Type=0
Dn Type=3
Dn Slope=0.005
Boundary for River Rch & Prof#=UNT 190 in LFCCL,Reach-1,2
Up Type=0
Dn Type=3
Dn Slope=0.005
Boundary for River Rch & Prof#=UNT 190 in LFCCL,Reach-1,3
Up Type=0
Dn Type=3
Dn Slope=0.005
Boundary for River Rch & Prof#=UNT 190 in LFCCL,Reach-1,4
Up Type=0
Dn Type=3
Dn Slope=0.005
Boundary for River Rch & Prof#=UNT 190 in LFCCL,Reach-1,5
Up Type=0
Dn Type=3
Dn Slope=0.005
Boundary for River Rch & Prof#=UNT 190 in LFCCL,Reach-1,6
Up Type=0
Dn Type=3
Dn Slope=0.005
Boundary for River Rch & Prof#=UNT 190 in LFCCL,Reach-1,7
Up Type=0
Dn Type=3
Dn Slope=0.005

--- UNT 190 in LFCCL Watershed.g01 (geometry) ---

Geom Title=Existing Conditions

River Reach=UNT 190 in LFCCL,Reach-1
Reach XY= 30
      2808720.49      7040248.80      2809046.15      7039975.22
      2809169.85      7039658.38      2809226.27      7039242.80
      2809322.84      7039157.08      2809349.97      7038771.88
      2809481.42      7038594.13      2809418.92      7038524.68
      2809477.95      7038326.77      2809356.42      7038187.88
      2809387.67      7037805.93      2809538.68      7037844.79
      2809655.47      7037661.60      2809962.98      7037539.14
      2810153.90      7037194.72      2810241.13      7036718.28
      2810377.78      7036577.05      2810393.67      7036474.25
      2810612.38      7036219.32      2810651.01      7036037.90
      2810801.27      7035866.11      2811017.76      7035832.06
      2811066.50      7035691.12      2811156.22      7035678.82
      2811282.67      7035539.74      2811302.11      7035465.59
      2811205.69      7035198.38      2811367.49      7035107.37
      2811385.69      7034944.56      2811446.16      7034921.82

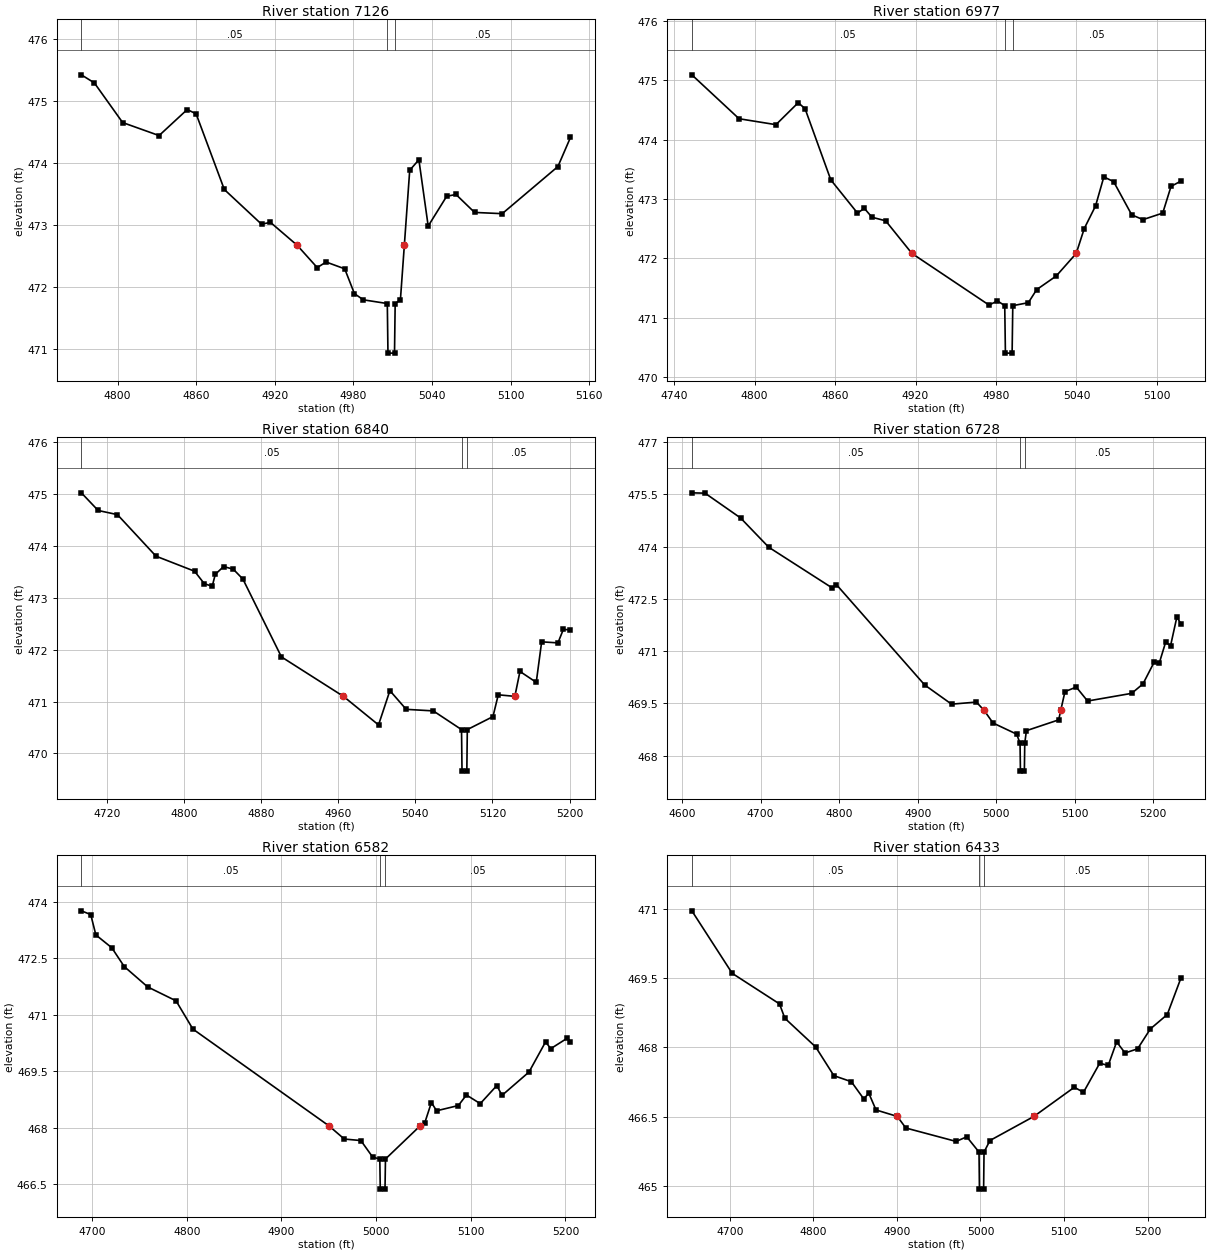
Type RM Length L Ch R = 1,7126,149,149,149
BEGIN DESCRIPTION:
UNT 190 in LFCCL Watershed 17.0
END DESCRIPTION:
XS GIS Cut Line= 3
      2808925.75      7040368.36      2808776.46      7040206.93
      2808668.85      7040097.58
#Sta/Elev= 30
  4772.4  475.43  4782.3  475.30  4803.9  474.66  4831.7  474.45  4853.2  474.87
  4860.0  474.80  4881.5  473.58  4909.9  473.02  4916.7  473.05  4937.1  472.68
  4952.4  472.32  4959.2  472.41  4973.4  472.30  4980.8  471.90  4987.6  471.80
  5005.9  471.74  5006.4  470.94  5011.4  470.94  5011.9  471.74  5015.9  471.80
  5018.9  472.68  5023.0  473.89  5030.0  474.06  5037.1  472.99  5051.2  473.47
  5058.3  473.50  5072.5  473.21  5093.6  473.19  5136.1  473.95  5145.7  474.42
#Mann=3,-1,0
  4772.4    0.05       0  5005.9    0.03       0  5011.9    0.05       0
Bank Sta=4937.1,5018.9
Exp/Cntr=0.3,0.1

Type RM Length L Ch R = 1,6977,137,137,137
BEGIN DESCRIPTION:
XS4194A
END DESCRIPTION:
XS GIS Cut Line= 3
      2808957.02      7040356.25      2808910.14      7040139.22
      2808825.10      7040024.68
#Sta/Elev= 30
  4753.2  475.09  4788.4  474.35  4815.9  474.25  4832.5  474.62  4837.6  474.52
  4856.8  473.32  4876.7  472.76  4881.8  472.84  4887.5  472.69  4897.7  472.63
  4917.3  472.08  4974.8  471.21  4981.1  471.28  4986.5  471.20  4987.0  470.40
  4992.0  470.40  4992.5  471.20  5004.1  471.25  5010.3  471.47  5024.9  471.70
  5039.8  472.08  5045.8  472.50  5054.2  472.88  5060.4  473.37  5067.7  473.29
  5081.2  472.73  5089.6  472.65  5104.3  472.76  5110.5  473.21  5117.9  473.30
#Mann=3,-1,0
  4753.2    0.05       0  4986.5    0.03       0  4992.5    0.05       0
Bank Sta=4917.3,5039.8
Exp/Cntr=0.3,0.1

Type RM Length L Ch R = 1,6840,112,112,112
BEGIN DESCRIPTION:
XS4192A
END DESCRIPTION:
XS GIS Cut Line= 3
      2808995.21      7040342.38      2809005.63      7040040.26
      2808915.34      7039856.21
#Sta/Elev= 30
  4693.6  475.02  4711.0  474.68  4731.0  474.60  4771.0  473.80  4811.0  473.51
  4821.1  473.27  4829.3  473.22  4832.5  473.45  4841.1  473.60  4851.1  473.55
  4861.1  473.36  4901.1  471.86  4965.4  471.10  5001.8  470.55  5013.6  471.21
  5030.5  470.85  5058.6  470.82  5087.9  470.46  5088.4  469.66  5093.4  469.66
  5093.9  470.46  5120.5  470.71  5126.0  471.13  5143.2  471.10  5148.5  471.58
  5165.4  471.37  5171.0  472.15  5187.9  472.13  5193.5  472.39  5200.9  472.38
#Mann=3,-1,0
  4693.6    0.05       0  5087.9    0.03       0  5093.9    0.05       0
Bank Sta=4965.4,5143.2
Exp/Cntr=0.3,0.1

Type RM Length L Ch R = 1,6728,146,146,146
BEGIN DESCRIPTION:
XS4193A
END DESCRIPTION:
XS GIS Cut Line= 4
      2809029.93      7040321.56      2809078.55      7040028.11
      2809042.09      7039871.86      2808913.32      7039768.84
#Sta/Elev= 30
  4612.5  475.54  4629.3  475.53  4674.5  474.82  4710.4  473.98  4791.4  472.81
  4796.5  472.91  4909.0  470.03  4943.2  469.48  4974.8  469.54  4984.7  469.30
  4996.0  468.94  5026.1  468.62  5030.4  468.36  5030.9  467.56  5035.9  467.56
  5036.4  468.36  5038.5  468.72  5079.6  469.03  5082.2  469.30  5087.6  469.84
  5102.0  469.97  5116.4  469.57  5172.5  469.79  5186.9  470.06  5201.3  470.69
  5207.7  470.66  5215.7  471.25  5222.1  471.16  5230.1  471.98  5235.3  471.78
#Mann=3,-1,0
  4612.5    0.05       0  5030.4    0.03       0  5036.4    0.05       0
Bank Sta=4984.7,5082.2
Exp/Cntr=0.3,0.1

Type RM Length L Ch R = 1,6582,149,149,149
BEGIN DESCRIPTION:
XS4195A
END DESCRIPTION:
XS GIS Cut Line= 3
      2809245.20      7040074.96      2809147.99      7039821.51
      2808925.05      7039719.55
#Sta/Elev= 30
  4688.7  473.76  4698.6  473.66  4704.0  473.12  4720.8  472.78  4734.0  472.28
  4758.7  471.74  4788.7  471.37  4806.5  470.62  4950.2  468.05  4966.4  467.70
  4983.9  467.66  4996.4  467.22  5003.9  467.17  5004.4  466.37  5009.4  466.37
  5009.9  467.17  5046.5  468.05  5051.4  468.13  5058.4  468.67  5063.9  468.45
  5086.9  468.59  5095.4  468.87  5110.0  468.64  5127.5  469.12  5133.0  468.86
  5161.5  469.48  5179.0  470.28  5184.5  470.10  5202.0  470.38  5205.3  470.28
#Mann=3,-1,0
  4688.7    0.05       0  5003.9    0.03       0  5009.9    0.05       0
Bank Sta=4950.2,5046.5
Exp/Cntr=0.3,0.1

Type RM Length L Ch R = 1,6433,124,124,124
BEGIN DESCRIPTION:
XS4196A
END DESCRIPTION:
XS GIS Cut Line= 3
      2809380.63      7039925.68      2809200.07      7039672.21
      2808928.78      7039632.46
#Sta/Elev= 30
  4654.6  470.95  4702.9  469.60  4759.5  468.94  4765.9  468.63  4802.8  468.01
  4824.6  467.39  4845.5  467.26  4860.3  466.89  4866.4  467.01  4875.0  466.65
  4900.5  466.51  4910.7  466.26  4970.9  465.97  4983.6  466.07  4998.3  465.74
  4998.8  464.94  5003.8  464.94  5004.3  465.74  5011.4  465.99  5064.0  466.51
  5112.4  467.14  5123.3  467.03  5142.8  467.66  5152.9  467.61  5163.0  468.12
  5173.1  467.88  5188.1  467.97  5203.4  468.40  5223.6  468.71  5240.0  469.50
#Mann=3,-1,0
  4654.6    0.05       0  4998.3    0.03       0  5004.3    0.05       0
Bank Sta=4900.5,5064
Exp/Cntr=0.3,0.1

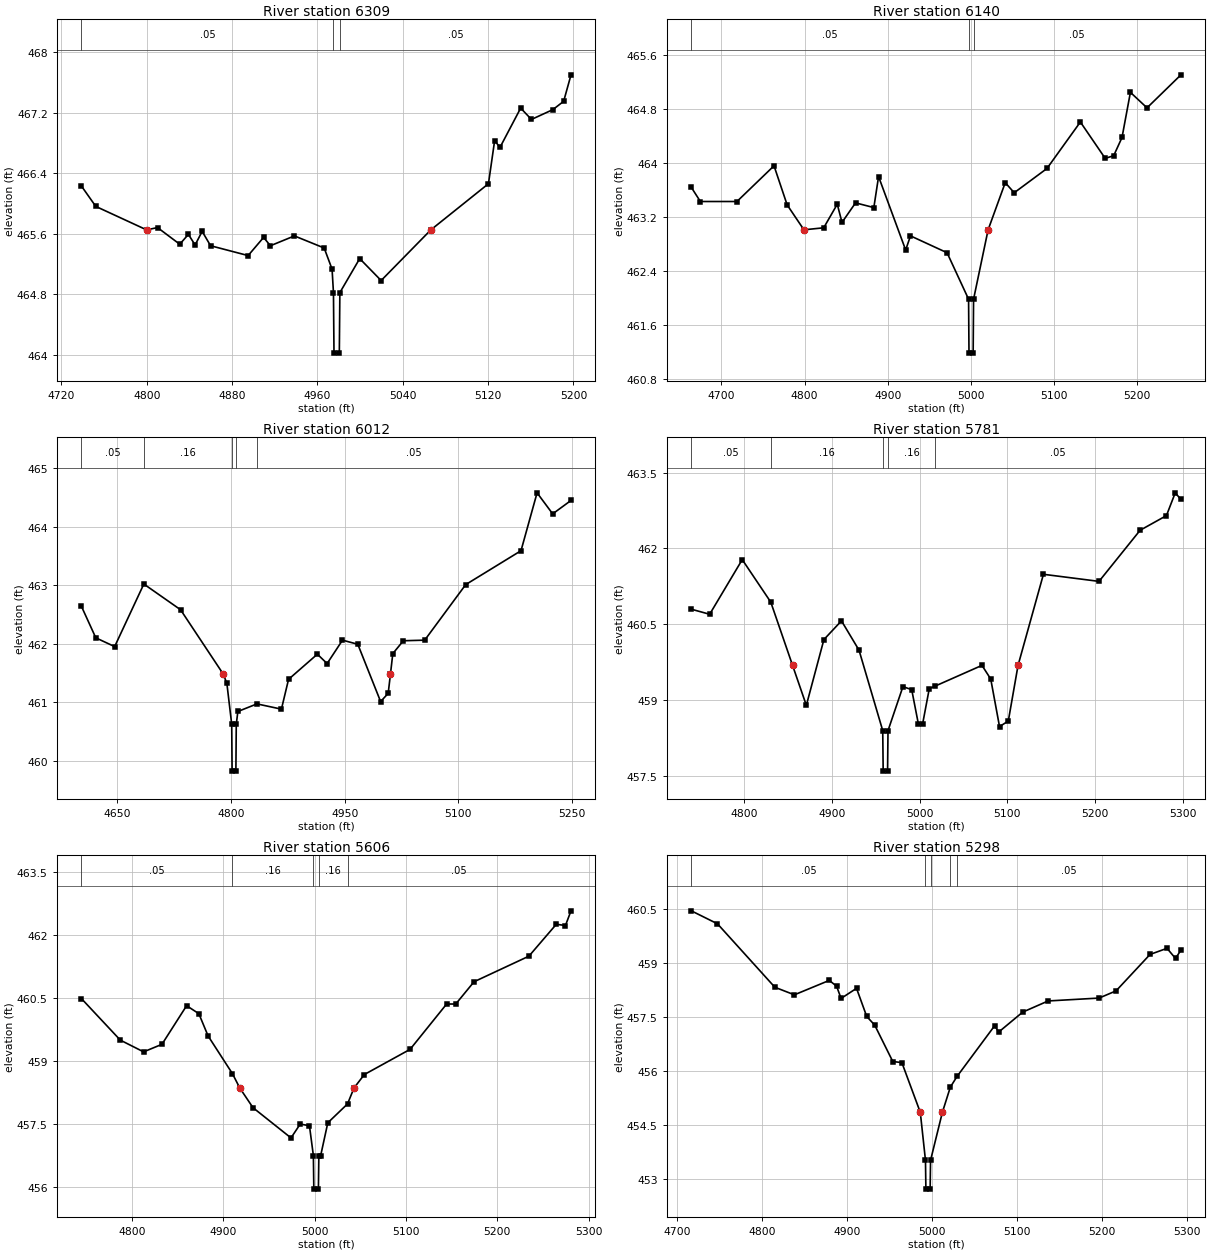
Type RM Length L Ch R = 1,6309,169,169,169
BEGIN DESCRIPTION:
XS4197A
END DESCRIPTION:
XS GIS Cut Line= 3
      2809374.11      7039695.63      2809183.15      7039545.90
      2808968.10      7039522.25
#Sta/Elev= 30
  4738.7  466.23  4752.2  465.96  4799.8  465.65  4810.1  465.68  4830.9  465.46
  4839.0  465.59  4845.3  465.45  4851.9  465.63  4859.8  465.44  4895.0  465.31
  4909.5  465.55  4915.9  465.44  4938.4  465.57  4966.3  465.41  4973.7  465.13
  4975.0  464.82  4975.5  464.02  4980.5  464.02  4981.0  464.82  4999.6  465.27
  5019.7  464.98  5066.3  465.65  5120.3  466.26  5126.1  466.83  5131.1  466.74
  5150.5  467.26  5160.6  467.11  5180.7  467.24  5190.8  467.35  5197.7  467.70
#Mann=3,-1,0
  4738.7    0.05       0  4975.0    0.03       0  4981.0    0.05       0
Bank Sta=4799.8,5066.3
Exp/Cntr=0.3,0.1

Type RM Length L Ch R = 1,6140,128,128,128
BEGIN DESCRIPTION:
XS4198A
END DESCRIPTION:
XS GIS Cut Line= 3
      2809512.99      7039543.29      2809210.93      7039383.58
      2808964.39      7039362.74
#Sta/Elev= 30
  4663.8  463.64  4674.7  463.43  4718.7  463.43  4763.3  463.96  4779.1  463.38
  4799.3  463.01  4823.1  463.04  4839.4  463.39  4845.1  463.12  4861.4  463.41
  4883.4  463.34  4889.1  463.80  4921.7  462.71  4927.5  462.92  4971.5  462.67
  4997.4  461.98  4997.9  461.18  5002.9  461.18  5003.4  461.98  5020.9  463.01
  5041.5  463.71  5052.3  463.56  5091.7  463.92  5131.9  464.61  5161.8  464.07
  5172.0  464.11  5182.0  464.38  5192.1  465.05  5212.1  464.82  5252.9  465.31
#Mann=3,-1,0
  4663.8    0.05       0  4997.4    0.03       0  5003.4    0.05       0
Bank Sta=4799.3,5020.9
Exp/Cntr=0.3,0.1

Type RM Length L Ch R = 1,6012,231,231,231
BEGIN DESCRIPTION:
XS4199A
END DESCRIPTION:
XS GIS Cut Line= 4
      2809613.69      7039328.02      2809263.01      7039262.05
      2809169.26      7039258.58      2808981.76      7039314.13
#Sta/Elev= 30
  4602.4  462.64  4621.4  462.10  4646.3  461.95  4684.8  463.02  4733.3  462.58
  4789.6  461.48  4794.4  461.32  4800.8  460.62  4801.3  459.82  4806.3  459.82
  4806.8  460.62  4808.9  460.84  4834.1  460.97  4866.4  460.88  4875.8  461.39
  4913.8  461.82  4926.7  461.66  4947.0  462.06  4967.2  461.99  4997.3  461.01
  5007.3  461.15  5010.3  461.48  5013.4  461.83  5027.3  462.05  5055.5  462.06
  5109.6  463.01  5182.6  463.59  5203.8  464.58  5224.4  464.22  5248.6  464.45
#Mann=5,-1,0
  4602.4    0.05       0  4684.8    0.16       0  4800.8    0.03       0
  4806.8    0.16       0  4834.1    0.05       0
Bank Sta=4789.6,5010.3
Exp/Cntr=0.3,0.1

Type RM Length L Ch R = 1,5781,175,175,175
BEGIN DESCRIPTION:
UNT 190 in LFCCL Watershed 15.0
END DESCRIPTION:
XS GIS Cut Line= 3
      2809585.92      7039081.49      2809325.00      7039075.00
      2809028.49      7039067.64
#Sta/Elev= 30
  4740.1  460.80  4761.0  460.70  4798.1  461.78  4830.6  460.94  4855.4  459.69
  4871.1  458.90  4891.1  460.20  4911.1  460.57  4931.1  459.99  4958.1  458.40
  4958.6  457.60  4963.6  457.60  4964.1  458.40  4981.1  459.27  4991.1  459.21
  4998.6  458.54  5003.6  458.54  5011.1  459.23  5017.7  459.28  5071.1  459.69
  5081.1  459.42  5091.1  458.48  5101.1  458.59  5112.2  459.69  5141.1  461.49
  5204.4  461.35  5251.2  462.36  5281.2  462.65  5291.2  463.10  5297.7  462.97
#Mann=5,-1,0
  4740.1    0.05       0  4830.6    0.16       0  4958.1    0.07       0
  4964.1    0.16       0  5017.7    0.05       0
Bank Sta=4855.4,5112.2
Exp/Cntr=0.3,0.1

Type RM Length L Ch R = 1,5606,308,308,308
BEGIN DESCRIPTION:
UNT 190 in LFCCL Watershed 14.0
END DESCRIPTION:
XS GIS Cut Line= 3
      2809582.45      7038935.66      2809325.51      7038900.94
      2809048.88      7038911.31
#Sta/Elev= 30
  4744.6  460.49  4787.2  459.50  4812.7  459.22  4832.8  459.40  4859.8  460.32
  4873.2  460.13  4883.3  459.60  4910.0  458.70  4918.0  458.36  4932.5  457.89
  4974.1  457.17  4984.2  457.50  4994.3  457.46  4998.6  456.75  4999.1  455.95
  5004.1  455.95  5004.6  456.75  5006.6  456.75  5014.4  457.53  5036.0  457.98
  5043.1  458.36  5054.4  458.68  5104.5  459.28  5144.5  460.36  5154.5  460.36
  5174.5  460.89  5234.6  461.50  5264.6  462.26  5274.6  462.23  5280.7  462.58
#Mann=5,-1,0
  4744.6    0.05       0  4910.0    0.16       0  4998.6    0.07       0
  5004.6    0.16       0  5036.0    0.05       0
Bank Sta=4918,5043.1
Exp/Cntr=0.3,0.1

Type RM Length L Ch R = 1,5298,192,192,192
BEGIN DESCRIPTION:
XS4200A
END DESCRIPTION:
XS GIS Cut Line= 3
      2809727.08      7038741.49      2809462.37      7038641.68
      2809168.65      7038635.20
#Sta/Elev= 30
  4716.7  460.45  4747.5  460.09  4815.1  458.33  4838.1  458.12  4879.2  458.52
  4887.8  458.36  4893.1  458.02  4911.3  458.30  4923.3  457.52  4932.7  457.28
  4954.0  456.27  4964.7  456.24  4986.4  454.86  4992.5  453.53  4993.0  452.73
  4998.0  452.73  4998.5  453.53  5012.4  454.86  5021.8  455.56  5029.8  455.86
  5073.9  457.26  5078.9  457.09  5107.0  457.64  5137.0  457.95  5197.0  458.03
  5217.0  458.23  5257.0  459.24  5277.0  459.41  5287.0  459.13  5293.4  459.36
#Mann=5,-1,0
  4716.7    0.05       0  4992.5    0.03       0  4998.5    0.05       0
  5021.8    0.16       0  5029.8    0.05       0
Bank Sta=4986.4,5012.4
Exp/Cntr=0.3,0.1

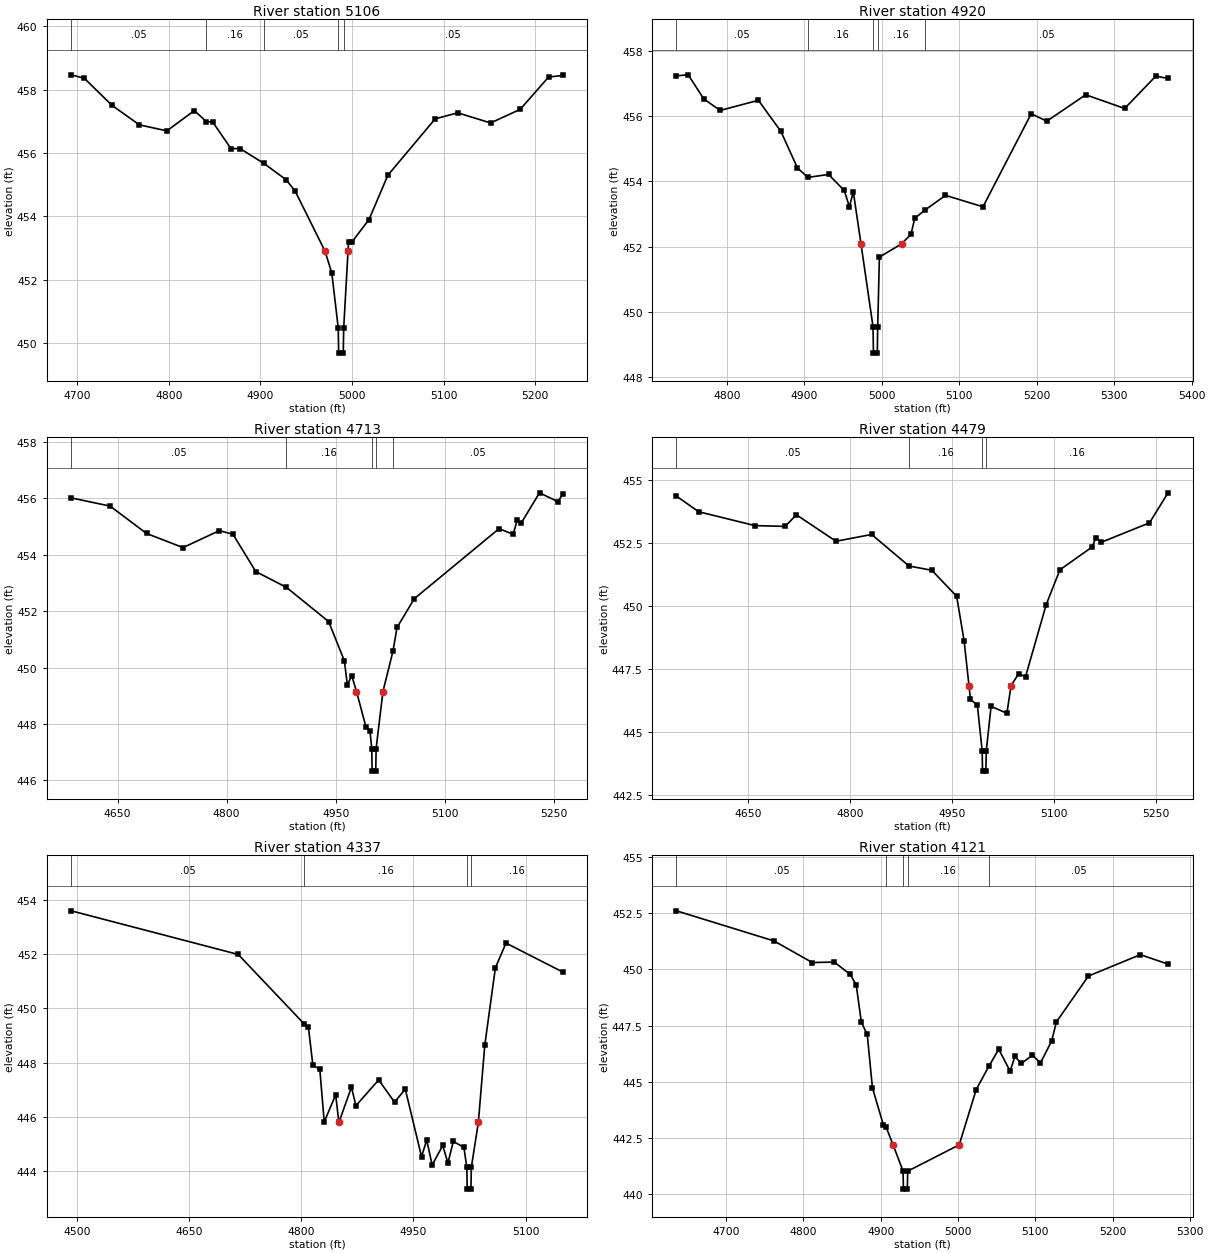
Type RM Length L Ch R = 1,5106,186,186,186
BEGIN DESCRIPTION:
XS4201A
END DESCRIPTION:
XS GIS Cut Line= 3
      2809729.26      7038496.28      2809423.31      7038491.94
      2809199.90      7038548.34
#Sta/Elev= 30
  4693.6  458.47  4707.9  458.36  4737.9  457.51  4767.9  456.89  4797.9  456.70
  4827.9  457.34  4841.1  456.99  4847.9  456.98  4867.9  456.14  4877.9  456.14
  4903.9  455.67  4927.9  455.16  4937.9  454.80  4970.5  452.90  4977.9  452.21
  4984.9  450.48  4985.4  449.68  4990.4  449.68  4990.9  450.48  4995.6  452.90
  4996.2  453.18  4999.6  453.18  5018.5  453.90  5039.1  455.30  5090.7  457.08
  5115.3  457.27  5151.2  456.95  5183.5  457.38  5214.4  458.40  5230.0  458.45
#Mann=5,-1,0
  4693.6    0.05       0  4841.1    0.16       0  4903.9    0.05       0
  4984.9    0.03       0  4990.9    0.05       0
Bank Sta=4970.5,4995.6
Exp/Cntr=0.3,0.1

Type RM Length L Ch R = 1,4920,207,207,207
BEGIN DESCRIPTION:
XS4202A
END DESCRIPTION:
XS GIS Cut Line= 3
      2809740.11      7038366.07      2809479.73      7038335.69
      2809109.33      7038374.68
#Sta/Elev= 30
  4734.9  457.23  4750.1  457.26  4770.3  456.52  4791.3  456.17  4840.7  456.48
  4869.7  455.53  4891.1  454.41  4904.5  454.12  4931.3  454.21  4951.5  453.72
  4958.2  453.22  4963.2  453.68  4973.1  452.09  4988.7  449.54  4989.2  448.74
  4994.2  448.74  4994.7  449.54  4996.9  451.68  5025.8  452.09  5037.6  452.38
  5042.6  452.87  5055.8  453.12  5082.2  453.57  5130.6  453.22  5192.9  456.07
  5213.0  455.84  5263.2  456.65  5313.5  456.23  5353.7  457.22  5369.5  457.15
#Mann=5,-1,0
  4734.9    0.05       0  4904.5    0.16       0  4988.7    0.07       0
  4994.7    0.16       0  5055.8    0.05       0
Bank Sta=4973.1,5025.8
Exp/Cntr=0.3,0.1

Type RM Length L Ch R = 1,4713,234,234,234
BEGIN DESCRIPTION:
XS4203A
END DESCRIPTION:
XS GIS Cut Line= 3
      2809768.40      7038205.48      2809388.59      7038179.44
      2809110.82      7038281.43
#Sta/Elev= 30
  4586.1  456.01  4639.6  455.72  4689.7  454.75  4739.9  454.25  4790.0  454.85
  4808.7  454.72  4840.1  453.40  4882.3  452.84  4940.3  451.63  4962.0  450.24
  4966.1  449.39  4972.2  449.71  4978.7  449.15  4991.9  447.88  4997.3  447.75
  4999.7  447.13  5000.2  446.33  5005.2  446.33  5005.7  447.13  5015.1  449.15
  5028.9  450.58  5034.5  451.42  5058.3  452.44  5174.9  454.92  5194.3  454.72
  5200.1  455.24  5205.4  455.12  5230.6  456.19  5255.7  455.88  5262.7  456.14
#Mann=5,-1,0
  4586.1    0.05       0  4882.3    0.16       0  4999.7    0.07       0
  5005.7    0.16       0  5028.9    0.05       0
Bank Sta=4978.7,5015.1
Exp/Cntr=0.3,0.1

Type RM Length L Ch R = 1,4479,142,142,142
BEGIN DESCRIPTION:
XS4204A
END DESCRIPTION:
XS GIS Cut Line= 3
      2809753.19      7038172.94      2809410.29      7037994.98
      2809078.03      7037943.20
#Sta/Elev= 30
  4545.1  454.36  4577.8  453.74  4660.7  453.19  4704.9  453.16  4721.4  453.62
  4779.7  452.57  4832.0  452.84  4886.9  451.59  4920.5  451.42  4957.0  450.39
  4968.0  448.61  4975.1  446.85  4977.3  446.30  4987.4  446.08  4994.5  444.26
  4995.0  443.46  5000.0  443.46  5000.5  444.26  5007.6  446.03  5030.8  445.75
  5037.0  446.85  5048.1  447.32  5058.2  447.20  5088.6  450.06  5108.8  451.44
  5156.5  452.35  5161.5  452.71  5169.6  452.53  5240.4  453.30  5267.7  454.49
#Mann=4,-1,0
  4545.1    0.05       0  4886.9    0.16       0  4994.5    0.07       0
  5000.5    0.16       0
Bank Sta=4975.1,5037
Exp/Cntr=0.3,0.1

Type RM Length L Ch R = 1,4337,216,216,216
BEGIN DESCRIPTION:
XS4205A
END DESCRIPTION:
XS GIS Cut Line= 3
      2809785.69      7038131.68      2809408.12      7037890.81
      2809263.23      7037739.44
#Sta/Elev= 30
  4492.4  453.60  4715.7  451.99  4804.1  449.42  4809.6  449.30  4815.5  447.91
  4824.8  447.75  4830.7  445.81  4846.0  446.81  4850.3  445.79  4867.1  447.09
  4873.1  446.41  4903.5  447.36  4924.7  446.54  4939.1  447.02  4960.8  444.53
  4967.8  445.14  4975.0  444.22  4989.2  444.94  4996.1  444.29  5003.3  445.09
  5017.5  444.87  5021.4  444.13  5021.9  443.33  5026.9  443.33  5027.4  444.13
  5036.8  445.79  5045.4  448.64  5059.6  451.50  5073.8  452.41  5149.8  451.34
#Mann=4,-1,0
  4492.4    0.05       0  4804.1    0.16       0  5021.4    0.07       0
  5027.4    0.16       0
Bank Sta=4850.3,5036.8
Exp/Cntr=0.3,0.1

Type RM Length L Ch R = 1,4121,187,187,187
BEGIN DESCRIPTION:
XS4206A
END DESCRIPTION:
XS GIS Cut Line= 4
      2809811.78      7038086.14      2809542.67      7037847.41
      2809488.41      7037773.62      2809440.66      7037595.64
#Sta/Elev= 30
  4635.9  452.61  4762.1  451.27  4811.5  450.31  4839.9  450.33  4860.8  449.78
  4868.4  449.30  4875.0  447.65  4882.6  447.11  4889.3  444.74  4903.5  443.08
  4907.1  442.98  4916.0  442.20  4928.9  441.03  4929.4  440.23  4934.4  440.23
  4934.9  441.03  5001.5  442.20  5023.5  444.66  5039.9  445.70  5052.6  446.45
  5067.3  445.48  5073.5  446.13  5081.9  445.82  5096.2  446.19  5106.5  445.84
  5120.9  446.81  5127.2  447.67  5168.6  449.71  5235.7  450.66  5271.5  450.24
#Mann=5,-1,0
  4635.9    0.05       0  4907.1    0.16       0  4928.9    0.07       0
  4934.9    0.16       0  5039.9    0.05       0
Bank Sta=4916,5001.5
Exp/Cntr=0.3,0.1

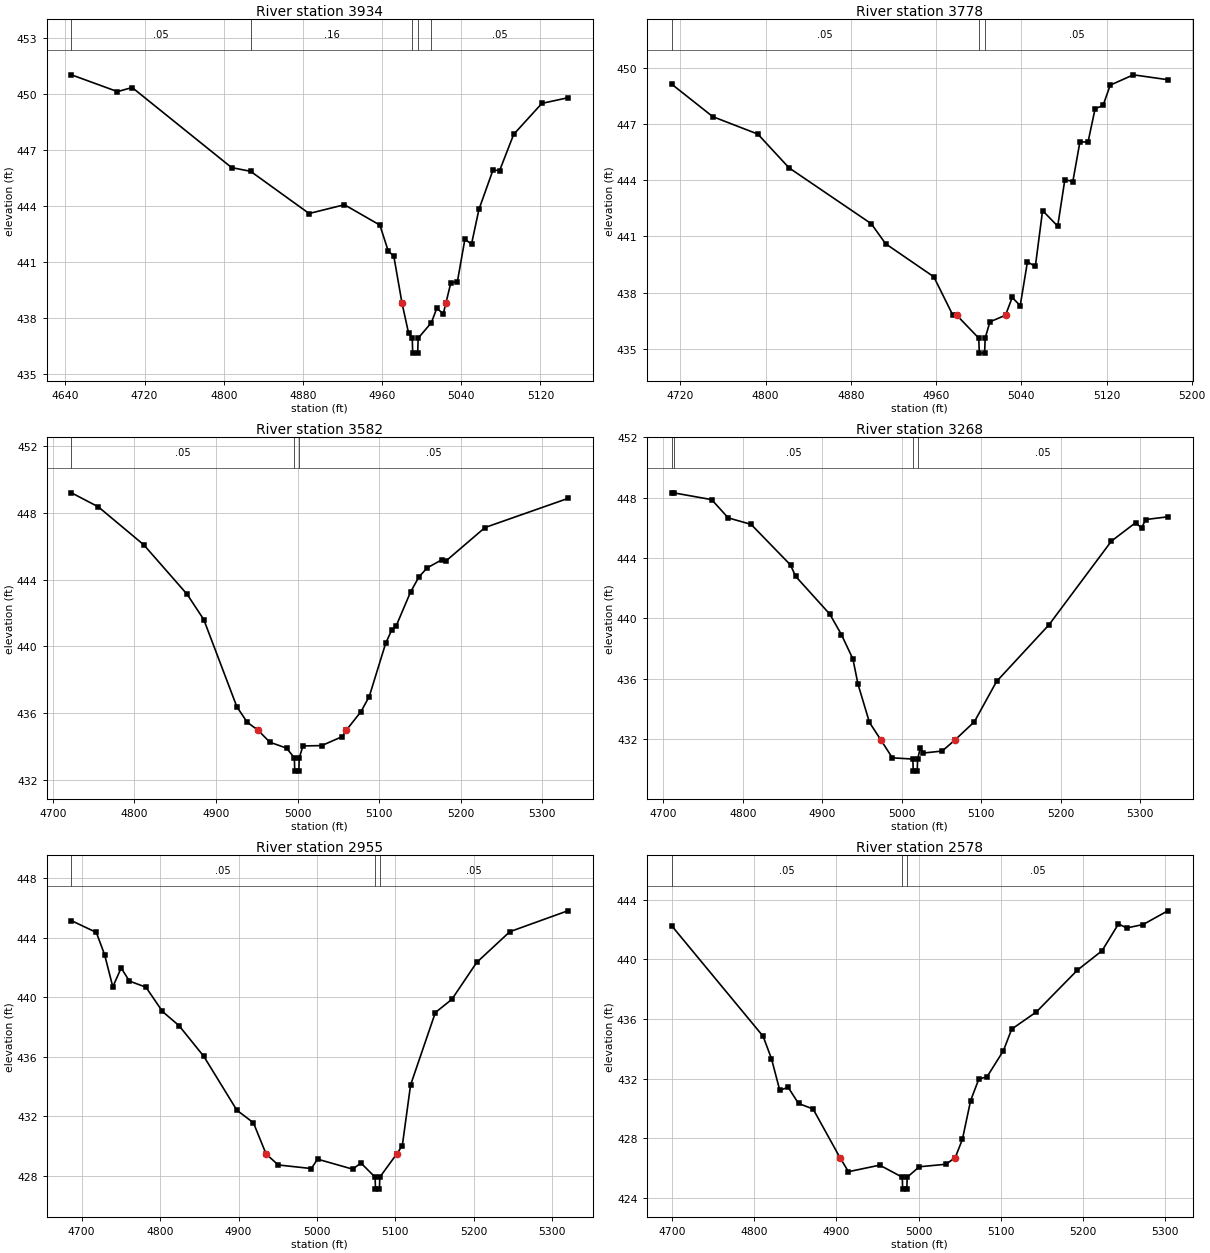
Type RM Length L Ch R = 1,3934,156,156,156
BEGIN DESCRIPTION:
XS4207A
END DESCRIPTION:
XS GIS Cut Line= 3
      2809826.94      7037977.60      2809640.32      7037710.69
      2809523.85      7037579.12
#Sta/Elev= 30
  4646.2  451.02  4692.7  450.12  4707.5  450.34  4808.0  446.05  4827.2  445.85
  4886.3  443.59  4922.0  444.06  4957.8  442.97  4966.2  441.59  4971.9  441.30
  4980.1  438.81  4986.8  437.18  4990.5  436.91  4991.0  436.11  4996.0  436.11
  4996.5  436.91  5009.8  437.74  5015.3  438.51  5021.9  438.22  5024.6  438.81
  5029.5  439.88  5036.1  439.93  5043.7  442.21  5050.4  441.95  5057.9  443.81
  5072.1  445.92  5078.8  445.89  5093.0  447.83  5121.5  449.49  5147.6  449.79
#Mann=5,-1,0
  4646.2    0.05       0  4827.2    0.16       0  4990.5    0.07       0
  4996.5    0.16       0  5009.8    0.05       0
Bank Sta=4980.1,5024.6
Exp/Cntr=0.3,0.1

Type RM Length L Ch R = 1,3778,196,196,196
BEGIN DESCRIPTION:
XS4208A
END DESCRIPTION:
XS GIS Cut Line= 3
      2809872.53      7037890.82      2809770.53      7037643.42
      2809623.00      7037511.07
#Sta/Elev= 30
  4711.7  449.12  4750.4  447.38  4792.7  446.45  4822.0  444.65  4899.2  441.67
  4912.7  440.60  4957.9  438.84  4975.7  436.80  4979.4  436.79  5000.1  435.57
  5000.6  434.77  5005.6  434.77  5006.1  435.57  5010.6  436.44  5025.2  436.79
  5031.5  437.74  5039.0  437.30  5045.8  439.64  5053.2  439.39  5060.0  442.37
  5074.2  441.54  5080.9  444.02  5088.4  443.92  5095.1  446.05  5102.6  446.01
  5109.3  447.80  5116.8  447.98  5123.5  449.06  5145.2  449.61  5177.5  449.35
#Mann=3,-1,0
  4711.7    0.05       0  5000.1    0.03       0  5006.1    0.05       0
Bank Sta=4979.4,5025.2
Exp/Cntr=0.3,0.1

Type RM Length L Ch R = 1,3582,314,314,314
BEGIN DESCRIPTION:
UNT 190 in LFCCL Watershed 9.0
END DESCRIPTION:
XS GIS Cut Line= 3
      2809975.00      7037824.99      2809925.00      7037525.00
      2809624.96      7037474.99
#Sta/Elev= 30
  4722.9  449.21  4755.8  448.37  4811.6  446.09  4864.8  443.12  4885.1  441.61
  4925.6  436.39  4938.3  435.46  4951.6  434.98  4966.2  434.26  4986.5  433.91
  4996.1  433.33  4996.6  432.53  5001.6  432.53  5002.1  433.33  5006.7  434.04
  5029.6  434.06  5054.9  434.60  5059.7  434.98  5077.7  436.09  5087.9  437.00
  5108.1  440.20  5115.7  441.01  5120.8  441.22  5138.5  443.26  5148.7  444.16
  5158.8  444.71  5176.6  445.19  5181.6  445.11  5229.8  447.13  5331.2  448.87
#Mann=3,-1,0
  4722.9    0.05       0  4996.1    0.03       0  5002.1    0.05       0
Bank Sta=4951.6,5059.7
Exp/Cntr=0.3,0.1

Type RM Length L Ch R = 1,3268,313,313,313
BEGIN DESCRIPTION:
UNT 190 in LFCCL Watershed 8.0
END DESCRIPTION:
XS GIS Cut Line= 3
      2810275.03      7037525.04      2810075.00      7037275.00
      2809775.04      7037225.01
#Sta/Elev= 30
  4710.4  448.32  4714.0  448.31  4760.9  447.87  4781.7  446.66  4810.5  446.23
  4860.1  443.54  4866.5  442.79  4909.7  440.27  4924.2  438.92  4938.6  437.31
  4945.0  435.64  4959.4  433.11  4974.1  431.92  4988.2  430.76  5014.0  430.68
  5014.5  429.88  5019.5  429.88  5020.0  430.68  5023.4  431.41  5027.4  431.08
  5050.9  431.21  5066.5  431.92  5091.4  433.15  5119.3  435.82  5185.2  439.57
  5263.8  445.12  5294.2  446.34  5301.8  445.99  5306.9  446.55  5334.7  446.73
#Mann=4,-1,0
  4710.4    0.08       0  4714.0    0.05       0  5014.0    0.03       0
  5020.0    0.05       0
Bank Sta=4974.1,5066.5
Exp/Cntr=0.3,0.1

Type RM Length L Ch R = 1,2955,377,377,377
BEGIN DESCRIPTION:
UNT 190 in LFCCL Watershed 7.0
END DESCRIPTION:
XS GIS Cut Line= 3
      2810475.03      7037125.01      2810175.00      7037025.00
      2809874.98      7036924.99
#Sta/Elev= 30
  4687.1  445.13  4718.8  444.34  4729.3  442.85  4739.8  440.69  4750.4  441.96
  4760.9  441.08  4782.0  440.67  4803.1  439.04  4824.2  438.09  4855.8  436.03
  4897.9  432.42  4919.0  431.58  4935.2  429.48  4950.7  428.75  4992.8  428.51
  5000.7  429.14  5045.5  428.47  5056.1  428.88  5074.1  427.93  5074.6  427.13
  5079.6  427.13  5080.1  427.93  5101.5  429.48  5108.8  430.05  5119.3  434.11
  5150.9  438.97  5172.0  439.86  5203.6  442.33  5245.8  444.39  5319.6  445.79
#Mann=3,-1,0
  4687.1    0.05       0  5074.1    0.03       0  5080.1    0.05       0
Bank Sta=4935.2,5101.5
Exp/Cntr=0.3,0.1

Type RM Length L Ch R = 1,2578,317,317,317
BEGIN DESCRIPTION:
UNT 190 in LFCCL Watershed 6.0
END DESCRIPTION:
XS GIS Cut Line= 3
      2810575.00      7036725.00      2810275.00      7036675.00
      2809975.04      7036675.00
#Sta/Elev= 30
  4699.2  442.27  4810.7  434.84  4820.9  433.33  4831.0  431.21  4841.1  431.42
  4853.8  430.33  4871.5  429.96  4904.2  426.70  4914.6  425.75  4952.7  426.19
  4980.1  425.38  4980.6  424.58  4985.6  424.58  4986.1  425.38  5000.8  426.08
  5033.3  426.25  5044.6  426.70  5053.3  427.92  5063.3  430.52  5073.3  431.97
  5083.3  432.12  5103.3  433.88  5113.3  435.32  5143.3  436.47  5193.3  439.28
  5223.3  440.58  5243.3  442.38  5253.3  442.11  5273.3  442.34  5303.3  443.26
#Mann=3,-1,0
  4699.2    0.05       0  4980.1    0.03       0  4986.1    0.05       0
Bank Sta=4904.2,5044.6
Exp/Cntr=0.3,0.1

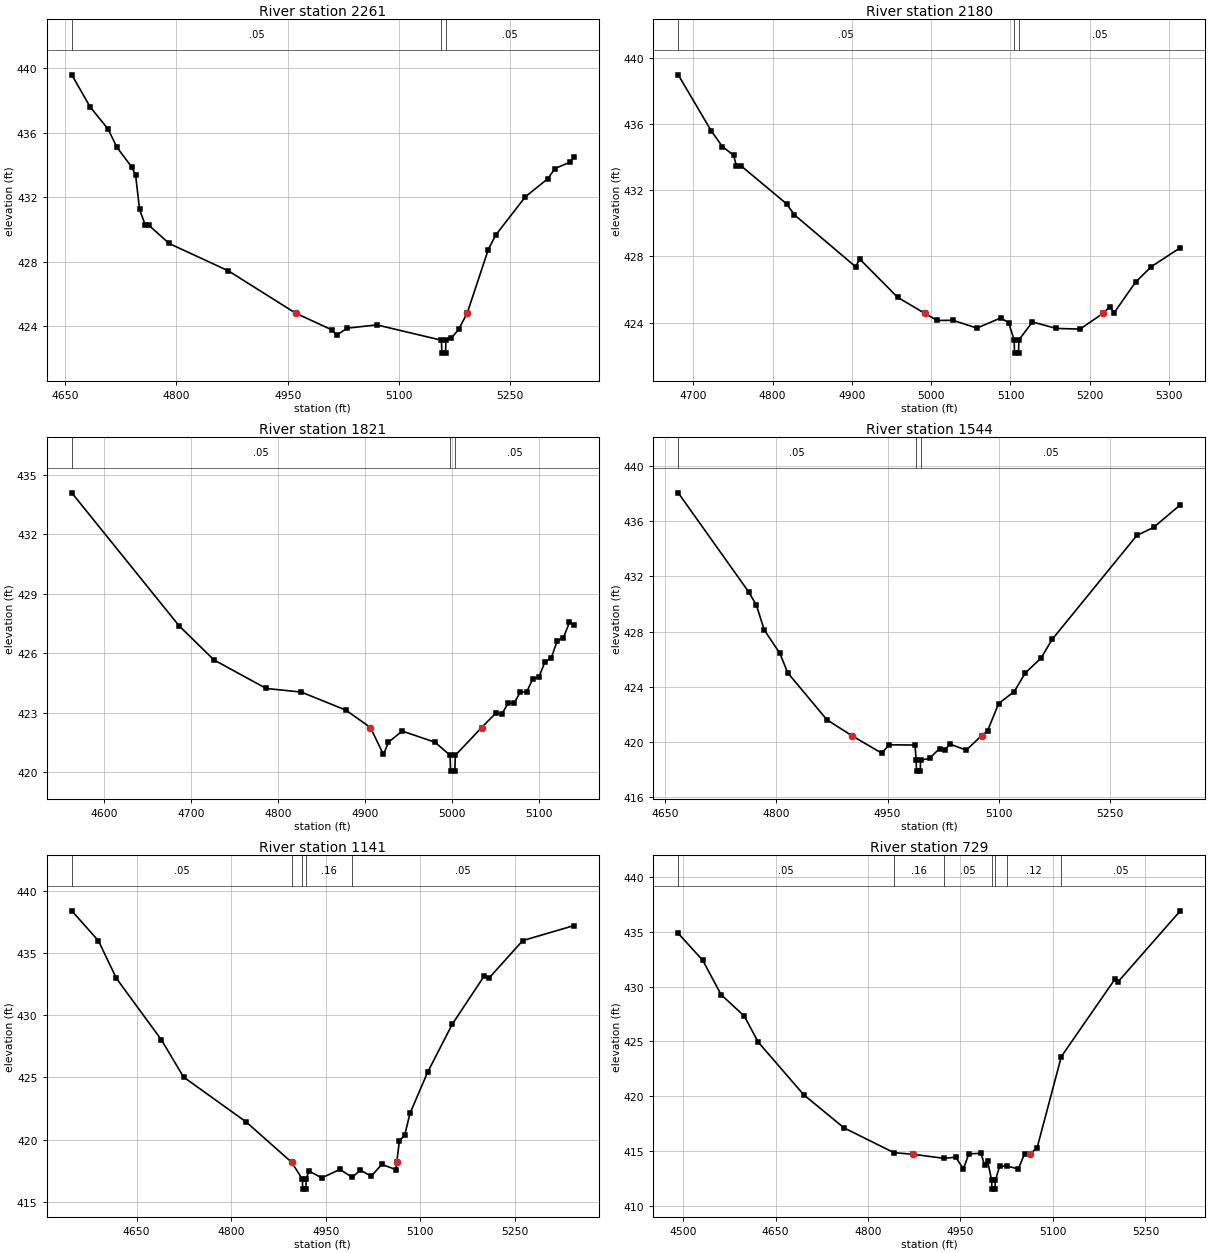
Type RM Length L Ch R = 1,2261,81,81,81
BEGIN DESCRIPTION:
XS4209A
END DESCRIPTION:
XS GIS Cut Line= 4
      2810540.92      7036699.40      2810445.45      7036664.68
      2810441.10      7036430.31      2810423.75      7036089.76
#Sta/Elev= 30
  4658.8  439.59  4683.7  437.59  4707.7  436.23  4719.6  435.10  4739.5  433.88
  4744.9  433.37  4750.2  431.24  4758.0  430.26  4762.7  430.26  4790.1  429.13
  4870.1  427.43  4960.6  424.81  5010.1  423.76  5015.8  423.44  5030.2  423.88
  5070.2  424.08  5157.3  423.13  5157.8  422.33  5162.8  422.33  5163.3  423.13
  5170.3  423.25  5180.4  423.80  5192.0  424.81  5220.4  428.75  5230.4  429.65
  5270.5  432.03  5300.5  433.14  5310.5  433.78  5330.5  434.17  5335.8  434.50
#Mann=3,-1,0
  4658.8    0.05       0  5157.3    0.04       0  5163.3    0.05       0
Bank Sta=4960.6,5192
Exp/Cntr=0.3,0.1

Type RM Length L Ch R = 1,2180,359,359,359
BEGIN DESCRIPTION:
XS4210A
END DESCRIPTION:
XS GIS Cut Line= 3
      2810547.46      7036671.21      2810495.36      7036614.77
      2810512.67      7036058.55
#Sta/Elev= 30
  4680.9  438.96  4722.4  435.59  4736.6  434.63  4750.7  434.11  4754.3  433.47
  4760.1  433.47  4817.5  431.18  4827.5  430.51  4904.7  427.38  4909.7  427.85
  4957.6  425.54  4991.8  424.57  5007.6  424.14  5027.6  424.15  5057.6  423.68
  5087.6  424.29  5097.6  424.01  5104.6  422.97  5105.1  422.17  5110.1  422.17
  5110.6  422.97  5127.7  424.05  5157.7  423.66  5187.7  423.62  5216.8  424.57
  5225.5  424.98  5230.5  424.59  5257.7  426.45  5277.7  427.39  5314.2  428.53
#Mann=3,-1,0
  4680.9    0.05       0  5104.6    0.04       0  5110.6    0.05       0
Bank Sta=4991.8,5216.8
Exp/Cntr=0.3,0.1

Type RM Length L Ch R = 1,1821,277,277,277
BEGIN DESCRIPTION:
XS4211A
END DESCRIPTION:
XS GIS Cut Line= 4
      2810686.33      7036478.04      2810708.03      7036174.23
      2810645.10      7036063.55      2810544.45      7035958.62
#Sta/Elev= 30
  4562.6  434.10  4686.0  427.39  4726.1  425.67  4786.2  424.23  4826.3  424.05
  4877.7  423.14  4906.0  422.26  4921.0  420.90  4926.7  421.52  4942.6  422.08
  4980.1  421.52  4997.6  420.86  4998.1  420.06  5003.1  420.06  5003.6  420.86
  5034.0  422.26  5050.0  422.98  5057.3  422.95  5064.2  423.48  5071.4  423.50
  5078.3  424.05  5085.6  424.05  5092.5  424.70  5099.7  424.80  5106.6  425.56
  5113.9  425.77  5120.8  426.63  5128.0  426.79  5134.9  427.58  5139.9  427.42
#Mann=3,-1,0
  4562.6    0.05       0  4997.6    0.03       0  5003.6    0.05       0
Bank Sta=4906,5034
Exp/Cntr=0.3,0.1

Type RM Length L Ch R = 1,1544,403,403,403
BEGIN DESCRIPTION:
UNT 190 in LFCCL Watershed 3.0
END DESCRIPTION:
XS GIS Cut Line= 3
      2810925.00      7036175.00      2810825.00      7035875.00
      2810624.99      7035574.98
#Sta/Elev= 30
  4667.8  438.06  4762.7  430.88  4773.2  429.91  4783.7  428.12  4804.8  426.42
  4815.4  425.01  4868.1  421.61  4901.8  420.45  4941.9  419.19  4952.4  419.79
  4987.0  419.77  4988.5  418.68  4989.0  417.88  4994.0  417.88  4994.5  418.68
  5006.6  418.80  5020.1  419.52  5027.6  419.40  5033.6  419.85  5056.1  419.40
  5076.6  420.45  5084.7  420.79  5099.7  422.78  5120.7  423.65  5135.8  425.01
  5156.8  426.07  5171.8  427.43  5286.0  434.97  5308.5  435.55  5344.6  437.19
#Mann=3,-1,0
  4667.8    0.05       0  4988.5    0.03       0  4994.5    0.05       0
Bank Sta=4901.8,5076.6
Exp/Cntr=0.3,0.1

Type RM Length L Ch R = 1,1141,412,412,412
BEGIN DESCRIPTION:
UNT 190 in LFCCL Watershed 2.0
END DESCRIPTION:
XS GIS Cut Line= 3
      2811425.03      7035975.02      2811075.00      7035675.00
      2810925.01      7035375.02
#Sta/Elev= 30
  4547.3  438.39  4589.6  435.98  4618.1  432.96  4689.5  428.02  4724.6  425.03
  4823.9  421.42  4896.0  418.18  4896.1  418.17  4913.1  416.82  4913.6  416.02
  4918.6  416.02  4919.1  416.82  4923.3  417.47  4944.1  416.93  4972.6  417.60
  4992.3  416.97  5005.0  417.55  5022.3  417.05  5039.1  418.01  5061.4  417.59
  5062.8  418.17  5067.0  419.91  5075.4  420.36  5083.8  422.11  5111.7  425.41
  5150.9  429.28  5201.2  433.13  5209.6  433.01  5262.7  436.00  5343.7  437.20
#Mann=5,-1,0
  4547.3    0.05       0  4896.0    0.16       0  4913.1    0.03       0
  4919.1    0.16       0  4992.3    0.05       0
Bank Sta=4896.1,5062.8
Exp/Cntr=0.3,0.1

Type RM Length L Ch R = 1,729,0,0,0
BEGIN DESCRIPTION:
UNT 190 in LFCCL Watershed 1.0
END DESCRIPTION:
XS GIS Cut Line= 3
      2811474.99      7035874.99      2811300.38      7035421.66
      2810975.01      7035375.00
#Sta/Elev= 30
  4492.1  434.86  4531.7  432.41  4561.7  429.26  4599.2  427.31  4621.7  424.94
  4695.5  420.13  4760.9  417.10  4842.0  414.83  4873.7  414.68  4923.6  414.31
  4942.2  414.42  4954.7  413.36  4963.6  414.72  4983.3  414.77  4989.0  413.69
  4994.0  414.06  5000.5  412.30  5001.0  411.50  5006.0  411.50  5006.5  412.30
  5013.6  413.60  5025.4  413.61  5043.9  413.34  5054.0  414.75  5062.2  414.68
  5074.3  415.28  5113.6  423.61  5200.7  430.69  5205.8  430.45  5306.6  436.92
#Mann=7,-1,0
  4492.1    0.05       0  4842.0    0.16       0  4923.6    0.05       0
  5000.5    0.03       0  5006.5    0.05       0  5025.4    0.12       0
  5113.6    0.05       0
Bank Sta=4873.7,5062.2
Exp/Cntr=0.3,0.1

Chan Stop Cuts=-1