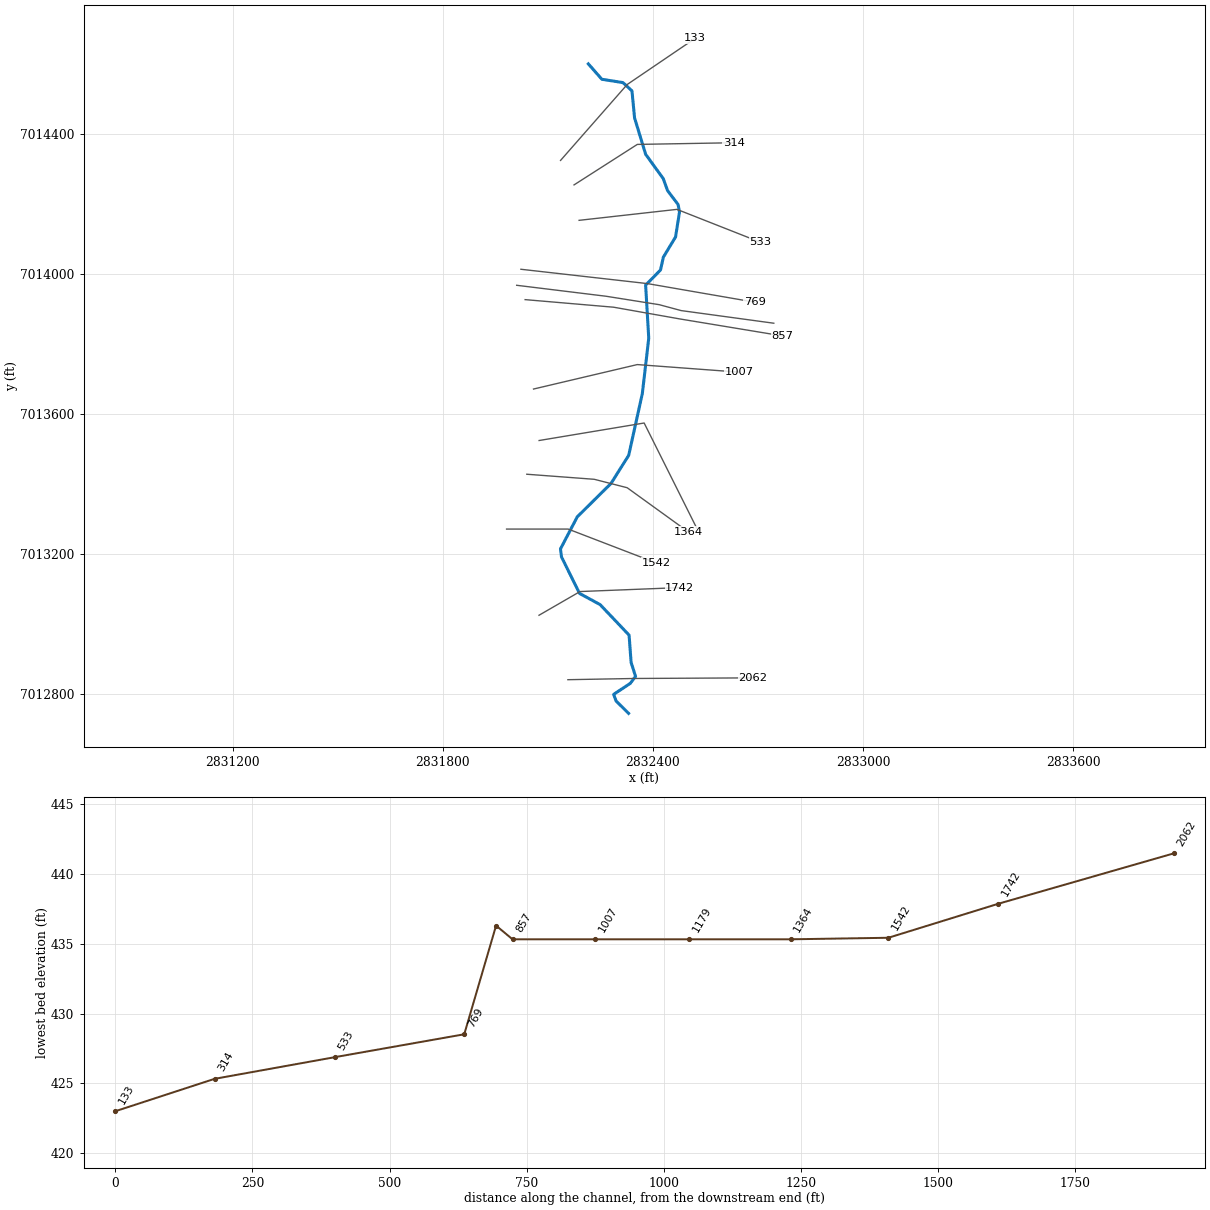
--- UNT 193 in LFCCL Watershed.prj (project) ---

Proj Title=UNT 193 in LFCCL Watershed Base Level Engineering
Current Plan=p01
Default Exp/Contr=0.3,0.1
English Units
Geom File=g01
Flow File=f01
Plan File=p01
BEGIN DESCRIPTION:
UNT 193 in LFCCL Watershed
END DESCRIPTION:

--- UNT 193 in LFCCL Watershed.p01 (plan) ---

Plan Title=Multiple Run
Short Identifier=Multiple
Geom File=g01
Flow File=f01
Subcritical Flow
K Sum by GR= 0
Std Step Tol= 0.01
Critical Tol= 0.01
Num of Std Step Trials= 20
Max Error Tol= 0.3
Flow Tol Ratio= 0.001
Split Flow NTrial= 30
Split Flow Tol= 0.02
Split Flow Ratio= 0.02
Log Output Level= 0
Friction Slope Method= 1
Unsteady Friction Slope Method= 2
Unsteady Bridges Friction Slope Method= 1
Parabolic Critical Depth
Global Vel Dist=  1 , 1 , 1
Global Log Level= 0
CheckData=True
Encroach Param= -1, 0, 0, 0
BEGIN DESCRIPTION:
Multiple Run
END DESCRIPTION:

--- UNT 193 in LFCCL Watershed.f01 (steady flow) ---

Flow Title=Multiple
Number of Profiles=7
Profile Names=10-year,25-year,50-year,1pct_min,100-year,1pct_plu,500-year
River Rch & RM= UNT 193 in LFCCL,Reach-1,2062
     174     216     247     141     282     562     366
Boundary for River Rch & Prof#=UNT 193 in LFCCL,Reach-1,1
Up Type=0
Dn Type=3
Dn Slope=0.005
Boundary for River Rch & Prof#=UNT 193 in LFCCL,Reach-1,2
Up Type=0
Dn Type=3
Dn Slope=0.005
Boundary for River Rch & Prof#=UNT 193 in LFCCL,Reach-1,3
Up Type=0
Dn Type=3
Dn Slope=0.005
Boundary for River Rch & Prof#=UNT 193 in LFCCL,Reach-1,4
Up Type=0
Dn Type=3
Dn Slope=0.005
Boundary for River Rch & Prof#=UNT 193 in LFCCL,Reach-1,5
Up Type=0
Dn Type=3
Dn Slope=0.005
Boundary for River Rch & Prof#=UNT 193 in LFCCL,Reach-1,6
Up Type=0
Dn Type=3
Dn Slope=0.005
Boundary for River Rch & Prof#=UNT 193 in LFCCL,Reach-1,7
Up Type=0
Dn Type=3
Dn Slope=0.005

--- UNT 193 in LFCCL Watershed.g01 (geometry) ---

Geom Title=Existing Conditions

River Reach=UNT 193 in LFCCL,Reach-1
Reach XY= 30
      2832330.59      7012745.71      2832294.99      7012781.01
      2832287.83      7012799.89      2832335.46      7012831.52
      2832350.48      7012851.33      2832337.78      7012891.16
      2832332.00      7012969.21      2832249.13      7013056.45
      2832190.52      7013088.18      2832139.01      7013192.48
      2832136.05      7013215.44      2832183.99      7013306.97
      2832280.45      7013402.42      2832330.86      7013482.63
      2832369.82      7013659.10      2832388.16      7013817.23
      2832379.24      7013968.67      2832421.67      7014011.91
      2832429.93      7014048.83      2832464.65      7014106.16
      2832475.95      7014177.31      2832471.96      7014199.08
      2832441.92      7014238.60      2832429.55      7014272.92
      2832379.35      7014342.27      2832347.66      7014446.30
      2832340.23      7014523.55      2832314.50      7014547.17
      2832254.18      7014556.68      2832215.59      7014600.71

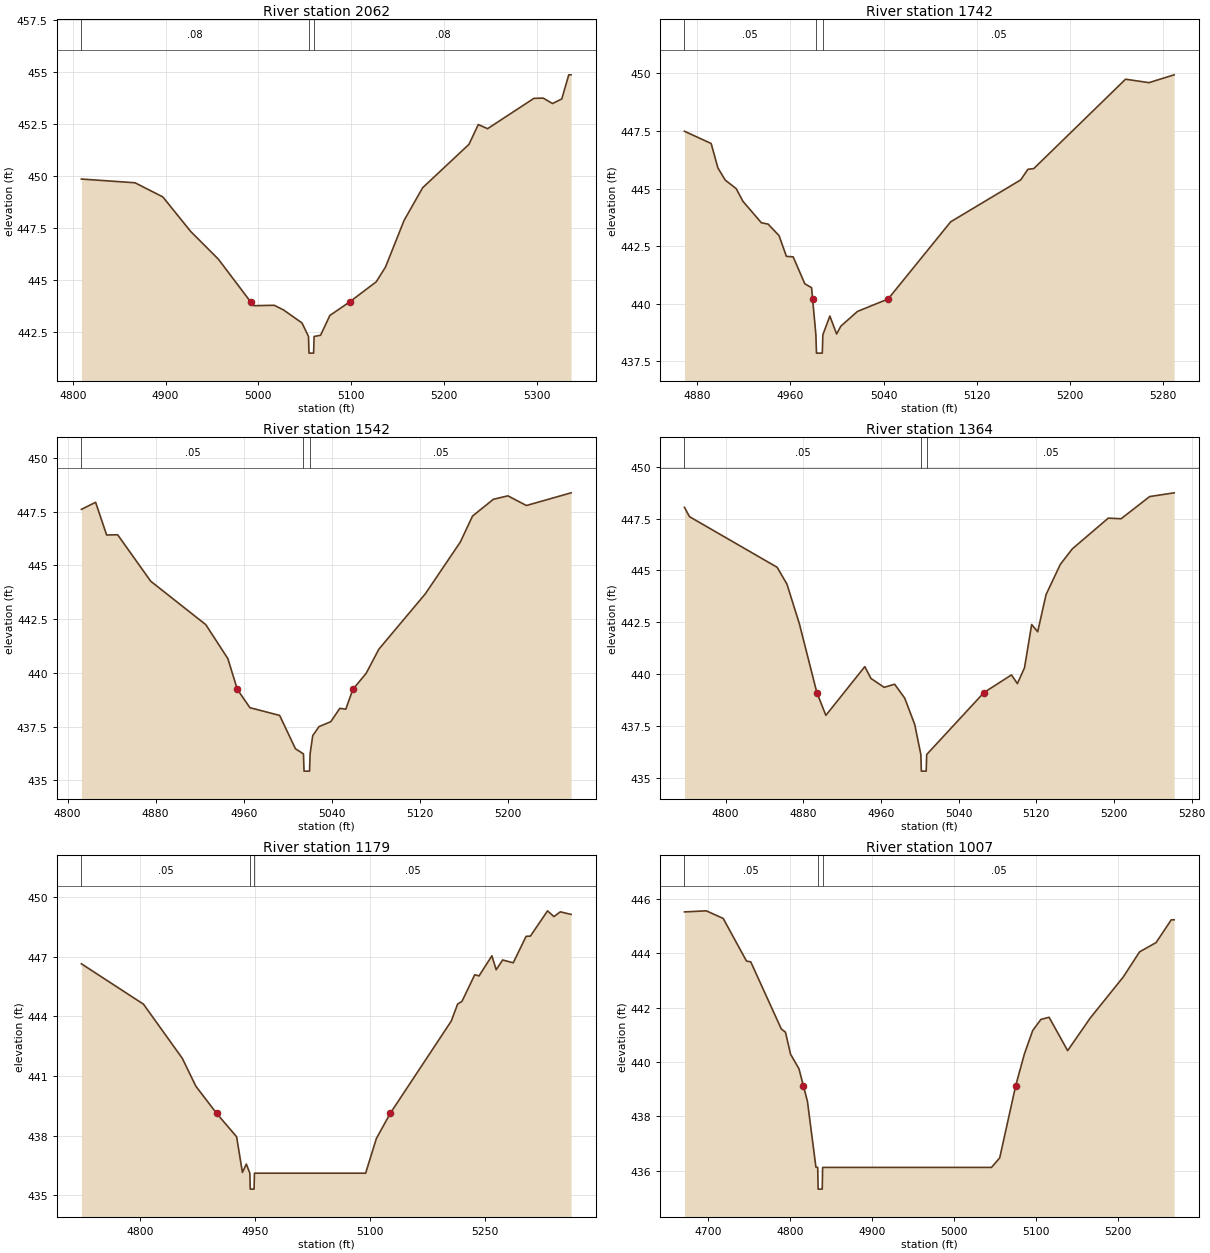
Type RM Length L Ch R = 1,2062,320,320,320
BEGIN DESCRIPTION:
Mapping XS 2c570a7a
END DESCRIPTION:
XS GIS Cut Line= 3
      2832157.19      7012841.90      2832346.40      7012845.37
      2832684.95      7012847.11
#Sta/Elev= 30
  4809.3  449.84  4867.1  449.66  4897.1  448.98  4927.1  447.32  4957.1  445.98
  4991.8  443.93  4995.3  443.75  5017.1  443.77  5027.1  443.55  5047.1  442.92
  5054.1  442.27  5054.6  441.47  5059.6  441.47  5060.1  442.27  5067.1  442.33
  5077.1  443.28  5098.4  443.93  5127.1  444.90  5137.1  445.61  5157.1  447.85
  5177.1  449.42  5227.1  451.51  5237.1  452.46  5247.1  452.26  5297.1  453.72
  5307.1  453.73  5317.1  453.47  5327.1  453.69  5334.6  454.85  5337.1  454.85
#Mann=3,-1,0
  4809.3    0.08       0  5054.1    0.07       0  5060.1    0.08       0
Bank Sta=4991.8,5098.4
Exp/Cntr=0.3,0.1

Type RM Length L Ch R = 1,1742,200,200,200
BEGIN DESCRIPTION:
Mapping XS 3a412167
END DESCRIPTION:
XS GIS Cut Line= 3
      2832074.70      7013025.93      2832191.89      7013093.64
      2832476.63      7013104.92
#Sta/Elev= 30
  4869.0  447.49  4891.9  446.96  4897.7  445.90  4904.0  445.37  4913.4  445.00
  4919.2  444.45  4935.0  443.52  4940.8  443.46  4950.2  442.96  4956.5  442.06
  4962.3  442.04  4972.3  440.87  4978.1  440.70  4979.0  440.21  4981.8  438.66
  4982.3  437.86  4987.3  437.86  4987.8  438.66  4993.8  439.47  4999.6  438.69
  5003.2  439.03  5017.5  439.67  5043.8  440.21  5097.5  443.56  5157.6  445.38
  5163.8  445.84  5168.8  445.87  5247.6  449.75  5267.7  449.60  5289.3  449.94
#Mann=3,-1,0
  4869.0    0.05       0  4981.8    0.03       0  4987.8    0.05       0
Bank Sta=4979,5043.8
Exp/Cntr=0.3,0.1

Type RM Length L Ch R = 1,1542,178,178,178
BEGIN DESCRIPTION:
XS4212A
END DESCRIPTION:
XS GIS Cut Line= 3
      2831982.07      7013272.09      2832157.89      7013272.09
      2832408.47      7013175.72
#Sta/Elev= 30
  4812.6  447.60  4825.5  447.93  4835.5  446.41  4845.5  446.42  4875.5  444.26
  4925.5  442.24  4945.5  440.66  4954.1  439.23  4965.5  438.38  4992.5  438.02
  5006.8  436.47  5014.1  436.23  5014.6  435.43  5019.6  435.43  5020.1  436.23
  5022.5  437.08  5028.2  437.50  5038.9  437.73  5047.1  438.35  5052.5  438.31
  5058.9  439.23  5071.0  439.98  5082.5  441.10  5124.6  443.67  5156.4  446.08
  5167.5  447.29  5186.4  448.07  5199.6  448.23  5216.4  447.78  5256.9  448.37
#Mann=3,-1,0
  4812.6    0.05       0  5014.1    0.03       0  5020.1    0.05       0
Bank Sta=4954.1,5058.9
Exp/Cntr=0.3,0.1

Type RM Length L Ch R = 1,1364,185,185,185
BEGIN DESCRIPTION:
XS4213A
END DESCRIPTION:
XS GIS Cut Line= 4
      2832039.83      7013428.69      2832232.58      7013414.23
      2832326.53      7013390.14      2832499.95      7013264.90
#Sta/Elev= 30
  4757.7  448.04  4762.9  447.59  4853.1  445.15  4863.2  444.34  4876.0  442.43
  4894.0  439.11  4903.3  438.01  4943.4  440.36  4949.7  439.79  4963.3  439.36
  4974.1  439.51  4984.5  438.84  4994.8  437.57  5001.1  436.12  5001.6  435.32
  5006.6  435.32  5007.1  436.12  5066.1  439.11  5094.4  439.96  5100.5  439.54
  5107.8  440.30  5115.2  442.39  5121.4  442.04  5130.0  443.83  5144.7  445.29
  5157.1  446.04  5194.1  447.52  5207.3  447.49  5236.7  448.56  5261.9  448.74
#Mann=3,-1,0
  4757.7    0.05       0  5001.1    0.03       0  5007.1    0.05       0
Bank Sta=4894,5066.1
Exp/Cntr=0.3,0.1

Type RM Length L Ch R = 1,1179,172,172,172
BEGIN DESCRIPTION:
UNT 193 in LFCCL Watershed 3.0
END DESCRIPTION:
XS GIS Cut Line= 3
      2832075.04      7013525.01      2832375.00      7013575.00
      2832525.00      7013275.01
#Sta/Elev= 30
  4723.1  446.64  4804.2  444.61  4854.9  441.89  4872.6  440.49  4899.6  439.13
  4925.8  437.95  4933.4  436.16  4938.5  436.58  4943.1  436.12  4943.6  435.32
  4948.6  435.32  4949.1  436.12  5094.3  436.12  5108.3  437.86  5126.5  439.13
  5206.1  443.76  5214.5  444.62  5220.1  444.75  5236.8  446.09  5242.4  446.03
  5259.2  447.04  5264.8  446.34  5273.2  446.83  5287.1  446.69  5303.9  448.02
  5309.5  448.03  5331.9  449.30  5340.2  449.01  5348.6  449.25  5362.6  449.12
#Mann=3,-1,0
  4723.1    0.05       0  4943.1   0.035       0  4949.1    0.05       0
Bank Sta=4899.6,5126.5
Exp/Cntr=0.3,0.1

Type RM Length L Ch R = 1,1007,150,150,150
BEGIN DESCRIPTION:
XS4214A
END DESCRIPTION:
XS GIS Cut Line= 3
      2832059.10      7013672.00      2832355.44      7013741.87
      2832646.97      7013720.18
#Sta/Elev= 30
  4671.7  445.53  4698.3  445.57  4718.9  445.29  4747.3  443.72  4752.5  443.69
  4789.7  441.22  4794.8  441.10  4801.0  440.29  4811.3  439.75  4816.6  439.13
  4821.6  438.55  4831.9  436.13  4834.1  436.12  4834.6  435.32  4839.6  435.32
  4840.1  436.12  5045.9  436.12  5055.9  436.47  5075.4  439.13  5086.0  440.30
  5096.1  441.16  5106.1  441.57  5116.1  441.65  5138.7  440.42  5166.2  441.62
  5206.4  443.13  5226.4  444.06  5246.5  444.40  5265.0  445.24  5268.5  445.24
#Mann=3,-1,0
  4671.7    0.05       0  4834.1    0.03       0  4840.1    0.05       0
Bank Sta=4816.6,5075.4
Exp/Cntr=0.3,0.1

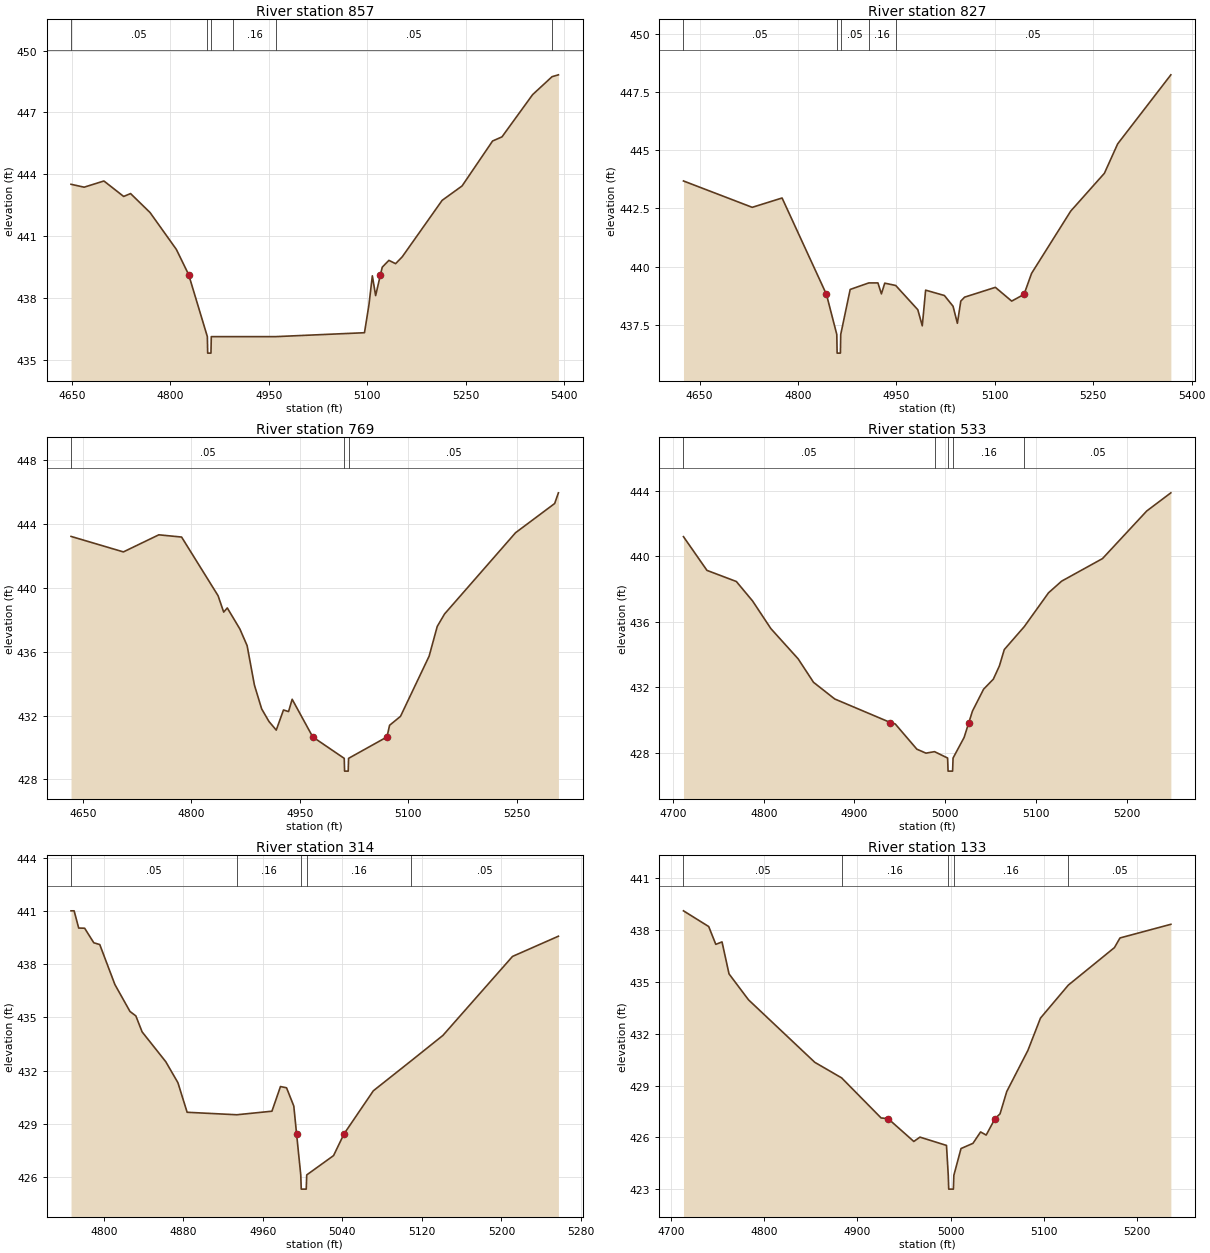
Type RM Length L Ch R = 1,857,30,30,30
BEGIN DESCRIPTION:
XS4215A
END DESCRIPTION:
XS GIS Cut Line= 4
      2832035.07      7013927.36      2832287.99      7013905.69
      2832478.30      7013871.96      2832769.83      7013823.77
#Sta/Elev= 30
  4648.7  443.51  4668.7  443.37  4698.8  443.67  4728.9  442.92  4739.4  443.06
  4769.1  442.14  4809.2  440.35  4827.9  439.13  4856.4  436.12  4856.9  435.32
  4861.9  435.32  4862.4  436.12  4895.9  436.12  4960.3  436.12  5095.8  436.31
  5102.6  437.66  5107.8  439.07  5112.8  438.11  5120.2  439.13  5122.9  439.49
  5133.0  439.82  5143.2  439.66  5153.3  439.99  5214.1  442.73  5244.5  443.43
  5291.0  445.61  5305.3  445.81  5352.0  447.86  5381.6  448.73  5391.3  448.82
#Mann=6,-1,0
  4648.7    0.05       0  4856.4    0.03       0  4862.4    0.05       0
  4895.9    0.16       0  4960.3    0.05       0  5381.6    0.08       0
Bank Sta=4827.9,5120.2
Exp/Cntr=0.3,0.1

Type RM Length L Ch R = 1,827,58,58,58
BEGIN DESCRIPTION:
XS4216A
END DESCRIPTION:
XS GIS Cut Line= 5
      2832010.95      7013968.32      2832266.30      7013937.00
      2832418.08      7013912.91      2832480.71      7013896.05
      2832745.36      7013859.96
#Sta/Elev= 30
  4625.4  443.68  4730.2  442.55  4775.7  442.95  4843.3  438.82  4859.1  437.10
  4859.6  436.30  4864.6  436.30  4865.1  437.10  4879.5  439.03  4907.9  439.31
  4921.8  439.31  4927.1  438.84  4932.2  439.30  4948.9  439.20  4982.6  438.16
  4989.4  437.47  4994.5  439.00  5023.1  438.77  5036.3  438.31  5042.9  437.58
  5048.1  438.53  5053.9  438.70  5100.8  439.12  5125.7  438.53  5144.5  438.82
  5156.0  439.72  5215.7  442.39  5267.0  444.01  5287.2  445.27  5368.3  448.23
#Mann=5,-1,0
  4625.4    0.05       0  4859.1    0.03       0  4865.1    0.05       0
  4907.9    0.16       0  4948.9    0.05       0
Bank Sta=4843.3,5144.5
Exp/Cntr=0.3,0.1

Type RM Length L Ch R = 1,769,236,236,236
BEGIN DESCRIPTION:
XS4217A
END DESCRIPTION:
XS GIS Cut Line= 3
      2832023.03      7014014.09      2832384.35      7013973.14
      2832690.17      7013920.16
#Sta/Elev= 30
  4633.7  443.22  4706.1  442.25  4755.1  443.32  4786.6  443.18  4837.0  439.51
  4844.8  438.48  4849.8  438.74  4867.2  437.42  4877.2  436.38  4887.3  433.91
  4897.3  432.42  4907.4  431.63  4917.5  431.09  4927.5  432.35  4934.5  432.25
  4939.5  433.02  4968.0  430.66  5011.5  429.32  5012.0  428.52  5017.0  428.52
  5017.5  429.32  5070.6  430.66  5074.2  431.39  5089.3  431.95  5128.9  435.72
  5140.1  437.58  5150.2  438.36  5248.4  443.45  5302.5  445.28  5307.7  445.95
#Mann=3,-1,0
  4633.7    0.05       0  5011.5    0.03       0  5017.5    0.05       0
Bank Sta=4968,5070.6
Exp/Cntr=0.3,0.1

Type RM Length L Ch R = 1,533,219,219,219
BEGIN DESCRIPTION:
XS4219A
END DESCRIPTION:
XS GIS Cut Line= 3
      2832189.24      7014153.82      2832468.67      7014185.14
      2832707.15      7014091.19
#Sta/Elev= 30
  4711.4  441.21  4737.3  439.15  4769.7  438.47  4787.6  437.28  4807.8  435.59
  4837.9  433.74  4854.8  432.31  4878.2  431.29  4939.6  429.85  4945.0  429.76
  4968.8  428.22  4978.8  427.98  4988.3  428.07  5002.7  427.68  5003.2  426.88
  5008.2  426.88  5008.7  427.68  5020.9  428.94  5026.1  429.85  5030.1  430.55
  5042.4  431.89  5053.1  432.50  5059.8  433.31  5065.2  434.31  5087.2  435.71
  5114.0  437.78  5128.4  438.49  5173.5  439.87  5222.3  442.78  5248.9  443.89
#Mann=5,-1,0
  4711.4    0.05       0  4988.3    0.16       0  5002.7    0.07       0
  5008.7    0.16       0  5087.2    0.05       0
Bank Sta=4939.6,5026.1
Exp/Cntr=0.3,0.1

Type RM Length L Ch R = 1,314,181,181,181
BEGIN DESCRIPTION:
XS4218A
END DESCRIPTION:
XS GIS Cut Line= 3
      2832174.77      7014255.01      2832355.44      7014370.64
      2832631.20      7014375.44
#Sta/Elev= 30
  4767.0  441.01  4770.1  441.01  4774.7  440.04  4780.7  440.03  4789.9  439.21
  4795.9  439.11  4811.1  436.86  4826.3  435.34  4832.2  435.09  4838.5  434.19
  4862.3  432.51  4874.5  431.33  4883.8  429.66  4933.8  429.52  4969.1  429.72
  4977.7  431.11  4983.8  431.04  4991.1  430.01  4993.9  428.44  4998.1  426.13
  4998.6  425.33  5003.6  425.33  5004.1  426.13  5031.1  427.22  5041.6  428.44
  5071.1  430.87  5109.4  432.57  5141.1  433.99  5211.1  438.44  5257.3  439.58
#Mann=5,-1,0
  4767.0    0.05       0  4933.8    0.16       0  4998.1    0.07       0
  5004.1    0.16       0  5109.4    0.05       0
Bank Sta=4993.9,5041.6
Exp/Cntr=0.3,0.1

Type RM Length L Ch R = 1,133,0,0,0
BEGIN DESCRIPTION:
UNT 193 in LFCCL Watershed 1.0
END DESCRIPTION:
XS GIS Cut Line= 3
      2832136.23      7014324.89      2832326.53      7014541.69
      2832520.81      7014673.60
#Sta/Elev= 30
  4713.2  439.12  4740.3  438.21  4747.9  437.18  4754.6  437.32  4762.1  435.47
  4783.0  433.97  4854.2  430.35  4883.0  429.45  4925.4  427.13  4932.9  427.09
  4960.5  425.77  4967.1  426.02  4995.6  425.54  4997.5  423.81  4998.0  423.01
  5003.0  423.01  5003.5  423.81  5011.2  425.36  5024.0  425.66  5032.2  426.32
  5038.2  426.14  5047.7  427.09  5053.1  427.37  5060.3  428.66  5083.0  431.04
  5096.5  432.91  5126.4  434.82  5175.9  436.99  5181.9  437.55  5236.5  438.34
#Mann=5,-1,0
  4713.2    0.05       0  4883.0    0.16       0  4997.5    0.07       0
  5003.5    0.16       0  5126.4    0.05       0
Bank Sta=4932.9,5047.7
Exp/Cntr=0.3,0.1

Chan Stop Cuts=-1