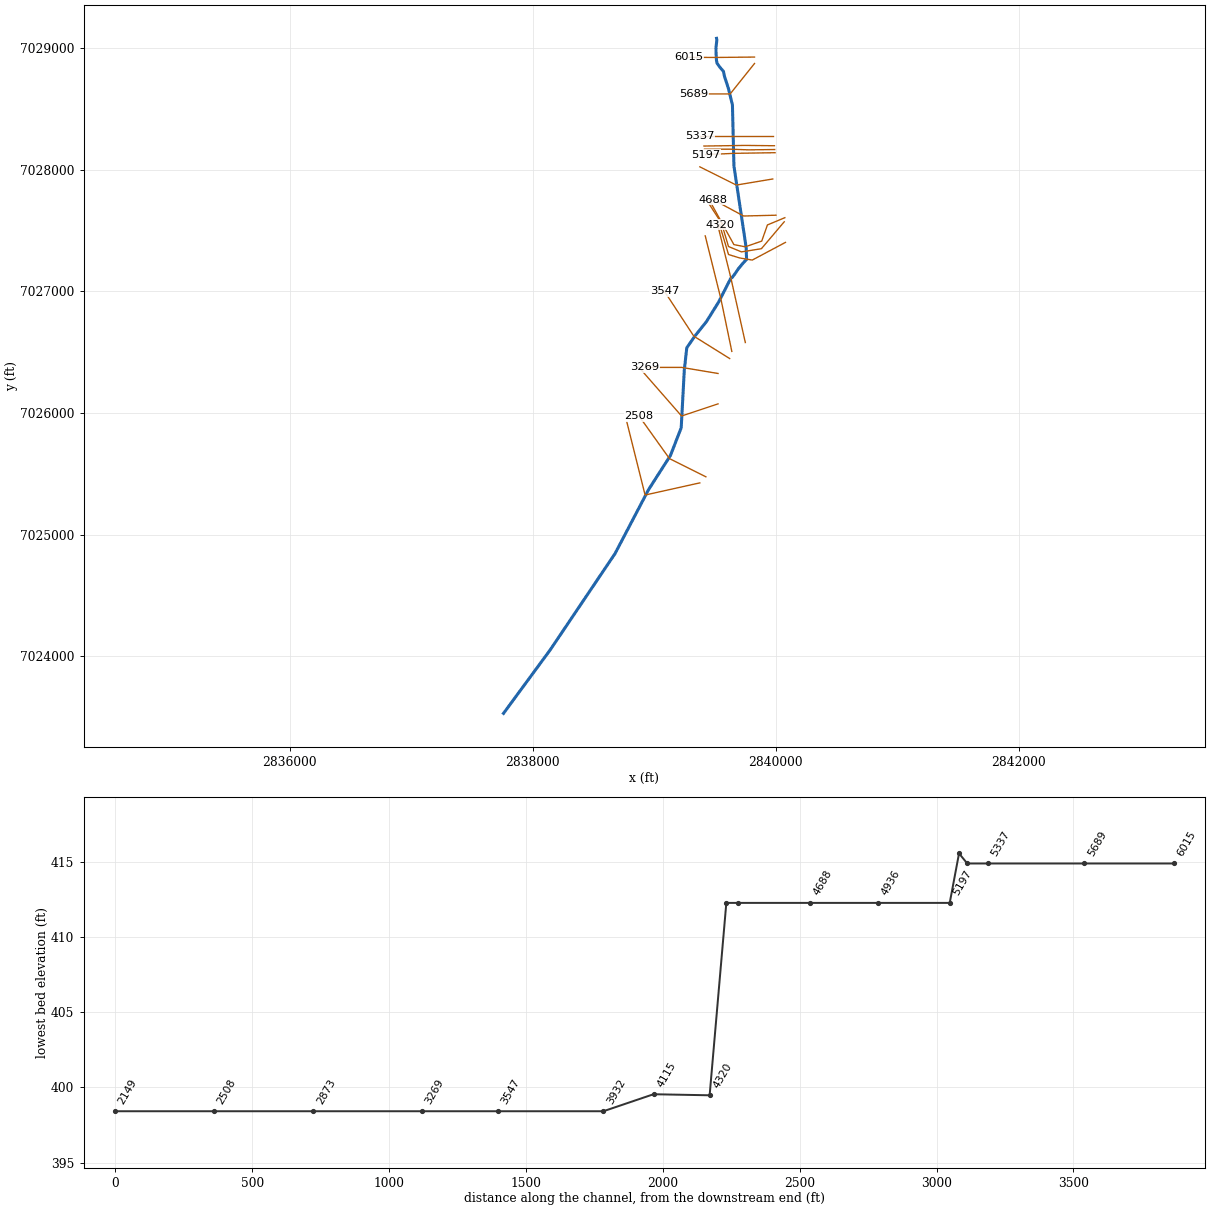
--- UNT 195 in LFCCL Watershed.prj (project) ---

Proj Title=UNT 195 in LFCCL Watershed Base Level Engineering
Current Plan=p01
Default Exp/Contr=0.3,0.1
English Units
Geom File=g01
Flow File=f01
Plan File=p01
BEGIN DESCRIPTION:
UNT 195 in LFCCL Watershed
END DESCRIPTION:

--- UNT 195 in LFCCL Watershed.p01 (plan) ---

Plan Title=Multiple Run
Short Identifier=Multiple
Geom File=g01
Flow File=f01
Subcritical Flow
K Sum by GR= 0
Std Step Tol= 0.01
Critical Tol= 0.01
Num of Std Step Trials= 20
Max Error Tol= 0.3
Flow Tol Ratio= 0.001
Split Flow NTrial= 30
Split Flow Tol= 0.02
Split Flow Ratio= 0.02
Log Output Level= 0
Friction Slope Method= 1
Unsteady Friction Slope Method= 2
Unsteady Bridges Friction Slope Method= 1
Parabolic Critical Depth
Global Vel Dist=  1 , 1 , 1
Global Log Level= 0
CheckData=True
Encroach Param= -1, 0, 0, 0
BEGIN DESCRIPTION:
Multiple Run
END DESCRIPTION:

--- UNT 195 in LFCCL Watershed.f01 (steady flow) ---

Flow Title=Multiple
Number of Profiles=7
Profile Names=10-year,25-year,50-year,1pct_min,100-year,1pct_plu,500-year
River Rch & RM= UNT 195 in LFCCL,Reach-1,6015
     253     320     370     214     427     851     566
River Rch & RM= UNT 195 in LFCCL,Reach-1,2149
     395     511     602     352     703    1403     962
Boundary for River Rch & Prof#=UNT 195 in LFCCL,Reach-1,1
Up Type=0
Dn Type=3
Dn Slope=0.005
Boundary for River Rch & Prof#=UNT 195 in LFCCL,Reach-1,2
Up Type=0
Dn Type=3
Dn Slope=0.005
Boundary for River Rch & Prof#=UNT 195 in LFCCL,Reach-1,3
Up Type=0
Dn Type=3
Dn Slope=0.005
Boundary for River Rch & Prof#=UNT 195 in LFCCL,Reach-1,4
Up Type=0
Dn Type=3
Dn Slope=0.005
Boundary for River Rch & Prof#=UNT 195 in LFCCL,Reach-1,5
Up Type=0
Dn Type=3
Dn Slope=0.005
Boundary for River Rch & Prof#=UNT 195 in LFCCL,Reach-1,6
Up Type=0
Dn Type=3
Dn Slope=0.005
Boundary for River Rch & Prof#=UNT 195 in LFCCL,Reach-1,7
Up Type=0
Dn Type=3
Dn Slope=0.005

--- UNT 195 in LFCCL Watershed.g01 (geometry) ---

Geom Title=Existing Conditions

River Reach=UNT 195 in LFCCL,Reach-1
Reach XY= 30
      2839512.69      7029082.14      2839515.29      7029067.38
      2839508.35      7029010.09      2839508.35      7028971.89
      2839511.82      7028902.45      2839517.89      7028875.54
      2839543.07      7028840.82      2839569.44      7028810.77
      2839578.22      7028768.82      2839610.83      7028668.33
      2839643.44      7028534.56      2839655.87      7028031.19
      2839756.27      7027360.90      2839759.67      7027263.55
      2839729.20      7027230.98      2839693.47      7027187.89
      2839664.05      7027144.81      2839641.98      7027115.39
      2839629.37      7027106.98      2839530.59      7026913.63
      2839429.71      7026751.80      2839334.09      7026632.01
      2839267.89      7026536.39      2839247.33      7026349.71
      2839222.01      7025878.22      2839133.41      7025650.38
      2838953.04      7025368.75      2838677.74      7024843.47
      2838142.96      7024049.21      2837760.02      7023528.75

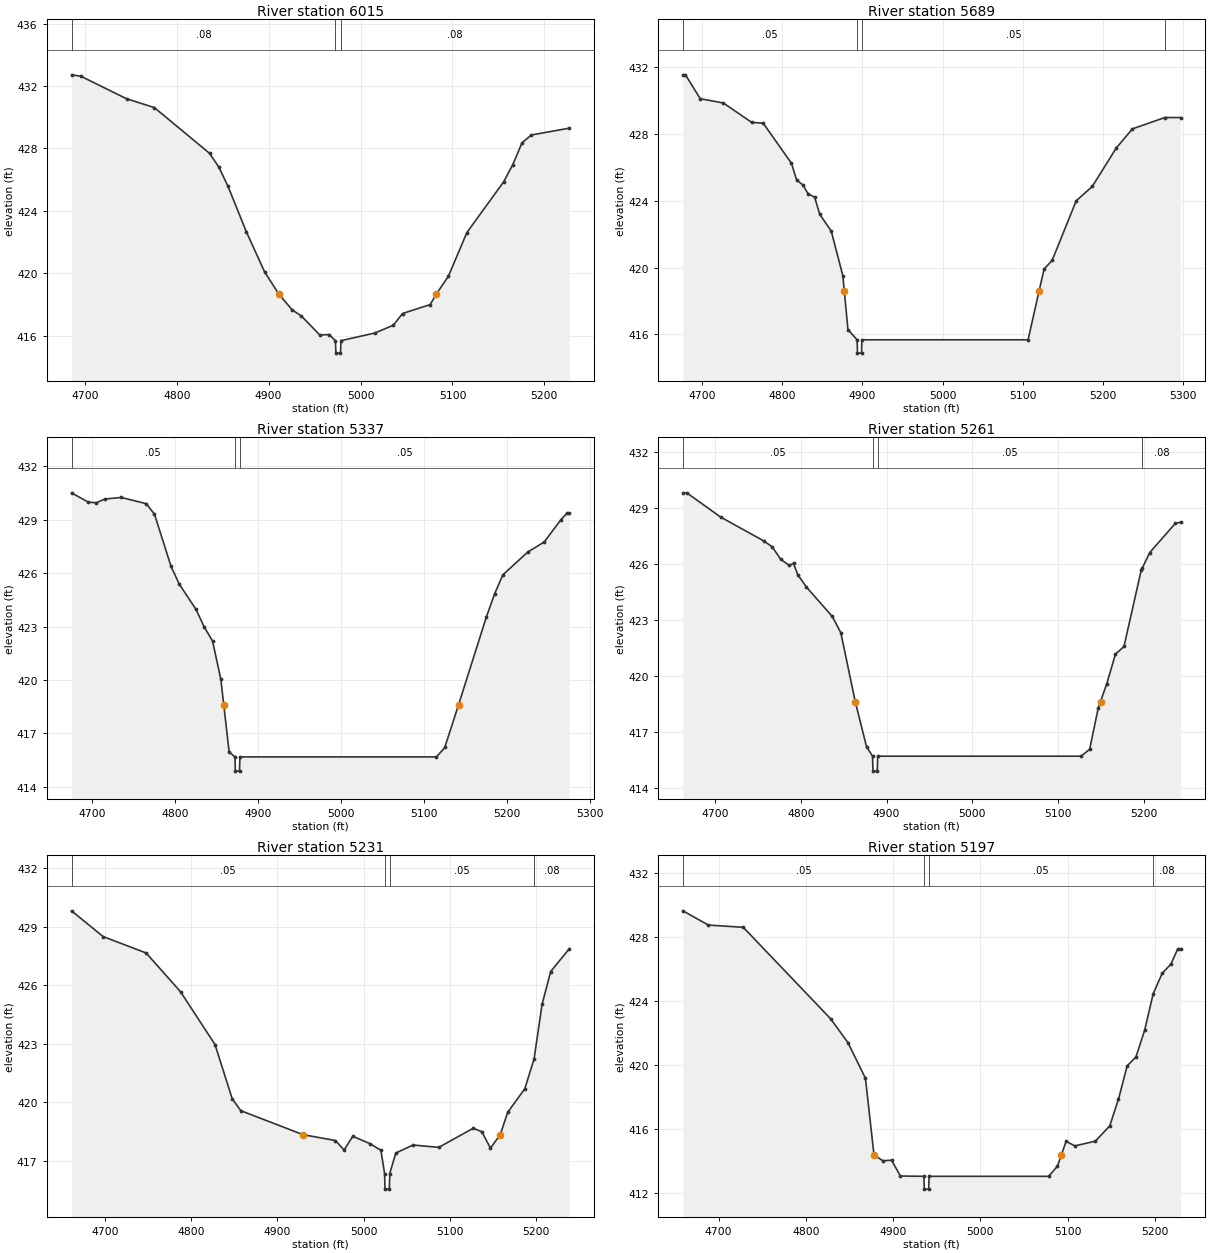
Type RM Length L Ch R = 1,6015,326,326,326
BEGIN DESCRIPTION:
Mapping XS 731231bb
END DESCRIPTION:
XS GIS Cut Line= 3
      2839825.08      7028928.04      2839509.37      7028924.79
      2839283.70      7028925.87
#Sta/Elev= 30
  4685.6  432.72  4695.7  432.63  4745.7  431.18  4775.7  430.62  4835.7  427.69
  4845.7  426.82  4855.7  425.59  4875.7  422.67  4895.7  420.08  4911.3  418.65
  4925.7  417.65  4935.7  417.26  4955.7  416.04  4965.7  416.07  4972.7  415.68
  4973.2  414.88  4978.2  414.88  4978.7  415.68  5015.7  416.17  5035.7  416.67
  5045.7  417.42  5075.7  417.99  5082.3  418.65  5095.7  419.82  5115.7  422.61
  5155.7  425.86  5165.7  426.97  5175.7  428.36  5185.7  428.86  5227.0  429.30
#Mann=3,-1,0
  4685.6    0.08       0  4972.7    0.07       0  4978.7    0.08       0
Bank Sta=4911.3,5082.3
Exp/Cntr=0.3,0.1

Type RM Length L Ch R = 1,5689,352,352,352
BEGIN DESCRIPTION:
UNT 195 in LFCCL Watershed 14.0
END DESCRIPTION:
XS GIS Cut Line= 3
      2839825.02      7028875.02      2839625.00      7028625.00
      2839324.99      7028625.00
#Sta/Elev= 30
  4676.2  431.56  4679.4  431.56  4697.8  430.13  4726.7  429.87  4761.9  428.71
  4776.3  428.66  4811.5  426.26  4817.9  425.26  4825.9  424.95  4832.3  424.42
  4840.3  424.23  4846.7  423.21  4861.1  422.19  4875.5  419.53  4877.3  418.63
  4881.9  416.29  4893.3  415.68  4893.8  414.88  4898.8  414.88  4899.3  415.68
  5106.4  415.68  5120.2  418.63  5126.4  419.92  5136.4  420.44  5166.4  424.01
  5186.4  424.87  5216.4  427.18  5236.4  428.32  5276.8  429.00  5296.4  429.00
#Mann=4,-1,0
  4676.2    0.05       0  4893.3   0.033       0  4899.3    0.05       0
  5276.8    0.08       0
Bank Sta=4877.3,5120.2
Exp/Cntr=0.3,0.1

Type RM Length L Ch R = 1,5337,76,76,76
BEGIN DESCRIPTION:
UNT 195 in LFCCL Watershed 13.0
END DESCRIPTION:
XS GIS Cut Line= 3
      2839975.05      7028275.00      2839675.00      7028275.00
      2839375.05      7028275.00
#Sta/Elev= 30
  4674.8  430.52  4694.8  430.00  4704.8  429.96  4714.8  430.17  4734.8  430.26
  4764.8  429.91  4774.8  429.32  4794.8  426.38  4804.8  425.38  4824.8  423.97
  4834.8  422.98  4844.8  422.19  4854.8  420.04  4858.3  418.62  4864.8  415.96
  4871.8  415.68  4872.3  414.88  4877.3  414.88  4877.8  415.68  5114.8  415.68
  5124.8  416.21  5141.5  418.62  5174.8  423.52  5184.8  424.83  5194.8  425.91
  5224.8  427.19  5244.8  427.76  5264.8  429.01  5272.3  429.38  5274.8  429.38
#Mann=3,-1,0
  4674.8    0.05       0  4871.8   0.033       0  4877.8    0.05       0
Bank Sta=4858.3,5141.5
Exp/Cntr=0.3,0.1

Type RM Length L Ch R = 1,5261,30,30,30
BEGIN DESCRIPTION:
XS4220A
END DESCRIPTION:
XS GIS Cut Line= 3
      2839988.98      7028198.62      2839746.83      7028201.22
      2839409.13      7028196.02
#Sta/Elev= 30
  4662.7  429.79  4667.2  429.79  4706.7  428.49  4756.7  427.22  4766.7  426.90
  4776.7  426.23  4786.6  425.90  4791.6  426.01  4796.7  425.39  4806.7  424.74
  4836.7  423.17  4846.7  422.30  4863.5  418.61  4876.7  416.19  4883.7  415.68
  4884.2  414.88  4889.2  414.88  4889.7  415.68  5126.7  415.68  5136.7  416.05
  5146.7  418.26  5149.4  418.61  5156.7  419.57  5166.7  421.14  5176.7  421.56
  5196.7  425.63  5198.1  425.76  5206.7  426.59  5236.7  428.16  5242.6  428.21
#Mann=4,-1,0
  4662.7    0.05       0  4883.7   0.033       0  4889.7    0.05       0
  5198.1    0.08       0
Bank Sta=4863.5,5149.4
Exp/Cntr=0.3,0.1

Type RM Length L Ch R = 1,5231,34,34,34
BEGIN DESCRIPTION:
XS4221A
END DESCRIPTION:
XS GIS Cut Line= 4
      2839991.66      7028167.37      2839775.47      7028164.76
      2839632.24      7028169.97      2839413.47      7028169.97
#Sta/Elev= 30
  4660.7  429.81  4697.4  428.49  4747.4  427.65  4787.4  425.66  4827.4  422.96
  4847.4  420.18  4857.4  419.57  4929.7  418.34  4967.4  418.04  4977.4  417.55
  4987.5  418.26  5007.5  417.88  5020.2  417.54  5024.5  416.35  5025.0  415.55
  5030.0  415.55  5030.5  416.35  5037.5  417.40  5057.5  417.81  5087.5  417.69
  5127.5  418.67  5137.5  418.49  5147.5  417.65  5158.9  418.34  5167.5  419.48
  5187.5  420.70  5198.2  422.22  5207.5  425.02  5217.5  426.70  5239.0  427.86
#Mann=4,-1,0
  4660.7    0.05       0  5024.5   0.035       0  5030.5    0.05       0
  5198.2    0.08       0
Bank Sta=4929.7,5158.9
Exp/Cntr=0.3,0.1

Type RM Length L Ch R = 1,5197,261,261,261
BEGIN DESCRIPTION:
XS4222A
END DESCRIPTION:
XS GIS Cut Line= 3
      2839994.24      7028141.32      2839663.49      7028136.11
      2839423.91      7028125.70
#Sta/Elev= 30
  4659.0  429.65  4688.2  428.76  4728.2  428.62  4828.3  422.91  4848.3  421.41
  4868.3  419.19  4878.1  414.40  4888.3  414.03  4898.3  414.07  4908.3  413.08
  4935.3  413.06  4935.8  412.26  4940.8  412.26  4941.3  413.06  5078.4  413.06
  5088.4  413.69  5093.0  414.40  5098.4  415.25  5108.4  414.96  5132.0  415.26
  5148.4  416.21  5158.4  417.87  5168.4  419.96  5178.5  420.52  5188.5  422.20
  5198.2  424.46  5208.5  425.74  5218.5  426.32  5226.5  427.28  5229.6  427.28
#Mann=4,-1,0
  4659.0    0.05       0  4935.3   0.033       0  4941.3    0.05       0
  5198.2    0.08       0
Bank Sta=4878.1,5093
Exp/Cntr=0.3,0.1

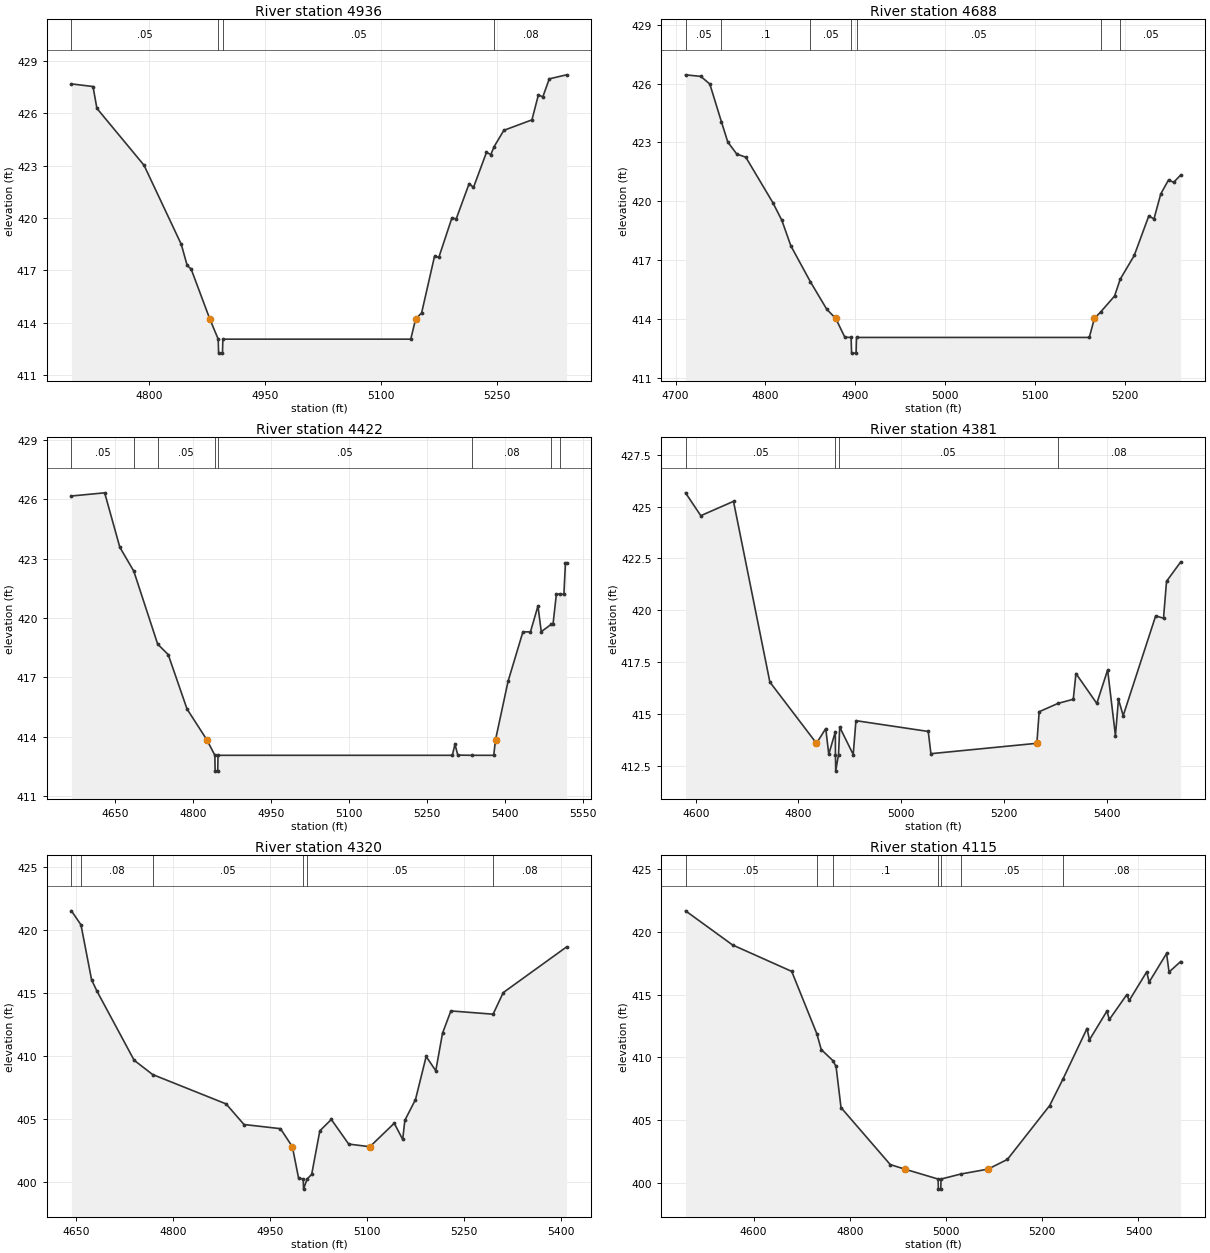
Type RM Length L Ch R = 1,4936,248,248,248
BEGIN DESCRIPTION:
UNT 195 in LFCCL Watershed 12.0
END DESCRIPTION:
XS GIS Cut Line= 3
      2839974.98      7027925.00      2839675.00      7027875.00
      2839375.02      7028024.99
#Sta/Elev= 30
  4700.1  427.68  4728.0  427.53  4733.0  426.28  4793.9  423.02  4842.0  418.49
  4849.6  417.28  4854.7  417.08  4878.8  414.22  4889.7  413.06  4890.2  412.26
  4895.2  412.26  4895.7  413.06  5138.4  413.06  5144.7  414.22  5152.4  414.56
  5169.1  417.81  5174.7  417.75  5191.5  420.00  5197.1  419.95  5213.8  421.97
  5219.4  421.75  5236.2  423.76  5241.8  423.63  5246.1  424.09  5258.6  425.02
  5294.9  425.62  5303.3  427.06  5308.9  426.93  5317.3  427.97  5339.6  428.20
#Mann=4,-1,0
  4700.1    0.05       0  4889.7   0.033       0  4895.7    0.05       0
  5246.1    0.08       0
Bank Sta=4878.8,5144.7
Exp/Cntr=0.3,0.1

Type RM Length L Ch R = 1,4688,266,266,266
BEGIN DESCRIPTION:
XS4226A
END DESCRIPTION:
XS GIS Cut Line= 3
      2840002.02      7027627.00      2839735.11      7027620.49
      2839485.56      7027755.03
#Sta/Elev= 30
  4711.1  426.45  4728.1  426.37  4738.1  425.98  4750.9  424.07  4758.1  423.02
  4768.1  422.41  4778.1  422.25  4808.2  419.93  4818.2  419.03  4828.2  417.73
  4849.9  415.90  4868.2  414.49  4878.1  414.03  4888.2  413.07  4895.2  413.06
  4895.7  412.26  4900.7  412.26  4901.2  413.06  5160.0  413.06  5165.7  414.03
  5172.5  414.35  5188.1  415.17  5194.4  416.03  5210.0  417.24  5226.2  419.26
  5231.9  419.10  5239.5  420.38  5248.1  421.09  5253.8  420.97  5261.6  421.34
#Mann=7,-1,0
  4711.1    0.05       0  4750.9     0.1       0  4849.9    0.05       0
  4895.2   0.033       0  4901.2    0.05       0  5172.5    0.08       0
  5194.4    0.05       0
Bank Sta=4878.1,5165.7
Exp/Cntr=0.3,0.1

Type RM Length L Ch R = 1,4422,41,41,41
BEGIN DESCRIPTION:
XS4229A
END DESCRIPTION:
XS GIS Cut Line= 6
      2840074.52      7027606.60      2839931.29      7027546.71
      2839884.41      7027413.89      2839749.00      7027367.02
      2839655.25      7027385.25      2839457.36      7027744.59
#Sta/Elev= 30
  4565.8  426.17  4629.8  426.33  4659.0  423.58  4685.9  422.37  4731.9  418.68
  4752.2  418.15  4788.4  415.40  4826.4  413.85  4842.0  413.06  4842.5  412.26
  4847.5  412.26  4848.0  413.06  5299.2  413.06  5304.3  413.62  5309.7  413.07
  5336.5  413.06  5378.9  413.06  5382.4  413.85  5406.5  416.80  5435.1  419.30
  5449.6  419.30  5464.1  420.61  5470.4  419.31  5490.1  419.69  5493.2  419.72
  5499.5  421.20  5507.4  421.22  5514.0  421.19  5516.9  422.76  5519.1  422.76
#Mann=8,-1,0
  4565.8    0.05       0  4685.9     0.1       0  4731.9    0.05       0
  4842.0   0.033       0  4848.0    0.05       0  5336.5    0.08       0
  5490.1    0.05       0  5507.4    0.08       0
Bank Sta=4826.4,5382.4
Exp/Cntr=0.3,0.1

Type RM Length L Ch R = 1,4381,61,61,61
BEGIN DESCRIPTION:
XS4228A
END DESCRIPTION:
XS GIS Cut Line= 6
      2840069.32      7027572.75      2839881.81      7027351.39
      2839717.75      7027325.35      2839610.98      7027369.62
      2839553.69      7027562.33      2839452.13      7027718.57
#Sta/Elev= 30
  4580.1  425.66  4609.8  424.56  4673.5  425.25  4744.3  416.55  4835.1  413.60
  4853.1  414.31  4859.0  413.07  4871.8  414.16  4872.0  413.06  4872.5  412.26
  4878.0  413.06  4880.3  414.38  4906.6  413.06  4911.9  414.69  5052.7  414.17
  5057.9  413.10  5264.2  413.60  5268.7  415.12  5305.2  415.52  5335.1  415.72
  5340.3  416.96  5380.9  415.52  5402.0  417.13  5417.2  413.97  5423.1  415.72
  5432.3  414.93  5495.6  419.74  5510.8  419.62  5516.7  421.40  5544.2  422.33
#Mann=4,-1,0
  4580.1    0.05       0  4872.0    0.03       0  4878.0    0.05       0
  5305.2    0.08       0
Bank Sta=4835.1,5264.2
Exp/Cntr=0.3,0.1

Type RM Length L Ch R = 1,4320,205,205,205
BEGIN DESCRIPTION:
XS4227A
END DESCRIPTION:
XS GIS Cut Line= 5
      2840079.73      7027403.48      2839806.72      7027258.08
      2839702.56      7027275.44      2839611.41      7027303.65
      2839537.63      7027548.86
#Sta/Elev= 30
  4642.9  421.52  4657.7  420.41  4674.1  416.06  4682.2  415.18  4740.0  409.68
  4768.6  408.55  4882.4  406.22  4910.0  404.59  4966.5  404.26  4984.9  402.83
  4994.5  400.35  5001.7  400.27  5002.2  399.47  5007.7  400.27  5014.8  400.64
  5027.4  404.09  5045.2  404.99  5072.1  403.04  5104.9  402.83  5142.6  404.69
  5155.7  403.41  5159.0  404.92  5175.5  406.57  5192.0  409.98  5206.9  408.85
  5217.3  411.82  5230.3  413.59  5295.6  413.33  5311.3  415.04  5409.3  418.66
#Mann=6,-1,0
  4642.9    0.05       0  4657.7    0.08       0  4768.6    0.05       0
  5001.7    0.03       0  5007.7    0.05       0  5295.6    0.08       0
Bank Sta=4984.9,5104.9
Exp/Cntr=0.3,0.1

Type RM Length L Ch R = 1,4115,183,183,183
BEGIN DESCRIPTION:
XS4225A
END DESCRIPTION:
XS GIS Cut Line= 3
      2839749.44      7026579.66      2839631.38      7027107.47
      2839513.72      7027581.54
#Sta/Elev= 30
  4458.4  421.65  4556.1  418.94  4679.1  416.84  4731.3  411.89  4740.5  410.63
  4764.7  409.75  4771.3  409.29  4781.6  406.02  4884.0  401.49  4914.1  401.13
  4983.5  400.34  4984.0  399.54  4989.0  399.54  4989.5  400.34  5030.7  400.74
  5087.2  401.13  5127.5  401.90  5215.4  406.18  5243.2  408.30  5293.0  412.30
  5298.1  411.40  5334.3  413.68  5339.5  413.02  5375.7  414.99  5380.8  414.53
  5417.1  416.80  5422.2  415.99  5458.4  418.26  5463.6  416.79  5487.7  417.62
#Mann=7,-1,0
  4458.4    0.05       0  4731.3    0.08       0  4764.7     0.1       0
  4983.5    0.07       0  4989.5     0.1       0  5030.7    0.05       0
  5243.2    0.08       0
Bank Sta=4914.1,5087.2
Exp/Cntr=0.3,0.1

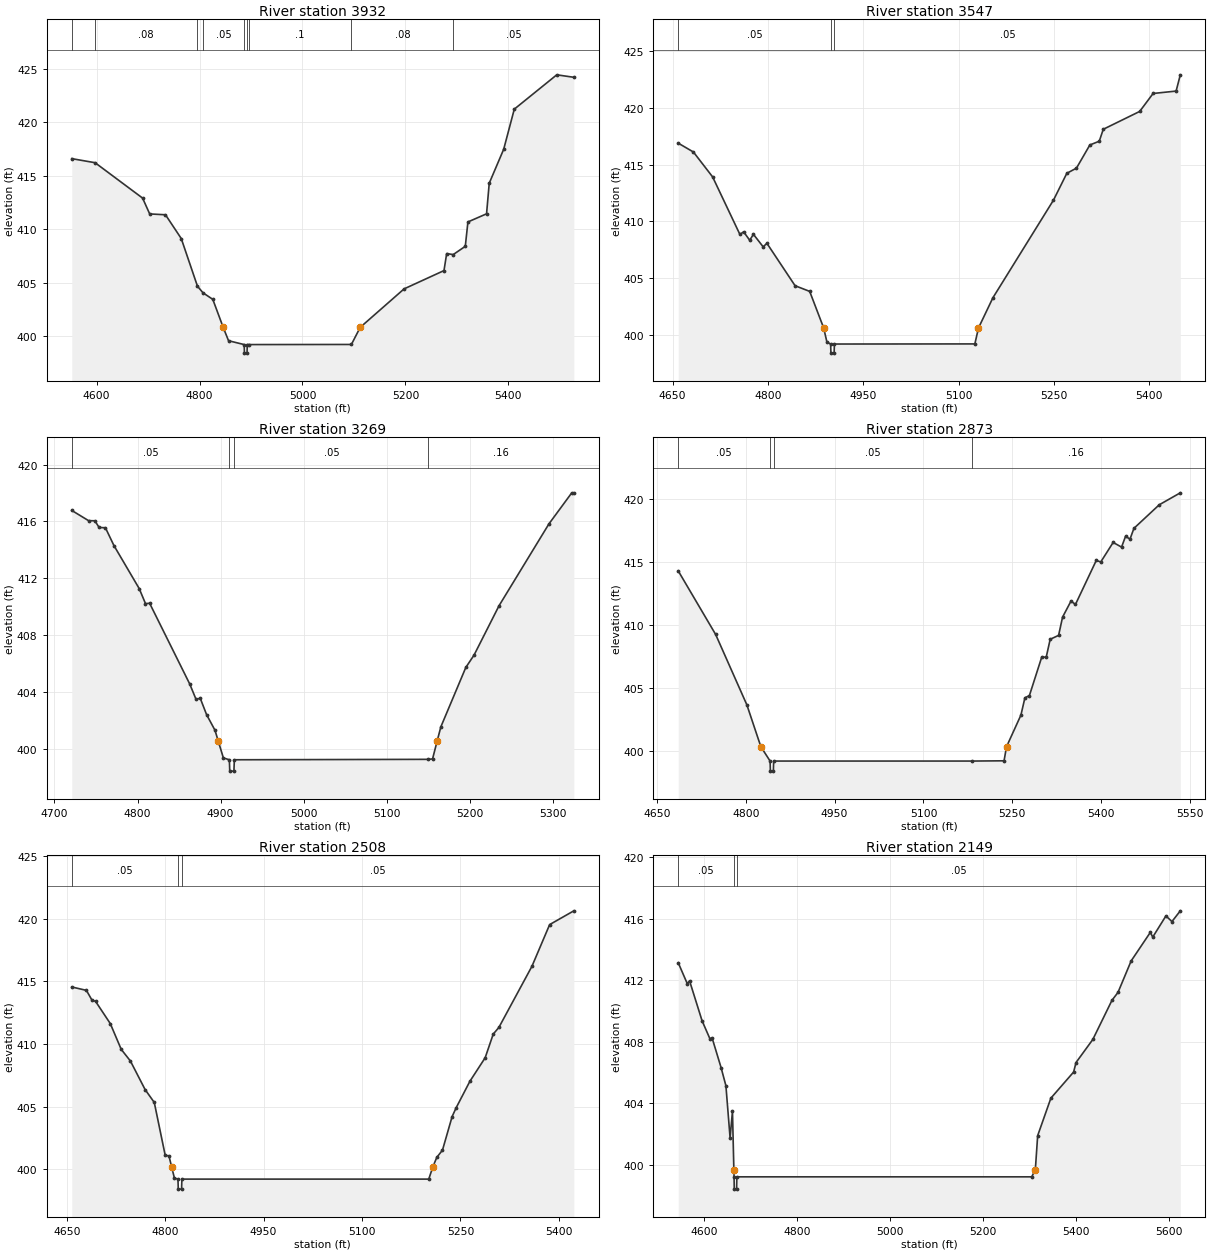
Type RM Length L Ch R = 1,3932,385,385,385
BEGIN DESCRIPTION:
XS4224A
END DESCRIPTION:
XS GIS Cut Line= 3
      2839638.33      7026506.74      2839548.04      7026940.80
      2839419.79      7027457.26
#Sta/Elev= 30
  4551.8  416.60  4597.1  416.22  4689.4  412.91  4703.2  411.43  4733.9  411.35
  4764.5  409.13  4796.0  404.67  4806.8  404.05  4825.8  403.44  4846.0  400.82
  4856.4  399.57  4886.8  399.21  4887.3  398.41  4892.3  398.41  4892.8  399.21
  4895.4  399.21  5095.1  399.22  5112.2  400.82  5197.5  404.42  5275.0  406.13
  5280.2  407.72  5293.0  407.63  5316.4  408.40  5321.5  410.68  5357.7  411.44
  5362.9  414.30  5391.0  417.48  5411.6  421.23  5494.1  424.44  5527.3  424.21
#Mann=9,-1,0
  4551.8    0.05       0  4597.1    0.08       0  4796.0     0.1       0
  4806.8    0.05       0  4886.8    0.07       0  4892.8    0.05       0
  4895.4     0.1       0  5095.1    0.08       0  5293.0    0.05       0
Bank Sta=4846,5112.2
Exp/Cntr=0.3,0.1

Type RM Length L Ch R = 1,3547,278,278,278
BEGIN DESCRIPTION:
XS4223A
END DESCRIPTION:
XS GIS Cut Line= 3
      2839620.92      7026447.77      2839325.82      7026631.77
      2839083.83      7027001.68
#Sta/Elev= 30
  4658.9  416.88  4682.8  416.10  4713.0  413.91  4755.9  408.85  4761.8  409.08
  4771.3  408.34  4777.2  408.86  4792.5  407.76  4798.4  408.07  4842.7  404.34
  4865.7  403.84  4887.7  400.62  4892.8  399.38  4898.6  399.21  4899.1  398.41
  4904.1  398.41  4904.6  399.21  5125.5  399.22  5131.2  400.62  5153.9  403.28
  5249.2  411.87  5270.2  414.23  5285.3  414.68  5306.4  416.72  5321.2  417.05
  5327.5  418.10  5384.8  419.67  5405.9  421.25  5442.1  421.46  5448.7  422.89
#Mann=3,-1,0
  4658.9    0.05       0  4898.6   0.033       0  4904.6    0.05       0
Bank Sta=4887.7,5131.2
Exp/Cntr=0.3,0.1

Type RM Length L Ch R = 1,3269,396,396,396
BEGIN DESCRIPTION:
UNT 195 in LFCCL Watershed 9.0
END DESCRIPTION:
XS GIS Cut Line= 3
      2839524.96      7026325.01      2839225.00      7026375.00
      2838925.00      7026375.00
#Sta/Elev= 30
  4720.9  416.77  4741.1  416.05  4748.7  416.04  4753.8  415.57  4761.4  415.55
  4771.6  414.30  4802.0  411.27  4809.6  410.21  4814.6  410.23  4862.8  404.55
  4870.4  403.47  4875.5  403.54  4883.1  402.39  4893.2  401.29  4897.3  400.50
  4903.3  399.34  4910.5  399.21  4911.0  398.41  4916.0  398.41  4916.5  399.21
  5149.9  399.24  5155.0  399.27  5160.4  400.50  5165.0  401.53  5195.0  405.71
  5205.0  406.59  5235.0  410.06  5295.0  415.82  5322.5  418.01  5325.0  418.01
#Mann=4,-1,0
  4720.9    0.05       0  4910.5   0.033       0  4916.5    0.05       0
  5149.9    0.16       0
Bank Sta=4897.3,5160.4
Exp/Cntr=0.3,0.1

Type RM Length L Ch R = 1,2873,365,365,365
BEGIN DESCRIPTION:
UNT 195 in LFCCL Watershed 8.0
END DESCRIPTION:
XS GIS Cut Line= 3
      2839524.96      7026074.99      2839225.00      7025975.00
      2838875.00      7026375.00
#Sta/Elev= 30
  4686.0  414.31  4749.2  409.26  4801.9  403.67  4825.5  400.35  4841.1  399.21
  4841.6  398.41  4846.6  398.41  4847.1  399.21  5182.5  399.21  5236.1  399.23
  5240.3  400.35  5264.6  402.86  5271.3  404.23  5278.9  404.41  5299.7  407.46
  5307.3  407.46  5314.0  408.88  5328.2  409.19  5334.9  410.64  5349.1  411.91
  5356.7  411.65  5391.8  415.14  5399.4  415.02  5420.3  416.57  5434.5  416.20
  5441.2  417.05  5448.8  416.84  5455.4  417.69  5498.1  419.56  5533.7  420.51
#Mann=4,-1,0
  4686.0    0.05       0  4841.1   0.033       0  4847.1    0.05       0
  5182.5    0.16       0
Bank Sta=4825.5,5240.3
Exp/Cntr=0.3,0.1

Type RM Length L Ch R = 1,2508,359,359,359
BEGIN DESCRIPTION:
UNT 195 in LFCCL Watershed 7.0
END DESCRIPTION:
XS GIS Cut Line= 3
      2839424.98      7025475.01      2839125.00      7025625.00
      2838875.00      7025975.00
#Sta/Elev= 30
  4657.5  414.55  4679.8  414.28  4688.2  413.51  4693.8  413.40  4716.2  411.63
  4732.9  409.57  4746.9  408.64  4769.3  406.36  4783.3  405.33  4800.0  401.10
  4805.6  401.07  4809.7  400.20  4814.0  399.29  4819.4  399.21  4819.9  398.41
  4824.9  398.41  4825.4  399.21  5201.8  399.21  5208.1  400.20  5214.1  400.95
  5222.7  401.52  5237.4  404.20  5243.6  404.91  5264.5  407.02  5287.8  408.90
  5300.1  410.79  5308.7  411.32  5359.1  416.20  5386.1  419.53  5423.0  420.63
#Mann=3,-1,0
  4657.5    0.05       0  4819.4   0.033       0  4825.4    0.05       0
Bank Sta=4809.7,5208.1
Exp/Cntr=0.3,0.1

Type RM Length L Ch R = 1,2149,0,0,0
BEGIN DESCRIPTION:
UNT 195 in LFCCL Watershed 6.0
END DESCRIPTION:
XS GIS Cut Line= 3
      2839375.05      7025425.01      2838925.00      7025325.00
      2838775.00      7025925.01
#Sta/Elev= 30
  4544.9  413.14  4564.2  411.79  4569.3  411.96  4596.2  409.36  4612.8  408.21
  4617.9  408.23  4637.1  406.31  4647.4  405.14  4656.4  401.74  4661.5  403.48
  4664.5  399.67  4664.9  399.21  4665.4  398.41  4670.4  398.41  4670.9  399.21
  5304.9  399.21  5312.7  399.67  5317.7  401.89  5346.1  404.33  5395.0  406.03
  5400.2  406.65  5436.3  408.15  5477.5  410.70  5490.4  411.21  5518.7  413.26
  5560.0  415.12  5565.1  414.81  5593.5  416.19  5606.4  415.82  5624.4  416.52
#Mann=3,-1,0
  4544.9    0.05       0  4664.9   0.033       0  4670.9    0.05       0
Bank Sta=4664.5,5312.7
Exp/Cntr=0.3,0.1

Chan Stop Cuts=-1