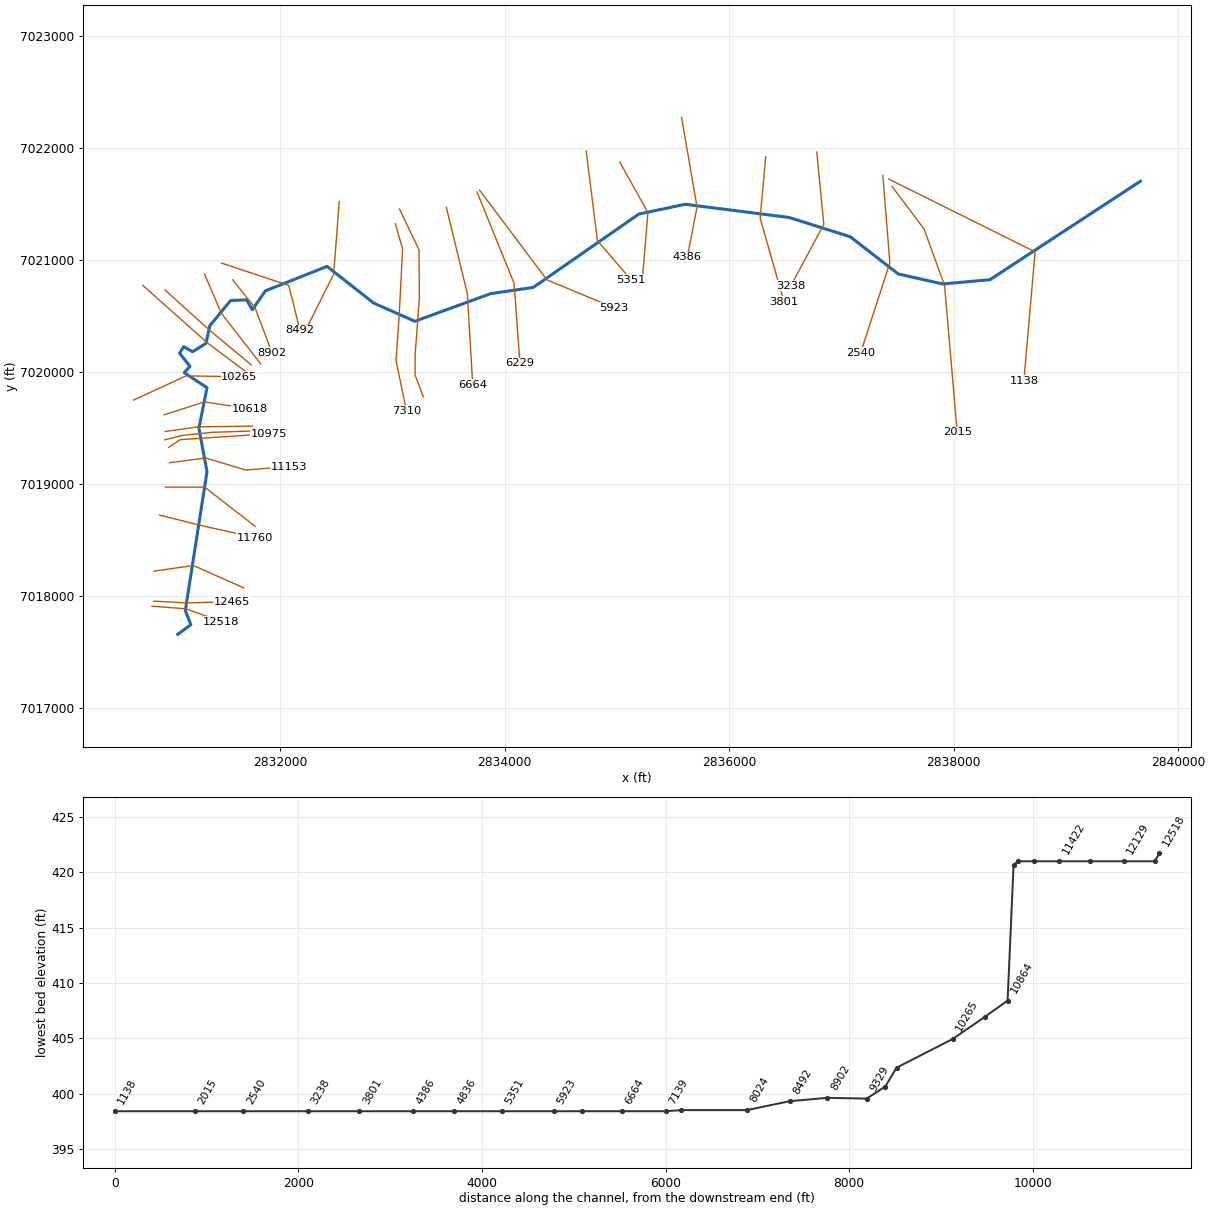
--- UNT 199 in LFCCL Watershed.prj (project) ---

Proj Title=UNT 199 in LFCCL Watershed Base Level Engineering
Current Plan=p01
Default Exp/Contr=0.3,0.1
English Units
Geom File=g01
Flow File=f01
Plan File=p01
BEGIN DESCRIPTION:
UNT 199 in LFCCL Watershed
END DESCRIPTION:

--- UNT 199 in LFCCL Watershed.p01 (plan) ---

Plan Title=Multiple Run
Short Identifier=Multiple
Geom File=g01
Flow File=f01
Subcritical Flow
K Sum by GR= 0
Std Step Tol= 0.01
Critical Tol= 0.01
Num of Std Step Trials= 20
Max Error Tol= 0.3
Flow Tol Ratio= 0.001
Split Flow NTrial= 30
Split Flow Tol= 0.02
Split Flow Ratio= 0.02
Log Output Level= 0
Friction Slope Method= 1
Unsteady Friction Slope Method= 2
Unsteady Bridges Friction Slope Method= 1
Parabolic Critical Depth
Global Vel Dist=  1 , 1 , 1
Global Log Level= 0
CheckData=True
Encroach Param= -1, 0, 0, 0
BEGIN DESCRIPTION:
Multiple Run
END DESCRIPTION:

--- UNT 199 in LFCCL Watershed.f01 (steady flow) ---

Flow Title=Multiple
Number of Profiles=7
Profile Names=10-year,25-year,50-year,1pct_min,100-year,1pct_plu,500-year
River Rch & RM= UNT 199 in LFCCL,Reach-1,12518
     484     640     765     455     909    1813    1282
River Rch & RM= UNT 199 in LFCCL,Reach-1,8024
     788    1062    1285     771    1539    3071    2213
River Rch & RM= UNT 199 in LFCCL,Reach-1,2015
     873    1180    1431     860    1716    3424    2474
Boundary for River Rch & Prof#=UNT 199 in LFCCL,Reach-1,1
Up Type=0
Dn Type=3
Dn Slope=0.005
Boundary for River Rch & Prof#=UNT 199 in LFCCL,Reach-1,2
Up Type=0
Dn Type=3
Dn Slope=0.005
Boundary for River Rch & Prof#=UNT 199 in LFCCL,Reach-1,3
Up Type=0
Dn Type=3
Dn Slope=0.005
Boundary for River Rch & Prof#=UNT 199 in LFCCL,Reach-1,4
Up Type=0
Dn Type=3
Dn Slope=0.005
Boundary for River Rch & Prof#=UNT 199 in LFCCL,Reach-1,5
Up Type=0
Dn Type=3
Dn Slope=0.005
Boundary for River Rch & Prof#=UNT 199 in LFCCL,Reach-1,6
Up Type=0
Dn Type=3
Dn Slope=0.005
Boundary for River Rch & Prof#=UNT 199 in LFCCL,Reach-1,7
Up Type=0
Dn Type=3
Dn Slope=0.005

--- UNT 199 in LFCCL Watershed.g01 (geometry) ---

Geom Title=Existing Conditions

River Reach=UNT 199 in LFCCL,Reach-1
Reach XY= 30
      2831085.40      7017660.72      2831202.24      7017746.57
      2831153.20      7017873.48      2831346.45      7019112.30
      2831274.34      7019500.25      2831346.45      7019862.23
      2831143.97      7019996.23      2831194.90      7020052.82
      2831102.46      7020169.78      2831138.25      7020229.20
      2831217.20      7020183.36      2831336.91      7020257.22
      2831372.57      7020416.83      2831556.80      7020640.12
      2831698.59      7020646.06      2831750.38      7020557.77
      2831866.69      7020726.72      2832416.24      7020944.72
      2832831.49      7020617.59      2833198.15      7020454.83
      2833874.24      7020701.65      2834253.42      7020757.10
      2835194.22      7021411.73      2835607.39      7021499.37
      2836533.88      7021381.32      2837077.23      7021209.77
      2837505.29      7020877.54      2837901.40      7020788.10
      2838323.07      7020826.43      2839663.45      7021705.33

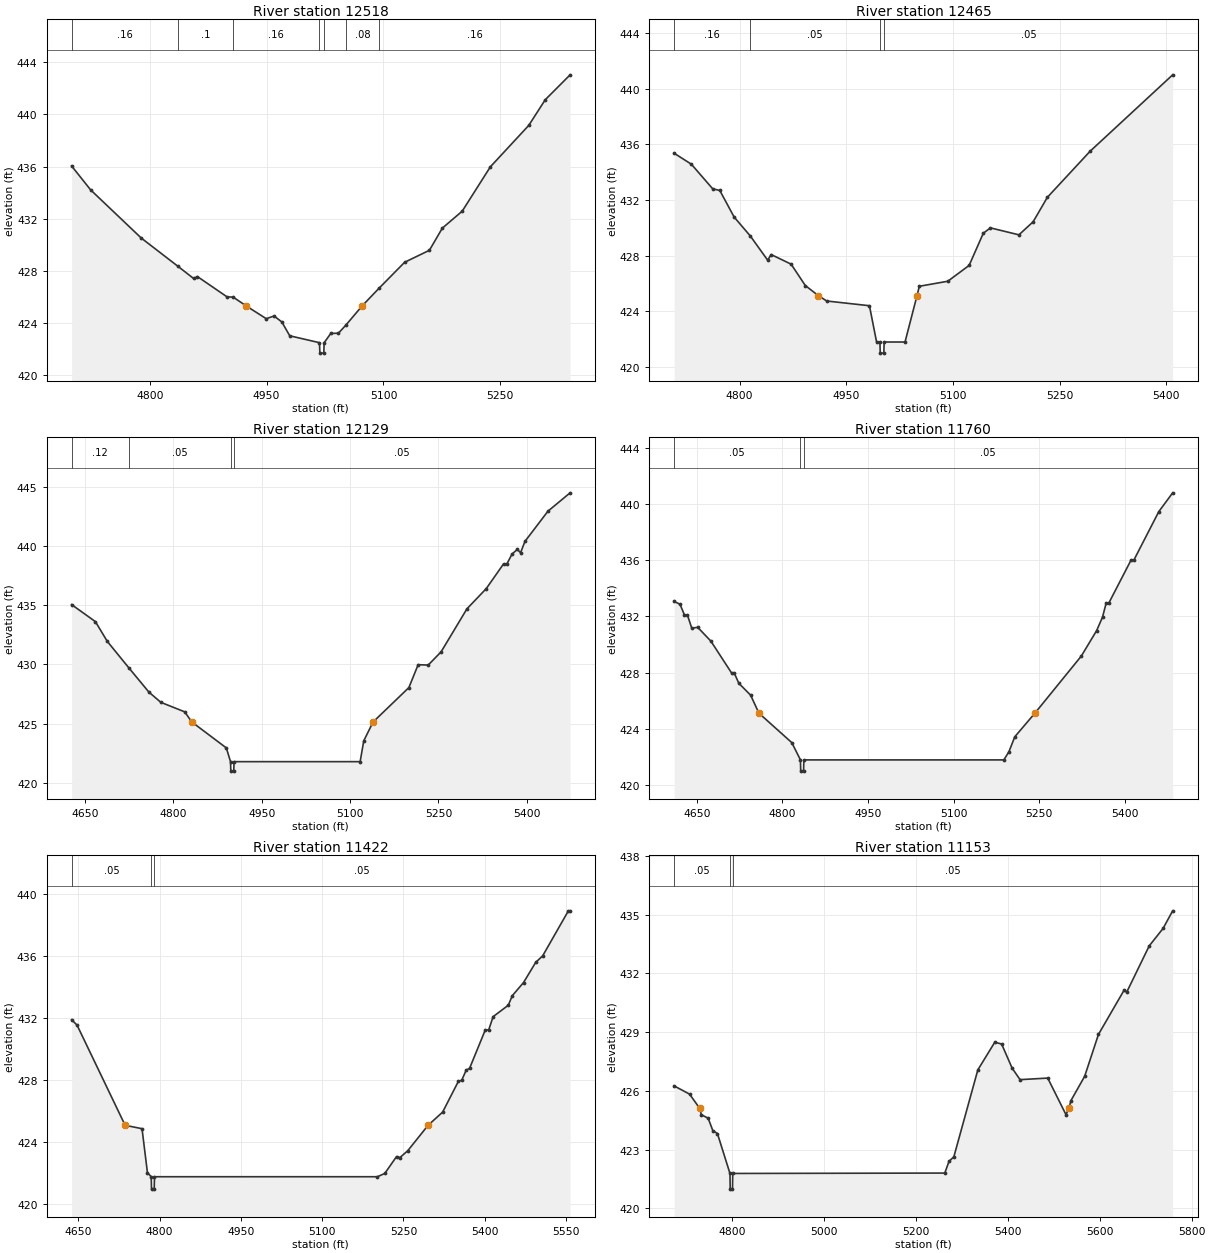
Type RM Length L Ch R = 1,12518,53,53,53
BEGIN DESCRIPTION:
UNT 199 in LFCCL Watershed 22.0
END DESCRIPTION:
XS GIS Cut Line= 3
      2830855.82      7017911.85      2831155.32      7017889.39
      2831475.03      7017774.99
#Sta/Elev= 30
  4699.7  436.05  4724.2  434.21  4789.1  430.52  4835.8  428.37  4856.2  427.42
  4861.3  427.56  4899.4  426.00  4907.0  425.99  4923.9  425.31  4949.6  424.33
  4959.6  424.54  4969.6  424.08  4979.7  423.02  5017.9  422.49  5018.4  421.69
  5023.4  421.69  5023.9  422.49  5032.4  423.20  5042.2  423.22  5051.8  423.84
  5072.6  425.31  5094.7  426.69  5127.2  428.66  5159.0  429.58  5175.6  431.28
  5201.1  432.58  5237.2  435.98  5286.5  439.16  5307.7  441.13  5339.6  443.04
#Mann=7,-1,0
  4699.7    0.16       0  4835.8     0.1       0  4907.0    0.16       0
  5017.9    0.07       0  5023.9    0.16       0  5051.8    0.08       0
  5094.7    0.16       0
Bank Sta=4923.9,5072.6
Exp/Cntr=0.3,0.1

Type RM Length L Ch R = 1,12465,336,336,336
BEGIN DESCRIPTION:
XS4230A
END DESCRIPTION:
XS GIS Cut Line= 3
      2830870.84      7017956.77      2831165.30      7017941.80
      2831571.04      7017951.76
#Sta/Elev= 30
  4708.1  435.36  4732.3  434.57  4762.3  432.80  4772.3  432.68  4792.4  430.77
  4815.1  429.41  4839.5  427.67  4844.5  428.07  4872.5  427.38  4892.5  425.84
  4910.7  425.12  4922.5  424.73  4982.6  424.39  4992.6  421.79  4997.3  421.78
  4997.8  420.98  5002.8  420.98  5003.3  421.78  5032.6  421.78  5049.5  425.12
  5052.7  425.79  5092.7  426.15  5122.7  427.29  5142.7  429.61  5152.7  429.99
  5192.7  429.49  5212.7  430.43  5232.7  432.19  5292.7  435.50  5408.8  441.00
#Mann=4,-1,0
  4708.1    0.16       0  4815.1    0.05       0  4997.3   0.035       0
  5003.3    0.05       0
Bank Sta=4910.7,5049.5
Exp/Cntr=0.3,0.1

Type RM Length L Ch R = 1,12129,369,369,369
BEGIN DESCRIPTION:
UNT 199 in LFCCL Watershed 21.0
END DESCRIPTION:
XS GIS Cut Line= 3
      2830875.00      7018225.00      2831225.00      7018275.00
      2831675.00      7018075.00
#Sta/Elev= 30
  4627.4  435.05  4667.8  433.61  4688.0  431.94  4724.3  429.72  4758.7  427.65
  4778.9  426.79  4819.3  425.99  4831.5  425.13  4890.0  422.94  4897.1  421.78
  4897.6  420.98  4902.6  420.98  4903.1  421.78  5117.1  421.78  5123.2  423.54
  5139.0  425.13  5199.8  428.04  5215.5  429.97  5232.6  429.94  5254.5  431.06
  5298.3  434.69  5331.1  436.40  5360.5  438.49  5366.0  438.48  5374.9  439.32
  5383.8  439.71  5389.3  439.43  5396.8  440.39  5435.8  442.94  5473.4  444.49
#Mann=4,-1,0
  4627.4    0.12       0  4724.3    0.05       0  4897.1   0.035       0
  4903.1    0.05       0
Bank Sta=4831.5,5139
Exp/Cntr=0.3,0.1

Type RM Length L Ch R = 1,11760,338,338,338
BEGIN DESCRIPTION:
UNT 199 in LFCCL Watershed 20.0
END DESCRIPTION:
XS GIS Cut Line= 3
      2830925.04      7018724.99      2831325.00      7018625.00
      2831774.95      7018525.01
#Sta/Elev= 30
  4610.3  433.07  4620.6  432.87  4628.3  432.11  4633.5  432.11  4641.2  431.16
  4651.5  431.23  4674.7  430.24  4710.8  427.98  4715.9  427.94  4723.6  427.24
  4744.3  426.39  4758.8  425.11  4816.4  423.01  4831.5  421.78  4832.0  420.98
  4837.0  420.98  4837.5  421.78  5187.8  421.78  5196.7  422.36  5207.0  423.43
  5242.2  425.11  5323.5  429.18  5350.4  431.00  5360.6  431.95  5367.0  432.95
  5372.1  432.99  5410.6  436.02  5415.7  436.03  5459.2  439.47  5483.5  440.81
#Mann=3,-1,0
  4610.3    0.05       0  4831.5   0.033       0  4837.5    0.05       0
Bank Sta=4758.8,5242.2
Exp/Cntr=0.3,0.1

Type RM Length L Ch R = 1,11422,269,269,269
BEGIN DESCRIPTION:
UNT 199 in LFCCL Watershed 19.0
END DESCRIPTION:
XS GIS Cut Line= 3
      2830975.02      7018975.00      2831325.00      7018975.00
      2831775.02      7018624.98
#Sta/Elev= 30
  4637.6  431.91  4647.6  431.57  4736.4  425.10  4767.6  424.88  4777.6  422.04
  4784.6  421.78  4785.1  420.98  4790.1  420.98  4790.6  421.78  5202.0  421.78
  5215.6  421.99  5237.3  423.08  5243.7  423.02  5258.1  423.46  5295.6  425.10
  5322.4  425.95  5351.4  427.93  5357.7  428.01  5365.8  428.65  5372.2  428.78
  5401.1  431.25  5407.5  431.26  5415.6  432.11  5443.7  432.85  5450.9  433.46
  5471.7  434.31  5494.3  435.62  5507.0  436.03  5554.5  438.94  5557.7  438.94
#Mann=3,-1,0
  4637.6    0.05       0  4784.6   0.033       0  4790.6    0.05       0
Bank Sta=4736.4,5295.6
Exp/Cntr=0.3,0.1

Type RM Length L Ch R = 1,11153,178,178,178
BEGIN DESCRIPTION:
XS4234A
END DESCRIPTION:
XS GIS Cut Line= 4
      2831011.66      7019192.27      2831336.22      7019234.79
      2831690.39      7019127.15      2832075.82      7019158.40
#Sta/Elev= 30
  4674.5  426.25  4708.1  425.83  4730.2  425.10  4733.7  424.78  4748.5  424.60
  4758.6  423.97  4768.6  423.82  4795.9  421.78  4796.4  420.98  4801.4  420.98
  4801.9  421.78  5263.1  421.80  5272.3  422.40  5282.8  422.63  5335.0  427.07
  5371.8  428.48  5386.7  428.39  5409.5  427.16  5426.8  426.57  5487.0  426.65
  5526.5  424.79  5533.3  425.10  5537.2  425.49  5567.3  426.74  5597.3  428.88
  5653.6  431.16  5658.6  431.03  5707.7  433.40  5737.8  434.29  5758.7  435.19
#Mann=3,-1,0
  4674.5    0.05       0  4795.9   0.033       0  4801.9    0.05       0
Bank Sta=4730.2,5533.3
Exp/Cntr=0.3,0.1

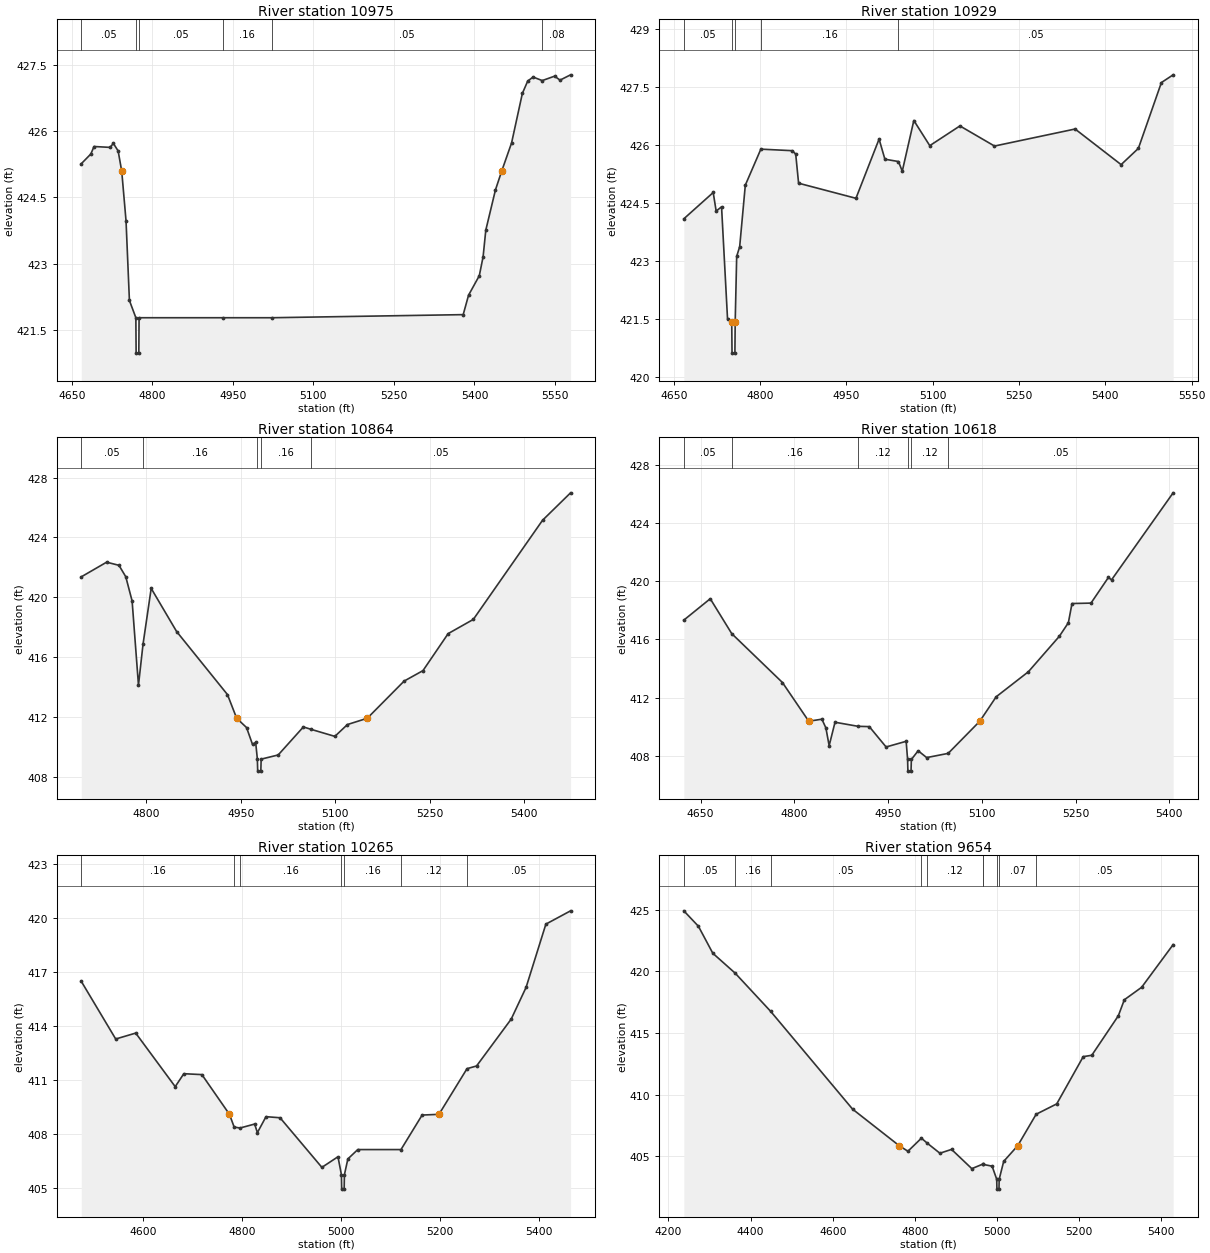
Type RM Length L Ch R = 1,10975,46,46,46
BEGIN DESCRIPTION:
XS4233A
END DESCRIPTION:
XS GIS Cut Line= 4
      2831005.91      7019329.61      2831107.05      7019397.99
      2831673.03      7019436.18      2831894.65      7019450.03
#Sta/Elev= 30
  4667.6  425.26  4685.4  425.48  4691.4  425.65  4721.3  425.63  4727.4  425.72
  4736.3  425.55  4743.0  425.09  4751.0  423.97  4757.3  422.17  4769.3  421.78
  4769.8  420.98  4774.8  420.98  4775.3  421.78  4930.9  421.78  5022.7  421.78
  5379.0  421.85  5389.0  422.29  5409.0  422.73  5416.1  423.16  5421.1  423.76
  5439.1  424.67  5450.6  425.09  5469.1  425.73  5489.2  426.85  5499.2  427.13
  5509.2  427.22  5526.2  427.14  5549.3  427.24  5559.3  427.15  5579.0  427.27
#Mann=6,-1,0
  4667.6    0.05       0  4769.3    0.07       0  4775.3    0.05       0
  4930.9    0.16       0  5022.7    0.05       0  5526.2    0.08       0
Bank Sta=4743,5450.6
Exp/Cntr=0.3,0.1

Type RM Length L Ch R = 1,10929,65,65,65
BEGIN DESCRIPTION:
XS4232A
END DESCRIPTION:
XS GIS Cut Line= 4
      2830971.39      7019397.16      2831124.41      7019436.18
      2831395.25      7019463.96      2831815.35      7019477.85
#Sta/Elev= 30
  4667.3  424.09  4718.4  424.77  4723.5  424.29  4732.9  424.40  4743.3  421.50
  4750.6  421.42  4751.1  420.62  4756.1  420.62  4756.6  421.42  4759.2  423.12
  4764.4  423.37  4774.2  424.96  4801.2  425.89  4856.0  425.85  4861.8  425.76
  4866.8  425.01  4966.5  424.62  5006.7  426.15  5016.8  425.63  5040.4  425.57
  5047.0  425.32  5067.1  426.63  5094.8  425.98  5147.2  426.49  5207.3  425.97
  5347.4  426.41  5427.4  425.49  5457.4  425.91  5497.4  427.61  5517.8  427.81
#Mann=5,-1,0
  4667.3    0.05       0  4750.6    0.07       0  4756.6    0.05       0
  4801.2    0.16       0  5040.4    0.05       0
Bank Sta=4750.6,4756.6
Exp/Cntr=0.3,0.1

Type RM Length L Ch R = 1,10864,246,246,246
BEGIN DESCRIPTION:
XS4231A
END DESCRIPTION:
XS GIS Cut Line= 3
      2830975.06      7019470.90      2831266.78      7019512.57
      2831749.45      7019519.51
#Sta/Elev= 30
  4696.4  421.37  4736.7  422.35  4756.3  422.14  4767.1  421.38  4777.2  419.76
  4787.3  414.14  4794.5  416.86  4807.5  420.60  4847.9  417.72  4928.7  413.51
  4943.3  411.93  4959.0  411.31  4968.5  410.18  4973.5  410.32  4976.2  409.20
  4976.7  408.40  4981.7  408.40  4982.2  409.20  5009.3  409.48  5049.3  411.35
  5061.5  411.19  5099.3  410.72  5119.3  411.51  5150.8  411.93  5209.3  414.41
  5239.3  415.11  5279.3  417.58  5319.3  418.53  5429.3  425.15  5473.8  426.98
#Mann=5,-1,0
  4696.4    0.05       0  4794.5    0.16       0  4976.2    0.07       0
  4982.2    0.16       0  5061.5    0.05       0
Bank Sta=4943.3,5150.8
Exp/Cntr=0.3,0.1

Type RM Length L Ch R = 1,10618,353,353,353
BEGIN DESCRIPTION:
UNT 199 in LFCCL Watershed 17.0
END DESCRIPTION:
XS GIS Cut Line= 3
      2830964.70      7019620.21      2831323.38      7019735.32
      2831724.97      7019675.00
#Sta/Elev= 30
  4623.3  417.32  4665.6  418.79  4700.0  416.39  4781.1  413.03  4823.2  410.37
  4844.2  410.51  4850.6  409.91  4855.8  408.69  4865.2  410.30  4902.1  410.02
  4920.0  410.00  4946.9  408.60  4979.0  408.99  4981.3  407.74  4981.8  406.94
  4986.8  406.94  4987.3  407.74  4998.2  408.34  5011.8  407.87  5046.2  408.16
  5096.8  410.37  5123.0  412.05  5174.5  413.77  5224.1  416.21  5238.5  417.14
  5244.3  418.46  5274.7  418.49  5302.5  420.25  5307.6  420.09  5406.1  426.07
#Mann=6,-1,0
  4623.3    0.05       0  4700.0    0.16       0  4902.1    0.12       0
  4981.3    0.07       0  4987.3    0.12       0  5046.2    0.05       0
Bank Sta=4823.2,5096.8
Exp/Cntr=0.3,0.1

Type RM Length L Ch R = 1,10265,611,611,611
BEGIN DESCRIPTION:
XS4235A
END DESCRIPTION:
XS GIS Cut Line= 3
      2830693.82      7019752.14      2831159.14      7019967.43
      2831634.88      7019960.48
#Sta/Elev= 30
  4475.0  416.49  4544.6  413.28  4585.0  413.61  4664.8  410.63  4682.2  411.35
  4718.7  411.30  4774.4  409.09  4783.9  408.38  4795.8  408.33  4825.3  408.55
  4830.8  408.07  4848.2  408.96  4876.6  408.90  4961.1  406.14  4993.6  406.73
  5000.6  405.73  5001.1  404.93  5006.1  404.93  5006.6  405.73  5013.6  406.61
  5033.6  407.13  5120.9  407.13  5163.6  409.05  5197.6  409.09  5254.3  411.63
  5273.6  411.78  5343.6  414.39  5373.6  416.15  5413.6  419.67  5463.5  420.41
#Mann=7,-1,0
  4475.0    0.16       0  4783.9    0.05       0  4795.8    0.16       0
  5000.6    0.07       0  5006.6    0.16       0  5120.9    0.12       0
  5254.3    0.05       0
Bank Sta=4774.4,5197.6
Exp/Cntr=0.3,0.1

Type RM Length L Ch R = 1,9654,122,122,122
BEGIN DESCRIPTION:
UNT 199 in LFCCL Watershed 15.0
END DESCRIPTION:
XS GIS Cut Line= 3
      2830775.04      7020774.97      2831350.11      7020262.57
      2831686.30      7020009.56
#Sta/Elev= 30
  4237.6  424.90  4273.1  423.65  4308.2  421.46  4362.5  419.85  4449.0  416.75
  4648.5  408.82  4761.9  405.86  4783.1  405.41  4815.9  406.47  4830.7  406.05
  4860.9  405.25  4889.3  405.56  4938.6  404.00  4966.2  404.38  4967.0  404.34
  4988.0  404.20  4999.2  403.14  4999.7  402.34  5004.7  402.34  5005.2  403.14
  5016.2  404.59  5050.3  405.86  5095.2  408.41  5145.3  409.25  5209.8  413.08
  5230.6  413.19  5295.2  416.39  5309.8  417.69  5351.9  418.70  5428.6  422.16
#Mann=10,-1,0
  4237.6    0.05       0  4362.5    0.16       0  4449.0    0.05       0
  4815.9    0.16       0  4830.7    0.12       0  4966.2    0.05       0
  4967.0    0.07       0  4999.2    0.07       0  5005.2    0.07       0
  5095.2    0.05       0
Bank Sta=4761.9,5050.3
Exp/Cntr=0.3,0.1

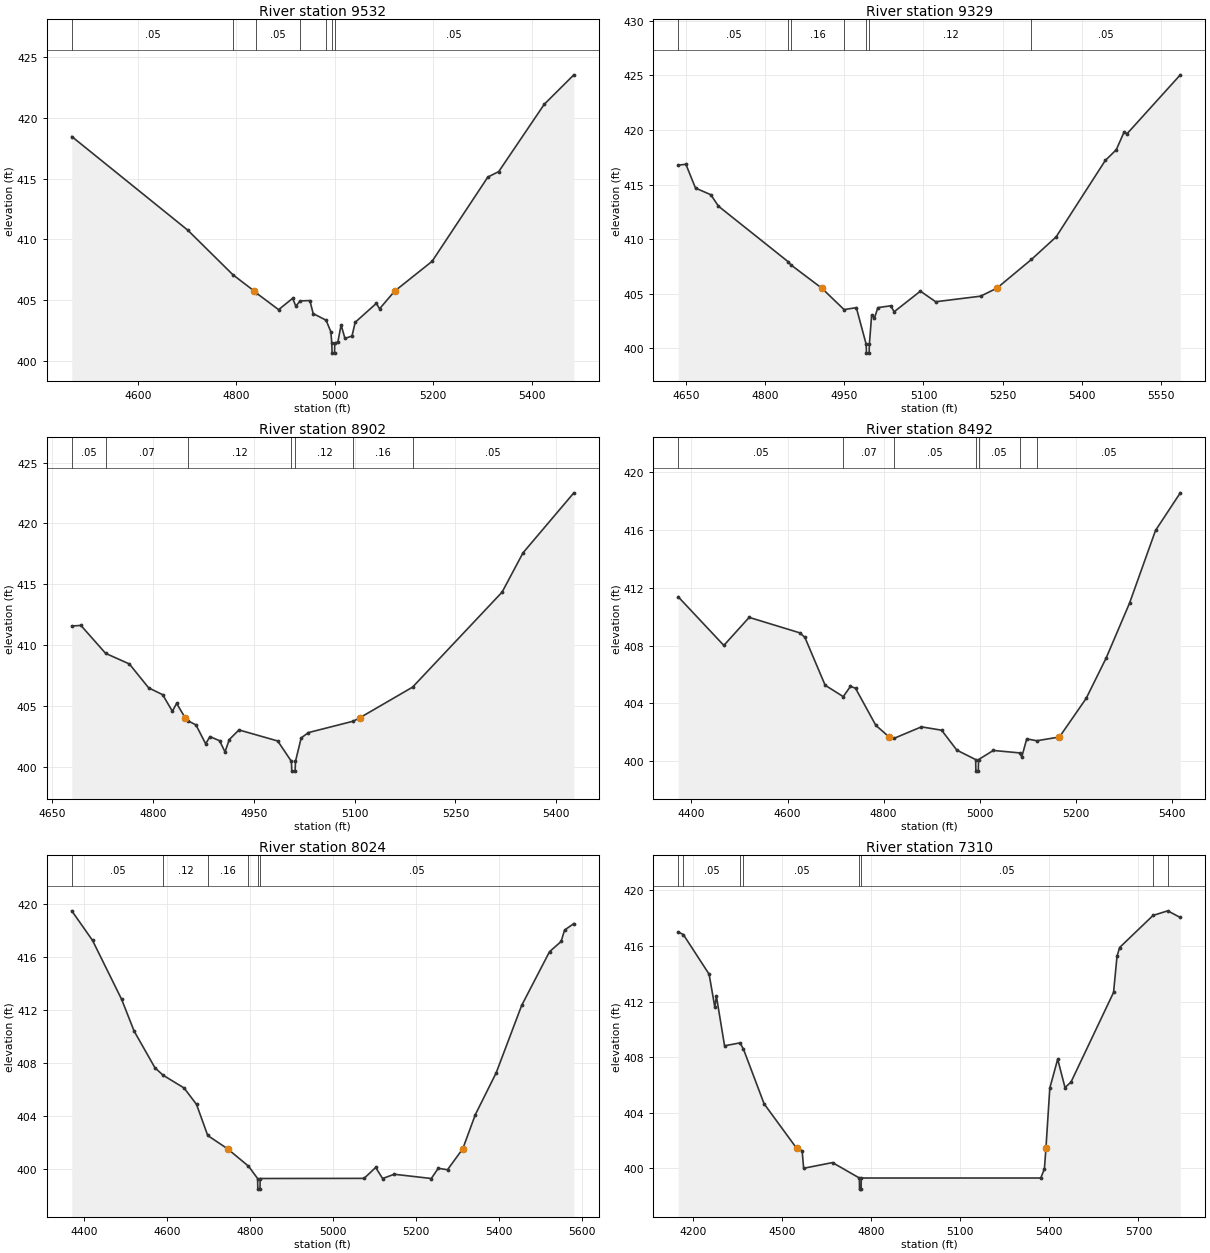
Type RM Length L Ch R = 1,9532,203,203,203
BEGIN DESCRIPTION:
XS4236A
END DESCRIPTION:
XS GIS Cut Line= 3
      2830971.66      7020734.77      2831367.47      7020377.15
      2831741.26      7020065.66
#Sta/Elev= 30
  4465.7  418.48  4701.3  410.77  4793.2  407.09  4836.8  405.74  4840.1  405.61
  4885.9  404.22  4914.3  405.15  4921.0  404.51  4929.6  404.94  4949.4  404.97
  4956.1  403.90  4982.4  403.35  4992.0  402.40  4994.0  401.44  4994.5  400.64
  4999.5  400.64  5000.0  401.44  5006.4  401.58  5012.9  402.96  5020.7  401.85
  5035.0  402.05  5041.5  403.18  5084.5  404.74  5091.0  404.29  5121.5  405.74
  5197.7  408.20  5311.0  415.14  5333.1  415.59  5425.5  421.13  5485.7  423.56
#Mann=7,-1,0
  4465.7    0.05       0  4793.2    0.12       0  4840.1    0.05       0
  4929.6    0.16       0  4982.4    0.05       0  4994.0    0.04       0
  5000.0    0.05       0
Bank Sta=4836.8,5121.5
Exp/Cntr=0.3,0.1

Type RM Length L Ch R = 1,9329,427,427,427
BEGIN DESCRIPTION:
UNT 199 in LFCCL Watershed 14.0
END DESCRIPTION:
XS GIS Cut Line= 3
      2831324.99      7020875.01      2831475.00      7020525.00
      2831825.01      7020074.99
#Sta/Elev= 30
  4635.6  416.78  4650.1  416.86  4668.3  414.68  4697.3  414.07  4711.8  413.02
  4844.3  407.91  4848.7  407.65  4907.6  405.50  4949.7  403.54  4972.9  403.72
  4991.6  400.35  4992.1  399.55  4997.1  399.55  4997.6  400.35  5001.9  403.02
  5007.3  402.77  5013.7  403.72  5038.1  403.89  5044.5  403.34  5094.2  405.23
  5123.2  404.26  5208.2  404.77  5239.0  405.50  5304.6  408.14  5351.2  410.20
  5444.4  417.21  5465.2  418.19  5479.7  419.78  5486.0  419.68  5586.5  425.06
#Mann=7,-1,0
  4635.6    0.05       0  4844.3    0.12       0  4848.7    0.16       0
  4949.7    0.12       0  4991.6    0.07       0  4997.6    0.12       0
  5304.6    0.05       0
Bank Sta=4907.6,5239
Exp/Cntr=0.3,0.1

Type RM Length L Ch R = 1,8902,410,410,410
BEGIN DESCRIPTION:
UNT 199 in LFCCL Watershed 13.0
END DESCRIPTION:
XS GIS Cut Line= 3
      2831574.98      7020825.02      2831775.00      7020575.00
      2831925.01      7020174.98
#Sta/Elev= 30
  4678.8  411.56  4692.4  411.61  4729.2  409.31  4764.5  408.44  4793.3  406.47
  4814.1  405.91  4828.5  404.55  4834.9  405.19  4847.4  404.03  4852.2  403.75
  4863.7  403.42  4878.1  401.87  4884.5  402.46  4898.9  402.12  4906.9  401.20
  4913.3  402.22  4927.7  403.01  4985.4  402.10  5005.8  400.42  5006.3  399.62
  5011.3  399.62  5011.8  400.42  5020.3  402.35  5031.0  402.79  5097.9  403.73
  5108.2  404.03  5186.1  406.53  5319.4  414.35  5350.5  417.58  5426.2  422.52
#Mann=7,-1,0
  4678.8    0.05       0  4729.2    0.07       0  4852.2    0.12       0
  5005.8    0.07       0  5011.8    0.12       0  5097.9    0.16       0
  5186.1    0.05       0
Bank Sta=4847.4,5108.2
Exp/Cntr=0.3,0.1

Type RM Length L Ch R = 1,8492,468,468,468
BEGIN DESCRIPTION:
UNT 199 in LFCCL Watershed 12.0
END DESCRIPTION:
XS GIS Cut Line= 3
      2831474.99      7020975.00      2832075.00      7020775.00
      2832175.01      7020374.97
#Sta/Elev= 30
  4372.5  411.37  4467.4  408.01  4520.1  409.95  4625.5  408.88  4636.0  408.57
  4678.2  405.26  4715.9  404.47  4730.9  405.18  4741.4  405.05  4783.6  402.49
  4811.4  401.68  4821.1  401.58  4878.5  402.38  4920.6  402.15  4952.3  400.77
  4991.4  400.12  4991.9  399.32  4996.9  399.32  4997.4  400.12  5028.2  400.75
  5083.0  400.58  5087.4  400.30  5097.7  401.55  5118.7  401.42  5165.8  401.68
  5221.4  404.35  5262.7  407.12  5311.6  410.93  5365.7  415.96  5417.3  418.56
#Mann=7,-1,0
  4372.5    0.05       0  4715.9    0.07       0  4821.1    0.05       0
  4991.4   0.035       0  4997.4    0.05       0  5083.0    0.16       0
  5118.7    0.05       0
Bank Sta=4811.4,5165.8
Exp/Cntr=0.3,0.1

Type RM Length L Ch R = 1,8024,714,714,714
BEGIN DESCRIPTION:
UNT 199 in LFCCL Watershed 11.0
END DESCRIPTION:
XS GIS Cut Line= 3
      2832525.00      7021524.97      2832475.00      7020875.00
      2832225.00      7020375.01
#Sta/Elev= 30
  4370.2  419.47  4420.3  417.24  4490.5  412.80  4520.6  410.41  4570.8  407.65
  4590.4  407.09  4641.0  406.13  4671.1  404.89  4698.1  402.55  4745.8  401.55
  4796.4  400.24  4818.4  399.31  4818.9  398.51  4824.1  398.51  4824.6  399.31
  5075.2  399.32  5103.1  400.14  5119.9  399.31  5147.9  399.63  5237.3  399.31
  5254.1  400.08  5276.4  399.97  5313.2  401.55  5343.5  404.12  5393.8  407.27
  5455.3  412.35  5522.4  416.39  5550.4  417.16  5558.7  418.02  5581.1  418.51
#Mann=6,-1,0
  4370.2    0.05       0  4590.4    0.12       0  4698.1    0.16       0
  4796.4    0.05       0  4818.4   0.033       0  4824.6    0.05       0
Bank Sta=4745.8,5313.2
Exp/Cntr=0.3,0.1

Type RM Length L Ch R = 1,7310,171,171,171
BEGIN DESCRIPTION:
UNT 199 in LFCCL Watershed 10.0
END DESCRIPTION:
XS GIS Cut Line= 5
      2833025.01      7021324.98      2833089.69      7021099.37
      2833058.44      7020502.15      2833030.66      7020102.85
      2833124.41      7019654.96
#Sta/Elev= 30
  4150.2  417.01  4167.5  416.82  4254.2  413.97  4273.5  411.59  4278.7  412.39
  4306.2  408.82  4357.9  409.03  4369.7  408.59  4439.3  404.65  4549.2  401.44
  4567.4  401.27  4572.5  400.01  4669.7  400.42  4760.1  399.31  4760.6  398.51
  4766.0  398.51  4766.5  399.31  5371.0  399.31  5383.2  399.97  5388.3  401.44
  5401.4  405.78  5427.9  407.86  5452.5  405.82  5472.7  406.21  5616.0  412.66
  5627.7  415.26  5636.4  415.89  5749.1  418.20  5798.5  418.53  5840.8  418.05
#Mann=8,-1,0
  4150.2    0.08       0  4167.5    0.05       0  4357.9    0.08       0
  4369.7    0.05       0  4760.1    0.03       0  4766.5    0.05       0
  5749.1    0.16       0  5798.5    0.08       0
Bank Sta=4549.2,5388.3
Exp/Cntr=0.3,0.1

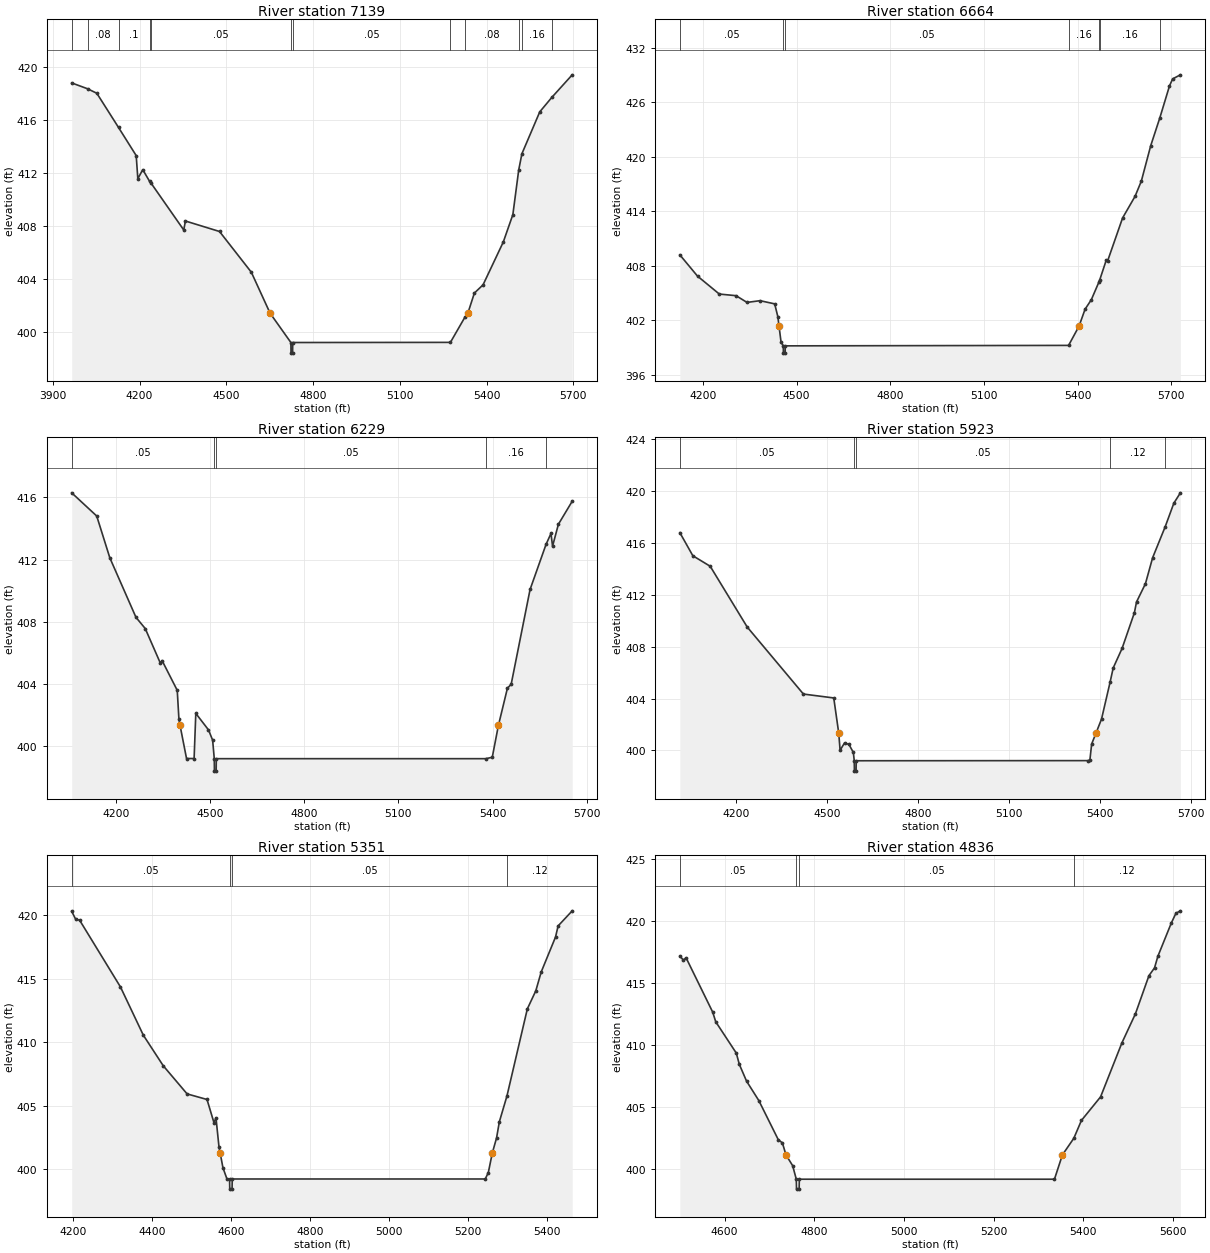
Type RM Length L Ch R = 1,7139,475,475,475
BEGIN DESCRIPTION:
XS4237A
END DESCRIPTION:
XS GIS Cut Line= 6
      2833061.93      7021456.98      2833235.53      7021092.43
      2833239.00      7020665.35      2833200.80      7020154.93
      2833200.80      7019974.37      2833273.71      7019779.96
#Sta/Elev= 30
  3965.4  418.78  4020.2  418.34  4052.3  418.00  4127.4  415.42  4188.5  413.30
  4194.1  411.56  4211.2  412.24  4234.5  411.37  4238.4  411.27  4353.0  407.69
  4358.6  408.37  4476.6  407.58  4586.6  404.51  4651.5  401.42  4723.4  399.21
  4723.9  398.41  4729.3  398.41  4729.8  399.21  5275.1  399.22  5324.7  401.10
  5335.4  401.42  5358.0  402.94  5388.0  403.56  5458.0  406.79  5491.0  408.85
  5511.3  412.22  5522.3  413.44  5584.1  416.60  5625.8  417.69  5696.3  419.39
#Mann=12,-1,0
  3965.4    0.05       0  4020.2    0.08       0  4127.4     0.1       0
  4234.5    0.08       0  4238.4    0.05       0  4723.4   0.033       0
  4729.8    0.05       0  5275.1     0.1       0  5324.7    0.08       0
  5511.3    0.05       0  5522.3    0.16       0  5625.8    0.05       0
Bank Sta=4651.5,5335.4
Exp/Cntr=0.3,0.1

Type RM Length L Ch R = 1,6664,435,435,435
BEGIN DESCRIPTION:
XS4238A
END DESCRIPTION:
XS GIS Cut Line= 3
      2833479.45      7021470.01      2833666.08      7020701.80
      2833713.82      7019890.16
#Sta/Elev= 30
  4126.0  409.22  4182.6  406.88  4252.4  404.91  4306.1  404.73  4341.1  403.99
  4382.9  404.18  4429.8  403.83  4439.9  402.42  4443.7  401.38  4450.2  399.62
  4457.3  399.21  4457.8  398.41  4463.2  398.41  4463.7  399.21  5371.4  399.26
  5404.9  401.38  5424.2  403.24  5444.3  404.29  5469.3  406.29  5470.8  406.43
  5491.8  408.61  5496.8  408.59  5544.4  413.28  5584.5  415.67  5604.5  417.34
  5634.6  421.24  5663.5  424.27  5694.7  427.81  5704.7  428.58  5729.6  429.03
#Mann=7,-1,0
  4126.0    0.05       0  4457.3   0.033       0  4463.7    0.05       0
  5371.4    0.16       0  5469.3    0.05       0  5470.8    0.16       0
  5663.5    0.05       0
Bank Sta=4443.7,5404.9
Exp/Cntr=0.3,0.1

Type RM Length L Ch R = 1,6229,306,306,306
BEGIN DESCRIPTION:
XS4239A
END DESCRIPTION:
XS GIS Cut Line= 3
      2833752.90      7021608.88      2834082.75      7020792.95
      2834134.83      7020081.13
#Sta/Elev= 30
  4059.6  416.29  4139.3  414.80  4181.1  412.11  4264.3  408.29  4293.8  407.57
  4342.1  405.34  4347.5  405.51  4395.7  403.60  4401.1  401.73  4404.6  401.35
  4425.3  399.22  4449.4  399.22  4454.8  402.12  4495.2  401.06  4508.4  400.40
  4513.6  399.21  4514.1  398.41  4519.6  398.41  4520.1  399.21  5378.3  399.21
  5398.8  399.30  5418.4  401.35  5447.1  403.74  5459.0  403.99  5519.2  410.08
  5570.1  412.98  5585.8  413.68  5590.8  412.86  5609.4  414.27  5653.4  415.75
#Mann=5,-1,0
  4059.6    0.05       0  4513.6   0.033       0  4520.1    0.05       0
  5378.3    0.16       0  5570.1    0.05       0
Bank Sta=4404.6,5418.4
Exp/Cntr=0.3,0.1

Type RM Length L Ch R = 1,5923,572,572,572
BEGIN DESCRIPTION:
UNT 199 in LFCCL Watershed 7.0
END DESCRIPTION:
XS GIS Cut Line= 3
      2833774.97      7021625.04      2834375.00      7020825.00
      2834974.96      7020575.02
#Sta/Elev= 30
  4013.7  416.79  4056.5  415.01  4113.7  414.20  4235.6  409.52  4421.0  404.35
  4521.0  404.05  4537.5  401.33  4541.9  400.02  4556.5  400.58  4571.0  400.47
  4585.6  399.85  4588.6  399.21  4589.1  398.41  4594.6  398.41  4595.1  399.21
  5359.9  399.22  5365.3  399.25  5371.2  400.50  5385.3  401.33  5403.7  402.42
  5431.8  405.25  5442.2  406.36  5471.5  407.87  5512.1  410.62  5519.1  411.45
  5548.4  412.85  5572.2  414.86  5613.5  417.24  5642.1  419.06  5663.7  419.86
#Mann=5,-1,0
  4013.7    0.05       0  4588.6   0.033       0  4595.1    0.05       0
  5431.8    0.12       0  5613.5    0.16       0
Bank Sta=4537.5,5385.3
Exp/Cntr=0.3,0.1

Type RM Length L Ch R = 1,5351,515,515,515
BEGIN DESCRIPTION:
UNT 199 in LFCCL Watershed 6.0
END DESCRIPTION:
XS GIS Cut Line= 3
      2834725.00      7021974.96      2834825.00      7021175.00
      2835125.02      7020824.97
#Sta/Elev= 30
  4197.3  420.32  4207.3  419.70  4217.4  419.62  4320.7  414.36  4378.7  410.55
  4429.1  408.14  4489.5  405.92  4539.9  405.48  4557.5  403.65  4562.6  404.04
  4570.1  401.77  4573.2  401.26  4580.2  400.10  4590.3  399.22  4597.0  399.21
  4597.5  398.41  4603.3  398.41  4603.8  399.21  5244.4  399.21  5252.1  399.72
  5262.2  401.26  5272.9  402.44  5280.1  403.73  5299.2  405.75  5350.9  412.63
  5372.3  414.05  5386.0  415.54  5422.2  418.29  5428.8  419.17  5464.5  420.36
#Mann=4,-1,0
  4197.3    0.05       0  4597.0   0.033       0  4603.8    0.05       0
  5299.2    0.12       0
Bank Sta=4573.2,5262.2
Exp/Cntr=0.3,0.1

Type RM Length L Ch R = 1,4836,450,450,450
BEGIN DESCRIPTION:
UNT 199 in LFCCL Watershed 5.0
END DESCRIPTION:
XS GIS Cut Line= 3
      2835024.98      7021875.04      2835275.00      7021425.00
      2835225.00      7020825.01
#Sta/Elev= 30
  4500.0  417.20  4508.1  416.87  4513.8  417.07  4573.3  412.68  4580.1  411.90
  4625.9  409.38  4632.7  408.47  4648.8  407.12  4676.2  405.55  4719.7  402.39
  4728.8  402.14  4736.8  401.17  4751.7  400.30  4759.8  399.21  4760.3  398.41
  4766.1  398.41  4766.6  399.21  5335.9  399.21  5353.6  401.17  5379.1  402.51
  5396.1  403.95  5438.8  405.85  5486.5  410.21  5516.6  412.55  5546.7  415.62
  5559.2  416.25  5566.7  417.19  5596.8  419.88  5606.9  420.65  5616.9  420.85
#Mann=4,-1,0
  4500.0    0.05       0  4759.8   0.033       0  4766.6    0.05       0
  5379.1    0.12       0
Bank Sta=4736.8,5353.6
Exp/Cntr=0.3,0.1

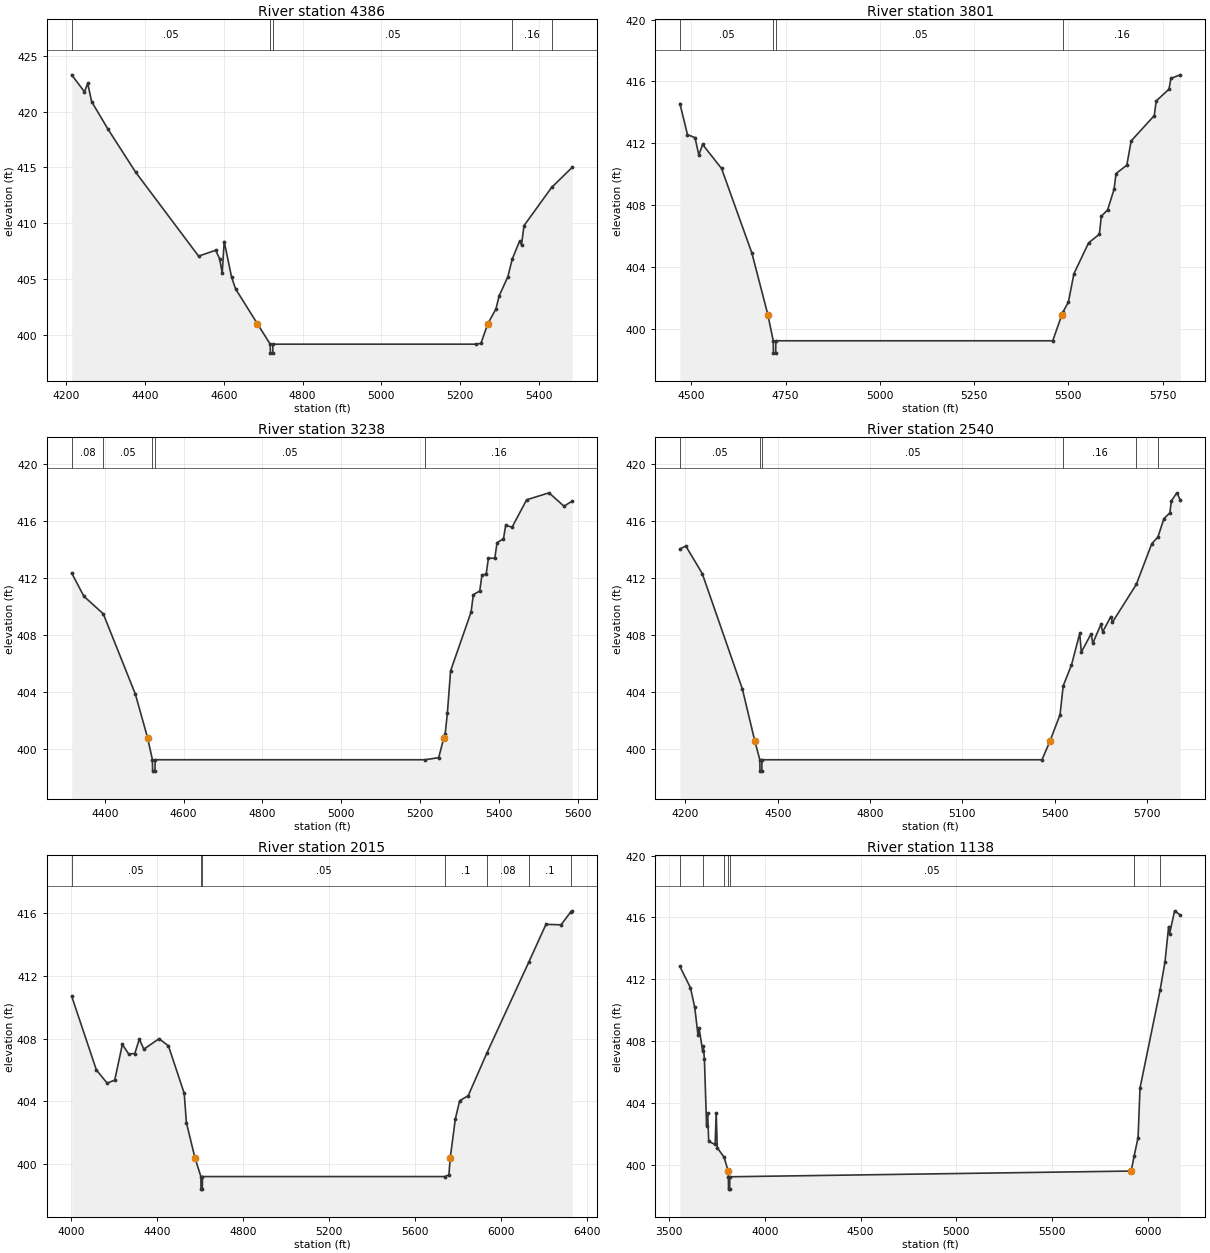
Type RM Length L Ch R = 1,4386,585,585,585
BEGIN DESCRIPTION:
UNT 199 in LFCCL Watershed 4.0
END DESCRIPTION:
XS GIS Cut Line= 3
      2835575.00      7022274.98      2835712.89      7021473.09
      2835625.00      7021024.99
#Sta/Elev= 30
  4214.1  423.28  4246.6  421.76  4254.7  422.52  4264.8  420.88  4306.5  418.41
  4376.4  414.58  4536.2  407.08  4579.4  407.60  4589.5  406.85  4596.1  405.58
  4601.2  408.38  4620.0  405.19  4630.1  404.15  4685.2  401.05  4718.0  399.21
  4718.5  398.41  4724.3  398.41  4724.8  399.21  5239.8  399.21  5252.8  399.28
  5270.4  401.05  5290.8  402.35  5299.2  403.54  5321.3  405.25  5332.1  406.80
  5350.7  408.40  5355.8  408.09  5362.1  409.80  5432.3  413.22  5484.4  415.01
#Mann=5,-1,0
  4214.1    0.05       0  4718.0   0.033       0  4724.8    0.05       0
  5332.1    0.16       0  5432.3    0.05       0
Bank Sta=4685.2,5270.4
Exp/Cntr=0.3,0.1

Type RM Length L Ch R = 1,3801,563,563,563
BEGIN DESCRIPTION:
UNT 199 in LFCCL Watershed 3.0
END DESCRIPTION:
XS GIS Cut Line= 3
      2836325.00      7021924.97      2836275.00      7021375.00
      2836487.91      7020629.45
#Sta/Elev= 30
  4469.6  414.57  4489.7  412.56  4509.7  412.36  4519.8  411.24  4529.8  411.92
  4580.0  410.37  4660.4  404.90  4702.8  400.91  4717.2  399.21  4717.7  398.41
  4723.6  398.41  4724.1  399.21  5458.6  399.21  5483.0  400.91  5485.3  401.05
  5500.2  401.72  5514.7  403.55  5553.7  405.55  5582.3  406.11  5587.5  407.27
  5604.2  407.69  5621.3  409.02  5626.5  410.04  5655.1  410.58  5666.6  412.15
  5727.9  413.79  5733.1  414.74  5766.9  415.50  5772.1  416.20  5797.2  416.43
#Mann=4,-1,0
  4469.6    0.05       0  4717.2   0.033       0  4724.1    0.05       0
  5485.3    0.16       0
Bank Sta=4702.8,5483
Exp/Cntr=0.3,0.1

Type RM Length L Ch R = 1,3238,698,698,698
BEGIN DESCRIPTION:
XS4240A
END DESCRIPTION:
XS GIS Cut Line= 3
      2836779.80      7021965.69      2836842.30      7021319.86
      2836549.41      7020773.23
#Sta/Elev= 30
  4316.3  412.34  4347.1  410.71  4396.4  409.47  4477.7  403.83  4508.6  400.77
  4521.0  399.21  4521.5  398.41  4527.4  398.41  4527.9  399.21  5212.6  399.21
  5246.9  399.36  5260.0  400.77  5263.2  401.00  5268.9  402.50  5277.0  405.46
  5329.0  409.60  5334.7  410.82  5350.9  411.08  5356.6  412.21  5367.2  412.26
  5372.9  413.38  5389.1  413.38  5394.8  414.47  5411.1  414.75  5416.7  415.69
  5433.0  415.57  5469.8  417.49  5526.6  417.98  5564.6  417.04  5585.3  417.40
#Mann=5,-1,0
  4316.3    0.08       0  4396.4    0.05       0  4521.0   0.033       0
  4527.9    0.05       0  5212.6    0.16       0
Bank Sta=4508.6,5260
Exp/Cntr=0.3,0.1

Type RM Length L Ch R = 1,2540,525,525,525
BEGIN DESCRIPTION:
XS4241A
END DESCRIPTION:
XS GIS Cut Line= 3
      2837368.34      7021757.36      2837430.84      7020976.11
      2837170.44      7020174.07
#Sta/Elev= 30
  4182.0  414.05  4201.1  414.26  4254.6  412.32  4385.0  404.20  4425.2  400.56
  4441.8  399.21  4442.3  398.41  4448.2  398.41  4448.7  399.21  5359.1  399.21
  5385.7  400.56  5417.8  402.39  5428.1  404.42  5455.0  405.88  5481.7  408.10
  5487.0  406.79  5518.9  408.08  5524.2  407.41  5550.9  408.75  5556.2  408.21
  5582.9  409.29  5588.1  408.89  5665.8  411.56  5716.0  414.42  5736.0  414.89
  5755.5  416.19  5774.6  416.58  5779.9  417.44  5797.5  418.00  5809.0  417.49
#Mann=6,-1,0
  4182.0    0.05       0  4441.8   0.033       0  4448.7    0.05       0
  5428.1    0.16       0  5665.8    0.05       0  5736.0    0.16       0
Bank Sta=4425.2,5385.7
Exp/Cntr=0.3,0.1

Type RM Length L Ch R = 1,2015,877,877,877
BEGIN DESCRIPTION:
XS4242A
END DESCRIPTION:
XS GIS Cut Line= 4
      2837449.50      7021659.71      2837735.96      7021277.76
      2837918.25      7020774.29      2838031.10      7019463.53
#Sta/Elev= 30
  4002.9  410.69  4117.7  406.00  4167.7  405.16  4203.1  405.35  4238.6  407.62
  4267.7  407.02  4296.3  407.04  4317.7  407.96  4338.6  407.32  4409.4  407.99
  4453.1  407.53  4526.4  404.51  4536.5  402.65  4576.6  400.39  4604.0  399.21
  4604.6  398.41  4610.7  398.41  4611.2  399.21  5737.7  399.21  5757.8  399.31
  5764.0  400.39  5787.9  402.89  5808.0  404.04  5847.7  404.36  5933.7  407.05
  6129.7  412.87  6209.5  415.27  6279.7  415.24  6325.7  416.08  6331.4  416.13
#Mann=7,-1,0
  4002.9    0.05       0  4604.0   0.033       0  4611.2    0.05       0
  5737.7     0.1       0  5933.7    0.08       0  6129.7     0.1       0
  6325.7    0.08       0
Bank Sta=4576.6,5764
Exp/Cntr=0.3,0.1

Type RM Length L Ch R = 1,1138,0,0,0
BEGIN DESCRIPTION:
UNT 199 in LFCCL Watershed 2.0
END DESCRIPTION:
XS GIS Cut Line= 3
      2837420.38      7021724.39      2838725.00      7021075.00
      2838625.00      7019925.04
#Sta/Elev= 30
  3557.2  412.82  3612.3  411.44  3634.7  410.17  3651.5  408.38  3657.1  408.86
  3675.7  407.37  3679.5  407.68  3685.2  406.80  3696.3  402.52  3701.8  403.31
  3707.6  401.50  3741.0  401.30  3746.6  403.35  3752.3  401.08  3787.6  400.48
  3809.1  399.58  3810.2  399.21  3810.8  398.41  3816.9  398.41  3817.4  399.21
  5912.2  399.58  5927.1  400.53  5948.0  401.75  5958.1  404.95  6062.9  411.29
  6088.5  413.12  6107.4  415.40  6112.4  414.95  6138.7  416.42  6168.8  416.14
#Mann=7,-1,0
  3557.2    0.05       0  3675.7    0.07       0  3787.6    0.05       0
  3810.2   0.033       0  3817.4    0.05       0  5927.1    0.16       0
  6062.9    0.08       0
Bank Sta=3809.1,5912.2
Exp/Cntr=0.3,0.1

Chan Stop Cuts=-1