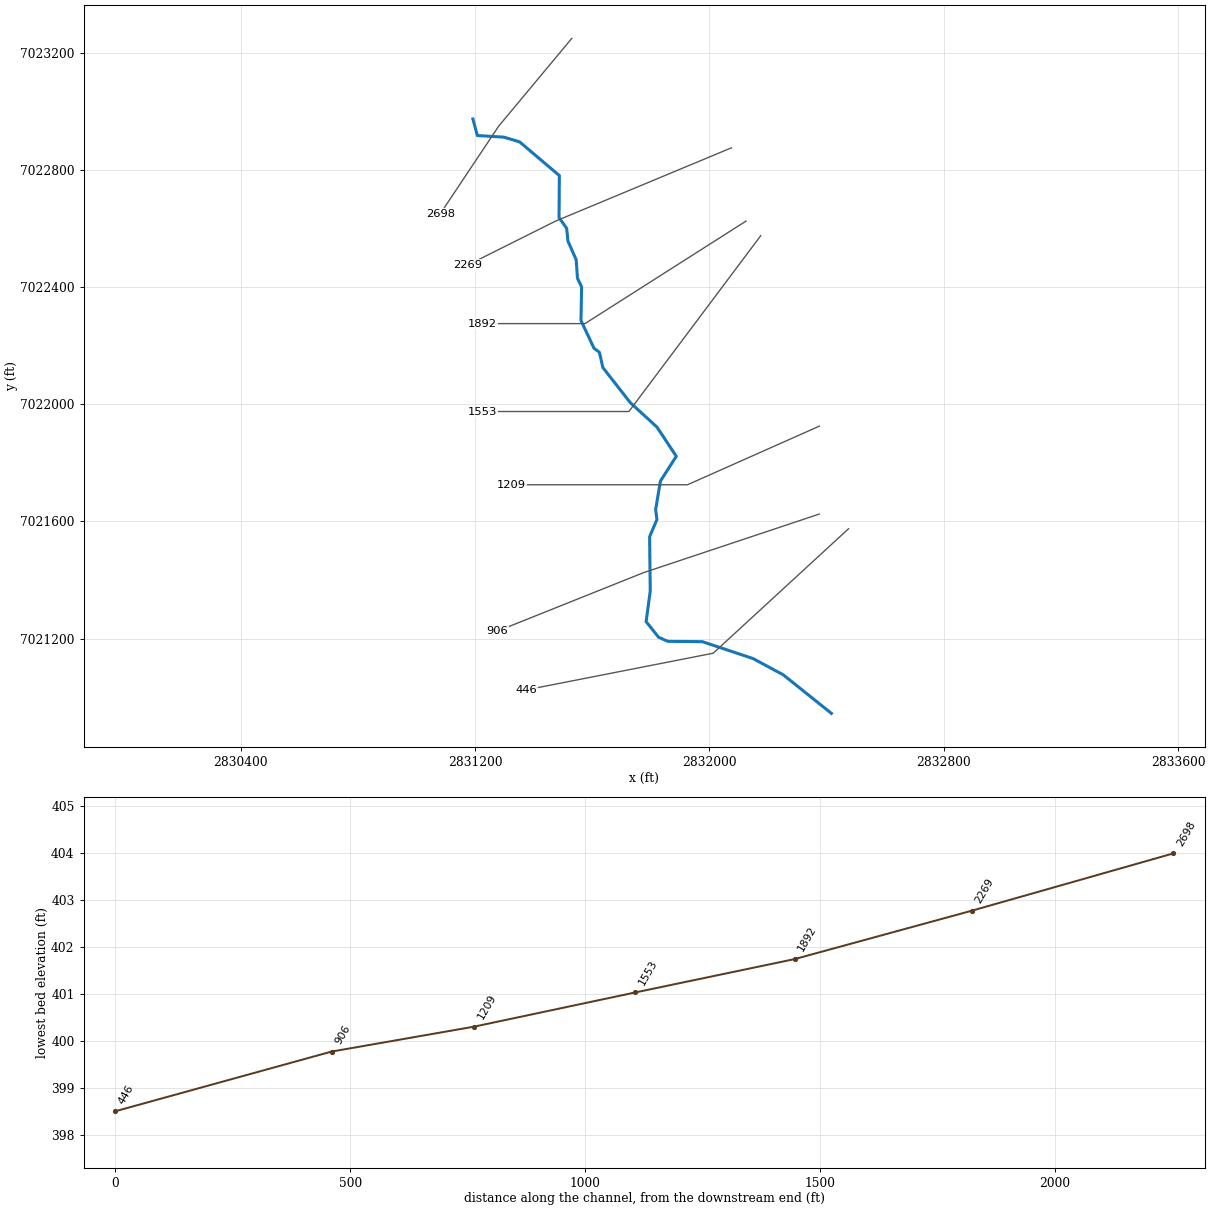
--- UNT 200 in LFCCL Watershed.prj (project) ---

Proj Title=UNT 200 in LFCCL Watershed Base Level Engineering
Current Plan=p01
Default Exp/Contr=0.3,0.1
English Units
Geom File=g01
Flow File=f01
Plan File=p01
BEGIN DESCRIPTION:
UNT 200 in LFCCL Watershed
END DESCRIPTION:

--- UNT 200 in LFCCL Watershed.p01 (plan) ---

Plan Title=Multiple Run
Short Identifier=Multiple
Geom File=g01
Flow File=f01
Subcritical Flow
K Sum by GR= 0
Std Step Tol= 0.01
Critical Tol= 0.01
Num of Std Step Trials= 20
Max Error Tol= 0.3
Flow Tol Ratio= 0.001
Split Flow NTrial= 30
Split Flow Tol= 0.02
Split Flow Ratio= 0.02
Log Output Level= 0
Friction Slope Method= 1
Unsteady Friction Slope Method= 2
Unsteady Bridges Friction Slope Method= 1
Parabolic Critical Depth
Global Vel Dist=  1 , 1 , 1
Global Log Level= 0
CheckData=True
Encroach Param= -1, 0, 0, 0
BEGIN DESCRIPTION:
Multiple Run
END DESCRIPTION:

--- UNT 200 in LFCCL Watershed.f01 (steady flow) ---

Flow Title=Multiple
Number of Profiles=7
Profile Names=10-year,25-year,50-year,1pct_min,100-year,1pct_plu,500-year
River Rch & RM= UNT 200 in LFCCL,Reach-1,2698
     207     255     291     165     330     659     424
Boundary for River Rch & Prof#=UNT 200 in LFCCL,Reach-1,1
Up Type=0
Dn Type=3
Dn Slope=0.005
Boundary for River Rch & Prof#=UNT 200 in LFCCL,Reach-1,2
Up Type=0
Dn Type=3
Dn Slope=0.005
Boundary for River Rch & Prof#=UNT 200 in LFCCL,Reach-1,3
Up Type=0
Dn Type=3
Dn Slope=0.005
Boundary for River Rch & Prof#=UNT 200 in LFCCL,Reach-1,4
Up Type=0
Dn Type=3
Dn Slope=0.005
Boundary for River Rch & Prof#=UNT 200 in LFCCL,Reach-1,5
Up Type=0
Dn Type=3
Dn Slope=0.005
Boundary for River Rch & Prof#=UNT 200 in LFCCL,Reach-1,6
Up Type=0
Dn Type=3
Dn Slope=0.005
Boundary for River Rch & Prof#=UNT 200 in LFCCL,Reach-1,7
Up Type=0
Dn Type=3
Dn Slope=0.005

--- UNT 200 in LFCCL Watershed.g01 (geometry) ---

Geom Title=Existing Conditions

River Reach=UNT 200 in LFCCL,Reach-1
Reach XY= 30
      2831192.40      7022973.38      2831207.59      7022916.95
      2831297.65      7022911.53      2831351.90      7022895.25
      2831487.53      7022780.23      2831486.45      7022637.00
      2831512.49      7022600.11      2831516.83      7022556.71
      2831545.04      7022492.69      2831549.38      7022429.76
      2831563.49      7022400.46      2831561.32      7022285.44
      2831605.81      7022191.04      2831624.25      7022176.93
      2831636.19      7022124.85      2831729.50      7022005.49
      2831820.65      7021921.94      2831886.84      7021822.12
      2831832.59      7021737.48      2831816.31      7021640.91
      2831820.65      7021606.19      2831795.69      7021547.59
      2831797.86      7021362.05      2831783.76      7021257.88
      2831826.08      7021204.71      2831857.54      7021190.61
      2831975.82      7021189.52      2832148.34      7021132.01
      2832251.42      7021076.67      2832416.24      7020944.72

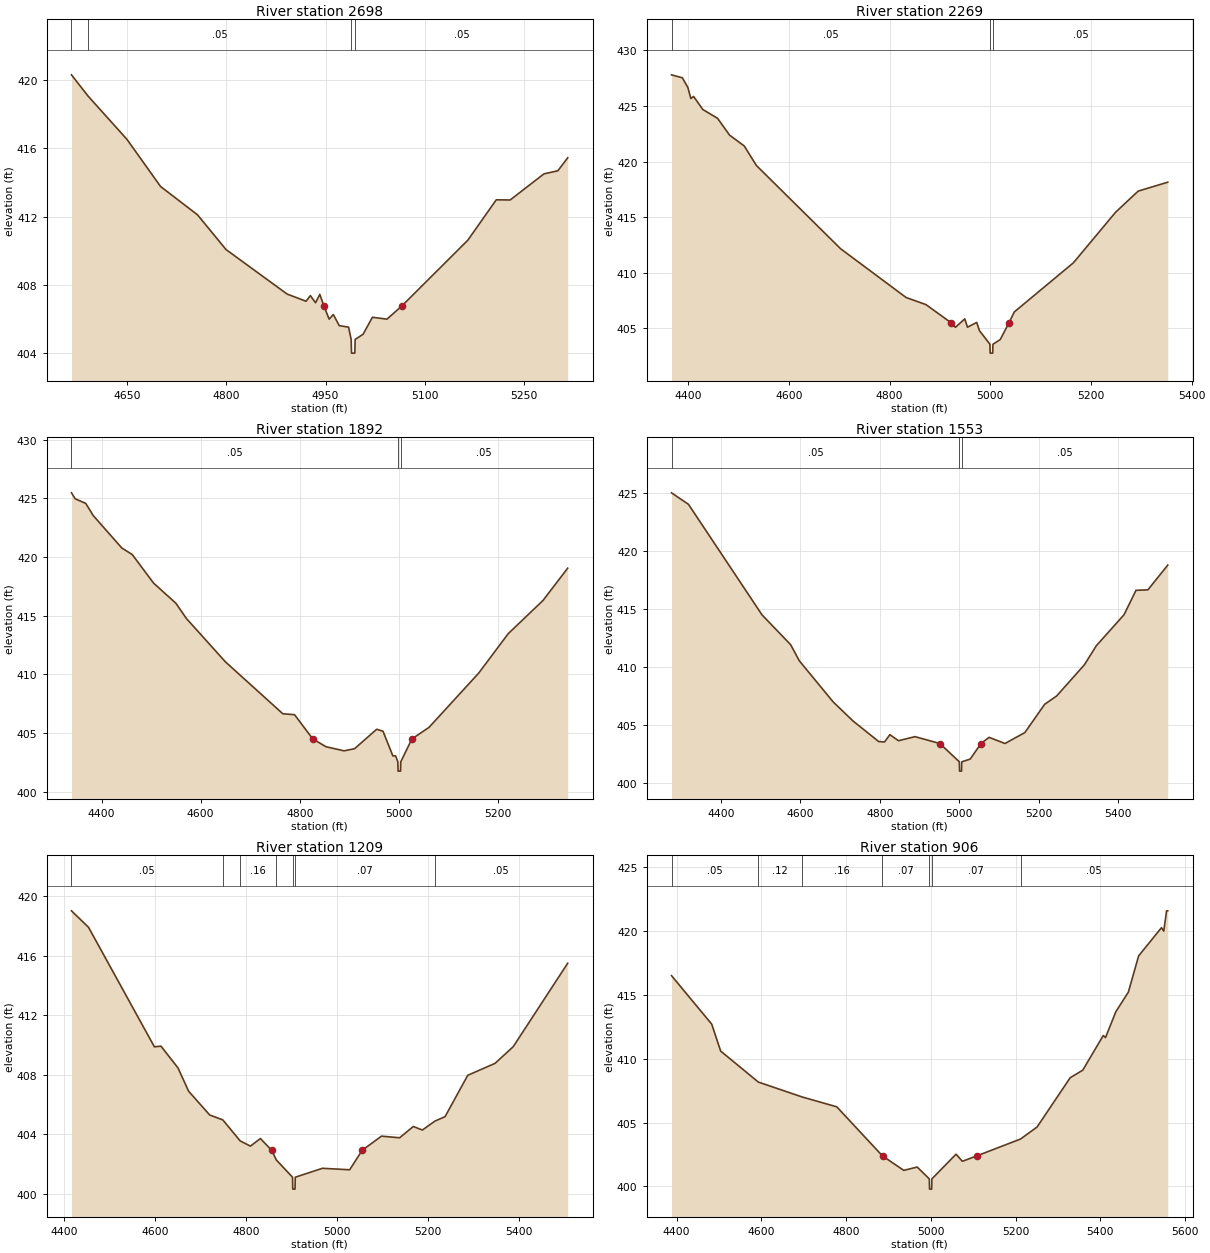
Type RM Length L Ch R = 1,2698,429,429,429
BEGIN DESCRIPTION:
UNT 200 in LFCCL Watershed 7.0
END DESCRIPTION:
XS GIS Cut Line= 3
      2831530.19      7023248.68      2831280.21      7022948.71
      2831080.62      7022649.32
#Sta/Elev= 30
  4565.9  420.30  4590.9  419.06  4649.8  416.52  4700.6  413.76  4756.5  412.10
  4799.5  410.07  4891.9  407.46  4920.6  407.04  4927.1  407.37  4934.9  406.95
  4941.4  407.44  4947.7  406.75  4955.5  405.99  4961.8  406.26  4970.8  405.61
  4984.9  405.52  4988.8  404.80  4989.3  404.00  4994.3  404.00  4994.8  404.80
  5006.9  405.11  5020.9  406.10  5042.9  405.99  5065.1  406.75  5165.1  410.61
  5208.2  412.98  5229.2  412.97  5280.3  414.50  5301.3  414.68  5316.2  415.44
#Mann=4,-1,0
  4565.9    0.08       0  4590.9    0.05       0  4988.8    0.03       0
  4994.8    0.05       0
Bank Sta=4947.7,5065.1
Exp/Cntr=0.3,0.1

Type RM Length L Ch R = 1,2269,377,377,377
BEGIN DESCRIPTION:
UNT 200 in LFCCL Watershed 6.0
END DESCRIPTION:
XS GIS Cut Line= 3
      2832074.96      7022874.98      2831475.00      7022625.00
      2831174.97      7022474.99
#Sta/Elev= 30
  4367.1  427.79  4388.7  427.52  4399.6  426.65  4405.5  425.66  4410.9  425.85
  4429.4  424.67  4458.6  423.88  4482.4  422.37  4511.7  421.39  4535.5  419.65
  4702.9  412.16  4832.9  407.78  4872.4  407.14  4921.7  405.53  4930.9  405.10
  4949.4  405.86  4954.8  405.11  4973.2  405.54  4978.6  404.80  4999.4  403.58
  4999.9  402.78  5004.9  402.78  5005.4  403.58  5019.9  404.00  5037.5  405.53
  5047.8  406.48  5165.2  410.90  5249.1  415.45  5293.8  417.34  5352.5  418.14
#Mann=3,-1,0
  4367.1    0.05       0  4999.4    0.03       0  5005.4    0.05       0
Bank Sta=4921.7,5037.5
Exp/Cntr=0.3,0.1

Type RM Length L Ch R = 1,1892,339,339,339
BEGIN DESCRIPTION:
UNT 200 in LFCCL Watershed 5.0
END DESCRIPTION:
XS GIS Cut Line= 3
      2832124.98      7022624.99      2831575.00      7022275.00
      2831224.99      7022275.00
#Sta/Elev= 30
  4339.2  425.47  4346.8  424.96  4368.0  424.57  4383.2  423.53  4440.8  420.77
  4461.9  420.21  4505.1  417.77  4550.0  416.06  4571.2  414.76  4649.9  411.07
  4765.9  406.64  4789.6  406.56  4826.5  404.49  4853.1  403.83  4889.5  403.48
  4910.7  403.66  4955.5  405.32  4968.2  405.15  4988.1  403.05  4993.6  403.05
  4998.1  402.55  4998.6  401.75  5003.6  401.75  5004.1  402.55  5026.5  404.49
  5061.1  405.48  5161.1  410.09  5221.1  413.47  5291.1  416.29  5341.1  419.05
#Mann=3,-1,0
  4339.2    0.05       0  4998.1    0.03       0  5004.1    0.05       0
Bank Sta=4826.5,5026.5
Exp/Cntr=0.3,0.1

Type RM Length L Ch R = 1,1553,344,344,344
BEGIN DESCRIPTION:
UNT 200 in LFCCL Watershed 4.0
END DESCRIPTION:
XS GIS Cut Line= 3
      2832175.00      7022575.00      2831725.00      7021975.00
      2831225.00      7021975.00
#Sta/Elev= 30
  4275.3  425.02  4318.0  424.03  4503.4  414.50  4575.3  411.94  4597.2  410.55
  4682.6  407.00  4732.6  405.36  4797.2  403.59  4811.8  403.55  4825.3  404.18
  4847.2  403.66  4888.8  404.01  4951.3  403.42  5000.4  401.84  5000.9  401.04
  5005.9  401.04  5006.4  401.84  5027.8  402.08  5054.9  403.42  5075.3  403.95
  5115.3  403.42  5165.3  404.36  5215.3  406.80  5245.3  407.51  5315.3  410.20
  5345.3  411.84  5415.3  414.52  5445.3  416.62  5475.3  416.66  5525.3  418.79
#Mann=3,-1,0
  4275.3    0.05       0  5000.4    0.03       0  5006.4    0.05       0
Bank Sta=4951.3,5054.9
Exp/Cntr=0.3,0.1

Type RM Length L Ch R = 1,1209,303,303,303
BEGIN DESCRIPTION:
UNT 200 in LFCCL Watershed 3.0
END DESCRIPTION:
XS GIS Cut Line= 3
      2832375.02      7021925.01      2831925.00      7021725.00
      2831324.97      7021725.00
#Sta/Elev= 30
  4415.6  419.01  4453.2  417.90  4598.2  409.87  4612.6  409.92  4650.2  408.45
  4673.5  406.89  4720.0  405.29  4748.9  404.96  4787.0  403.55  4809.6  403.20
  4831.5  403.71  4856.4  402.92  4866.6  402.27  4902.3  401.11  4902.8  400.31
  4907.8  400.31  4908.3  401.11  4968.1  401.71  5028.1  401.61  5055.6  402.92
  5098.1  403.87  5138.1  403.76  5168.1  404.52  5188.1  404.28  5215.7  404.88
  5238.1  405.18  5288.1  407.96  5348.1  408.76  5388.1  409.88  5508.1  415.49
#Mann=7,-1,0
  4415.6    0.05       0  4748.9    0.07       0  4787.0    0.16       0
  4866.6    0.07       0  4902.3    0.07       0  4908.3    0.07       0
  5215.7    0.05       0
Bank Sta=4856.4,5055.6
Exp/Cntr=0.3,0.1

Type RM Length L Ch R = 1,906,460,460,460
BEGIN DESCRIPTION:
UNT 200 in LFCCL Watershed 2.0
END DESCRIPTION:
XS GIS Cut Line= 3
      2832375.01      7021625.00      2831775.00      7021425.00
      2831274.99      7021224.99
#Sta/Elev= 30
  4388.2  416.51  4483.1  412.71  4504.2  410.60  4593.1  408.17  4696.7  407.00
  4778.2  406.23  4885.8  402.39  4886.2  402.38  4936.3  401.25  4968.0  401.51
  4996.6  400.58  4997.1  399.78  5002.1  399.78  5002.6  400.58  5059.7  402.52
  5074.5  401.96  5108.3  402.38  5212.0  403.71  5250.9  404.65  5329.0  408.51
  5358.6  409.10  5407.1  411.82  5412.4  411.66  5436.7  413.68  5466.3  415.22
  5490.5  418.06  5544.4  420.27  5549.8  420.00  5556.5  421.59  5559.2  421.59
#Mann=7,-1,0
  4388.2    0.05       0  4593.1    0.12       0  4696.7    0.16       0
  4885.8    0.07       0  4996.6    0.07       0  5002.6    0.07       0
  5212.0    0.05       0
Bank Sta=4886.2,5108.3
Exp/Cntr=0.3,0.1

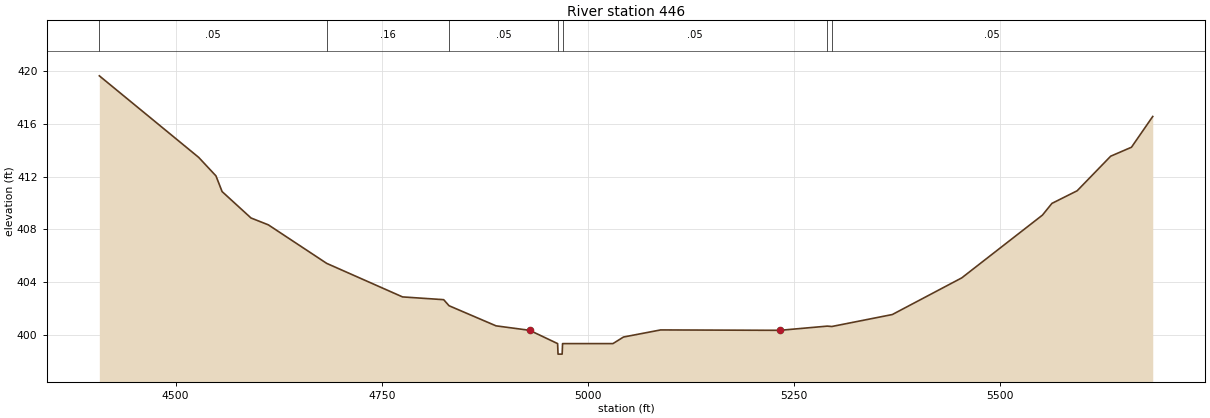
Type RM Length L Ch R = 1,446,0,0,0
BEGIN DESCRIPTION:
UNT 200 in LFCCL Watershed 1.0
END DESCRIPTION:
XS GIS Cut Line= 3
      2832475.00      7021575.00      2832012.65      7021150.02
      2831374.98      7021025.00
#Sta/Elev= 30
  4407.5  419.67  4528.0  413.47  4549.0  412.06  4556.4  410.87  4591.5  408.86
  4612.5  408.34  4683.3  405.41  4775.3  402.86  4825.2  402.65  4831.7  402.19
  4888.7  400.66  4929.5  400.32  4963.4  399.31  4963.9  398.51  4968.9  398.51
  4969.4  399.31  5030.5  399.31  5043.3  399.81  5088.4  400.35  5233.1  400.32
  5290.6  400.64  5296.0  400.61  5369.4  401.52  5453.7  404.31  5551.5  409.08
  5563.0  409.97  5593.6  410.93  5634.3  413.56  5659.5  414.24  5685.3  416.58
#Mann=7,-1,0
  4407.5    0.05       0  4683.3    0.16       0  4831.7    0.05       0
  4963.4   0.035       0  4969.4    0.05       0  5290.6    0.07       0
  5296.0    0.05       0
Bank Sta=4929.5,5233.1
Exp/Cntr=0.3,0.1

Chan Stop Cuts=-1