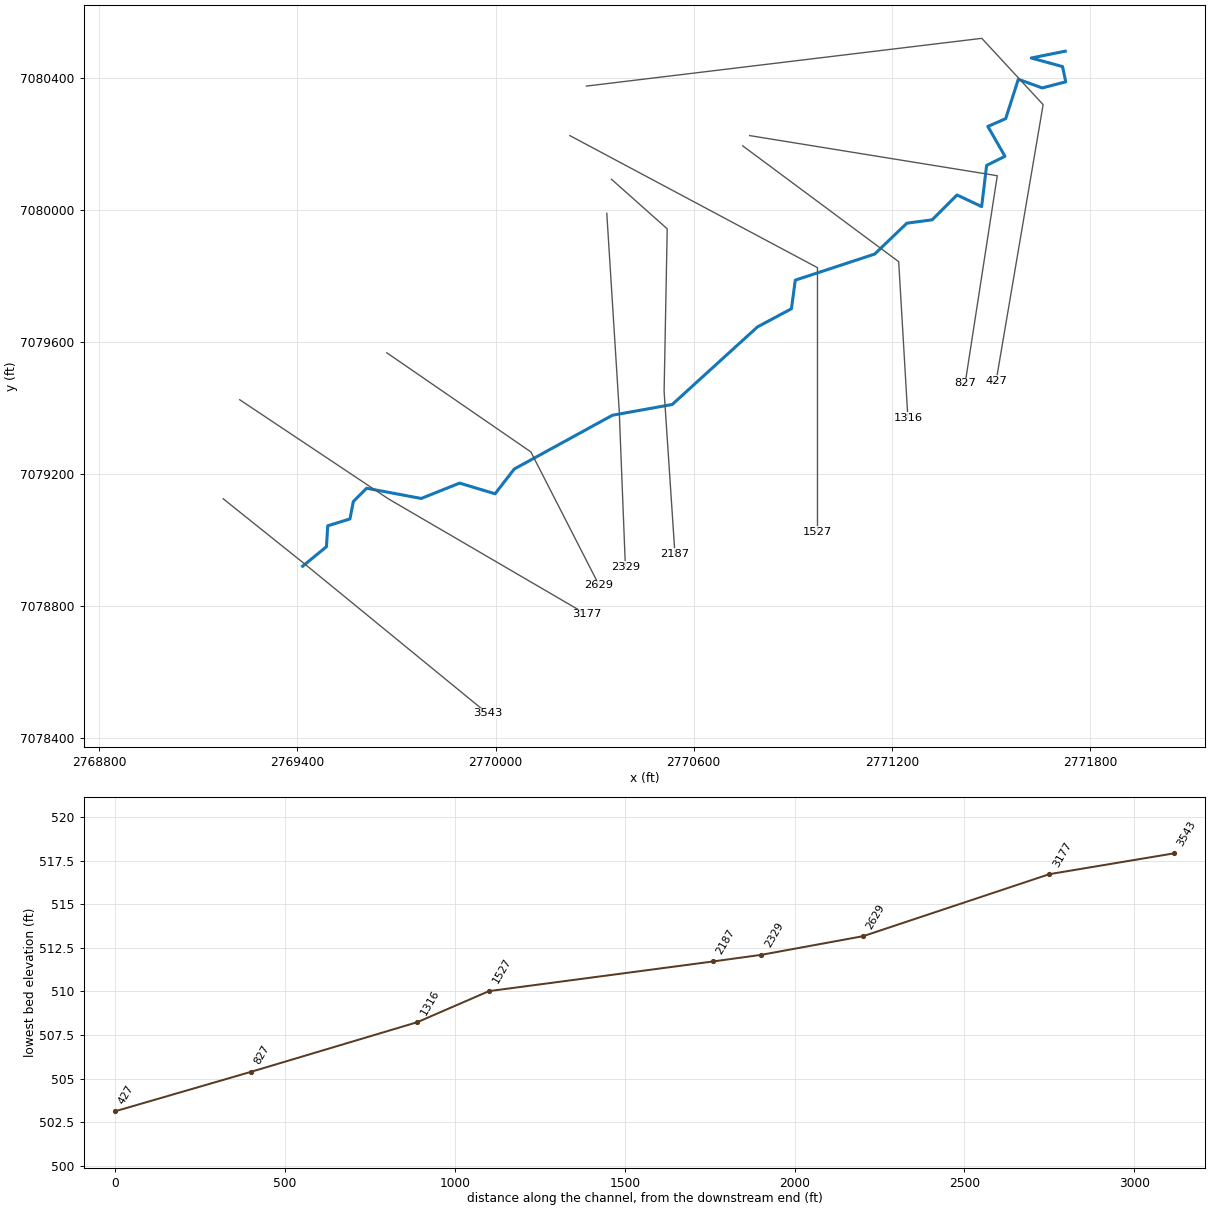
--- WEST FORK TURKEY CREEK TRIB 1.prj (project) ---

Proj Title=WEST FORK TURKEY CREEK TRIB 1 Base Level Engineering
Current Plan=p01
Default Exp/Contr=0.3,0.1
English Units
Geom File=g01
Flow File=f01
Plan File=p01
BEGIN DESCRIPTION:
WEST FORK TURKEY CREEK TRIB 1
END DESCRIPTION:

--- WEST FORK TURKEY CREEK TRIB 1.p01 (plan) ---

Plan Title=Multiple Run
Short Identifier=Multiple
Geom File=g01
Flow File=f01
Subcritical Flow
K Sum by GR= 0
Std Step Tol= 0.01
Critical Tol= 0.01
Num of Std Step Trials= 20
Max Error Tol= 0.3
Flow Tol Ratio= 0.001
Split Flow NTrial= 30
Split Flow Tol= 0.02
Split Flow Ratio= 0.02
Log Output Level= 0
Friction Slope Method= 1
Unsteady Friction Slope Method= 2
Unsteady Bridges Friction Slope Method= 1
Parabolic Critical Depth
Global Vel Dist=  1 , 1 , 1
Global Log Level= 0
CheckData=True
Encroach Param= -1, 0, 0, 0
BEGIN DESCRIPTION:
Multiple Run
END DESCRIPTION:

--- WEST FORK TURKEY CREEK TRIB 1.f01 (steady flow) ---

Flow Title=Multiple
Number of Profiles=7
Profile Names=10-year,25-year,50-year,1pct_min,100-year,1pct_plu,500-year
River Rch & RM= WEST FORK TURKEY,Reach-1,3543
     944    1293    1582     959    1914    3819    2797
Boundary for River Rch & Prof#=WEST FORK TURKEY,Reach-1,1
Up Type=0
Dn Type=3
Dn Slope=0.005
Boundary for River Rch & Prof#=WEST FORK TURKEY,Reach-1,2
Up Type=0
Dn Type=3
Dn Slope=0.005
Boundary for River Rch & Prof#=WEST FORK TURKEY,Reach-1,3
Up Type=0
Dn Type=3
Dn Slope=0.005
Boundary for River Rch & Prof#=WEST FORK TURKEY,Reach-1,4
Up Type=0
Dn Type=3
Dn Slope=0.005
Boundary for River Rch & Prof#=WEST FORK TURKEY,Reach-1,5
Up Type=0
Dn Type=3
Dn Slope=0.005
Boundary for River Rch & Prof#=WEST FORK TURKEY,Reach-1,6
Up Type=0
Dn Type=3
Dn Slope=0.005
Boundary for River Rch & Prof#=WEST FORK TURKEY,Reach-1,7
Up Type=0
Dn Type=3
Dn Slope=0.005

--- WEST FORK TURKEY CREEK TRIB 1.g01 (geometry) ---

Geom Title=Existing Conditions

River Reach=WEST FORK TURKEY,Reach-1
Reach XY= 30
      2769415.59      7078920.71      2769487.74      7078979.84
      2769491.62      7079043.19      2769558.84      7079063.87
      2769569.19      7079116.88      2769609.26      7079156.95
      2769774.74      7079125.93      2769891.09      7079172.47
      2769998.40      7079140.15      2770056.57      7079215.13
      2770353.91      7079378.02      2770535.01      7079410.60
      2770793.21      7079645.56      2770896.10      7079700.58
      2770907.72      7079787.15      2771148.20      7079866.16
      2771245.79      7079959.75      2771322.30      7079969.96
      2771397.61      7080045.29      2771472.28      7080009.98
      2771487.29      7080134.80      2771542.89      7080162.34
      2771491.04      7080252.78      2771545.01      7080276.33
      2771583.33      7080395.62      2771655.66      7080369.42
      2771727.02      7080387.93      2771717.25      7080434.12
      2771622.50      7080460.06      2771725.59      7080480.71

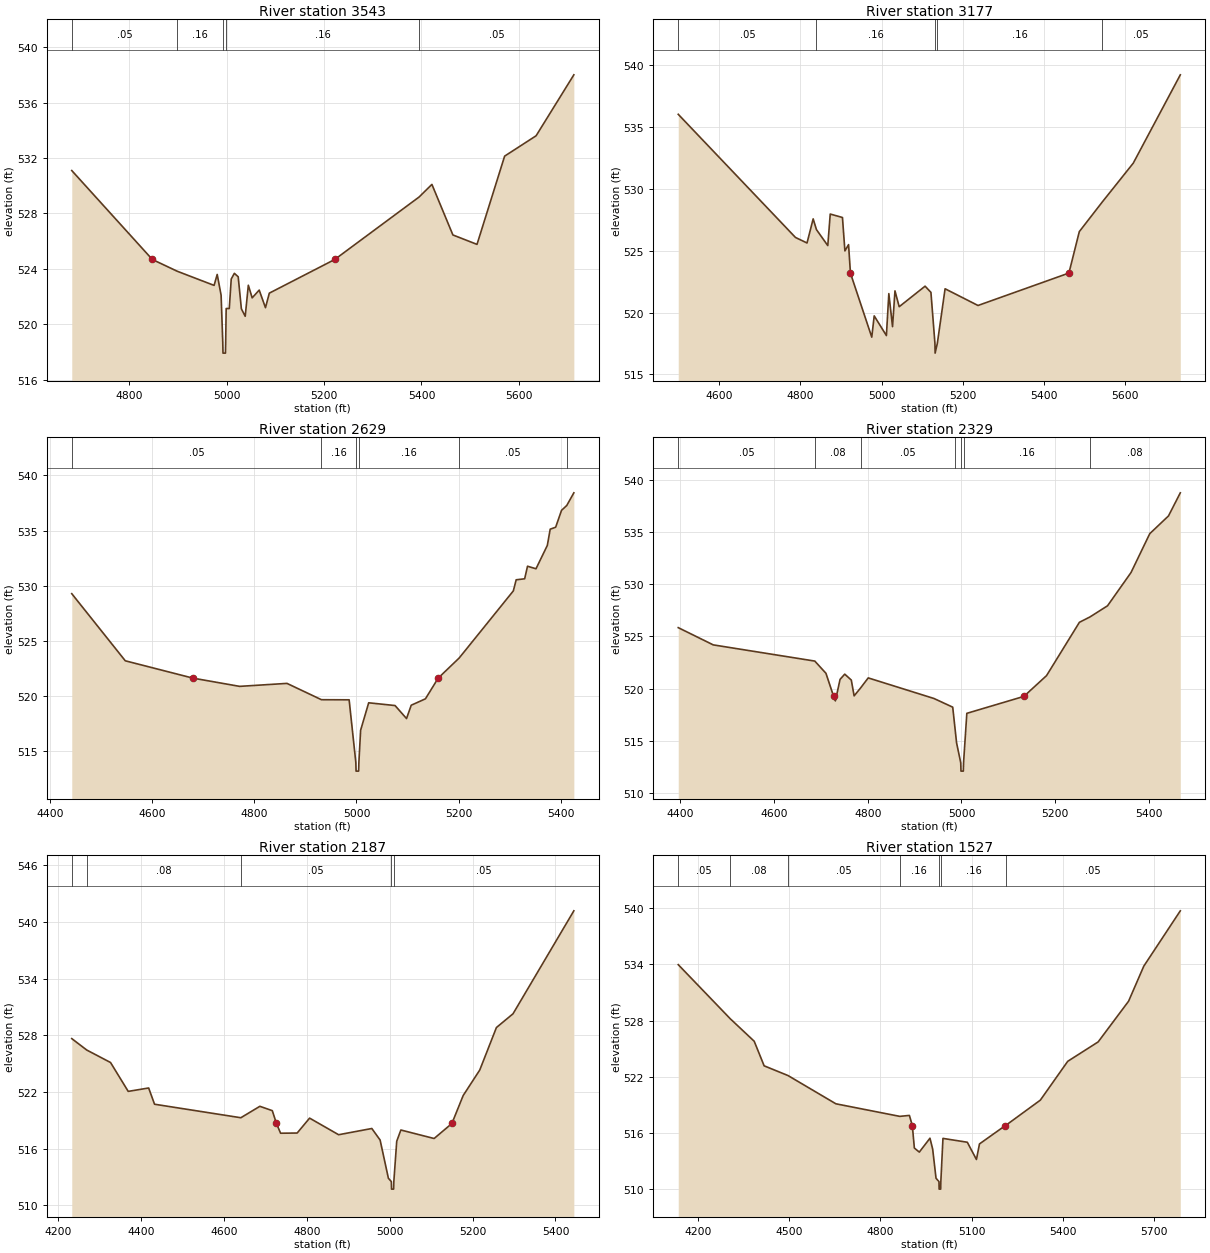
Type RM Length L Ch R = 1,3543,366,366,366
BEGIN DESCRIPTION:
WEST FORK TURKEY CREEK TRIB 1 6.0
END DESCRIPTION:
XS GIS Cut Line= 3
      2769174.97      7079125.02      2769425.00      7078925.00
      2769974.98      7078475.02
#Sta/Elev= 30
  4682.0  531.09  4847.4  524.67  4898.6  523.82  4974.2  522.80  4980.6  523.59
  4988.6  522.09  4992.0  518.71  4992.5  517.91  4997.5  517.91  4998.0  518.71
  4999.0  521.13  5005.4  521.13  5009.4  523.26  5015.8  523.67  5023.7  523.42
  5030.2  521.11  5038.1  520.57  5044.5  522.81  5052.4  521.90  5066.8  522.46
  5079.7  521.19  5087.6  522.24  5221.9  524.67  5395.1  529.18  5421.4  530.09
  5464.5  526.44  5514.0  525.76  5570.7  532.13  5635.3  533.60  5712.8  538.00
#Mann=5,-1,0
  4682.0    0.05       0  4898.6    0.16       0  4992.0    0.07       0
  4998.0    0.16       0  5395.1    0.05       0
Bank Sta=4847.4,5221.9
Exp/Cntr=0.3,0.1

Type RM Length L Ch R = 1,3177,548,548,548
BEGIN DESCRIPTION:
WEST FORK TURKEY CREEK TRIB 1 5.0
END DESCRIPTION:
XS GIS Cut Line= 3
      2769225.04      7079424.97      2769675.00      7079125.00
      2770275.00      7078775.00
#Sta/Elev= 30
  4499.7  536.02  4788.1  526.07  4816.6  525.62  4831.7  527.57  4839.8  526.70
  4867.7  525.41  4873.7  527.96  4903.8  527.68  4909.8  524.98  4918.8  525.49
  4923.4  523.19  4975.9  518.01  4981.9  519.73  5011.9  518.14  5017.9  521.53
  5027.0  518.86  5033.0  521.75  5043.4  520.47  5107.1  522.13  5121.5  521.63
  5131.3  517.52  5131.8  516.72  5137.3  517.52  5156.3  521.92  5237.3  520.57
  5461.0  523.19  5486.6  526.54  5543.0  528.93  5619.3  532.07  5735.1  539.21
#Mann=5,-1,0
  4499.7    0.05       0  4839.8    0.16       0  5131.3    0.07       0
  5137.3    0.16       0  5543.0    0.05       0
Bank Sta=4923.4,5461
Exp/Cntr=0.3,0.1

Type RM Length L Ch R = 1,2629,300,300,300
BEGIN DESCRIPTION:
Mapping XS a7c36b26
END DESCRIPTION:
XS GIS Cut Line= 3
      2769670.52      7079567.24      2770106.90      7079266.93
      2770313.40      7078863.33
#Sta/Elev= 30
  4442.6  529.27  4547.4  523.18  4679.6  521.61  4771.3  520.86  4864.0  521.13
  4931.5  519.65  4985.7  519.64  4998.8  513.97  4999.3  513.17  5004.3  513.17
  5004.8  513.97  5008.2  516.88  5024.0  519.37  5075.6  519.12  5098.1  517.94
  5107.3  519.15  5135.1  519.73  5160.1  521.61  5201.1  523.43  5307.2  529.52
  5312.8  530.53  5329.4  530.62  5335.0  531.76  5351.6  531.53  5373.8  533.65
  5379.4  535.12  5390.1  535.30  5401.6  536.83  5411.8  537.27  5425.7  538.42
#Mann=6,-1,0
  4442.6    0.05       0  4931.5    0.16       0  4998.8    0.07       0
  5004.8    0.16       0  5201.1    0.05       0  5411.8    0.08       0
Bank Sta=4679.6,5160.1
Exp/Cntr=0.3,0.1

Type RM Length L Ch R = 1,2329,142,142,142
BEGIN DESCRIPTION:
Mapping XS 450bc1eb
END DESCRIPTION:
XS GIS Cut Line= 3
      2770336.85      7079989.59      2770374.39      7079393.64
      2770393.15      7078919.84
#Sta/Elev= 30
  4395.7  525.83  4470.4  524.18  4687.1  522.63  4710.9  521.46  4727.3  519.25
  4731.0  518.82  4741.0  520.88  4751.0  521.38  4765.0  520.81  4771.0  519.30
  4785.0  520.07  4801.1  521.02  4941.4  519.05  4981.4  518.22  4985.7  516.43
  4989.6  514.81  4998.5  512.90  4999.0  512.10  5004.0  512.10  5004.5  512.90
  5011.5  517.63  5133.2  519.25  5181.6  521.24  5251.7  526.34  5274.1  526.85
  5311.7  527.92  5361.8  531.10  5401.8  534.82  5441.8  536.52  5467.0  538.73
#Mann=7,-1,0
  4395.7    0.05       0  4687.1    0.08       0  4785.0    0.05       0
  4985.7    0.16       0  4998.5    0.07       0  5004.5    0.16       0
  5274.1    0.08       0
Bank Sta=4727.3,5133.2
Exp/Cntr=0.3,0.1

Type RM Length L Ch R = 1,2187,660,660,660
BEGIN DESCRIPTION:
Mapping XS c7359727
END DESCRIPTION:
XS GIS Cut Line= 4
      2770350.90      7080092.87      2770519.86      7079942.68
      2770510.47      7079449.95      2770543.23      7078958.62
#Sta/Elev= 30
  4233.0  527.66  4269.1  526.45  4326.5  525.13  4369.2  522.07  4418.5  522.43
  4432.7  520.71  4640.9  519.28  4686.8  520.49  4716.8  520.03  4726.8  518.67
  4736.8  517.64  4776.8  517.66  4806.8  519.24  4876.8  517.48  4956.9  518.14
  4976.9  516.92  4996.9  512.87  5004.0  512.52  5004.5  511.72  5009.5  511.72
  5010.0  512.52  5017.0  516.79  5027.0  517.98  5107.2  517.08  5150.1  518.67
  5177.3  521.63  5217.4  524.34  5257.5  528.83  5297.6  530.29  5444.3  541.19
#Mann=5,-1,0
  4233.0    0.05       0  4269.1    0.08       0  4640.9    0.05       0
  5004.0    0.03       0  5010.0    0.05       0
Bank Sta=4726.8,5150.1
Exp/Cntr=0.3,0.1

Type RM Length L Ch R = 1,1527,211,211,211
BEGIN DESCRIPTION:
WEST FORK TURKEY CREEK TRIB 1 2.0
END DESCRIPTION:
XS GIS Cut Line= 3
      2770225.01      7080224.99      2770975.00      7079825.00
      2770975.00      7079024.98
#Sta/Elev= 30
  4136.0  533.96  4307.3  528.18  4385.7  525.79  4418.3  523.17  4496.9  522.13
  4654.1  519.12  4864.0  517.78  4895.7  517.88  4905.3  516.80  4912.0  514.40
  4928.3  513.97  4963.3  515.45  4972.2  514.28  4983.2  511.18  4992.9  510.82
  4993.4  510.02  4998.5  510.02  4999.0  510.82  5006.0  515.43  5086.0  515.02
  5116.0  513.18  5126.0  514.84  5211.0  516.80  5213.4  516.84  5326.0  519.51
  5416.0  523.65  5516.0  525.72  5616.0  530.06  5666.0  533.80  5786.0  539.70
#Mann=7,-1,0
  4136.0    0.05       0  4307.3    0.08       0  4496.9    0.05       0
  4864.0    0.16       0  4992.9    0.07       0  4999.0    0.16       0
  5213.4    0.05       0
Bank Sta=4905.3,5211
Exp/Cntr=0.3,0.1

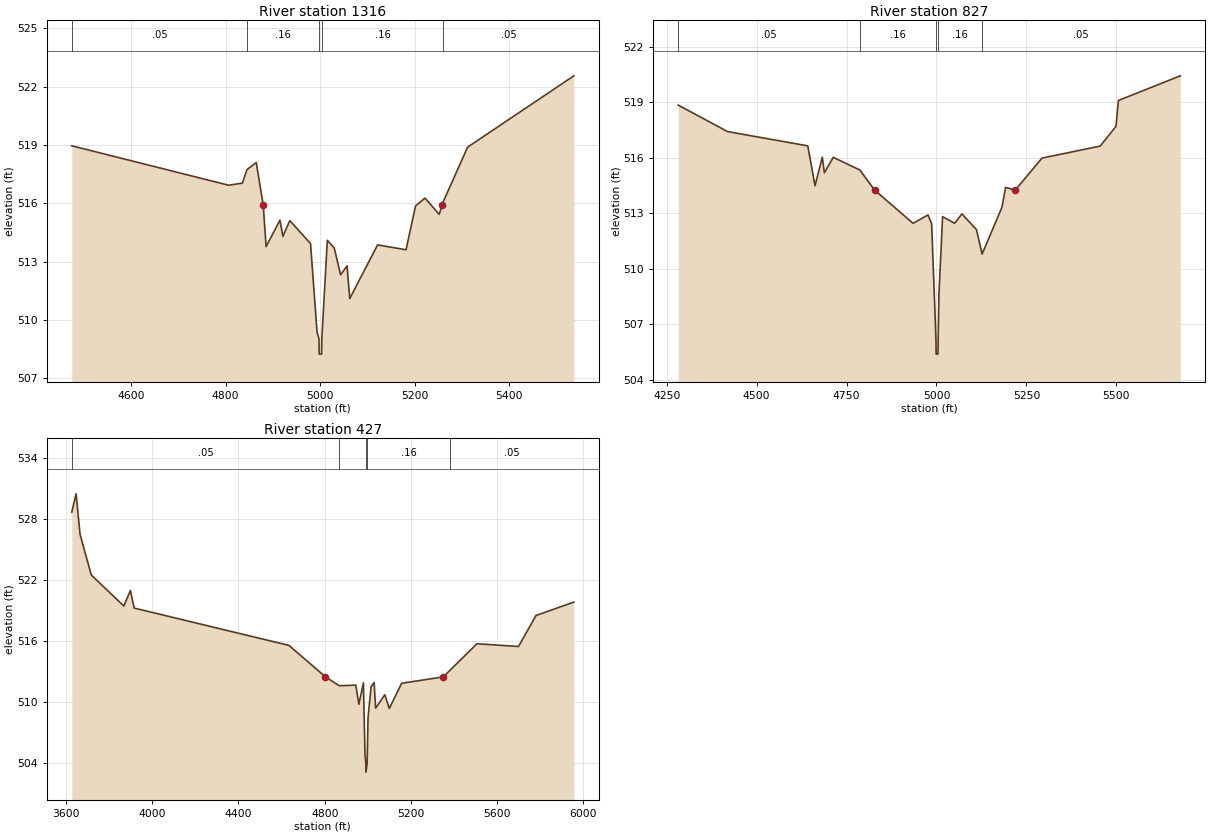
Type RM Length L Ch R = 1,1316,489,489,489
BEGIN DESCRIPTION:
Mapping XS 0138b70d
END DESCRIPTION:
XS GIS Cut Line= 3
      2770748.72      7080193.83      2771220.98      7079843.11
      2771248.76      7079370.87
#Sta/Elev= 30
  4474.9  518.96  4806.6  516.93  4835.6  517.04  4845.1  517.73  4864.9  518.10
  4879.6  515.90  4885.7  513.77  4914.9  515.13  4921.2  514.30  4935.8  515.11
  4979.6  513.93  4993.4  509.36  4997.4  509.04  4997.9  508.24  5003.0  508.24
  5003.5  509.04  5015.1  514.10  5029.7  513.70  5043.2  512.32  5056.8  512.78
  5062.5  511.10  5121.4  513.86  5181.5  513.61  5201.5  515.86  5221.6  516.27
  5251.6  515.43  5257.6  515.90  5259.5  516.05  5311.7  518.89  5536.2  522.56
#Mann=5,-1,0
  4474.9    0.05       0  4845.1    0.16       0  4997.4    0.07       0
  5003.5    0.16       0  5259.5    0.05       0
Bank Sta=4879.6,5257.6
Exp/Cntr=0.3,0.1

Type RM Length L Ch R = 1,827,400,400,400
BEGIN DESCRIPTION:
Mapping XS 6c03b639
END DESCRIPTION:
XS GIS Cut Line= 3
      2770769.56      7080225.06      2771519.59      7080103.52
      2771422.36      7079475.01
#Sta/Elev= 30
  4282.1  518.84  4419.3  517.41  4642.2  516.64  4662.4  514.49  4682.7  516.03
  4688.3  515.19  4713.1  516.02  4786.8  515.34  4828.3  514.25  4934.9  512.46
  4976.5  512.91  4986.6  512.43  4998.6  506.20  4999.1  505.40  5004.2  505.40
  5004.7  506.20  5006.9  508.62  5017.0  512.82  5050.5  512.46  5070.8  512.97
  5111.2  512.12  5126.9  510.80  5182.1  513.33  5192.2  514.40  5219.0  514.25
  5293.4  515.98  5455.3  516.63  5499.0  517.69  5505.9  519.09  5677.9  520.42
#Mann=5,-1,0
  4282.1    0.05       0  4786.8    0.16       0  4998.6    0.07       0
  5004.7    0.16       0  5126.9    0.05       0
Bank Sta=4828.3,5219
Exp/Cntr=0.3,0.1

Type RM Length L Ch R = 1,427,0,0,0
BEGIN DESCRIPTION:
WEST FORK TURKEY CREEK TRIB 1 1.0
END DESCRIPTION:
XS GIS Cut Line= 4
      2770275.05      7080375.01      2771472.66      7080519.64
      2771658.48      7080318.80      2771516.11      7079481.95
#Sta/Elev= 30
  3626.7  528.72  3646.8  530.52  3665.1  526.54  3717.3  522.53  3868.4  519.48
  3898.6  521.01  3916.1  519.28  4633.9  515.61  4803.5  512.51  4867.6  511.64
  4944.2  511.70  4958.4  509.81  4979.4  511.93  4986.7  504.92  4990.5  503.94
  4991.0  503.14  4996.6  503.94  5000.9  508.49  5015.1  511.54  5029.2  511.95
  5036.1  509.43  5078.6  510.75  5099.6  509.40  5156.7  511.88  5350.3  512.51
  5381.9  513.18  5506.1  515.77  5698.8  515.50  5780.0  518.55  5955.5  519.87
#Mann=5,-1,0
  3626.7    0.05       0  4867.6    0.16       0  4990.5    0.07       0
  4996.6    0.16       0  5381.9    0.05       0
Bank Sta=4803.5,5350.3
Exp/Cntr=0.3,0.1

Chan Stop Cuts=-1