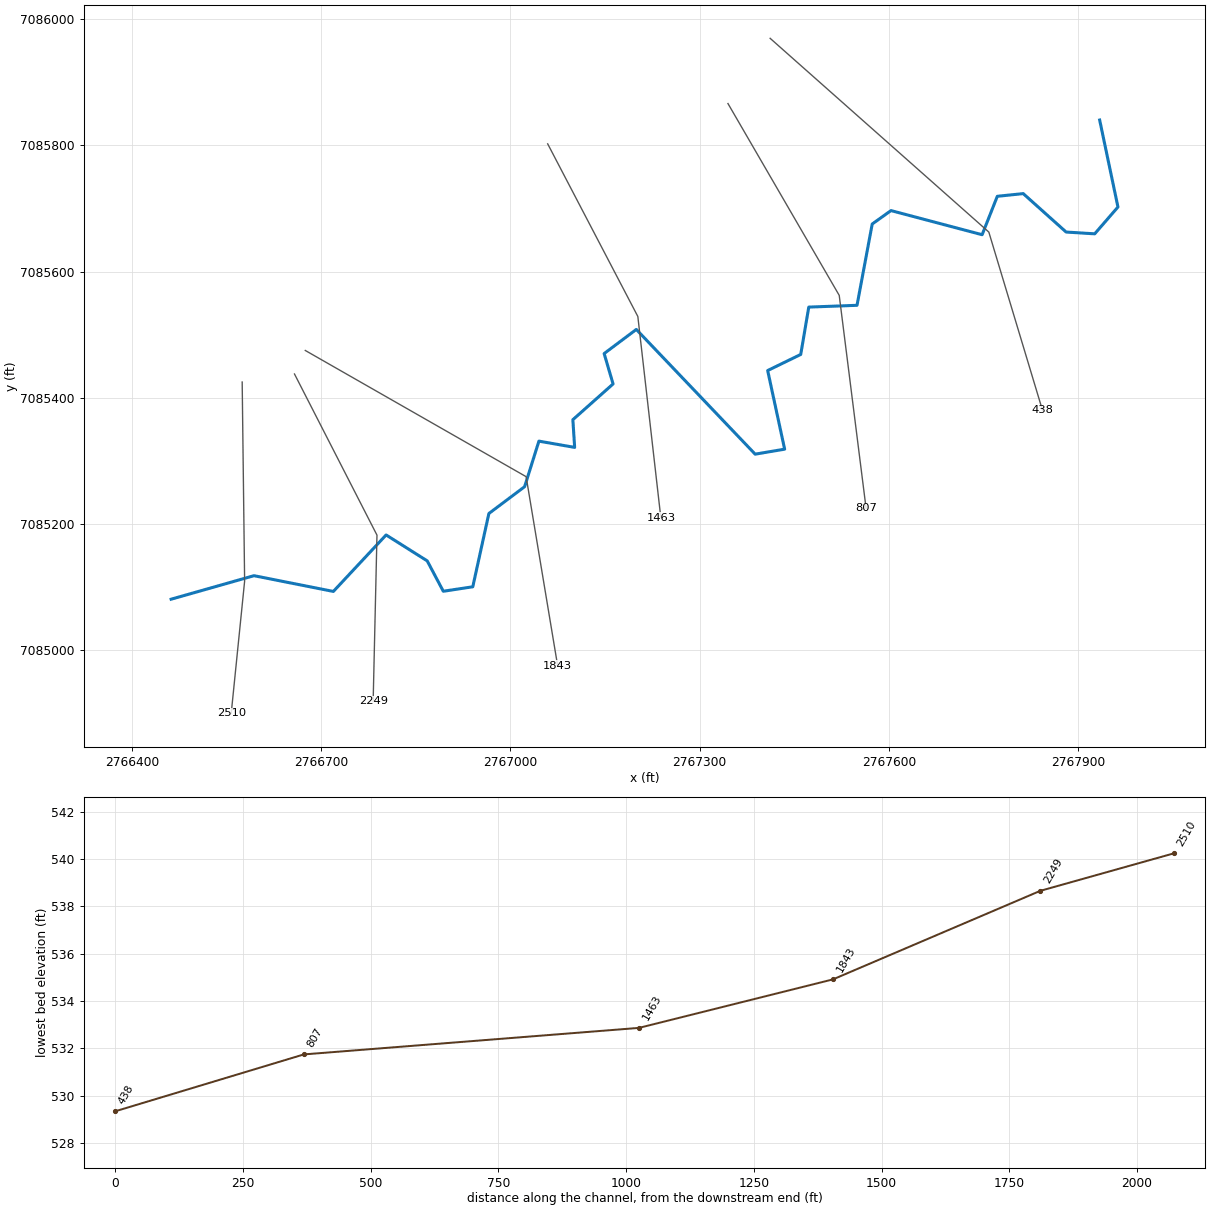
--- WEST FORK TURKEY CREEK TRIB 3.prj (project) ---

Proj Title=WEST FORK TURKEY CREEK TRIB 3 Base Level Engineering
Current Plan=p01
Default Exp/Contr=0.3,0.1
English Units
Geom File=g01
Flow File=f01
Plan File=p01
BEGIN DESCRIPTION:
WEST FORK TURKEY CREEK TRIB 3
END DESCRIPTION:

--- WEST FORK TURKEY CREEK TRIB 3.p01 (plan) ---

Plan Title=Multiple Run
Short Identifier=Multiple
Geom File=g01
Flow File=f01
Subcritical Flow
K Sum by GR= 0
Std Step Tol= 0.01
Critical Tol= 0.01
Num of Std Step Trials= 20
Max Error Tol= 0.3
Flow Tol Ratio= 0.001
Split Flow NTrial= 30
Split Flow Tol= 0.02
Split Flow Ratio= 0.02
Log Output Level= 0
Friction Slope Method= 1
Unsteady Friction Slope Method= 2
Unsteady Bridges Friction Slope Method= 1
Parabolic Critical Depth
Global Vel Dist=  1 , 1 , 1
Global Log Level= 0
CheckData=True
Encroach Param= -1, 0, 0, 0
BEGIN DESCRIPTION:
Multiple Run
END DESCRIPTION:

--- WEST FORK TURKEY CREEK TRIB 3.f01 (steady flow) ---

Flow Title=Multiple
Number of Profiles=7
Profile Names=10-year,25-year,50-year,1pct_min,100-year,1pct_plu,500-year
River Rch & RM= WEST FORK TURKEY,Reach-1,2510
     315     402     470     273     545    1087     729
Boundary for River Rch & Prof#=WEST FORK TURKEY,Reach-1,1
Up Type=0
Dn Type=3
Dn Slope=0.005
Boundary for River Rch & Prof#=WEST FORK TURKEY,Reach-1,2
Up Type=0
Dn Type=3
Dn Slope=0.005
Boundary for River Rch & Prof#=WEST FORK TURKEY,Reach-1,3
Up Type=0
Dn Type=3
Dn Slope=0.005
Boundary for River Rch & Prof#=WEST FORK TURKEY,Reach-1,4
Up Type=0
Dn Type=3
Dn Slope=0.005
Boundary for River Rch & Prof#=WEST FORK TURKEY,Reach-1,5
Up Type=0
Dn Type=3
Dn Slope=0.005
Boundary for River Rch & Prof#=WEST FORK TURKEY,Reach-1,6
Up Type=0
Dn Type=3
Dn Slope=0.005
Boundary for River Rch & Prof#=WEST FORK TURKEY,Reach-1,7
Up Type=0
Dn Type=3
Dn Slope=0.005

--- WEST FORK TURKEY CREEK TRIB 3.g01 (geometry) ---

Geom Title=Existing Conditions

River Reach=WEST FORK TURKEY,Reach-1
Reach XY= 30
      2766462.40      7085080.80      2766593.69      7085118.08
      2766719.50      7085093.13      2766803.09      7085182.63
      2766868.23      7085141.56      2766893.72      7085093.41
      2766940.45      7085100.49      2766965.94      7085216.61
      2767022.59      7085259.10      2767045.25      7085331.32
      2767101.89      7085321.40      2767099.06      7085365.30
      2767162.78      7085421.95      2767148.62      7085470.10
      2767199.60      7085508.33      2767387.93      7085310.68
      2767434.68      7085318.57      2767407.77      7085443.19
      2767460.17      7085468.68      2767472.91      7085543.74
      2767549.38      7085546.57      2767573.46      7085675.43
      2767603.20      7085696.68      2767747.64      7085658.44
      2767771.71      7085719.33      2767812.78      7085723.58
      2767880.75      7085662.69      2767926.07      7085659.86
      2767962.89      7085702.34      2767933.91      7085840.17

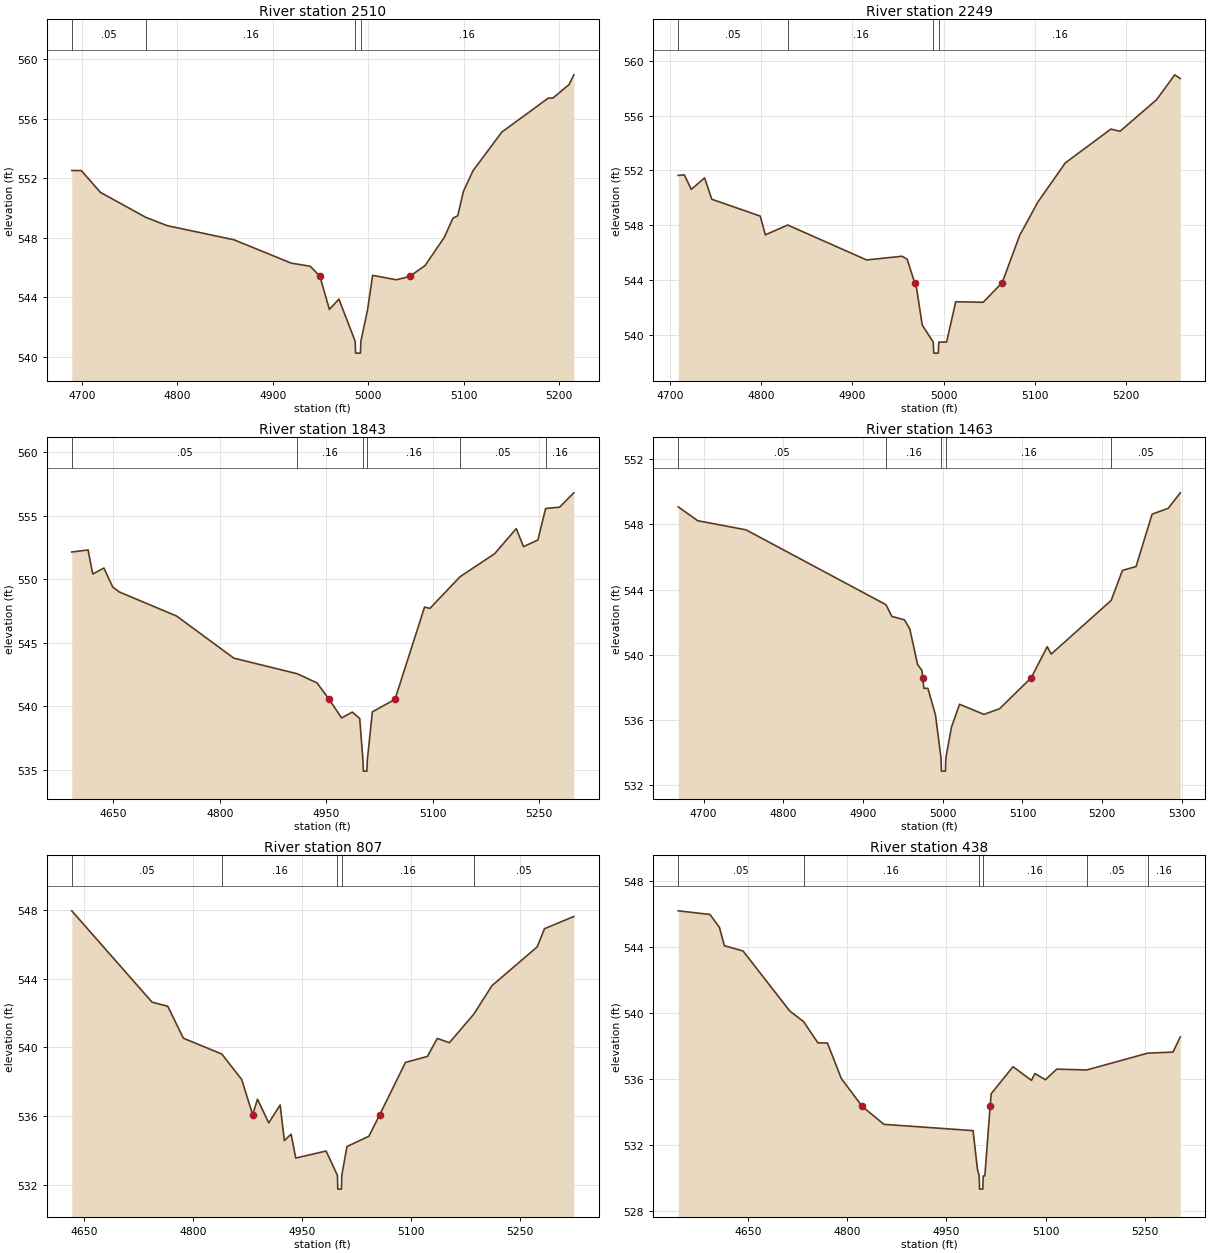
Type RM Length L Ch R = 1,2510,261,261,261
BEGIN DESCRIPTION:
WEST FORK TURKEY CREEK TRIB 3 4.0
END DESCRIPTION:
XS GIS Cut Line= 3
      2766575.00      7085424.98      2766578.87      7085109.41
      2766557.62      7084899.88
#Sta/Elev= 30
  4689.2  552.52  4699.2  552.51  4719.2  551.05  4766.7  549.37  4789.2  548.81
  4859.2  547.86  4919.2  546.29  4939.2  546.08  4949.2  545.41  4959.2  543.18
  4969.2  543.87  4986.2  541.04  4986.7  540.24  4991.7  540.24  4992.2  541.04
  4999.2  543.15  5004.5  545.47  5029.3  545.17  5043.5  545.40  5059.5  546.13
  5079.6  548.02  5088.7  549.31  5093.7  549.48  5099.7  551.12  5109.7  552.50
  5139.9  555.10  5188.5  557.38  5193.5  557.39  5210.3  558.29  5215.4  558.95
#Mann=4,-1,0
  4689.2    0.05       0  4766.7    0.16       0  4986.2    0.07       0
  4992.2    0.16       0
Bank Sta=4949.2,5043.5
Exp/Cntr=0.3,0.1

Type RM Length L Ch R = 1,2249,406,406,406
BEGIN DESCRIPTION:
Mapping XS 2bd92ce8
END DESCRIPTION:
XS GIS Cut Line= 3
      2766657.89      7085437.72      2766788.61      7085182.36
      2766782.56      7084918.91
#Sta/Elev= 30
  4709.1  551.63  4715.8  551.67  4723.4  550.61  4738.0  551.45  4745.9  549.89
  4799.0  548.66  4804.6  547.29  4829.1  548.01  4915.6  545.46  4954.4  545.73
  4960.0  545.52  4968.3  543.80  4970.5  543.35  4976.6  540.71  4988.7  539.46
  4989.2  538.66  4994.2  538.66  4994.7  539.46  5003.3  539.47  5013.3  542.41
  5043.4  542.37  5064.2  543.80  5083.4  547.25  5103.4  549.69  5133.4  552.54
  5183.4  555.01  5193.4  554.85  5233.4  557.15  5253.4  558.97  5259.5  558.70
#Mann=4,-1,0
  4709.1    0.05       0  4829.1    0.16       0  4988.7    0.07       0
  4994.7    0.16       0
Bank Sta=4968.3,5064.2
Exp/Cntr=0.3,0.1

Type RM Length L Ch R = 1,1843,380,380,380
BEGIN DESCRIPTION:
WEST FORK TURKEY CREEK TRIB 3 3.0
END DESCRIPTION:
XS GIS Cut Line= 3
      2766675.01      7085474.99      2767025.00      7085275.00
      2767074.99      7084975.04
#Sta/Elev= 30
  4591.6  552.14  4614.6  552.30  4621.1  550.41  4636.9  550.88  4649.2  549.39
  4658.5  549.00  4739.2  547.11  4819.8  543.80  4909.3  542.57  4937.1  541.85
  4954.1  540.56  4971.7  539.10  4986.8  539.56  4997.2  539.06  5001.8  535.72
  5002.3  534.92  5007.3  534.92  5007.8  535.72  5015.0  539.58  5046.9  540.56
  5088.5  547.81  5096.1  547.71  5138.6  550.20  5187.3  552.01  5217.7  553.98
  5227.9  552.56  5248.1  553.08  5259.1  555.56  5278.6  555.66  5298.8  556.79
#Mann=6,-1,0
  4591.6    0.05       0  4909.3    0.16       0  5001.8    0.07       0
  5007.8    0.16       0  5138.6    0.05       0  5259.1    0.16       0
Bank Sta=4954.1,5046.9
Exp/Cntr=0.3,0.1

Type RM Length L Ch R = 1,1463,656,656,656
BEGIN DESCRIPTION:
Mapping XS 270a2bda
END DESCRIPTION:
XS GIS Cut Line= 3
      2767059.15      7085802.43      2767202.01      7085528.88
      2767238.46      7085209.87
#Sta/Elev= 30
  4668.3  549.08  4692.7  548.23  4753.3  547.67  4928.8  543.08  4936.2  542.36
  4952.0  542.15  4958.7  541.59  4968.5  539.41  4974.1  539.03  4975.0  538.59
  4976.3  537.95  4981.4  537.95  4990.9  536.33  4997.9  533.67  4998.4  532.87
  5003.4  532.87  5003.9  533.67  5011.0  535.57  5021.1  536.97  5051.8  536.35
  5071.4  536.70  5110.9  538.59  5131.1  540.50  5136.1  540.05  5211.3  543.34
  5225.4  545.18  5242.5  545.42  5262.6  548.63  5282.8  548.99  5298.0  549.94
#Mann=5,-1,0
  4668.3    0.05       0  4928.8    0.16       0  4997.9    0.07       0
  5003.9    0.16       0  5211.3    0.05       0
Bank Sta=4975,5110.9
Exp/Cntr=0.3,0.1

Type RM Length L Ch R = 1,807,369,369,369
BEGIN DESCRIPTION:
Mapping XS e970d57f
END DESCRIPTION:
XS GIS Cut Line= 3
      2767344.85      7085866.31      2767521.17      7085562.32
      2767563.73      7085224.92
#Sta/Elev= 30
  4632.7  547.96  4743.3  542.64  4764.9  542.40  4786.4  540.54  4839.3  539.62
  4866.7  538.14  4881.9  536.08  4888.5  536.99  4904.0  535.61  4919.7  536.65
  4925.5  534.58  4934.8  534.95  4941.2  533.56  4983.0  533.97  4998.6  532.55
  4999.1  531.75  5004.1  531.75  5004.6  532.55  5011.7  534.23  5041.9  534.83
  5056.8  536.08  5092.3  539.13  5122.5  539.48  5136.1  540.53  5152.8  540.28
  5186.4  541.94  5211.4  543.60  5273.7  545.86  5283.8  546.92  5324.2  547.63
#Mann=5,-1,0
  4632.7    0.05       0  4839.3    0.16       0  4998.6    0.07       0
  5004.6    0.16       0  5186.4    0.05       0
Bank Sta=4881.9,5056.8
Exp/Cntr=0.3,0.1

Type RM Length L Ch R = 1,438,0,0,0
BEGIN DESCRIPTION:
WEST FORK TURKEY CREEK TRIB 3 1.0
END DESCRIPTION:
XS GIS Cut Line= 3
      2767411.71      7085969.66      2767758.26      7085662.62
      2767843.37      7085379.96
#Sta/Elev= 30
  4544.9  546.19  4592.8  545.97  4607.1  545.19  4614.6  544.08  4642.8  543.76
  4713.3  540.13  4734.1  539.49  4755.9  538.20  4770.2  538.19  4791.1  536.05
  4822.6  534.36  4855.5  533.27  4990.1  532.89  4996.8  530.54  4999.4  530.15
  4999.9  529.35  5004.9  529.35  5005.4  530.15  5007.9  530.15  5015.9  534.36
  5017.5  535.12  5050.5  536.76  5078.3  535.93  5083.5  536.34  5099.4  535.97
  5116.5  536.61  5161.8  536.56  5254.1  537.58  5292.0  537.64  5303.1  538.56
#Mann=6,-1,0
  4544.9    0.05       0  4734.1    0.16       0  4999.4    0.07       0
  5005.4    0.16       0  5161.8    0.05       0  5254.1    0.16       0
Bank Sta=4822.6,5015.9
Exp/Cntr=0.3,0.1

Chan Stop Cuts=-1