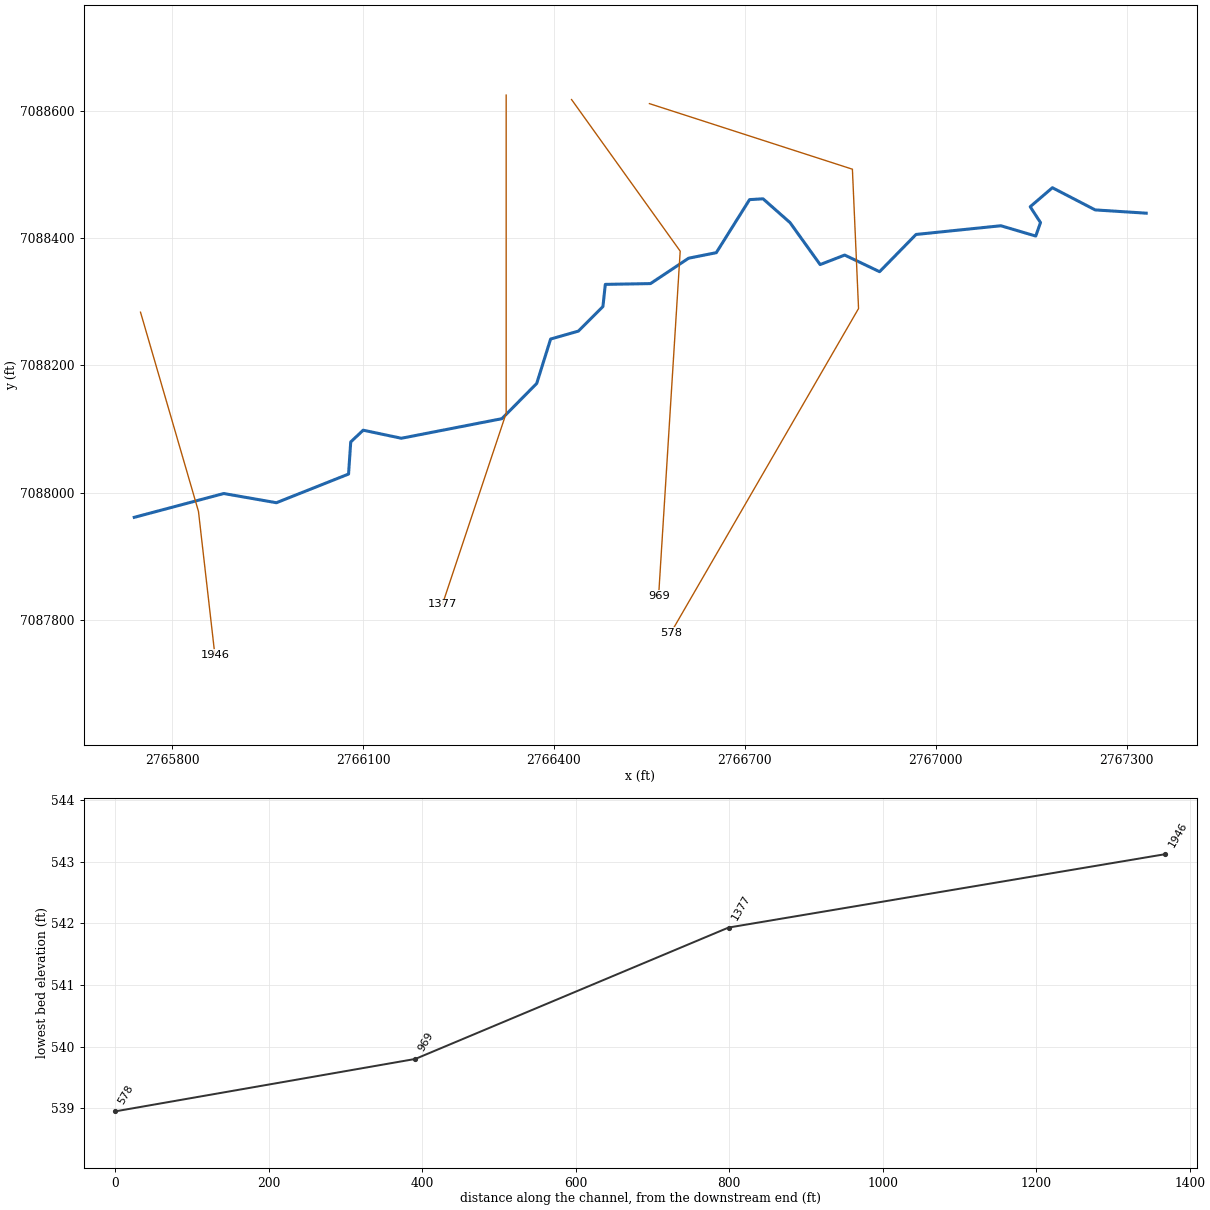
--- WEST FORK TURKEY CREEK TRIB 4.prj (project) ---

Proj Title=WEST FORK TURKEY CREEK TRIB 4 Base Level Engineering
Current Plan=p01
Default Exp/Contr=0.3,0.1
English Units
Geom File=g01
Flow File=f01
Plan File=p01
BEGIN DESCRIPTION:
WEST FORK TURKEY CREEK TRIB 4
END DESCRIPTION:

--- WEST FORK TURKEY CREEK TRIB 4.p01 (plan) ---

Plan Title=Multiple Run
Short Identifier=Multiple
Geom File=g01
Flow File=f01
Subcritical Flow
K Sum by GR= 0
Std Step Tol= 0.01
Critical Tol= 0.01
Num of Std Step Trials= 20
Max Error Tol= 0.3
Flow Tol Ratio= 0.001
Split Flow NTrial= 30
Split Flow Tol= 0.02
Split Flow Ratio= 0.02
Log Output Level= 0
Friction Slope Method= 1
Unsteady Friction Slope Method= 2
Unsteady Bridges Friction Slope Method= 1
Parabolic Critical Depth
Global Vel Dist=  1 , 1 , 1
Global Log Level= 0
CheckData=True
Encroach Param= -1, 0, 0, 0
BEGIN DESCRIPTION:
Multiple Run
END DESCRIPTION:

--- WEST FORK TURKEY CREEK TRIB 4.f01 (steady flow) ---

Flow Title=Multiple
Number of Profiles=7
Profile Names=10-year,25-year,50-year,1pct_min,100-year,1pct_plu,500-year
River Rch & RM= WEST FORK TURKEY,Reach-1,1946
     605     806     968     577    1152    2299    1626
Boundary for River Rch & Prof#=WEST FORK TURKEY,Reach-1,1
Up Type=0
Dn Type=3
Dn Slope=0.005
Boundary for River Rch & Prof#=WEST FORK TURKEY,Reach-1,2
Up Type=0
Dn Type=3
Dn Slope=0.005
Boundary for River Rch & Prof#=WEST FORK TURKEY,Reach-1,3
Up Type=0
Dn Type=3
Dn Slope=0.005
Boundary for River Rch & Prof#=WEST FORK TURKEY,Reach-1,4
Up Type=0
Dn Type=3
Dn Slope=0.005
Boundary for River Rch & Prof#=WEST FORK TURKEY,Reach-1,5
Up Type=0
Dn Type=3
Dn Slope=0.005
Boundary for River Rch & Prof#=WEST FORK TURKEY,Reach-1,6
Up Type=0
Dn Type=3
Dn Slope=0.005
Boundary for River Rch & Prof#=WEST FORK TURKEY,Reach-1,7
Up Type=0
Dn Type=3
Dn Slope=0.005

--- WEST FORK TURKEY CREEK TRIB 4.g01 (geometry) ---

Geom Title=Existing Conditions

River Reach=WEST FORK TURKEY,Reach-1
Reach XY= 30
      2765740.75      7087961.32      2765881.34      7087998.75
      2765964.06      7087984.28      2766077.38      7088029.35
      2766080.82      7088079.85      2766100.41      7088098.28
      2766160.34      7088085.60      2766318.30      7088116.38
      2766372.98      7088171.75      2766394.82      7088241.54
      2766438.40      7088253.99      2766477.00      7088292.59
      2766480.74      7088327.46      2766551.72      7088328.70
      2766611.49      7088368.55      2766655.08      7088377.27
      2766707.38      7088460.70      2766728.55      7088461.95
      2766770.89      7088424.59      2766818.21      7088358.59
      2766856.81      7088373.53      2766911.60      7088347.38
      2766968.88      7088405.91      2767102.12      7088419.61
      2767156.92      7088403.42      2767164.39      7088424.59
      2767148.20      7088449.50      2767183.07      7088479.38
      2767250.31      7088444.51      2767330.43      7088439.37

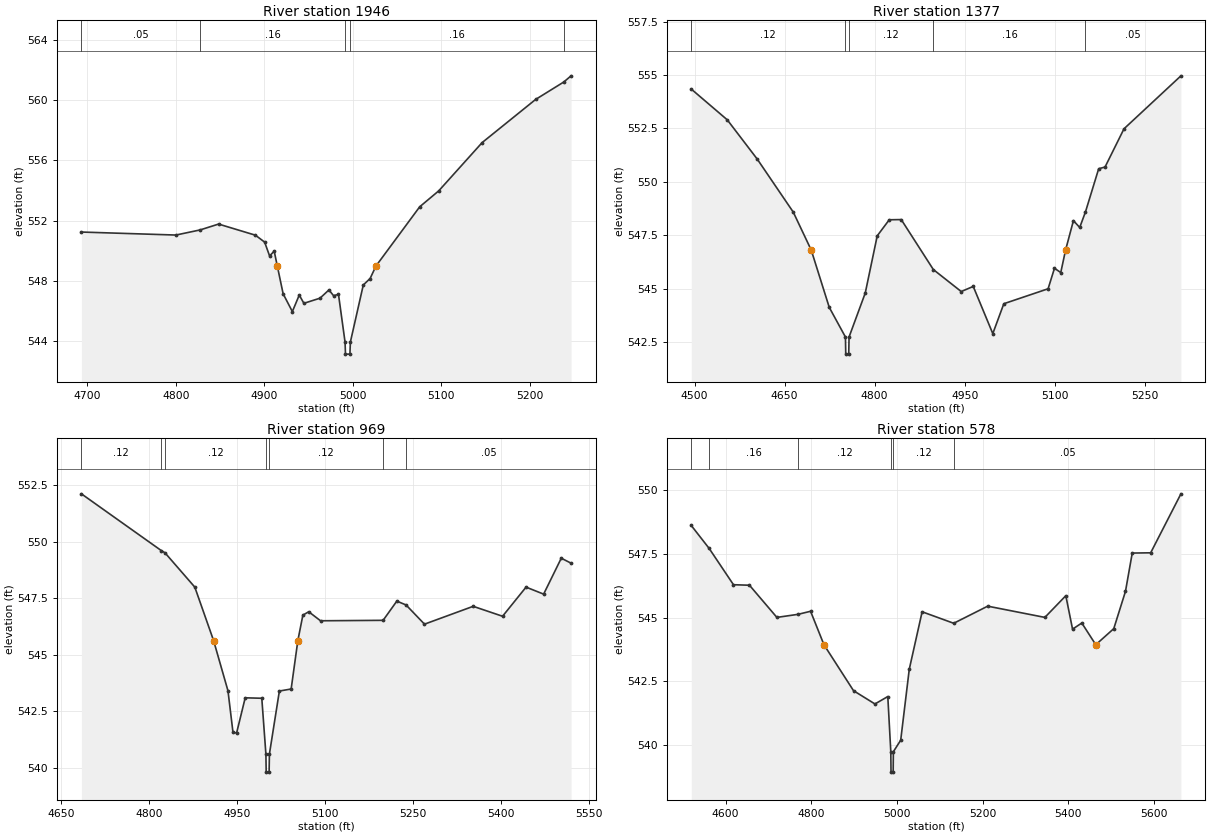
Type RM Length L Ch R = 1,1946,569,569,569
BEGIN DESCRIPTION:
WEST FORK TURKEY CREEK TRIB 4 3.0
END DESCRIPTION:
XS GIS Cut Line= 3
      2765750.59      7088283.72      2765841.61      7087970.69
      2765867.37      7087745.25
#Sta/Elev= 30
  4693.5  551.24  4800.2  551.04  4827.5  551.38  4848.4  551.77  4890.0  551.03
  4900.4  550.57  4906.0  549.65  4911.2  549.97  4914.7  548.98  4921.3  547.13
  4931.7  545.95  4939.5  547.05  4944.7  546.50  4962.9  546.84  4973.0  547.39
  4978.2  547.01  4983.8  547.09  4991.2  543.92  4991.7  543.12  4996.7  543.12
  4997.2  543.92  5011.8  547.72  5019.5  548.15  5026.1  548.98  5075.5  552.92
  5097.0  553.98  5146.0  557.19  5206.4  560.06  5238.2  561.22  5246.4  561.63
#Mann=5,-1,0
  4693.5    0.05       0  4827.5    0.16       0  4991.2    0.07       0
  4997.2    0.16       0  5238.2    0.05       0
Bank Sta=4914.7,5026.1
Exp/Cntr=0.3,0.1

Type RM Length L Ch R = 1,1377,408,408,408
BEGIN DESCRIPTION:
WEST FORK TURKEY CREEK TRIB 4 2.0
END DESCRIPTION:
XS GIS Cut Line= 3
      2766325.00      7088624.95      2766325.00      7088125.00
      2766224.99      7087824.98
#Sta/Elev= 30
  4494.3  554.34  4554.3  552.90  4604.3  551.06  4664.3  548.58  4694.3  546.80
  4724.3  544.12  4751.3  542.73  4751.8  541.93  4756.8  541.93  4757.3  542.73
  4784.3  544.79  4804.3  547.47  4824.3  548.22  4844.3  548.23  4897.8  545.89
  4944.3  544.86  4964.3  545.10  4996.9  542.89  5015.3  544.29  5089.1  544.99
  5099.7  545.95  5110.2  545.75  5118.2  546.80  5131.3  548.18  5141.8  547.86
  5151.4  548.59  5173.4  550.61  5184.0  550.69  5215.6  552.48  5310.5  554.96
#Mann=5,-1,0
  4494.3    0.12       0  4751.3    0.07       0  4757.3    0.12       0
  4897.8    0.16       0  5151.4    0.05       0
Bank Sta=4694.3,5118.2
Exp/Cntr=0.3,0.1

Type RM Length L Ch R = 1,969,391,391,391
BEGIN DESCRIPTION:
Mapping XS 2d64d93c
END DESCRIPTION:
XS GIS Cut Line= 3
      2766427.73      7088617.95      2766598.39      7088379.68
      2766564.50      7087838.32
#Sta/Elev= 30
  4684.6  552.12  4820.8  549.61  4827.2  549.51  4878.1  547.99  4910.2  545.62
  4934.7  543.40  4943.2  541.57  4949.4  541.53  4964.1  543.09  4992.4  543.07
  4999.4  540.60  4999.9  539.80  5004.9  539.80  5005.4  540.60  5022.4  543.39
  5042.5  543.48  5053.9  545.62  5062.5  546.75  5072.5  546.90  5092.6  546.50
  5199.4  546.52  5222.8  547.37  5238.6  547.20  5270.0  546.35  5353.1  547.14
  5403.2  546.70  5443.3  547.99  5473.3  547.68  5503.4  549.27  5520.1  549.05
#Mann=7,-1,0
  4684.6    0.12       0  4820.8    0.16       0  4827.2    0.12       0
  4999.4    0.07       0  5005.4    0.12       0  5199.4    0.16       0
  5238.6    0.05       0
Bank Sta=4910.2,5053.9
Exp/Cntr=0.3,0.1

Type RM Length L Ch R = 1,578,0,0,0
BEGIN DESCRIPTION:
WEST FORK TURKEY CREEK TRIB 4 1.0
END DESCRIPTION:
XS GIS Cut Line= 4
      2766550.11      7088611.53      2766868.90      7088508.49
      2766878.56      7088289.51      2766583.91      7087780.22
#Sta/Elev= 30
  4520.1  548.61  4561.9  547.71  4618.6  546.29  4655.9  546.27  4719.9  545.01
  4769.2  545.13  4798.5  545.25  4829.7  543.94  4898.7  542.14  4948.7  541.62
  4978.7  541.91  4985.7  539.75  4986.2  538.95  4991.2  538.95  4991.7  539.75
  5008.8  540.20  5028.8  542.98  5058.8  545.23  5132.5  544.78  5211.8  545.45
  5345.2  545.01  5394.1  545.86  5409.8  544.55  5431.4  544.79  5464.0  543.94
  5506.0  544.57  5533.3  546.03  5549.1  547.53  5592.1  547.54  5662.7  549.85
#Mann=6,-1,0
  4520.1    0.12       0  4561.9    0.16       0  4769.2    0.12       0
  4985.7    0.07       0  4991.7    0.12       0  5132.5    0.05       0
Bank Sta=4829.7,5464
Exp/Cntr=0.3,0.1

Chan Stop Cuts=-1