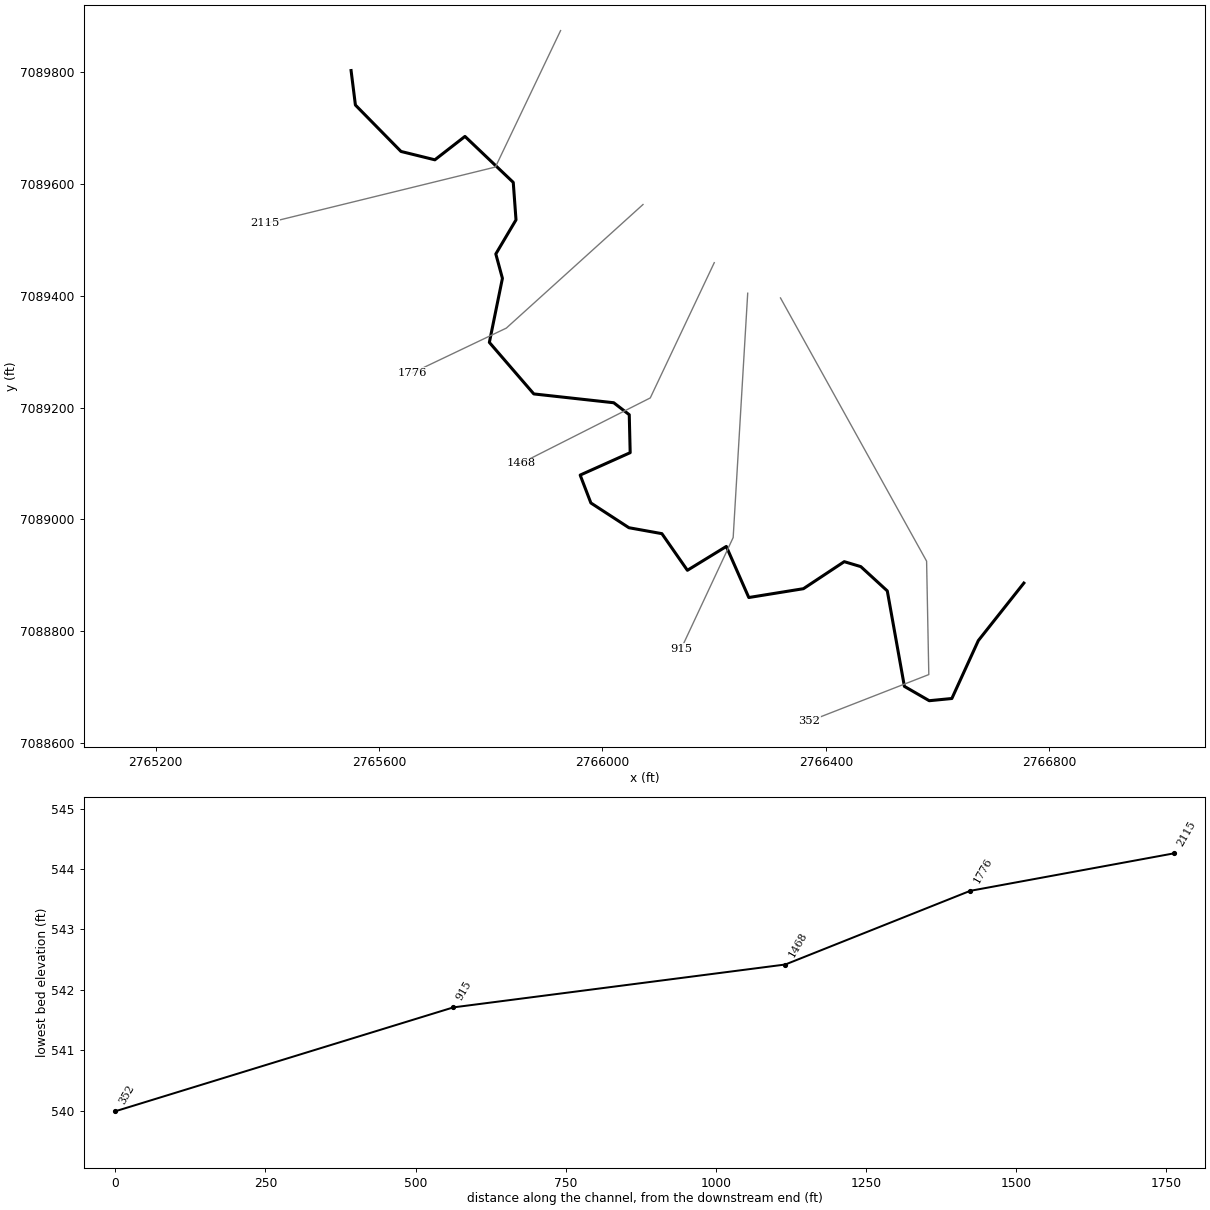
--- WEST FORK TURKEY CREEK TRIB 5.prj (project) ---

Proj Title=WEST FORK TURKEY CREEK TRIB 5 Base Level Engineering
Current Plan=p01
Default Exp/Contr=0.3,0.1
English Units
Geom File=g01
Flow File=f01
Plan File=p01
BEGIN DESCRIPTION:
WEST FORK TURKEY CREEK TRIB 5
END DESCRIPTION:

--- WEST FORK TURKEY CREEK TRIB 5.p01 (plan) ---

Plan Title=Multiple Run
Short Identifier=Multiple
Geom File=g01
Flow File=f01
Subcritical Flow
K Sum by GR= 0
Std Step Tol= 0.01
Critical Tol= 0.01
Num of Std Step Trials= 20
Max Error Tol= 0.3
Flow Tol Ratio= 0.001
Split Flow NTrial= 30
Split Flow Tol= 0.02
Split Flow Ratio= 0.02
Log Output Level= 0
Friction Slope Method= 1
Unsteady Friction Slope Method= 2
Unsteady Bridges Friction Slope Method= 1
Parabolic Critical Depth
Global Vel Dist=  1 , 1 , 1
Global Log Level= 0
CheckData=True
Encroach Param= -1, 0, 0, 0
BEGIN DESCRIPTION:
Multiple Run
END DESCRIPTION:

--- WEST FORK TURKEY CREEK TRIB 5.f01 (steady flow) ---

Flow Title=Multiple
Number of Profiles=7
Profile Names=10-year,25-year,50-year,1pct_min,100-year,1pct_plu,500-year
River Rch & RM= WEST FORK TURKEY,Reach-1,2115
     465     606     716     421     840    1676    1150
Boundary for River Rch & Prof#=WEST FORK TURKEY,Reach-1,1
Up Type=0
Dn Type=3
Dn Slope=0.005
Boundary for River Rch & Prof#=WEST FORK TURKEY,Reach-1,2
Up Type=0
Dn Type=3
Dn Slope=0.005
Boundary for River Rch & Prof#=WEST FORK TURKEY,Reach-1,3
Up Type=0
Dn Type=3
Dn Slope=0.005
Boundary for River Rch & Prof#=WEST FORK TURKEY,Reach-1,4
Up Type=0
Dn Type=3
Dn Slope=0.005
Boundary for River Rch & Prof#=WEST FORK TURKEY,Reach-1,5
Up Type=0
Dn Type=3
Dn Slope=0.005
Boundary for River Rch & Prof#=WEST FORK TURKEY,Reach-1,6
Up Type=0
Dn Type=3
Dn Slope=0.005
Boundary for River Rch & Prof#=WEST FORK TURKEY,Reach-1,7
Up Type=0
Dn Type=3
Dn Slope=0.005

--- WEST FORK TURKEY CREEK TRIB 5.g01 (geometry) ---

Geom Title=Existing Conditions

River Reach=WEST FORK TURKEY,Reach-1
Reach XY= 30
      2765549.87      7089803.44      2765557.61      7089741.69
      2765639.24      7089658.59      2765699.91      7089643.62
      2765753.81      7089685.50      2765840.27      7089603.21
      2765845.20      7089536.06      2765809.04      7089475.01
      2765820.87      7089431.36      2765797.49      7089316.64
      2765877.07      7089224.38      2766020.22      7089208.60
      2766047.99      7089187.15      2766049.65      7089119.19
      2765960.10      7089079.06      2765979.28      7089029.12
      2766047.35      7088984.80      2766106.44      7088974.17
      2766152.10      7088908.54      2766221.76      7088951.27
      2766262.05      7088859.80      2766359.87      7088875.61
      2766432.99      7088924.02      2766462.64      7088915.13
      2766510.06      7088871.65      2766540.69      7088700.71
      2766585.16      7088675.02      2766625.67      7088678.98
      2766673.10      7088782.73      2766754.62      7088885.66

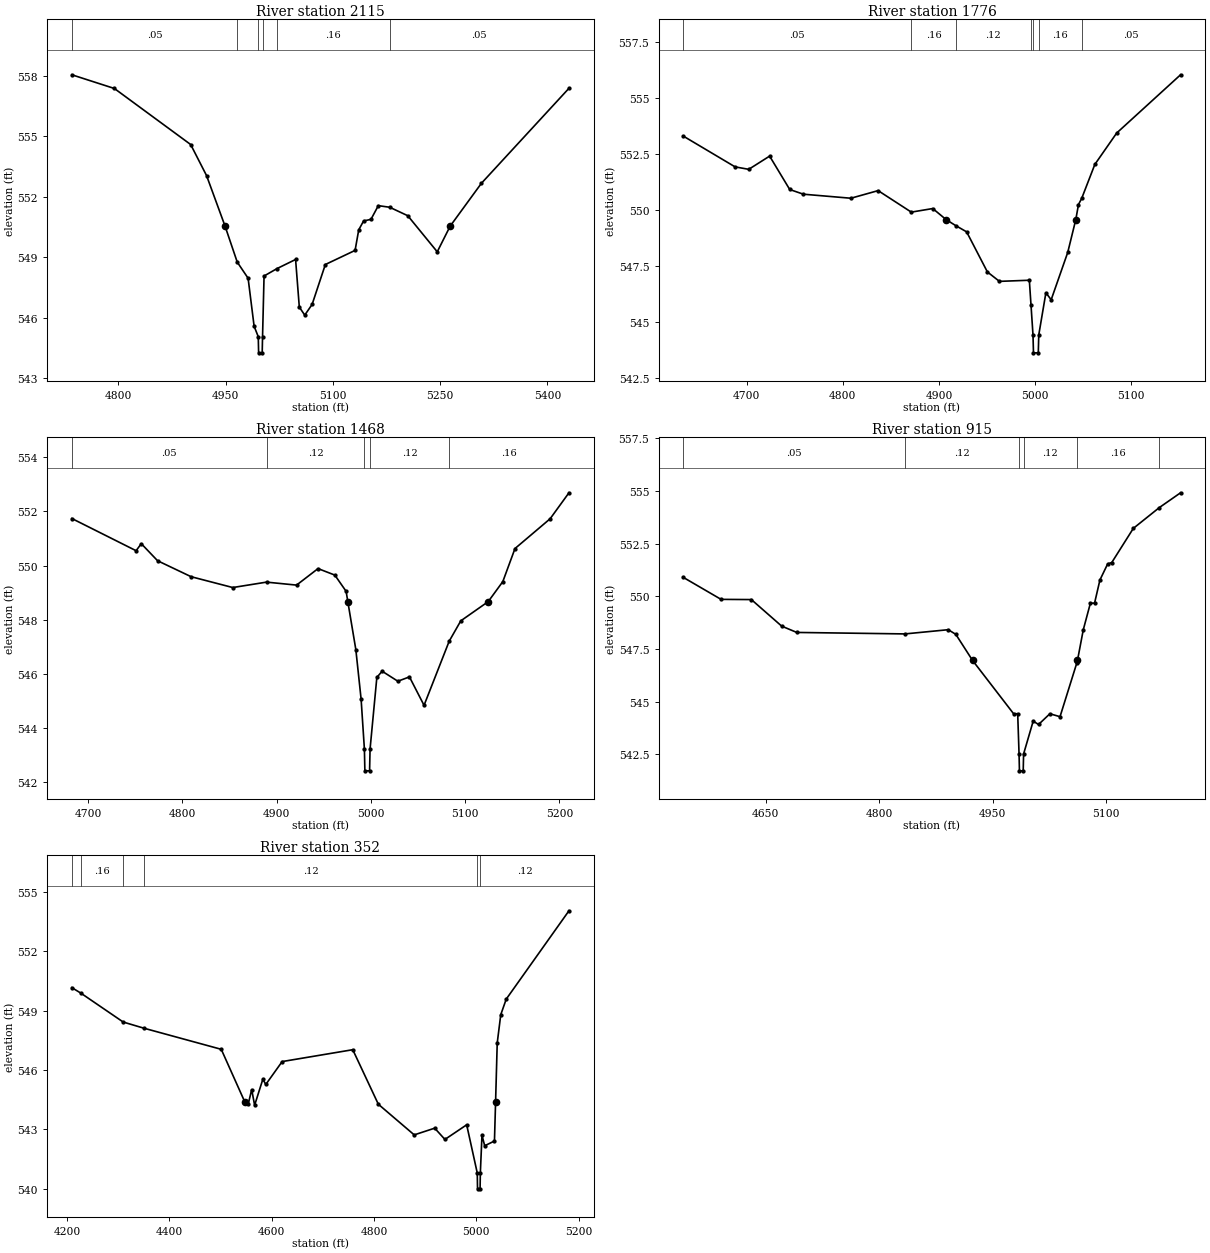
Type RM Length L Ch R = 1,2115,339,339,339
BEGIN DESCRIPTION:
WEST FORK TURKEY CREEK TRIB 5 1.0
END DESCRIPTION:
XS GIS Cut Line= 3
      2765925.00      7089875.00      2765808.36      7089630.69
      2765396.11      7089529.57
#Sta/Elev= 30
  4734.9  558.05  4794.4  557.37  4901.1  554.59  4923.3  553.05  4949.2  550.54
  4966.2  548.76  4981.4  547.96  4989.8  545.58  4995.6  545.06  4996.1  544.26
  5001.1  544.26  5001.6  545.06  5003.7  548.07  5021.9  548.44  5047.8  548.89
  5053.0  546.53  5060.6  546.13  5070.9  546.66  5089.4  548.64  5131.0  549.34
  5136.1  550.36  5142.9  550.80  5153.2  550.88  5163.5  551.56  5179.4  551.48
  5204.7  551.06  5245.9  549.27  5263.9  550.54  5307.7  552.67  5430.1  557.38
#Mann=6,-1,0
  4734.9    0.05       0  4966.2    0.12       0  4995.6    0.07       0
  5001.6    0.12       0  5021.9    0.16       0  5179.4    0.05       0
Bank Sta=4949.2,5263.9
Exp/Cntr=0.3,0.1

Type RM Length L Ch R = 1,1776,308,308,308
BEGIN DESCRIPTION:
Mapping XS 98ce4444
END DESCRIPTION:
XS GIS Cut Line= 3
      2766072.60      7089563.57      2765827.82      7089342.23
      2765659.23      7089261.82
#Sta/Elev= 30
  4634.4  553.31  4688.1  551.94  4702.3  551.83  4724.0  552.42  4744.9  550.93
  4759.1  550.72  4808.5  550.54  4836.8  550.88  4871.3  549.92  4893.6  550.08
  4907.4  549.59  4917.4  549.32  4928.8  549.04  4950.4  547.25  4962.9  546.83
  4994.0  546.88  4995.7  545.79  4997.8  544.44  4998.3  543.64  5003.3  543.64
  5003.8  544.44  5011.2  546.32  5016.7  546.01  5033.9  548.12  5042.3  549.59
  5045.1  550.26  5048.4  550.53  5062.1  552.05  5084.8  553.45  5151.2  556.05
#Mann=7,-1,0
  4634.4    0.05       0  4871.3    0.16       0  4917.4    0.12       0
  4995.7    0.16       0  4997.8    0.07       0  5003.8    0.16       0
  5048.4    0.05       0
Bank Sta=4907.4,5042.3
Exp/Cntr=0.3,0.1

Type RM Length L Ch R = 1,1468,553,553,553
BEGIN DESCRIPTION:
Mapping XS e212e669
END DESCRIPTION:
XS GIS Cut Line= 3
      2766200.22      7089459.42      2766085.63      7089217.23
      2765853.90      7089100.06
#Sta/Elev= 30
  4682.6  551.74  4750.8  550.55  4756.3  550.81  4773.6  550.18  4809.2  549.59
  4853.4  549.19  4889.2  549.39  4921.1  549.28  4943.9  549.89  4961.7  549.65
  4973.7  549.05  4975.5  548.67  4984.0  546.90  4989.6  545.07  4993.1  543.22
  4993.6  542.42  4998.6  542.42  4999.1  543.22  5006.3  545.87  5011.9  546.10
  5028.6  545.73  5040.9  545.89  5056.4  544.84  5083.1  547.21  5095.4  547.96
  5124.5  548.67  5140.0  549.41  5152.9  550.63  5190.2  551.73  5210.2  552.69
#Mann=5,-1,0
  4682.6    0.05       0  4889.2    0.12       0  4993.1    0.07       0
  4999.1    0.12       0  5083.1    0.16       0
Bank Sta=4975.5,5124.5
Exp/Cntr=0.3,0.1

Type RM Length L Ch R = 1,915,563,563,563
BEGIN DESCRIPTION:
Mapping XS 8f57f0ec
END DESCRIPTION:
XS GIS Cut Line= 3
      2766260.11      7089404.75      2766234.07      7088967.23
      2766141.10      7088768.38
#Sta/Elev= 30
  4541.0  550.89  4590.8  549.85  4630.9  549.84  4671.0  548.58  4691.0  548.28
  4834.2  548.21  4891.4  548.41  4901.4  548.19  4923.6  546.95  4977.9  544.42
  4983.3  544.42  4985.1  542.51  4985.6  541.71  4990.6  541.71  4991.1  542.51
  5003.8  544.07  5010.9  543.91  5025.9  544.42  5039.3  544.28  5061.6  546.84
  5062.4  546.95  5070.1  548.41  5079.5  549.67  5085.0  549.67  5092.1  550.77
  5102.3  551.53  5107.8  551.60  5136.3  553.22  5170.8  554.21  5198.8  554.91
#Mann=6,-1,0
  4541.0    0.05       0  4834.2    0.12       0  4985.1    0.07       0
  4991.1    0.12       0  5061.6    0.16       0  5170.8    0.05       0
Bank Sta=4923.6,5062.4
Exp/Cntr=0.3,0.1

Type RM Length L Ch R = 1,352,0,0,0
BEGIN DESCRIPTION:
WEST FORK TURKEY CREEK TRIB 5 0.0
END DESCRIPTION:
XS GIS Cut Line= 4
      2766318.80      7089396.28      2766580.44      7088924.93
      2766584.40      7088721.83      2766370.82      7088638.49
#Sta/Elev= 30
  4209.6  550.17  4226.8  549.90  4310.0  548.43  4350.2  548.12  4501.6  547.05
  4547.4  544.40  4554.2  544.27  4561.1  545.01  4566.8  544.22  4582.9  545.54
  4588.6  545.27  4620.6  546.43  4758.6  547.03  4808.6  544.27  4878.7  542.72
  4918.7  543.06  4938.7  542.49  4981.2  543.23  5001.9  540.79  5002.4  539.99
  5007.4  539.99  5007.9  540.79  5011.1  542.70  5016.4  542.17  5035.5  542.41
  5037.7  544.40  5040.9  547.37  5047.8  548.80  5058.5  549.59  5181.1  554.06
#Mann=6,-1,0
  4209.6    0.05       0  4226.8    0.16       0  4310.0    0.05       0
  4350.2    0.12       0  5001.9    0.07       0  5007.9    0.12       0
Bank Sta=4547.4,5037.7
Exp/Cntr=0.3,0.1

Chan Stop Cuts=-1