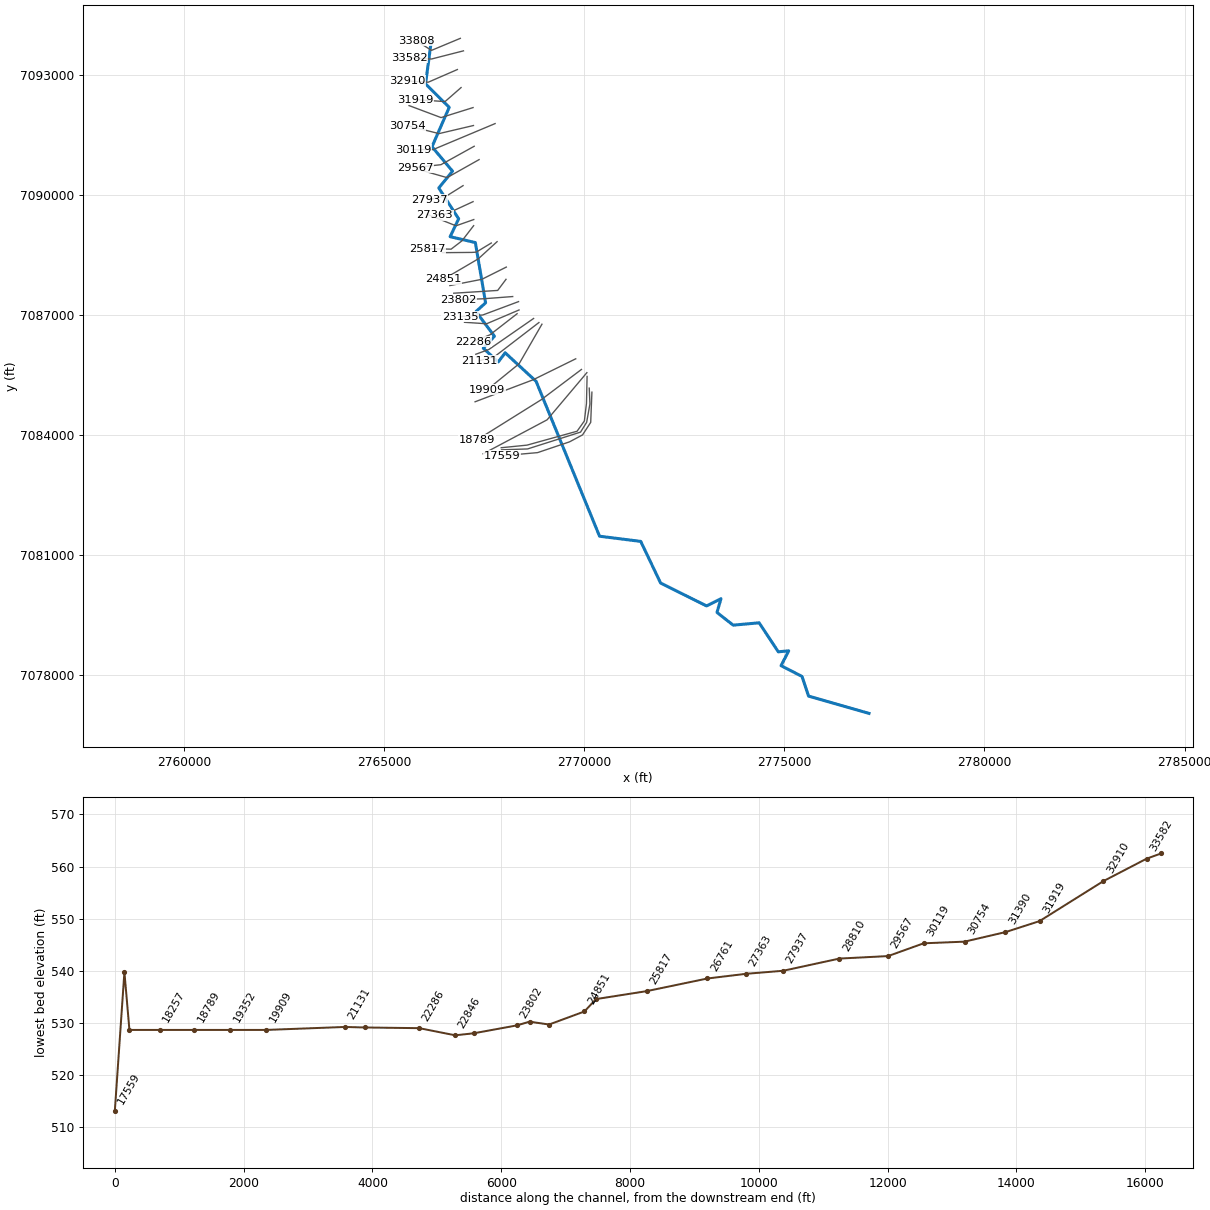
--- WEST FORK TURKEY CREEK.prj (project) ---

Proj Title=WEST FORK TURKEY CREEK Base Level Engineering
Current Plan=p01
Default Exp/Contr=0.3,0.1
English Units
Geom File=g01
Flow File=f01
Plan File=p01
BEGIN DESCRIPTION:
WEST FORK TURKEY CREEK
END DESCRIPTION:

--- WEST FORK TURKEY CREEK.p01 (plan) ---

Plan Title=Multiple Run
Short Identifier=Multiple
Geom File=g01
Flow File=f01
Subcritical Flow
K Sum by GR= 0
Std Step Tol= 0.01
Critical Tol= 0.01
Num of Std Step Trials= 20
Max Error Tol= 0.3
Flow Tol Ratio= 0.001
Split Flow NTrial= 30
Split Flow Tol= 0.02
Split Flow Ratio= 0.02
Log Output Level= 0
Friction Slope Method= 1
Unsteady Friction Slope Method= 2
Unsteady Bridges Friction Slope Method= 1
Parabolic Critical Depth
Global Vel Dist=  1 , 1 , 1
Global Log Level= 0
CheckData=True
Encroach Param= -1, 0, 0, 0
BEGIN DESCRIPTION:
Multiple Run
END DESCRIPTION:

--- WEST FORK TURKEY CREEK.f01 (steady flow) ---

Flow Title=Multiple
Number of Profiles=7
Profile Names=10-year,25-year,50-year,1pct_min,100-year,1pct_plu,500-year
River Rch & RM= WEST FORK TURKEY,Reach-1,33808
     707     944    1135     676    1348    2690    1900
River Rch & RM= WEST FORK TURKEY,Reach-1,33582
     872    1176    1422     852    1699    3390    2422
River Rch & RM= WEST FORK TURKEY,Reach-1,25817
    1145    1568    1915    1158    2310    4608    3354
River Rch & RM= WEST FORK TURKEY,Reach-1,24851
    1422    1963    2412    1465    2923    5832    4287
River Rch & RM= WEST FORK TURKEY,Reach-1,19909
    1736    2420    2992    1827    3646    7275    5411
River Rch & RM= WEST FORK TURKEY,Reach-1,13887
    1967    2756    3419    2094    4178    8337    6237
River Rch & RM= WEST FORK TURKEY,Reach-1,11014
    2429    3428    4274    2628    5243   10462    7890
Boundary for River Rch & Prof#=WEST FORK TURKEY,Reach-1,1
Up Type=0
Dn Type=3
Dn Slope=0.005
Boundary for River Rch & Prof#=WEST FORK TURKEY,Reach-1,2
Up Type=0
Dn Type=3
Dn Slope=0.005
Boundary for River Rch & Prof#=WEST FORK TURKEY,Reach-1,3
Up Type=0
Dn Type=3
Dn Slope=0.005
Boundary for River Rch & Prof#=WEST FORK TURKEY,Reach-1,4
Up Type=0
Dn Type=3
Dn Slope=0.005
Boundary for River Rch & Prof#=WEST FORK TURKEY,Reach-1,5
Up Type=0
Dn Type=3
Dn Slope=0.005
Boundary for River Rch & Prof#=WEST FORK TURKEY,Reach-1,6
Up Type=0
Dn Type=3
Dn Slope=0.005
Boundary for River Rch & Prof#=WEST FORK TURKEY,Reach-1,7
Up Type=0
Dn Type=3
Dn Slope=0.005

--- WEST FORK TURKEY CREEK.g01 (geometry) ---

Geom Title=Existing Conditions

River Reach=WEST FORK TURKEY,Reach-1
Reach XY= 30
      2766178.82      7093823.61      2766037.80      7092766.65
      2766628.44      7092180.86      2766198.52      7091197.08
      2766711.29      7090586.83      2766368.24      7090166.21
      2766865.00      7089395.70      2766651.89      7088950.01
      2767281.77      7088802.49      2767537.69      7087297.62
      2767297.58      7087079.25      2767759.02      7086461.69
      2767480.38      7086164.27      2767851.90      7085818.43
      2768026.79      7086048.66      2768799.49      7085335.25
      2770384.46      7081466.54      2771413.70      7081336.88
      2771909.24      7080298.23      2773057.04      7079725.18
      2773418.27      7079905.76      2773318.66      7079562.26
      2773722.11      7079244.91      2774372.15      7079303.23
      2774850.05      7078578.59      2775110.19      7078603.57
      2774919.21      7078232.71      2775442.70      7077963.35
      2775605.79      7077472.49      2777115.59      7077040.71

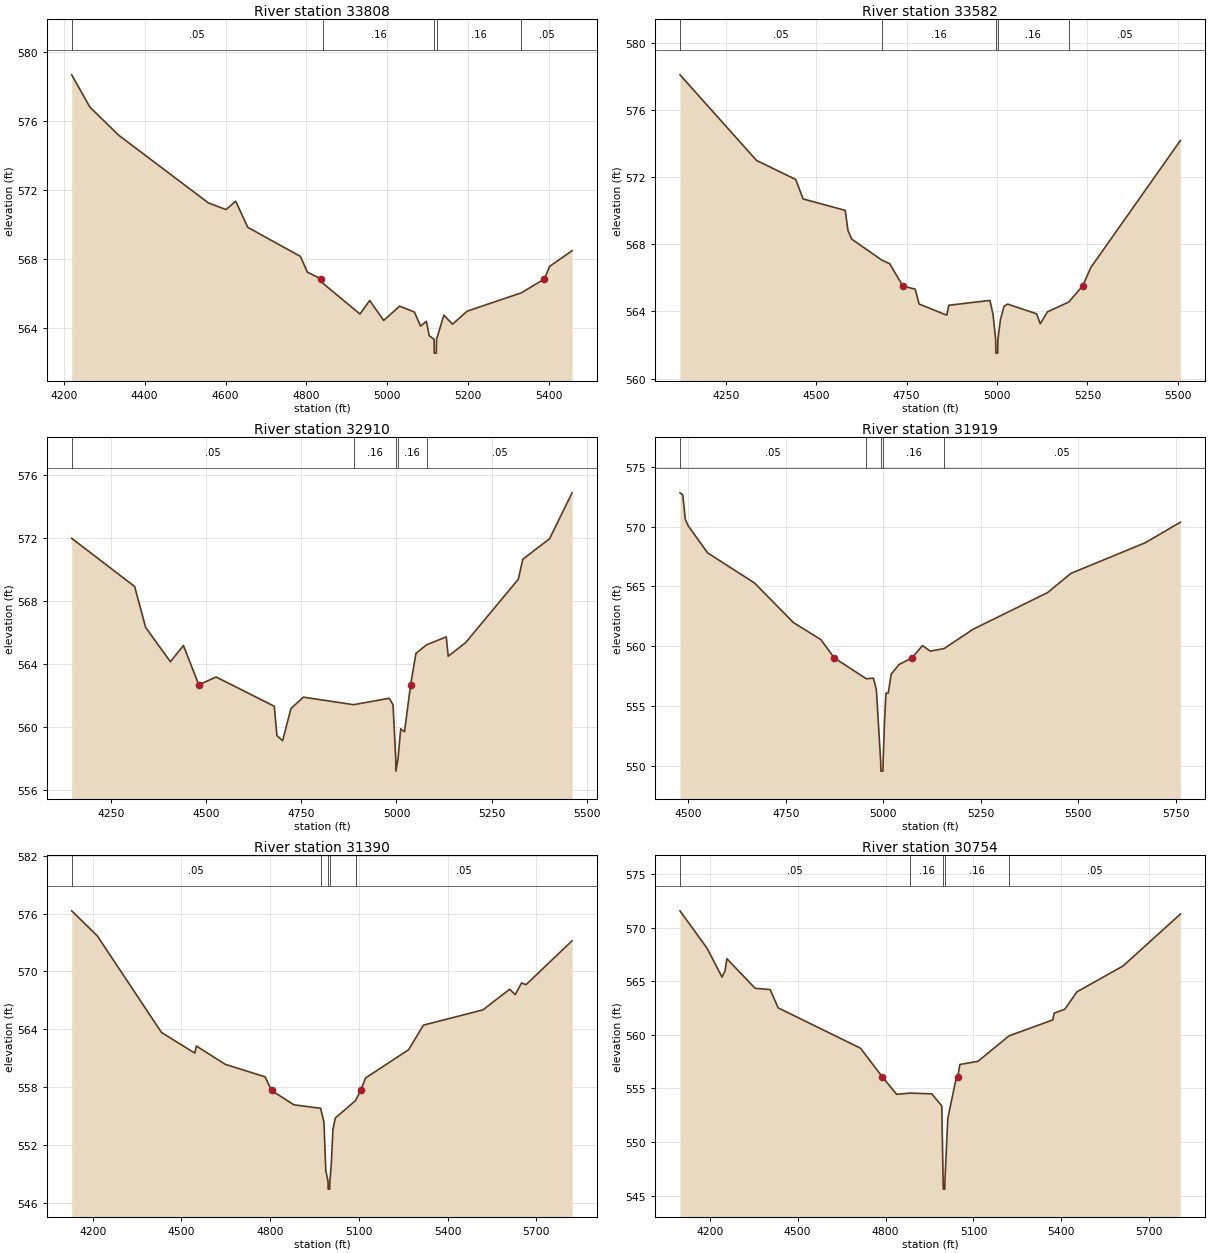
Type RM Length L Ch R = 1,33808,226,226,226
BEGIN DESCRIPTION:
WEST FORK TURKEY CREEK 38.0
END DESCRIPTION:
XS GIS Cut Line= 3
      2766906.73      7093904.95      2766186.73      7093604.43
      2765800.43      7093848.04
#Sta/Elev= 30
  4219.8  578.70  4265.0  576.82  4336.0  575.19  4557.6  571.26  4601.2  570.87
  4625.1  571.36  4655.1  569.84  4785.2  568.15  4802.6  567.23  4836.7  566.84
  4840.7  566.59  4932.5  564.80  4956.3  565.59  4991.0  564.43  5030.4  565.26
  5066.9  564.92  5082.2  564.10  5096.6  564.38  5103.4  563.55  5115.6  563.33
  5116.1  562.53  5121.1  562.53  5121.6  563.33  5139.8  564.74  5161.0  564.21
  5197.5  564.97  5331.0  566.03  5388.5  566.84  5401.1  567.57  5456.7  568.48
#Mann=5,-1,0
  4219.8    0.05       0  4840.7    0.16       0  5115.6    0.07       0
  5121.6    0.16       0  5331.0    0.05       0
Bank Sta=4836.7,5388.5
Exp/Cntr=0.3,0.1

Type RM Length L Ch R = 1,33582,672,672,672
BEGIN DESCRIPTION:
Mapping XS ff5eea36
END DESCRIPTION:
XS GIS Cut Line= 3
      2766984.84      7093592.44      2766186.22      7093388.44
      2765628.20      7093418.72
#Sta/Elev= 30
  4123.7  578.09  4335.4  572.99  4443.5  571.86  4464.1  570.70  4580.4  570.02
  4588.0  568.82  4598.3  568.31  4682.1  567.05  4703.0  566.85  4739.9  565.51
  4773.8  565.33  4784.7  564.44  4861.2  563.78  4866.7  564.37  4980.4  564.66
  4989.2  563.79  4996.3  562.32  4996.8  561.52  5001.8  561.52  5002.3  562.32
  5009.3  563.50  5019.3  564.31  5029.3  564.44  5109.4  563.86  5119.4  563.27
  5139.5  563.98  5198.1  564.56  5236.4  565.51  5259.6  566.63  5506.8  574.18
#Mann=5,-1,0
  4123.7    0.05       0  4682.1    0.16       0  4996.3    0.07       0
  5002.3    0.16       0  5198.1    0.05       0
Bank Sta=4739.9,5236.4
Exp/Cntr=0.3,0.1

Type RM Length L Ch R = 1,32910,991,991,991
BEGIN DESCRIPTION:
Mapping XS a2818969
END DESCRIPTION:
XS GIS Cut Line= 3
      2766832.47      7093125.54      2766106.78      7092809.57
      2765585.91      7092837.35
#Sta/Elev= 30
  4147.7  572.00  4312.9  568.94  4341.8  566.34  4406.7  564.16  4441.0  565.19
  4481.3  562.69  4526.7  563.19  4679.4  561.33  4686.2  559.47  4701.2  559.14
  4723.0  561.18  4755.7  561.91  4887.4  561.43  4981.0  561.84  4991.0  561.43
  4998.0  558.01  4998.5  557.21  5004.1  558.01  5011.1  559.90  5021.1  559.71
  5037.1  562.69  5051.1  564.69  5079.3  565.24  5130.7  565.74  5135.7  564.51
  5181.3  565.37  5319.7  569.40  5331.5  570.67  5401.6  571.97  5460.8  574.89
#Mann=5,-1,0
  4147.7    0.05       0  4887.4    0.16       0  4998.0    0.07       0
  5004.1    0.16       0  5079.3    0.05       0
Bank Sta=4481.3,5037.1
Exp/Cntr=0.3,0.1

Type RM Length L Ch R = 1,31919,529,529,529
BEGIN DESCRIPTION:
WEST FORK TURKEY CREEK 36.0
END DESCRIPTION:
XS GIS Cut Line= 3
      2766924.97      7092674.97      2766525.00      7092325.00
      2765775.03      7092375.00
#Sta/Elev= 30
  4478.9  572.83  4486.0  572.65  4492.6  570.60  4500.2  570.06  4549.6  567.81
  4670.1  565.28  4769.8  561.97  4840.0  560.55  4874.2  559.02  4956.6  557.27
  4974.8  557.32  4982.4  556.38  4993.5  550.34  4994.0  549.54  4999.2  549.54
  4999.7  550.34  5003.2  553.54  5007.0  556.07  5012.9  556.07  5020.4  557.65
  5040.4  558.46  5074.1  559.02  5100.6  560.05  5120.6  559.58  5156.3  559.80
  5230.9  561.42  5421.3  564.48  5481.4  566.09  5671.8  568.65  5762.0  570.37
#Mann=5,-1,0
  4478.9    0.05       0  4956.6    0.16       0  4993.5    0.07       0
  4999.7    0.16       0  5156.3    0.05       0
Bank Sta=4874.2,5074.1
Exp/Cntr=0.3,0.1

Type RM Length L Ch R = 1,31390,636,636,636
BEGIN DESCRIPTION:
WEST FORK TURKEY CREEK 35.0
END DESCRIPTION:
XS GIS Cut Line= 3
      2767225.02      7092175.01      2766425.00      7091925.00
      2765624.97      7092225.01
#Sta/Elev= 30
  4128.6  576.28  4215.1  573.69  4432.4  563.67  4545.1  561.53  4550.3  562.27
  4647.8  560.37  4782.9  559.07  4804.5  557.66  4880.3  556.17  4970.7  555.81
  4981.9  554.38  4988.1  549.37  4995.7  548.23  4996.2  547.43  5001.4  547.43
  5001.9  548.23  5006.8  550.02  5012.2  553.59  5020.2  554.80  5088.9  556.61
  5106.2  557.66  5122.5  558.95  5268.5  561.89  5318.3  564.43  5519.5  566.01
  5610.2  568.15  5628.9  567.59  5650.3  568.81  5665.4  568.62  5821.2  573.18
#Mann=5,-1,0
  4128.6    0.05       0  4970.7    0.16       0  4995.7    0.07       0
  5001.9    0.16       0  5088.9    0.05       0
Bank Sta=4804.5,5106.2
Exp/Cntr=0.3,0.1

Type RM Length L Ch R = 1,30754,635,635,635
BEGIN DESCRIPTION:
WEST FORK TURKEY CREEK 34.0
END DESCRIPTION:
XS GIS Cut Line= 3
      2767234.58      7091726.87      2766375.00      7091525.00
      2765574.99      7091725.00
#Sta/Elev= 30
  4098.6  571.57  4190.6  568.09  4242.0  565.39  4252.3  565.98  4258.6  567.10
  4355.0  564.34  4406.3  564.22  4433.4  562.52  4714.5  558.75  4788.6  556.09
  4837.8  554.45  4884.3  554.56  4957.8  554.49  4991.9  553.37  4996.5  546.40
  4997.0  545.60  5002.2  545.60  5002.7  546.40  5012.5  552.20  5040.8  555.91
  5046.6  556.09  5053.7  557.23  5115.6  557.53  5221.2  559.90  5370.7  561.39
  5375.8  562.03  5411.9  562.39  5453.1  564.01  5610.3  566.42  5806.2  571.27
#Mann=5,-1,0
  4098.6    0.05       0  4884.3    0.16       0  4996.5    0.07       0
  5002.7    0.16       0  5221.2    0.05       0
Bank Sta=4788.6,5046.6
Exp/Cntr=0.3,0.1

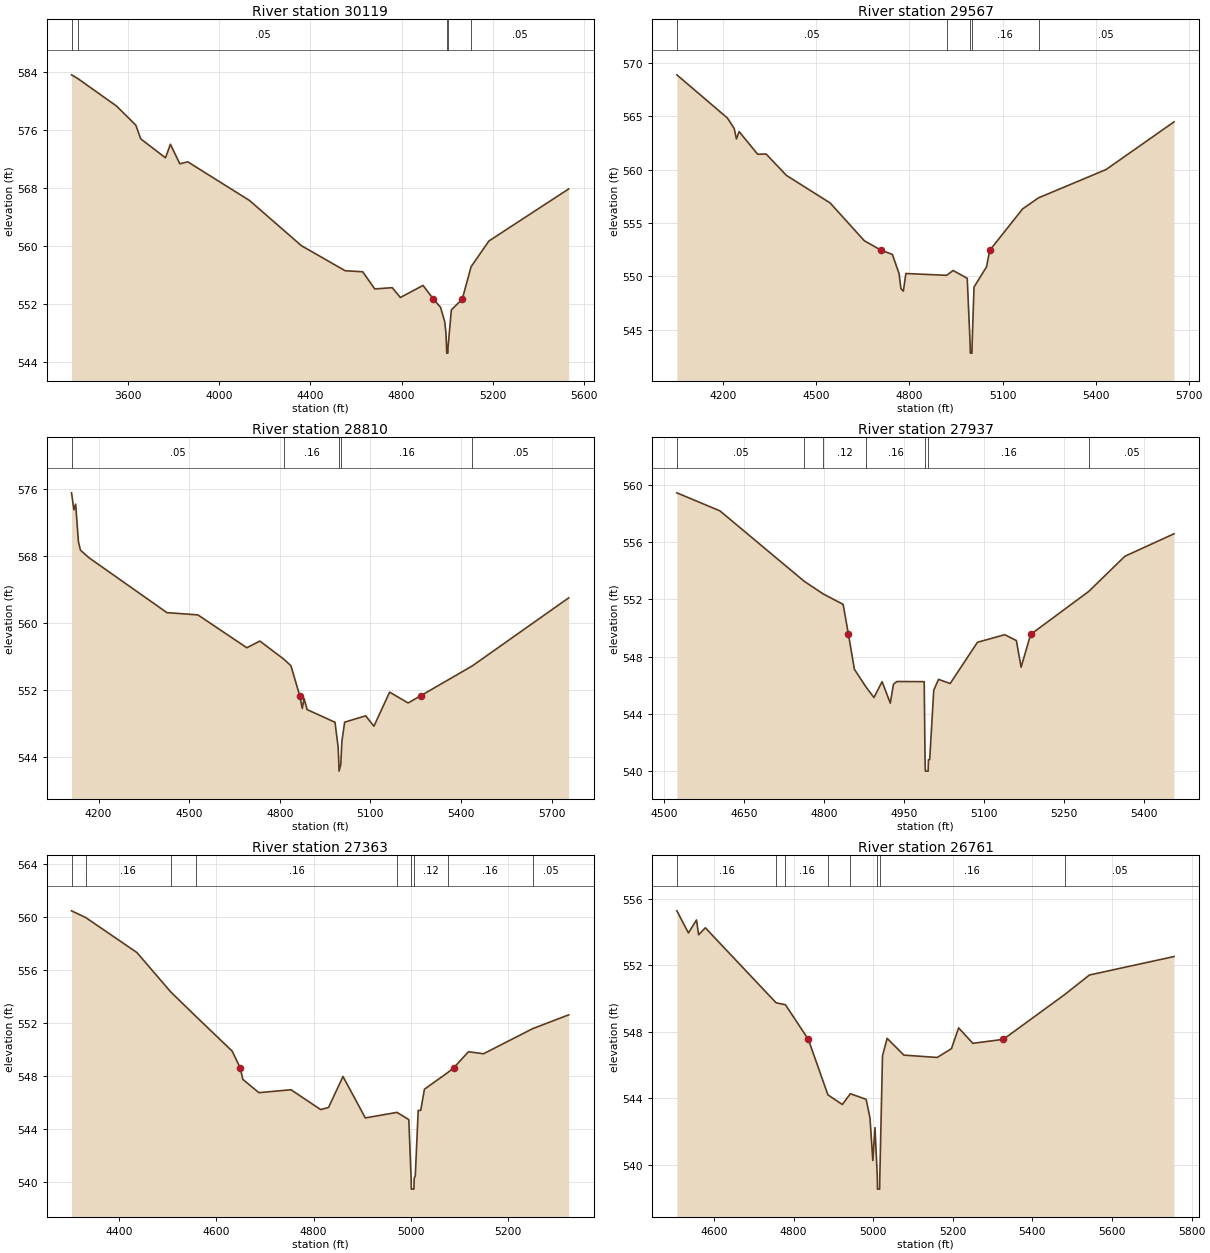
Type RM Length L Ch R = 1,30119,552,552,552
BEGIN DESCRIPTION:
WEST FORK TURKEY CREEK 33.0
END DESCRIPTION:
XS GIS Cut Line= 3
      2767775.04      7091775.02      2766225.00      7091125.00
      2765725.02      7091125.00
#Sta/Elev= 30
  3351.9  583.55  3381.2  583.00  3549.2  579.26  3633.9  576.63  3655.6  574.74
  3764.0  572.14  3785.7  574.00  3827.0  571.31  3861.6  571.59  4132.7  566.27
  4360.4  560.05  4552.3  556.61  4629.0  556.47  4682.0  554.11  4758.7  554.28
  4794.2  552.93  4893.8  554.59  4939.4  552.71  4970.6  551.58  4988.9  549.60
  4994.3  548.01  4997.0  546.08  4997.5  545.28  5002.8  545.28  5003.3  546.08
  5018.1  551.23  5065.8  552.71  5104.4  557.15  5182.7  560.70  5532.7  567.86
#Mann=5,-1,0
  3351.9    0.08       0  3381.2    0.05       0  4997.0    0.03       0
  5003.3    0.16       0  5104.4    0.05       0
Bank Sta=4939.4,5065.8
Exp/Cntr=0.3,0.1

Type RM Length L Ch R = 1,29567,757,757,757
BEGIN DESCRIPTION:
WEST FORK TURKEY CREEK 32.0
END DESCRIPTION:
XS GIS Cut Line= 3
      2767252.80      7091208.64      2766422.83      7090748.68
      2765775.01      7090675.00
#Sta/Elev= 30
  4051.1  568.87  4213.8  564.83  4235.6  563.86  4242.9  562.87  4251.6  563.56
  4311.2  561.44  4338.6  561.46  4403.9  559.46  4544.7  556.88  4654.5  553.35
  4709.1  552.45  4745.0  552.07  4766.7  550.26  4772.5  548.87  4780.3  548.63
  4788.5  550.28  4919.9  550.11  4940.7  550.56  4986.1  549.83  4995.5  543.63
  4996.0  542.83  5001.3  542.83  5001.8  543.63  5007.9  549.01  5048.1  550.90
  5058.5  552.45  5164.6  556.33  5215.6  557.36  5433.2  560.01  5652.0  564.47
#Mann=5,-1,0
  4051.1    0.05       0  4919.9    0.16       0  4995.5    0.07       0
  5001.8    0.16       0  5215.6    0.05       0
Bank Sta=4709.1,5058.5
Exp/Cntr=0.3,0.1

Type RM Length L Ch R = 1,28810,873,873,873
BEGIN DESCRIPTION:
WEST FORK TURKEY CREEK 31.0
END DESCRIPTION:
XS GIS Cut Line= 3
      2767374.98      7090874.99      2766575.00      7090425.00
      2765874.97      7090625.01
#Sta/Elev= 30
  4110.5  575.50  4118.4  573.48  4124.2  574.15  4133.4  569.67  4140.1  568.67
  4167.8  567.78  4426.3  561.23  4528.9  560.96  4690.8  557.05  4734.2  557.84
  4813.9  555.67  4836.8  554.91  4866.1  551.33  4874.4  549.82  4880.2  551.01
  4890.4  549.68  4982.8  548.17  4993.0  545.25  4995.6  543.15  4996.1  542.35
  5001.9  543.15  5005.4  545.83  5014.6  548.18  5084.3  548.94  5111.6  547.70
  5163.6  551.76  5224.7  550.47  5266.5  551.33  5437.1  554.88  5756.4  562.99
#Mann=5,-1,0
  4110.5    0.05       0  4813.9    0.16       0  4995.6    0.07       0
  5001.9    0.16       0  5437.1    0.05       0
Bank Sta=4866.1,5266.5
Exp/Cntr=0.3,0.1

Type RM Length L Ch R = 1,27937,574,574,574
BEGIN DESCRIPTION:
WEST FORK TURKEY CREEK 30.0
END DESCRIPTION:
XS GIS Cut Line= 3
      2766975.00      7090225.00      2766575.00      7089975.00
      2766124.98      7089875.00
#Sta/Elev= 30
  4524.1  559.45  4604.9  558.19  4763.4  553.26  4799.0  552.38  4836.0  551.66
  4846.0  549.56  4857.2  547.12  4878.5  545.91  4893.8  545.15  4909.1  546.26
  4924.5  544.76  4930.4  546.08  4936.8  546.27  4988.1  546.26  4989.7  540.81
  4990.2  540.01  4995.5  540.01  4996.0  540.81  4998.4  540.81  5006.0  545.66
  5015.0  546.42  5036.8  546.13  5088.0  549.01  5139.2  549.54  5161.0  549.13
  5169.9  547.27  5187.8  549.56  5296.7  552.56  5364.6  555.02  5456.8  556.59
#Mann=7,-1,0
  4524.1    0.05       0  4763.4    0.16       0  4799.0    0.12       0
  4878.5    0.16       0  4989.7    0.07       0  4996.0    0.16       0
  5296.7    0.05       0
Bank Sta=4846,5187.8
Exp/Cntr=0.3,0.1

Type RM Length L Ch R = 1,27363,602,602,602
BEGIN DESCRIPTION:
WEST FORK TURKEY CREEK 29.0
END DESCRIPTION:
XS GIS Cut Line= 3
      2767225.04      7089825.02      2766575.00      7089525.00
      2766270.27      7089488.84
#Sta/Elev= 30
  4302.1  560.46  4331.4  559.95  4436.6  557.31  4505.8  554.35  4558.9  552.45
  4632.6  549.86  4649.2  548.59  4654.6  547.72  4687.6  546.72  4753.7  546.94
  4814.7  545.44  4830.8  545.60  4860.6  547.94  4906.5  544.81  4971.7  545.23
  4996.0  544.68  5000.7  540.23  5001.2  539.43  5006.5  539.43  5007.0  540.23
  5009.3  540.44  5015.3  545.38  5020.5  545.38  5028.1  546.98  5075.8  548.23
  5088.1  548.59  5118.7  549.81  5149.7  549.66  5251.0  551.56  5324.9  552.60
#Mann=9,-1,0
  4302.1    0.05       0  4331.4    0.16       0  4505.8    0.12       0
  4558.9    0.16       0  4971.7    0.12       0  5000.7    0.07       0
  5007.0    0.12       0  5075.8    0.16       0  5251.0    0.05       0
Bank Sta=4649.2,5088.1
Exp/Cntr=0.3,0.1

Type RM Length L Ch R = 1,26761,944,944,944
BEGIN DESCRIPTION:
WEST FORK TURKEY CREEK 28.0
END DESCRIPTION:
XS GIS Cut Line= 3
      2767242.50      7089377.74      2766798.03      7089221.48
      2766075.67      7089510.03
#Sta/Elev= 30
  4506.8  555.27  4535.9  553.94  4556.1  554.72  4561.4  553.83  4578.3  554.25
  4756.0  549.74  4779.6  549.62  4837.0  547.54  4886.3  544.20  4922.5  543.62
  4942.6  544.27  4982.3  543.93  4992.0  542.81  4999.1  540.25  5004.5  542.23
  5010.3  539.33  5010.8  538.53  5016.2  538.53  5016.7  539.33  5023.4  546.55
  5035.0  547.60  5077.2  546.59  5160.8  546.45  5196.6  546.98  5214.6  548.23
  5250.4  547.30  5326.9  547.54  5480.9  550.23  5543.3  551.41  5755.8  552.52
#Mann=8,-1,0
  4506.8    0.16       0  4756.0    0.12       0  4779.6    0.16       0
  4886.3    0.12       0  4942.6    0.16       0  5010.3    0.07       0
  5016.7    0.16       0  5480.9    0.05       0
Bank Sta=4837,5326.9
Exp/Cntr=0.3,0.1

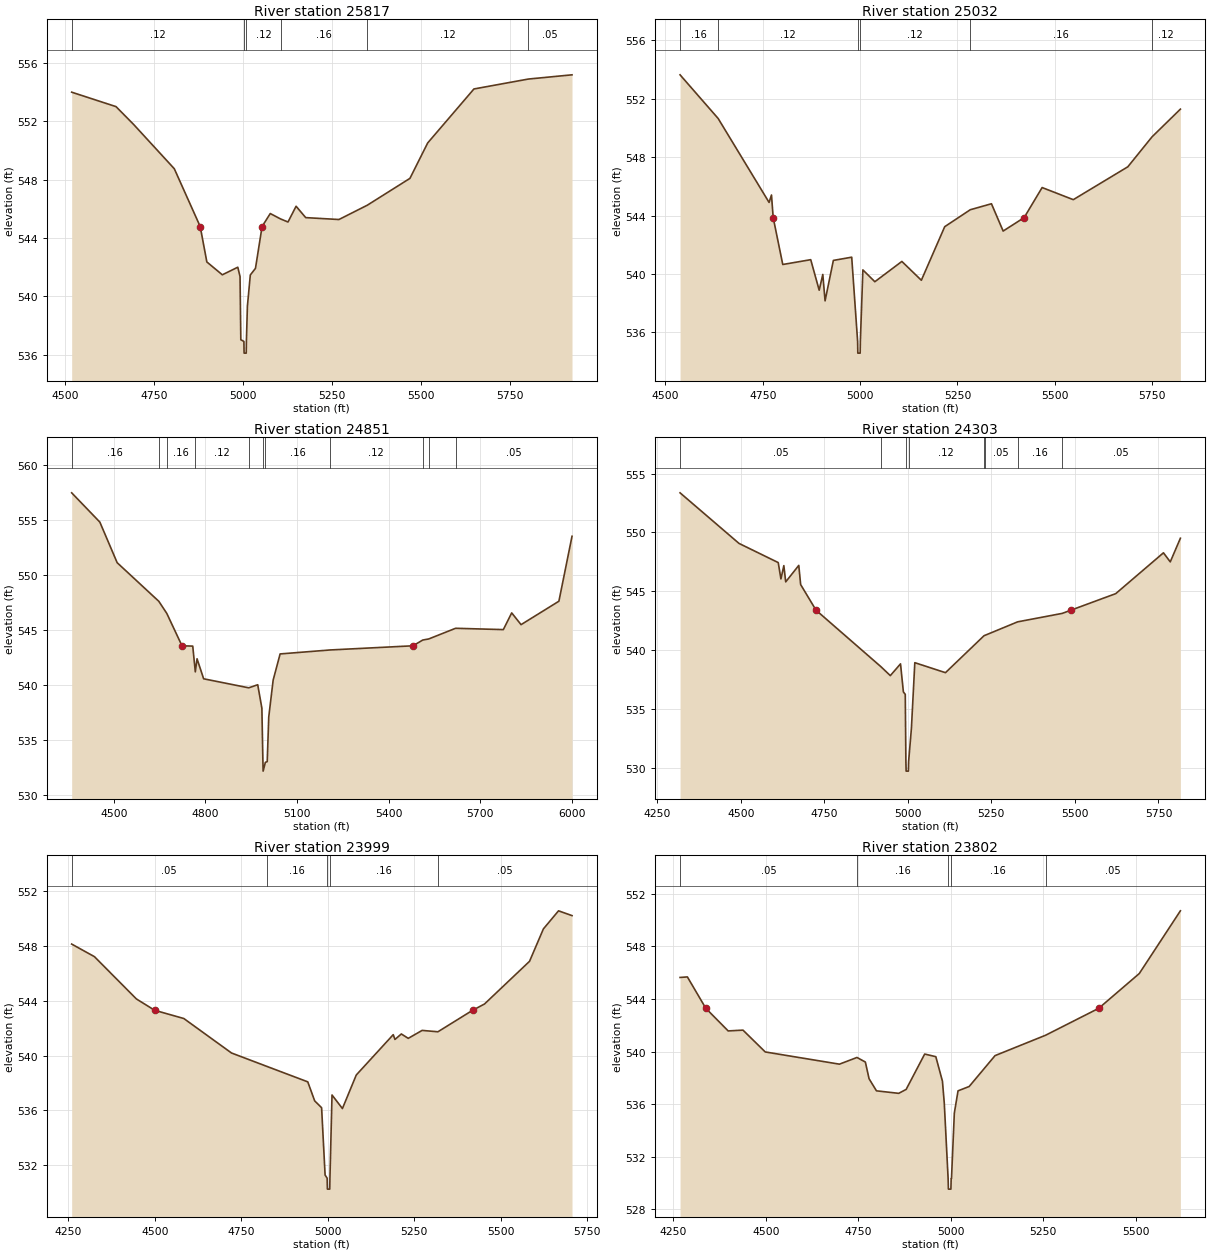
Type RM Length L Ch R = 1,25817,785,785,785
BEGIN DESCRIPTION:
WEST FORK TURKEY CREEK 27.0
END DESCRIPTION:
XS GIS Cut Line= 4
      2767239.01      7089224.96      2766947.34      7088846.48
      2766676.51      7088638.15      2766089.26      7088650.70
#Sta/Elev= 30
  4517.4  553.99  4642.1  553.00  4691.9  551.77  4806.0  548.74  4878.8  544.78
  4897.5  542.35  4941.0  541.47  4984.5  541.99  4990.8  541.35  4993.0  537.02
  5001.7  536.90  5002.2  536.10  5008.2  536.10  5008.7  536.90  5011.5  539.31
  5019.7  541.46  5034.2  541.91  5052.8  544.78  5075.8  545.67  5104.8  545.30
  5125.7  545.09  5148.4  546.17  5175.5  545.39  5268.9  545.26  5348.6  546.24
  5468.5  548.08  5518.5  550.51  5648.5  554.21  5801.5  554.89  5924.3  555.18
#Mann=6,-1,0
  4517.4    0.12       0  5001.7    0.07       0  5008.7    0.12       0
  5104.8    0.16       0  5348.6    0.12       0  5801.5    0.05       0
Bank Sta=4878.8,5052.8
Exp/Cntr=0.3,0.1

Type RM Length L Ch R = 1,25032,181,181,181
BEGIN DESCRIPTION:
Mapping XS ac12d813
END DESCRIPTION:
XS GIS Cut Line= 4
      2767680.40      7088791.87      2767303.64      7088563.24
      2767194.15      7088556.79      2766459.97      7088550.35
#Sta/Elev= 30
  4537.8  553.64  4635.6  550.65  4766.4  544.90  4772.5  545.41  4776.9  543.86
  4801.5  540.65  4873.3  540.98  4895.0  538.89  4904.3  539.97  4910.1  538.16
  4931.4  540.93  4978.5  541.15  4993.7  535.38  4994.2  534.58  5000.2  534.58
  5000.7  535.38  5007.2  540.28  5037.9  539.47  5107.3  540.86  5157.3  539.57
  5217.3  543.24  5282.9  544.40  5337.3  544.81  5367.3  542.94  5421.2  543.86
  5467.4  545.92  5547.4  545.09  5687.4  547.34  5749.5  549.39  5822.4  551.29
#Mann=6,-1,0
  4537.8    0.16       0  4635.6    0.12       0  4993.7    0.07       0
  5000.7    0.12       0  5282.9    0.16       0  5749.5    0.12       0
Bank Sta=4776.9,5421.2
Exp/Cntr=0.3,0.1

Type RM Length L Ch R = 1,24851,548,548,548
BEGIN DESCRIPTION:
WEST FORK TURKEY CREEK 26.0
END DESCRIPTION:
XS GIS Cut Line= 3
      2767824.99      7088825.00      2767353.59      7088395.09
      2766491.11      7087889.38
#Sta/Elev= 30
  4362.3  557.49  4454.5  554.83  4511.2  551.14  4647.6  547.63  4673.7  546.53
  4723.4  543.59  4758.6  543.56  4767.0  541.22  4772.7  542.41  4794.3  540.59
  4941.9  539.77  4971.3  540.05  4984.9  537.92  4988.3  533.00  4989.0  532.20
  4996.3  533.00  5002.4  533.06  5007.4  537.12  5021.8  540.47  5044.6  542.85
  5208.0  543.21  5479.8  543.59  5511.3  544.11  5531.0  544.21  5619.0  545.18
  5775.3  545.06  5802.7  546.58  5833.3  545.51  5957.2  547.64  6000.1  553.54
#Mann=11,-1,0
  4362.3    0.16       0  4647.6    0.12       0  4673.7    0.16       0
  4767.0    0.12       0  4941.9    0.16       0  4988.3    0.07       0
  4996.3    0.16       0  5208.0    0.12       0  5511.3    0.05       0
  5531.0    0.16       0  5619.0    0.05       0
Bank Sta=4723.4,5479.8
Exp/Cntr=0.3,0.1

Type RM Length L Ch R = 1,24303,304,304,304
BEGIN DESCRIPTION:
WEST FORK TURKEY CREEK 25.0
END DESCRIPTION:
XS GIS Cut Line= 3
      2768054.95      7088190.22      2767443.87      7087884.68
      2766645.22      7087728.42
#Sta/Elev= 30
  4318.6  553.36  4494.9  549.06  4612.3  547.43  4620.4  546.04  4629.1  547.17
  4634.7  545.79  4673.8  547.19  4679.4  545.56  4725.5  543.38  4919.9  538.57
  4947.7  537.82  4978.2  538.82  4986.8  536.43  4992.4  536.23  4994.3  530.50
  4995.0  529.70  5001.7  529.70  5002.4  530.50  5010.8  533.33  5021.0  538.92
  5112.7  538.07  5228.0  541.21  5229.7  541.23  5328.5  542.39  5462.0  543.11
  5487.7  543.38  5622.2  544.79  5764.9  548.26  5785.3  547.49  5815.6  549.50
#Mann=8,-1,0
  4318.6    0.05       0  4919.9    0.12       0  4994.3    0.07       0
  5002.4    0.12       0  5228.0    0.16       0  5229.7    0.05       0
  5328.5    0.16       0  5462.0    0.05       0
Bank Sta=4725.5,5487.7
Exp/Cntr=0.3,0.1

Type RM Length L Ch R = 1,23999,197,197,197
BEGIN DESCRIPTION:
WEST FORK TURKEY CREEK 24.0
END DESCRIPTION:
XS GIS Cut Line= 3
      2768048.01      7087884.64      2767839.70      7087606.90
      2766742.48      7087537.45
#Sta/Elev= 30
  4259.8  548.15  4325.6  547.23  4446.9  544.14  4499.8  543.31  4584.0  542.71
  4721.9  540.19  4823.1  539.22  4942.4  538.08  4962.4  536.69  4982.4  536.19
  4992.5  531.27  4998.4  531.04  4999.1  530.24  5005.9  530.24  5006.5  531.04
  5012.5  537.12  5042.6  536.13  5082.6  538.58  5189.5  541.53  5194.5  541.18
  5212.9  541.58  5232.9  541.26  5273.0  541.84  5318.7  541.74  5418.9  543.31
  5453.4  543.77  5583.6  546.89  5623.7  549.26  5667.4  550.58  5706.4  550.23
#Mann=5,-1,0
  4259.8    0.05       0  4823.1    0.16       0  4998.4    0.07       0
  5006.5    0.16       0  5318.7    0.05       0
Bank Sta=4499.8,5418.9
Exp/Cntr=0.3,0.1

Type RM Length L Ch R = 1,23802,667,667,667
BEGIN DESCRIPTION:
WEST FORK TURKEY CREEK 23.0
END DESCRIPTION:
XS GIS Cut Line= 3
      2768214.71      7087454.12      2767485.53      7087398.57
      2766863.97      7087377.73
#Sta/Elev= 30
  4268.1  545.64  4287.9  545.68  4337.8  543.29  4398.2  541.57  4438.3  541.63
  4498.5  539.97  4699.1  539.04  4746.6  539.55  4769.3  539.20  4779.3  537.93
  4799.3  537.01  4859.5  536.82  4879.6  537.12  4929.7  539.81  4959.8  539.61
  4977.7  537.75  4982.7  536.07  4993.1  530.33  4993.8  529.53  5000.6  529.53
  5001.3  530.33  5002.2  530.33  5009.9  535.32  5019.9  537.01  5050.0  537.34
  5120.0  539.69  5256.6  541.24  5400.4  543.29  5510.2  545.94  5621.3  550.71
#Mann=5,-1,0
  4268.1    0.05       0  4746.6    0.16       0  4993.1    0.07       0
  5001.3    0.16       0  5256.6    0.05       0
Bank Sta=4337.8,5400.4
Exp/Cntr=0.3,0.1

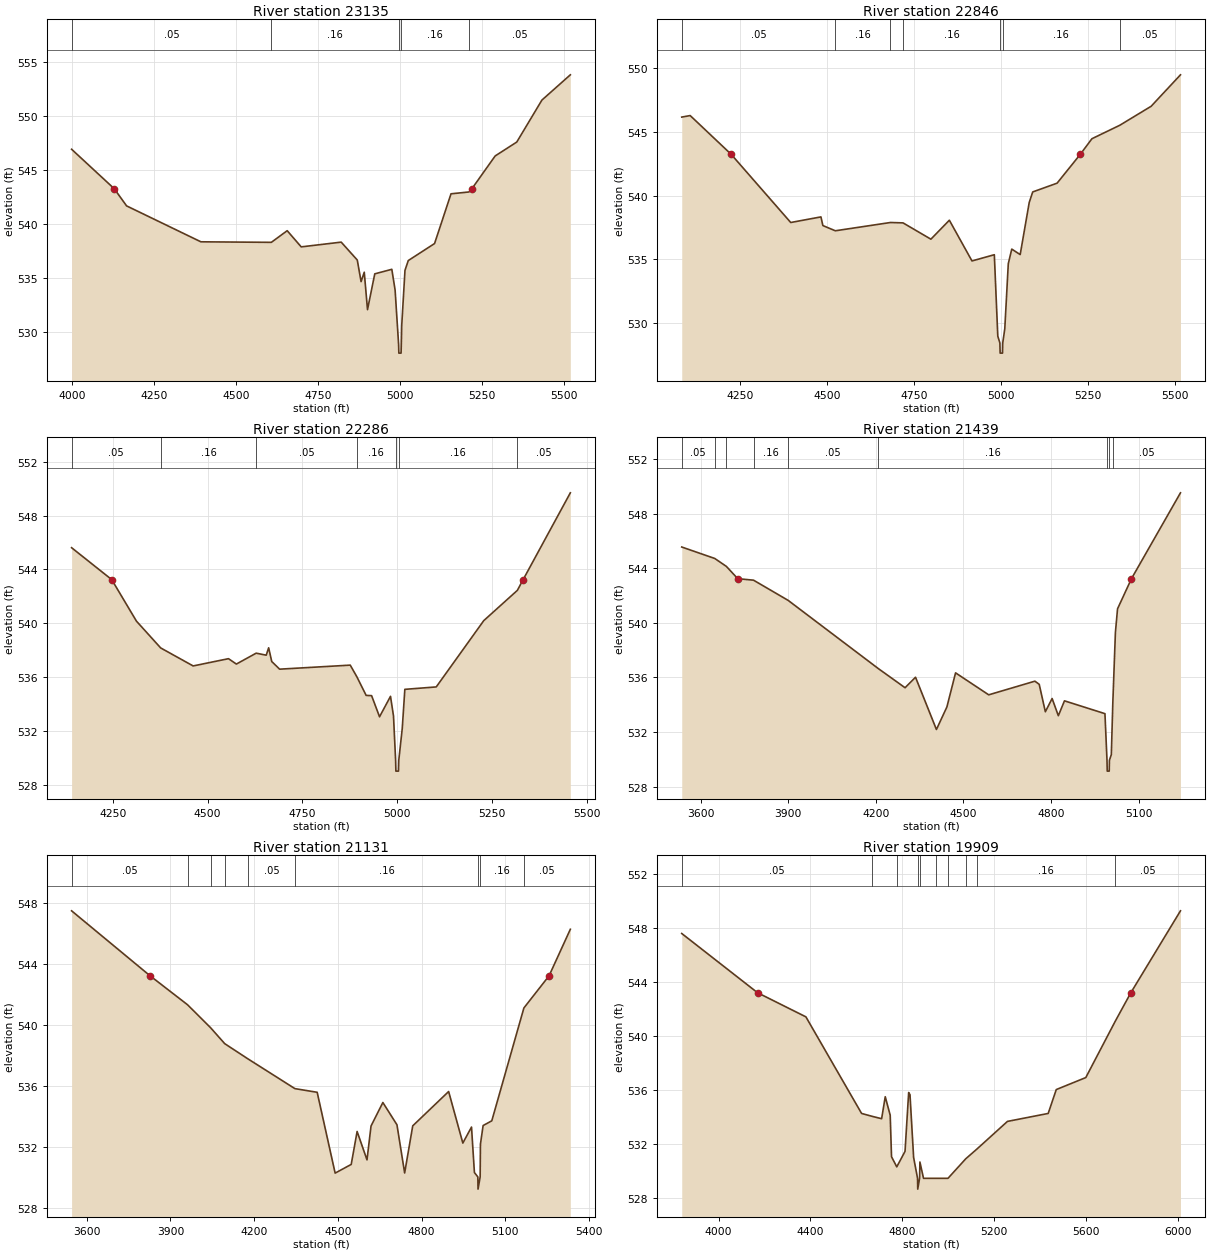
Type RM Length L Ch R = 1,23135,289,289,289
BEGIN DESCRIPTION:
Mapping XS 06bbac6e
END DESCRIPTION:
XS GIS Cut Line= 3
      2768360.54      7087327.39      2767466.44      7086993.18
      2766902.21      7086954.12
#Sta/Elev= 30
  3998.1  546.92  4128.1  543.26  4165.7  541.67  4392.1  538.34  4606.9  538.29
  4655.2  539.37  4697.9  537.87  4819.8  538.31  4868.8  536.65  4880.4  534.65
  4890.1  535.52  4900.0  532.05  4922.1  535.37  4974.1  535.79  4984.1  533.87
  4994.8  528.82  4995.5  528.02  5002.3  528.02  5003.0  528.82  5004.2  530.54
  5014.2  535.69  5024.2  536.60  5104.4  538.18  5154.5  542.79  5209.2  542.96
  5218.2  543.26  5289.1  546.30  5355.0  547.59  5431.6  551.48  5518.2  553.82
#Mann=5,-1,0
  3998.1    0.05       0  4606.9    0.16       0  4994.8    0.07       0
  5003.0    0.16       0  5209.2    0.05       0
Bank Sta=4128.1,5218.2
Exp/Cntr=0.3,0.1

Type RM Length L Ch R = 1,22846,560,560,560
BEGIN DESCRIPTION:
Mapping XS af9f98e0
END DESCRIPTION:
XS GIS Cut Line= 4
      2768373.52      7087119.04      2767557.58      7086771.83
      2767466.44      7086780.51      2767010.75      7086810.89
#Sta/Elev= 30
  4081.0  546.17  4105.3  546.29  4223.1  543.25  4394.6  537.89  4481.5  538.33
  4487.1  537.65  4522.9  537.24  4681.5  537.89  4717.7  537.86  4797.9  536.58
  4851.0  538.07  4916.1  534.87  4980.4  535.36  4990.4  528.96  4996.4  528.43
  4997.1  527.63  5003.9  527.63  5004.6  528.43  5010.5  529.54  5020.6  534.66
  5030.6  535.80  5054.8  535.37  5080.8  539.46  5090.8  540.29  5161.0  540.98
  5227.9  543.25  5261.2  544.47  5341.5  545.53  5431.6  547.02  5516.0  549.49
#Mann=7,-1,0
  4081.0    0.05       0  4522.9    0.16       0  4681.5    0.05       0
  4717.7    0.16       0  4996.4    0.07       0  5004.6    0.16       0
  5341.5    0.05       0
Bank Sta=4223.1,5227.9
Exp/Cntr=0.3,0.1

Type RM Length L Ch R = 1,22286,847,847,847
BEGIN DESCRIPTION:
WEST FORK TURKEY CREEK 22.0
END DESCRIPTION:
XS GIS Cut Line= 3
      2768325.01      7087025.01      2767647.36      7086498.24
      2767225.01      7086325.01
#Sta/Elev= 30
  4141.7  545.61  4247.4  543.24  4312.7  540.15  4376.5  538.16  4462.1  536.82
  4555.3  537.36  4576.1  536.96  4628.3  537.77  4654.8  537.62  4661.2  538.17
  4669.3  537.15  4690.1  536.58  4876.3  536.88  4893.6  536.02  4918.2  534.63
  4932.6  534.61  4953.5  533.04  4982.4  534.56  4990.3  533.10  4995.9  529.80
  4996.6  529.00  5003.4  529.00  5004.2  529.80  5013.4  532.18  5020.2  535.08
  5103.0  535.26  5228.3  540.19  5316.9  542.44  5332.1  543.24  5456.5  549.69
#Mann=7,-1,0
  4141.7    0.05       0  4376.5    0.16       0  4628.3    0.05       0
  4893.6    0.16       0  4995.9    0.07       0  5004.2    0.16       0
  5316.9    0.05       0
Bank Sta=4247.4,5332.1
Exp/Cntr=0.3,0.1

Type RM Length L Ch R = 1,21439,308,308,308
BEGIN DESCRIPTION:
Mapping XS ff2b4ffe
END DESCRIPTION:
XS GIS Cut Line= 3
      2768737.16      7086906.55      2767622.69      7086133.81
      2767292.83      7086012.28
#Sta/Elev= 30
  3535.4  545.55  3648.5  544.71  3688.2  544.13  3727.2  543.23  3781.2  543.12
  3899.8  541.64  4208.7  536.64  4300.1  535.24  4335.9  536.01  4407.5  532.18
  4443.3  533.83  4473.0  536.33  4586.5  534.72  4744.6  535.72  4759.4  535.49
  4780.4  533.48  4803.6  534.45  4824.9  533.19  4845.9  534.28  4984.5  533.34
  4991.5  529.93  4992.3  529.13  4999.1  529.13  4999.8  529.93  5006.3  530.34
  5011.5  534.16  5020.3  539.29  5027.6  541.02  5075.3  543.23  5243.1  549.52
#Mann=9,-1,0
  3535.4    0.05       0  3648.5    0.16       0  3688.2    0.05       0
  3781.2    0.16       0  3899.8    0.05       0  4208.7    0.16       0
  4991.5    0.07       0  4999.8    0.16       0  5011.5    0.05       0
Bank Sta=3727.2,5075.3
Exp/Cntr=0.3,0.1

Type RM Length L Ch R = 1,21131,1222,1222,1222
BEGIN DESCRIPTION:
Mapping XS 74c5d538
END DESCRIPTION:
XS GIS Cut Line= 3
      2768869.96      7086804.97      2767770.26      7085960.20
      2767383.93      7085851.68
#Sta/Elev= 30
  3545.6  547.48  3826.9  543.22  3961.3  541.32  4044.1  539.81  4094.5  538.77
  4177.1  537.78  4346.2  535.82  4426.0  535.58  4490.4  530.28  4548.0  530.85
  4569.2  533.01  4604.6  531.15  4619.1  533.37  4661.5  534.91  4712.0  533.45
  4739.6  530.29  4768.6  533.38  4897.3  535.63  4948.2  532.25  4979.3  533.30
  4989.7  530.32  5002.0  530.03  5002.7  529.23  5010.3  530.03  5011.3  532.18
  5020.9  533.40  5052.0  533.71  5167.1  541.11  5257.4  543.22  5333.6  546.27
#Mann=9,-1,0
  3545.6    0.05       0  3961.3    0.16       0  4044.1    0.05       0
  4094.5    0.16       0  4177.1    0.05       0  4346.2    0.16       0
  5002.0    0.07       0  5010.3    0.16       0  5167.1    0.05       0
Bank Sta=3826.9,5257.4
Exp/Cntr=0.3,0.1

Type RM Length L Ch R = 1,19909,557,557,557
BEGIN DESCRIPTION:
WEST FORK TURKEY CREEK 19.0
END DESCRIPTION:
XS GIS Cut Line= 3
      2768945.49      7086763.32      2768375.00      7085775.00
      2767575.03      7085125.02
#Sta/Elev= 30
  3839.5  547.61  4169.6  543.22  4380.2  541.43  4622.7  534.27  4670.1  534.05
  4710.0  533.88  4725.7  535.51  4747.3  534.14  4753.1  531.06  4775.9  530.31
  4811.9  531.46  4827.7  535.82  4833.5  535.66  4849.3  531.01  4866.4  529.46
  4867.2  528.66  4875.3  529.46  4876.7  530.67  4892.4  529.46  4948.8  529.46
  4998.9  529.46  5076.4  530.91  5124.2  531.62  5257.9  533.68  5435.3  534.27
  5470.5  536.04  5599.1  536.93  5727.5  541.11  5795.3  543.22  6011.4  549.29
#Mann=10,-1,0
  3839.5    0.05       0  4670.1    0.16       0  4775.9    0.05       0
  4866.4   0.033       0  4875.3    0.05       0  4948.8    0.07       0
  4998.9    0.05       0  5076.4    0.12       0  5124.2    0.16       0
  5727.5    0.05       0
Bank Sta=4169.6,5795.3
Exp/Cntr=0.3,0.1

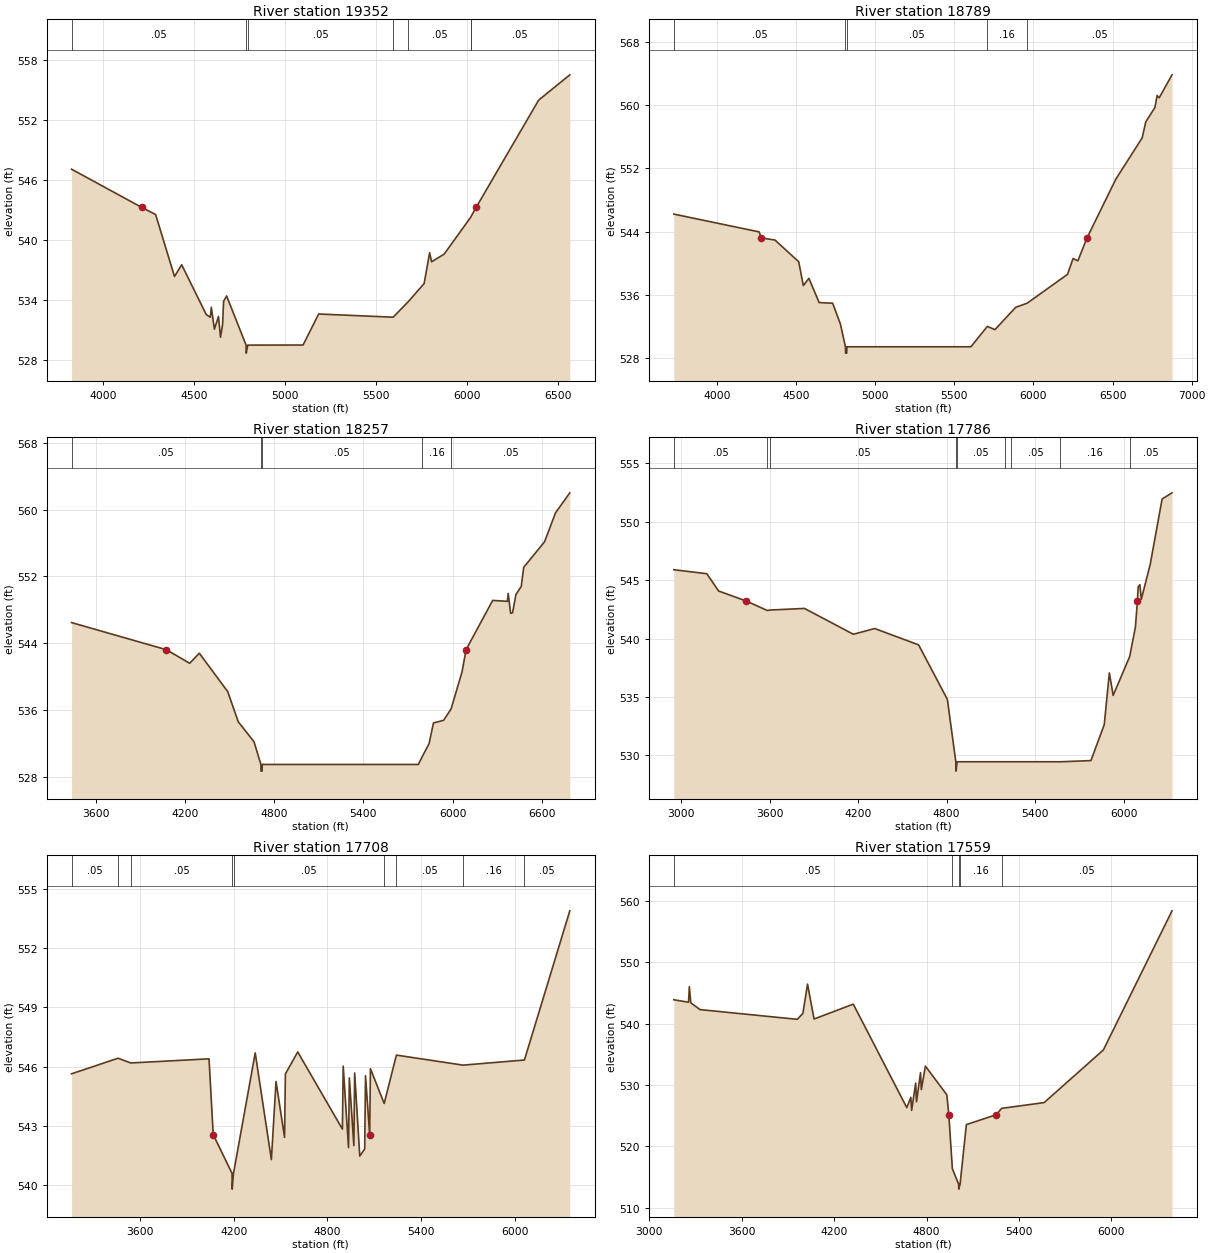
Type RM Length L Ch R = 1,19352,563,563,563
BEGIN DESCRIPTION:
WEST FORK TURKEY CREEK 18.0
END DESCRIPTION:
XS GIS Cut Line= 3
      2769789.24      7085898.74      2768725.00      7085375.00
      2767275.04      7084825.01
#Sta/Elev= 30
  3826.3  547.04  4211.9  543.22  4288.0  542.51  4391.7  536.32  4431.1  537.49
  4565.9  532.52  4588.4  532.25  4594.0  533.24  4610.9  531.05  4633.3  532.33
  4644.6  530.25  4655.8  531.51  4661.4  533.84  4678.1  534.37  4785.0  529.46
  4785.8  528.66  4794.1  529.46  5098.0  529.47  5183.6  532.57  5592.8  532.25
  5675.3  533.79  5763.0  535.61  5793.2  538.69  5803.9  537.79  5872.9  538.55
  6018.9  542.24  6019.5  542.27  6048.6  543.22  6392.1  553.94  6563.2  556.47
#Mann=7,-1,0
  3826.3    0.05       0  4785.0   0.033       0  4794.1    0.05       0
  5592.8    0.16       0  5675.3    0.05       0  6018.9    0.16       0
  6019.5    0.05       0
Bank Sta=4211.9,6048.6
Exp/Cntr=0.3,0.1

Type RM Length L Ch R = 1,18789,532,532,532
BEGIN DESCRIPTION:
WEST FORK TURKEY CREEK 17.0
END DESCRIPTION:
XS GIS Cut Line= 3
      2769932.46      7085633.10      2768925.00      7084875.00
      2767325.03      7083875.02
#Sta/Elev= 30
  3728.3  546.23  4267.6  543.98  4281.4  543.22  4367.6  542.95  4517.5  540.21
  4546.6  537.20  4582.0  538.11  4646.6  535.05  4732.0  534.97  4781.2  532.32
  4812.8  529.46  4813.6  528.66  4821.0  528.66  4821.9  529.46  5605.3  529.46
  5709.3  532.04  5757.4  531.63  5888.3  534.45  5960.7  534.97  6215.6  538.61
  6250.9  540.62  6281.0  540.32  6338.9  543.22  6521.6  550.67  6687.3  555.86
  6710.2  557.89  6768.0  559.70  6781.6  561.21  6795.2  560.93  6875.9  563.83
#Mann=5,-1,0
  3728.3    0.05       0  4812.8   0.033       0  4821.9    0.05       0
  5709.3    0.16       0  5960.7    0.05       0
Bank Sta=4281.4,6338.9
Exp/Cntr=0.3,0.1

Type RM Length L Ch R = 1,18257,471,471,471
BEGIN DESCRIPTION:
WEST FORK TURKEY CREEK 16.0
END DESCRIPTION:
XS GIS Cut Line= 3
      2770067.90      7085552.39      2769075.00      7084375.00
      2767475.02      7083525.01
#Sta/Elev= 30
  3437.2  546.47  4074.9  543.22  4231.7  541.59  4296.6  542.80  4487.8  538.19
  4558.8  534.57  4664.7  532.18  4710.8  529.46  4711.6  528.66  4719.0  528.66
  4719.9  529.46  5770.0  529.46  5796.1  530.39  5842.1  531.94  5871.9  534.44
  5939.9  534.75  5990.6  536.12  6064.4  540.58  6091.2  543.22  6270.4  549.13
  6369.0  549.02  6374.7  549.97  6391.0  547.58  6404.1  547.65  6426.8  549.83
  6462.6  550.81  6478.9  553.09  6619.3  556.16  6693.0  559.63  6789.1  562.03
#Mann=5,-1,0
  3437.2    0.05       0  4710.8   0.033       0  4719.9    0.05       0
  5796.1    0.16       0  5990.6    0.05       0
Bank Sta=4074.9,6091.2
Exp/Cntr=0.3,0.1

Type RM Length L Ch R = 1,17786,78,78,78
BEGIN DESCRIPTION:
Mapping XS 313dc427
END DESCRIPTION:
XS GIS Cut Line= 6
      2770073.10      7085458.63      2770057.58      7084783.98
      2770005.50      7084345.61      2769823.21      7084089.54
      2768573.21      7083742.32      2767928.22      7083677.38
#Sta/Elev= 30
  2951.1  545.89  3174.8  545.55  3254.8  544.07  3440.6  543.22  3585.4  542.40
  3601.7  542.44  3836.4  542.58  4167.8  540.37  4312.9  540.86  4610.1  539.46
  4805.0  534.80  4862.2  529.46  4863.1  528.66  4871.5  529.46  5193.5  529.46
  5235.5  529.46  5568.7  529.46  5777.8  529.56  5868.2  532.64  5902.6  537.06
  5928.5  535.14  6040.6  538.47  6079.3  540.99  6092.9  543.22  6097.9  544.42
  6109.4  544.61  6119.5  543.37  6179.8  546.36  6260.2  551.94  6327.3  552.47
#Mann=9,-1,0
  2951.1    0.05       0  3585.4    0.08       0  3601.7    0.05       0
  4862.2   0.033       0  4871.5    0.05       0  5193.5    0.16       0
  5235.5    0.05       0  5568.7    0.16       0  6040.6    0.05       0
Bank Sta=3440.6,6092.9
Exp/Cntr=0.3,0.1

Type RM Length L Ch R = 1,17708,149,149,149
BEGIN DESCRIPTION:
Mapping XS 47f59a6f
END DESCRIPTION:
XS GIS Cut Line= 6
      2770127.03      7085165.89      2770144.39      7084770.96
      2770061.92      7084310.89      2769910.01      7084067.84
      2768586.23      7083646.83      2767935.19      7083625.13
#Sta/Elev= 30
  3161.1  545.63  3458.8  546.42  3540.7  546.18  4041.5  546.39  4068.4  542.54
  4189.0  540.57  4189.8  539.77  4198.3  540.57  4337.4  546.69  4440.9  541.27
  4470.8  545.24  4525.3  542.40  4530.6  545.62  4609.7  546.74  4895.8  542.82
  4901.0  546.02  4935.1  541.88  4940.3  545.42  4969.2  541.98  4974.4  545.67
  5007.1  541.45  5038.6  541.81  5043.9  545.53  5070.5  542.54  5075.4  545.89
  5163.5  544.12  5241.7  546.58  5668.5  546.07  6061.8  546.33  6352.4  553.91
#Mann=9,-1,0
  3161.1    0.05       0  3458.8    0.08       0  3540.7    0.05       0
  4189.0    0.03       0  4198.3    0.05       0  5163.5    0.16       0
  5241.7    0.05       0  5668.5    0.16       0  6061.8    0.05       0
Bank Sta=4068.4,5070.5
Exp/Cntr=0.3,0.1

Type RM Length L Ch R = 1,17559,276,276,276
BEGIN DESCRIPTION:
Mapping XS 965e97f5
END DESCRIPTION:
XS GIS Cut Line= 6
      2770193.87      7085065.27      2770163.49      7084310.02
      2769959.49      7083997.52      2769633.97      7083823.91
      2768835.36      7083554.82      2767950.02      7083476.69
#Sta/Elev= 30
  3160.5  543.89  3256.3  543.48  3261.3  546.02  3270.9  543.38  3330.9  542.28
  3961.7  540.70  3997.9  541.66  4028.2  546.43  4070.4  540.75  4324.9  543.17
  4672.0  526.32  4698.2  528.00  4703.5  525.88  4729.7  530.32  4734.9  527.28
  4761.2  532.02  4766.4  529.26  4792.6  533.08  4931.7  528.42  4944.6  525.18
  4967.6  516.39  5008.4  513.86  5009.2  513.06  5017.7  513.86  5058.4  523.56
  5253.4  525.18  5287.2  526.21  5562.8  527.14  5947.3  535.71  6392.6  558.36
#Mann=5,-1,0
  3160.5    0.05       0  4967.6    0.16       0  5008.4    0.07       0
  5017.7    0.16       0  5287.2    0.05       0
Bank Sta=4944.6,5253.4
Exp/Cntr=0.3,0.1