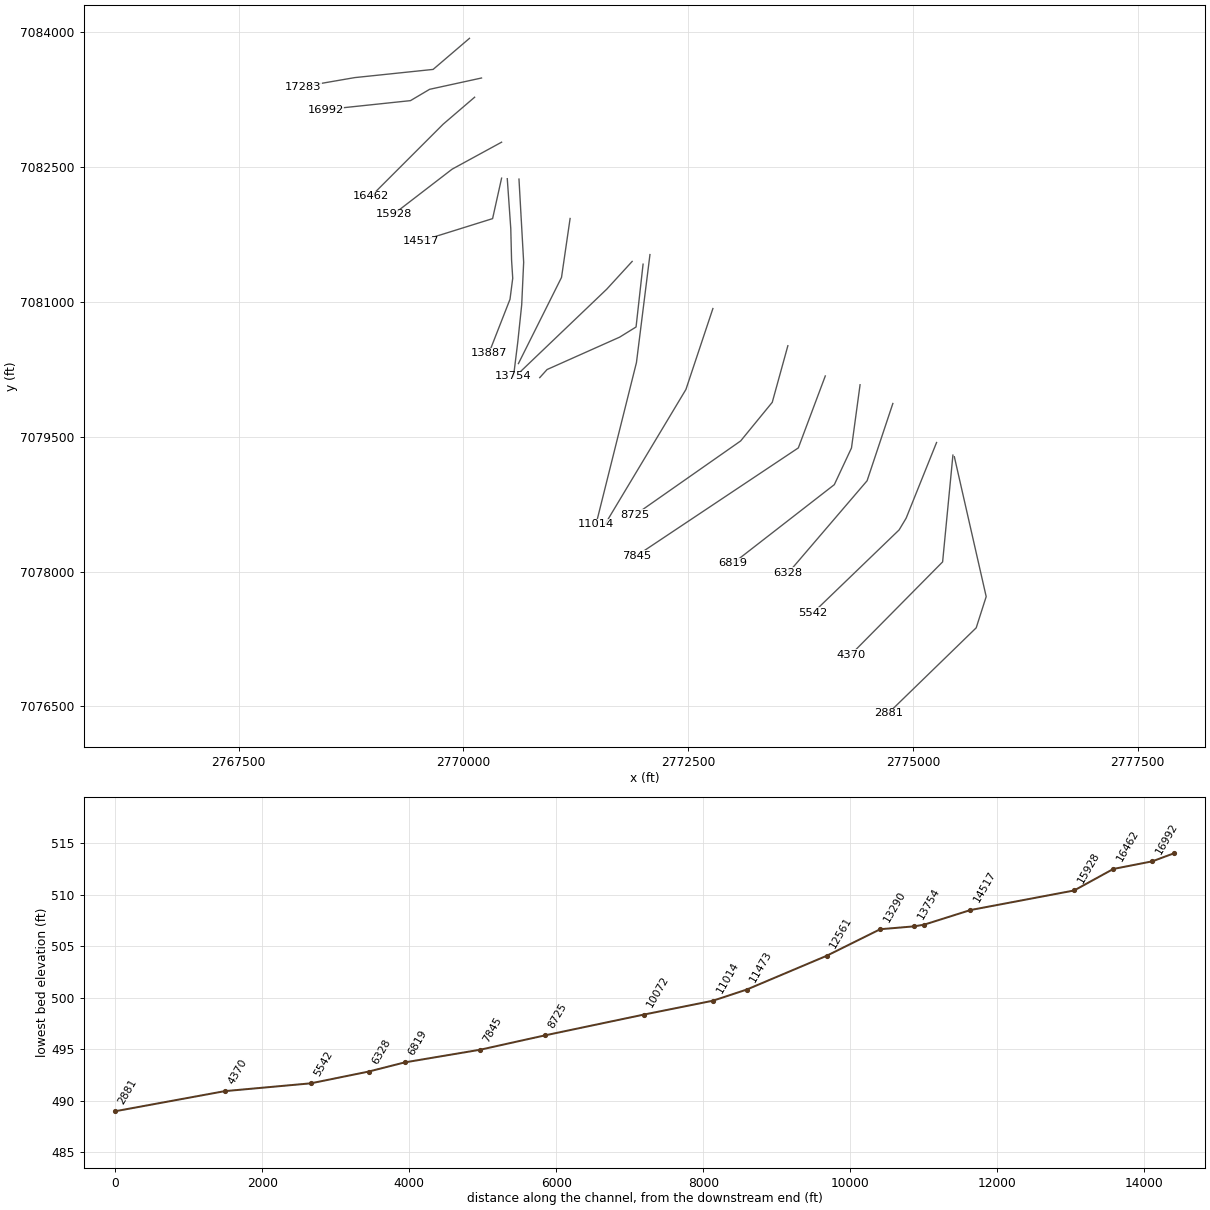
HEC-RAS study WEST FORK TURKEY CREEK.prj: WEST FORK TURKEY CREEK Base Level Engineering

--- WEST FORK TURKEY CREEK.g01 (geometry) --- (continued)

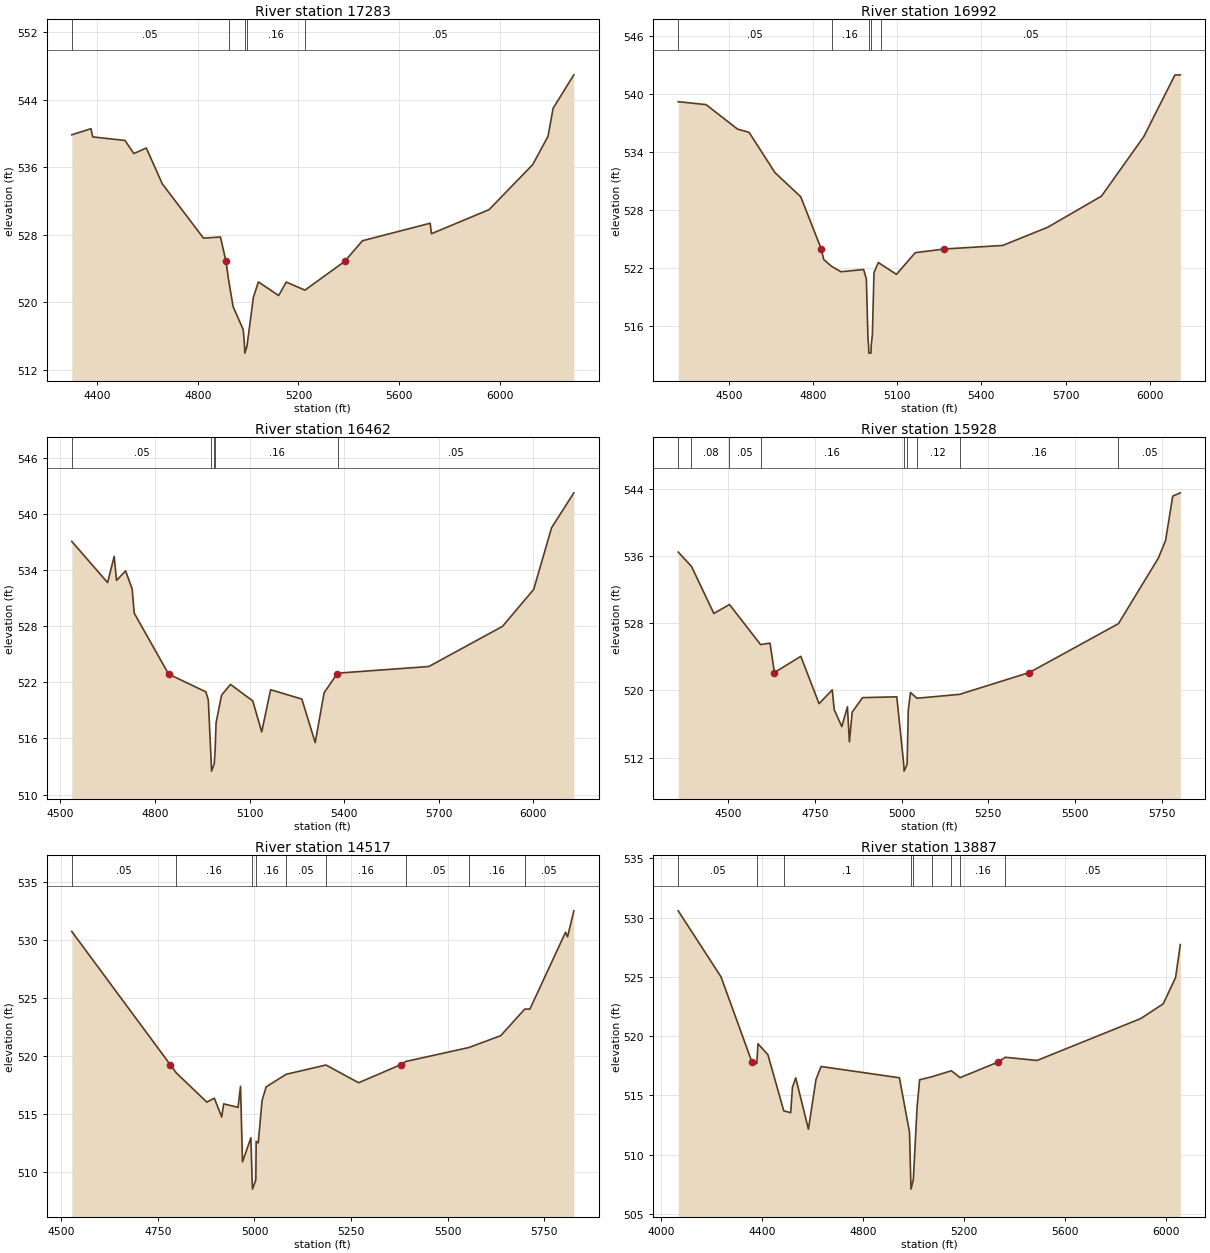
Type RM Length L Ch R = 1,17283,291,291,291
BEGIN DESCRIPTION:
Mapping XS b4f25507
END DESCRIPTION:
XS GIS Cut Line= 4
      2770067.86      7083929.96      2769663.49      7083584.33
      2768791.09      7083493.18      2768213.86      7083393.36
#Sta/Elev= 30
  4299.2  539.83  4375.7  540.55  4382.3  539.58  4510.7  539.16  4545.9  537.61
  4595.3  538.27  4658.9  534.03  4822.5  527.61  4890.0  527.74  4912.0  524.85
  4922.0  522.73  4940.2  519.51  4980.5  516.79  4985.8  514.81  4986.7  514.01
  4995.2  514.81  5020.7  520.59  5040.8  522.43  5121.2  520.82  5151.4  522.41
  5225.7  521.46  5383.3  524.85  5454.1  527.30  5723.3  529.37  5728.3  528.13
  5957.3  530.98  6130.6  536.30  6191.4  539.64  6211.8  542.97  6294.1  546.92
#Mann=5,-1,0
  4299.2    0.05       0  4922.0    0.16       0  4985.8    0.07       0
  4995.2    0.16       0  5225.7    0.05       0
Bank Sta=4912,5383.3
Exp/Cntr=0.3,0.1

Type RM Length L Ch R = 1,16992,530,530,530
BEGIN DESCRIPTION:
Mapping XS ccd89287
END DESCRIPTION:
XS GIS Cut Line= 4
      2770201.71      7083488.85      2769624.42      7083362.97
      2769411.75      7083237.11      2768465.58      7083137.28
#Sta/Elev= 30
  4319.4  539.25  4418.4  538.95  4531.0  536.41  4571.9  536.08  4664.0  531.92
  4756.1  529.41  4829.2  524.01  4838.0  522.92  4865.9  522.22  4899.4  521.66
  4980.1  521.89  4989.9  520.92  4995.7  514.71  4997.8  514.04  4998.7  513.24
  5006.3  513.24  5007.2  514.04  5011.3  515.15  5017.1  521.58  5032.7  522.62
  5042.5  522.42  5097.1  521.39  5164.2  523.63  5266.8  524.01  5475.9  524.38
  5636.8  526.27  5827.8  529.48  5978.7  535.64  6089.3  542.00  6108.8  542.03
#Mann=5,-1,0
  4319.4    0.05       0  4865.9    0.16       0  4997.8    0.07       0
  5007.2    0.16       0  5042.5    0.05       0
Bank Sta=4829.2,5266.8
Exp/Cntr=0.3,0.1

Type RM Length L Ch R = 1,16462,534,534,534
BEGIN DESCRIPTION:
WEST FORK TURKEY CREEK 13.0
END DESCRIPTION:
XS GIS Cut Line= 3
      2770125.01      7083275.01      2769775.00      7082975.00
      2768974.97      7082174.97
#Sta/Elev= 30
  4536.0  537.05  4649.6  532.65  4670.5  535.45  4678.1  532.88  4706.7  533.90
  4727.5  531.97  4734.1  529.38  4843.1  522.87  4961.3  520.97  4969.0  520.12
  4978.5  513.30  4979.4  512.50  4988.0  513.30  4990.8  514.82  4993.7  517.66
  5011.1  520.61  5039.4  521.77  5110.1  520.00  5138.4  516.69  5166.7  521.20
  5265.7  520.20  5308.1  515.55  5336.4  520.88  5377.1  522.87  5379.6  522.97
  5668.7  523.68  5902.1  527.97  6001.1  531.92  6057.7  538.50  6128.4  542.24
#Mann=5,-1,0
  4536.0    0.05       0  4978.5    0.07       0  4988.0    0.05       0
  4990.8    0.16       0  5379.6    0.05       0
Bank Sta=4843.1,5377.1
Exp/Cntr=0.3,0.1

Type RM Length L Ch R = 1,15928,1411,1411,1411
BEGIN DESCRIPTION:
WEST FORK TURKEY CREEK 12.0
END DESCRIPTION:
XS GIS Cut Line= 3
      2770425.03      7082775.02      2769875.00      7082475.00
      2769225.00      7081975.00
#Sta/Elev= 30
  4356.7  536.46  4394.9  534.76  4459.3  529.16  4504.3  530.23  4594.0  525.46
  4621.1  525.63  4633.9  522.14  4709.9  524.06  4762.5  518.43  4800.5  520.08
  4806.2  517.71  4828.0  515.71  4844.2  518.06  4849.9  513.89  4857.9  517.43
  4887.8  519.15  4986.4  519.25  5006.5  511.21  5007.5  510.41  5016.1  511.21
  5019.5  517.65  5025.8  519.76  5044.4  519.08  5167.2  519.54  5368.5  522.14
  5625.1  527.95  5739.9  535.74  5760.7  537.81  5781.5  543.12  5803.3  543.51
#Mann=9,-1,0
  4356.7    0.05       0  4394.9    0.08       0  4504.3    0.05       0
  4594.0    0.16       0  5006.5    0.07       0  5016.1    0.16       0
  5044.4    0.12       0  5167.2    0.16       0  5625.1    0.05       0
Bank Sta=4633.9,5368.5
Exp/Cntr=0.3,0.1

Type RM Length L Ch R = 1,14517,630,630,630
BEGIN DESCRIPTION:
WEST FORK TURKEY CREEK 10.0
END DESCRIPTION:
XS GIS Cut Line= 3
      2770425.01      7082375.02      2770325.00      7081925.00
      2769524.96      7081674.99
#Sta/Elev= 30
  4527.2  530.72  4781.8  519.25  4798.2  518.51  4876.8  516.01  4896.0  516.35
  4915.2  514.73  4920.3  515.86  4957.5  515.56  4963.9  517.37  4969.0  510.86
  4990.8  512.94  4993.9  509.31  4994.8  508.51  5003.5  509.31  5004.4  512.63
  5009.7  512.49  5019.6  516.14  5030.1  517.32  5081.9  518.41  5184.9  519.21
  5269.5  517.68  5379.3  519.25  5391.0  519.51  5555.2  520.72  5637.2  521.74
  5699.4  524.03  5712.7  524.03  5804.9  530.65  5810.1  530.26  5826.4  532.50
#Mann=9,-1,0
  4527.2    0.05       0  4798.2    0.16       0  4993.9    0.07       0
  5003.5    0.16       0  5081.9    0.05       0  5184.9    0.16       0
  5391.0    0.05       0  5555.2    0.16       0  5699.4    0.05       0
Bank Sta=4781.8,5379.3
Exp/Cntr=0.3,0.1

Type RM Length L Ch R = 1,13887,133,133,133
BEGIN DESCRIPTION:
Mapping XS 742324f8
END DESCRIPTION:
XS GIS Cut Line= 6
      2770488.14      7082369.09      2770527.20      7081813.50
      2770535.88      7081466.27      2770548.90      7081262.28
      2770518.52      7081027.91      2770284.34      7080429.43
#Sta/Elev= 30
  4068.6  530.58  4237.9  525.01  4360.7  517.80  4379.5  517.69  4384.4  519.36
  4423.6  518.44  4486.3  513.70  4513.8  513.54  4520.8  515.69  4533.8  516.48
  4584.0  512.15  4614.0  516.35  4634.1  517.44  4944.2  516.49  4984.2  511.90
  4989.1  507.89  4990.1  507.09  4999.3  507.89  5014.3  514.04  5024.3  516.32
  5073.3  516.58  5150.0  517.08  5184.5  516.50  5333.1  517.80  5363.5  518.22
  5489.2  517.95  5899.1  521.48  5988.6  522.73  6037.5  524.94  6056.3  527.73
#Mann=9,-1,0
  4068.6    0.05       0  4379.5    0.16       0  4486.3     0.1       0
  4989.1    0.07       0  4999.3     0.1       0  5073.3    0.16       0
  5150.0    0.05       0  5184.5    0.16       0  5363.5    0.05       0
Bank Sta=4360.7,5333.1
Exp/Cntr=0.3,0.1

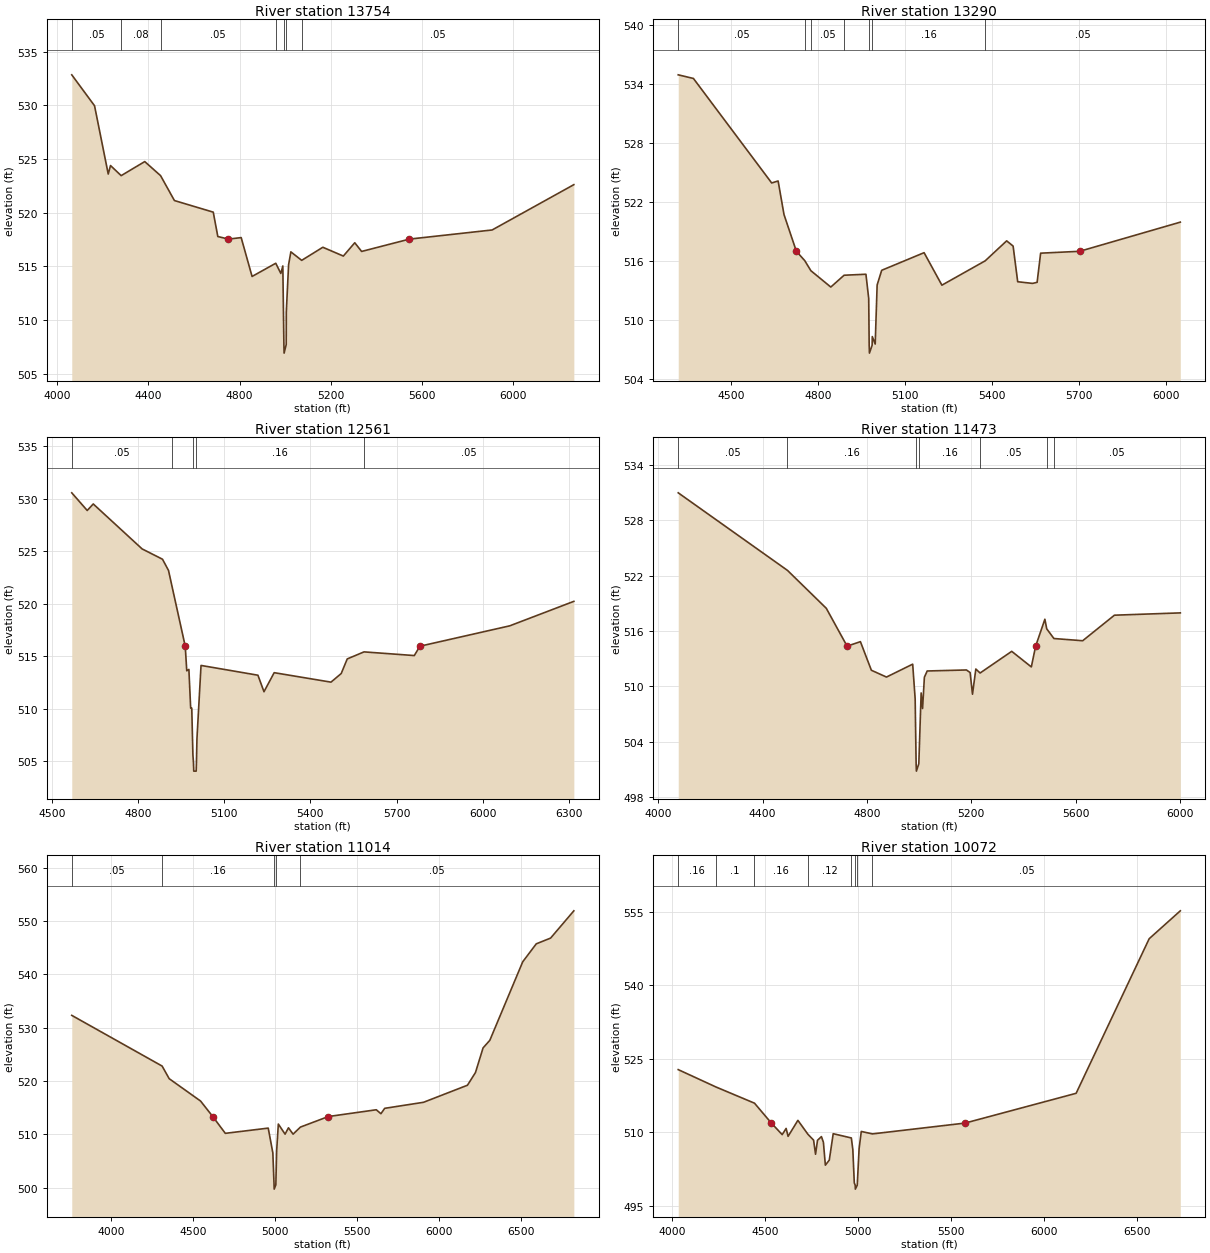
Type RM Length L Ch R = 1,13754,464,464,464
BEGIN DESCRIPTION:
Mapping XS 5d95e436
END DESCRIPTION:
XS GIS Cut Line= 5
      2770618.35      7082364.70      2770670.43      7081440.23
      2770648.73      7080967.14      2770605.33      7080554.82
      2770557.68      7080169.27
#Sta/Elev= 30
  4063.9  532.85  4163.8  529.97  4223.9  523.61  4233.9  524.40  4280.6  523.46
  4384.1  524.77  4453.5  523.46  4514.3  521.14  4684.6  520.06  4704.6  517.79
  4751.4  517.55  4807.1  517.69  4854.9  514.07  4958.8  515.30  4981.1  514.35
  4989.8  515.05  4994.5  507.73  4995.4  506.93  5004.7  507.73  5005.1  510.77
  5015.1  515.16  5025.1  516.36  5072.6  515.57  5165.3  516.79  5255.3  515.97
  5305.4  517.21  5335.4  516.40  5545.4  517.55  5908.1  518.40  6266.5  522.62
#Mann=7,-1,0
  4063.9    0.05       0  4280.6    0.08       0  4453.5    0.05       0
  4958.8    0.16       0  4994.5    0.07       0  5004.7    0.16       0
  5072.6    0.05       0
Bank Sta=4751.4,5545.4
Exp/Cntr=0.3,0.1

Type RM Length L Ch R = 1,13290,729,729,729
BEGIN DESCRIPTION:
Mapping XS 8d71bce4
END DESCRIPTION:
XS GIS Cut Line= 3
      2771186.92      7081926.34      2771091.44      7081270.96
      2770612.18      7080312.84
#Sta/Elev= 30
  4317.3  534.91  4369.8  534.54  4639.9  523.93  4662.2  524.13  4682.5  520.72
  4725.2  516.99  4754.2  516.04  4775.3  515.02  4844.1  513.36  4890.0  514.56
  4965.4  514.66  4975.0  512.19  4976.6  507.45  4977.5  506.65  4986.8  507.45
  4987.3  508.33  4997.4  507.57  5004.1  513.57  5019.8  515.06  5166.2  516.85
  5227.7  513.55  5377.1  516.02  5451.3  518.05  5473.6  517.52  5489.4  513.90
  5540.7  513.73  5556.5  513.84  5568.6  516.80  5703.4  516.99  6050.9  519.95
#Mann=7,-1,0
  4317.3    0.05       0  4754.2    0.16       0  4775.3    0.05       0
  4890.0    0.16       0  4976.6    0.07       0  4986.8    0.16       0
  5377.1    0.05       0
Bank Sta=4725.2,5703.4
Exp/Cntr=0.3,0.1

Type RM Length L Ch R = 1,12561,1088,1088,1088
BEGIN DESCRIPTION:
Mapping XS 7094d62b
END DESCRIPTION:
XS GIS Cut Line= 3
      2771877.04      7081448.92      2771594.91      7081140.75
      2770633.02      7080221.68
#Sta/Elev= 30
  4569.3  530.56  4623.1  528.88  4644.1  529.50  4814.3  525.22  4885.2  524.24
  4906.2  523.17  4917.7  521.74  4964.4  515.96  4969.7  513.62  4977.1  513.75
  4983.3  510.07  4987.1  510.07  4991.1  505.62  4993.1  504.87  4994.1  504.07
  5002.5  504.07  5003.4  504.87  5005.2  507.17  5019.4  514.13  5217.5  513.20
  5238.6  511.63  5274.1  513.44  5471.9  512.54  5507.5  513.36  5528.5  514.75
  5586.9  515.42  5761.9  515.07  5781.5  515.96  6094.4  517.90  6317.5  520.23
#Mann=5,-1,0
  4569.3    0.05       0  4917.7    0.16       0  4993.1    0.07       0
  5003.4    0.16       0  5586.9    0.05       0
Bank Sta=4964.4,5781.5
Exp/Cntr=0.3,0.1

Type RM Length L Ch R = 1,11473,459,459,459
BEGIN DESCRIPTION:
Mapping XS 3cf60b6d
END DESCRIPTION:
XS GIS Cut Line= 5
      2771998.56      7081418.56      2771920.43      7080719.75
      2771738.14      7080606.90      2770930.85      7080246.66
      2770849.19      7080156.40
#Sta/Elev= 30
  4077.1  530.97  4495.5  522.56  4644.2  518.45  4724.0  514.34  4775.0  514.83
  4816.9  511.73  4874.8  510.99  4975.2  512.39  4984.7  508.62  4988.4  501.59
  4989.4  500.79  4998.7  501.59  5007.6  509.27  5013.1  507.58  5020.0  510.97
  5030.8  511.65  5181.1  511.76  5195.2  511.48  5204.3  509.13  5217.1  511.86
  5233.5  511.43  5354.6  513.78  5429.7  512.09  5446.2  514.34  5481.6  517.26
  5488.7  516.22  5516.2  515.17  5626.4  514.93  5748.0  517.70  6000.4  517.95
#Mann=7,-1,0
  4077.1    0.05       0  4495.5    0.16       0  4988.4    0.07       0
  4998.7    0.16       0  5233.5    0.05       0  5488.7    0.16       0
  5516.2    0.05       0
Bank Sta=4724,5446.2
Exp/Cntr=0.3,0.1

Type RM Length L Ch R = 1,11014,942,942,942
BEGIN DESCRIPTION:
WEST FORK TURKEY CREEK 5.0
END DESCRIPTION:
XS GIS Cut Line= 3
      2772075.00      7081525.02      2771925.00      7080325.00
      2771474.99      7078524.96
#Sta/Elev= 30
  3758.5  532.29  4310.2  522.78  4353.1  520.42  4544.6  516.23  4619.3  513.32
  4695.8  510.17  4957.8  511.15  4985.9  506.51  4993.4  500.51  4994.1  499.71
  5004.2  500.51  5009.1  506.85  5019.4  511.91  5060.6  510.02  5081.2  511.21
  5109.6  510.02  5154.1  511.34  5324.8  513.32  5617.3  514.59  5645.6  513.85
  5668.8  514.86  5905.9  515.99  6173.9  519.19  6222.8  521.57  6269.2  526.19
  6310.4  527.61  6511.4  542.34  6593.9  545.70  6681.5  546.78  6823.3  551.89
#Mann=5,-1,0
  3758.5    0.05       0  4310.2    0.16       0  4993.4    0.07       0
  5004.2    0.16       0  5154.1    0.05       0
Bank Sta=4619.3,5324.8
Exp/Cntr=0.3,0.1

Type RM Length L Ch R = 1,10072,1347,1347,1347
BEGIN DESCRIPTION:
WEST FORK TURKEY CREEK 4.0
END DESCRIPTION:
XS GIS Cut Line= 3
      2772775.01      7080925.03      2772475.00      7080025.00
      2771575.00      7078525.00
#Sta/Elev= 30
  4034.4  522.79  4237.1  519.24  4444.2  515.93  4534.9  511.86  4593.1  509.50
  4614.2  510.77  4624.7  509.15  4677.4  512.42  4731.6  509.56  4761.8  508.37
  4772.3  505.49  4782.8  508.34  4803.9  509.10  4814.5  507.94  4825.0  503.26
  4846.1  504.29  4867.2  509.69  4964.6  508.82  4972.6  506.47  4980.5  499.63
  4985.4  499.16  4986.2  498.36  4996.3  499.16  5006.4  506.66  5018.1  510.15
  5078.2  509.65  5575.6  511.86  6172.6  517.95  6565.2  549.55  6732.4  555.25
#Mann=8,-1,0
  4034.4    0.16       0  4237.1     0.1       0  4444.2    0.16       0
  4731.6    0.12       0  4964.6    0.16       0  4985.4    0.07       0
  4996.3    0.16       0  5078.2    0.05       0
Bank Sta=4534.9,5575.6
Exp/Cntr=0.3,0.1

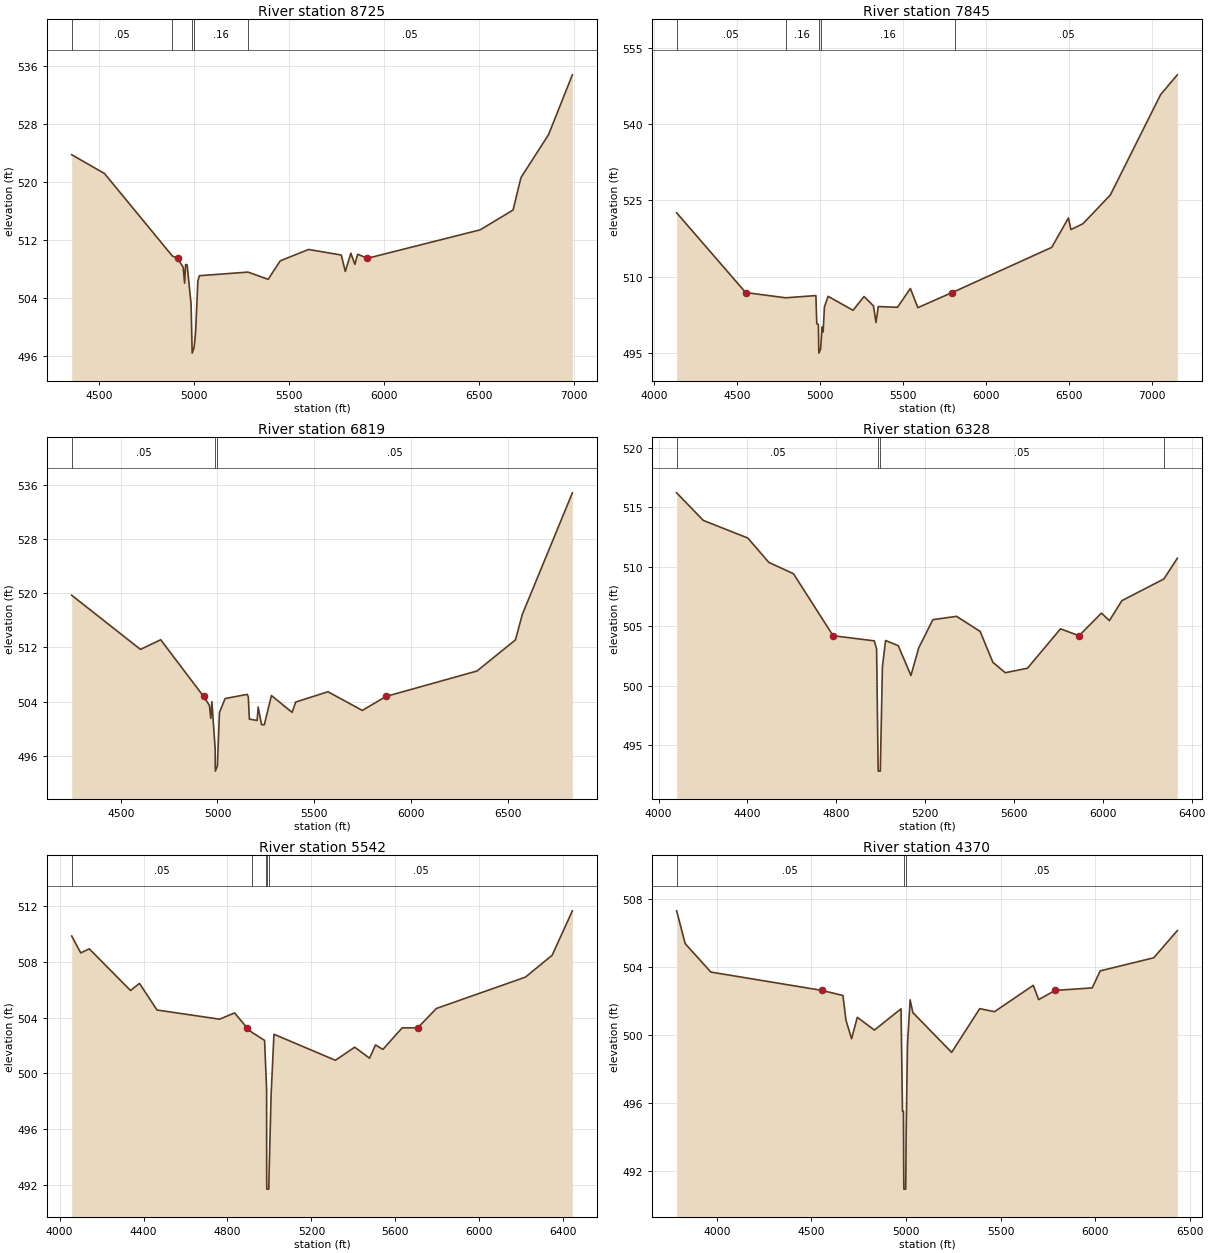
Type RM Length L Ch R = 1,8725,880,880,880
BEGIN DESCRIPTION:
Mapping XS 3d0bf980
END DESCRIPTION:
XS GIS Cut Line= 4
      2773608.81      7080511.45      2773435.19      7079882.07
      2773083.62      7079452.38      2771911.77      7078632.09
#Sta/Elev= 30
  4355.3  523.79  4528.0  521.19  4886.0  509.77  4913.6  509.46  4942.9  508.20
  4950.3  506.02  4955.5  508.61  4963.7  508.54  4984.4  503.12  4989.5  497.14
  4990.3  496.34  5000.5  497.14  5008.2  499.19  5020.1  506.30  5028.0  507.05
  5284.3  507.55  5390.5  506.55  5454.4  509.11  5603.4  510.68  5776.0  509.91
  5797.0  507.64  5826.6  510.16  5847.5  508.62  5862.4  510.02  5913.8  509.46
  6508.4  513.40  6681.1  516.14  6722.9  520.63  6867.8  526.55  6993.8  534.84
#Mann=5,-1,0
  4355.3    0.05       0  4886.0    0.16       0  4989.5    0.07       0
  5000.5    0.16       0  5284.3    0.05       0
Bank Sta=4913.6,5913.8
Exp/Cntr=0.3,0.1

Type RM Length L Ch R = 1,7845,1026,1026,1026
BEGIN DESCRIPTION:
WEST FORK TURKEY CREEK 2.0
END DESCRIPTION:
XS GIS Cut Line= 3
      2774025.01      7080175.02      2773725.00      7079375.00
      2771925.04      7078175.03
#Sta/Elev= 30
  4134.8  522.57  4551.1  506.87  4792.4  505.84  4974.1  506.28  4979.4  500.71
  4989.2  500.59  4991.2  495.75  4992.0  494.95  5002.2  495.75  5011.8  500.08
  5017.8  499.13  5025.3  504.02  5047.8  506.13  5198.0  503.38  5264.1  506.10
  5321.2  504.24  5336.3  500.98  5349.8  504.12  5465.5  503.97  5543.6  507.67
  5588.6  503.90  5794.5  506.87  5815.1  507.16  6395.4  515.77  6496.0  521.55
  6511.1  519.27  6583.2  520.41  6748.4  526.06  7051.9  545.84  7152.5  549.73
#Mann=5,-1,0
  4134.8    0.05       0  4792.4    0.16       0  4991.2    0.07       0
  5002.2    0.16       0  5815.1    0.05       0
Bank Sta=4551.1,5794.5
Exp/Cntr=0.3,0.1

Type RM Length L Ch R = 1,6819,491,491,491
BEGIN DESCRIPTION:
Mapping XS c14b7c3c
END DESCRIPTION:
XS GIS Cut Line= 4
      2774411.75      7080077.39      2774316.26      7079374.26
      2774125.29      7078966.27      2772997.12      7078089.77
#Sta/Elev= 30
  4246.3  519.69  4601.9  511.69  4706.5  513.12  4928.1  504.75  4958.2  503.43
  4965.6  501.51  4971.1  503.97  4988.2  496.97  4988.5  494.52  4989.2  493.72
  4999.5  494.52  5010.3  502.39  5039.6  504.44  5153.8  505.05  5159.3  504.72
  5164.9  501.40  5205.0  501.20  5210.5  503.18  5227.9  500.58  5242.1  500.57
  5279.0  504.88  5385.7  502.40  5404.3  503.92  5571.3  505.44  5748.8  502.68
  5871.5  504.75  6341.6  508.50  6540.7  513.10  6576.0  516.85  6835.0  534.81
#Mann=3,-1,0
  4246.3    0.05       0  4988.5    0.03       0  4999.5    0.05       0
Bank Sta=4928.1,5871.5
Exp/Cntr=0.3,0.1

Type RM Length L Ch R = 1,6328,786,786,786
BEGIN DESCRIPTION:
Mapping XS 28758a40
END DESCRIPTION:
XS GIS Cut Line= 3
      2774776.32      7079869.01      2774489.87      7079009.68
      2773613.14      7077985.37
#Sta/Elev= 30
  4081.5  516.22  4201.7  513.90  4402.0  512.42  4496.8  510.37  4607.5  509.42
  4785.9  504.21  4971.2  503.78  4981.7  503.10  4988.2  493.63  4988.9  492.83
  4998.4  492.83  4999.2  493.63  5007.9  501.61  5022.1  503.81  5079.2  503.37
  5136.3  500.87  5171.4  503.19  5235.1  505.56  5341.6  505.84  5448.0  504.57
  5505.1  501.98  5561.1  501.10  5661.0  501.48  5809.6  504.79  5893.2  504.21
  5993.8  506.11  6029.8  505.48  6086.0  507.16  6275.1  508.98  6335.6  510.72
#Mann=4,-1,0
  4081.5    0.05       0  4988.2    0.03       0  4999.2    0.05       0
  6275.1     0.1       0
Bank Sta=4785.9,5893.2
Exp/Cntr=0.3,0.1

Type RM Length L Ch R = 1,5542,1172,1172,1172
BEGIN DESCRIPTION:
Mapping XS f1bc6291
END DESCRIPTION:
XS GIS Cut Line= 4
      2775262.44      7079435.01      2774923.90      7078593.01
      2774845.78      7078462.80      2773890.92      7077542.67
#Sta/Elev= 30
  4057.9  509.86  4101.0  508.65  4141.8  508.94  4338.1  505.95  4381.0  506.46
  4464.3  504.55  4762.6  503.89  4833.9  504.34  4893.6  503.27  4917.1  502.94
  4976.8  502.37  4983.6  499.91  4986.4  498.89  4986.8  492.49  4987.5  491.69
  4997.1  491.69  4997.8  492.49  5007.9  498.45  5021.4  502.81  5314.2  500.94
  5406.3  501.88  5477.0  501.09  5505.3  502.04  5540.6  501.72  5632.4  503.27
  5706.5  503.27  5795.3  504.66  6219.5  506.91  6346.8  508.48  6443.3  511.67
#Mann=5,-1,0
  4057.9    0.05       0  4917.1    0.16       0  4983.6    0.05       0
  4986.8    0.03       0  4997.8    0.05       0
Bank Sta=4893.6,5706.5
Exp/Cntr=0.3,0.1

Type RM Length L Ch R = 1,4370,1489,1489,1489
BEGIN DESCRIPTION:
Mapping XS 63b939a3
END DESCRIPTION:
XS GIS Cut Line= 3
      2775444.34      7079294.87      2775329.76      7078107.37
      2774308.77      7077075.12
#Sta/Elev= 30
  3787.9  507.29  3833.1  505.36  3968.6  503.69  4556.5  502.61  4666.5  502.31
  4681.9  500.88  4712.0  499.77  4742.2  501.03  4832.6  500.28  4973.3  501.53
  4980.9  495.50  4986.1  495.50  4987.5  491.73  4988.2  490.93  4997.8  490.93
  4998.5  491.73  5000.1  494.04  5007.2  499.41  5021.3  502.06  5035.5  501.31
  5240.5  498.97  5389.0  501.54  5466.8  501.36  5671.9  502.91  5700.2  502.07
  5786.8  502.61  5983.0  502.76  6025.4  503.76  6308.2  504.53  6432.8  506.13
#Mann=3,-1,0
  3787.9    0.05       0  4987.5    0.03       0  4998.5    0.05       0
Bank Sta=4556.5,5786.8
Exp/Cntr=0.3,0.1

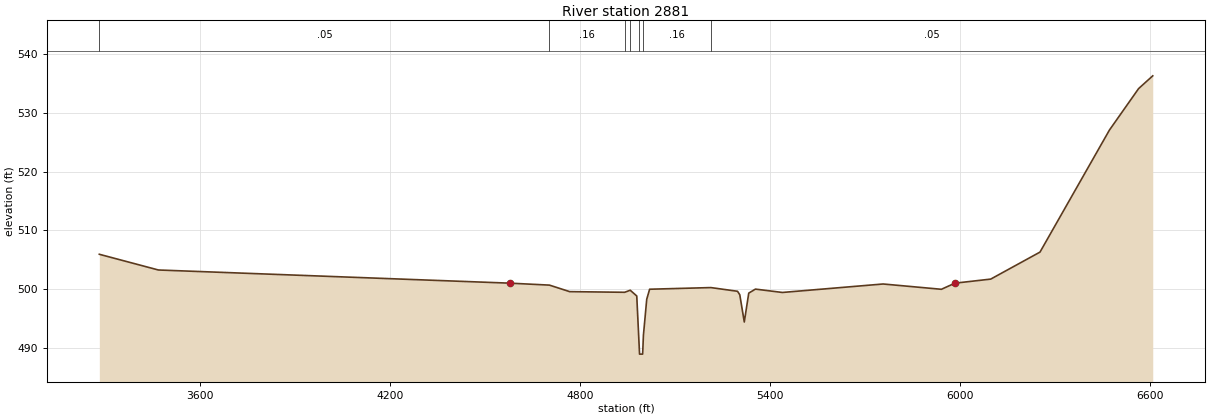
Type RM Length L Ch R = 1,2881,546,546,546
BEGIN DESCRIPTION:
Mapping XS 7d927b2f
END DESCRIPTION:
XS GIS Cut Line= 4
      2775460.20      7079276.77      2775814.35      7077721.26
      2775703.24      7077374.04      2774724.10      7076422.67
#Sta/Elev= 30
  3283.0  505.95  3469.4  503.28  4579.1  501.04  4703.7  500.71  4767.7  499.60
  4941.3  499.49  4958.7  499.84  4979.4  498.86  4987.5  489.78  4988.2  488.98
  4997.9  488.98  4998.6  489.78  5000.4  492.17  5010.9  498.31  5020.0  500.01
  5213.3  500.29  5297.5  499.66  5304.6  499.07  5318.8  494.44  5332.9  499.35
  5354.0  500.03  5438.9  499.46  5757.1  500.90  5941.0  500.00  5983.7  501.04
  6096.6  501.73  6252.2  506.32  6471.4  527.06  6563.5  534.11  6608.1  536.28
#Mann=7,-1,0
  3283.0    0.05       0  4703.7    0.16       0  4941.3    0.12       0
  4958.7    0.16       0  4987.5    0.07       0  4998.6    0.16       0
  5213.3    0.05       0
Bank Sta=4579.1,5983.7
Exp/Cntr=0.3,0.1