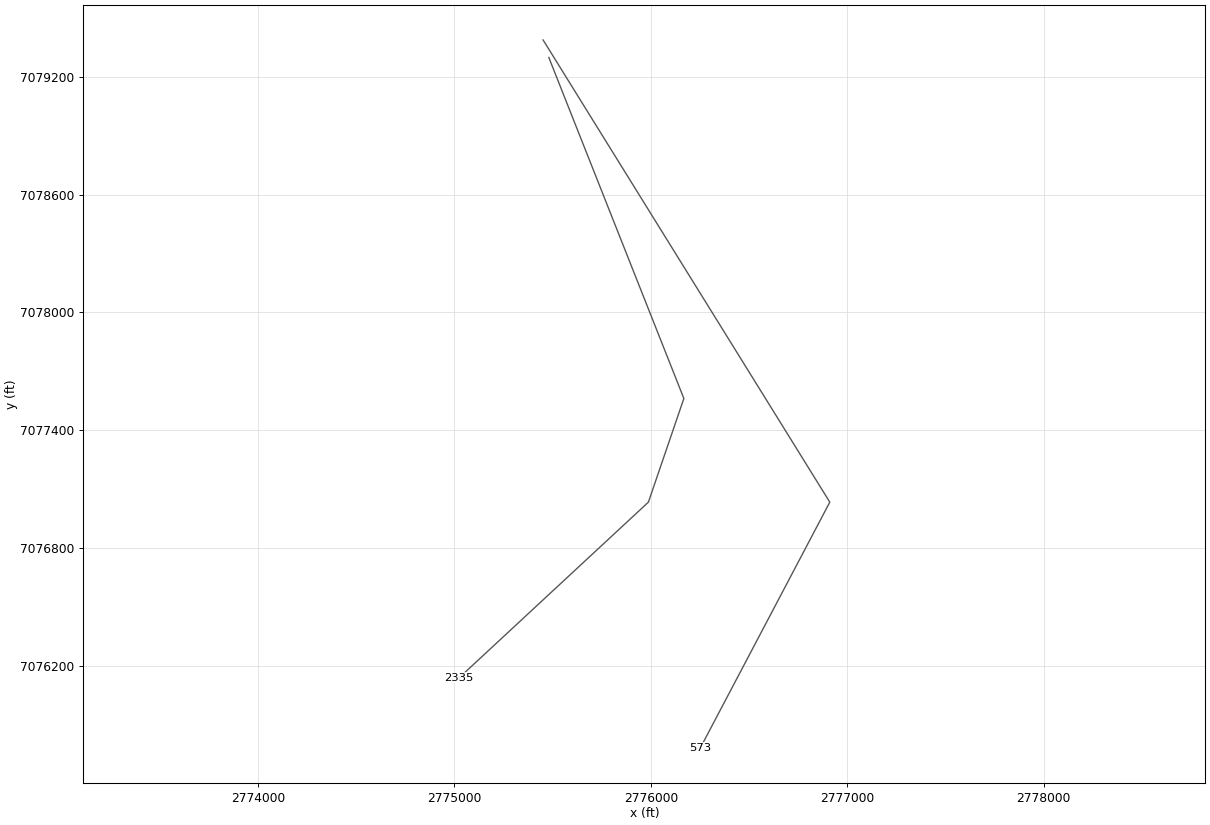
HEC-RAS study WEST FORK TURKEY CREEK.prj: WEST FORK TURKEY CREEK Base Level Engineering

--- WEST FORK TURKEY CREEK.g01 (geometry) --- (continued)

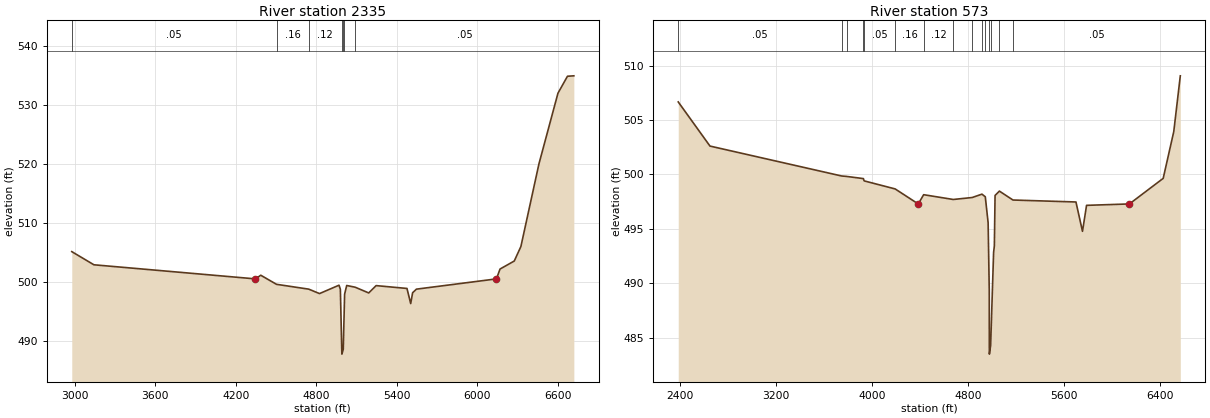
Type RM Length L Ch R = 1,2335,1762,1762,1762
BEGIN DESCRIPTION:
Mapping XS b8c6ade9
END DESCRIPTION:
XS GIS Cut Line= 4
      2775481.02      7079297.66      2776168.52      7077561.54
      2775987.97      7077033.76      2775023.80      7076138.96
#Sta/Elev= 30
  2977.9  505.09  3142.8  502.86  4346.6  500.47  4385.9  501.09  4503.2  499.55
  4743.5  498.73  4823.7  497.98  4968.9  499.40  4978.9  498.71  4989.4  488.52
  4990.1  487.72  5000.5  488.52  5007.0  494.54  5010.6  497.88  5026.2  499.35
  5089.2  499.06  5190.3  498.09  5245.3  499.33  5475.2  498.85  5503.0  496.29
  5517.2  498.12  5545.6  498.73  6141.8  500.47  6168.6  502.14  6274.6  503.50
  6324.0  505.96  6458.3  519.95  6600.0  531.93  6670.9  534.81  6718.4  534.88
#Mann=7,-1,0
  2977.9    0.05       0  4503.2    0.16       0  4743.5    0.12       0
  4989.4    0.07       0  5000.5    0.12       0  5007.0    0.16       0
  5089.2    0.05       0
Bank Sta=4346.6,6141.8
Exp/Cntr=0.3,0.1

Type RM Length L Ch R = 1,573,0,0,0
BEGIN DESCRIPTION:
WEST FORK TURKEY CREEK 1.0
END DESCRIPTION:
XS GIS Cut Line= 3
      2775451.85      7079386.91      2776911.58      7077033.76
      2776253.34      7075784.16
#Sta/Elev= 30
  2385.6  506.67  2650.1  502.61  3746.5  499.86  3787.9  499.82  3927.5  499.62
  3934.1  499.41  4192.2  498.67  4384.5  497.29  4429.6  498.14  4675.9  497.70
  4833.4  497.88  4915.0  498.19  4942.9  497.95  4966.5  495.56  4975.9  489.37
  4976.3  484.28  4977.0  483.48  4987.4  484.28  5012.1  492.83  5018.4  493.43
  5024.3  498.07  5060.3  498.47  5173.4  497.65  5698.0  497.47  5752.4  494.77
  5786.3  497.16  6143.2  497.29  6424.5  499.64  6512.6  503.94  6567.1  509.07
#Mann=15,-1,0
  2385.6    0.05       0  3746.5     0.1       0  3787.9    0.05       0
  3927.5     0.1       0  3934.1    0.05       0  4192.2    0.16       0
  4429.6    0.12       0  4675.9    0.16       0  4833.4    0.12       0
  4915.0    0.16       0  4942.9    0.12       0  4976.3    0.07       0
  4987.4    0.12       0  5060.3    0.16       0  5173.4    0.05       0
Bank Sta=4384.5,6143.2
Exp/Cntr=0.3,0.1

Chan Stop Cuts=-1