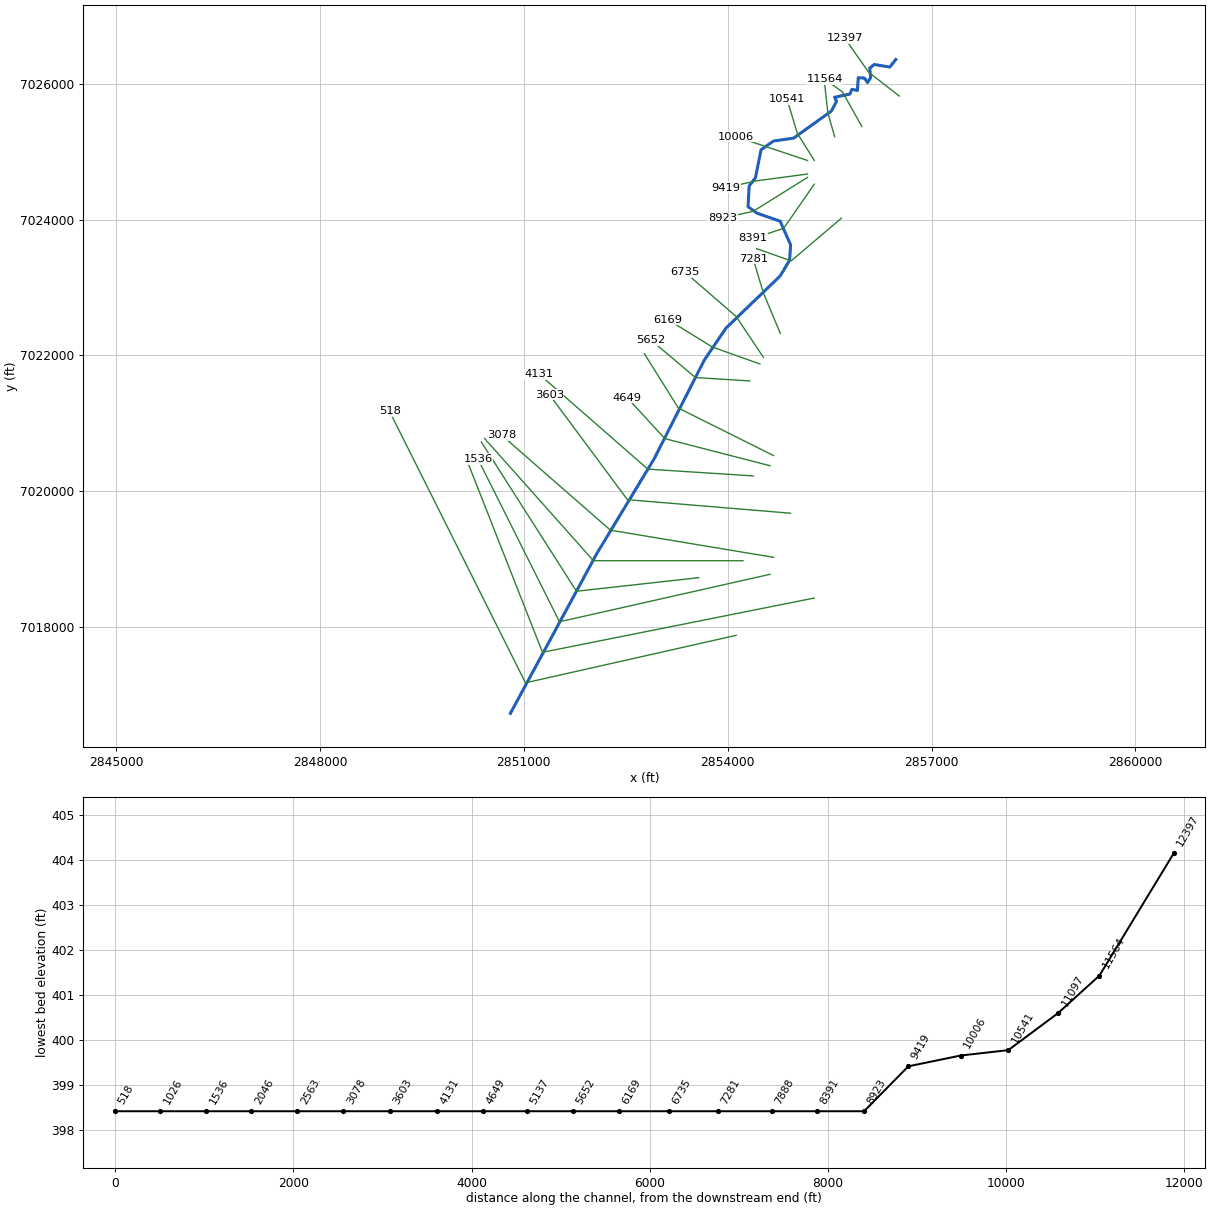
--- WHITE OAK BRANCH.prj (project) ---

Proj Title=WHITE OAK BRANCH Base Level Engineering
Current Plan=p01
Default Exp/Contr=0.3,0.1
English Units
Geom File=g01
Flow File=f01
Plan File=p01
BEGIN DESCRIPTION:
WHITE OAK BRANCH
END DESCRIPTION:

--- WHITE OAK BRANCH.p01 (plan) ---

Plan Title=Multiple Run
Short Identifier=Multiple
Geom File=g01
Flow File=f01
Subcritical Flow
K Sum by GR= 0
Std Step Tol= 0.01
Critical Tol= 0.01
Num of Std Step Trials= 20
Max Error Tol= 0.3
Flow Tol Ratio= 0.001
Split Flow NTrial= 30
Split Flow Tol= 0.02
Split Flow Ratio= 0.02
Log Output Level= 0
Friction Slope Method= 1
Unsteady Friction Slope Method= 2
Unsteady Bridges Friction Slope Method= 1
Parabolic Critical Depth
Global Vel Dist=  1 , 1 , 1
Global Log Level= 0
CheckData=True
Encroach Param= -1, 0, 0, 0
BEGIN DESCRIPTION:
Multiple Run
END DESCRIPTION:

--- WHITE OAK BRANCH.f01 (steady flow) ---

Flow Title=Multiple
Number of Profiles=7
Profile Names=10-year,25-year,50-year,1pct_min,100-year,1pct_plu,500-year
River Rch & RM= WHITE OAK BRANCH,Reach-1,12397
     604     811     980     589    1175    2345    1693
River Rch & RM= WHITE OAK BRANCH,Reach-1,10541
     894    1224    1498     910    1816    3623    2674
River Rch & RM= WHITE OAK BRANCH,Reach-1,7281
    1009    1386    1699    1033    2061    4113    3042
River Rch & RM= WHITE OAK BRANCH,Reach-1,4649
    1253    1736    2140    1307    2609    5205    3887
River Rch & RM= WHITE OAK BRANCH,Reach-1,2563
    1385    1922    2372    1451    2895    5775    4320
River Rch & RM= WHITE OAK BRANCH,Reach-1,518
    1528    2129    2634    1614    3221    6426    4827
Boundary for River Rch & Prof#=WHITE OAK BRANCH,Reach-1,1
Up Type=0
Dn Type=3
Dn Slope=0.005
Boundary for River Rch & Prof#=WHITE OAK BRANCH,Reach-1,2
Up Type=0
Dn Type=3
Dn Slope=0.005
Boundary for River Rch & Prof#=WHITE OAK BRANCH,Reach-1,3
Up Type=0
Dn Type=3
Dn Slope=0.005
Boundary for River Rch & Prof#=WHITE OAK BRANCH,Reach-1,4
Up Type=0
Dn Type=3
Dn Slope=0.005
Boundary for River Rch & Prof#=WHITE OAK BRANCH,Reach-1,5
Up Type=0
Dn Type=3
Dn Slope=0.005
Boundary for River Rch & Prof#=WHITE OAK BRANCH,Reach-1,6
Up Type=0
Dn Type=3
Dn Slope=0.005
Boundary for River Rch & Prof#=WHITE OAK BRANCH,Reach-1,7
Up Type=0
Dn Type=3
Dn Slope=0.005

--- WHITE OAK BRANCH.g01 (geometry) ---

Geom Title=Existing Conditions

River Reach=WHITE OAK BRANCH,Reach-1
Reach XY= 30
      2856474.76      7026362.92      2856385.94      7026251.78
      2856155.90      7026289.20      2856090.66      7026233.53
      2856104.43      7026097.16      2856056.22      7026022.77
      2856014.89      7026088.89      2855921.23      7026094.40
      2855910.21      7025907.06      2855828.94      7025923.59
      2855798.63      7025853.34      2855574.10      7025806.51
      2855603.03      7025745.90      2855525.89      7025602.64
      2854972.15      7025204.55      2854673.23      7025160.47
      2854491.41      7025032.37      2854408.76      7024619.12
      2854316.47      7024497.91      2854299.94      7024193.49
      2854432.17      7024097.06      2854772.41      7023979.98
      2854926.32      7023630.38      2854911.80      7023405.40
      2854773.91      7023173.15      2853975.57      7022403.85
      2853656.24      7021932.11      2852915.97      7020473.34
      2852074.09      7019079.88      2850802.66      7016724.80

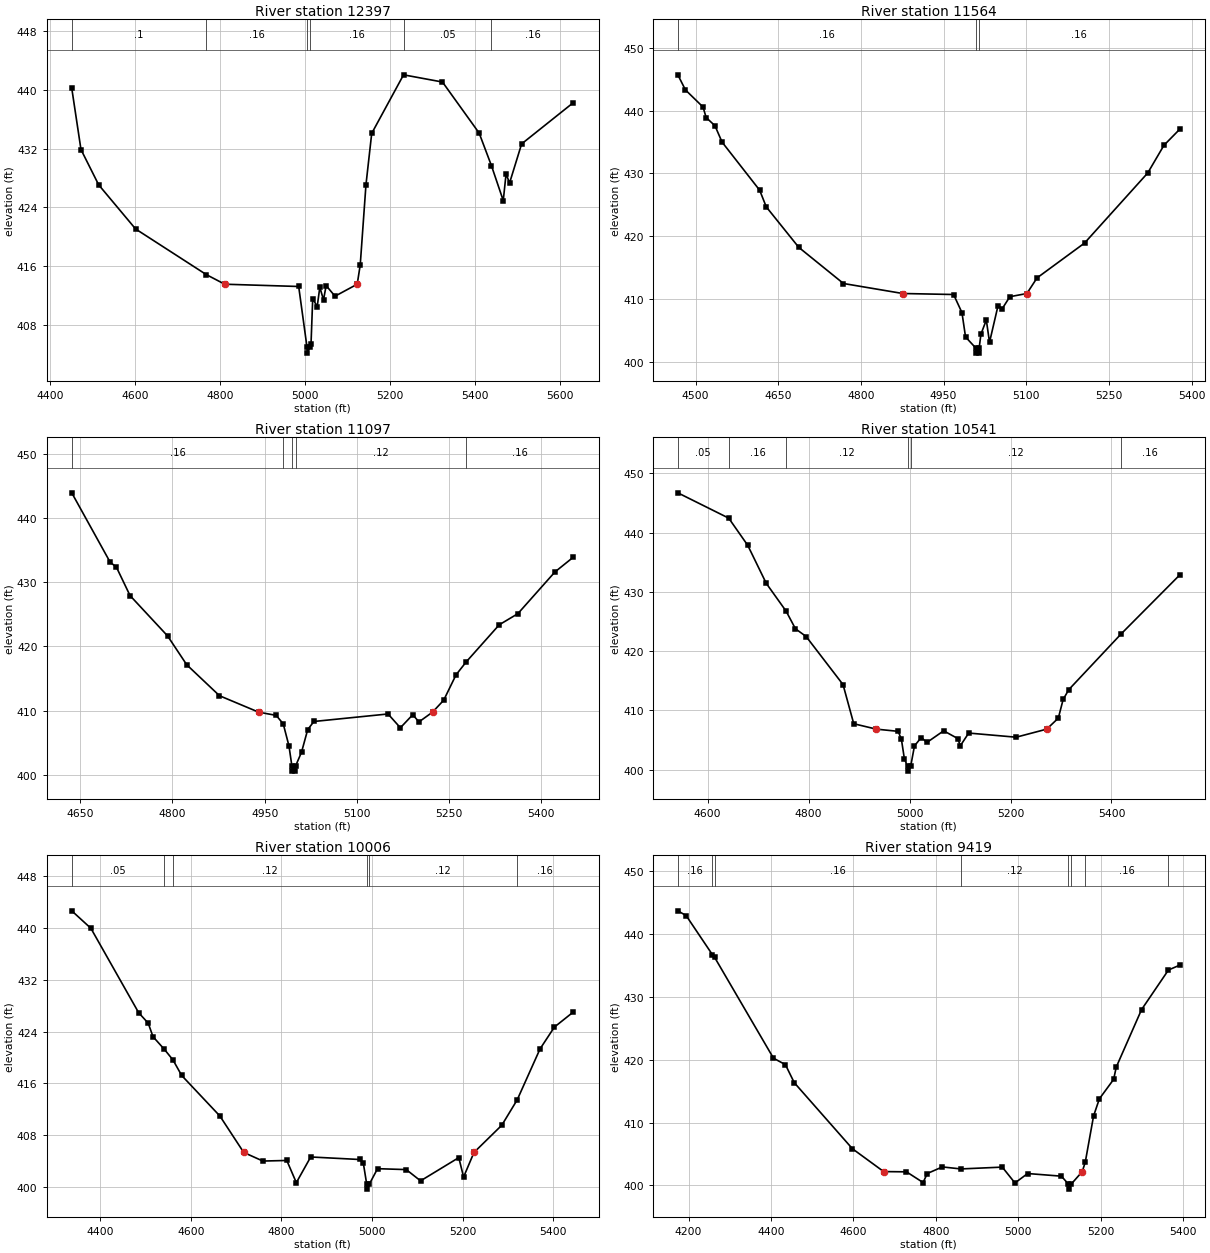
Type RM Length L Ch R = 1,12397,833,833,833
BEGIN DESCRIPTION:
WHITE OAK BRANCH 24.0
END DESCRIPTION:
XS GIS Cut Line= 3
      2856525.02      7025824.98      2856075.00      7026175.00
      2855725.03      7026674.96
#Sta/Elev= 30
  4450.5  440.21  4472.2  431.86  4513.9  427.05  4600.7  421.05  4767.3  414.83
  4810.5  413.53  4984.4  413.22  5004.0  404.95  5004.5  404.15  5010.0  404.95
  5013.4  405.36  5017.4  411.57  5028.0  410.49  5034.1  413.12  5042.8  411.40
  5049.0  413.34  5069.9  411.90  5122.1  413.53  5129.2  416.16  5142.7  427.08
  5156.2  434.06  5231.1  442.03  5322.7  441.05  5409.0  434.10  5438.0  429.65
  5465.7  424.91  5472.3  428.55  5480.5  427.30  5508.9  432.63  5630.9  438.26
#Mann=6,-1,0
  4450.5     0.1       0  4767.3    0.16       0  5004.0    0.07       0
  5010.0    0.16       0  5231.1    0.05       0  5438.0    0.16       0
Bank Sta=4810.5,5122.1
Exp/Cntr=0.3,0.1

Type RM Length L Ch R = 1,11564,467,467,467
BEGIN DESCRIPTION:
WHITE OAK BRANCH 22.0
END DESCRIPTION:
XS GIS Cut Line= 3
      2855975.02      7025374.97      2855690.49      7025884.23
      2855424.98      7026075.01
#Sta/Elev= 30
  4467.8  445.68  4481.6  443.28  4513.5  440.56  4519.2  438.89  4535.2  437.58
  4548.0  434.99  4616.3  427.33  4628.2  424.69  4687.2  418.25  4768.3  412.50
  4875.9  410.91  4968.1  410.75  4983.3  407.87  4989.8  404.00  5008.5  402.23
  5009.0  401.43  5014.0  401.43  5014.5  402.23  5017.7  404.43  5027.5  406.70
  5033.3  403.15  5048.7  408.96  5056.4  408.50  5070.2  410.40  5101.1  410.91
  5119.5  413.39  5205.7  418.93  5320.4  430.08  5349.8  434.48  5378.1  437.00
#Mann=3,-1,0
  4467.8    0.16       0  5008.5    0.07       0  5014.5    0.16       0
Bank Sta=4875.9,5101.1
Exp/Cntr=0.3,0.1

Type RM Length L Ch R = 1,11097,556,556,556
BEGIN DESCRIPTION:
WHITE OAK BRANCH 21.0
END DESCRIPTION:
XS GIS Cut Line= 3
      2855575.00      7025225.01      2855475.00      7025575.00
      2855425.00      7026025.04
#Sta/Elev= 30
  4636.0  443.92  4698.4  433.14  4708.8  432.33  4730.9  427.92  4792.0  421.64
  4823.2  417.15  4876.5  412.33  4940.3  409.77  4968.8  409.27  4980.3  407.95
  4989.6  404.52  4994.4  401.39  4994.9  400.59  4999.9  400.59  5000.4  401.39
  5010.1  403.55  5020.1  407.05  5030.2  408.32  5150.9  409.49  5171.0  407.34
  5191.2  409.38  5201.2  408.25  5223.3  409.77  5241.5  411.63  5261.6  415.58
  5278.1  417.59  5332.0  423.38  5362.2  425.10  5422.6  431.60  5452.8  433.92
#Mann=5,-1,0
  4636.0    0.16       0  4980.3    0.12       0  4994.4    0.07       0
  5000.4    0.12       0  5278.1    0.16       0
Bank Sta=4940.3,5223.3
Exp/Cntr=0.3,0.1

Type RM Length L Ch R = 1,10541,535,535,535
BEGIN DESCRIPTION:
WHITE OAK BRANCH 20.0
END DESCRIPTION:
XS GIS Cut Line= 3
      2855274.98      7024875.03      2855025.00      7025275.00
      2854874.99      7025775.02
#Sta/Elev= 30
  4541.1  446.70  4641.9  442.43  4679.6  437.84  4716.2  431.44  4755.6  426.74
  4774.0  423.78  4795.2  422.47  4868.3  414.36  4889.5  407.76  4934.3  406.85
  4977.4  406.48  4983.9  405.14  4989.8  401.84  4996.2  400.57  4996.7  399.77
  5002.2  400.57  5009.8  404.03  5023.2  405.44  5034.5  404.61  5067.6  406.57
  5095.4  405.27  5100.6  404.05  5117.2  406.19  5211.1  405.49  5271.7  406.85
  5294.7  408.71  5304.2  411.85  5315.5  413.52  5419.1  422.91  5534.8  432.82
#Mann=6,-1,0
  4541.1    0.05       0  4641.9    0.16       0  4755.6    0.12       0
  4996.2    0.07       0  5002.2    0.12       0  5419.1    0.16       0
Bank Sta=4934.3,5271.7
Exp/Cntr=0.3,0.1

Type RM Length L Ch R = 1,10006,587,587,587
BEGIN DESCRIPTION:
WHITE OAK BRANCH 19.0
END DESCRIPTION:
XS GIS Cut Line= 3
      2855175.02      7024874.99      2854575.00      7025075.00
      2854125.02      7025224.99
#Sta/Elev= 30
  4337.6  442.67  4379.8  439.97  4485.2  426.92  4506.3  425.30  4516.8  423.22
  4542.0  421.25  4560.9  419.62  4580.1  417.22  4664.4  410.95  4717.0  405.32
  4759.3  403.99  4812.0  404.08  4833.0  400.65  4864.7  404.62  4972.7  404.23
  4980.6  403.76  4988.2  400.45  4988.7  399.65  4994.2  400.45  5012.2  402.81
  5075.5  402.67  5107.1  400.93  5191.4  404.52  5202.0  401.52  5224.9  405.32
  5286.3  409.53  5320.3  413.46  5370.6  421.32  5402.3  424.70  5444.4  427.05
#Mann=6,-1,0
  4337.6    0.05       0  4542.0    0.16       0  4560.9    0.12       0
  4988.2    0.07       0  4994.2    0.12       0  5320.3    0.16       0
Bank Sta=4717,5224.9
Exp/Cntr=0.3,0.1

Type RM Length L Ch R = 1,9419,496,496,496
BEGIN DESCRIPTION:
WHITE OAK BRANCH 18.0
END DESCRIPTION:
XS GIS Cut Line= 3
      2855175.02      7024675.00      2854425.00      7024575.00
      2853975.04      7024475.01
#Sta/Elev= 30
  4174.1  443.66  4194.3  442.90  4257.8  436.71  4263.3  436.27  4406.2  420.23
  4435.2  419.20  4456.6  416.34  4597.8  405.83  4673.6  402.20  4729.0  402.16
  4769.3  400.46  4779.4  401.89  4816.0  402.94  4861.0  402.62  4961.5  402.91
  4992.2  400.39  5023.0  401.89  5104.9  401.47  5122.0  400.21  5122.5  399.41
  5128.8  400.21  5155.6  402.20  5162.9  403.71  5183.0  411.04  5197.1  413.77
  5231.7  416.86  5238.1  418.82  5299.5  427.96  5364.7  434.25  5391.7  435.01
#Mann=8,-1,0
  4174.1    0.16       0  4257.8    0.05       0  4263.3    0.16       0
  4861.0    0.12       0  5122.0    0.07       0  5128.8    0.12       0
  5162.9    0.16       0  5364.7    0.05       0
Bank Sta=4673.6,5155.6
Exp/Cntr=0.3,0.1

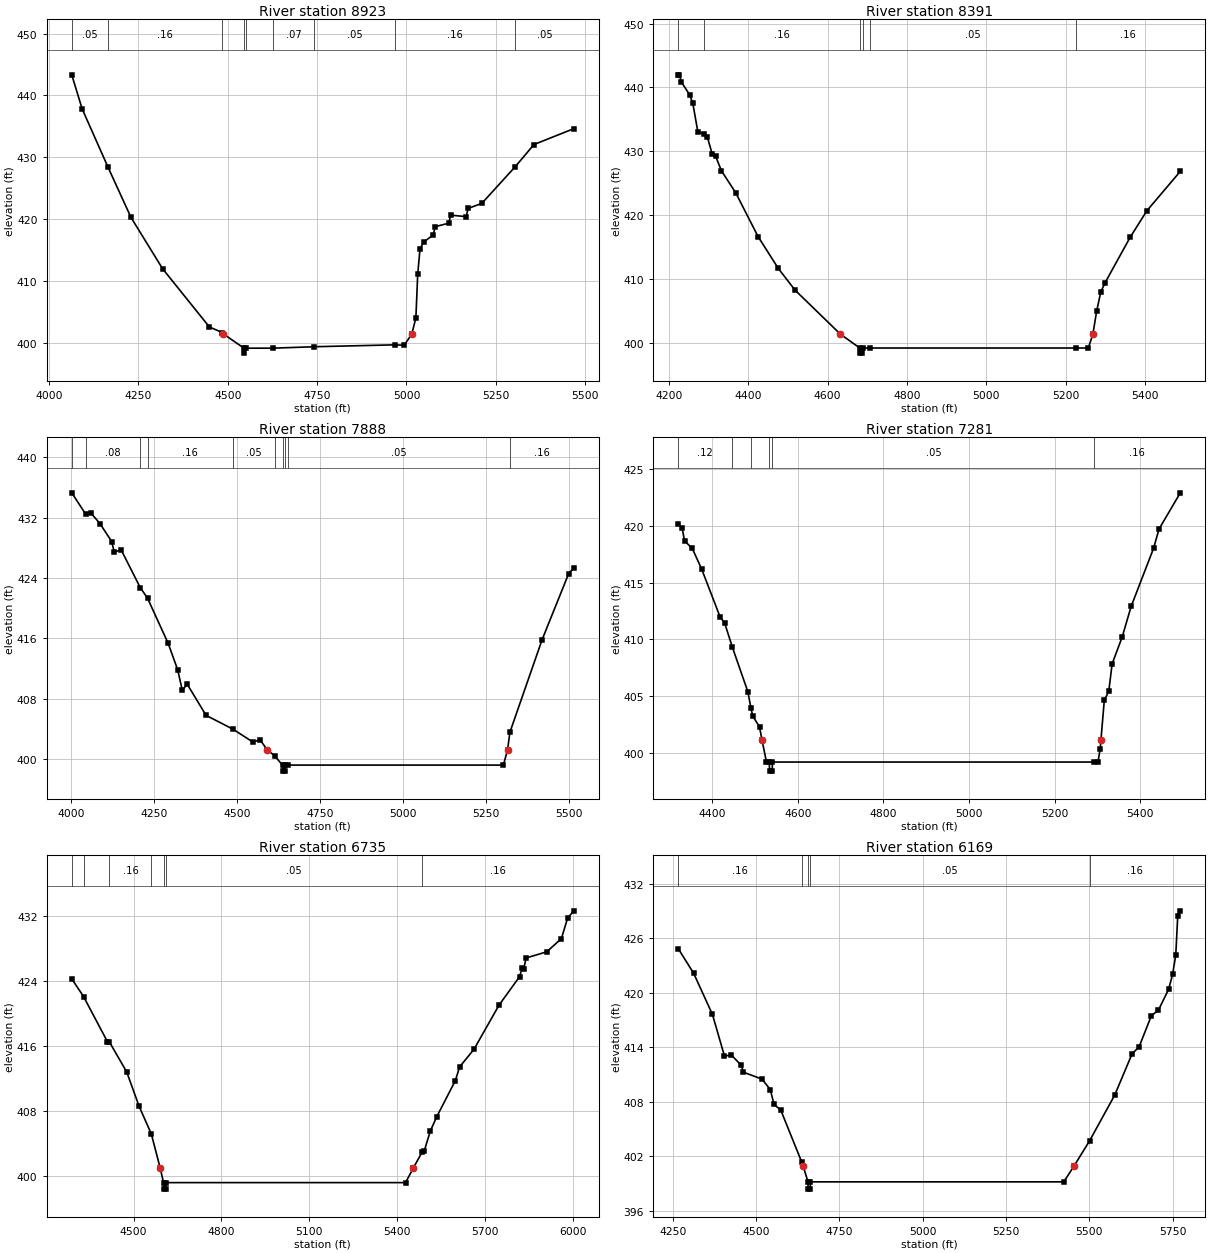
Type RM Length L Ch R = 1,8923,532,532,532
BEGIN DESCRIPTION:
WHITE OAK BRANCH 17.0
END DESCRIPTION:
XS GIS Cut Line= 3
      2855174.97      7024624.98      2854375.00      7024125.00
      2853925.04      7024025.01
#Sta/Elev= 30
  4063.7  443.33  4092.6  437.85  4165.4  428.38  4229.4  420.31  4317.8  412.03
  4448.7  402.63  4484.9  401.73  4487.9  401.51  4545.5  399.21  4546.0  398.41
  4552.3  399.21  4625.9  399.21  4741.0  399.44  4968.9  399.75  4993.5  399.67
  5014.9  401.51  5026.3  404.10  5031.4  411.13  5037.8  415.22  5048.0  416.34
  5074.9  417.48  5080.1  418.82  5118.5  419.39  5123.6  420.68  5167.1  420.44
  5172.3  421.76  5210.7  422.58  5303.6  428.46  5356.6  432.08  5468.0  434.64
#Mann=9,-1,0
  4063.7    0.05       0  4165.4    0.16       0  4484.9    0.05       0
  4545.5    0.07       0  4552.3    0.05       0  4625.9    0.07       0
  4741.0    0.05       0  4968.9    0.16       0  5303.6    0.05       0
Bank Sta=4487.9,5014.9
Exp/Cntr=0.3,0.1

Type RM Length L Ch R = 1,8391,503,503,503
BEGIN DESCRIPTION:
WHITE OAK BRANCH 16.0
END DESCRIPTION:
XS GIS Cut Line= 3
      2855275.00      7024525.01      2854825.00      7023875.00
      2854375.02      7023725.01
#Sta/Elev= 30
  4224.0  441.98  4227.0  441.98  4231.4  440.89  4252.4  438.87  4260.5  437.56
  4273.3  433.04  4288.8  432.76  4297.0  432.29  4309.1  429.65  4317.9  429.26
  4332.8  426.95  4368.6  423.52  4425.4  416.61  4476.0  411.67  4517.9  408.29
  4632.6  401.37  4681.4  399.21  4681.9  398.41  4687.7  398.41  4688.2  399.21
  4707.0  399.21  5226.8  399.21  5257.0  399.21  5268.6  401.37  5278.1  404.99
  5288.6  408.00  5299.2  409.42  5362.4  416.53  5404.6  420.70  5488.9  426.87
#Mann=6,-1,0
  4224.0    0.05       0  4288.8    0.16       0  4681.4   0.033       0
  4688.2    0.16       0  4707.0    0.05       0  5226.8    0.16       0
Bank Sta=4632.6,5268.6
Exp/Cntr=0.3,0.1

Type RM Length L Ch R = 1,7888,607,607,607
BEGIN DESCRIPTION:
WHITE OAK BRANCH 15.0
END DESCRIPTION:
XS GIS Cut Line= 3
      2855675.03      7024025.03      2854935.28      7023394.64
      2854425.03      7023574.99
#Sta/Elev= 30
  4001.9  435.27  4043.3  432.48  4058.5  432.65  4087.0  431.19  4122.2  428.82
  4129.9  427.43  4150.7  427.72  4208.2  422.73  4230.4  421.30  4292.4  415.34
  4320.9  411.86  4335.2  409.09  4349.5  409.95  4406.6  405.80  4487.6  403.97
  4548.2  402.25  4569.1  402.58  4590.4  401.27  4613.1  400.44  4637.1  399.21
  4637.6  398.41  4643.4  398.41  4643.9  399.21  4654.1  399.21  5302.9  399.21
  5315.6  401.27  5322.3  403.54  5419.6  415.83  5499.6  424.57  5515.0  425.33
#Mann=10,-1,0
  4001.9    0.05       0  4043.3    0.08       0  4208.2     0.1       0
  4230.4    0.16       0  4487.6    0.05       0  4613.1    0.07       0
  4637.1   0.033       0  4643.9    0.07       0  4654.1    0.05       0
  5322.3    0.16       0
Bank Sta=4590.4,5315.6
Exp/Cntr=0.3,0.1

Type RM Length L Ch R = 1,7281,546,546,546
BEGIN DESCRIPTION:
WHITE OAK BRANCH 14.0
END DESCRIPTION:
XS GIS Cut Line= 3
      2854775.00      7022325.01      2854525.00      7022925.00
      2854375.00      7023424.99
#Sta/Elev= 30
  4321.1  420.17  4330.3  419.77  4335.7  418.68  4353.6  418.02  4375.3  416.23
  4418.6  411.99  4429.4  411.44  4447.5  409.30  4483.6  405.39  4490.8  403.93
  4495.0  403.25  4510.7  402.31  4516.4  401.16  4526.9  399.22  4533.6  399.21
  4534.1  398.41  4540.3  398.41  4540.9  399.21  5292.4  399.21  5300.8  399.21
  5306.1  400.39  5307.8  401.16  5315.6  404.63  5326.1  405.45  5333.9  407.85
  5357.4  410.22  5378.3  412.91  5430.5  418.01  5443.5  419.73  5493.1  422.91
#Mann=6,-1,0
  4321.1    0.12       0  4447.5    0.16       0  4490.8    0.05       0
  4533.6   0.033       0  4540.9    0.05       0  5292.4    0.16       0
Bank Sta=4516.4,5307.8
Exp/Cntr=0.3,0.1

Type RM Length L Ch R = 1,6735,566,566,566
BEGIN DESCRIPTION:
WHITE OAK BRANCH 13.0
END DESCRIPTION:
XS GIS Cut Line= 3
      2854524.97      7021975.04      2854125.00      7022575.00
      2853375.03      7023224.98
#Sta/Elev= 30
  4289.1  424.24  4329.3  422.07  4410.7  416.53  4417.8  416.48  4476.8  412.79
  4518.9  408.59  4560.9  405.16  4590.5  401.05  4602.4  399.21  4602.9  398.41
  4609.1  398.41  4609.7  399.21  5428.5  399.21  5455.5  401.05  5485.7  403.00
  5492.1  403.09  5513.0  405.55  5534.9  407.31  5598.5  411.75  5612.8  413.42
  5662.1  415.60  5747.6  421.02  5817.9  424.53  5825.5  425.53  5832.1  425.49
  5839.8  426.81  5910.0  427.56  5960.4  429.19  5981.3  431.69  6002.6  432.60
#Mann=7,-1,0
  4289.1    0.16       0  4329.3    0.12       0  4417.8    0.16       0
  4560.9    0.05       0  4602.4   0.033       0  4609.7    0.05       0
  5485.7    0.16       0
Bank Sta=4590.5,5455.5
Exp/Cntr=0.3,0.1

Type RM Length L Ch R = 1,6169,517,517,517
BEGIN DESCRIPTION:
WHITE OAK BRANCH 12.0
END DESCRIPTION:
XS GIS Cut Line= 3
      2854475.00      7021875.00      2853775.00      7022125.00
      2853125.02      7022524.99
#Sta/Elev= 30
  4266.8  424.85  4313.0  422.14  4369.3  417.62  4405.4  413.04  4425.5  413.17
  4456.3  412.02  4461.6  411.28  4517.9  410.51  4542.9  409.36  4554.0  407.73
  4574.2  407.11  4637.4  401.37  4641.8  400.90  4656.0  399.21  4656.5  398.41
  4662.8  398.41  4663.4  399.21  5423.6  399.21  5453.5  400.90  5500.8  403.71
  5576.3  408.74  5628.4  413.28  5649.7  414.07  5686.4  417.48  5707.6  418.10
  5738.1  420.38  5750.2  422.03  5759.7  424.18  5765.6  428.48  5773.3  429.02
#Mann=5,-1,0
  4266.8    0.16       0  4637.4    0.05       0  4656.0   0.033       0
  4663.4    0.05       0  5500.8    0.16       0
Bank Sta=4641.8,5453.5
Exp/Cntr=0.3,0.1

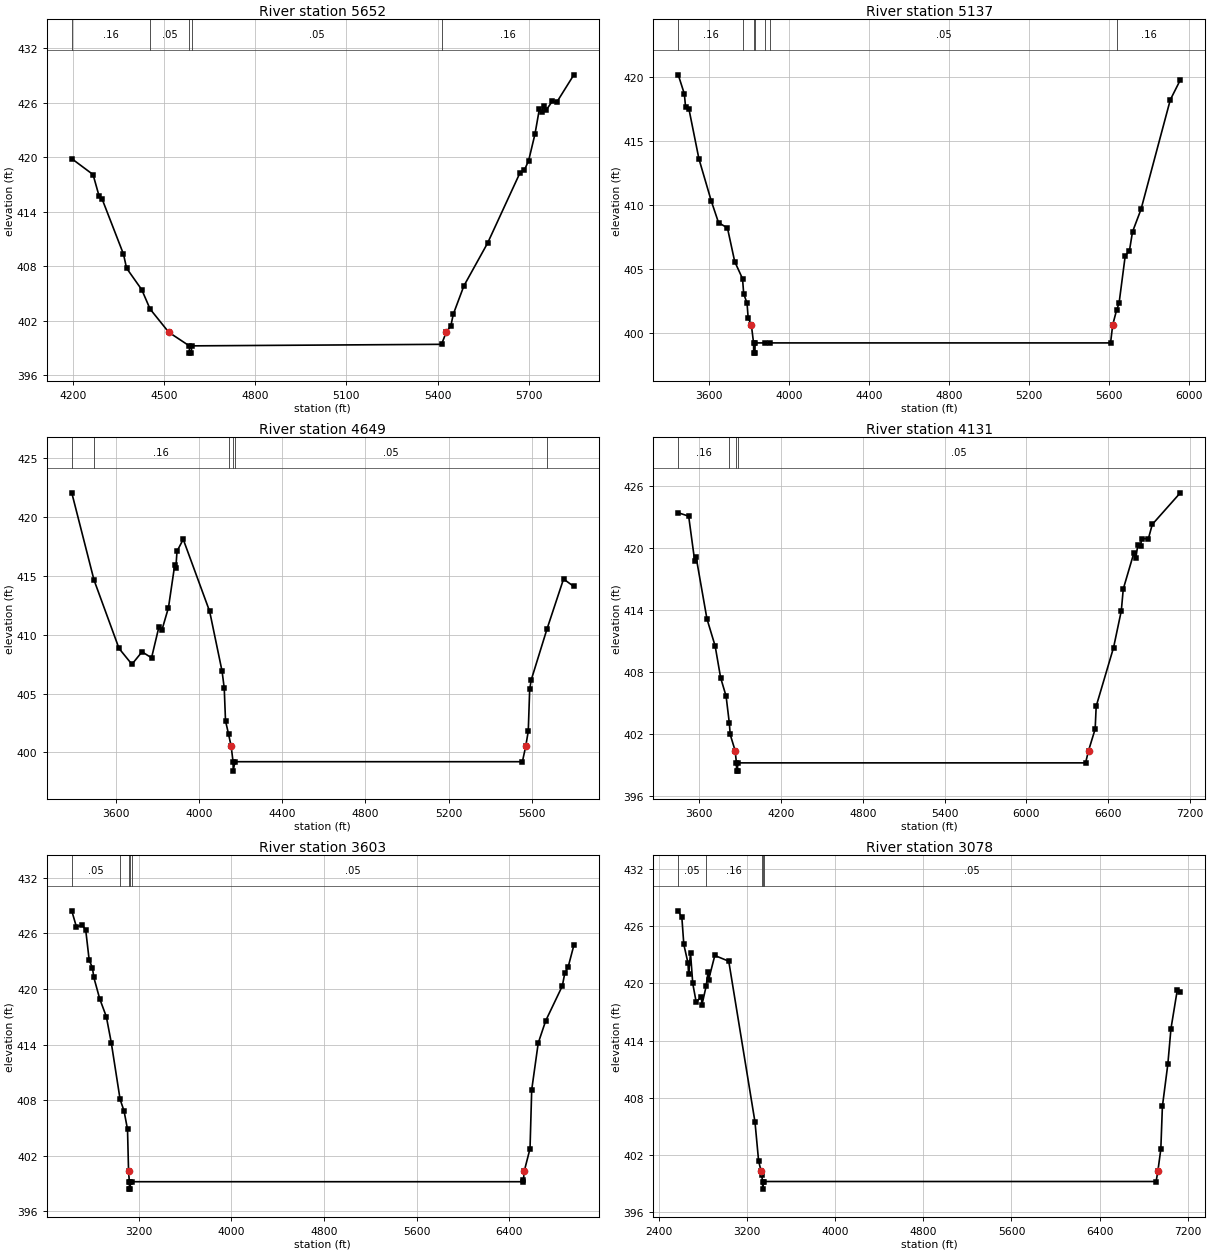
Type RM Length L Ch R = 1,5652,515,515,515
BEGIN DESCRIPTION:
WHITE OAK BRANCH 11.0
END DESCRIPTION:
XS GIS Cut Line= 3
      2854325.00      7021625.00      2853525.00      7021675.00
      2852875.02      7022224.98
#Sta/Elev= 30
  4195.8  419.83  4265.9  418.08  4286.0  415.68  4296.0  415.36  4366.1  409.31
  4376.2  407.77  4426.2  405.40  4453.6  403.27  4515.1  400.71  4582.8  399.21
  4583.4  398.41  4589.7  398.41  4590.3  399.21  5413.3  399.38  5428.5  400.71
  5443.9  401.41  5451.7  402.68  5486.8  405.82  5564.8  410.53  5671.4  418.27
  5685.7  418.55  5700.0  419.63  5720.8  422.54  5735.1  425.26  5742.8  424.97
  5749.4  425.64  5757.1  425.15  5778.0  426.17  5792.3  426.04  5848.8  429.07
#Mann=5,-1,0
  4195.8    0.16       0  4453.6    0.05       0  4582.8   0.033       0
  4590.3    0.05       0  5413.3    0.16       0
Bank Sta=4515.1,5428.5
Exp/Cntr=0.3,0.1

Type RM Length L Ch R = 1,5137,488,488,488
BEGIN DESCRIPTION:
WHITE OAK BRANCH 10.0
END DESCRIPTION:
XS GIS Cut Line= 3
      2854674.97      7020525.01      2853275.00      7021225.00
      2852775.01      7022024.99
#Sta/Elev= 30
  3445.7  420.20  3476.4  418.70  3482.0  417.72  3498.8  417.55  3549.1  413.62
  3610.6  410.33  3646.9  408.63  3691.6  408.21  3728.0  405.57  3767.0  404.24
  3772.7  403.06  3789.5  402.32  3795.1  401.16  3810.9  400.62  3822.1  399.21
  3822.7  398.41  3829.0  398.41  3829.6  399.21  3879.1  399.21  3906.2  399.21
  5605.8  399.21  5616.5  400.62  5635.6  401.76  5648.3  402.32  5679.0  406.02
  5700.2  406.44  5715.5  407.91  5758.0  409.67  5904.2  418.24  5954.3  419.80
#Mann=7,-1,0
  3445.7    0.16       0  3767.0    0.05       0  3822.1   0.033       0
  3829.6    0.05       0  3879.1     0.1       0  3906.2    0.05       0
  5635.6    0.16       0
Bank Sta=3810.9,5616.5
Exp/Cntr=0.3,0.1

Type RM Length L Ch R = 1,4649,518,518,518
BEGIN DESCRIPTION:
WHITE OAK BRANCH 9.0
END DESCRIPTION:
XS GIS Cut Line= 3
      2854625.01      7020375.00      2853075.00      7020775.00
      2852525.02      7021374.97
#Sta/Elev= 30
  3387.9  422.04  3494.8  414.64  3615.1  408.83  3677.1  407.48  3725.8  408.54
  3771.6  408.03  3807.2  410.67  3821.7  410.40  3853.0  412.30  3883.3  415.94
  3888.5  415.67  3894.0  417.08  3924.0  418.09  4051.1  411.97  4110.8  406.89
  4121.2  405.45  4127.3  402.68  4142.0  401.55  4154.5  400.51  4163.6  399.21
  4164.4  398.41  4172.3  399.21  5555.1  399.21  5571.1  400.51  5583.4  401.80
  5590.2  405.36  5597.6  406.15  5672.8  410.44  5753.0  414.72  5802.6  414.09
#Mann=6,-1,0
  3387.9    0.05       0  3494.8    0.16       0  4142.0    0.05       0
  4163.6   0.033       0  4172.3    0.05       0  5672.8    0.16       0
Bank Sta=4154.5,5571.1
Exp/Cntr=0.3,0.1

Type RM Length L Ch R = 1,4131,528,528,528
BEGIN DESCRIPTION:
WHITE OAK BRANCH 8.0
END DESCRIPTION:
XS GIS Cut Line= 3
      2854374.98      7020225.00      2852825.00      7020325.00
      2851225.02      7021724.98
#Sta/Elev= 30
  3448.1  423.44  3524.5  423.11  3568.3  418.81  3578.3  419.20  3658.5  413.16
  3718.6  410.53  3758.7  407.46  3798.8  405.67  3822.7  403.04  3828.9  401.96
  3864.9  400.40  3874.6  399.21  3875.4  398.41  3882.6  398.41  3883.3  399.21
  6433.0  399.21  6455.0  400.40  6503.3  402.49  6510.9  404.70  6638.1  410.38
  6695.0  413.95  6709.2  416.05  6787.1  419.55  6801.3  419.07  6815.5  420.28
  6836.4  420.22  6844.0  420.93  6893.4  420.93  6921.8  422.31  7127.3  425.37
#Mann=4,-1,0
  3448.1    0.16       0  3822.7    0.05       0  3874.6   0.033       0
  3883.3    0.05       0
Bank Sta=3864.9,6455
Exp/Cntr=0.3,0.1

Type RM Length L Ch R = 1,3603,525,525,525
BEGIN DESCRIPTION:
WHITE OAK BRANCH 7.0
END DESCRIPTION:
XS GIS Cut Line= 3
      2854925.04      7019675.00      2852525.00      7019875.00
      2851374.99      7021425.01
#Sta/Elev= 30
  2619.8  428.44  2660.0  426.71  2710.1  426.90  2740.3  426.38  2770.4  423.11
  2798.0  422.32  2810.5  421.25  2860.7  418.97  2918.4  417.02  2961.0  414.23
  3037.3  408.10  3071.4  406.85  3101.5  404.86  3110.5  400.34  3117.2  399.21
  3118.0  398.41  3125.2  398.41  3126.0  399.21  3136.9  399.21  6514.8  399.21
  6522.4  399.36  6529.4  400.34  6579.5  402.78  6594.1  409.13  6650.4  414.17
  6715.1  416.58  6858.6  420.33  6880.0  421.72  6908.4  422.35  6958.2  424.72
#Mann=5,-1,0
  2619.8    0.05       0  3037.3    0.16       0  3117.2   0.033       0
  3126.0    0.16       0  3136.9    0.05       0
Bank Sta=3110.5,6529.4
Exp/Cntr=0.3,0.1

Type RM Length L Ch R = 1,3078,515,515,515
BEGIN DESCRIPTION:
WHITE OAK BRANCH 6.0
END DESCRIPTION:
XS GIS Cut Line= 3
      2854674.99      7019025.00      2852275.00      7019425.00
      2850675.02      7020824.98
#Sta/Elev= 30
  2573.9  427.63  2606.8  426.93  2624.6  424.10  2662.6  422.14  2667.7  420.96
  2685.4  423.19  2705.7  420.00  2736.1  418.10  2784.3  418.56  2789.3  417.76
  2827.4  419.72  2845.1  421.25  2850.2  420.41  2905.9  422.94  3032.6  422.34
  3270.9  405.45  3303.8  401.36  3326.5  400.29  3331.4  399.92  3339.9  399.21
  3340.7  398.41  3348.9  399.21  6913.3  399.21  6929.0  400.28  6956.0  402.60
  6970.3  407.09  7019.6  411.52  7048.1  415.26  7105.0  419.28  7133.0  419.08
#Mann=5,-1,0
  2573.9    0.05       0  2827.4    0.16       0  3331.4    0.05       0
  3339.9   0.033       0  3348.9    0.05       0
Bank Sta=3326.5,6929
Exp/Cntr=0.3,0.1

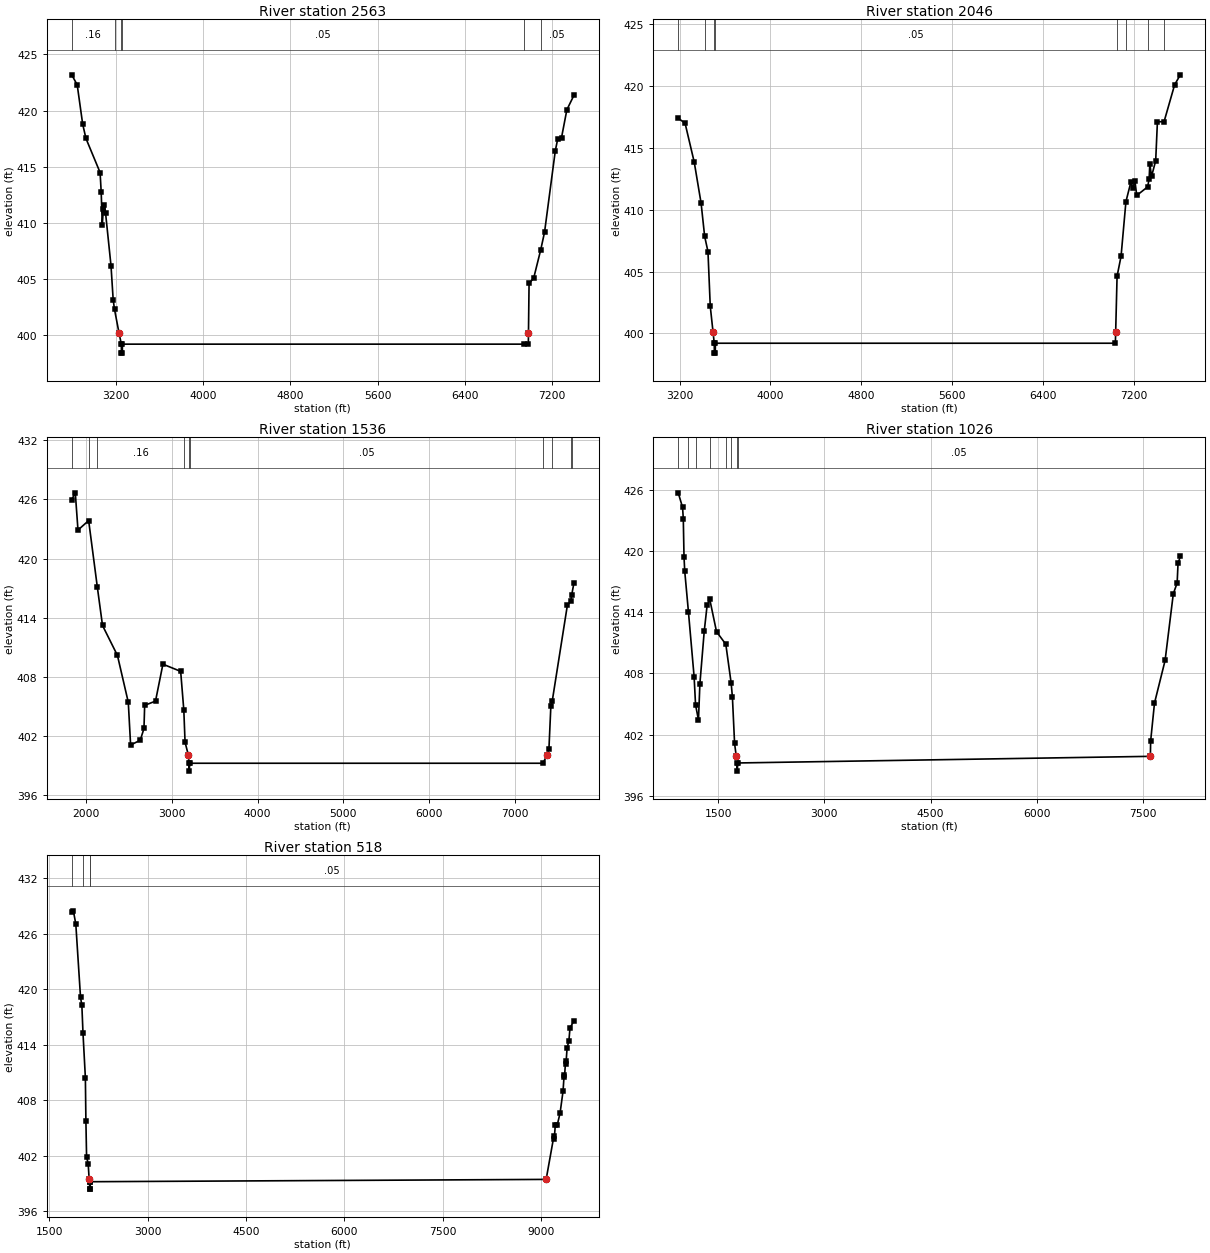
Type RM Length L Ch R = 1,2563,517,517,517
BEGIN DESCRIPTION:
WHITE OAK BRANCH 5.0
END DESCRIPTION:
XS GIS Cut Line= 3
      2854225.05      7018975.00      2852025.00      7018975.00
      2850424.98      7020775.03
#Sta/Elev= 30
  2792.9  423.19  2842.9  422.29  2892.9  418.81  2922.9  417.53  3052.9  414.49
  3062.9  412.76  3072.9  409.82  3082.9  411.27  3092.9  411.56  3102.9  410.90
  3152.9  406.21  3172.9  403.17  3185.1  402.31  3226.3  400.22  3247.9  399.21
  3248.9  398.41  3256.9  398.41  3257.9  399.21  6944.6  399.21  6983.6  399.21
  6984.9  400.22  6990.3  404.61  7032.9  405.10  7097.3  407.61  7132.4  409.18
  7231.1  416.43  7252.8  417.46  7288.0  417.59  7337.3  420.08  7401.3  421.35
#Mann=6,-1,0
  2792.9    0.16       0  3185.1    0.05       0  3247.9   0.033       0
  3257.9    0.05       0  6944.6    0.08       0  7097.3    0.05       0
Bank Sta=3226.3,6984.9
Exp/Cntr=0.3,0.1

Type RM Length L Ch R = 1,2046,510,510,510
BEGIN DESCRIPTION:
WHITE OAK BRANCH 4.0
END DESCRIPTION:
XS GIS Cut Line= 3
      2853575.05      7018725.01      2851775.00      7018525.00
      2850375.00      7020725.00
#Sta/Elev= 30
  3188.4  417.40  3248.8  416.98  3329.3  413.84  3389.7  410.52  3420.8  407.85
  3450.0  406.62  3470.2  402.20  3494.6  400.12  3505.4  399.21  3506.4  398.41
  3514.4  398.41  3515.4  399.21  7035.7  399.21  7038.3  400.13  7050.6  404.62
  7085.7  406.24  7128.5  410.65  7172.0  412.23  7187.3  411.73  7208.4  412.28
  7223.7  411.15  7320.0  411.85  7332.9  412.51  7338.8  413.70  7354.1  412.70
  7390.5  413.96  7405.7  417.11  7464.1  417.11  7557.3  420.10  7607.2  420.90
#Mann=8,-1,0
  3188.4    0.16       0  3420.8    0.05       0  3505.4   0.033       0
  3515.4    0.05       0  7050.6    0.08       0  7128.5    0.05       0
  7320.0    0.08       0  7464.1    0.05       0
Bank Sta=3494.6,7038.3
Exp/Cntr=0.3,0.1

Type RM Length L Ch R = 1,1536,510,510,510
BEGIN DESCRIPTION:
WHITE OAK BRANCH 3.0
END DESCRIPTION:
XS GIS Cut Line= 3
      2854625.04      7018775.01      2851525.00      7018075.00
      2850324.99      7020475.02
#Sta/Elev= 30
  1829.6  425.99  1870.7  426.67  1902.1  422.89  2026.7  423.85  2127.7  417.12
  2188.5  413.20  2362.7  410.16  2489.4  405.40  2516.5  401.06  2629.3  401.55
  2672.5  402.74  2680.5  405.09  2807.2  405.52  2893.6  409.27  3100.9  408.54
  3137.7  404.60  3152.1  401.35  3191.7  400.00  3198.4  399.21  3199.4  398.41
  3208.4  399.21  7331.1  399.21  7375.4  400.00  7400.3  400.69  7422.6  405.00
  7439.2  405.55  7615.5  415.26  7655.5  415.66  7665.5  416.28  7691.0  417.47
#Mann=10,-1,0
  1829.6    0.16       0  2026.7    0.05       0  2127.7    0.16       0
  3137.7    0.05       0  3198.4   0.033       0  3208.4    0.05       0
  7331.1    0.07       0  7439.2    0.05       0  7655.5    0.08       0
  7665.5    0.05       0
Bank Sta=3191.7,7375.4
Exp/Cntr=0.3,0.1

Type RM Length L Ch R = 1,1026,508,508,508
BEGIN DESCRIPTION:
WHITE OAK BRANCH 2.0
END DESCRIPTION:
XS GIS Cut Line= 3
      2855274.99      7018425.00      2851275.00      7017625.00
      2850175.01      7020424.97
#Sta/Elev= 30
   936.4  425.70   997.6  424.27  1007.8  423.16  1018.0  419.38  1028.2  418.01
  1080.2  414.04  1160.7  407.65  1180.8  404.92  1221.9  403.42  1242.3  406.99
  1303.5  412.14  1344.3  414.68  1381.8  415.24  1476.9  412.08  1608.0  410.85
  1683.5  407.04  1701.2  405.67  1731.8  401.12  1755.6  399.86  1767.6  399.21
  1768.6  398.41  1777.6  399.21  7601.2  399.86  7605.2  401.37  7659.4  405.08
  7809.0  409.26  7925.0  415.80  7979.2  416.86  7991.7  418.78  8023.9  419.46
#Mann=8,-1,0
   936.4    0.16       0  1080.2    0.05       0  1180.8    0.16       0
  1381.8    0.07       0  1608.0    0.16       0  1683.5    0.05       0
  1767.6   0.033       0  1777.6    0.05       0
Bank Sta=1755.6,7601.2
Exp/Cntr=0.3,0.1

Type RM Length L Ch R = 1,518,0,0,0
BEGIN DESCRIPTION:
WHITE OAK BRANCH 1.0
END DESCRIPTION:
XS GIS Cut Line= 3
      2854125.03      7017875.01      2851025.00      7017175.00
      2849025.01      7021174.98
#Sta/Elev= 30
  1846.1  428.31  1870.3  428.45  1907.6  427.02  1979.4  419.13  1999.9  418.24
  2016.8  415.30  2053.4  410.43  2061.4  405.78  2071.7  401.89  2096.6  401.14
  2110.9  399.46  2117.8  399.21  2118.7  398.41  2127.2  398.41  2128.1  399.21
  9074.3  399.46  9191.7  404.12  9197.2  403.84  9214.0  405.33  9242.0  405.29
  9286.7  406.63  9331.4  408.97  9348.2  410.72  9353.8  410.54  9370.5  412.22
  9376.1  411.92  9392.9  413.61  9420.9  414.43  9437.6  415.80  9496.3  416.56
#Mann=4,-1,0
  1846.1    0.16       0  2016.8    0.05       0  2117.8   0.033       0
  2128.1    0.05       0
Bank Sta=2110.9,9074.3
Exp/Cntr=0.3,0.1

Chan Stop Cuts=-1