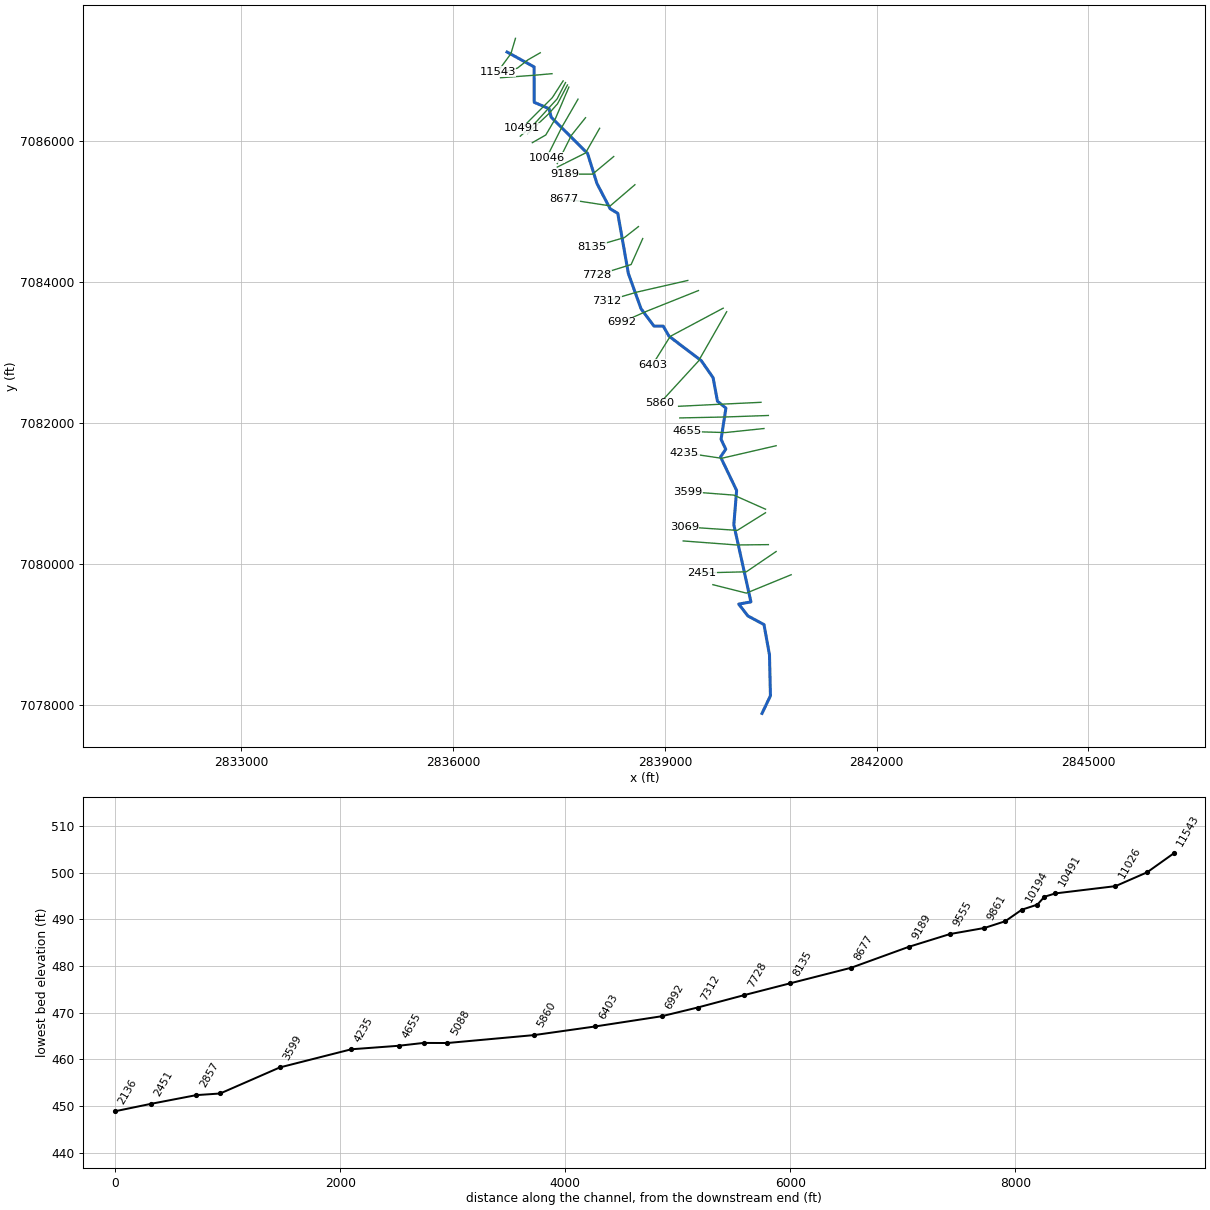
--- WOOD CREEK.prj (project) ---

Proj Title=WOOD CREEK Base Level Engineering
Current Plan=p01
Default Exp/Contr=0.3,0.1
English Units
Geom File=g01
Flow File=f01
Plan File=p01
Y Axis Title=Elevation
X Axis Title(PF)=Main Channel Distance
X Axis Title(XS)=Station
BEGIN DESCRIPTION:
WOOD CREEK
END DESCRIPTION:
DSS Export Rating Curves= 0
DSS Export Rating Curve Sorted= 0
DSS Export Volume Flow Curves= 0
DXF OffsetX= 0
DXF OffsetY= 0
DXF ScaleX= 1
DXF ScaleY= 10

--- WOOD CREEK.p01 (plan) ---

Plan Title=Multiple Run
Short Identifier=Multiple
Geom File=g01
Flow File=f01
Subcritical Flow
K Sum by GR= 0
Std Step Tol= 0.01
Critical Tol= 0.01
Num of Std Step Trials= 20
Max Error Tol= 0.3
Flow Tol Ratio= 0.001
Split Flow NTrial= 30
Split Flow Tol= 0.02
Split Flow Ratio= 0.02
Log Output Level= 0
Friction Slope Method= 1
Unsteady Friction Slope Method= 2
Unsteady Bridges Friction Slope Method= 1
Parabolic Critical Depth
Global Vel Dist=  1 , 1 , 1
Global Log Level= 0
CheckData=True
Encroach Param= -1, 0, 0, 0
BEGIN DESCRIPTION:
Multiple Run
END DESCRIPTION:

--- WOOD CREEK.f01 (steady flow) ---

Flow Title=Multiple
Number of Profiles=7
Profile Names=10-year,25-year,50-year,1pct_min,100-year,1pct_plu,500-year
River Rch & RM= WOOD CREEK,Reach-1,11543
     796    1070    1293     775    1547    3086    2205
River Rch & RM= WOOD CREEK,Reach-1,10491
     894    1210    1468     883    1762    3515    2531
River Rch & RM= WOOD CREEK,Reach-1,7312
    1411    1955    2409    1469    2932    5849    4333
Boundary for River Rch & Prof#=WOOD CREEK,Reach-1,1
Up Type=0
Dn Type=3
Dn Slope=0.005
Boundary for River Rch & Prof#=WOOD CREEK,Reach-1,2
Up Type=0
Dn Type=3
Dn Slope=0.005
Boundary for River Rch & Prof#=WOOD CREEK,Reach-1,3
Up Type=0
Dn Type=3
Dn Slope=0.005
Boundary for River Rch & Prof#=WOOD CREEK,Reach-1,4
Up Type=0
Dn Type=3
Dn Slope=0.005
Boundary for River Rch & Prof#=WOOD CREEK,Reach-1,5
Up Type=0
Dn Type=3
Dn Slope=0.005
Boundary for River Rch & Prof#=WOOD CREEK,Reach-1,6
Up Type=0
Dn Type=3
Dn Slope=0.005
Boundary for River Rch & Prof#=WOOD CREEK,Reach-1,7
Up Type=0
Dn Type=3
Dn Slope=0.005

--- WOOD CREEK.g01 (geometry) ---

Geom Title=Existing Conditions
Program Version=5.07

River Reach=WOOD CREEK      ,Reach-1
Reach XY= 30
       2836763.5      7087256.22      2837147.05      7087045.27
      2837148.43      7086543.28      2837358.64      7086453.39
      2837389.06      7086331.69       2837903.6      7085819.55
      2838037.44      7085391.48      2838223.74      7085034.79
      2838331.92      7084969.43      2838481.99      7084116.99
      2838660.88      7083618.07       2838845.4       7083370.7
      2838975.91      7083370.18      2839058.48       7083227.4
      2839515.14      7082880.64      2839682.21      7082639.33
      2839744.04      7082306.16      2839864.02      7082208.86
      2839795.45      7081765.46      2839861.63      7081625.83
      2839787.85      7081516.27      2840015.59      7081040.71
      2839975.98      7080554.77      2840218.17      7079461.26
      2840045.48      7079429.71      2840175.87      7079261.48
      2840403.23      7079139.77      2840481.09      7078710.27
      2840494.66      7078130.44      2840375.59      7077880.71

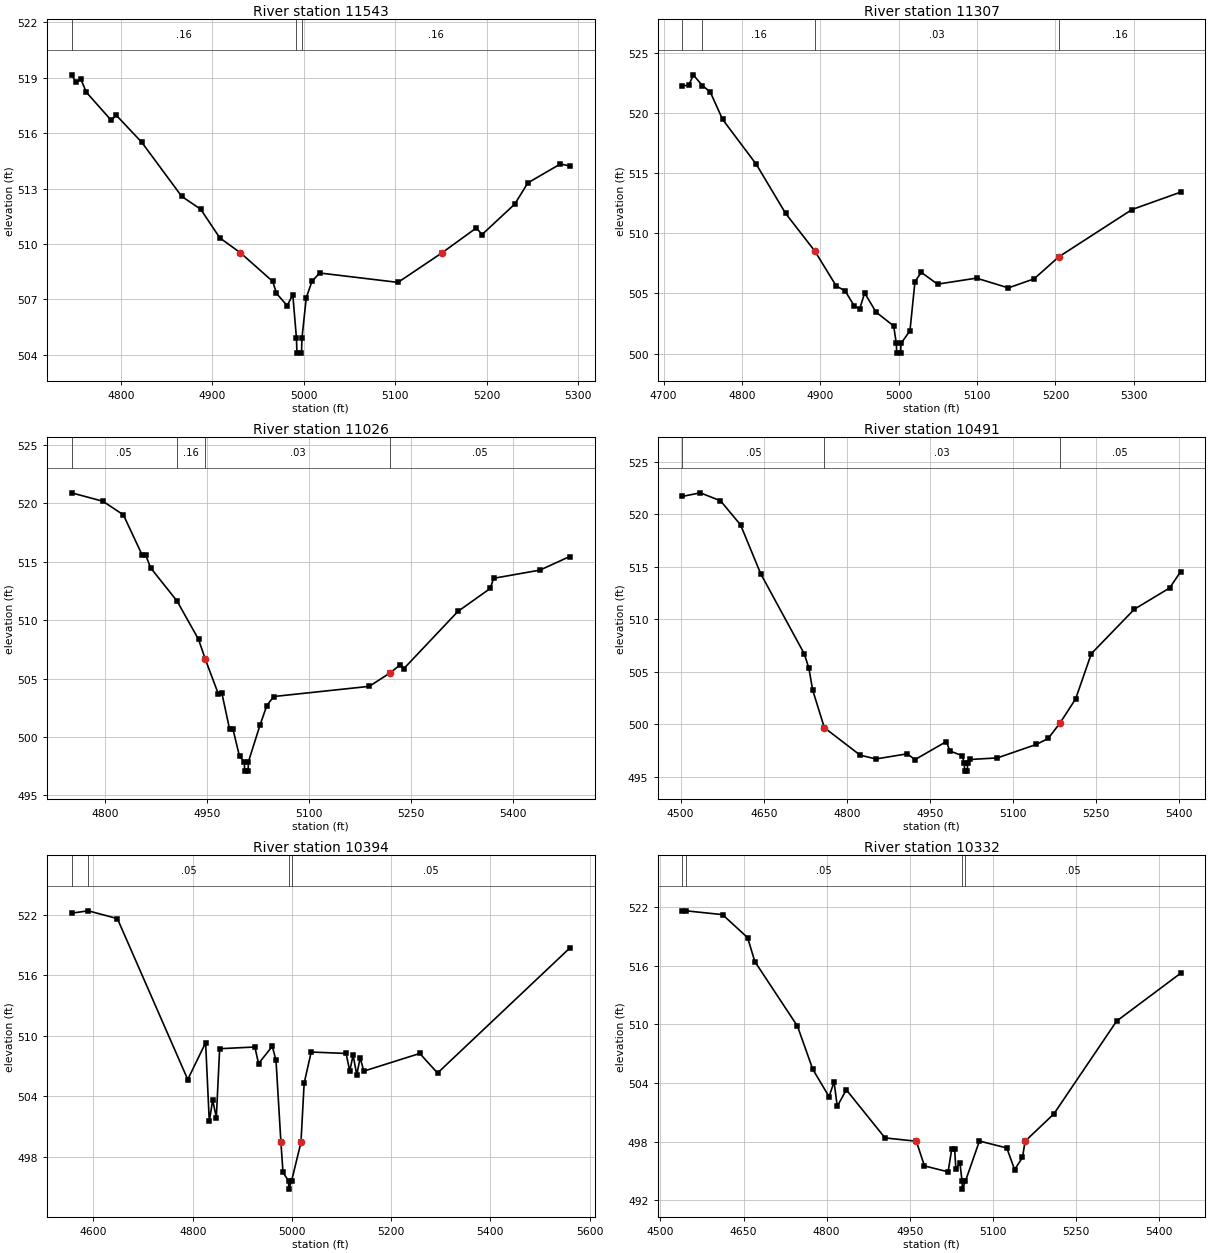
Type RM Length L Ch R = 1 ,11543   ,236,236,236
BEGIN DESCRIPTION:
WOOD CREEK 18.0
END DESCRIPTION:
XS GIS Cut Line= 3
      2836882.74       7087450.4      2836817.98      7087232.23
       2836630.5      7086976.58
#Sta/Elev= 30
  4746.1  519.16  4751.1  518.75  4756.3  518.92  4762.2  518.22  4789.6  516.69
  4794.8  516.98  4822.8  515.51  4866.5  512.58  4887.3  511.88  4908.2  510.33
  4930.8  509.52  4966.1  507.97  4970.1  507.33  4981.8  506.66    4988  507.25
    4992  504.89  4992.5  504.09  4997.5  504.09    4998  504.89  5002.7  507.09
  5008.9  507.97  5017.3  508.43    5103  507.92  5151.1  509.52  5188.7  510.87
  5194.9  510.51  5230.7  512.16    5245  513.31  5280.5  514.33  5290.7  514.23
#Mann= 3 ,-1 , 0
  4746.1     .16       0    4992     .07       0    4998     .16       0
Bank Sta=4930.8,5151.1
XS Rating Curve= 0 ,0
Exp/Cntr=0.3,0.1

Type RM Length L Ch R = 1 ,11307   ,281,281,281
BEGIN DESCRIPTION:
Mapping XS d99d542d
END DESCRIPTION:
XS GIS Cut Line= 4
      2837233.82      7087245.88      2837056.56      7087143.62
        2836910.      7087027.73      2836675.63       7086959.8
#Sta/Elev= 30
  4724.1  522.25  4732.2  522.29    4738  523.16  4749.7  522.25  4759.5  521.75
  4775.3  519.46  4818.4  515.72  4855.7  511.65    4893  508.52  4920.4  505.61
  4931.6  505.22  4943.5  503.94  4950.3  503.73  4956.6  505.03  4971.1  503.45
  4993.6   502.3    4997  500.84  4997.5  500.04  5002.5  500.04    5003  500.84
  5014.4   501.9  5020.8  505.98  5028.8  506.75  5049.6  505.77  5099.3  506.27
  5139.9  505.46  5172.8  506.21  5204.1  508.03  5297.8  511.97  5359.6  513.41
#Mann= 4 ,-1 , 0
  4724.1     .05       0  4749.7     .16       0    4893     .03       0
  5204.1     .16       0
Bank Sta=4893,5204.1
XS Rating Curve= 0 ,0
Exp/Cntr=0.3,0.1

Type RM Length L Ch R = 1 ,11026   ,535,535,535
BEGIN DESCRIPTION:
Mapping XS 93c9a1c1
END DESCRIPTION:
XS GIS Cut Line= 3
      2837400.79      7086949.34      2837169.04      7086928.89
       2836671.4      7086891.39
#Sta/Elev= 30
  4751.3  520.88  4797.3  520.16  4827.4     519    4855  515.56    4860  515.58
  4867.5  514.46  4906.2  511.63  4937.8  508.35  4947.9  506.63  4967.1  503.65
  4972.1  503.74  4983.5  500.65  4988.5  500.65    4998  498.34  5005.1  497.88
  5005.6  497.08  5010.6  497.08  5011.1  497.88  5028.1  501.01  5038.1  502.68
  5048.2  503.46  5188.6  504.33  5218.7  505.46  5234.5  506.19  5239.5  505.85
  5318.9  510.74  5366.3   512.7  5371.3  513.57  5439.3  514.27    5483  515.43
#Mann= 4 ,-1 , 0
  4751.3     .05       0  4906.2     .16       0  4947.9     .03       0
  5218.7     .05       0
Bank Sta=4947.9,5218.7
XS Rating Curve= 0 ,0
Exp/Cntr=0.3,0.1

Type RM Length L Ch R = 1 ,10491   ,97,97,97
BEGIN DESCRIPTION:
Mapping XS d5e26bee
END DESCRIPTION:
XS GIS Cut Line= 4
      2837557.58      7086847.06      2837404.22       7086608.5
      2837261.07      7086465.35      2836968.99      7086173.27
#Sta/Elev= 30
  4503.2  521.72  4535.5  522.06  4571.9   521.3  4608.2     519  4644.5  514.34
  4723.1  506.71  4731.5  505.33  4738.3  503.25  4759.4  499.66  4824.1  497.04
  4852.4  496.68  4908.9  497.17  4923.1  496.62  4979.6  498.34    4986  497.44
  5007.9     497    5012  496.32  5012.5  495.52  5017.5  495.52    5018  496.32
  5022.1  496.63  5071.6  496.78  5142.3  498.07  5163.5  498.64  5184.7   500.1
    5213  502.41  5241.3  506.72    5319  510.96  5382.7  512.99  5402.3  514.52
#Mann= 3 , 0 , 0
  4503.2     .05       0  4759.4     .03       0  5184.7     .05       0
Bank Sta=4759.4,5184.7
XS Rating Curve= 0 ,0
Exp/Cntr=0.3,0.1

Type RM Length L Ch R = 1 ,10394   ,62,62,62
BEGIN DESCRIPTION:
Mapping XS 441b2b1d
END DESCRIPTION:
XS GIS Cut Line= 5
      2837591.67      7086823.21      2837472.39      7086591.46
      2837298.56      7086400.59      2837165.63      7086254.03
      2836950.88      7086063.14
#Sta/Elev= 30
  4555.8  522.14  4589.5  522.37  4648.1   521.6    4790  505.66    4826   509.3
  4833.4   501.5  4840.2  503.62  4847.6  501.89  4854.3  508.71  4925.3  508.88
  4932.7  507.24  4960.4  508.95  4967.9  507.55  4977.8  499.43    4982  496.46
  4993.2   495.6  4993.7   494.8  4999.2   495.6  5018.2  499.43  5024.6  505.28
  5038.8  508.38  5109.2  508.24  5116.5   506.5  5123.3  508.07  5130.7  506.12
  5137.5  507.82  5144.9  506.49  5257.7  508.24  5293.5   506.3  5559.8  518.67
#Mann= 4 ,-1 , 0
  4555.8     .08       0  4589.5     .05       0  4993.2     .03       0
  4999.2     .05       0
Bank Sta=4977.8,5018.2
XS Rating Curve= 0 ,0
Exp/Cntr=0.3,0.1

Type RM Length L Ch R = 1 ,10332   ,138,138,138
BEGIN DESCRIPTION:
Mapping XS 1c04b2d6
END DESCRIPTION:
XS GIS Cut Line= 4
      2837618.94      7086789.13       2837479.2      7086523.29
      2837353.09      7086380.14      2837056.55      7086100.64
#Sta/Elev= 30
  4539.8  521.61  4546.4  521.65  4612.2  521.26  4657.4   518.9  4670.4  516.45
  4747.3  509.83    4775   505.4  4804.3   502.6  4813.4  504.11  4819.1  501.61
  4835.5   503.3  4905.3  498.37  4961.8  498.03  4976.4   495.5  5019.1  494.89
  5025.7  497.24  5030.9  497.24  5033.1  495.18  5040.4  495.82  5044.3  493.92
  5044.8  493.12  5050.3  493.92  5075.6  498.05    5125  497.34  5139.1  495.12
  5153.3  496.37    5158  498.03  5209.9  500.83  5323.2  510.35  5438.4  515.24
#Mann= 4 ,-1 , 0
  4539.8     .08       0  4546.4     .05       0  5044.3     .03       0
  5050.3     .05       0
Bank Sta=4961.8,5158
XS Rating Curve= 0 ,0
Exp/Cntr=0.3,0.1

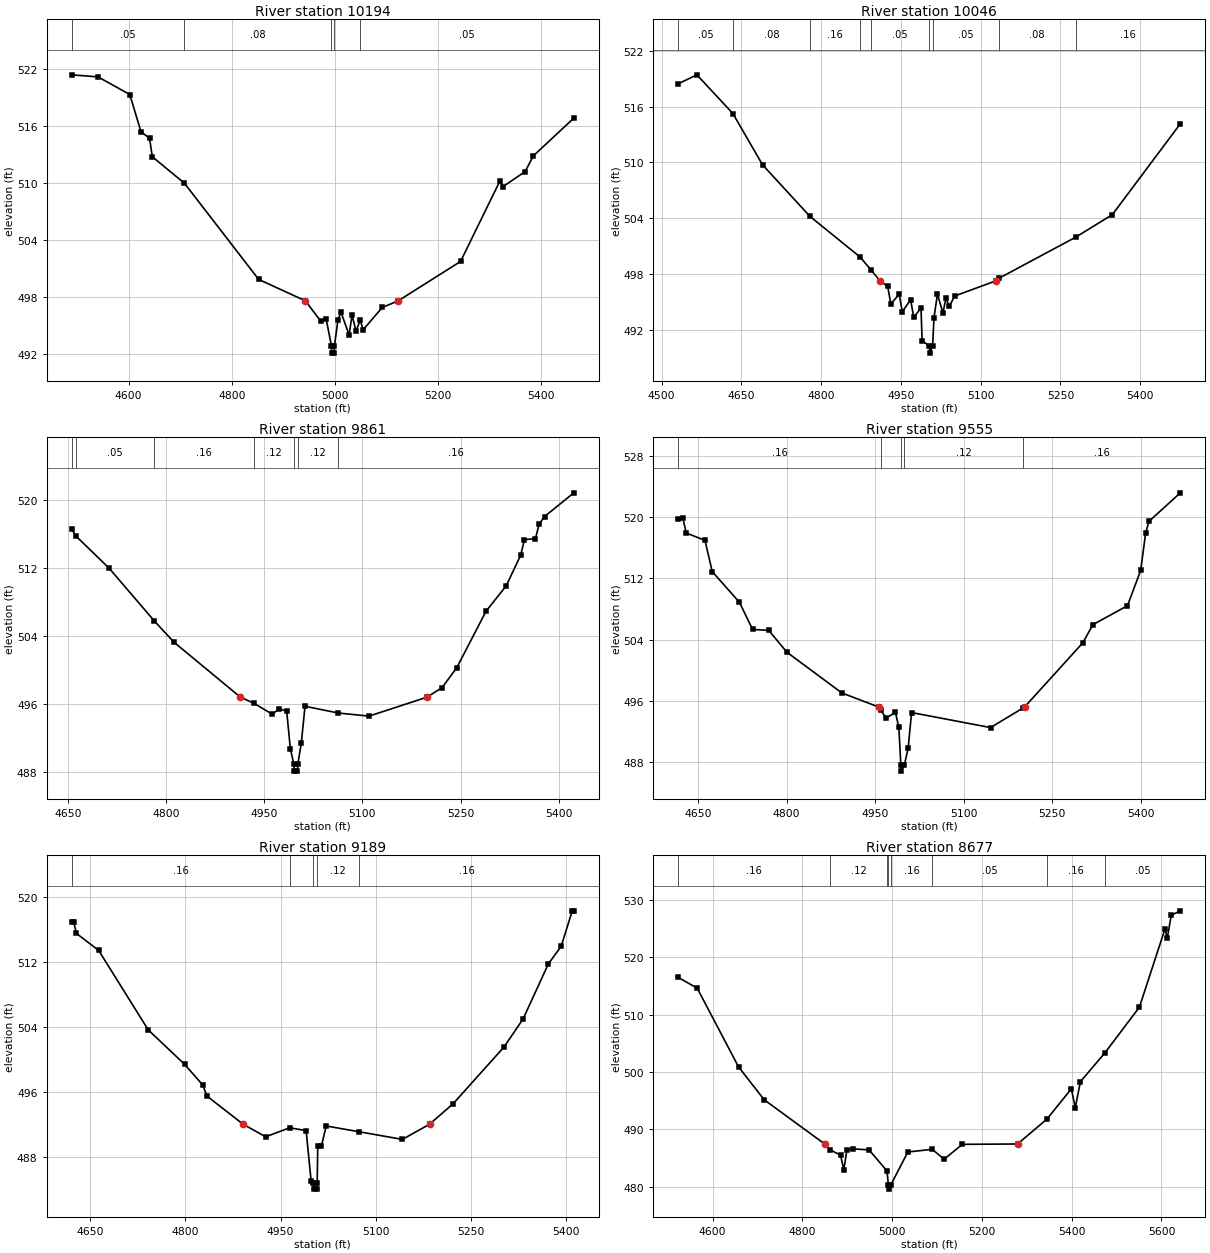
Type RM Length L Ch R = 1 ,10194   ,148,148,148
BEGIN DESCRIPTION:
Mapping XS 66c49510
END DESCRIPTION:
XS GIS Cut Line= 4
      2837639.41       7086758.5      2837448.53      7086311.97
      2837312.19       7086080.2      2837121.36      7085971.15
#Sta/Elev= 30
  4489.6  521.42  4540.7   521.2  4602.2  519.34  4623.9  515.42  4640.5  514.72
  4645.9  512.77  4708.3  509.97  4852.3  499.82    4943  497.56  4973.3  495.38
  4983.3  495.62  4993.4  492.84  4993.9  492.04  4998.9  492.04  4999.4  492.84
  5006.2  495.56    5012  496.36  5027.7  493.97  5033.5  496.03  5041.3  494.37
  5049.3  495.52    5055   494.5  5092.1  496.86    5123  497.56  5244.1  501.72
  5320.4  510.21  5326.2  509.61  5369.4  511.21  5385.2  512.86  5463.9  516.85
#Mann= 5 ,-1 , 0
  4489.6     .05       0  4708.3     .08       0  4993.4     .07       0
  4999.4     .08       0  5049.3     .05       0
Bank Sta=4943,5123
XS Rating Curve= 0 ,0
Exp/Cntr=0.3,0.1

Type RM Length L Ch R = 1 ,10046   ,185,185,185
BEGIN DESCRIPTION:
Mapping XS 123ac919
END DESCRIPTION:
XS GIS Cut Line= 3
      2837768.91      7086588.04      2837540.55      7086192.68
      2837322.43      7085756.44
#Sta/Elev= 30
  4531.2  518.44  4566.3   519.4  4634.1  515.24  4689.8  509.75    4779  504.22
  4873.1  499.87  4893.5   498.5  4910.3  497.33  4925.2  496.71    4931  494.83
  4946.8  495.88  4952.6     494  4968.3  495.29  4974.1  493.39  4987.8  494.41
  4989.9  490.86  5003.7  490.36  5004.2  489.56  5009.7  490.36  5012.2  493.36
  5018.7  495.89    5029  493.85  5034.6  495.45  5041.1  494.59  5051.4  495.69
  5129.6  497.33  5134.2  497.58  5278.7  501.99  5347.7  504.41  5475.5  514.15
#Mann= 9 ,-1 , 0
  4531.2     .05       0  4634.1     .08       0    4779     .16       0
  4873.1     .08       0  4893.5     .05       0  5003.7     .04       0
  5009.7     .05       0  5134.2     .08       0  5278.7     .16       0
Bank Sta=4910.3,5129.6
XS Rating Curve= 0 ,0
Exp/Cntr=0.3,0.1

Type RM Length L Ch R = 1 ,9861    ,306,306,306
BEGIN DESCRIPTION:
WOOD CREEK 15.0
END DESCRIPTION:
XS GIS Cut Line= 3
        2837875.        7086325.        2837675.        7086075.
      2837474.98      7085674.97
#Sta/Elev= 30
  4655.8  516.55  4662.7  515.72  4712.6  512.01    4782  505.78  4811.9  503.29
  4913.5  496.82  4933.9  496.11  4962.3  494.82  4972.7  495.45  4984.3  495.17
  4989.9  490.75  4995.3  488.92  4995.8  488.12  5000.8  488.12  5001.3  488.92
  5006.7  491.45  5012.3  495.75  5063.4  494.95  5110.1  494.59  5198.9  496.82
  5221.9  497.95  5244.3  500.29    5289  506.93  5319.7   509.9  5342.1  513.54
  5347.7  515.36  5364.5  515.45  5370.1  517.17  5378.4  518.06  5423.2  520.85
#Mann= 7 ,-1 , 0
  4655.8     .16       0  4662.7     .05       0    4782     .16       0
  4933.9     .12       0  4995.3     .07       0  5001.3     .12       0
  5063.4     .16       0
Bank Sta=4913.5,5198.9
XS Rating Curve= 0 ,0
Exp/Cntr=0.3,0.1

Type RM Length L Ch R = 1 ,9555    ,366,366,366
BEGIN DESCRIPTION:
WOOD CREEK 14.0
END DESCRIPTION:
XS GIS Cut Line= 3
      2838074.98      7086174.97        2837875.        7085825.
      2837474.99        7085625.
#Sta/Elev= 30
  4616.6  519.69  4624.5  519.82  4630.2  517.92  4661.9  516.96  4674.2  512.88
  4720.2  508.88  4742.5  505.33  4769.9   505.2  4800.8  502.34  4893.7  497.03
  4956.2  495.19  4959.6  494.78  4968.6  493.75  4984.4  494.49  4990.2  492.54
  4993.6  487.62  4994.1  486.82  4999.6  487.62    5006  489.85  5011.8  494.47
  5145.5  492.51  5200.9  495.08  5203.2   495.2    5302   503.6  5318.8  505.95
  5377.4  508.43  5399.8  513.04  5408.2  517.93  5413.8  519.44  5466.9  523.17
#Mann= 5 ,-1 , 0
  4616.6     .16       0  4959.6     .12       0  4993.6     .07       0
  4999.6     .12       0  5200.9     .16       0
Bank Sta=4956.2,5203.2
XS Rating Curve= 0 ,0
Exp/Cntr=0.3,0.1

Type RM Length L Ch R = 1 ,9189    ,512,512,512
BEGIN DESCRIPTION:
WOOD CREEK 13.0
END DESCRIPTION:
XS GIS Cut Line= 3
      2838275.01      7085775.01        2837975.        7085525.
      2837575.03        7085525.
#Sta/Elev= 30
  4621.3  516.87  4624.6  516.87  4628.5  515.51  4663.6  513.42  4741.7  503.65
    4799  499.41  4827.6  496.87  4834.1  495.52    4891  492.06  4926.6  490.51
  4964.4  491.62  4990.3  491.27  4998.2  485.05  5001.7  484.88  5002.2  484.08
  5007.2  484.08  5007.7  484.88  5008.6  489.33  5014.3  489.33  5021.8  491.84
  5073.8  491.13  5141.8  490.19  5184.7  492.06  5221.8  494.58  5301.8  501.54
  5331.8  504.98  5371.8  511.78  5391.8  513.91  5409.3  518.28  5411.8  518.28
#Mann= 5 ,-1 , 0
  4621.3     .16       0  4964.4     .12       0  5001.7     .07       0
  5007.7     .12       0  5073.8     .16       0
Bank Sta=4891,5184.7
XS Rating Curve= 0 ,0
Exp/Cntr=0.3,0.1

Type RM Length L Ch R = 1 ,8677    ,542,542,542
BEGIN DESCRIPTION:
WOOD CREEK 12.0
END DESCRIPTION:
XS GIS Cut Line= 3
      2838574.99      7085374.99        2838225.        7085075.
      2837575.01        7085175.
#Sta/Elev= 30
  4523.4  516.51  4565.6  514.64  4657.8  500.91  4714.9  495.18  4849.7  487.47
  4861.9  486.45    4885  485.52  4892.2  482.99  4899.3  486.44  4913.6  486.62
  4948.7  486.43  4988.6  482.76  4991.5   480.4    4992   479.6  4997.5   480.4
  5034.9  486.07  5089.2  486.54  5115.9  484.82  5156.4  487.41  5279.4  487.47
  5345.1  491.83  5399.2  497.09    5408  493.79  5419.4  498.33    5474  503.36
  5550.9  511.33  5607.9  524.98  5612.9  523.35  5621.8  527.35    5642  528.12
#Mann= 8 ,-1 , 0
  4523.4     .16       0  4861.9     .12       0  4988.6     .16       0
  4991.5     .07       0  4997.5     .16       0  5089.2     .05       0
  5345.1     .16       0    5474     .05       0
Bank Sta=4849.7,5279.4
XS Rating Curve= 0 ,0
Exp/Cntr=0.3,0.1

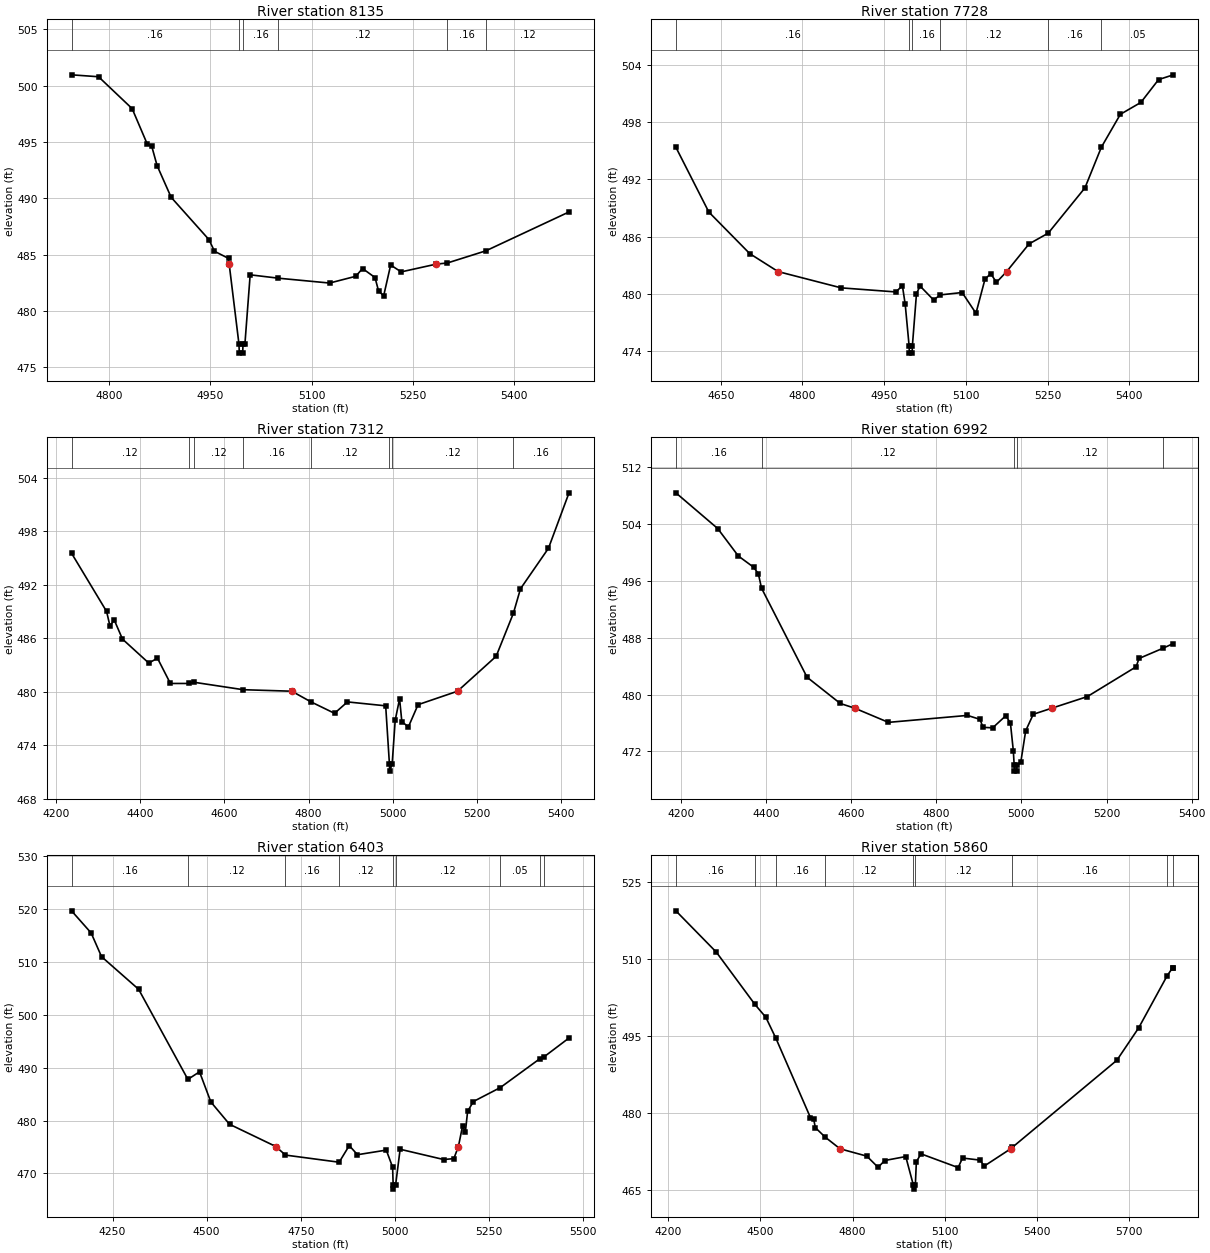
Type RM Length L Ch R = 1 ,8135    ,407,407,407
BEGIN DESCRIPTION:
WOOD CREEK 11.0
END DESCRIPTION:
XS GIS Cut Line= 3
      2838625.16      7084781.82        2838425.        7084625.
      2837961.04      7084490.99
#Sta/Elev= 30
  4744.4  500.97  4784.4   500.8  4834.2  497.97  4856.7  494.81  4863.1  494.66
  4871.2  492.91    4892   490.1  4948.1  486.34  4956.2  485.31    4977  484.68
    4978  484.17  4992.5  477.07    4993  476.27    4998  476.27  4998.5  477.07
  5001.3  477.07  5009.1  483.22    5051  482.92  5126.8  482.49  5165.6  483.09
  5175.6  483.78  5194.1  482.98  5199.3   481.8  5206.9  481.35  5217.3  484.09
  5232.9  483.48  5284.9  484.17  5301.3  484.27  5358.4  485.35  5481.6   488.8
#Mann= 6 ,-1 , 0
  4744.4     .16       0  4992.5     .07       0  4998.5     .16       0
    5051     .12       0  5301.3     .16       0  5358.4     .12       0
Bank Sta=4978,5284.9
XS Rating Curve= 0 ,0
Exp/Cntr=0.3,0.1

Type RM Length L Ch R = 1 ,7728    ,416,416,416
BEGIN DESCRIPTION:
Mapping XS 860f0748
END DESCRIPTION:
XS GIS Cut Line= 3
       2838685.9       7084612.5      2838520.98      7084243.61
      2838034.84      7084091.69
#Sta/Elev= 30
  4567.5  495.39    4628  488.58  4703.1  484.21  4755.2  482.32    4871  480.61
  4971.6  480.18  4983.4  480.85  4988.6  478.87  4995.7  474.55  4996.2  473.75
  5001.3  473.75  5001.8  474.55  5009.3  480.01  5015.9   480.8  5040.7  479.34
  5053.1  479.87  5093.1  480.12  5118.5  477.94    5135  481.51  5145.5  482.11
  5156.2  481.19  5174.8  482.32    5216  485.23  5251.2  486.36  5318.6  491.12
  5348.8   495.4  5383.6  498.85  5421.3   500.1  5453.8   502.5  5480.9     503
#Mann= 6 ,-1 , 0
  4567.5     .16       0  4995.7     .07       0  5001.8     .16       0
  5053.1     .12       0  5251.2     .16       0  5348.8     .05       0
Bank Sta=4755.2,5174.8
XS Rating Curve= 0 ,0
Exp/Cntr=0.3,0.1

Type RM Length L Ch R = 1 ,7312    ,320,320,320
BEGIN DESCRIPTION:
Mapping XS ac67ce94
END DESCRIPTION:
XS GIS Cut Line= 3
      2839323.91      7084017.91      2838603.45      7083852.99
      2838179.04       7083727.4
#Sta/Elev= 30
  4236.7  495.54  4319.9  489.01  4327.9  487.39  4338.2  488.04  4357.7   485.9
  4420.2  483.21  4440.8  483.76  4471.5  480.92  4515.3  480.92  4526.9  481.06
  4644.5  480.22  4759.9  480.05  4805.2  478.86  4861.4  477.57  4892.1  478.85
  4982.9  478.41  4991.8  471.88  4992.3  471.08  4998.3  471.88  5005.5  476.79
  5015.9  479.19  5021.3  476.64  5036.8  476.04  5059.8  478.54  5153.5  480.05
  5245.3  483.97  5286.3  488.81  5303.1  491.55  5369.6   496.1  5418.4  502.32
#Mann= 8 ,-1 , 0
  4236.7     .12       0  4515.3     .16       0  4526.9     .12       0
  4644.5     .16       0  4805.2     .12       0  4991.8     .07       0
  4998.3     .12       0  5286.3     .16       0
Bank Sta=4759.9,5153.5
XS Rating Curve= 0 ,0
Exp/Cntr=0.3,0.1

Type RM Length L Ch R = 1 ,6992    ,589,589,589
BEGIN DESCRIPTION:
WOOD CREEK 9.0
END DESCRIPTION:
XS GIS Cut Line= 3
      2839475.02      7083875.01        2838725.        7083575.
      2838395.11      7083427.64
#Sta/Elev= 30
  4187.9  508.42  4286.2  503.39  4334.7  499.52    4371  497.92  4381.8     497
  4389.2  494.99  4496.2  482.44  4574.3  478.74  4607.8  478.09  4687.4  476.08
  4873.2  477.06  4902.8   476.5  4909.5  475.38  4932.4  475.31  4963.4  477.02
  4974.2  475.94  4980.9   472.1    4983  470.01  4983.5  469.21    4989  469.21
  4989.5  470.01  4998.4  470.44    5010  474.89  5027.8  477.22    5072  478.09
  5154.8  479.71  5269.5  483.91  5276.3  485.08  5331.7   486.5    5357  487.19
#Mann= 5 ,-1 , 0
  4187.9     .16       0  4389.2     .12       0    4983     .07       0
  4989.5     .12       0  5331.7     .16       0
Bank Sta=4607.8,5072
XS Rating Curve= 0 ,0
Exp/Cntr=0.3,0.1

Type RM Length L Ch R = 1 ,6403    ,543,543,543
BEGIN DESCRIPTION:
WOOD CREEK 8.0
END DESCRIPTION:
XS GIS Cut Line= 3
      2839825.04      7083625.02        2839075.        7083225.
      2838825.02      7082825.04
#Sta/Elev= 30
  4141.1  519.67  4193.2  515.48  4220.8     511  4319.3  504.83  4450.2  487.79
  4481.1  489.22  4511.2  483.52  4560.8   479.3  4683.9  475.09  4709.4  473.47
  4852.1  472.12  4878.9  475.26  4900.8  473.54  4977.3  474.41  4994.1  471.19
  4995.6  467.83  4996.1  467.03  5002.1  467.83  5014.1  474.57  5129.7  472.63
  5156.8   472.8  5168.9  475.09  5179.8  478.91  5187.5  477.88  5193.4  481.74
  5208.7   483.6  5280.1  486.23  5384.8  491.67  5397.2  492.09  5462.8  495.62
#Mann= 9 ,-1 , 0
  4141.1     .16       0  4450.2     .12       0  4709.4     .16       0
  4852.1     .12       0  4995.6     .07       0  5002.1     .12       0
  5280.1     .05       0  5384.8     .16       0  5397.2     .05       0
Bank Sta=4683.9,5168.9
XS Rating Curve= 0 ,0
Exp/Cntr=0.3,0.1

Type RM Length L Ch R = 1 ,5860    ,772,772,772
BEGIN DESCRIPTION:
WOOD CREEK 7.0
END DESCRIPTION:
XS GIS Cut Line= 3
      2839874.98      7083574.97        2839475.        7082875.
      2838925.02      7082275.03
#Sta/Elev= 30
  4224.4  519.44  4356.1  511.39    4482  501.18  4517.3  498.69  4550.3  494.57
  4662.8  479.11  4672.8  478.94  4678.6  477.17  4710.4  475.33  4759.1  473.04
  4846.3  471.61    4883  469.43  4904.6  470.76    4973  471.53  4997.8  465.98
  4998.3  465.18  5004.3  465.98  5007.6  470.52  5022.7  472.06  5143.7  469.38
  5157.9  471.24  5214.7  470.84  5228.8  469.68  5314.7  473.04  5320.4  473.34
  5660.5   490.3  5731.4   496.6  5824.6  506.81    5842  508.32  5844.5  508.32
#Mann= 9 ,-1 , 0
  4224.4     .16       0    4482     .12       0  4550.3     .16       0
  4710.4     .12       0  4997.8     .07       0  5004.3     .12       0
  5320.4     .16       0  5824.6     .05       0    5842     .16       0
Bank Sta=4759.1,5314.7
XS Rating Curve= 0 ,0
Exp/Cntr=0.3,0.1

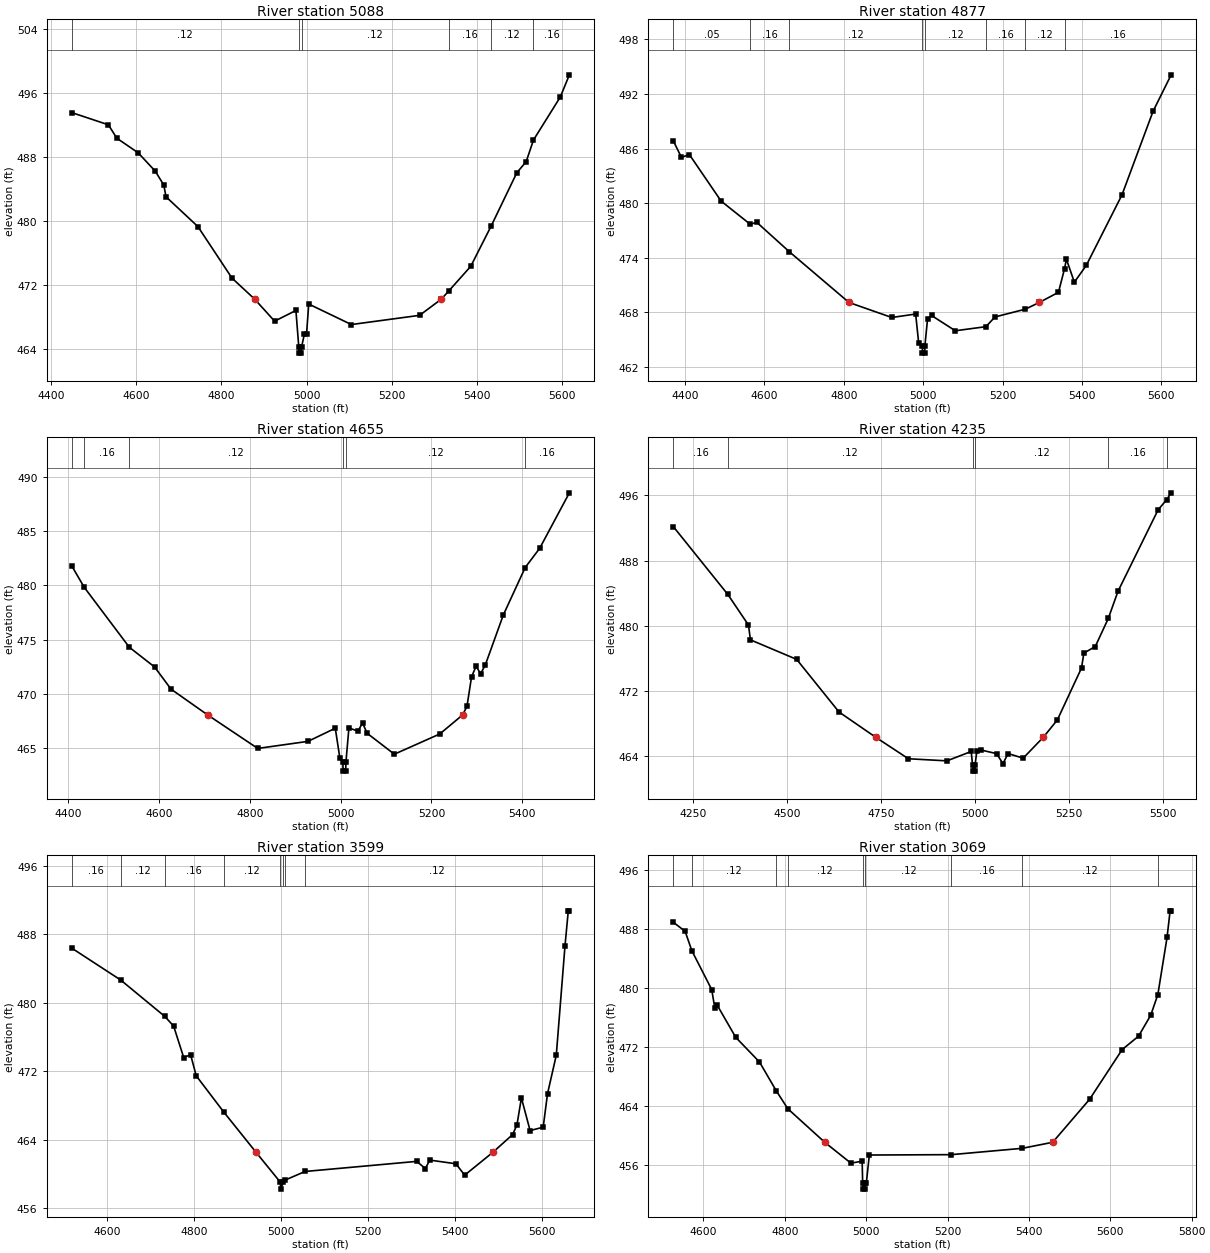
Type RM Length L Ch R = 1 ,5088    ,211,211,211
BEGIN DESCRIPTION:
Mapping XS 14d78f95
END DESCRIPTION:
XS GIS Cut Line= 3
      2840361.26      7082290.49      2839810.04      7082264.44
      2839193.72      7082234.06
#Sta/Elev= 30
  4448.1  493.53  4534.5     492  4554.5  490.32  4604.5   488.5  4644.6  486.21
  4664.6  484.48    4670     483  4744.7  479.29  4824.8  472.85  4878.1  470.22
  4924.9  467.47  4974.9  468.81  4981.6  464.28  4982.1  463.48  4987.8  463.48
  4988.3  464.28  4994.9  465.88  4999.9  465.88    5005  469.61  5105.1  467.05
  5265.3   468.2  5316.3  470.22  5334.6  471.29  5385.4  474.32  5433.6  479.38
  5493.5     486  5515.6   487.4  5532.7   490.1  5595.7  495.47    5617  498.24
#Mann= 6 ,-1 , 0
  4448.1     .12       0  4981.6     .07       0  4988.3     .12       0
  5334.6     .16       0  5433.6     .12       0  5532.7     .16       0
Bank Sta=4878.1,5316.3
XS Rating Curve= 0 ,0
Exp/Cntr=0.3,0.1

Type RM Length L Ch R = 1 ,4877    ,222,222,222
BEGIN DESCRIPTION:
Mapping XS 51f96e40
END DESCRIPTION:
XS GIS Cut Line= 3
      2840465.39      7082103.85      2839844.77      7082082.15
       2839211.1      7082069.13
#Sta/Elev= 30
  4370.3  486.84  4390.7  485.03  4410.7  485.34  4490.8  480.22  4563.9  477.68
  4580.8  477.88    4663  474.64  4813.1  469.07    4921  467.42  4981.1   467.8
  4988.7  464.61  4997.7   464.3  4998.2   463.5  5003.9   463.5  5004.4   464.3
  5011.1  467.28  5021.1  467.64  5081.1  465.96  5158.2  466.41  5181.1  467.48
  5257.2  468.33  5292.7  469.07  5341.1  470.19  5356.3  472.78  5361.1  473.83
  5381.1   471.3  5411.2  473.15  5501.2  480.91  5579.5   490.1  5625.1  494.11
#Mann= 8 ,-1 , 0
  4370.3     .05       0  4563.9     .16       0    4663     .12       0
  4997.7     .07       0  5004.4     .12       0  5158.2     .16       0
  5257.2     .12       0  5356.3     .16       0
Bank Sta=4813.1,5292.7
XS Rating Curve= 0 ,0
Exp/Cntr=0.3,0.1

Type RM Length L Ch R = 1 ,4655    ,420,420,420
BEGIN DESCRIPTION:
Mapping XS 07567577
END DESCRIPTION:
XS GIS Cut Line= 3
      2840402.91      7081918.96      2839856.05      7081861.67
      2839309.62      7081877.28
#Sta/Elev= 30
  4407.4  481.82  4435.3  479.82  4534.6   474.3  4590.3  472.48  4626.5  470.44
    4707  468.07  4817.5  464.98  4928.1  465.63  4988.3  466.84  4998.3  464.11
    5005  463.69  5005.5  462.89  5011.2  462.89  5011.7  463.69  5018.3  466.87
  5038.3  466.57  5048.3  467.34  5058.3  466.38  5118.4  464.45  5218.4  466.31
  5268.9  468.07  5278.4  468.87  5288.4  471.57  5298.4  472.54  5308.4  471.87
  5318.4  472.63  5358.5  477.28  5406.6  481.64  5438.5  483.41  5503.9  488.52
#Mann= 6 ,-1 , 0
  4407.4     .12       0  4435.3     .16       0  4534.6     .12       0
    5005     .07       0  5011.7     .12       0  5406.6     .16       0
Bank Sta=4707,5268.9
XS Rating Curve= 0 ,0
Exp/Cntr=0.3,0.1

Type RM Length L Ch R = 1 ,4235    ,636,636,636
BEGIN DESCRIPTION:
WOOD CREEK 4.0
END DESCRIPTION:
XS GIS Cut Line= 3
      2840575.04      7081675.01      2839803.97      7081497.08
      2839275.01        7081575.
#Sta/Elev= 30
  4196.5  492.16  4341.7  483.83  4396.7  480.07  4401.8  478.26    4525  475.86
  4637.8   469.4  4735.8  466.29  4822.6  463.66  4925.2   463.4  4989.8  464.55
  4993.5  462.94    4994  462.14  4999.8  462.14  5000.3  462.94  5004.9  464.58
  5017.1  464.72  5057.5  464.29  5074.6  463.05  5087.9   464.3  5128.3  463.73
  5181.8  466.29  5219.3  468.42  5283.7   474.8    5290  476.63  5320.4  477.44
    5355  480.88    5381  484.23  5487.7  494.22  5510.6  495.47  5522.5  496.31
#Mann= 6 ,-1 , 0
  4196.5     .16       0  4341.7     .12       0  4993.5     .07       0
  5000.3     .12       0    5355     .16       0  5510.6     .05       0
Bank Sta=4735.8,5181.8
XS Rating Curve= 0 ,0
Exp/Cntr=0.3,0.1

Type RM Length L Ch R = 1 ,3599    ,530,530,530
BEGIN DESCRIPTION:
WOOD CREEK 3.0
END DESCRIPTION:
XS GIS Cut Line= 3
      2840425.02      7080774.99        2839975.        7080975.
      2839324.99        7081025.
#Sta/Elev= 30
  4518.9   486.4  4631.9  482.66  4733.1  478.42  4753.5  477.29  4776.8   473.6
  4792.5  473.95  4805.5  471.48  4868.5  467.27  4943.3  462.53    4999  459.05
  4999.5  458.25  5005.9  459.05  5010.5  459.32  5055.6  460.31  5312.3  461.49
  5332.3  460.65  5342.3  461.64  5402.5  461.21  5422.6  459.88    5487  462.53
  5532.9  464.62  5542.9  465.77    5553   468.9    5573  465.09  5603.1  465.48
  5613.1   469.4  5633.2  473.88  5653.3  486.69  5660.8  490.74  5663.3  490.74
#Mann= 8 ,-1 , 0
  4518.9     .16       0  4631.9     .12       0  4733.1     .16       0
  4868.5     .12       0    4999     .07       0  5005.9     .12       0
  5010.5     .16       0  5055.6     .12       0
Bank Sta=4943.3,5487
XS Rating Curve= 0 ,0
Exp/Cntr=0.3,0.1

Type RM Length L Ch R = 1 ,3069    ,212,212,212
BEGIN DESCRIPTION:
WOOD CREEK 2.0
END DESCRIPTION:
XS GIS Cut Line= 3
      2840424.99      7080724.99        2840025.        7080475.
      2839274.95        7080525.
#Sta/Elev= 30
  4526.2  488.89  4555.1  487.68  4571.8  485.02  4620.5  479.76  4628.2  477.23
  4634.1  477.63  4679.5  473.28  4737.9  469.93  4779.2  466.01  4807.7  463.57
  4898.3  459.03  4962.5   456.2  4990.2  456.46  4991.5  453.47    4992  452.67
  4997.9  452.67  4998.4  453.47  5000.4  453.47  5007.9   457.3  5209.5  457.35
  5383.7  458.21  5458.5  459.03  5549.1  464.86  5629.3  471.62  5669.4  473.43
  5699.4  476.28  5716.9  479.08  5739.5  486.83    5747  490.45  5749.6  490.45
#Mann= 9 ,-1 , 0
  4526.2     .16       0  4571.8     .12       0  4779.2     .16       0
  4807.7     .12       0  4991.5     .07       0  4998.4     .12       0
  5209.5     .16       0  5383.7     .12       0  5716.9     .16       0
Bank Sta=4898.3,5458.5
XS Rating Curve= 0 ,0
Exp/Cntr=0.3,0.1

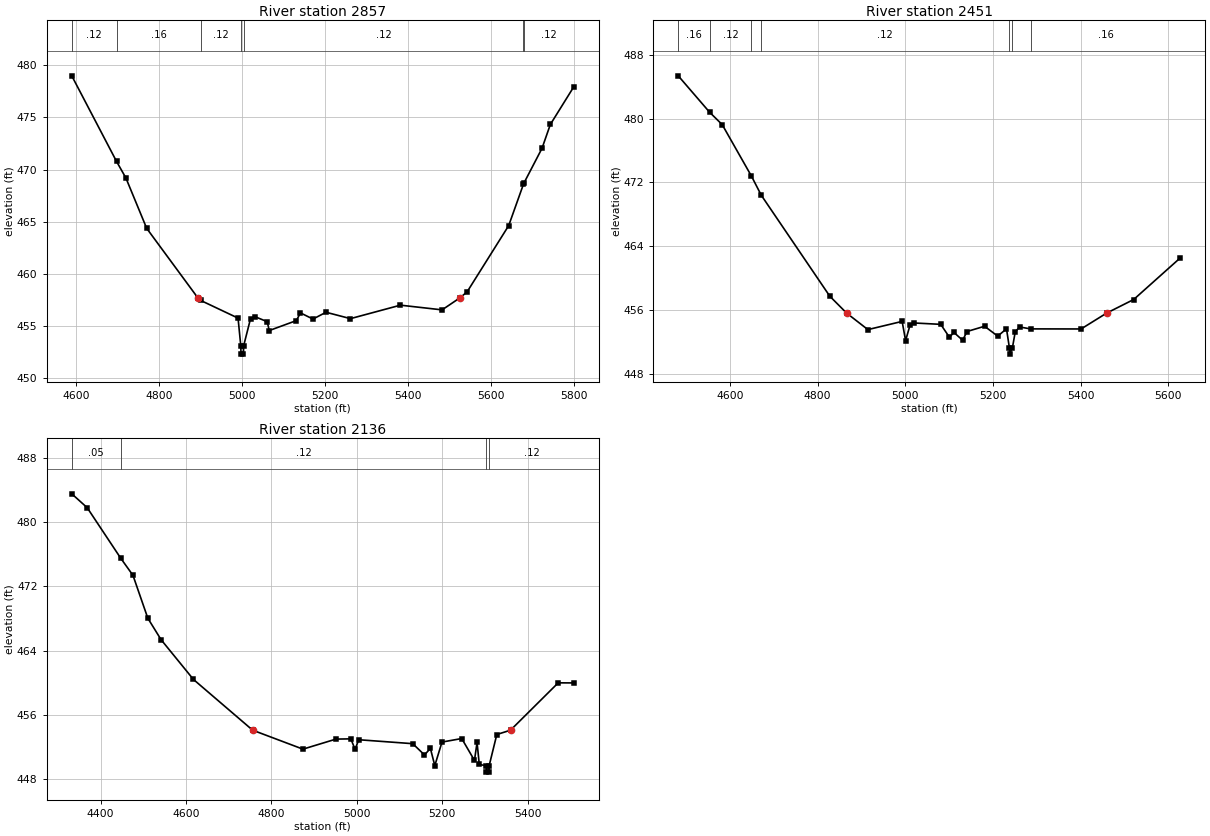
Type RM Length L Ch R = 1 ,2857    ,406,406,406
BEGIN DESCRIPTION:
Mapping XS fdb1a4c6
END DESCRIPTION:
XS GIS Cut Line= 3
      2840465.41      7080273.12      2840017.51      7080267.92
      2839258.59       7080325.1
#Sta/Elev= 30
  4590.3  478.98  4698.1  470.78  4720.7  469.19  4770.7  464.37  4893.9  457.71
  4900.9  457.46  4990.7  455.77  4997.3  453.12  4997.8  452.32  5003.7  452.32
  5004.2  453.12  5020.7  455.71  5030.7  455.92  5060.8  455.43  5065.9  454.58
    5131  455.53    5141  456.27  5171.1  455.68  5202.6  456.33  5261.4  455.72
  5381.7  457.01    5482  456.56  5524.9  457.71  5542.2  458.28  5642.4  464.63
  5677.7  468.57  5678.9  468.69  5722.7  472.04  5742.7  474.32  5799.3  477.94
#Mann= 7 ,-1 , 0
  4590.3     .12       0  4698.1     .16       0  4900.9     .12       0
  4997.3     .07       0  5004.2     .12       0  5677.7     .16       0
  5678.9     .12       0
Bank Sta=4893.9,5524.9
XS Rating Curve= 0 ,0
Exp/Cntr=0.3,0.1

Type RM Length L Ch R = 1 ,2451    ,315,315,315
BEGIN DESCRIPTION:
WOOD CREEK 1.0
END DESCRIPTION:
XS GIS Cut Line= 3
      2840575.04      7080175.03      2840152.93      7079887.71
      2839518.74      7079872.11
#Sta/Elev= 30
  4482.2  485.39  4553.7  480.82  4582.5  479.26  4649.2  472.79  4671.6  470.39
  4827.9  457.71  4866.3  455.59  4914.7  453.52  4992.8  454.55  5000.7  452.14
  5010.7  454.06  5020.8  454.35  5080.8  454.18  5100.8  452.55  5110.8  453.17
  5130.8  452.18  5140.8  453.28  5180.8  453.94  5210.8   452.7  5230.8  453.62
  5237.4  451.24  5237.9  450.44  5244.3  451.24  5250.8  453.25  5260.8  453.85
  5285.6  453.61  5400.9   453.6  5459.1  455.59  5520.9   457.3  5627.2  462.53
#Mann= 7 ,-1 , 0
  4482.2     .16       0  4553.7     .12       0  4649.2     .16       0
  4671.6     .12       0  5237.4     .07       0  5244.3     .12       0
  5285.6     .16       0
Bank Sta=4866.3,5459.1
XS Rating Curve= 0 ,0
Exp/Cntr=0.3,0.1

Type RM Length L Ch R = 1 ,2136    ,0,0,0
BEGIN DESCRIPTION:
Mapping XS 7cbe0214
END DESCRIPTION:
XS GIS Cut Line= 3
      2840788.35      7079846.04      2840152.93      7079585.62
      2839679.53      7079705.28
#Sta/Elev= 30
  4332.7   483.5  4368.7  481.78  4447.5  475.47  4475.9  473.36  4510.7  468.02
  4541.7  465.35  4617.5   460.4    4756  454.09  4873.7  451.73    4951  452.98
  4985.8  453.01  4995.6  451.72  5004.4   452.9  5130.7  452.41  5158.1  451.01
    5172  451.82  5182.3  449.68  5199.1  452.61  5245.3  453.05  5275.1  450.33
  5281.2  452.56  5286.4  449.82  5302.6  449.67  5303.1  448.87    5309  448.87
  5309.5  449.67  5327.4  453.55  5359.5  454.09  5471.1  459.98  5507.7  459.97
#Mann= 4 ,-1 , 0
  4332.7     .05       0  4447.5     .12       0  5302.6     .07       0
  5309.5     .12       0
Bank Sta=4756,5359.5
XS Rating Curve= 0 ,0
Exp/Cntr=0.3,0.1
LCMann Table=0

Chan Stop Cuts=-1
Use User Specified Reach Order=0
Composite Channel Slope=5