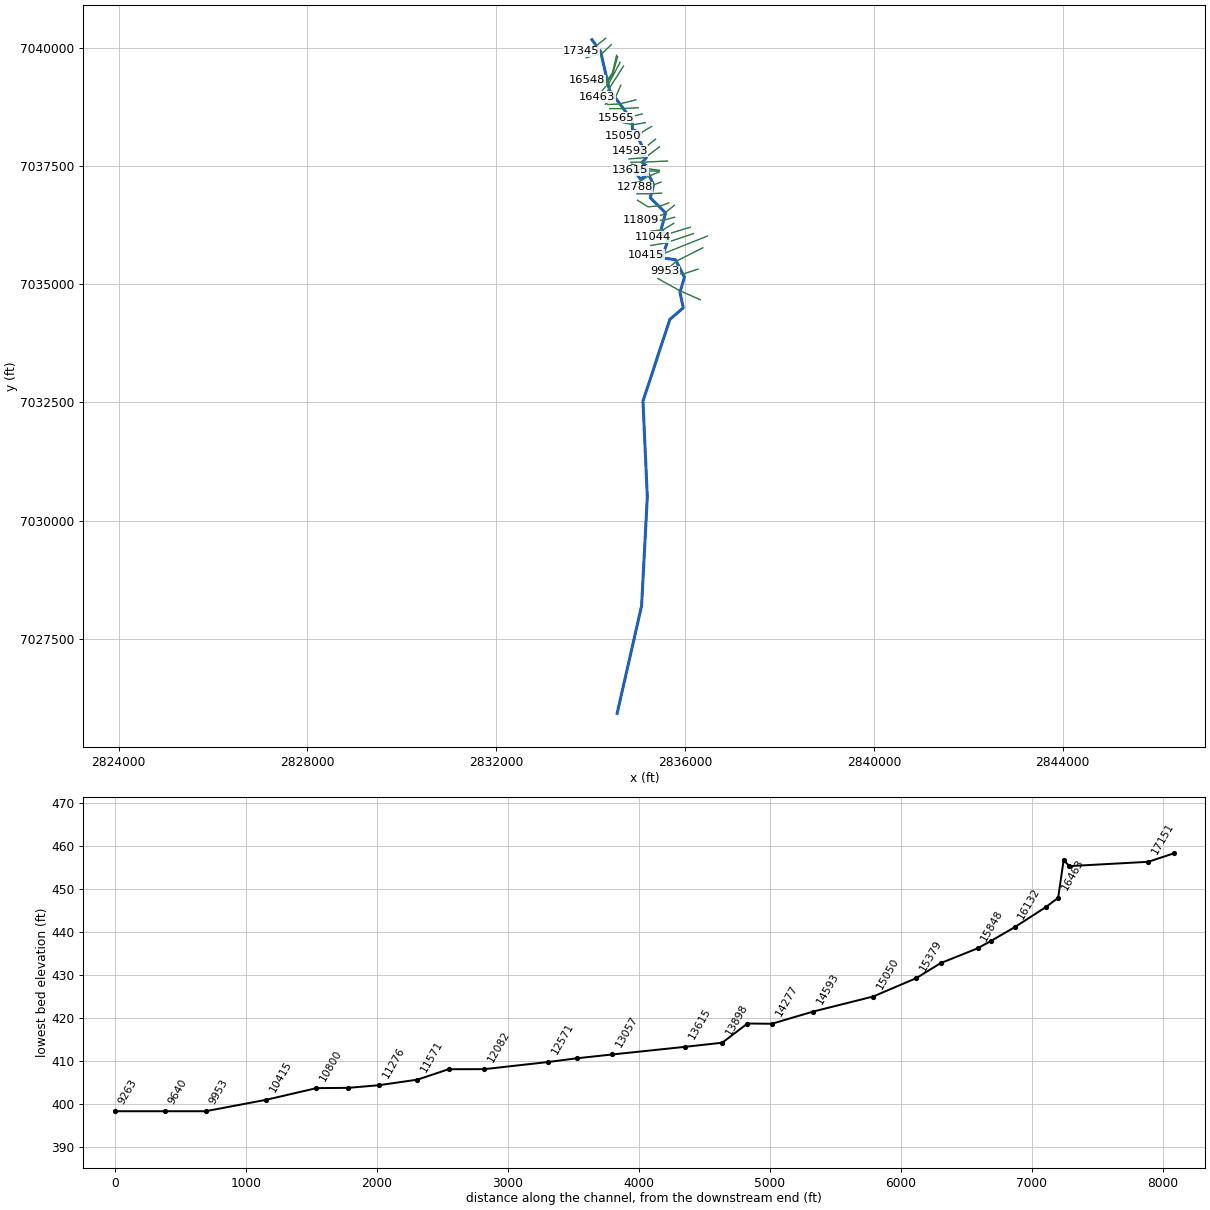
--- White Oak Branch 2.prj (project) ---

Proj Title=White Oak Branch 2 Base Level Engineering
Current Plan=p01
Default Exp/Contr=0.3,0.1
English Units
Geom File=g01
Flow File=f01
Plan File=p01
BEGIN DESCRIPTION:
White Oak Branch 2
END DESCRIPTION:

--- White Oak Branch 2.p01 (plan) ---

Plan Title=Multiple Run
Short Identifier=Multiple
Geom File=g01
Flow File=f01
Subcritical Flow
K Sum by GR= 0
Std Step Tol= 0.01
Critical Tol= 0.01
Num of Std Step Trials= 20
Max Error Tol= 0.3
Flow Tol Ratio= 0.001
Split Flow NTrial= 30
Split Flow Tol= 0.02
Split Flow Ratio= 0.02
Log Output Level= 0
Friction Slope Method= 1
Unsteady Friction Slope Method= 2
Unsteady Bridges Friction Slope Method= 1
Parabolic Critical Depth
Global Vel Dist=  1 , 1 , 1
Global Log Level= 0
CheckData=True
Encroach Param= -1, 0, 0, 0
BEGIN DESCRIPTION:
Multiple Run
END DESCRIPTION:

--- White Oak Branch 2.f01 (steady flow) ---

Flow Title=Multiple
Number of Profiles=7
Profile Names=10-year,25-year,50-year,1pct_min,100-year,1pct_plu,500-year
River Rch & RM= White Oak Branch,Reach-1,17345
     592     793     956     573    1144    2282    1639
River Rch & RM= White Oak Branch,Reach-1,7270
     824    1118    1359     821    1637    3267    2380
Boundary for River Rch & Prof#=White Oak Branch,Reach-1,1
Up Type=0
Dn Type=3
Dn Slope=0.005
Boundary for River Rch & Prof#=White Oak Branch,Reach-1,2
Up Type=0
Dn Type=3
Dn Slope=0.005
Boundary for River Rch & Prof#=White Oak Branch,Reach-1,3
Up Type=0
Dn Type=3
Dn Slope=0.005
Boundary for River Rch & Prof#=White Oak Branch,Reach-1,4
Up Type=0
Dn Type=3
Dn Slope=0.005
Boundary for River Rch & Prof#=White Oak Branch,Reach-1,5
Up Type=0
Dn Type=3
Dn Slope=0.005
Boundary for River Rch & Prof#=White Oak Branch,Reach-1,6
Up Type=0
Dn Type=3
Dn Slope=0.005
Boundary for River Rch & Prof#=White Oak Branch,Reach-1,7
Up Type=0
Dn Type=3
Dn Slope=0.005

--- White Oak Branch 2.g01 (geometry) ---

Geom Title=Existing Conditions

River Reach=White Oak Branch,Reach-1
Reach XY= 30
      2834028.97      7040180.91      2834211.99      7039931.78
      2834399.49      7039114.07      2834880.17      7038475.62
      2834886.48      7038271.15      2835068.44      7038213.78
      2835003.11      7038111.49      2835131.13      7037846.07
      2835048.21      7037754.97      2835180.52      7037682.89
      2835089.14      7037586.04      2835189.44      7037506.81
      2834948.10      7037376.63      2835060.59      7037224.76
      2835217.97      7037357.46      2835333.41      7037108.93
      2835264.64      7036834.15      2835589.02      7036515.20
      2835495.53      7036170.27      2835640.83      7035930.21
      2835503.11      7035562.54      2835797.50      7035524.64
      2835987.02      7035151.91      2835892.26      7034830.99
      2835963.01      7034505.02      2835678.73      7034258.64
      2835109.12      7032529.75      2835200.96      7030503.67
      2835080.42      7028196.35      2834561.94      7025916.48

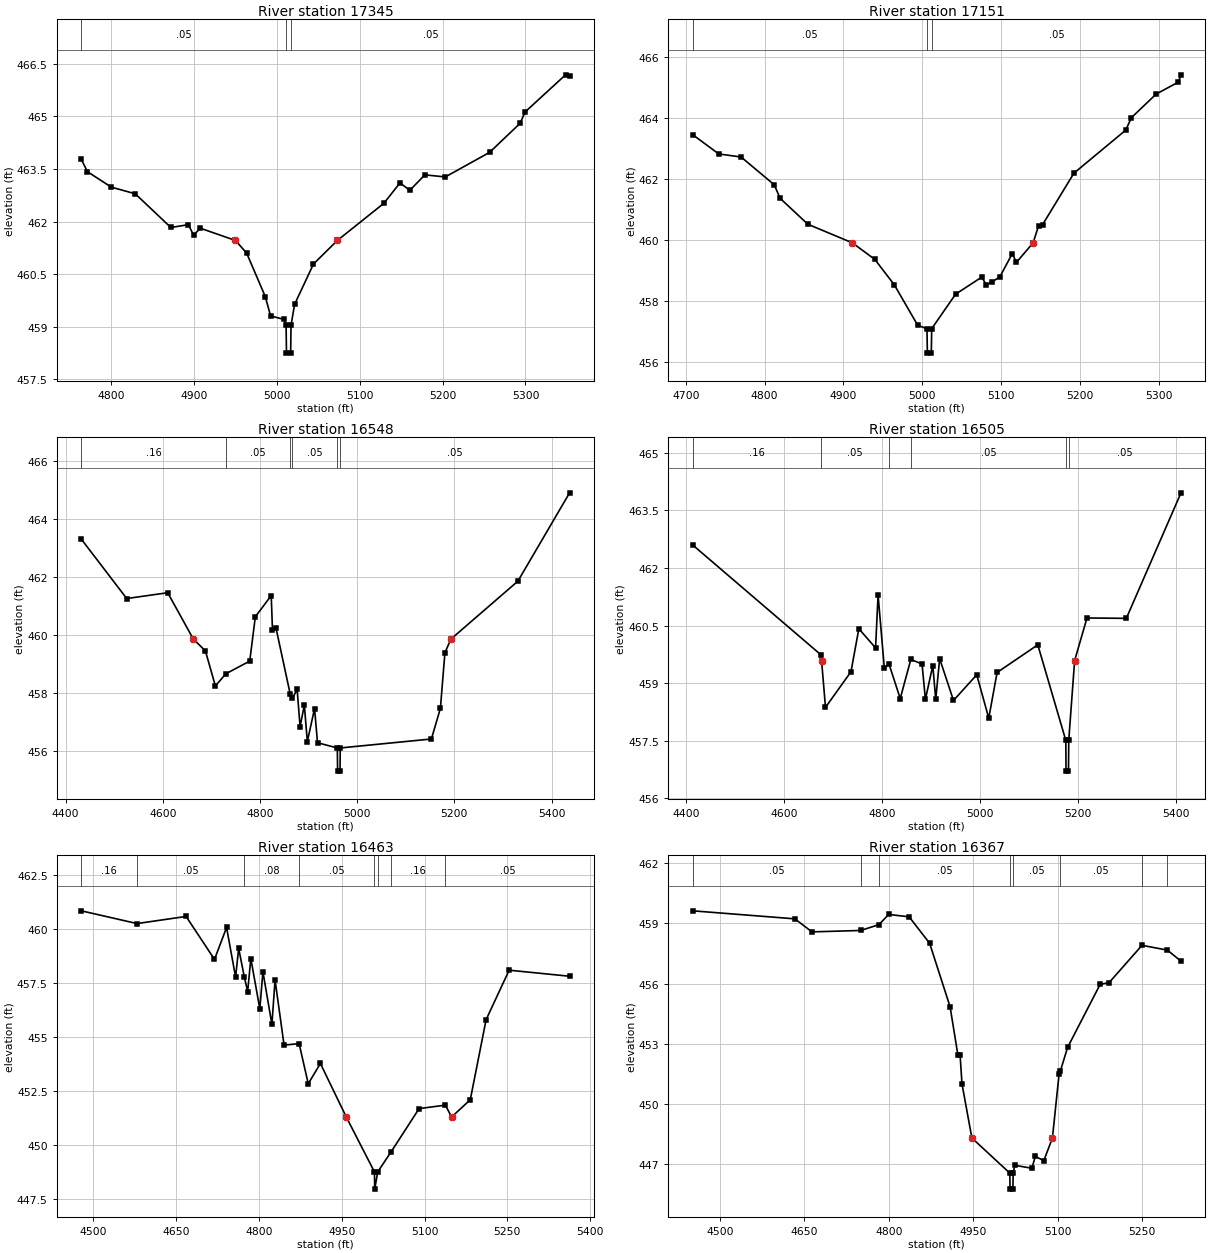
Type RM Length L Ch R = 1,17345,194,194,194
BEGIN DESCRIPTION:
White Oak Branch 2 29.0
END DESCRIPTION:
XS GIS Cut Line= 3
      2834319.65      7040211.53      2834133.86      7040063.94
      2833804.71      7039938.56
#Sta/Elev= 30
  4763.8  463.77  4771.2  463.42  4800.0  462.98  4828.9  462.79  4871.9  461.83
  4893.0  461.91  4899.4  461.61  4907.4  461.81  4949.9  461.46  4963.4  461.10
  4985.9  459.86  4992.3  459.31  5008.7  459.21  5011.0  459.05  5011.5  458.25
  5016.5  458.25  5017.0  459.05  5021.3  459.64  5044.1  460.79  5072.9  461.46
  5129.1  462.52  5148.5  463.10  5160.4  462.89  5178.6  463.33  5203.2  463.27
  5256.7  463.97  5293.6  464.80  5299.5  465.12  5348.4  466.18  5353.3  466.14
#Mann=3,-1,0
  4763.8    0.05       0  5011.0    0.03       0  5017.0    0.05       0
Bank Sta=4949.9,5072.9
Exp/Cntr=0.3,0.1

Type RM Length L Ch R = 1,17151,603,603,603
BEGIN DESCRIPTION:
Mapping XS 491ccac7
END DESCRIPTION:
XS GIS Cut Line= 3
      2834439.44      7040076.99      2834257.13      7039903.35
      2833904.76      7039799.59
#Sta/Elev= 30
  4708.9  463.45  4741.9  462.82  4770.2  462.72  4812.3  461.81  4819.6  461.37
  4854.8  460.52  4911.3  459.91  4939.7  459.37  4964.4  458.54  4994.2  457.21
  5005.9  457.10  5006.4  456.30  5011.4  456.30  5011.9  457.10  5042.2  458.23
  5075.5  458.79  5080.8  458.54  5088.0  458.62  5098.4  458.80  5114.1  459.56
  5119.3  459.27  5140.5  459.91  5147.4  460.47  5152.6  460.51  5192.2  462.19
  5257.9  463.60  5265.2  464.01  5296.5  464.78  5324.5  465.17  5328.0  465.41
#Mann=3,-1,0
  4708.9    0.05       0  5005.9    0.03       0  5011.9    0.05       0
Bank Sta=4911.3,5140.5
Exp/Cntr=0.3,0.1

Type RM Length L Ch R = 1,16548,43,43,43
BEGIN DESCRIPTION:
Mapping XS fef8a21f
END DESCRIPTION:
XS GIS Cut Line= 6
      2834550.97      7039853.45      2834460.68      7039473.23
      2834346.10      7039322.19      2834306.17      7039299.62
      2834226.31      7039297.88      2833928.80      7039318.65
#Sta/Elev= 30
  4432.3  463.31  4525.7  461.26  4610.1  461.46  4662.8  459.86  4687.7  459.45
  4708.2  458.24  4729.6  458.66  4778.9  459.10  4790.4  460.63  4823.1  461.36
  4825.7  460.18  4833.1  460.23  4862.2  457.96  4866.9  457.81  4876.4  458.13
  4882.5  456.84  4891.3  457.58  4897.4  456.32  4912.3  457.46  4918.4  456.28
  4959.2  456.10  4959.7  455.30  4964.7  455.30  4965.2  456.10  5152.8  456.41
  5171.3  457.47  5180.6  459.39  5193.0  459.86  5330.8  461.86  5437.2  464.91
#Mann=6,-1,0
  4432.3    0.16       0  4729.6    0.05       0  4862.2    0.08       0
  4866.9    0.05       0  4959.2    0.04       0  4965.2    0.05       0
Bank Sta=4662.8,5193
Exp/Cntr=0.3,0.1

Type RM Length L Ch R = 1,16505,42,42,42
BEGIN DESCRIPTION:
Mapping XS ba310f9e
END DESCRIPTION:
XS GIS Cut Line= 6
      2834571.78      7039825.61      2834465.89      7039448.92
      2834361.73      7039292.67      2834330.48      7039271.84
      2834290.55      7039261.42      2833953.76      7039285.73
#Sta/Elev= 30
  4414.0  462.60  4675.4  459.74  4676.7  459.59  4684.7  458.37  4736.7  459.30
  4752.7  460.42  4786.8  459.92  4791.9  461.30  4804.7  459.39  4814.2  459.50
  4837.1  458.60  4858.7  459.62  4881.6  459.50  4888.4  458.58  4903.5  459.46
  4909.5  458.58  4917.5  459.64  4945.7  458.55  4993.1  459.22  5017.6  458.09
  5034.6  459.28  5117.6  460.00  5174.7  457.51  5175.2  456.71  5180.2  456.71
  5180.7  457.51  5192.7  459.59  5217.9  460.70  5298.1  460.69  5409.6  463.96
#Mann=6,-1,0
  4414.0    0.16       0  4675.4    0.05       0  4814.2    0.08       0
  4858.7    0.05       0  5174.7    0.04       0  5180.7    0.05       0
Bank Sta=4676.7,5192.7
Exp/Cntr=0.3,0.1

Type RM Length L Ch R = 1,16463,96,96,96
BEGIN DESCRIPTION:
Mapping XS 03fdaa7c
END DESCRIPTION:
XS GIS Cut Line= 4
      2834623.86      7039702.36      2834402.52      7039288.33
      2834327.00      7039202.39      2834137.69      7038969.00
#Sta/Elev= 30
  4478.4  460.83  4579.3  460.24  4668.2  460.57  4719.6  458.58  4741.5  460.06
  4757.8  457.76  4763.4  459.09  4773.6  457.77  4779.7  457.09  4785.4  458.62
  4801.7  456.29  4807.3  458.01  4823.6  455.57  4829.3  457.63  4845.6  454.61
  4872.9  454.68  4889.4  452.82  4911.4  453.76  4958.3  451.28  5009.3  448.74
  5009.8  447.94  5015.3  448.74  5039.6  449.67  5090.2  451.67  5137.8  451.83
  5149.1  451.28  5182.9  452.08  5211.6  455.79  5253.3  458.08  5362.8  457.80
#Mann=8,-1,0
  4478.4    0.16       0  4579.3    0.05       0  4773.6    0.08       0
  4872.9    0.05       0  5009.3    0.04       0  5015.3    0.05       0
  5039.6    0.16       0  5137.8    0.05       0
Bank Sta=4958.3,5149.1
Exp/Cntr=0.3,0.1

Type RM Length L Ch R = 1,16367,235,235,235
BEGIN DESCRIPTION:
Mapping XS 1692aa94
END DESCRIPTION:
XS GIS Cut Line= 4
      2834696.79      7039624.26      2834441.59      7039223.23
      2834316.59      7039027.92      2834238.47      7038887.30
#Sta/Elev= 30
  4451.3  459.63  4632.9  459.23  4663.3  458.58  4749.9  458.65  4782.3  458.94
  4799.7  459.45  4836.1  459.33  4872.5  458.01  4908.9  454.84  4922.6  452.46
  4926.6  452.46  4930.0  451.00  4947.6  448.30  5015.0  446.55  5015.5  445.75
  5020.5  445.75  5021.0  446.55  5023.9  446.94  5054.3  446.79  5060.3  447.38
  5075.5  447.17  5090.8  448.30  5102.6  451.48  5105.1  451.66  5117.8  452.82
  5175.6  455.96  5191.6  456.05  5250.1  457.91  5295.2  457.67  5319.4  457.12
#Mann=8,-1,0
  4451.3    0.05       0  4749.9    0.08       0  4782.3    0.05       0
  5015.0    0.04       0  5021.0    0.05       0  5105.1    0.05       0
  5250.1    0.16       0  5295.2    0.08       0
Bank Sta=4947.6,5090.8
Exp/Cntr=0.3,0.1

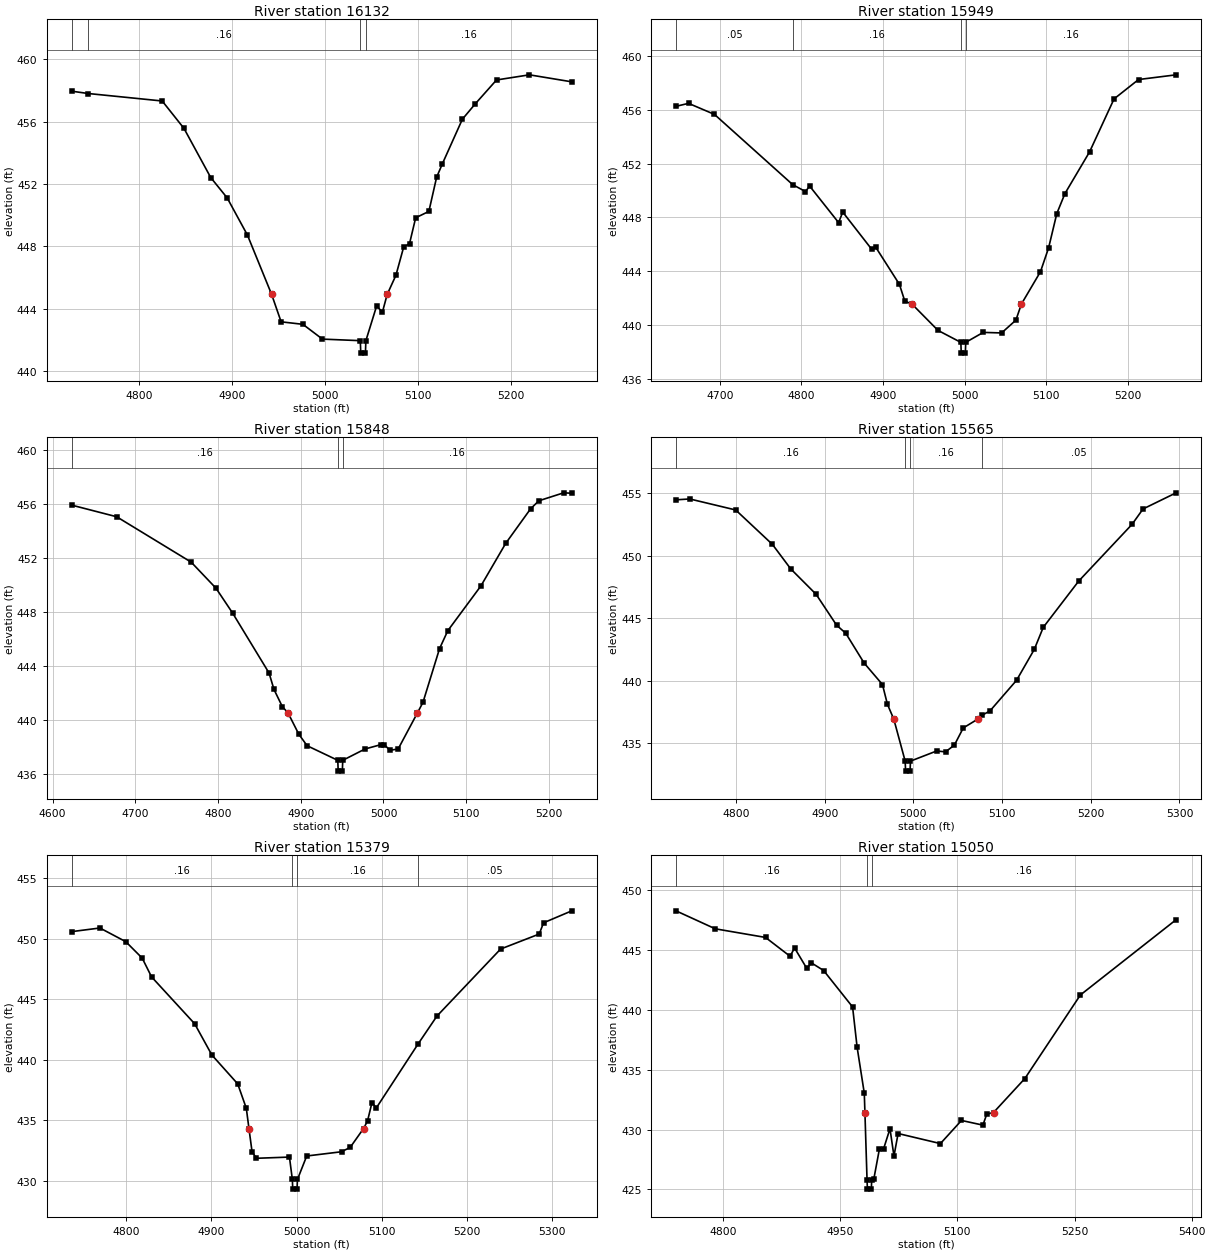
Type RM Length L Ch R = 1,16132,183,183,183
BEGIN DESCRIPTION:
Mapping XS 30df7235
END DESCRIPTION:
XS GIS Cut Line= 3
      2834639.52      7039218.05      2834537.94      7038986.25
      2834311.35      7038814.35
#Sta/Elev= 30
  4727.9  457.96  4745.7  457.81  4825.2  457.33  4848.6  455.57  4877.4  452.41
  4895.0  451.11  4916.8  448.72  4942.8  444.91  4953.0  443.15  4976.4  442.99
  4997.4  442.04  5038.1  441.94  5038.6  441.14  5043.6  441.14  5044.1  441.94
  5055.6  444.16  5061.9  443.78  5067.0  444.91  5076.4  446.14  5084.7  447.95
  5091.0  448.17  5097.6  449.83  5111.8  450.24  5120.1  452.43  5126.4  453.31
  5147.8  456.16  5161.7  457.15  5184.5  458.68  5219.9  459.01  5265.4  458.56
#Mann=4,-1,0
  4727.9    0.05       0  4745.7    0.16       0  5038.1    0.07       0
  5044.1    0.16       0
Bank Sta=4942.8,5067
Exp/Cntr=0.3,0.1

Type RM Length L Ch R = 1,15949,101,101,101
BEGIN DESCRIPTION:
Mapping XS 630a661f
END DESCRIPTION:
XS GIS Cut Line= 3
      2834959.86      7038910.74      2834618.67      7038822.19
      2834359.09      7038809.21
#Sta/Elev= 30
  4646.4  456.25  4661.8  456.47  4693.5  455.65  4789.3  450.43  4804.9  449.92
  4810.1  450.32  4845.5  447.61  4850.6  448.39  4886.0  445.63  4891.2  445.76
  4920.0  443.02  4926.6  441.77  4935.3  441.56  4967.2  439.60  4995.2  438.71
  4995.7  437.91  5000.7  437.91  5001.2  438.71  5022.6  439.45  5045.1  439.41
  5062.6  440.36  5069.4  441.56  5092.7  443.96  5102.7  445.74  5112.7  448.28
  5122.7  449.77  5152.8  452.86  5182.8  456.80  5212.8  458.24  5258.8  458.59
#Mann=4,-1,0
  4646.4    0.05       0  4789.3    0.16       0  4995.2    0.07       0
  5001.2    0.16       0
Bank Sta=4935.3,5069.4
Exp/Cntr=0.3,0.1

Type RM Length L Ch R = 1,15848,283,283,283
BEGIN DESCRIPTION:
Mapping XS 723710f8
END DESCRIPTION:
XS GIS Cut Line= 3
      2835009.30      7038741.46      2834631.69      7038723.23
      2834405.14      7038723.23
#Sta/Elev= 30
  4623.1  455.90  4677.5  455.04  4767.6  451.68  4797.6  449.75  4817.6  447.92
  4861.7  443.48  4867.7  442.26  4877.7  441.00  4884.7  440.52  4897.7  438.95
  4907.7  438.10  4944.8  437.02  4945.3  436.22  4950.3  436.22  4950.8  437.02
  4977.8  437.86  4997.0  438.18  5001.1  438.18  5007.8  437.76  5017.8  437.86
  5041.0  440.52  5047.8  441.31  5067.8  445.28  5077.8  446.61  5117.8  449.92
  5147.8  453.07  5177.8  455.62  5187.8  456.22  5217.8  456.81  5227.7  456.78
#Mann=3,-1,0
  4623.1    0.16       0  4944.8    0.07       0  4950.8    0.16       0
Bank Sta=4884.7,5041
Exp/Cntr=0.3,0.1

Type RM Length L Ch R = 1,15565,186,186,186
BEGIN DESCRIPTION:
Mapping XS 78ee1e3a
END DESCRIPTION:
XS GIS Cut Line= 3
      2835090.03      7038611.25      2834834.82      7038543.54
      2834535.36      7038527.92
#Sta/Elev= 30
  4732.3  454.45  4747.8  454.52  4799.6  453.64  4841.0  450.89  4861.7  448.93
  4890.3  446.90  4913.4  444.43  4923.7  443.79  4944.4  441.41  4965.1  439.69
  4970.7  438.11  4977.9  436.92  4990.7  433.57  4991.2  432.77  4996.2  432.77
  4996.7  433.57  5026.2  434.38  5036.2  434.31  5046.2  434.85  5056.2  436.22
  5072.4  436.92  5077.2  437.23  5086.3  437.58  5116.3  440.03  5136.3  442.50
  5146.4  444.26  5186.4  447.96  5246.5  452.49  5258.9  453.72  5296.2  455.01
#Mann=4,-1,0
  4732.3    0.16       0  4990.7    0.07       0  4996.7    0.16       0
  5077.2    0.05       0
Bank Sta=4977.9,5072.4
Exp/Cntr=0.3,0.1

Type RM Length L Ch R = 1,15379,329,329,329
BEGIN DESCRIPTION:
Mapping XS 2b737a7a
END DESCRIPTION:
XS GIS Cut Line= 3
      2835157.76      7038423.75      2834897.32      7038382.08
      2834579.78      7038447.15
#Sta/Elev= 30
  4735.7  450.58  4768.9  450.88  4799.3  449.75  4818.6  448.39  4829.6  446.84
  4880.3  442.96  4900.5  440.38  4930.9  437.99  4941.0  435.97  4944.1  434.30
  4947.7  432.40  4952.8  431.84  4991.7  431.94  4995.1  430.09  4995.6  429.29
  5000.6  429.29  5001.1  430.09  5012.0  432.03  5052.9  432.38  5063.1  432.74
  5078.8  434.30  5083.5  434.93  5088.7  436.45  5093.8  436.00  5142.6  441.26
  5165.1  443.60  5239.9  449.14  5285.3  450.38  5290.4  451.31  5323.6  452.30
#Mann=4,-1,0
  4735.7    0.16       0  4995.1    0.07       0  5001.1    0.16       0
  5142.6    0.05       0
Bank Sta=4944.1,5078.8
Exp/Cntr=0.3,0.1

Type RM Length L Ch R = 1,15050,457,457,457
BEGIN DESCRIPTION:
Mapping XS 42f48bc6
END DESCRIPTION:
XS GIS Cut Line= 3
      2835293.12      7038345.61      2835066.59      7038212.81
      2834694.22      7038147.71
#Sta/Elev= 30
  4739.5  448.25  4789.8  446.75  4854.2  446.03  4885.6  444.46  4891.4  445.15
  4907.1  443.44  4912.9  443.91  4928.6  443.27  4965.7  440.23  4971.5  436.87
  4980.7  433.03  4981.5  431.42  4984.2  425.83  4984.7  425.03  4989.7  425.03
  4990.2  425.83  4993.0  425.91  5000.1  428.39  5005.4  428.39  5013.6  430.07
  5018.7  427.79  5024.0  429.67  5078.2  428.83  5105.2  430.76  5132.6  430.37
  5137.6  431.29  5146.2  431.42  5186.4  434.26  5257.5  441.23  5380.1  447.51
#Mann=3,-1,0
  4739.5    0.16       0  4984.2    0.07       0  4990.2    0.16       0
Bank Sta=4981.5,5146.2
Exp/Cntr=0.3,0.1

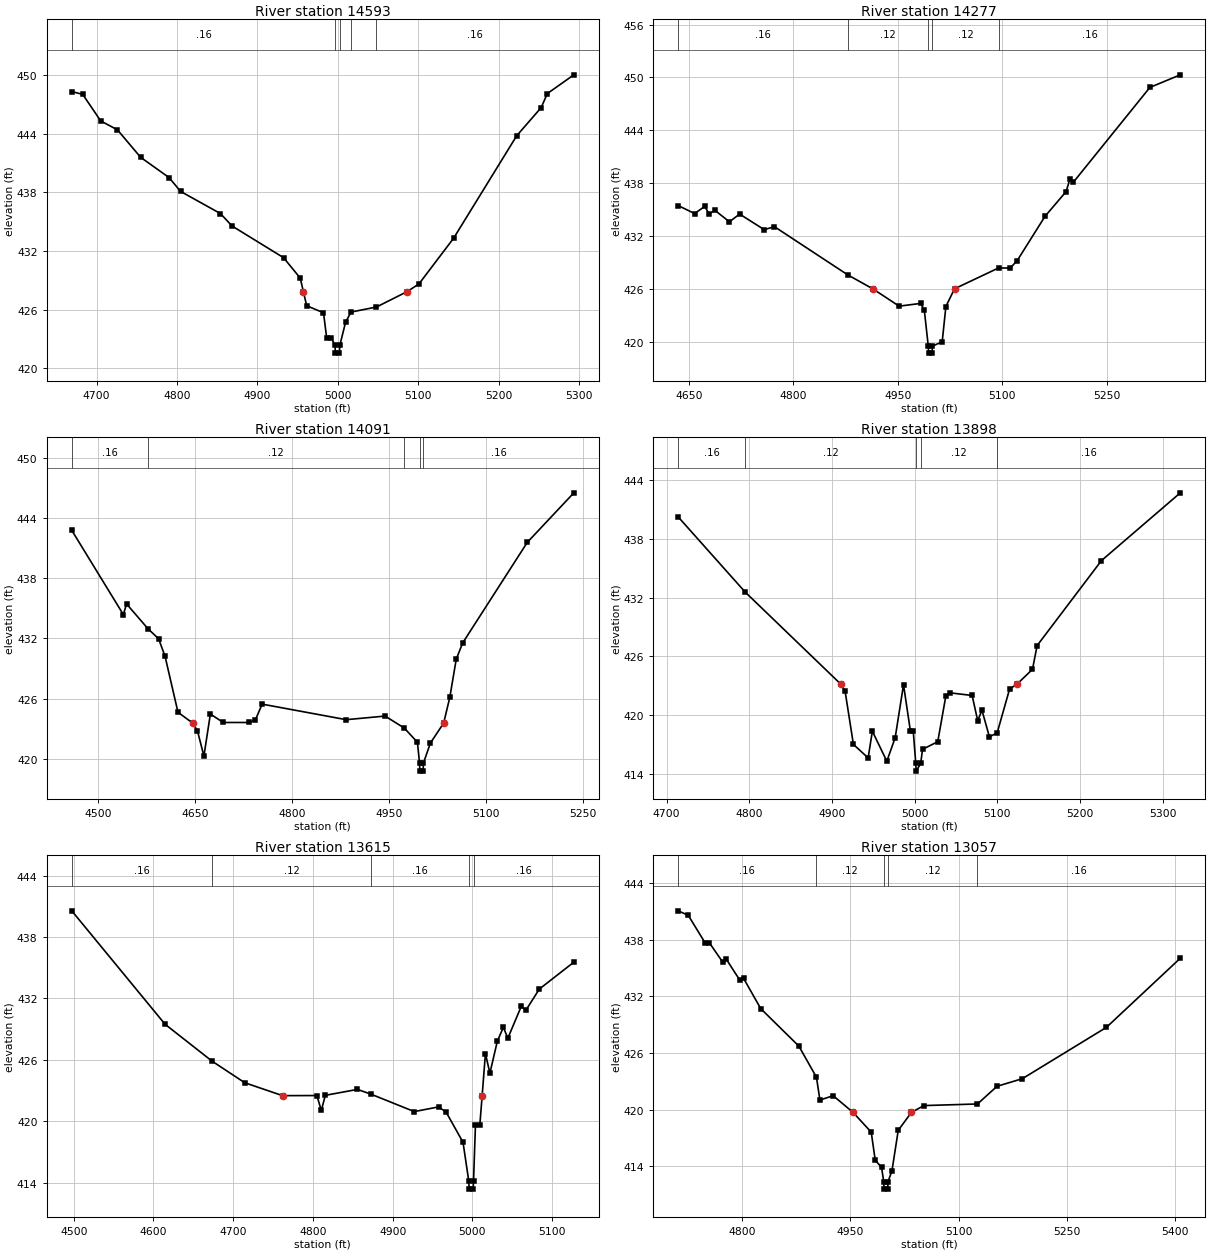
Type RM Length L Ch R = 1,14593,316,316,316
BEGIN DESCRIPTION:
White Oak Branch 2 28.0
END DESCRIPTION:
XS GIS Cut Line= 3
      2835375.00      7038075.00      2835125.00      7037875.00
      2834824.99      7037825.00
#Sta/Elev= 30
  4669.1  448.32  4682.7  448.03  4705.1  445.31  4725.9  444.40  4754.7  441.59
  4790.0  439.52  4804.4  438.10  4854.0  435.83  4868.4  434.56  4932.4  431.32
  4953.2  429.23  4957.1  427.84  4961.2  426.40  4982.1  425.68  4986.1  423.09
  4991.8  423.09  4996.4  422.35  4996.9  421.55  5001.9  421.55  5002.4  422.35
  5009.5  424.69  5016.2  425.75  5048.0  426.27  5086.0  427.84  5100.8  428.63
  5143.9  433.31  5222.4  443.80  5252.8  446.68  5260.4  448.11  5293.4  450.03
#Mann=5,-1,0
  4669.1    0.16       0  4996.4    0.07       0  5002.4    0.16       0
  5016.2    0.12       0  5048.0    0.16       0
Bank Sta=4957.1,5086
Exp/Cntr=0.3,0.1

Type RM Length L Ch R = 1,14277,186,186,186
BEGIN DESCRIPTION:
Mapping XS d75506d3
END DESCRIPTION:
XS GIS Cut Line= 4
      2835459.82      7037913.33      2835199.40      7037718.02
      2835087.42      7037678.96      2834811.42      7037658.13
#Sta/Elev= 30
  4634.7  435.45  4658.2  434.55  4672.8  435.36  4679.0  434.50  4687.4  434.91
  4708.2  433.61  4722.8  434.49  4758.2  432.72  4772.8  433.06  4878.1  427.59
  4914.0  426.01  4951.9  424.04  4982.7  424.35  4988.0  423.61  4993.7  419.51
  4994.2  418.71  4999.2  418.71  4999.7  419.51  5013.7  419.99  5019.0  424.00
  5031.4  426.01  5094.8  428.38  5111.3  428.36  5121.4  429.21  5161.5  434.25
  5191.6  437.04  5197.2  438.49  5202.2  438.12  5311.9  448.86  5355.6  450.29
#Mann=5,-1,0
  4634.7    0.16       0  4878.1    0.12       0  4993.7    0.07       0
  4999.7    0.12       0  5094.8    0.16       0
Bank Sta=4914,5031.4
Exp/Cntr=0.3,0.1

Type RM Length L Ch R = 1,14091,193,193,193
BEGIN DESCRIPTION:
Mapping XS d6bcd396
END DESCRIPTION:
XS GIS Cut Line= 3
      2835629.13      7037613.86      2835087.42      7037587.81
      2834853.07      7037590.42
#Sta/Elev= 30
  4459.4  442.78  4539.2  434.38  4544.2  435.44  4577.4  432.96  4593.7  431.97
  4603.7  430.22  4623.7  424.64  4646.5  423.56  4653.8  422.80  4663.8  420.27
  4673.8  424.46  4693.8  423.62  4733.8  423.62  4743.4  423.87  4753.9  425.45
  4884.0  423.90  4944.1  424.26  4973.7  423.07  4994.1  421.65  4997.4  419.57
  4997.9  418.77  5002.9  418.77  5003.4  419.57  5014.2  421.57  5034.7  423.56
  5044.2  426.12  5054.2  429.94  5064.2  431.56  5164.2  441.59  5236.1  446.52
#Mann=5,-1,0
  4459.4    0.16       0  4577.4    0.12       0  4973.7    0.16       0
  4997.4    0.07       0  5003.4    0.16       0
Bank Sta=4646.5,5034.7
Exp/Cntr=0.3,0.1

Type RM Length L Ch R = 1,13898,283,283,283
BEGIN DESCRIPTION:
Mapping XS 94bee52a
END DESCRIPTION:
XS GIS Cut Line= 3
      2835454.58      7037415.94      2835173.36      7037457.60
      2834863.48      7037548.74
#Sta/Elev= 30
  4714.1  440.22  4795.1  432.56  4910.8  423.17  4915.9  422.47  4926.0  417.03
  4943.8  415.66  4948.9  418.38  4966.4  415.32  4976.5  417.71  4986.6  423.12
  4995.0  418.35  4998.4  418.35  5001.4  415.11  5001.9  414.31  5007.4  415.11
  5009.6  416.53  5028.0  417.31  5037.7  421.93  5043.0  422.29  5069.6  422.02
  5076.3  419.46  5081.5  420.51  5090.5  417.80  5099.9  418.22  5114.9  422.68
  5123.8  423.17  5142.6  424.69  5148.2  427.11  5226.0  435.77  5321.4  442.68
#Mann=5,-1,0
  4714.1    0.16       0  4795.1    0.12       0  5001.4    0.07       0
  5007.4    0.12       0  5099.9    0.16       0
Bank Sta=4910.8,5123.8
Exp/Cntr=0.3,0.1

Type RM Length L Ch R = 1,13615,558,558,558
BEGIN DESCRIPTION:
Mapping XS 5c454168
END DESCRIPTION:
XS GIS Cut Line= 4
      2835451.98      7037400.31      2835168.15      7037405.52
      2834949.40      7037363.85      2834838.75      7037417.89
#Sta/Elev= 30
  4497.5  440.57  4614.5  429.48  4673.5  425.87  4714.5  423.76  4761.9  422.50
  4804.9  422.51  4810.5  421.05  4815.5  422.53  4855.8  423.11  4872.9  422.64
  4927.1  420.94  4957.6  421.40  4967.0  420.89  4988.2  417.94  4995.4  414.16
  4995.9  413.36  5000.9  413.36  5001.4  414.16  5003.8  419.65  5009.3  419.65
  5012.2  422.50  5016.3  426.62  5021.9  424.69  5031.2  427.81  5038.8  429.19
  5044.4  428.11  5061.3  431.24  5066.9  430.83  5083.9  432.92  5127.2  435.55
#Mann=5,-1,0
  4497.5    0.16       0  4673.5    0.12       0  4872.9    0.16       0
  4995.4    0.07       0  5001.4    0.16       0
Bank Sta=4761.9,5012.2
Exp/Cntr=0.3,0.1

Type RM Length L Ch R = 1,13057,269,269,269
BEGIN DESCRIPTION:
Mapping XS 61636cfe
END DESCRIPTION:
XS GIS Cut Line= 4
      2835454.58      7037384.68      2835188.98      7037272.71
      2835030.13      7037171.14      2834813.95      7037137.29
#Sta/Elev= 30
  4711.7  441.06  4725.6  440.58  4749.4  437.61  4754.8  437.68  4773.1  435.65
  4778.5  435.91  4796.8  433.74  4802.2  433.91  4826.0  430.70  4878.8  426.73
  4903.2  423.43  4908.0  421.01  4926.3  421.48  4953.9  419.71  4979.1  417.61
  4984.6  414.65  4993.4  413.88  4996.4  412.38  4996.9  411.58  5001.9  411.58
  5002.4  412.38  5007.8  413.52  5016.5  417.81  5034.8  419.71  5052.1  420.43
  5126.3  420.60  5153.3  422.47  5188.5  423.28  5305.0  428.72  5407.3  436.04
#Mann=5,-1,0
  4711.7    0.16       0  4903.2    0.12       0  4996.4    0.07       0
  5002.4    0.12       0  5126.3    0.16       0
Bank Sta=4953.9,5034.8
Exp/Cntr=0.3,0.1

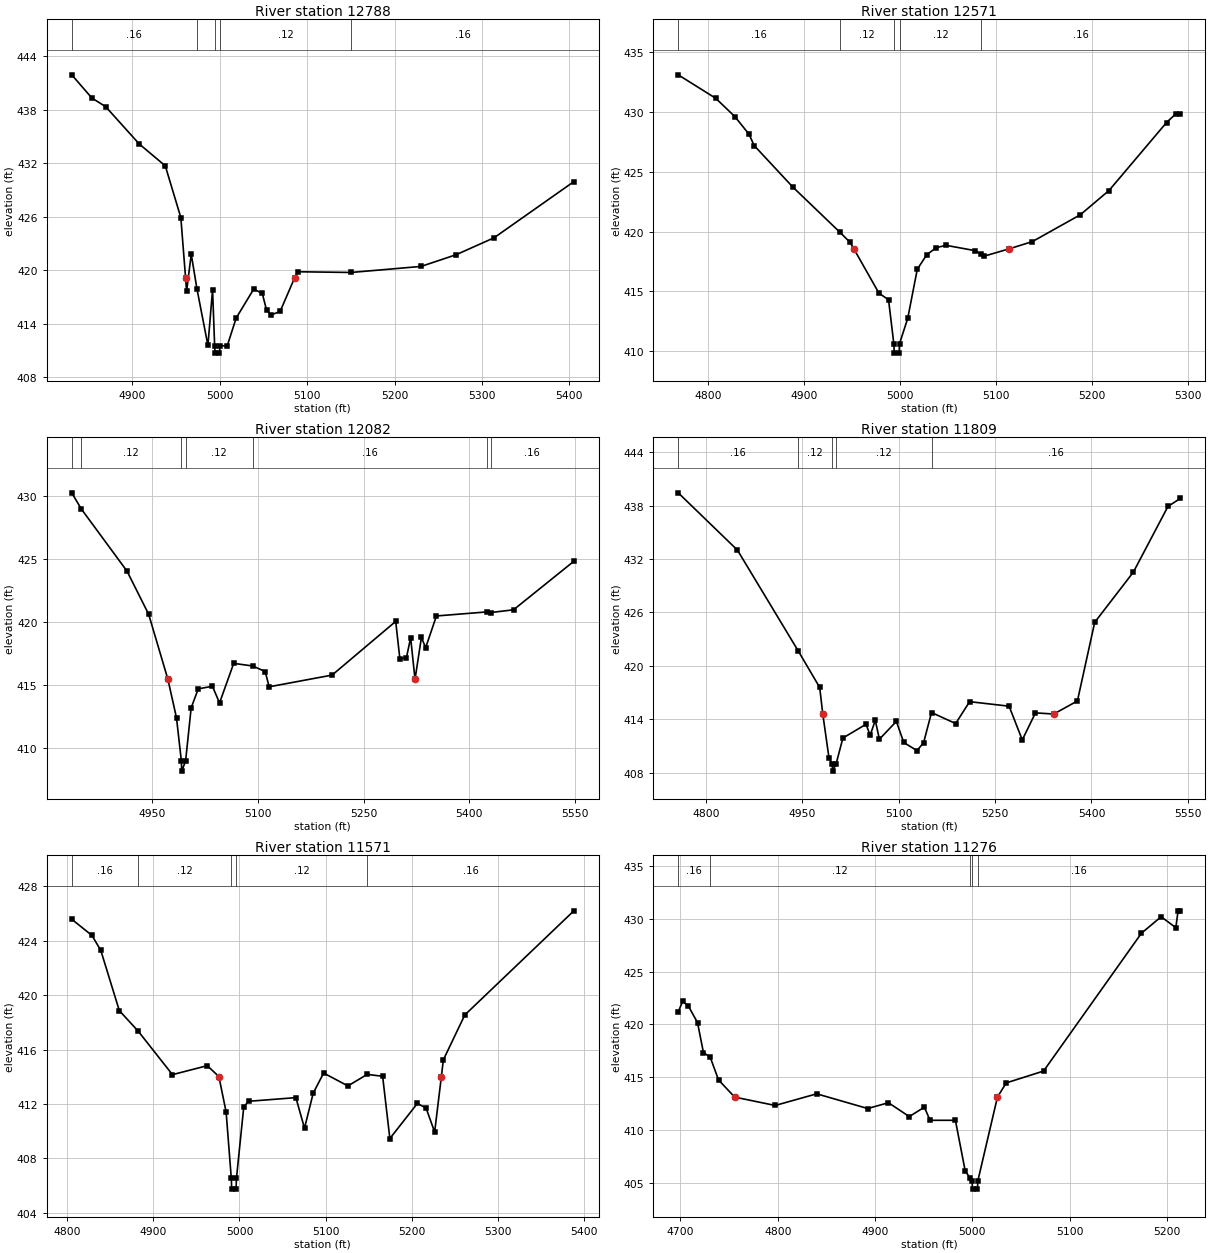
Type RM Length L Ch R = 1,12788,217,217,217
BEGIN DESCRIPTION:
Mapping XS e87cf91d
END DESCRIPTION:
XS GIS Cut Line= 3
      2835491.09      7037168.55      2835332.21      7037106.04
      2834931.18      7037059.17
#Sta/Elev= 30
  4830.6  441.89  4853.6  439.29  4869.4  438.32  4907.8  434.14  4937.6  431.69
  4955.4  425.89  4960.8  419.16  4962.0  417.62  4967.3  421.79  4973.8  417.92
  4986.4  411.56  4991.7  417.82  4994.1  411.50  4994.6  410.70  4999.6  410.70
  5000.1  411.50  5008.6  411.55  5018.7  414.63  5038.8  417.88  5048.6  417.39
  5053.6  415.48  5058.9  414.99  5069.0  415.37  5085.7  419.16  5089.1  419.82
  5150.2  419.74  5230.4  420.42  5270.4  421.73  5313.7  423.62  5405.1  429.92
#Mann=5,-1,0
  4830.6    0.16       0  4973.8    0.12       0  4994.1    0.07       0
  5000.1    0.12       0  5150.2    0.16       0
Bank Sta=4960.8,5085.7
Exp/Cntr=0.3,0.1

Type RM Length L Ch R = 1,12571,489,489,489
BEGIN DESCRIPTION:
Mapping XS 5eb7ced6
END DESCRIPTION:
XS GIS Cut Line= 3
      2835504.06      7036934.16      2835273.13      7036921.07
      2834980.64      7036918.54
#Sta/Elev= 30
  4768.7  433.10  4807.8  431.14  4827.9  429.60  4842.6  428.13  4847.9  427.19
  4888.0  423.74  4937.0  419.97  4948.0  419.10  4951.9  418.56  4978.1  414.85
  4988.1  414.30  4993.6  410.64  4994.1  409.84  4999.1  409.84  4999.6  410.64
  5008.1  412.74  5018.1  416.85  5028.1  418.08  5038.1  418.66  5048.1  418.85
  5078.1  418.41  5084.9  418.10  5088.1  417.95  5114.1  418.56  5138.1  419.16
  5188.1  421.40  5218.1  423.43  5278.1  429.11  5287.8  429.84  5292.5  429.84
#Mann=5,-1,0
  4768.7    0.16       0  4937.0    0.12       0  4993.6    0.07       0
  4999.6    0.12       0  5084.9    0.16       0
Bank Sta=4951.9,5114.1
Exp/Cntr=0.3,0.1

Type RM Length L Ch R = 1,12082,273,273,273
BEGIN DESCRIPTION:
Mapping XS 71ee0d8a
END DESCRIPTION:
XS GIS Cut Line= 4
      2835655.12      7036725.83      2835501.48      7036671.14
      2835217.63      7036642.50      2834993.69      7036783.11
#Sta/Elev= 30
  4835.8  430.26  4849.2  428.99  4914.2  424.05  4945.0  420.62  4972.3  415.46
  4984.5  412.40  4991.4  408.98  4991.9  408.18  4997.4  408.98  5005.3  413.20
  5015.4  414.71  5035.5  414.91  5045.6  413.59  5065.7  416.73  5092.8  416.52
  5110.4  416.08  5116.0  414.87  5205.4  415.80  5295.7  420.06  5301.6  417.09
  5310.9  417.18  5316.9  418.76  5323.1  415.46  5332.2  418.79  5338.2  417.97
  5353.5  420.49  5424.6  420.81  5430.3  420.76  5463.0  420.98  5548.6  424.83
#Mann=7,-1,0
  4835.8    0.16       0  4849.2    0.12       0  4991.4    0.07       0
  4997.4    0.12       0  5092.8    0.16       0  5424.6    0.12       0
  5430.3    0.16       0
Bank Sta=4972.3,5323.1
Exp/Cntr=0.3,0.1

Type RM Length L Ch R = 1,11809,238,238,238
BEGIN DESCRIPTION:
White Oak Branch 2 23.0
END DESCRIPTION:
XS GIS Cut Line= 3
      2835775.03      7036675.02      2835525.00      7036475.00
      2835074.97      7036374.99
#Sta/Elev= 30
  4757.0  439.45  4849.1  433.01  4943.9  421.65  4977.1  417.57  4981.9  414.58
  4991.6  409.63  4996.6  408.96  4997.1  408.16  5002.6  408.96  5013.2  411.88
  5049.2  413.43  5055.6  412.19  5063.6  413.87  5070.0  411.75  5096.4  413.75
  5107.9  411.38  5128.4  410.47  5138.7  411.34  5151.1  414.75  5188.6  413.51
  5210.4  415.97  5271.8  415.46  5292.3  411.67  5312.8  414.71  5341.3  414.58
  5378.1  416.05  5405.0  424.89  5465.2  430.54  5519.0  437.92  5538.2  438.82
#Mann=5,-1,0
  4757.0    0.16       0  4943.9    0.12       0  4996.6    0.07       0
  5002.6    0.12       0  5151.1    0.16       0
Bank Sta=4981.9,5341.3
Exp/Cntr=0.3,0.1

Type RM Length L Ch R = 1,11571,295,295,295
BEGIN DESCRIPTION:
Mapping XS 68cf25f6
END DESCRIPTION:
XS GIS Cut Line= 3
      2835777.48      7036423.74      2835592.63      7036371.67
      2835204.60      7036324.79
#Sta/Elev= 30
  4805.3  425.59  4828.7  424.40  4839.0  423.30  4860.5  418.87  4882.4  417.36
  4922.2  414.16  4962.6  414.82  4976.1  414.02  4984.5  411.41  4990.5  406.54
  4991.0  405.74  4996.0  405.74  4996.5  406.54  5005.0  411.80  5010.6  412.20
  5065.5  412.47  5075.5  410.22  5085.6  412.80  5097.7  414.28  5125.9  413.33
  5148.3  414.18  5166.2  414.04  5174.6  409.46  5206.5  412.04  5216.6  411.71
  5226.6  409.94  5234.4  414.02  5236.7  415.25  5261.6  418.55  5388.2  426.21
#Mann=5,-1,0
  4805.3    0.16       0  4882.4    0.12       0  4990.5    0.07       0
  4996.5    0.12       0  5148.3    0.16       0
Bank Sta=4976.1,5234.4
Exp/Cntr=0.3,0.1

Type RM Length L Ch R = 1,11276,232,232,232
BEGIN DESCRIPTION:
Mapping XS 99fcc959
END DESCRIPTION:
XS GIS Cut Line= 3
      2835761.90      7036293.54      2835537.94      7036158.12
      2835285.38      7036129.48
#Sta/Elev= 30
  4697.7  421.19  4702.2  422.18  4708.1  421.74  4717.5  420.18  4723.6  417.34
  4730.5  416.92  4739.1  414.76  4755.7  413.14  4797.3  412.35  4840.0  413.45
  4892.4  412.06  4913.7  412.61  4935.1  411.30  4950.6  412.19  4956.4  410.95
  4982.5  410.95  4992.6  406.15  4997.9  405.47  4999.6  405.25  5000.1  404.45
  5005.1  404.45  5005.6  405.25  5025.7  413.14  5034.7  414.48  5073.1  415.60
  5173.7  428.62  5193.9  430.17  5209.0  429.14  5211.3  430.73  5213.6  430.73
#Mann=5,-1,0
  4697.7    0.16       0  4730.5    0.12       0  4997.9    0.16       0
  4999.6    0.07       0  5005.6    0.16       0
Bank Sta=4755.7,5025.7
Exp/Cntr=0.3,0.1

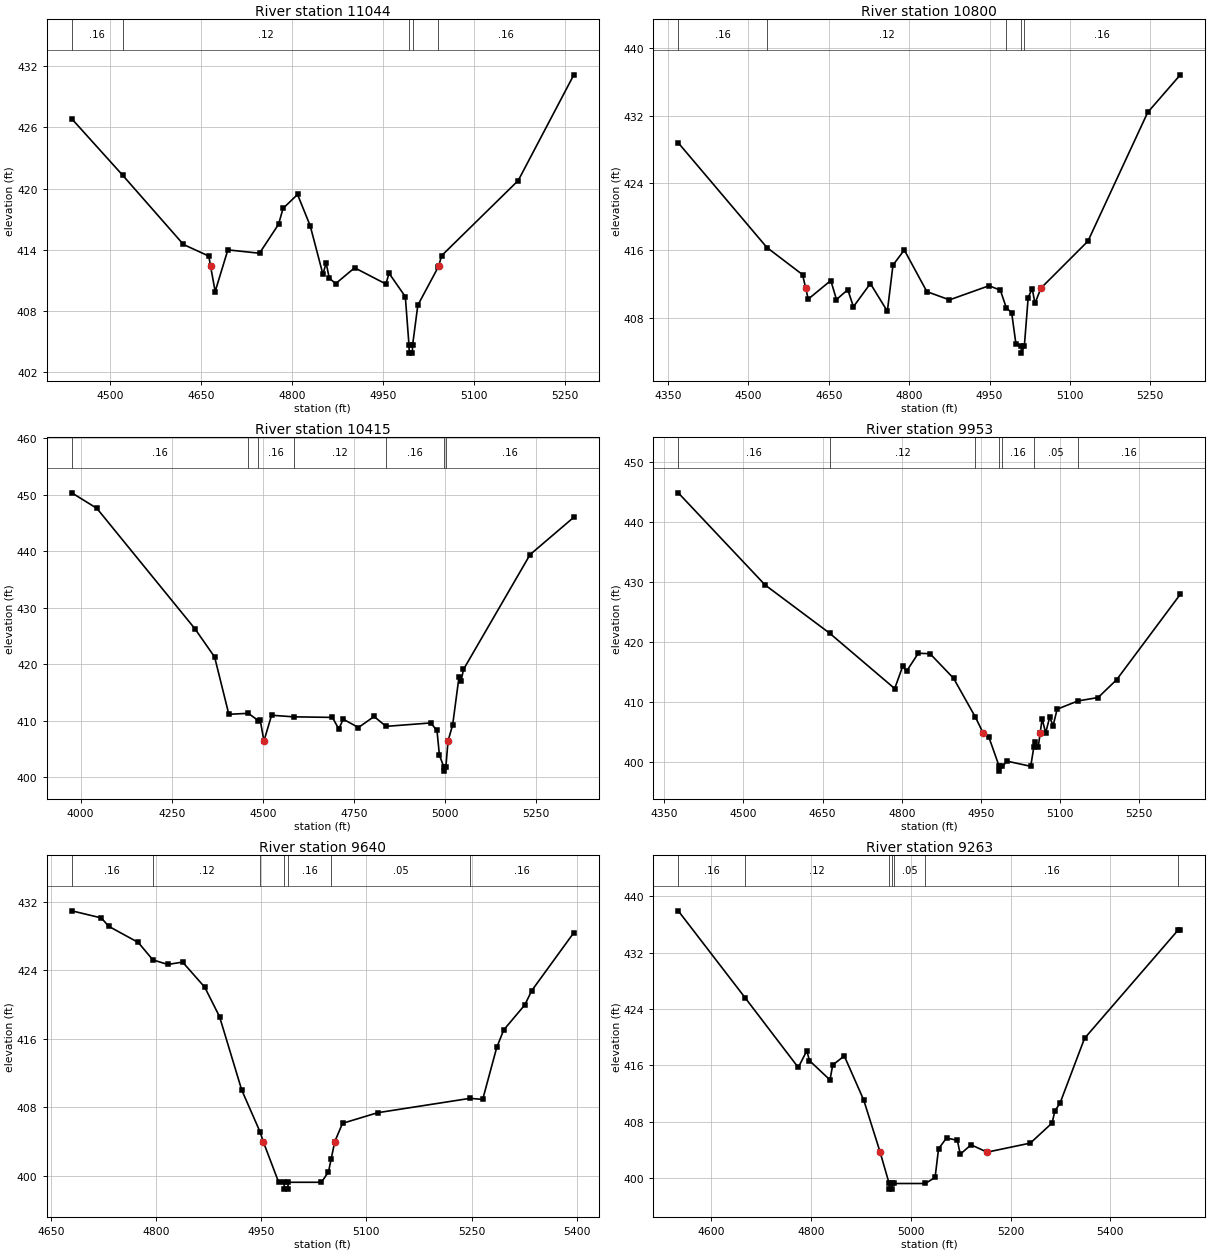
Type RM Length L Ch R = 1,11044,244,244,244
BEGIN DESCRIPTION:
Mapping XS d9597eda
END DESCRIPTION:
XS GIS Cut Line= 3
      2836111.13      7036211.98      2835574.40      7036048.75
      2835311.40      7036004.48
#Sta/Elev= 30
  4436.9  426.85  4521.1  421.29  4621.0  414.51  4662.8  413.37  4665.7  412.39
  4673.3  409.89  4694.2  413.98  4746.4  413.65  4777.8  416.49  4785.2  418.05
  4809.1  419.42  4830.0  416.34  4850.9  411.59  4856.2  412.69  4861.4  411.21
  4871.9  410.66  4903.2  412.22  4954.7  410.63  4960.0  411.68  4986.8  409.38
  4992.8  404.64  4993.3  403.84  4998.3  403.84  4998.8  404.64  5007.4  408.55
  5041.2  412.31  5041.6  412.39  5046.8  413.42  5172.9  420.79  5264.6  431.17
#Mann=5,-1,0
  4436.9    0.16       0  4521.1    0.12       0  4992.8    0.07       0
  4998.8    0.12       0  5041.2    0.16       0
Bank Sta=4665.7,5041.6
Exp/Cntr=0.3,0.1

Type RM Length L Ch R = 1,10800,385,385,385
BEGIN DESCRIPTION:
White Oak Branch 2 21.0
END DESCRIPTION:
XS GIS Cut Line= 3
      2836175.04      7036075.01      2835575.00      7035875.00
      2835275.04      7035825.01
#Sta/Elev= 30
  4369.3  428.77  4534.8  416.32  4601.2  413.10  4607.1  411.49  4611.8  410.19
  4653.9  412.40  4664.5  410.14  4685.6  411.31  4696.1  409.28  4727.7  412.04
  4759.4  408.75  4769.9  414.23  4791.0  416.03  4833.1  411.08  4875.3  410.10
  4949.1  411.78  4970.2  411.25  4981.1  409.19  4991.3  408.56  4999.2  404.89
  5008.9  404.57  5009.4  403.77  5014.9  404.57  5022.1  410.38  5029.7  411.44
  5034.7  409.67  5045.8  411.49  5133.6  417.08  5245.1  432.39  5305.9  436.85
#Mann=5,-1,0
  4369.3    0.16       0  4534.8    0.12       0  4981.1    0.16       0
  5008.9    0.07       0  5014.9    0.16       0
Bank Sta=4607.1,5045.8
Exp/Cntr=0.3,0.1

Type RM Length L Ch R = 1,10415,462,462,462
BEGIN DESCRIPTION:
White Oak Branch 2 20.0
END DESCRIPTION:
XS GIS Cut Line= 3
      2836475.02      7036025.01      2835475.00      7035625.00
      2835174.95      7035625.00
#Sta/Elev= 30
  3975.9  450.32  4044.6  447.58  4313.8  426.25  4367.7  421.26  4406.7  411.12
  4460.2  411.29  4488.0  409.98  4492.9  410.03  4503.0  406.39  4523.9  410.95
  4584.7  410.67  4690.8  410.57  4708.3  408.52  4720.4  410.25  4762.2  408.78
  4805.2  410.73  4837.8  408.98  4960.1  409.59  4977.6  408.27  4984.3  403.87
  4996.1  401.86  4996.6  401.06  5002.1  401.86  5007.9  406.39  5020.6  409.24
  5038.1  417.77  5043.5  416.96  5050.3  419.06  5233.0  439.39  5353.0  446.00
#Mann=7,-1,0
  3975.9    0.16       0  4460.2    0.12       0  4488.0    0.16       0
  4584.7    0.12       0  4837.8    0.16       0  4996.1    0.07       0
  5002.1    0.16       0
Bank Sta=4503,5007.9
Exp/Cntr=0.3,0.1

Type RM Length L Ch R = 1,9953,313,313,313
BEGIN DESCRIPTION:
White Oak Branch 2 19.0
END DESCRIPTION:
XS GIS Cut Line= 3
      2836375.02      7035775.01      2835816.59      7035494.06
      2835575.03      7035275.03
#Sta/Elev= 30
  4376.6  444.80  4541.2  429.44  4663.3  421.41  4786.7  412.17  4802.0  415.93
  4809.1  415.06  4831.4  418.06  4853.7  417.98  4898.3  413.88  4939.7  407.39
  4954.3  404.75  4965.3  404.03  4984.6  399.21  4985.1  398.41  4990.6  399.21
  4999.8  400.07  5044.4  399.21  5050.4  402.50  5051.8  403.27  5058.5  402.36
  5062.3  404.75  5066.0  407.13  5072.7  404.77  5080.2  407.38  5086.9  406.01
  5094.4  408.73  5133.5  410.10  5172.1  410.68  5207.2  413.65  5327.8  427.89
#Mann=7,-1,0
  4376.6    0.16       0  4663.3    0.12       0  4939.7    0.16       0
  4984.6    0.07       0  4990.6    0.16       0  5050.4    0.05       0
  5133.5    0.16       0
Bank Sta=4954.3,5062.3
Exp/Cntr=0.3,0.1

Type RM Length L Ch R = 1,9640,377,377,377
BEGIN DESCRIPTION:
White Oak Branch 2 18.0
END DESCRIPTION:
XS GIS Cut Line= 3
      2836274.99      7035325.00      2835975.00      7035225.00
      2835575.01      7035225.00
#Sta/Elev= 30
  4679.7  430.94  4721.8  430.11  4732.4  429.13  4774.6  427.24  4795.3  425.21
  4816.7  424.67  4837.8  424.95  4869.4  422.01  4890.5  418.57  4922.1  410.00
  4948.5  405.06  4952.8  403.97  4974.8  399.22  4982.4  399.21  4982.9  398.41
  4987.9  398.41  4988.4  399.21  5035.9  399.21  5045.9  400.43  5049.6  401.89
  5054.9  403.97  5065.9  406.10  5115.9  407.34  5247.7  409.02  5265.9  408.90
  5285.9  414.97  5295.9  417.02  5325.9  419.94  5335.9  421.62  5395.9  428.39
#Mann=7,-1,0
  4679.7    0.16       0  4795.3    0.12       0  4948.5    0.16       0
  4982.4    0.07       0  4988.4    0.16       0  5049.6    0.05       0
  5247.7    0.16       0
Bank Sta=4952.8,5054.9
Exp/Cntr=0.3,0.1

Type RM Length L Ch R = 1,9263,347,347,347
BEGIN DESCRIPTION:
White Oak Branch 2 17.0
END DESCRIPTION:
XS GIS Cut Line= 3
      2836325.02      7034674.99      2835875.00      7034875.00
      2835425.04      7035124.98
#Sta/Elev= 30
  4533.3  437.94  4667.7  425.57  4774.1  415.69  4791.2  418.06  4796.6  416.66
  4837.7  413.92  4843.2  416.04  4866.4  417.33  4905.4  411.06  4938.3  403.66
  4956.4  399.21  4956.9  398.41  4961.9  398.41  4962.4  399.21  4965.5  399.21
  5029.0  399.21  5048.6  400.08  5055.5  404.14  5071.5  405.67  5093.3  405.34
  5099.0  403.36  5120.7  404.71  5152.8  403.66  5239.7  404.95  5283.2  407.80
  5288.9  409.52  5299.2  410.62  5348.4  419.83  5536.6  435.25  5540.5  435.25
#Mann=7,-1,0
  4533.3    0.16       0  4667.7    0.12       0  4956.4   0.035       0
  4962.4    0.12       0  4965.5    0.05       0  5029.0    0.16       0
  5536.6    0.05       0
Bank Sta=4938.3,5152.8
Exp/Cntr=0.3,0.1