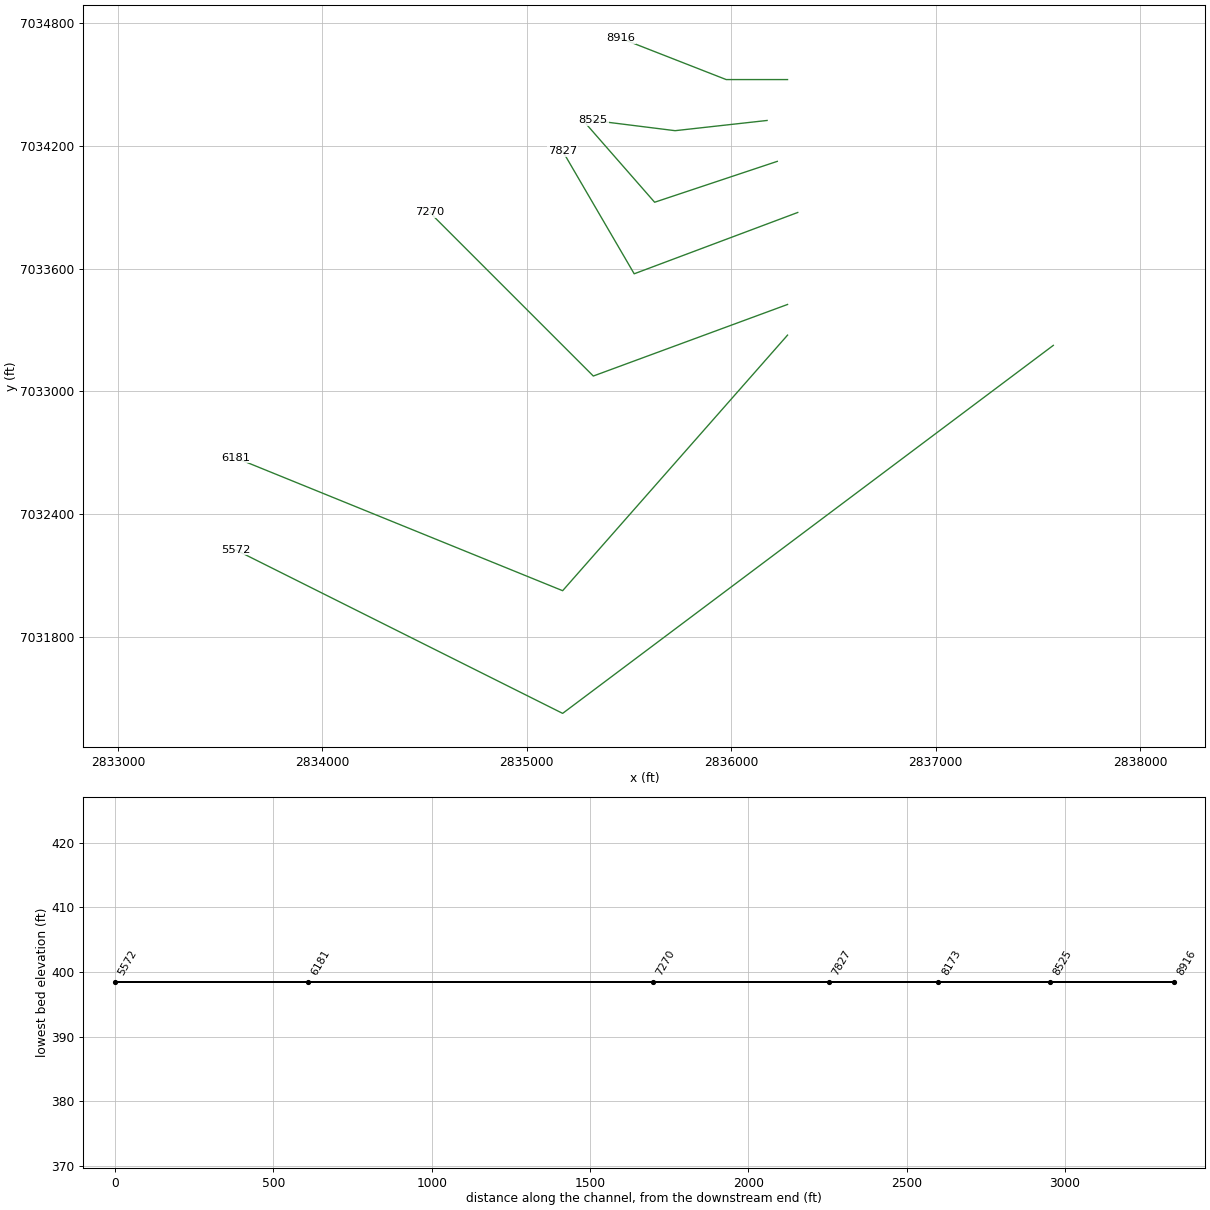
HEC-RAS study White Oak Branch 2.prj: White Oak Branch 2 Base Level Engineering

--- White Oak Branch 2.g01 (geometry) --- (continued)

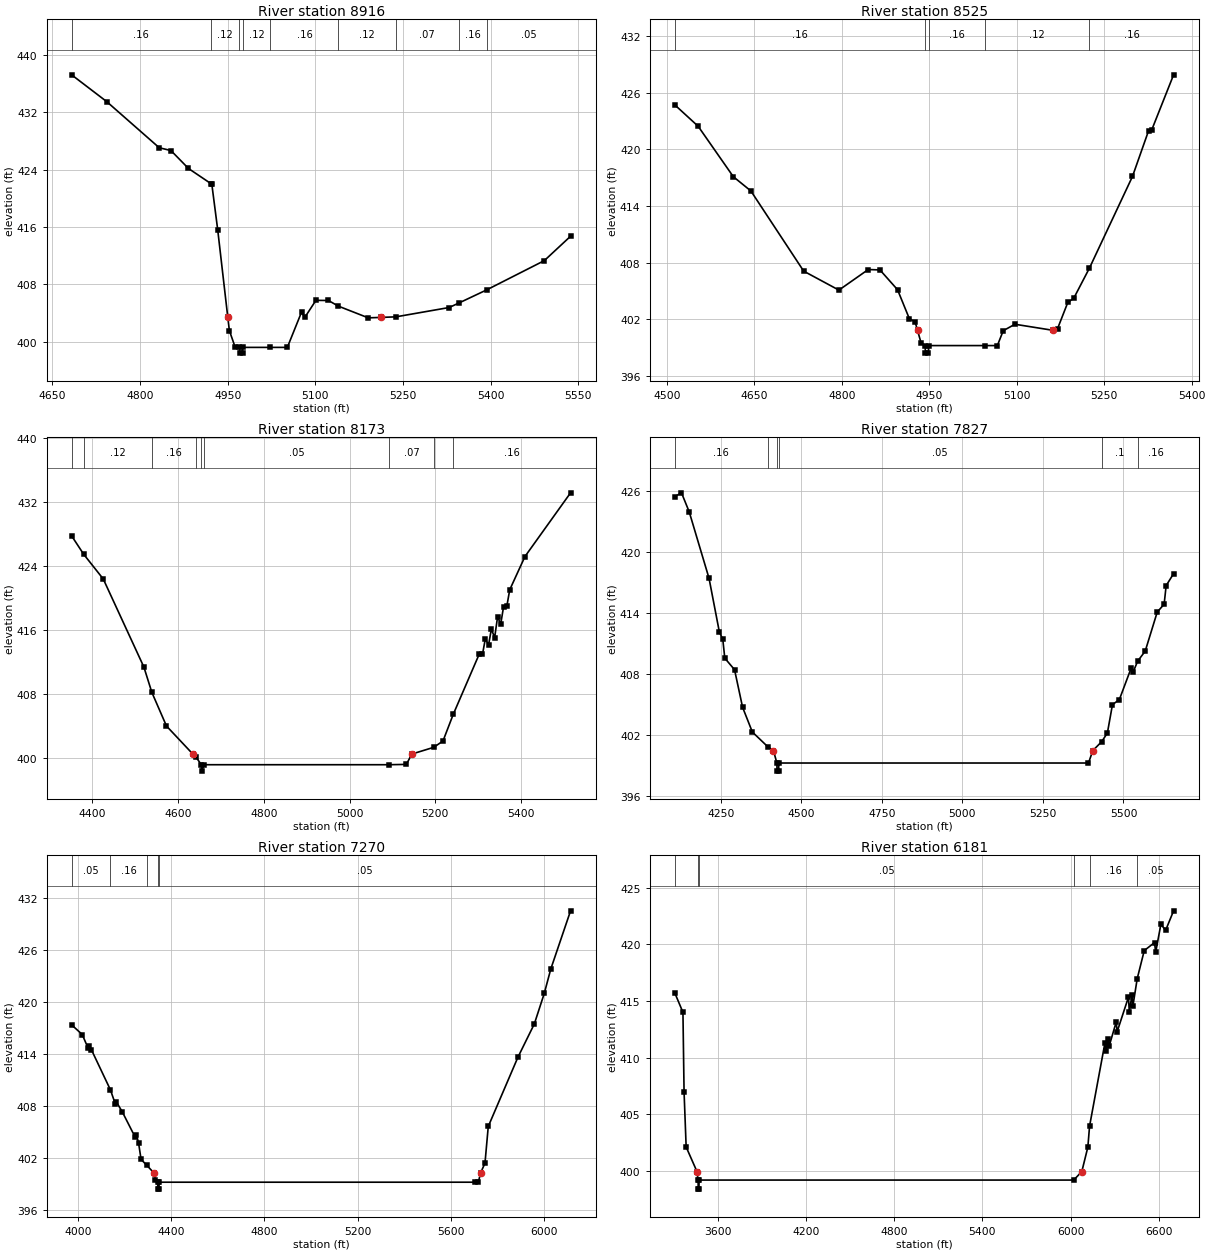
Type RM Length L Ch R = 1,8916,391,391,391
BEGIN DESCRIPTION:
White Oak Branch 2 16.0
END DESCRIPTION:
XS GIS Cut Line= 3
      2836274.96      7034525.00      2835975.00      7034525.00
      2835459.07      7034726.66
#Sta/Elev= 30
  4682.9  437.22  4742.9  433.49  4832.9  427.05  4852.9  426.66  4882.9  424.16
  4921.1  422.06  4922.9  421.94  4932.9  415.63  4950.2  403.39  4952.9  401.55
  4962.9  399.21  4969.9  399.21  4970.4  398.41  4975.4  398.41  4975.9  399.21
  5023.2  399.21  5052.1  399.21  5076.6  404.17  5081.9  403.38  5101.0  405.77
  5122.4  405.75  5139.5  404.96  5190.6  403.33  5212.1  403.39  5237.9  403.47
  5329.0  404.77  5345.2  405.38  5393.0  407.22  5491.9  411.31  5536.8  414.71
#Mann=9,-1,0
  4682.9    0.16       0  4921.1    0.12       0  4969.9    0.07       0
  4975.9    0.12       0  5023.2    0.16       0  5139.5    0.12       0
  5237.9    0.07       0  5345.2    0.16       0  5393.0    0.05       0
Bank Sta=4950.2,5212.1
Exp/Cntr=0.3,0.1

Type RM Length L Ch R = 1,8525,352,352,352
BEGIN DESCRIPTION:
White Oak Branch 2 15.0
END DESCRIPTION:
XS GIS Cut Line= 3
      2836175.04      7034325.00      2835725.00      7034275.00
      2835325.03      7034325.00
#Sta/Elev= 30
  4513.1  424.74  4553.4  422.46  4613.8  417.11  4643.9  415.60  4734.5  407.10
  4794.9  405.09  4845.2  407.27  4865.3  407.23  4895.5  405.13  4915.6  402.08
  4925.7  401.70  4929.8  400.82  4935.7  399.52  4942.8  399.21  4943.3  398.41
  4948.3  398.41  4948.8  399.21  5045.3  399.21  5066.7  399.21  5076.8  400.79
  5096.9  401.47  5162.9  400.82  5170.0  401.01  5187.6  403.79  5197.7  404.22
  5224.7  407.43  5298.5  417.14  5326.2  422.00  5331.2  422.02  5369.0  427.91
#Mann=5,-1,0
  4513.1    0.16       0  4942.8   0.033       0  4948.8    0.16       0
  5045.3    0.12       0  5224.7    0.16       0
Bank Sta=4929.8,5162.9
Exp/Cntr=0.3,0.1

Type RM Length L Ch R = 1,8173,346,346,346
BEGIN DESCRIPTION:
White Oak Branch 2 14.0
END DESCRIPTION:
XS GIS Cut Line= 3
      2836224.99      7034125.00      2835625.00      7033925.00
      2835274.97      7034325.04
#Sta/Elev= 30
  4351.4  427.77  4379.6  425.47  4425.2  422.39  4520.0  411.40  4538.5  408.25
  4572.7  404.04  4634.2  400.54  4642.1  400.12  4654.1  399.21  4654.6  398.41
  4660.1  399.21  5092.2  399.21  5132.4  399.25  5145.0  400.54  5196.2  401.38
  5217.8  402.17  5241.6  405.48  5302.7  413.06  5309.9  412.99  5316.5  414.89
  5324.1  414.17  5330.7  416.13  5338.3  415.07  5345.0  417.61  5352.6  416.81
  5359.2  418.95  5366.8  419.02  5373.5  421.04  5409.0  425.19  5515.4  433.14
#Mann=9,-1,0
  4351.4    0.16       0  4379.6    0.12       0  4538.5    0.16       0
  4642.1    0.05       0  4654.1   0.033       0  4660.1    0.05       0
  5092.2    0.07       0  5196.2    0.12       0  5241.6    0.16       0
Bank Sta=4634.2,5145
Exp/Cntr=0.3,0.1

Type RM Length L Ch R = 1,7827,557,557,557
BEGIN DESCRIPTION:
White Oak Branch 2 13.0
END DESCRIPTION:
XS GIS Cut Line= 3
      2836324.99      7033875.00      2835525.00      7033575.00
      2835175.01      7034174.99
#Sta/Elev= 30
  4106.6  425.47  4127.9  425.85  4152.0  423.96  4213.4  417.42  4245.4  412.14
  4256.1  411.40  4262.3  409.55  4292.6  408.41  4317.5  404.71  4347.8  402.27
  4395.6  400.82  4413.4  400.43  4424.0  399.21  4424.5  398.41  4429.5  398.41
  4430.0  399.21  5391.4  399.21  5404.8  400.43  5432.5  401.32  5450.1  402.17
  5465.8  404.96  5487.3  405.47  5524.5  408.62  5530.3  408.20  5544.2  409.26
  5567.5  410.24  5604.8  414.09  5626.3  414.87  5632.5  416.70  5655.6  417.88
#Mann=6,-1,0
  4106.6    0.16       0  4395.6    0.05       0  4424.0   0.033       0
  4430.0    0.05       0  5432.5     0.1       0  5544.2    0.16       0
Bank Sta=4413.4,5404.8
Exp/Cntr=0.3,0.1

Type RM Length L Ch R = 1,7270,1089,1089,1089
BEGIN DESCRIPTION:
White Oak Branch 2 12.0
END DESCRIPTION:
XS GIS Cut Line= 3
      2836274.99      7033425.00      2835325.00      7033075.00
      2834524.99      7033875.01
#Sta/Elev= 30
  3971.4  417.39  4017.1  416.27  4042.2  414.69  4047.5  414.91  4056.7  414.50
  4138.3  409.87  4158.7  408.28  4164.0  408.47  4189.1  407.34  4244.7  404.40
  4250.0  404.66  4259.1  403.74  4269.8  401.85  4293.7  401.18  4325.1  400.28
  4330.7  399.52  4341.4  399.21  4341.9  398.41  4346.9  398.41  4347.4  399.21
  5705.1  399.21  5719.2  399.23  5728.6  400.28  5747.5  401.41  5761.6  405.65
  5888.9  413.64  5959.6  417.50  6002.1  421.01  6030.3  423.84  6115.2  430.56
#Mann=5,-1,0
  3971.4    0.05       0  4138.3    0.16       0  4293.7    0.05       0
  4341.4   0.033       0  4347.4    0.05       0
Bank Sta=4325.1,5728.6
Exp/Cntr=0.3,0.1

Type RM Length L Ch R = 1,6181,609,609,609
BEGIN DESCRIPTION:
White Oak Branch 2 11.0
END DESCRIPTION:
XS GIS Cut Line= 3
      2836275.02      7033275.03      2835175.00      7032025.00
      2833575.01      7032675.00
#Sta/Elev= 30
  3307.8  415.76  3364.3  414.01  3371.9  406.98  3386.1  402.13  3459.6  399.96
  3467.4  399.21  3467.9  398.41  3473.3  398.41  3473.8  399.21  6020.8  399.21
  6076.0  399.96  6117.1  402.12  6128.7  403.97  6232.7  411.28  6238.1  410.57
  6256.7  411.64  6262.1  411.04  6310.3  413.18  6315.7  412.28  6393.3  415.36
  6398.7  414.07  6417.4  415.55  6422.8  414.53  6452.6  416.98  6500.4  419.46
  6570.4  420.17  6578.1  419.31  6613.6  421.78  6645.9  421.25  6699.9  422.97
#Mann=6,-1,0
  3307.8    0.05       0  3467.4   0.033       0  3473.8    0.05       0
  6020.8    0.07       0  6128.7    0.16       0  6452.6    0.05       0
Bank Sta=3459.6,6076
Exp/Cntr=0.3,0.1

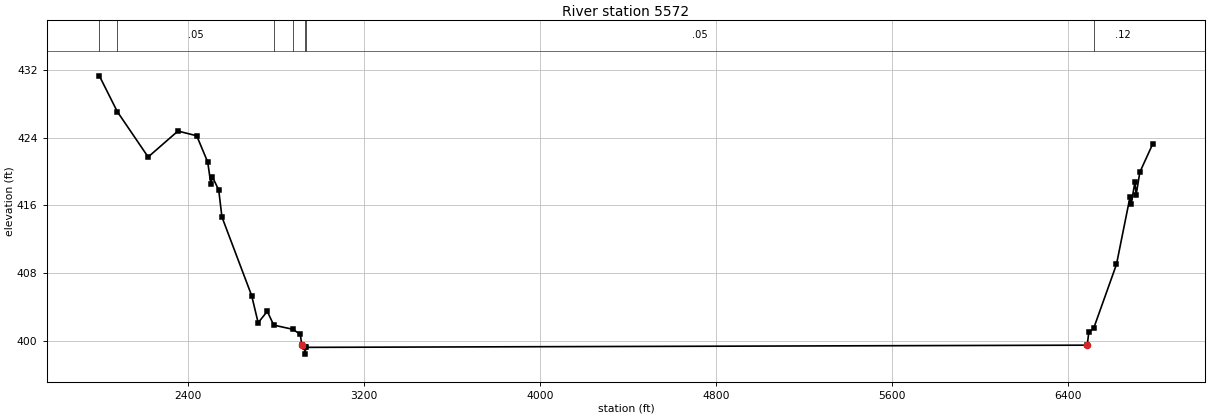
Type RM Length L Ch R = 1,5572,0,0,0
BEGIN DESCRIPTION:
White Oak Branch 2 10.0
END DESCRIPTION:
XS GIS Cut Line= 3
      2837574.98      7033224.99      2835175.00      7031425.00
      2833575.03      7032224.98
#Sta/Elev= 30
  1996.8  431.32  2078.6  427.08  2218.7  421.72  2354.1  424.79  2439.5  424.23
  2489.5  421.12  2504.1  418.47  2510.3  419.40  2539.5  417.82  2554.1  414.63
  2689.5  405.31  2718.7  402.12  2760.3  403.47  2789.6  401.84  2875.6  401.35
  2910.3  400.76  2917.3  399.47  2929.8  399.21  2930.3  398.41  2936.6  399.21
  6487.7  399.47  6494.9  400.99  6516.9  401.45  6620.7  409.02  6682.2  416.98
  6687.8  416.14  6704.6  418.79  6710.2  417.26  6726.9  419.92  6785.6  423.27
#Mann=7,-1,0
  1996.8    0.16       0  2078.6    0.05       0  2789.6    0.16       0
  2875.6    0.05       0  2929.8   0.033       0  2936.6    0.05       0
  6516.9    0.12       0
Bank Sta=2917.3,6487.7
Exp/Cntr=0.3,0.1

Chan Stop Cuts=-1