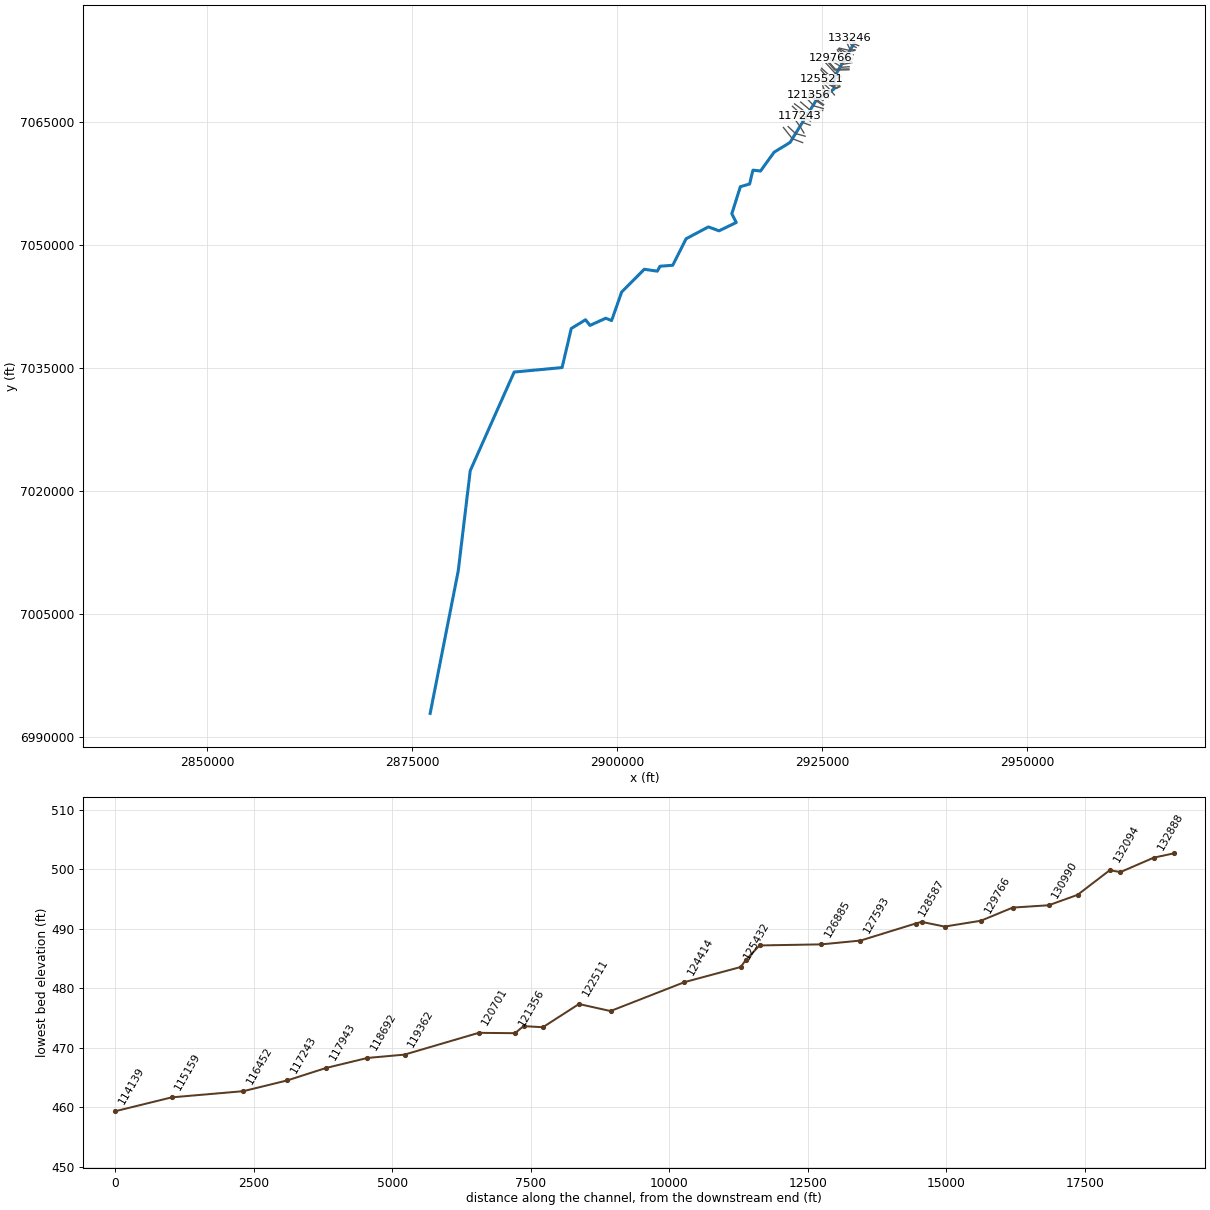
--- CANEY CREEK.prj (project) ---

Proj Title=CANEY CREEK Base Level Engineering
Current Plan=p01
Default Exp/Contr=0.3,0.1
English Units
Geom File=g01
Flow File=f01
Plan File=p01
BEGIN DESCRIPTION:
CANEY CREEK
END DESCRIPTION:

--- CANEY CREEK.p01 (plan) ---

Plan Title=Multiple Run
Short Identifier=Multiple
Geom File=g01
Flow File=f01
Subcritical Flow
K Sum by GR= 0
Std Step Tol= 0.01
Critical Tol= 0.01
Num of Std Step Trials= 20
Max Error Tol= 0.3
Flow Tol Ratio= 0.001
Split Flow NTrial= 30
Split Flow Tol= 0.02
Split Flow Ratio= 0.02
Log Output Level= 0
Friction Slope Method= 1
Unsteady Friction Slope Method= 2
Unsteady Bridges Friction Slope Method= 1
Parabolic Critical Depth
Global Vel Dist=  1 , 1 , 1
Global Log Level= 0
CheckData=True
Encroach Param= -1, 0, 0, 0
BEGIN DESCRIPTION:
Multiple Run
END DESCRIPTION:

--- CANEY CREEK.f01 (steady flow) ---

Flow Title=Multiple
Program Version=5.07
Number of Profiles= 7
Profile Names=10-year,25-year,50-year,1pct_min,100-year,1pct_plu,500-year
River Rch & RM=CANEY CREEK,Reach-1         ,133246
     818    1101    1332     799    1594    3180    2276
River Rch & RM=CANEY CREEK,Reach-1         ,132888
     842    1134    1372     823    1642    3276    2345
River Rch & RM=CANEY CREEK,Reach-1         ,131512
    1602    2225    2746    1676    3343    6670    4948
River Rch & RM=CANEY CREEK,Reach-1         ,124414
    2045    2875    3578    2200    4389    8757    6595
River Rch & RM=CANEY CREEK,Reach-1         ,121356
    2590    3679    4610    2852    5690   11352    8656
River Rch & RM=CANEY CREEK,Reach-1         ,118692
    2803    3989    5004    3097    6179   12329    9413
River Rch & RM=CANEY CREEK,Reach-1         ,115159
    3082    4400    5532    3430    6844   13656   10467
River Rch & RM=CANEY CREEK,Reach-1         ,112328
    3174    4528    5688    3524    7032   14030   10737
River Rch & RM=CANEY CREEK,Reach-1         ,109745
    4148    5977    7562    4715    9407   18770   14545
River Rch & RM=CANEY CREEK,Reach-1         ,105695
    4642    6718    8524    5330   10634   21219   16540
River Rch & RM=CANEY CREEK,Reach-1         ,103499
    4691    6769    8571    5348   10671   21292   16535
River Rch & RM=CANEY CREEK,Reach-1         ,93432
    4610    6636    8390    5226   10427   20804   16101
River Rch & RM=CANEY CREEK,Reach-1         ,89695
    4894    7065    8949    5585   11143   22234   17275
River Rch & RM=CANEY CREEK,Reach-1         ,87623
    4985    7178    9077    5655   11283   22513   17432
River Rch & RM=CANEY CREEK,Reach-1         ,80255
    5571    8042   10188    6359   12687   25315   19684
River Rch & RM=CANEY CREEK,Reach-1         ,76222
    5899    8535   10832    6773   13513   26963   21041
River Rch & RM=CANEY CREEK,Reach-1         ,73251
    5936    8573   10866    6785   13537   27010   21022
River Rch & RM=CANEY CREEK,Reach-1         ,71314
    5964    8607   10903    6805   13578   27091   21066
River Rch & RM=CANEY CREEK,Reach-1         ,63746
    6016    8682   10999    6865   13697   27329   21252
River Rch & RM=CANEY CREEK,Reach-1         ,62678
    5981    8619   10908    6801   13570   27075   21011
River Rch & RM=CANEY CREEK,Reach-1         ,59943
    6065    8734   11047    6884   13735   27405   21244
River Rch & RM=CANEY CREEK,Reach-1         ,52813
    6102    8777   11094    6908   13783   27500   21285
Boundary for River Rch & Prof#=CANEY CREEK,Reach-1         , 1
Up Type= 0
Dn Type= 3
Dn Slope=0.00031
Boundary for River Rch & Prof#=CANEY CREEK,Reach-1         , 2
Up Type= 0
Dn Type= 3
Dn Slope=0.00031
Boundary for River Rch & Prof#=CANEY CREEK,Reach-1         , 3
Up Type= 0
Dn Type= 3
Dn Slope=0.00031
Boundary for River Rch & Prof#=CANEY CREEK,Reach-1         , 4
Up Type= 0
Dn Type= 3
Dn Slope=0.00031
Boundary for River Rch & Prof#=CANEY CREEK,Reach-1         , 5
Up Type= 0
Dn Type= 3
Dn Slope=0.00031
Boundary for River Rch & Prof#=CANEY CREEK,Reach-1         , 6
Up Type= 0
Dn Type= 3
Dn Slope=0.00031
Boundary for River Rch & Prof#=CANEY CREEK,Reach-1         , 7
Up Type= 0
Dn Type= 3
Dn Slope=0.00031
DSS Import GetInterval= 0
DSS Import GetPeak= 0
DSS Import FillOption= 0

--- CANEY CREEK.g01 (geometry) ---

Geom Title=Existing Conditions

River Reach=CANEY CREEK,Reach-1
Reach XY= 30
      2928919.28      7074649.44      2926510.54      7070569.29
      2926419.52      7069018.05      2924295.59      7067700.71
      2921073.37      7062512.20      2919135.34      7061329.87
      2917478.44      7059036.14      2916553.36      7059143.39
      2916146.17      7057450.99      2915023.00      7057127.42
      2913979.01      7053829.01      2914519.45      7052754.96
      2912415.10      7051741.85      2911126.50      7052218.69
      2908402.69      7050775.66      2906774.56      7047543.19
      2905220.40      7047418.86      2904891.49      7046820.67
      2903303.64      7047052.66      2900541.75      7044279.11
      2899316.30      7040795.63      2898603.28      7041082.11
      2896680.99      7040203.67      2896136.19      7040892.76
      2894399.73      7039830.61      2893275.92      7035063.33
      2887433.32      7034516.07      2882077.34      7022495.70
      2880610.70      7010259.30      2877188.26      6992888.46

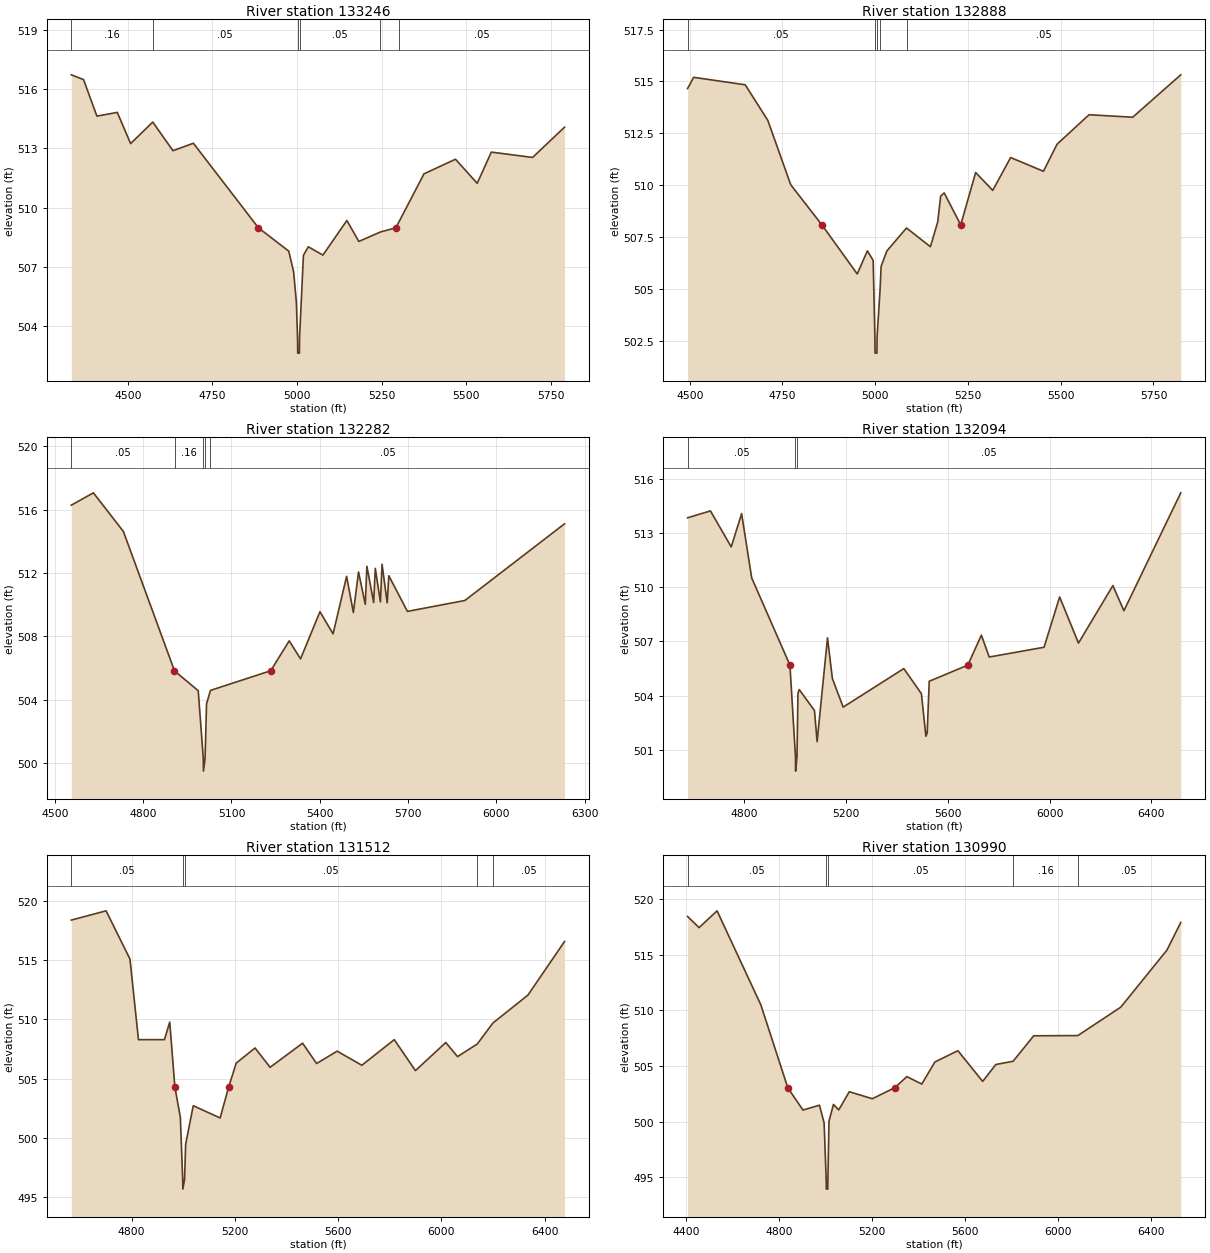
Type RM Length L Ch R = 1,133246,358,358,358
BEGIN DESCRIPTION:
CANEY CREEK 134.0
END DESCRIPTION:
XS GIS Cut Line= 3
      2929448.74      7074322.33      2928901.85      7074530.67
      2928363.63      7075216.46
#Sta/Elev= 30
  4333.3  516.72  4369.4  516.48  4408.9  514.63  4469.1  514.82  4508.5  513.24
  4573.9  514.33  4633.7  512.88  4693.9  513.26  4886.0  508.98  4975.7  507.80
  4990.1  506.75  4998.2  505.21  5001.6  503.44  5002.1  502.64  5007.1  502.64
  5007.6  503.44  5019.0  507.59  5033.5  508.02  5076.6  507.60  5147.4  509.35
  5182.7  508.29  5246.7  508.77  5291.7  508.98  5302.5  509.32  5375.2  511.71
  5468.3  512.45  5532.4  511.23  5574.1  512.81  5696.1  512.54  5790.3  514.07
#Mann=6,-1,0
  4333.3    0.16       0  4573.9    0.05       0  5001.6    0.03       0
  5007.6    0.05       0  5246.7    0.16       0  5302.5    0.05       0
Bank Sta=4886,5291.7
Exp/Cntr=0.3,0.1

Type RM Length L Ch R = 1,132888,606,606,606
BEGIN DESCRIPTION:
Mapping XS c2e28dfc
END DESCRIPTION:
XS GIS Cut Line= 4
      2929140.53      7074101.00      2928762.96      7074278.93
      2928541.61      7074409.14      2928194.41      7074964.66
#Sta/Elev= 30
  4494.3  514.66  4510.7  515.20  4649.7  514.84  4710.5  513.13  4772.4  510.03
  4856.4  508.10  4951.6  505.74  4978.9  506.85  4994.5  506.39  4999.1  502.73
  4999.6  501.93  5004.6  501.93  5005.1  502.73  5013.0  504.94  5016.0  506.11
  5031.6  506.85  5084.4  507.95  5148.8  507.05  5168.5  508.24  5176.4  509.48
  5185.9  509.64  5230.5  508.10  5270.8  510.62  5316.8  509.76  5365.1  511.34
  5453.5  510.68  5490.1  511.98  5576.4  513.40  5694.1  513.28  5823.6  515.32
#Mann=5,-1,0
  4494.3    0.05       0  4999.1    0.03       0  5005.1    0.05       0
  5013.0    0.16       0  5084.4    0.05       0
Bank Sta=4856.4,5230.5
Exp/Cntr=0.3,0.1

Type RM Length L Ch R = 1,132282,188,188,188
BEGIN DESCRIPTION:
CANEY CREEK 133.0
END DESCRIPTION:
XS GIS Cut Line= 4
      2928979.95      7073827.54      2928680.50      7073814.52
      2928368.00      7073905.67      2927929.94      7074859.86
#Sta/Elev= 30
  4556.0  516.29  4631.0  517.07  4732.9  514.63  4906.4  505.83  4906.6  505.82
  4987.1  504.57  5004.3  500.29  5004.8  499.49  5010.3  500.29  5015.3  503.74
  5028.7  504.59  5233.2  505.83  5296.2  507.72  5334.6  506.58  5400.6  509.56
  5445.1  508.16  5491.1  511.79  5514.1  509.51  5531.6  512.07  5554.5  510.03
  5560.0  512.43  5583.0  510.14  5588.5  512.30  5606.0  510.18  5611.5  512.56
  5629.0  510.12  5634.5  511.83  5697.7  509.58  5892.9  510.27  6231.2  515.11
#Mann=5,-1,0
  4556.0    0.05       0  4906.6    0.16       0  5004.3    0.07       0
  5010.3    0.16       0  5028.7    0.05       0
Bank Sta=4906.4,5233.2
Exp/Cntr=0.3,0.1

Type RM Length L Ch R = 1,132094,582,582,582
BEGIN DESCRIPTION:
CANEY CREEK 132.0
END DESCRIPTION:
XS GIS Cut Line= 3
      2928993.04      7073740.75      2928650.11      7073671.29
      2927100.63      7074018.52
#Sta/Elev= 30
  4577.6  513.84  4667.4  514.22  4749.1  512.23  4789.9  514.07  4829.4  510.52
  4979.8  505.69  5001.5  500.63  5002.0  499.83  5007.5  500.63  5011.3  504.14
  5016.4  504.34  5076.2  503.18  5086.5  501.46  5127.4  507.20  5146.5  504.95
  5188.9  503.37  5427.2  505.50  5496.4  504.11  5513.9  501.76  5519.0  501.93
  5527.1  504.80  5678.6  505.69  5732.1  507.35  5762.8  506.14  5978.3  506.68
  6039.5  509.46  6113.5  506.91  6248.7  510.09  6292.1  508.70  6515.4  515.22
#Mann=3,-1,0
  4577.6    0.05       0  5001.5    0.03       0  5007.5    0.05       0
Bank Sta=4979.8,5678.6
Exp/Cntr=0.3,0.1

Type RM Length L Ch R = 1,131512,522,522,522
BEGIN DESCRIPTION:
CANEY CREEK 131.0
END DESCRIPTION:
XS GIS Cut Line= 3
      2928775.99      7073211.22      2928203.07      7073345.77
      2927040.58      7073973.40
#Sta/Elev= 30
  4566.9  518.36  4701.5  519.14  4793.9  515.08  4826.9  508.28  4927.4  508.28
  4948.0  509.76  4967.9  504.28  4989.1  501.74  4998.2  496.48  4998.7  495.68
  5005.3  496.48  5009.6  499.46  5039.0  502.71  5143.1  501.68  5176.0  504.28
  5205.4  506.30  5278.2  507.58  5336.7  505.95  5462.4  507.98  5516.7  506.27
  5596.4  507.31  5691.8  506.12  5817.4  508.28  5899.3  505.67  6016.9  508.04
  6062.4  506.85  6139.1  507.92  6199.3  509.68  6335.1  512.04  6476.5  516.55
#Mann=5,-1,0
  4566.9    0.05       0  4998.2    0.03       0  5005.3    0.05       0
  6139.1    0.16       0  6199.3    0.05       0
Bank Sta=4967.9,5176
Exp/Cntr=0.3,0.1

Type RM Length L Ch R = 1,130990,649,649,649
BEGIN DESCRIPTION:
CANEY CREEK 130.0
END DESCRIPTION:
XS GIS Cut Line= 3
      2928676.13      7072725.12      2928025.11      7072924.76
      2926977.05      7073910.90
#Sta/Elev= 30
  4407.1  518.45  4456.6  517.45  4533.8  518.96  4722.1  510.50  4837.8  503.05
  4903.2  501.04  4973.9  501.48  4994.0  499.88  5003.0  494.73  5003.6  493.93
  5009.7  493.93  5010.2  494.73  5014.9  500.04  5034.2  501.55  5056.8  501.05
  5102.2  502.69  5201.4  502.06  5297.4  503.05  5349.8  504.05  5413.8  503.38
  5470.4  505.37  5569.1  506.38  5675.6  503.62  5732.2  505.14  5806.6  505.43
  5894.9  507.72  6084.6  507.74  6269.5  510.30  6467.8  515.43  6527.1  517.91
#Mann=5,-1,0
  4407.1    0.05       0  5003.0    0.03       0  5010.2    0.05       0
  5806.6    0.16       0  6084.6    0.05       0
Bank Sta=4837.8,5297.4
Exp/Cntr=0.3,0.1

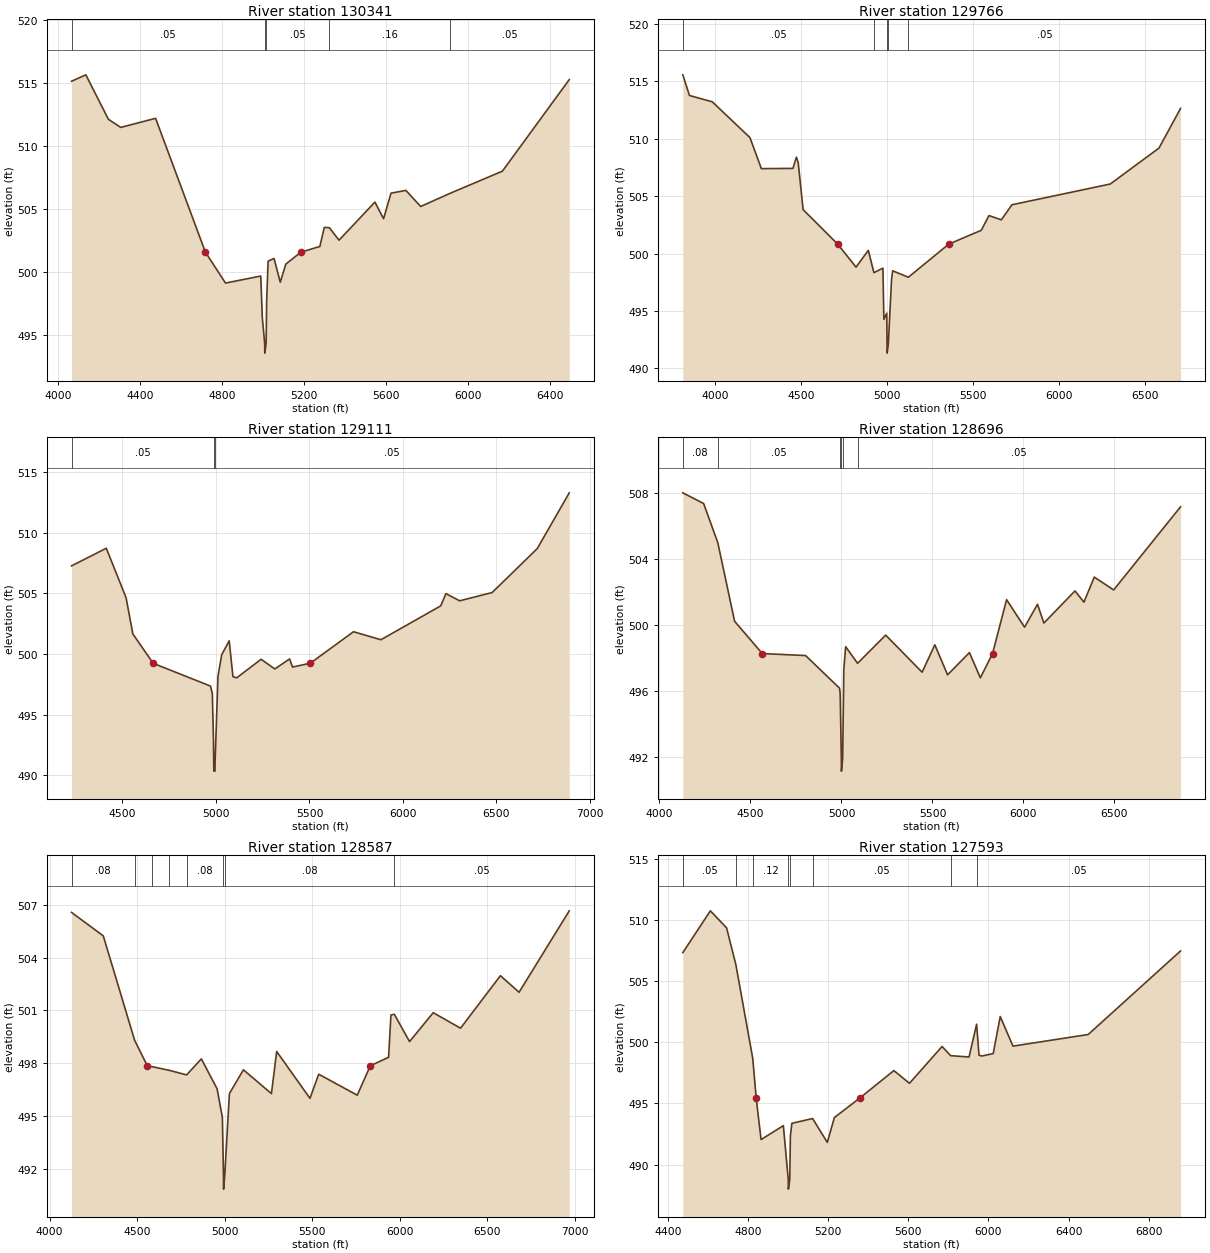
Type RM Length L Ch R = 1,130341,575,575,575
BEGIN DESCRIPTION:
CANEY CREEK 129.0
END DESCRIPTION:
XS GIS Cut Line= 3
      2928554.68      7072434.31      2927703.93      7072475.00
      2926844.57      7073797.14
#Sta/Elev= 30
  4067.1  515.16  4136.9  515.67  4247.0  512.13  4307.1  511.49  4477.2  512.21
  4720.2  501.57  4818.4  499.11  4990.4  499.67  4997.9  496.36  5009.4  494.34
  5010.0  493.54  5016.6  494.34  5019.0  497.64  5026.2  500.85  5055.2  501.07
  5085.5  499.18  5112.6  500.62  5186.4  501.57  5278.6  502.02  5300.5  503.54
  5325.4  503.51  5372.2  502.52  5547.4  505.55  5589.6  504.23  5625.9  506.26
  5698.4  506.48  5770.8  505.20  5913.1  506.24  6169.5  508.01  6495.7  515.29
#Mann=5,-1,0
  4067.1    0.05       0  5009.4    0.03       0  5016.6    0.05       0
  5325.4    0.16       0  5913.1    0.05       0
Bank Sta=4720.2,5186.4
Exp/Cntr=0.3,0.1

Type RM Length L Ch R = 1,129766,655,655,655
BEGIN DESCRIPTION:
CANEY CREEK 128.0
END DESCRIPTION:
XS GIS Cut Line= 3
      2928663.12      7072265.04      2927561.35      7072049.23
      2925985.22      7072855.30
#Sta/Elev= 30
  3811.8  515.57  3850.6  513.77  3983.1  513.22  4202.2  510.10  4268.4  507.40
  4451.9  507.42  4472.2  508.40  4482.4  507.94  4511.1  503.83  4712.4  500.82
  4818.7  498.82  4890.0  500.28  4922.6  498.34  4974.9  498.73  4980.5  494.27
  4997.1  494.81  4999.0  492.13  4999.6  491.33  5006.4  492.13  5025.0  497.72
  5031.5  498.50  5122.7  497.94  5357.4  500.82  5546.8  502.03  5591.3  503.31
  5663.5  502.94  5724.5  504.25  6296.5  506.06  6579.6  509.19  6704.8  512.64
#Mann=5,-1,0
  3811.8    0.05       0  4922.6    0.16       0  4999.0    0.07       0
  5006.4    0.16       0  5122.7    0.05       0
Bank Sta=4712.4,5357.4
Exp/Cntr=0.3,0.1

Type RM Length L Ch R = 1,129111,415,415,415
BEGIN DESCRIPTION:
CANEY CREEK 127.0
END DESCRIPTION:
XS GIS Cut Line= 3
      2928295.98      7071752.89      2927400.11      7071690.39
      2925900.13      7072617.46
#Sta/Elev= 30
  4227.8  507.27  4413.6  508.72  4519.5  504.64  4555.6  501.66  4664.1  499.24
  4970.6  497.36  4980.6  496.76  4986.7  492.89  4988.0  491.15  4988.6  490.35
  4994.9  490.35  4995.4  491.15  5010.7  498.15  5030.7  499.95  5070.8  501.09
  5090.9  498.14  5110.9  498.04  5241.4  499.57  5314.7  498.77  5393.9  499.60
  5409.3  498.93  5504.2  499.24  5735.5  501.84  5882.1  501.18  6201.6  503.97
  6229.7  504.98  6303.0  504.39  6476.7  505.07  6717.9  508.69  6889.2  513.29
#Mann=3,-1,0
  4227.8    0.05       0  4988.0    0.03       0  4995.4    0.05       0
Bank Sta=4664.1,5504.2
Exp/Cntr=0.3,0.1

Type RM Length L Ch R = 1,128696,109,109,109
BEGIN DESCRIPTION:
CANEY CREEK 126.0
END DESCRIPTION:
XS GIS Cut Line= 3
      2928259.52      7071487.27      2926603.24      7071450.81
      2925890.59      7072259.80
#Sta/Elev= 30
  4128.2  508.02  4242.7  507.37  4320.4  505.00  4412.8  500.23  4564.9  498.27
  4802.9  498.15  4989.4  496.17  4992.9  495.83  4999.2  491.94  4999.8  491.14
  5006.6  491.94  5012.9  497.33  5022.9  498.69  5088.4  497.68  5243.0  499.39
  5443.0  497.14  5513.1  498.80  5583.1  496.98  5703.1  498.33  5763.1  496.80
  5830.1  498.27  5907.3  501.54  6006.0  499.87  6077.1  501.26  6112.2  500.12
  6283.0  502.07  6332.3  501.39  6389.2  502.91  6495.5  502.13  6863.0  507.17
#Mann=6,-1,0
  4128.2    0.08       0  4320.4    0.05       0  4989.4    0.16       0
  4999.2    0.07       0  5006.6    0.16       0  5088.4    0.05       0
Bank Sta=4564.9,5830.1
Exp/Cntr=0.3,0.1

Type RM Length L Ch R = 1,128587,994,994,994
BEGIN DESCRIPTION:
Mapping XS 0ce99037
END DESCRIPTION:
XS GIS Cut Line= 4
      2928256.03      7071378.76      2926901.85      7071348.38
      2926524.28      7071344.88      2925809.05      7072193.60
#Sta/Elev= 30
  4125.3  506.56  4306.4  505.23  4485.3  499.31  4557.7  497.86  4584.4  497.81
  4683.4  497.60  4782.4  497.34  4866.5  498.25  4956.5  496.55  4986.5  494.93
  4992.8  491.66  4993.4  490.86  5000.2  491.66  5026.6  496.28  5106.6  497.63
  5266.6  496.28  5296.6  498.67  5486.7  496.01  5536.7  497.38  5756.7  496.19
  5831.4  497.86  5935.6  498.34  5949.1  500.74  5968.4  500.78  6055.3  499.23
  6190.5  500.87  6346.5  499.99  6574.1  502.97  6680.7  502.03  6967.3  506.65
#Mann=8,-1,0
  4125.3    0.08       0  4485.3    0.05       0  4584.4    0.08       0
  4683.4    0.05       0  4782.4    0.08       0  4992.8    0.07       0
  5000.2    0.08       0  5968.4    0.05       0
Bank Sta=4557.7,5831.4
Exp/Cntr=0.3,0.1

Type RM Length L Ch R = 1,127593,708,708,708
BEGIN DESCRIPTION:
CANEY CREEK 125.0
END DESCRIPTION:
XS GIS Cut Line= 3
      2927290.70      7070601.85      2926842.82      7070674.76
      2925473.04      7072174.76
#Sta/Elev= 30
  4474.1  507.33  4611.6  510.75  4692.6  509.36  4738.9  506.36  4823.3  498.69
  4840.4  495.45  4864.9  492.05  4976.1  493.19  5000.6  488.80  5001.2  488.00
  5008.2  488.80  5011.2  492.32  5018.6  493.38  5122.2  493.77  5195.6  491.82
  5230.8  493.85  5358.1  495.45  5528.0  497.69  5605.7  496.65  5768.6  499.66
  5811.3  498.91  5903.2  498.80  5941.1  501.48  5953.0  498.95  5967.2  498.88
  6023.9  499.08  6059.0  502.11  6122.6  499.69  6498.2  500.64  6959.2  507.47
#Mann=8,-1,0
  4474.1    0.05       0  4738.9    0.16       0  4823.3    0.12       0
  5000.6    0.07       0  5008.2    0.12       0  5122.2    0.05       0
  5811.3    0.08       0  5941.1    0.05       0
Bank Sta=4840.4,5358.1
Exp/Cntr=0.3,0.1

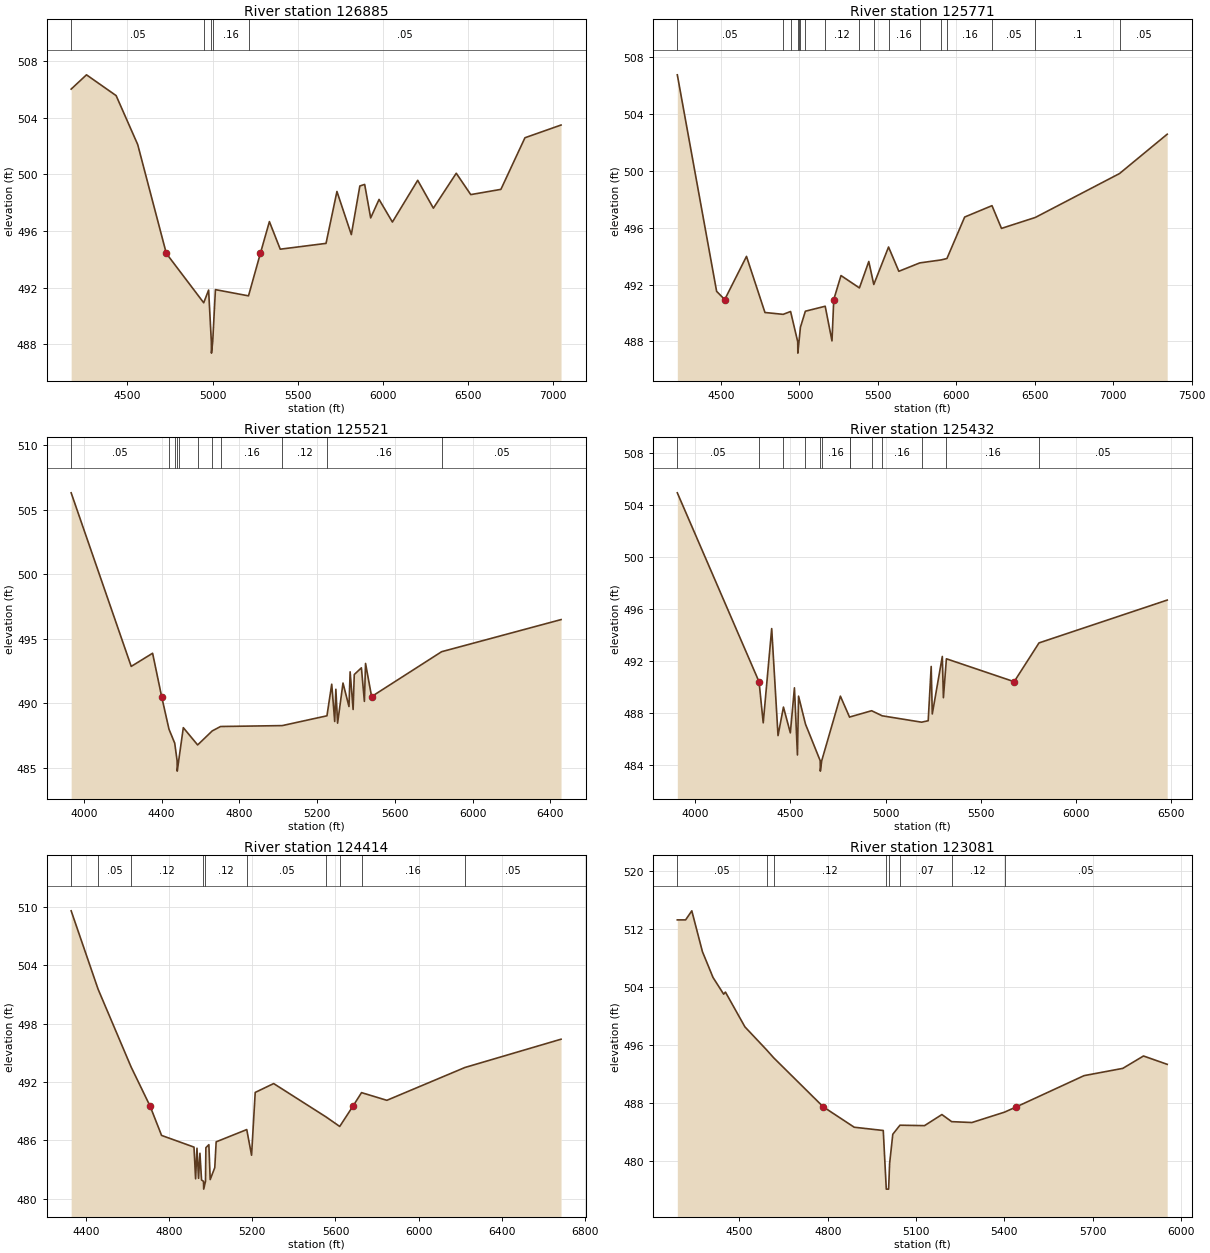
Type RM Length L Ch R = 1,126885,1114,1114,1114
BEGIN DESCRIPTION:
CANEY CREEK 124.0
END DESCRIPTION:
XS GIS Cut Line= 4
      2927275.11      7070528.93      2926613.66      7070304.97
      2926301.16      7070304.97      2924926.17      7071565.38
#Sta/Elev= 30
  4169.7  506.03  4259.7  507.04  4433.8  505.57  4560.4  502.11  4728.4  494.41
  4947.9  490.92  4976.7  491.82  4992.8  488.16  4993.4  487.36  5000.6  488.16
  5016.7  491.85  5210.9  491.41  5280.5  494.41  5333.6  496.66  5397.2  494.71
  5666.0  495.12  5730.1  498.79  5814.6  495.74  5864.6  499.18  5892.9  499.29
  5928.1  496.92  5977.4  498.23  6055.7  496.63  6204.3  499.58  6296.2  497.61
  6430.6  500.08  6515.7  498.57  6692.7  498.94  6833.9  502.59  7045.8  503.49
#Mann=5,-1,0
  4169.7    0.05       0  4947.9    0.16       0  4992.8    0.07       0
  5000.6    0.16       0  5210.9    0.05       0
Bank Sta=4728.4,5280.5
Exp/Cntr=0.3,0.1

Type RM Length L Ch R = 1,125771,250,250,250
BEGIN DESCRIPTION:
CANEY CREEK 123.0
END DESCRIPTION:
XS GIS Cut Line= 3
      2927125.02      7069525.00      2926325.00      7069575.00
      2924849.03      7071366.26
#Sta/Elev= 30
  4221.5  506.77  4472.0  491.53  4523.7  490.95  4662.4  493.99  4780.1  490.04
  4896.0  489.91  4943.5  490.11  4989.0  487.98  4989.7  487.18  4997.0  487.98
  5006.2  489.00  5037.6  490.13  5164.1  490.48  5207.4  488.04  5218.7  490.95
  5264.8  492.64  5382.3  491.77  5442.0  493.63  5473.8  492.01  5567.9  494.65
  5633.5  492.94  5766.5  493.53  5902.8  493.74  5940.1  493.84  6053.1  496.76
  6227.3  497.56  6287.7  495.96  6503.5  496.73  7040.1  499.82  7344.1  502.59
#Mann=17,-1,0
  4221.5    0.05       0  4896.0    0.16       0  4943.5    0.12       0
  4989.0    0.07       0  4997.0    0.12       0  5006.2    0.12       0
  5037.6    0.07       0  5164.1    0.12       0  5382.3    0.16       0
  5473.8    0.12       0  5567.9    0.16       0  5766.5    0.05       0
  5902.8     0.1       0  5940.1    0.16       0  6227.3    0.05       0
  6503.5     0.1       0  7040.1    0.05       0
Bank Sta=4523.7,5218.7
Exp/Cntr=0.3,0.1

Type RM Length L Ch R = 1,125521,89,89,89
BEGIN DESCRIPTION:
Mapping XS 988de5c1
END DESCRIPTION:
XS GIS Cut Line= 4
      2927129.24      7069406.51      2926676.16      7069166.95
      2925811.57      7069698.20      2924968.90      7070223.57
#Sta/Elev= 30
  3934.8  506.30  4243.8  492.84  4353.8  493.86  4400.3  490.50  4438.1  487.97
  4467.6  486.89  4479.9  485.52  4480.5  484.72  4487.9  485.52  4511.8  488.09
  4585.5  486.75  4660.7  487.84  4703.4  488.18  5020.8  488.25  5250.8  489.01
  5275.3  491.46  5290.7  488.57  5296.6  491.07  5305.5  488.44  5333.3  491.55
  5364.1  489.73  5370.0  492.42  5385.4  489.50  5391.3  492.21  5428.0  492.73
  5443.4  490.13  5449.3  493.07  5480.5  490.50  5840.7  493.98  6455.1  496.47
#Mann=11,-1,0
  3934.8    0.05       0  4438.1    0.16       0  4467.6    0.07       0
  4479.9    0.07       0  4487.9    0.07       0  4585.5    0.16       0
  4660.7    0.05       0  4703.4    0.16       0  5020.8    0.12       0
  5250.8    0.16       0  5840.7    0.05       0
Bank Sta=4400.3,5480.5
Exp/Cntr=0.3,0.1

Type RM Length L Ch R = 1,125432,1018,1018,1018
BEGIN DESCRIPTION:
Mapping XS 09df5849
END DESCRIPTION:
XS GIS Cut Line= 4
      2927160.52      7069312.78      2926691.78      7069083.62
      2925967.82      7069500.29      2924926.52      7070130.27
#Sta/Elev= 30
  3905.7  504.94  4335.0  490.43  4335.3  490.41  4357.1  487.27  4401.6  494.51
  4434.9  486.29  4463.4  488.48  4499.6  486.50  4521.1  489.96  4536.9  484.80
  4542.7  489.32  4579.2  487.17  4656.5  484.36  4657.2  483.56  4664.5  484.36
  4762.6  489.32  4810.9  487.70  4812.1  487.72  4926.7  488.20  4982.3  487.81
  5189.1  487.32  5223.9  487.43  5239.7  491.60  5245.4  487.95  5298.1  492.37
  5303.9  489.20  5319.6  492.19  5675.6  490.43  5806.2  493.41  6479.8  496.70
#Mann=13,-1,0
  3905.7    0.05       0  4335.3    0.16       0  4463.4    0.07       0
  4579.2    0.16       0  4656.5    0.07       0  4664.5    0.16       0
  4810.9    0.12       0  4812.1    0.16       0  4926.7    0.07       0
  4982.3    0.16       0  5189.1    0.12       0  5319.6    0.16       0
  5806.2    0.05       0
Bank Sta=4335,5675.6
Exp/Cntr=0.3,0.1

Type RM Length L Ch R = 1,124414,1333,1333,1333
BEGIN DESCRIPTION:
CANEY CREEK 122.0
END DESCRIPTION:
XS GIS Cut Line= 3
      2926488.68      7068315.36      2925915.74      7068992.47
      2924863.63      7070018.54
#Sta/Elev= 30
  4328.7  509.56  4458.3  501.52  4616.9  493.55  4708.7  489.51  4763.6  486.52
  4919.6  485.32  4927.3  482.07  4933.9  485.21  4941.6  482.12  4948.2  484.69
  4955.9  481.95  4965.3  481.81  4966.3  481.01  4974.9  481.81  4976.8  485.26
  4991.1  485.57  4997.6  481.99  5019.6  483.22  5026.2  485.86  5173.4  487.12
  5196.5  484.49  5214.1  490.93  5302.8  491.84  5554.6  488.42  5620.6  487.44
  5683.9  489.51  5725.6  490.91  5847.3  490.12  6223.1  493.49  6685.3  496.39
#Mann=10,-1,0
  4328.7    0.12       0  4458.3    0.05       0  4616.9    0.12       0
  4965.3    0.07       0  4974.9    0.12       0  5173.4    0.05       0
  5554.6    0.16       0  5620.6    0.05       0  5725.6    0.16       0
  6223.1    0.05       0
Bank Sta=4708.7,5683.9
Exp/Cntr=0.3,0.1

Type RM Length L Ch R = 1,123081,570,570,570
BEGIN DESCRIPTION:
CANEY CREEK 121.0
END DESCRIPTION:
XS GIS Cut Line= 3
      2925787.28      7067929.09      2925474.51      7068401.22
      2925063.32      7069419.71
#Sta/Elev= 30
  4288.9  513.31  4317.1  513.31  4338.1  514.56  4374.2  508.93  4410.3  505.36
  4446.4  503.06  4452.4  503.35  4518.6  498.55  4592.6  495.36  4616.4  494.28
  4784.9  487.51  4890.1  484.70  4988.7  484.25  4998.0  476.96  4999.0  476.16
  5006.8  476.16  5007.7  476.96  5010.3  479.68  5021.1  483.73  5045.5  484.98
  5128.9  484.92  5188.0  486.45  5221.2  485.47  5290.0  485.35  5400.7  486.78
  5441.0  487.51  5671.1  491.82  5802.6  492.82  5873.0  494.53  5953.6  493.38
#Mann=8,-1,0
  4288.9    0.05       0  4592.6    0.16       0  4616.4    0.12       0
  4998.0    0.07       0  5007.7    0.12       0  5045.5    0.07       0
  5221.2    0.12       0  5400.7    0.05       0
Bank Sta=4784.9,5441
Exp/Cntr=0.3,0.1

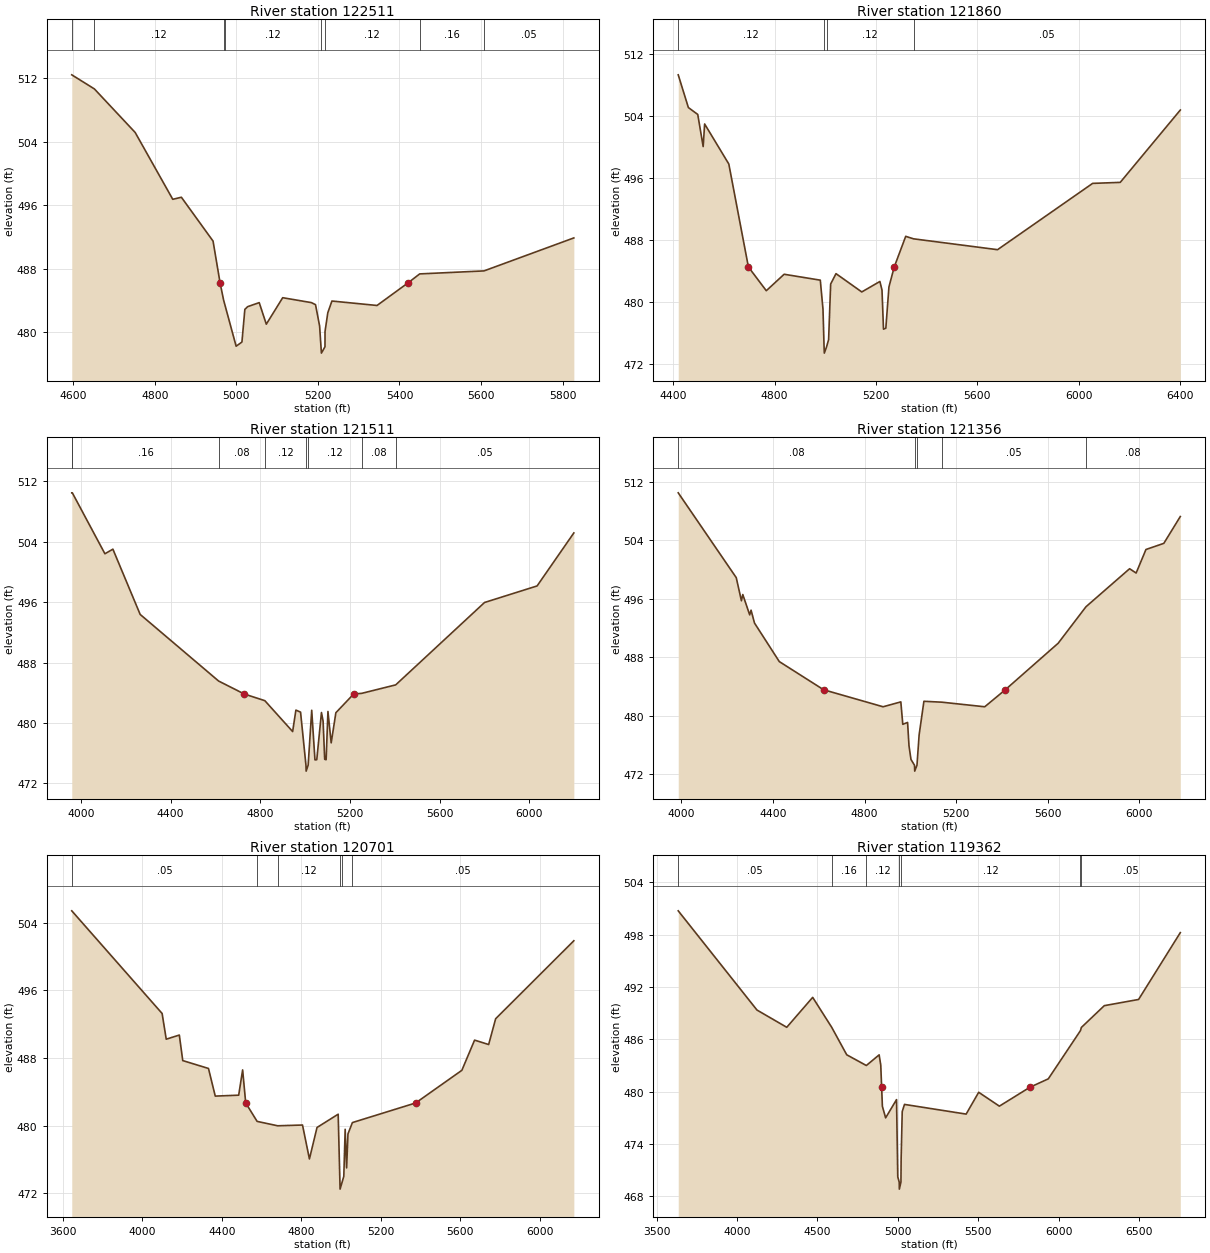
Type RM Length L Ch R = 1,122511,651,651,651
BEGIN DESCRIPTION:
CANEY CREEK 120.0
END DESCRIPTION:
XS GIS Cut Line= 3
      2925425.00      7067875.00      2925106.66      7068210.51
      2925025.00      7068974.96
#Sta/Elev= 30
  4596.3  512.44  4651.8  510.66  4751.8  505.17  4844.0  496.74  4865.1  497.00
  4942.8  491.47  4959.9  486.24  4968.6  484.04  4971.9  483.42  4999.4  478.21
  5013.6  478.74  5020.8  482.86  5027.7  483.20  5056.0  483.71  5073.4  480.99
  5113.6  484.33  5184.0  483.71  5194.1  483.45  5204.1  480.76  5207.5  478.14
  5208.5  477.34  5217.3  478.14  5217.4  480.06  5224.2  482.43  5234.3  483.91
  5344.9  483.35  5422.0  486.24  5449.5  487.33  5607.3  487.71  5827.6  491.87
#Mann=8,-1,0
  4596.3    0.05       0  4651.8    0.12       0  4968.6    0.07       0
  4971.9    0.12       0  5207.5    0.07       0  5217.3    0.12       0
  5449.5    0.16       0  5607.3    0.05       0
Bank Sta=4959.9,5422
Exp/Cntr=0.3,0.1

Type RM Length L Ch R = 1,121860,349,349,349
BEGIN DESCRIPTION:
CANEY CREEK 119.0
END DESCRIPTION:
XS GIS Cut Line= 3
      2925103.85      7067639.20      2924625.00      7067925.00
      2923429.31      7068697.71
#Sta/Elev= 30
  4419.8  509.33  4459.8  505.11  4496.8  504.22  4518.2  500.08  4524.0  502.99
  4619.4  497.83  4696.7  484.55  4767.3  481.49  4837.7  483.61  4980.4  482.85
  4991.0  479.12  4995.3  474.24  4996.3  473.44  5005.1  474.24  5013.2  475.18
  5021.3  482.35  5042.4  483.69  5144.1  481.33  5215.6  482.68  5223.9  481.57
  5229.8  476.53  5239.0  476.65  5251.3  481.98  5272.2  484.55  5317.5  488.50
  5348.3  488.18  5679.9  486.78  6055.1  495.33  6164.0  495.46  6401.1  504.79
#Mann=4,-1,0
  4419.8    0.12       0  4995.3    0.07       0  5005.1    0.12       0
  5348.3    0.05       0
Bank Sta=4696.7,5272.2
Exp/Cntr=0.3,0.1

Type RM Length L Ch R = 1,121511,155,155,155
BEGIN DESCRIPTION:
CANEY CREEK 118.0
END DESCRIPTION:
XS GIS Cut Line= 3
      2925179.45      7067133.51      2924502.33      7067617.91
      2923392.98      7068482.47
#Sta/Elev= 30
  3959.2  510.48  3961.7  510.48  4107.0  502.41  4142.6  503.02  4264.2  494.38
  4614.0  485.56  4728.6  483.84  4820.2  482.96  4944.2  478.87  4958.7  481.71
  4979.5  481.44  5003.5  474.43  5004.5  473.63  5013.4  474.43  5029.2  481.69
  5043.7  475.12  5051.8  475.14  5072.7  481.39  5080.0  480.25  5087.1  475.20
  5093.5  475.14  5101.6  481.53  5116.1  477.37  5136.9  481.36  5216.3  483.84
  5252.3  483.93  5403.8  485.05  5800.0  495.96  6034.3  498.15  6198.2  505.17
#Mann=8,-1,0
  3959.2    0.08       0  3961.7    0.16       0  4614.0    0.08       0
  4820.2    0.12       0  5003.5    0.07       0  5013.4    0.12       0
  5252.3    0.08       0  5403.8    0.05       0
Bank Sta=4728.6,5216.3
Exp/Cntr=0.3,0.1

Type RM Length L Ch R = 1,121356,655,655,655
BEGIN DESCRIPTION:
Mapping XS 2155fb03
END DESCRIPTION:
XS GIS Cut Line= 4
      2925096.10      7067044.97      2924570.04      7067393.95
      2923856.50      7067904.37      2923335.63      7068347.10
#Sta/Elev= 30
  3986.5  510.50  4239.8  498.90  4262.4  495.74  4268.4  496.59  4298.5  493.81
  4304.5  494.45  4319.5  492.69  4427.8  487.42  4621.2  483.57  4881.0  481.24
  4958.4  481.91  4967.0  478.84  4987.9  479.10  4994.1  475.90  5002.7  474.04
  5018.2  473.24  5019.0  472.44  5028.9  473.24  5038.3  477.40  5059.2  481.99
  5137.0  481.87  5324.8  481.24  5414.6  483.57  5645.4  489.93  5766.8  494.92
  5957.3  500.12  5985.8  499.53  6028.7  502.75  6106.7  503.59  6178.7  507.26
#Mann=5,-1,0
  3986.5    0.08       0  5018.2    0.07       0  5028.9    0.08       0
  5137.0    0.05       0  5766.8    0.08       0
Bank Sta=4621.2,5414.6
Exp/Cntr=0.3,0.1

Type RM Length L Ch R = 1,120701,1339,1339,1339
BEGIN DESCRIPTION:
CANEY CREEK 117.0
END DESCRIPTION:
XS GIS Cut Line= 3
      2925132.57      7066654.36      2923981.50      7066977.28
      2923070.06      7067946.00
#Sta/Elev= 30
  3645.5  505.41  4100.0  493.27  4120.7  490.23  4186.5  490.72  4203.8  487.70
  4333.2  486.77  4367.3  483.50  4485.2  483.61  4505.0  486.60  4520.5  482.69
  4577.9  480.51  4681.4  479.99  4806.2  480.08  4841.0  476.07  4879.2  479.79
  4985.6  481.36  4994.4  473.30  4995.2  472.50  5005.1  473.30  5013.9  474.01
  5020.8  479.58  5028.1  475.01  5034.9  479.03  5057.2  480.37  5375.4  482.69
  5607.8  486.55  5671.8  490.12  5742.6  489.60  5777.8  492.65  6171.1  501.87
#Mann=6,-1,0
  3645.5    0.05       0  4577.9    0.07       0  4681.4    0.12       0
  4994.4    0.07       0  5005.1    0.12       0  5057.2    0.05       0
Bank Sta=4520.5,5375.4
Exp/Cntr=0.3,0.1

Type RM Length L Ch R = 1,119362,670,670,670
BEGIN DESCRIPTION:
CANEY CREEK 116.0
END DESCRIPTION:
XS GIS Cut Line= 3
      2925054.42      7066419.99      2923769.11      7066261.58
      2922378.70      7067444.87
#Sta/Elev= 30
  3635.1  500.74  4124.4  489.37  4309.6  487.39  4470.8  490.82  4589.0  487.39
  4682.4  484.24  4804.3  483.01  4883.9  484.23  4894.0  483.05  4899.4  480.51
  4904.1  478.33  4924.2  477.01  4992.0  479.10  4999.7  470.24  5008.7  469.64
  5009.5  468.84  5019.4  469.64  5020.6  472.34  5027.4  477.73  5041.4  478.55
  5424.7  477.44  5502.7  479.94  5631.2  478.35  5820.4  480.51  5935.3  481.48
  6135.3  487.01  6140.8  487.37  6283.5  489.87  6496.5  490.58  6755.9  498.24
#Mann=7,-1,0
  3635.1    0.05       0  4589.0    0.16       0  4804.3    0.12       0
  5008.7    0.07       0  5019.4    0.12       0  6135.3    0.16       0
  6140.8    0.05       0
Bank Sta=4899.4,5820.4
Exp/Cntr=0.3,0.1

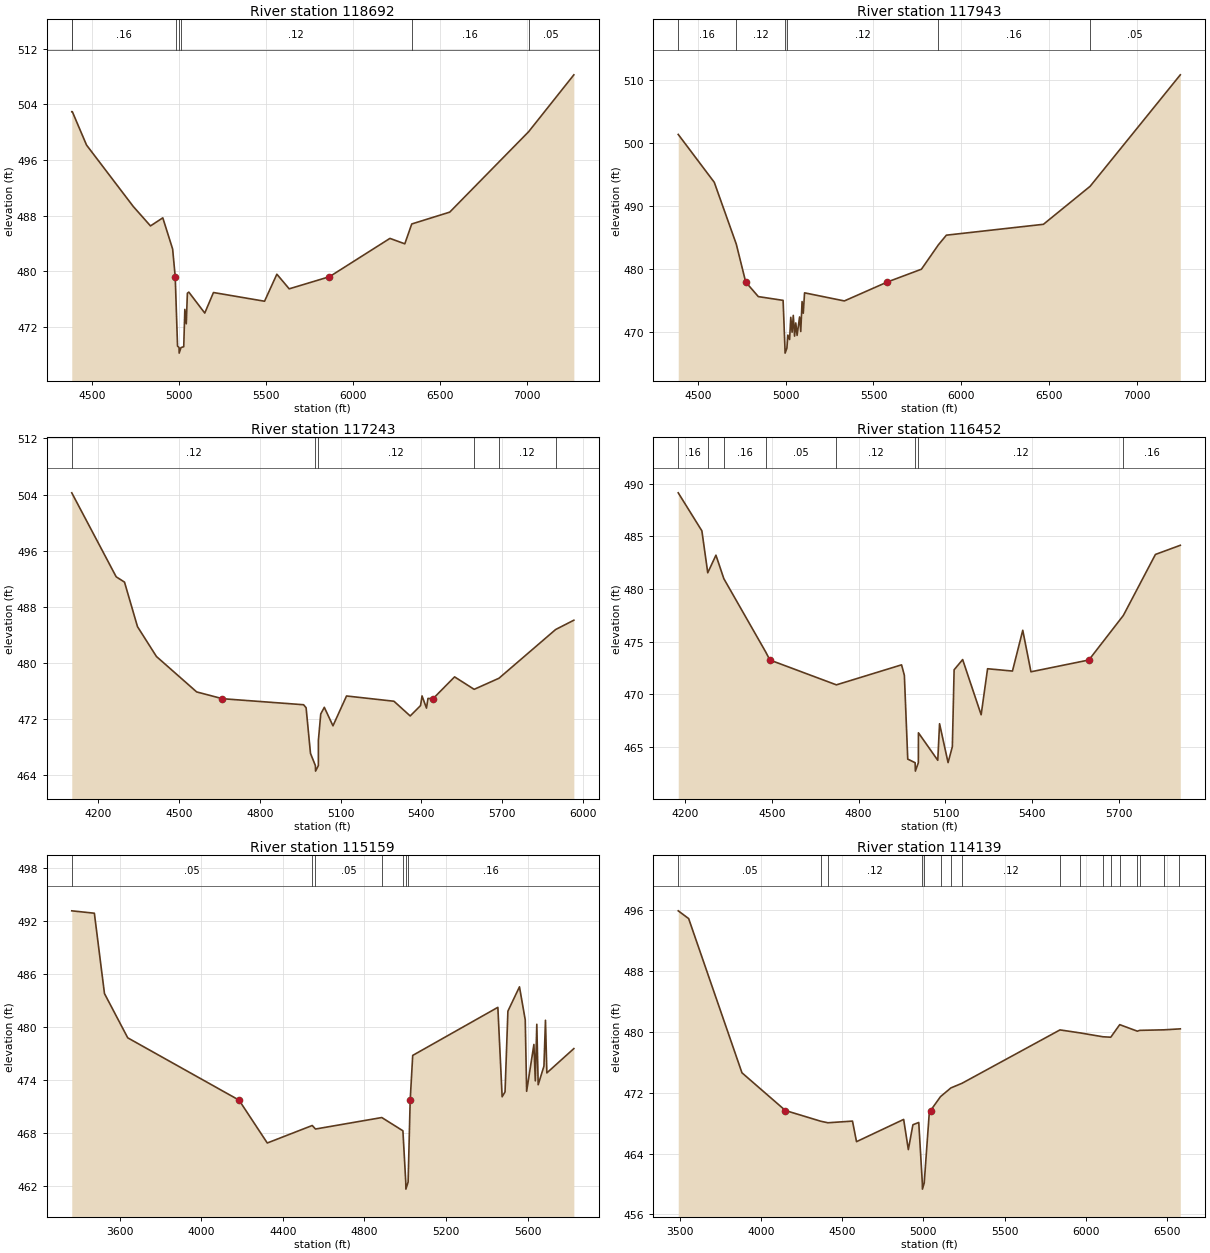
Type RM Length L Ch R = 1,118692,749,749,749
BEGIN DESCRIPTION:
CANEY CREEK 115.0
END DESCRIPTION:
XS GIS Cut Line= 3
      2923875.02      7065424.98      2923425.00      7065875.00
      2921625.02      7067224.98
#Sta/Elev= 30
  4381.3  502.94  4384.5  502.94  4466.2  498.15  4734.9  489.33  4833.9  486.54
  4904.6  487.70  4961.2  483.22  4976.0  479.25  4981.1  475.46  4989.4  469.29
  4998.1  469.08  4998.8  468.28  5009.1  469.08  5025.0  469.20  5031.3  474.56
  5039.6  472.49  5045.9  476.88  5054.2  477.04  5145.9  474.03  5195.9  476.98
  5489.6  475.73  5560.4  479.61  5631.3  477.51  5862.9  479.25  6210.4  484.75
  6295.9  483.97  6335.8  486.82  6554.2  488.52  7008.0  500.07  7267.7  508.23
#Mann=7,-1,0
  4381.3    0.12       0  4384.5    0.16       0  4981.1    0.12       0
  4998.1    0.07       0  5009.1    0.12       0  6335.8    0.16       0
  7008.0    0.05       0
Bank Sta=4976,5862.9
Exp/Cntr=0.3,0.1

Type RM Length L Ch R = 1,117943,700,700,700
BEGIN DESCRIPTION:
CANEY CREEK 114.0
END DESCRIPTION:
XS GIS Cut Line= 3
      2923574.99      7065125.00      2923025.00      7065425.00
      2921375.00      7066925.00
#Sta/Elev= 30
  4389.2  501.41  4594.2  493.79  4719.3  483.96  4773.1  477.91  4844.8  475.59
  4985.8  474.99  4996.4  467.39  4997.1  466.59  5007.5  467.39  5012.8  469.47
  5022.8  468.76  5029.5  472.29  5037.0  469.92  5043.7  472.60  5051.2  469.30
  5057.9  471.40  5065.4  469.41  5079.5  472.35  5086.3  470.03  5093.7  474.80
  5100.5  472.94  5107.9  476.19  5334.3  474.90  5578.4  477.91  5772.8  479.95
  5869.2  483.83  5914.7  485.37  6466.8  487.10  6732.5  493.15  7245.6  510.90
#Mann=6,-1,0
  4389.2    0.16       0  4719.3    0.12       0  4996.4    0.07       0
  5007.5    0.12       0  5869.2    0.16       0  6732.5    0.05       0
Bank Sta=4773.1,5578.4
Exp/Cntr=0.3,0.1

Type RM Length L Ch R = 1,117243,791,791,791
BEGIN DESCRIPTION:
CANEY CREEK 113.0
END DESCRIPTION:
XS GIS Cut Line= 3
      2923525.00      7064625.00      2922675.00      7064925.00
      2922224.98      7065775.04
#Sta/Elev= 30
  4102.4  504.24  4267.2  492.25  4298.1  491.49  4346.3  485.13  4416.6  480.87
  4565.9  475.81  4661.7  474.84  4962.7  473.98  4972.0  473.55  4988.3  467.03
  5006.4  465.30  5007.2  464.50  5017.5  465.30  5017.6  468.88  5026.4  472.67
  5039.6  473.61  5071.7  470.97  5122.0  475.23  5298.0  474.48  5358.3  472.38
  5396.7  473.86  5402.3  475.24  5418.7  473.50  5424.3  474.88  5443.0  474.84
  5523.0  477.96  5595.7  476.18  5687.6  477.76  5898.0  484.72  5965.6  486.05
#Mann=6,-1,0
  4102.4    0.12       0  5006.4    0.07       0  5017.5    0.12       0
  5595.7    0.16       0  5687.6    0.12       0  5898.0    0.16       0
Bank Sta=4661.7,5443
Exp/Cntr=0.3,0.1

Type RM Length L Ch R = 1,116452,1293,1293,1293
BEGIN DESCRIPTION:
CANEY CREEK 112.0
END DESCRIPTION:
XS GIS Cut Line= 3
      2922775.02      7063674.96      2922325.00      7064425.00
      2921825.01      7065124.98
#Sta/Elev= 30
  4176.7  489.12  4258.4  485.51  4278.7  481.53  4307.0  483.20  4334.3  480.97
  4479.0  474.01  4493.4  473.25  4723.2  470.89  4948.4  472.79  4958.1  471.79
  4969.8  463.84  4995.3  463.50  4996.1  462.70  5006.4  463.50  5006.7  466.34
  5073.5  463.73  5079.7  467.20  5109.1  463.51  5123.9  465.02  5130.0  472.32
  5159.5  473.29  5223.4  468.05  5245.6  472.42  5331.6  472.20  5367.2  476.07
  5395.5  472.13  5595.6  473.25  5714.8  477.48  5825.6  483.27  5911.6  484.14
#Mann=8,-1,0
  4176.7    0.16       0  4278.7    0.12       0  4334.3    0.16       0
  4479.0    0.05       0  4723.2    0.12       0  4995.3    0.07       0
  5006.4    0.12       0  5714.8    0.16       0
Bank Sta=4493.4,5595.6
Exp/Cntr=0.3,0.1

Type RM Length L Ch R = 1,115159,1020,1020,1020
BEGIN DESCRIPTION:
CANEY CREEK 111.0
END DESCRIPTION:
XS GIS Cut Line= 3
      2922929.67      7063281.40      2921746.98      7063606.91
      2920846.33      7064453.30
#Sta/Elev= 30
  3364.5  493.15  3475.3  492.88  3524.9  483.79  3639.0  478.78  4184.9  471.73
  4323.5  466.88  4544.0  468.86  4559.9  468.46  4885.1  469.76  4988.7  468.26
  5002.7  462.46  5003.3  461.66  5014.2  462.46  5024.4  471.73  5036.8  476.79
  5454.4  482.23  5475.4  472.11  5489.6  472.66  5503.7  481.80  5560.4  484.55
  5588.7  480.81  5595.6  472.73  5631.2  478.03  5638.1  473.91  5645.4  480.31
  5652.2  473.47  5680.5  475.58  5687.9  480.77  5694.7  474.81  5827.1  477.56
#Mann=7,-1,0
  3364.5    0.05       0  4544.0    0.16       0  4559.9    0.05       0
  4885.1    0.12       0  4988.7    0.16       0  5002.7    0.07       0
  5014.2    0.16       0
Bank Sta=4184.9,5024.4
Exp/Cntr=0.3,0.1

Type RM Length L Ch R = 1,114139,534,534,534
BEGIN DESCRIPTION:
CANEY CREEK 110.0
END DESCRIPTION:
XS GIS Cut Line= 3
      2922615.07      7062500.12      2921356.35      7062977.57
      2920271.27      7064344.78
#Sta/Elev= 30
  3490.8  495.86  3555.0  494.84  3883.2  474.60  4150.7  469.65  4367.2  468.25
  4412.2  468.04  4563.8  468.26  4588.6  465.56  4878.9  468.48  4907.8  464.52
  4935.9  467.78  4971.9  468.08  4993.9  460.13  4994.5  459.33  5005.5  460.13
  5036.0  469.15  5044.8  469.65  5105.8  471.47  5169.4  472.61  5238.9  473.23
  5841.6  480.23  5964.2  479.84  6105.3  479.33  6154.2  479.27  6209.4  480.92
  6318.3  480.06  6332.1  480.17  6482.4  480.24  6577.3  480.36  6582.5  480.37
#Mann=17,-1,0
  3490.8    0.05       0  4367.2    0.16       0  4412.2    0.12       0
  4993.9    0.07       0  5005.5    0.12       0  5105.8    0.08       0
  5169.4    0.05       0  5238.9    0.12       0  5841.6    0.08       0
  5964.2    0.05       0  6105.3    0.16       0  6154.2    0.08       0
  6209.4    0.16       0  6318.3    0.08       0  6332.1    0.16       0
  6482.4    0.05       0  6577.3    0.16       0
Bank Sta=4150.7,5044.8
Exp/Cntr=0.3,0.1