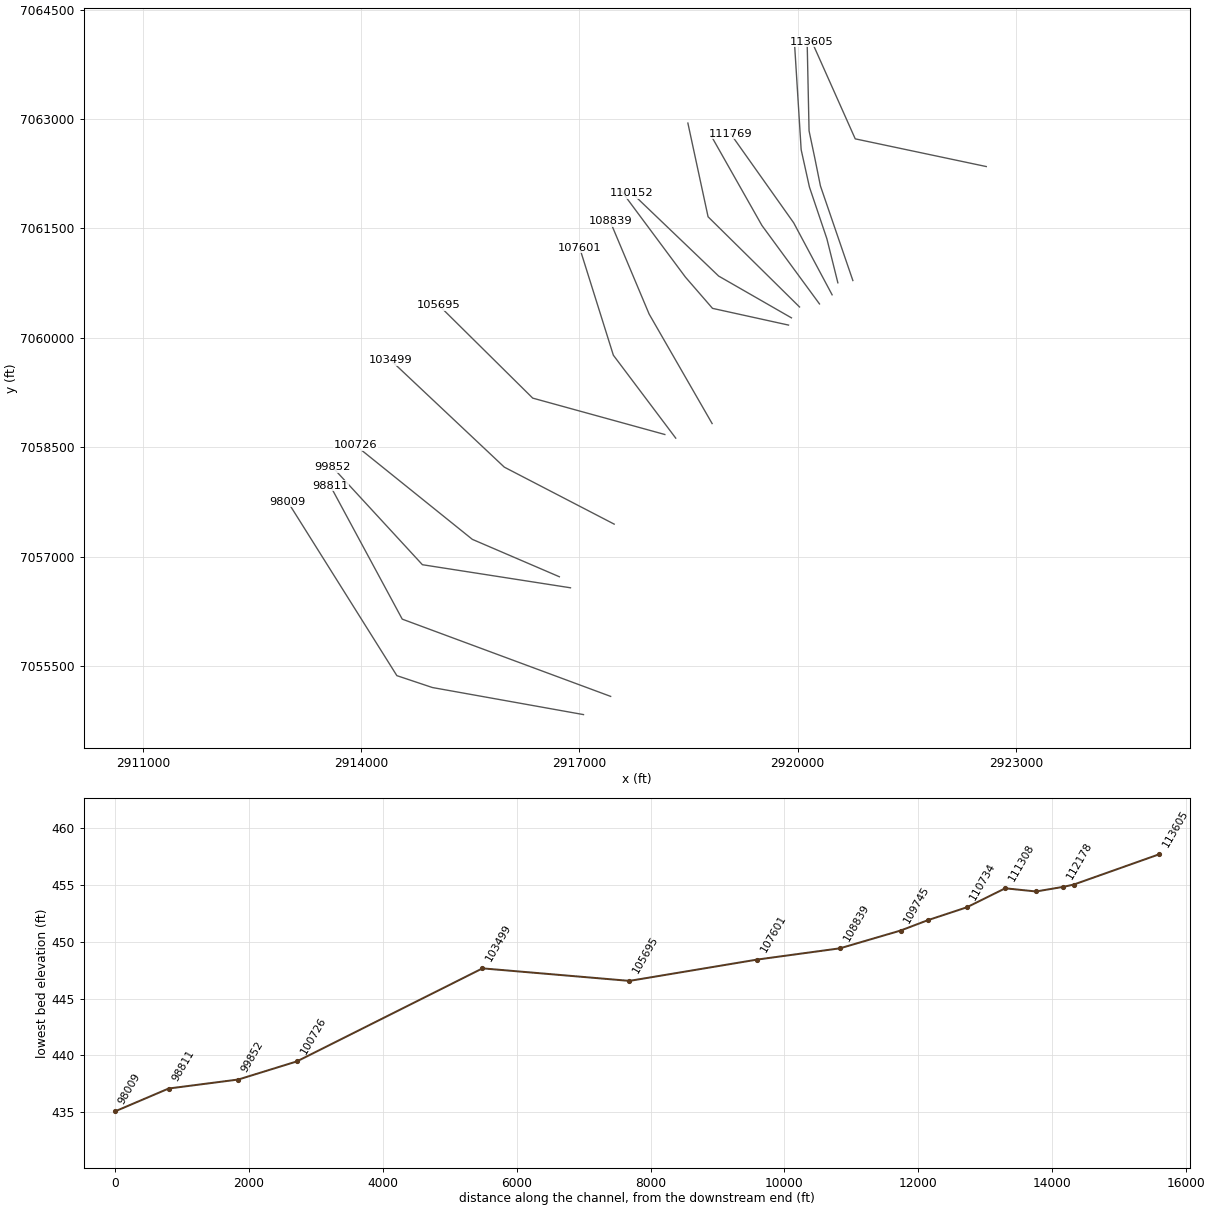
HEC-RAS study CANEY CREEK.prj: CANEY CREEK Base Level Engineering

--- CANEY CREEK.g01 (geometry) --- (continued)

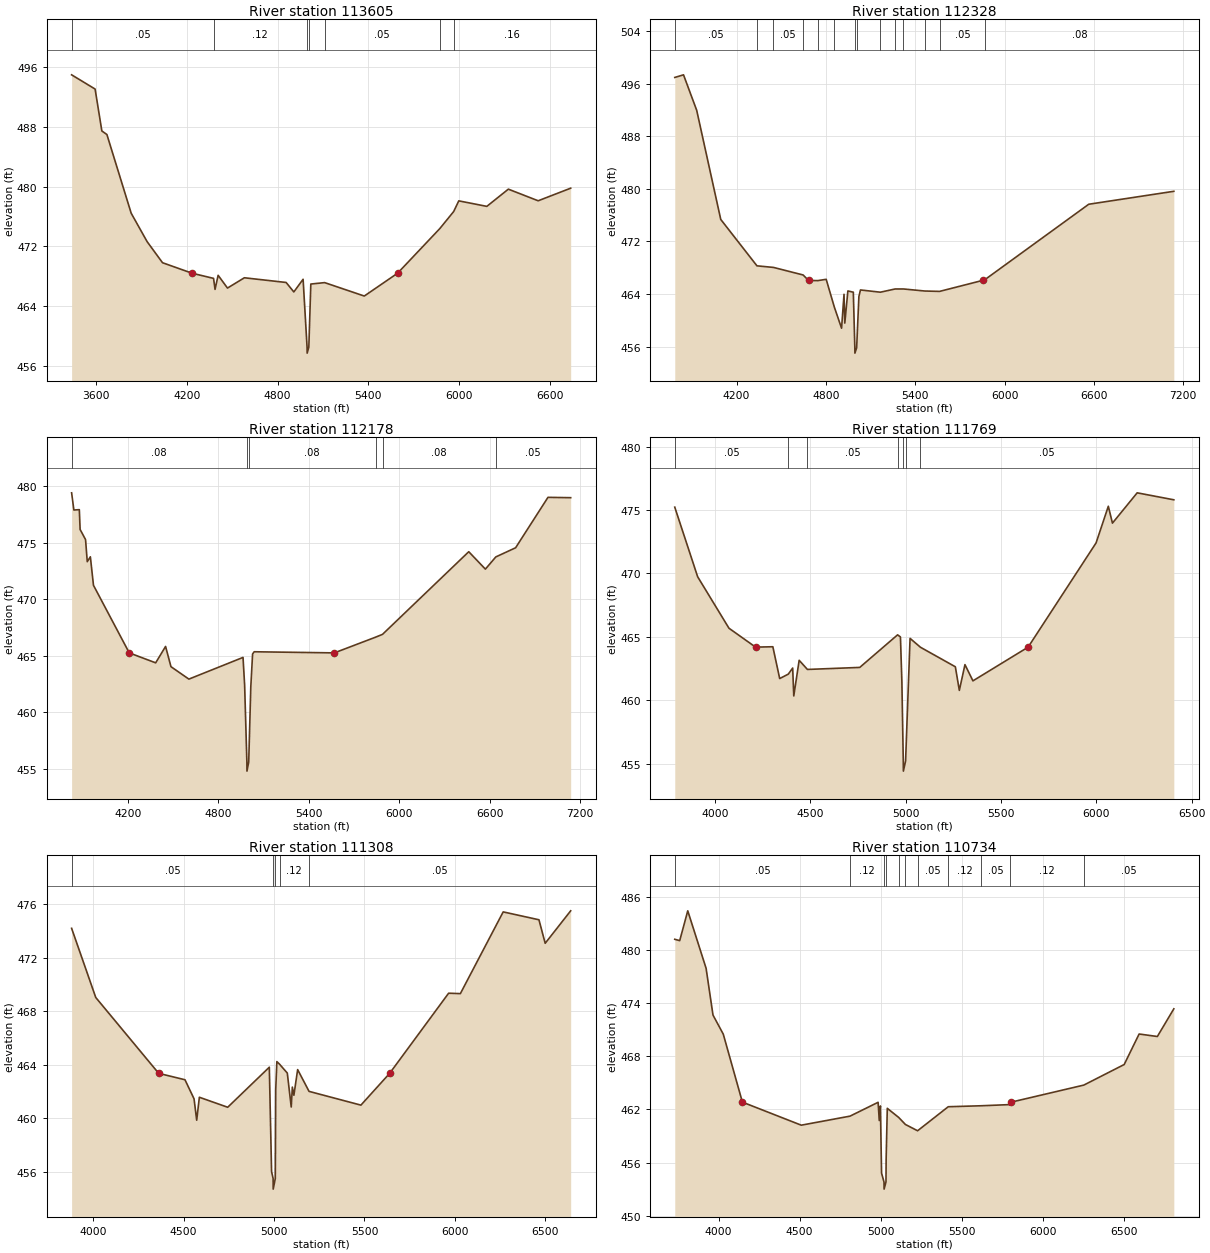
Type RM Length L Ch R = 1,113605,1277,1277,1277
BEGIN DESCRIPTION:
CANEY CREEK 109.0
END DESCRIPTION:
XS GIS Cut Line= 3
      2922593.34      7062348.23      2920792.11      7062728.01
      2920195.90      7064061.35
#Sta/Elev= 30
  3437.2  495.00  3592.6  493.09  3637.2  487.47  3670.6  486.99  3831.3  476.43
  3936.3  472.63  4038.5  469.79  4234.2  468.38  4376.1  467.69  4386.0  466.21
  4406.4  468.10  4468.3  466.39  4580.1  467.77  4856.3  467.14  4907.2  465.87
  4968.5  467.57  4994.8  458.46  4995.4  457.66  5006.4  458.46  5019.6  466.93
  5111.1  467.12  5373.3  465.32  5593.5  468.38  5872.9  474.37  5964.7  476.66
  5998.4  478.09  6183.9  477.35  6326.3  479.66  6523.5  478.10  6738.6  479.79
#Mann=7,-1,0
  3437.2    0.05       0  4376.1    0.12       0  4994.8    0.07       0
  5006.4    0.12       0  5111.1    0.05       0  5872.9    0.12       0
  5964.7    0.16       0
Bank Sta=4234.2,5593.5
Exp/Cntr=0.3,0.1

Type RM Length L Ch R = 1,112328,150,150,150
BEGIN DESCRIPTION:
CANEY CREEK 108.0
END DESCRIPTION:
XS GIS Cut Line= 5
      2920759.57      7060785.70      2920313.82      7062082.61
      2920235.69      7062468.02      2920157.57      7062837.81
      2920131.52      7064046.15
#Sta/Elev= 30
  3785.2  496.94  3844.0  497.34  3932.5  491.94  4094.0  475.34  4337.1  468.28
  4447.8  468.04  4647.1  466.89  4683.3  466.06  4745.0  466.03  4802.0  466.23
  4857.2  461.97  4905.3  458.79  4921.7  463.95  4927.0  459.57  4947.6  464.46
  4984.2  464.27  4994.4  455.80  4994.9  455.00  5006.5  455.80  5021.6  463.61
  5032.2  464.61  5165.8  464.27  5265.1  464.76  5321.0  464.76  5463.8  464.45
  5563.2  464.39  5852.1  466.06  5869.1  466.20  6565.1  477.65  7136.4  479.62
#Mann=14,-1,0
  3785.2    0.05       0  4337.1    0.08       0  4447.8    0.05       0
  4647.1    0.08       0  4745.0    0.05       0  4857.2    0.12       0
  4994.4    0.07       0  5006.5    0.12       0  5165.8    0.05       0
  5265.1    0.12       0  5321.0    0.08       0  5463.8    0.12       0
  5563.2    0.05       0  5869.1    0.08       0
Bank Sta=4683.3,5852.1
Exp/Cntr=0.3,0.1

Type RM Length L Ch R = 1,112178,409,409,409
BEGIN DESCRIPTION:
CANEY CREEK 107.0
END DESCRIPTION:
XS GIS Cut Line= 5
      2920553.41      7060754.44      2920402.36      7061358.65
      2920162.77      7062066.98      2920049.06      7062577.83
      2919960.52      7063989.25
#Sta/Elev= 30
  3828.4  479.43  3843.4  477.91  3879.5  477.94  3884.7  476.19  3920.8  475.29
  3932.1  473.34  3952.7  473.77  3973.3  471.25  4210.5  465.27  4385.6  464.39
  4451.2  465.84  4487.0  464.05  4605.7  462.95  4964.6  464.87  4975.2  462.44
  4990.2  455.61  4990.7  454.81  5002.3  455.61  5016.2  462.29  5028.0  465.17
  5038.5  465.37  5569.9  465.27  5843.2  466.66  5889.3  466.91  6460.9  474.22
  6571.1  472.68  6640.3  473.76  6771.5  474.57  6986.0  479.03  7136.5  479.00
#Mann=6,-1,0
  3828.4    0.08       0  4990.2    0.07       0  5002.3    0.08       0
  5843.2    0.05       0  5889.3    0.08       0  6640.3    0.05       0
Bank Sta=4210.5,5569.9
Exp/Cntr=0.3,0.1

Type RM Length L Ch R = 1,111769,461,461,461
BEGIN DESCRIPTION:
Mapping XS 2af1689c
END DESCRIPTION:
XS GIS Cut Line= 3
      2920474.41      7060589.98      2919946.63      7061576.10
      2919079.26      7062797.35
#Sta/Elev= 30
  3790.2  475.22  3910.2  469.73  4074.4  465.67  4213.9  464.18  4304.4  464.21
  4340.3  461.70  4385.4  462.05  4408.4  462.53  4414.1  460.33  4442.4  463.14
  4485.7  462.42  4760.0  462.58  4958.5  465.15  4973.4  464.98  4980.9  461.44
  4988.2  455.20  4988.7  454.40  5000.3  455.20  5023.8  464.87  5078.3  464.17
  5261.2  462.63  5282.1  460.77  5311.6  462.80  5353.4  461.52  5642.8  464.18
  5999.0  472.40  6063.2  475.29  6084.8  473.96  6214.5  476.35  6406.6  475.80
#Mann=7,-1,0
  3790.2    0.05       0  4385.4    0.07       0  4485.7    0.05       0
  4958.5    0.16       0  4988.2    0.07       0  5000.3    0.16       0
  5078.3    0.05       0
Bank Sta=4213.9,5642.8
Exp/Cntr=0.3,0.1

Type RM Length L Ch R = 1,111308,574,574,574
BEGIN DESCRIPTION:
Mapping XS 33b8ae00
END DESCRIPTION:
XS GIS Cut Line= 3
      2920300.79      7060464.99      2919509.13      7061541.37
      2918807.74      7062777.49
#Sta/Elev= 30
  3881.8  474.21  4015.2  469.03  4363.0  463.35  4508.2  462.87  4558.3  461.44
  4572.9  459.84  4587.6  461.56  4744.2  460.81  4974.1  463.81  4986.6  455.99
  4995.1  455.48  4995.6  454.68  5007.2  455.48  5009.6  462.12  5015.8  464.23
  5031.0  464.03  5073.5  463.37  5095.2  460.83  5101.4  462.32  5109.9  461.71
  5130.7  463.63  5193.7  462.00  5480.2  460.97  5639.0  463.35  5964.8  469.35
  6029.7  469.32  6266.3  475.44  6463.9  474.85  6498.4  473.09  6639.2  475.52
#Mann=5,-1,0
  3881.8    0.05       0  4995.1    0.03       0  5007.2    0.05       0
  5031.0    0.12       0  5193.7    0.05       0
Bank Sta=4363,5639
Exp/Cntr=0.3,0.1

Type RM Length L Ch R = 1,110734,582,582,582
BEGIN DESCRIPTION:
CANEY CREEK 105.0
END DESCRIPTION:
XS GIS Cut Line= 3
      2920026.52      7060423.29      2918769.54      7061659.43
      2918491.76      7062944.18
#Sta/Elev= 30
  3730.1  481.18  3760.6  481.03  3810.2  484.39  3923.3  477.91  3965.8  472.64
  4029.3  470.48  4147.1  462.82  4510.2  460.22  4810.9  461.24  4984.0  462.80
  4991.1  460.75  4998.1  462.39  5005.3  454.81  5020.4  453.81  5020.9  453.01
  5032.5  453.81  5033.5  456.39  5040.6  462.12  5111.0  461.09  5152.4  460.30
  5227.5  459.59  5416.4  462.30  5621.0  462.41  5795.0  462.54  5805.2  462.82
  6252.4  464.74  6501.4  467.06  6593.5  470.50  6706.0  470.22  6807.5  473.34
#Mann=11,-1,0
  3730.1    0.05       0  4810.9    0.12       0  5020.4    0.07       0
  5032.5    0.12       0  5111.0    0.05       0  5152.4    0.07       0
  5227.5    0.05       0  5416.4    0.12       0  5621.0    0.05       0
  5795.0    0.12       0  6252.4    0.05       0
Bank Sta=4147.1,5805.2
Exp/Cntr=0.3,0.1

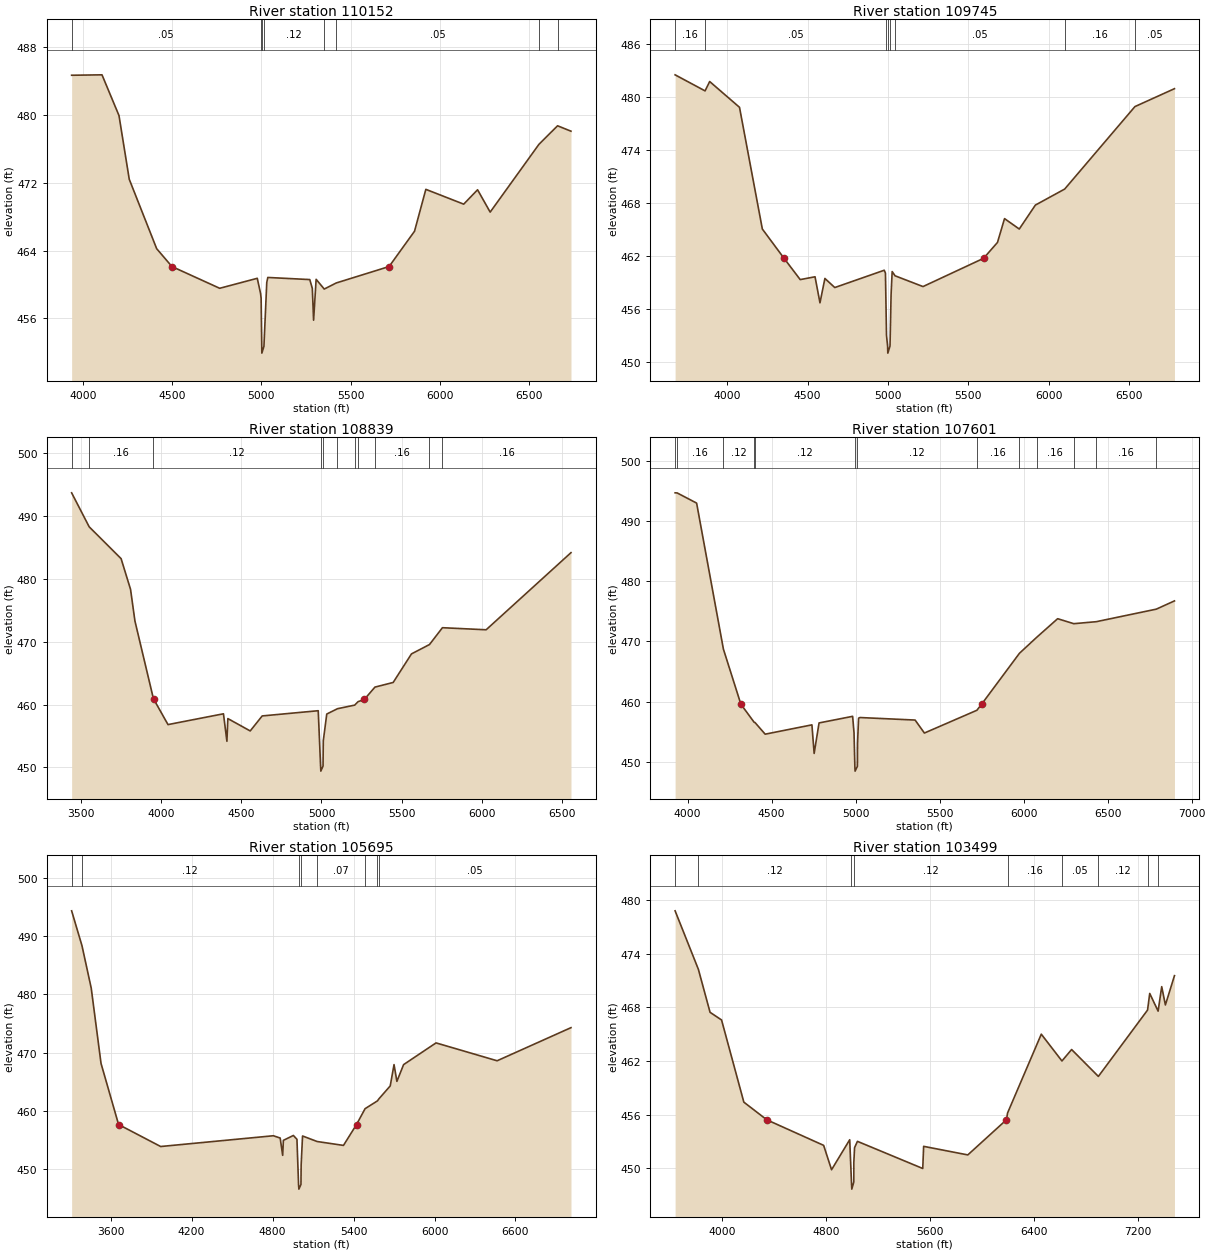
Type RM Length L Ch R = 1,110152,407,407,407
BEGIN DESCRIPTION:
Mapping XS 2be57d99
END DESCRIPTION:
XS GIS Cut Line= 3
      2919915.42      7060273.99      2918914.67      7060847.00
      2917723.56      7061984.06
#Sta/Elev= 30
  3936.2  484.71  4106.5  484.76  4201.7  479.95  4259.3  472.42  4413.0  464.22
  4498.5  462.11  4766.4  459.54  4977.1  460.72  4995.6  458.93  4998.7  458.35
  5002.3  452.68  5002.8  451.88  5014.4  452.68  5030.3  460.22  5036.1  460.82
  5271.5  460.57  5285.7  459.53  5292.9  455.77  5307.1  460.60  5352.6  459.45
  5420.0  460.17  5716.2  462.11  5858.8  466.28  5922.3  471.23  6134.6  469.48
  6212.3  471.18  6283.0  468.54  6556.5  476.55  6660.9  478.74  6736.1  478.10
#Mann=8,-1,0
  3936.2    0.05       0  4995.6    0.12       0  5002.3    0.07       0
  5014.4    0.12       0  5352.6    0.07       0  5420.0    0.05       0
  6556.5    0.16       0  6660.9    0.05       0
Bank Sta=4498.5,5716.2
Exp/Cntr=0.3,0.1

Type RM Length L Ch R = 1,109745,906,906,906
BEGIN DESCRIPTION:
CANEY CREEK 104.0
END DESCRIPTION:
XS GIS Cut Line= 4
      2919875.04      7060174.99      2918830.31      7060404.22
      2918457.82      7060832.74      2917580.36      7062010.05
#Sta/Elev= 30
  3676.2  482.50  3862.5  480.68  3891.3  481.74  4076.7  478.82  4218.8  465.03
  4353.9  461.71  4454.3  459.30  4546.5  459.62  4577.2  456.67  4607.9  459.43
  4669.3  458.40  4976.8  460.36  4984.4  460.04  4986.8  457.47  4991.0  452.97
  4997.8  451.77  4999.1  450.97  5012.8  451.77  5019.5  457.64  5026.2  460.21
  5044.3  459.73  5218.0  458.51  5594.6  461.71  5681.2  463.51  5725.0  466.21
  5816.7  465.03  5916.8  467.74  6099.3  469.56  6536.0  478.90  6781.9  480.93
#Mann=8,-1,0
  3676.2    0.16       0  3862.5    0.05       0  4986.8    0.12       0
  4997.8    0.07       0  5012.8    0.12       0  5044.3    0.05       0
  6099.3    0.16       0  6536.0    0.05       0
Bank Sta=4353.9,5594.6
Exp/Cntr=0.3,0.1

Type RM Length L Ch R = 1,108839,1238,1238,1238
BEGIN DESCRIPTION:
CANEY CREEK 103.0
END DESCRIPTION:
XS GIS Cut Line= 3
      2918825.00      7058824.99      2917959.26      7060325.88
      2917424.06      7061595.62
#Sta/Elev= 30
  3443.7  493.73  3553.2  488.31  3751.8  483.25  3810.7  478.36  3838.0  473.32
  3951.9  461.08  3956.0  460.82  4044.0  456.82  4389.5  458.54  4411.0  454.16
  4416.8  457.78  4556.1  455.81  4630.8  458.20  4979.8  459.03  4994.6  450.21
  4996.0  449.41  5009.7  450.21  5011.4  454.25  5032.9  458.50  5099.8  459.35
  5206.8  459.92  5228.0  460.47  5266.8  460.82  5333.1  462.79  5446.7  463.53
  5560.7  468.08  5672.9  469.57  5753.6  472.25  6025.7  471.92  6554.3  484.20
#Mann=11,-1,0
  3443.7    0.05       0  3553.2    0.16       0  3951.9    0.12       0
  4994.6    0.07       0  5009.7    0.12       0  5099.8    0.05       0
  5206.8    0.08       0  5228.0    0.05       0  5333.1    0.16       0
  5672.9    0.12       0  5753.6    0.16       0
Bank Sta=3956,5266.8
Exp/Cntr=0.3,0.1

Type RM Length L Ch R = 1,107601,1906,1906,1906
BEGIN DESCRIPTION:
CANEY CREEK 102.0
END DESCRIPTION:
XS GIS Cut Line= 3
      2918324.97      7058625.03      2917467.46      7059761.86
      2917002.88      7061238.01
#Sta/Elev= 30
  3926.2  494.74  3938.6  494.72  4054.2  493.03  4213.7  468.72  4317.4  459.57
  4396.6  456.55  4401.6  456.51  4462.2  454.57  4740.3  456.12  4753.6  451.37
  4782.8  456.44  4982.6  457.54  4990.9  454.79  4995.9  449.22  4997.2  448.42
  5011.0  449.22  5011.7  452.96  5018.0  457.23  5026.3  457.34  5354.4  456.92
  5409.7  454.76  5722.1  458.55  5750.5  459.57  5975.2  468.03  6077.0  470.67
  6202.6  473.79  6298.4  472.96  6432.0  473.29  6789.7  475.38  6897.7  476.75
#Mann=13,-1,0
  3926.2    0.05       0  3938.6    0.16       0  4213.7    0.12       0
  4396.6    0.16       0  4401.6    0.12       0  4995.9    0.07       0
  5011.0    0.12       0  5722.1    0.16       0  5975.2    0.05       0
  6077.0    0.16       0  6298.4    0.12       0  6432.0    0.16       0
  6789.7    0.12       0
Bank Sta=4317.4,5750.5
Exp/Cntr=0.3,0.1

Type RM Length L Ch R = 1,105695,2196,2196,2196
BEGIN DESCRIPTION:
CANEY CREEK 101.0
END DESCRIPTION:
XS GIS Cut Line= 3
      2918175.01      7058675.00      2916358.95      7059173.75
      2915065.56      7060449.78
#Sta/Elev= 30
  3311.1  494.36  3387.9  488.36  3456.3  481.08  3528.9  468.15  3659.0  457.65
  3970.8  453.87  4806.1  455.72  4856.3  455.33  4875.0  452.35  4880.2  454.93
  4954.2  455.77  4980.7  455.11  4992.6  447.35  4995.0  446.55  5010.4  447.35
  5011.8  450.70  5022.2  455.68  5130.0  454.73  5325.4  454.06  5422.2  457.65
  5485.5  460.37  5577.2  461.71  5587.3  462.04  5671.9  464.28  5700.1  467.94
  5721.3  465.06  5770.9  467.94  6011.3  471.67  6463.9  468.60  7011.3  474.29
#Mann=8,-1,0
  3311.1    0.16       0  3387.9    0.12       0  4992.6    0.07       0
  5010.4    0.12       0  5130.0    0.07       0  5485.5    0.12       0
  5577.2    0.07       0  5587.3    0.05       0
Bank Sta=3659,5422.2
Exp/Cntr=0.3,0.1

Type RM Length L Ch R = 1,103499,2773,2773,2773
BEGIN DESCRIPTION:
CANEY CREEK 100.0
END DESCRIPTION:
XS GIS Cut Line= 3
      2917478.76      7057446.32      2915968.33      7058227.57
      2914405.81      7059694.61
#Sta/Elev= 30
  3638.1  478.81  3817.5  472.25  3907.1  467.45  3995.7  466.59  4167.2  457.39
  4344.2  455.41  4781.5  452.55  4842.3  449.82  4982.1  453.18  4995.6  448.45
  4998.1  447.65  5013.7  448.45  5013.8  450.63  5019.5  452.29  5041.6  453.00
  5544.4  449.96  5551.2  452.44  5891.2  451.48  6188.2  455.41  6197.4  456.18
  6456.8  465.00  6615.9  462.00  6690.3  463.28  6896.2  460.27  7274.9  467.70
  7291.5  469.56  7356.1  467.58  7383.8  470.32  7412.1  468.27  7481.9  471.55
#Mann=9,-1,0
  3638.1    0.16       0  3817.5    0.12       0  4995.6    0.07       0
  5013.7    0.12       0  6197.4    0.16       0  6615.9    0.05       0
  6896.2    0.12       0  7274.9    0.16       0  7356.1    0.12       0
Bank Sta=4344.2,6188.2
Exp/Cntr=0.3,0.1

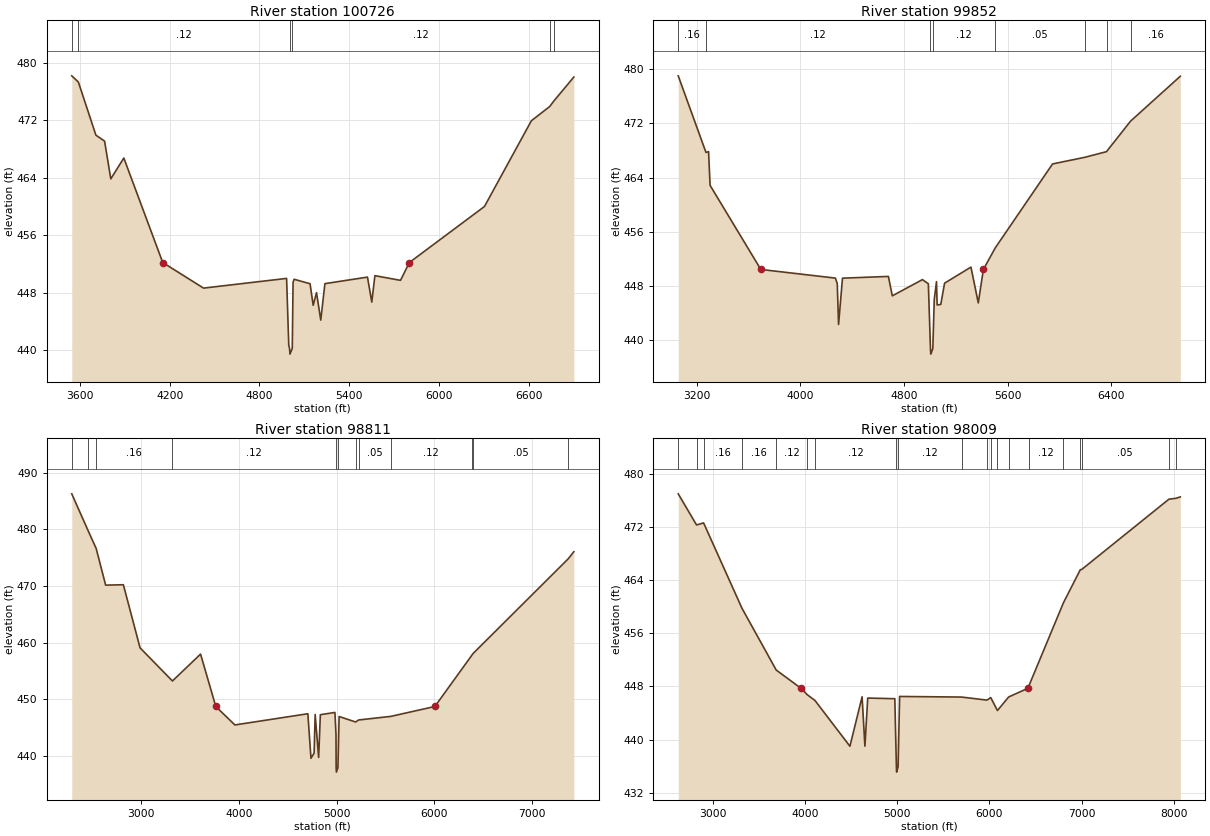
Type RM Length L Ch R = 1,100726,874,874,874
BEGIN DESCRIPTION:
CANEY CREEK 99.0
END DESCRIPTION:
XS GIS Cut Line= 3
      2916725.02      7056724.99      2915529.08      7057237.54
      2913924.99      7058525.00
#Sta/Elev= 30
  3544.5  478.18  3588.6  477.32  3705.9  469.93  3763.9  469.10  3805.6  463.85
  3892.7  466.75  4152.9  452.22  4425.8  448.66  4981.4  450.01  4995.8  440.72
  5001.2  440.28  5003.7  439.48  5019.3  440.28  5024.6  449.45  5031.1  449.89
  5138.3  449.27  5159.1  446.28  5181.5  448.03  5209.9  444.21  5237.5  449.28
  5522.3  450.19  5551.1  446.72  5571.9  450.39  5743.1  449.74  5802.6  452.22
  6304.8  460.01  6618.4  471.93  6741.5  473.92  6768.6  474.67  6902.5  478.01
#Mann=6,-1,0
  3544.5    0.16       0  3588.6    0.12       0  5001.2    0.07       0
  5019.3    0.12       0  6741.5    0.16       0  6768.6    0.12       0
Bank Sta=4152.9,5802.6
Exp/Cntr=0.3,0.1

Type RM Length L Ch R = 1,99852,1041,1041,1041
BEGIN DESCRIPTION:
CANEY CREEK 98.0
END DESCRIPTION:
XS GIS Cut Line= 3
      2916878.10      7056573.54      2914842.85      7056889.80
      2913610.37      7058224.11
#Sta/Elev= 30
  3056.9  479.04  3271.1  467.71  3291.0  467.84  3302.9  462.84  3694.5  450.41
  4270.3  449.13  4284.6  448.30  4294.7  442.27  4325.0  449.12  4679.2  449.38
  4709.6  446.51  4942.4  448.91  4987.8  448.29  5004.2  438.69  5006.7  437.89
  5022.3  438.69  5033.4  445.95  5050.7  448.60  5055.7  445.16  5084.0  445.24
  5113.0  448.38  5316.7  450.76  5373.4  445.46  5412.6  450.41  5504.8  453.61
  5946.7  466.01  6197.6  467.00  6363.2  467.83  6549.0  472.34  6933.0  478.98
#Mann=8,-1,0
  3056.9    0.16       0  3271.1    0.12       0  5004.2    0.07       0
  5022.3    0.12       0  5504.8    0.05       0  6197.6    0.16       0
  6363.2    0.05       0  6549.0    0.16       0
Bank Sta=3694.5,5412.6
Exp/Cntr=0.3,0.1

Type RM Length L Ch R = 1,98811,802,802,802
BEGIN DESCRIPTION:
CANEY CREEK 97.0
END DESCRIPTION:
XS GIS Cut Line= 3
      2917430.18      7055084.77      2914565.58      7056143.80
      2913575.02      7057974.96
#Sta/Elev= 30
  2291.0  486.29  2455.9  479.87  2540.8  476.62  2637.7  470.15  2818.9  470.22
  2989.5  459.07  3320.8  453.21  3608.5  457.96  3764.4  448.70  3959.7  445.44
  4706.0  447.42  4738.0  439.55  4770.0  440.46  4780.7  447.29  4816.5  439.69
  4834.0  447.25  4983.0  447.65  4993.9  443.77  4995.5  437.90  4998.0  437.10
  5013.6  437.90  5025.9  446.93  5194.8  445.96  5225.4  446.32  5553.7  446.95
  6005.3  448.70  6381.2  457.70  6395.0  458.04  7369.8  474.81  7427.0  476.06
#Mann=12,-1,0
  2291.0    0.16       0  2455.9    0.12       0  2540.8    0.16       0
  3320.8    0.12       0  4995.5    0.07       0  5013.6    0.12       0
  5194.8    0.16       0  5225.4    0.05       0  5553.7    0.12       0
  6381.2    0.16       0  6395.0    0.05       0  7369.8    0.16       0
Bank Sta=3764.4,6005.3
Exp/Cntr=0.3,0.1

Type RM Length L Ch R = 1,98009,1080,1080,1080
BEGIN DESCRIPTION:
CANEY CREEK 96.0
END DESCRIPTION:
XS GIS Cut Line= 4
      2917056.87      7054835.22      2914980.08      7055206.30
      2914491.80      7055369.06      2912991.30      7057753.91
#Sta/Elev= 30
  2626.6  477.02  2825.0  472.33  2901.5  472.64  3317.1  459.79  3688.7  450.47
  3957.4  447.72  4025.5  446.75  4109.2  445.88  4487.5  438.99  4619.5  446.44
  4650.0  439.00  4680.5  446.25  4974.1  446.15  4991.3  435.89  4993.8  435.09
  5009.5  435.89  5026.2  446.49  5697.7  446.40  5972.7  445.94  6013.9  446.32
  6086.6  444.37  6207.0  446.40  6415.8  447.72  6428.3  448.12  6802.0  460.61
  6985.3  465.60  6997.8  465.60  7945.0  476.21  8023.0  476.35  8068.6  476.56
#Mann=20,-1,0
  2626.6    0.16       0  2825.0    0.12       0  2901.5    0.16       0
  3317.1    0.16       0  3688.7    0.12       0  4025.5    0.16       0
  4109.2    0.12       0  4991.3    0.07       0  5009.5    0.12       0
  5697.7    0.16       0  5972.7     0.1       0  6013.9    0.12       0
  6086.6    0.07       0  6207.0    0.16       0  6428.3    0.12       0
  6802.0    0.16       0  6985.3    0.12       0  6997.8    0.05       0
  7945.0    0.08       0  8023.0    0.05       0
Bank Sta=3957.4,6415.8
Exp/Cntr=0.3,0.1