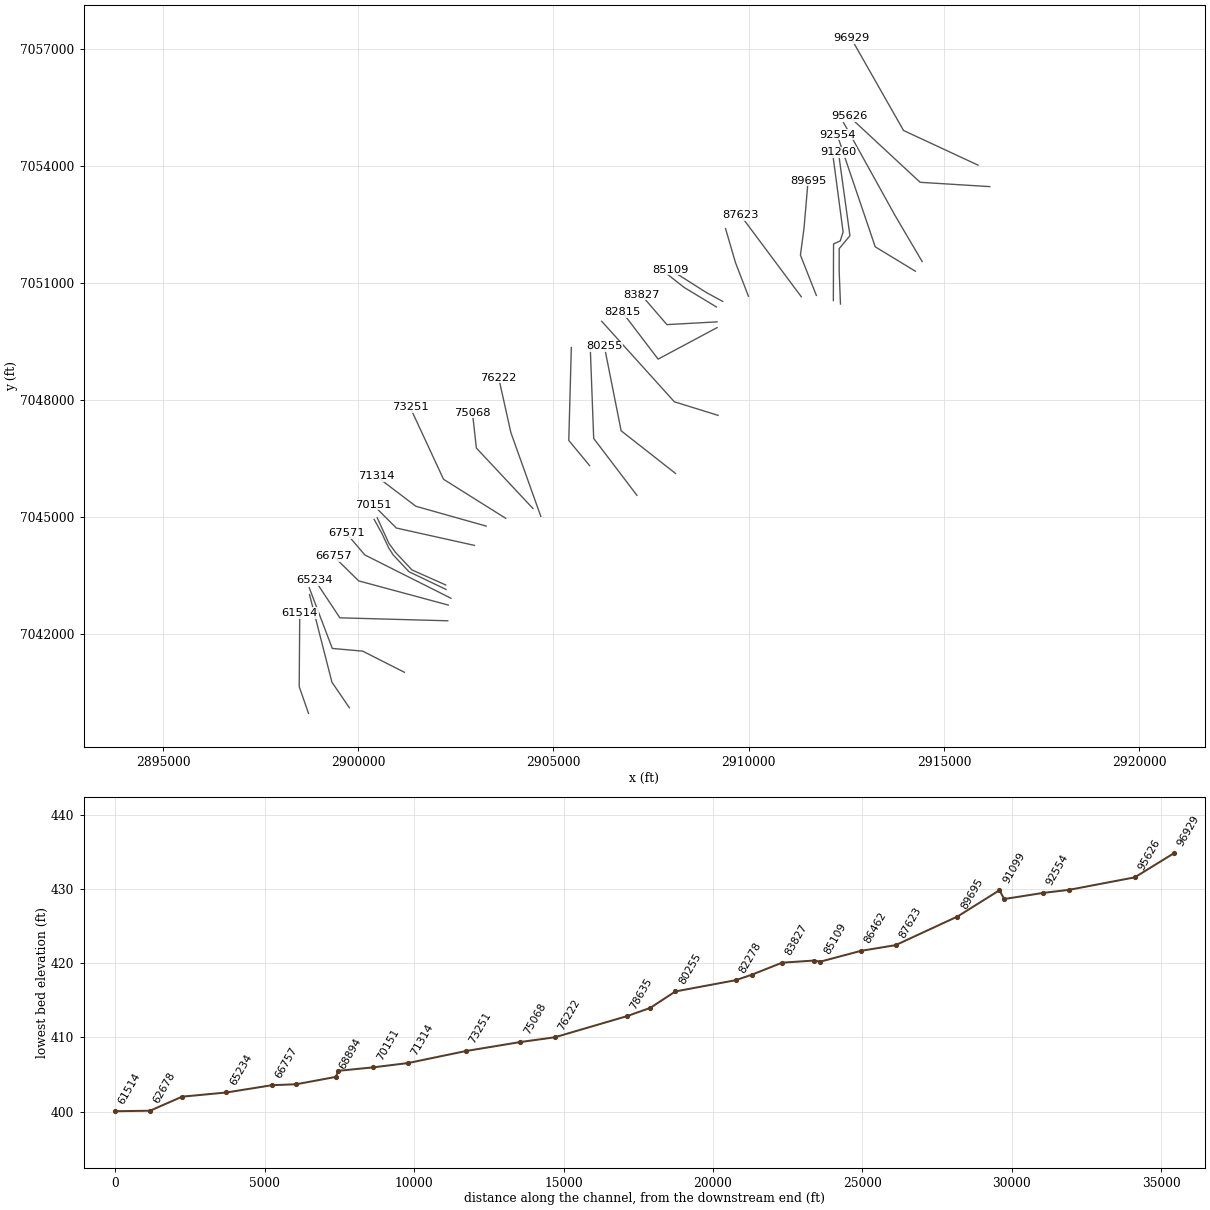
HEC-RAS study CANEY CREEK.prj: CANEY CREEK Base Level Engineering

--- CANEY CREEK.g01 (geometry) --- (continued)

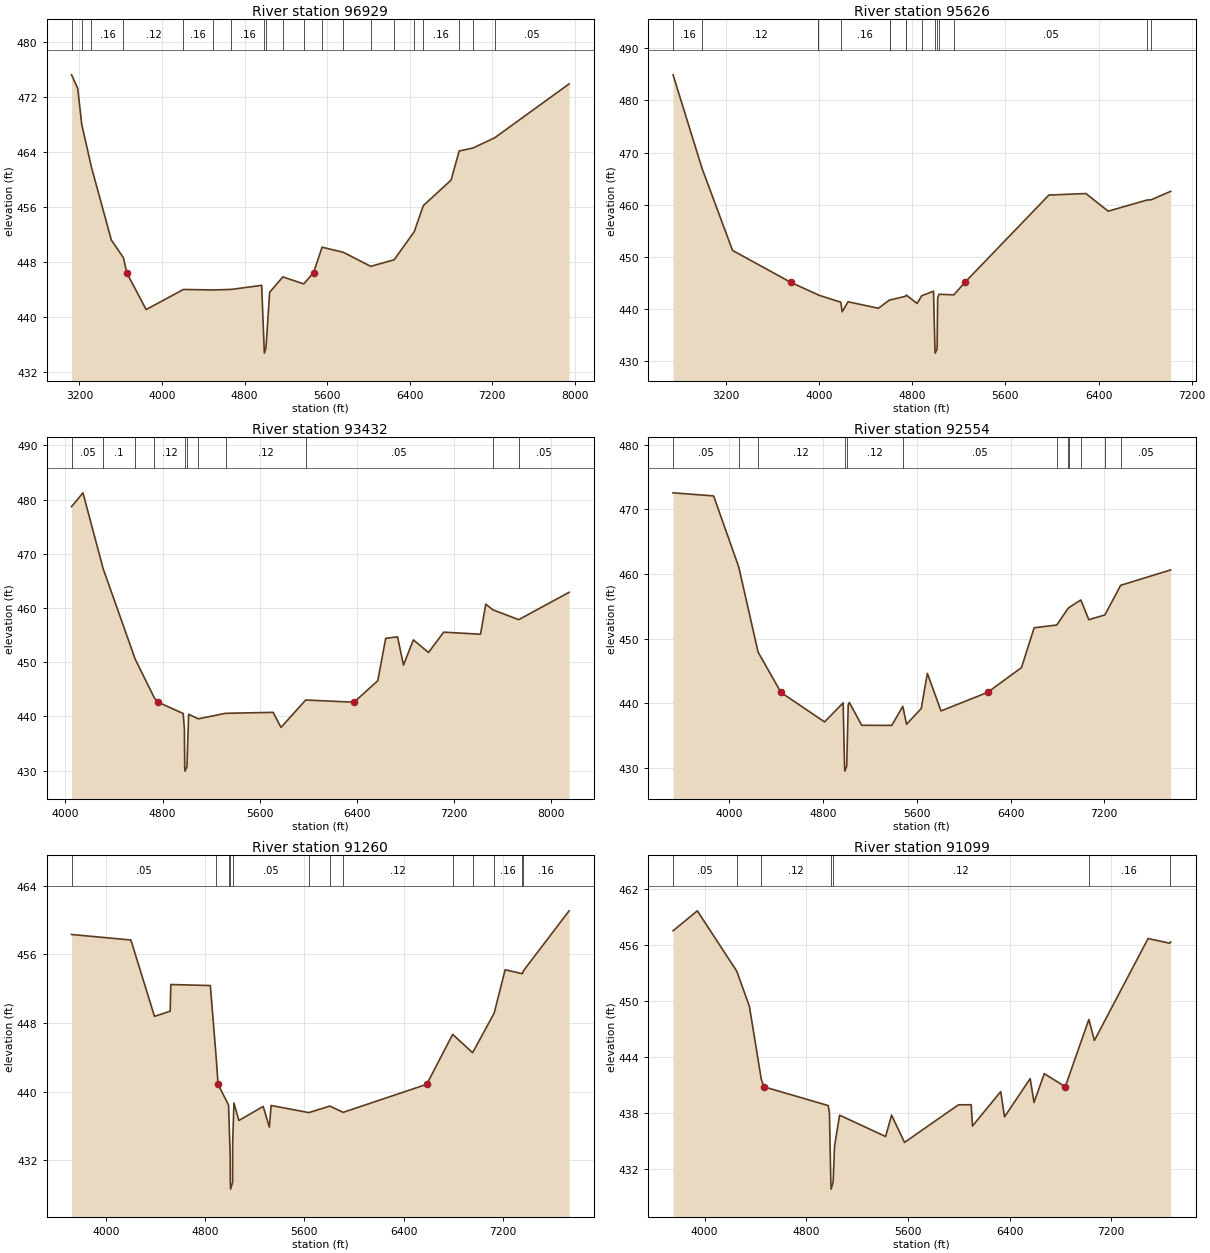
Type RM Length L Ch R = 1,96929,1303,1303,1303
BEGIN DESCRIPTION:
CANEY CREEK 95.0
END DESCRIPTION:
XS GIS Cut Line= 3
      2915875.04      7054024.98      2913966.62      7054913.34
      2912624.99      7057275.01
#Sta/Elev= 30
  3123.7  475.28  3183.7  473.30  3222.3  468.09  3316.5  461.84  3509.5  451.25
  3626.6  448.67  3658.6  446.48  3846.4  441.14  4207.6  444.06  4497.5  443.99
  4672.7  444.07  4965.8  444.66  4989.7  435.60  4992.2  434.80  5008.0  435.60
  5043.0  443.64  5171.0  445.89  5373.0  444.87  5468.2  446.48  5551.2  450.21
  5758.3  449.46  6022.9  447.42  6249.7  448.38  6444.1  452.46  6532.2  456.26
  6800.8  459.96  6879.8  464.20  7014.6  464.64  7223.6  466.12  7944.9  473.96
#Mann=20,-1,0
  3123.7    0.16       0  3222.3    0.12       0  3316.5    0.16       0
  3626.6    0.12       0  4207.6    0.16       0  4497.5    0.12       0
  4672.7    0.16       0  4989.7    0.07       0  5008.0    0.12       0
  5171.0    0.05       0  5373.0    0.16       0  5551.2    0.16       0
  5758.3    0.05       0  6022.9    0.12       0  6249.7    0.16       0
  6444.1    0.12       0  6532.2    0.16       0  6879.8    0.16       0
  7014.6    0.08       0  7223.6    0.05       0
Bank Sta=3658.6,5468.2
Exp/Cntr=0.3,0.1

Type RM Length L Ch R = 1,95626,2194,2194,2194
BEGIN DESCRIPTION:
CANEY CREEK 94.0
END DESCRIPTION:
XS GIS Cut Line= 3
      2916174.95      7053475.00      2914391.97      7053585.21
      2912569.50      7055277.50
#Sta/Elev= 30
  2745.5  484.90  2994.0  467.00  3256.4  451.25  3756.8  445.13  3987.9  442.78
  3991.8  442.71  4186.6  441.32  4198.2  439.48  4248.3  441.41  4508.8  440.17
  4604.6  441.75  4608.6  441.75  4742.7  442.47  4748.8  442.70  4841.2  441.09
  4880.8  442.55  4982.4  443.44  4994.7  432.37  4997.2  431.57  5013.0  432.37
  5018.0  442.09  5029.3  442.85  5157.1  442.74  5251.8  445.13  5973.3  461.86
  6291.4  462.15  6482.4  458.77  6814.9  460.90  6852.5  460.96  7018.9  462.57
#Mann=16,-1,0
  2745.5    0.16       0  2994.0    0.12       0  3987.9     0.1       0
  3991.8    0.05       0  4186.6    0.16       0  4604.6    0.05       0
  4608.6    0.12       0  4742.7    0.16       0  4748.8    0.12       0
  4880.8    0.16       0  4994.7    0.07       0  5013.0    0.16       0
  5029.3    0.12       0  5157.1    0.05       0  6814.9    0.08       0
  6852.5    0.05       0
Bank Sta=3756.8,5251.8
Exp/Cntr=0.3,0.1

Type RM Length L Ch R = 1,93432,878,878,878
BEGIN DESCRIPTION:
CANEY CREEK 93.0
END DESCRIPTION:
XS GIS Cut Line= 3
      2914444.06      7051553.95      2913749.61      7052734.52
      2912427.70      7055120.65
#Sta/Elev= 30
  4050.0  478.71  4144.0  481.26  4310.1  467.27  4574.2  450.56  4731.4  443.43
  4762.5  442.61  4969.4  440.53  4979.3  437.69  4981.8  430.69  4984.3  429.89
  5000.2  430.69  5014.2  440.39  5093.8  439.54  5317.8  440.56  5709.7  440.74
  5775.0  437.96  5978.2  443.02  6376.3  442.61  6571.8  446.58  6637.0  454.40
  6734.4  454.68  6783.6  449.46  6864.9  454.12  6989.6  451.79  7114.4  455.54
  7417.8  455.16  7461.3  460.72  7519.2  459.67  7732.6  457.85  8147.5  462.90
#Mann=11,-1,0
  4050.0    0.05       0  4310.1     0.1       0  4574.2    0.16       0
  4731.4    0.12       0  4981.8    0.07       0  5000.2    0.12       0
  5093.8    0.05       0  5317.8    0.12       0  5978.2    0.05       0
  7519.2    0.08       0  7732.6    0.05       0
Bank Sta=4762.5,6376.3
Exp/Cntr=0.3,0.1

Type RM Length L Ch R = 1,92554,1294,1294,1294
BEGIN DESCRIPTION:
CANEY CREEK 92.0
END DESCRIPTION:
XS GIS Cut Line= 3
      2914270.46      7051306.56      2913241.80      7051931.56
      2912265.25      7054809.12
#Sta/Elev= 30
  3522.9  472.56  3868.6  472.08  4083.3  461.06  4247.9  447.90  4442.7  441.66
  4814.7  437.09  4973.1  440.04  4985.0  430.27  4987.5  429.47  5003.4  430.27
  5016.4  439.75  5025.9  440.10  5131.4  436.57  5387.9  436.55  5481.6  439.51
  5513.5  436.72  5639.1  439.17  5691.2  444.61  5807.3  438.79  6204.1  441.66
  6493.7  445.50  6601.9  451.67  6794.6  452.09  6886.1  454.54  6897.1  454.78
  6999.6  455.97  7067.6  452.92  7204.6  453.65  7339.2  458.24  7765.3  460.62
#Mann=12,-1,0
  3522.9    0.05       0  4083.3    0.16       0  4247.9    0.12       0
  4985.0    0.07       0  5003.4    0.12       0  5481.6    0.05       0
  6794.6    0.16       0  6886.1    0.12       0  6897.1    0.16       0
  6999.6    0.12       0  7204.6    0.16       0  7339.2    0.05       0
Bank Sta=4442.7,6204.1
Exp/Cntr=0.3,0.1

Type RM Length L Ch R = 1,91260,161,161,161
BEGIN DESCRIPTION:
CANEY CREEK 91.0
END DESCRIPTION:
XS GIS Cut Line= 5
      2912351.17      7050467.13      2912318.18      7051309.17
      2912318.18      7051885.56      2912593.70      7052215.87
      2912299.08      7054356.08
#Sta/Elev= 30
  3724.2  458.33  4202.4  457.69  4392.6  448.79  4519.1  449.39  4524.1  452.50
  4842.7  452.38  4891.6  443.65  4904.8  440.87  4989.3  438.45  5002.7  432.54
  5003.5  429.45  5006.0  428.65  5022.0  429.45  5022.7  434.04  5032.7  438.69
  5072.7  436.65  5268.6  438.29  5318.1  435.88  5332.4  438.40  5636.3  437.57
  5805.8  438.33  5913.0  437.60  6586.7  440.87  6795.2  446.69  6956.1  444.55
  7129.6  449.16  7218.4  454.22  7356.7  453.76  7365.1  454.09  7733.8  461.09
#Mann=13,-1,0
  3724.2    0.05       0  4891.6    0.12       0  4989.3    0.05       0
  5003.5    0.04       0  5022.0    0.05       0  5636.3    0.12       0
  5805.8    0.05       0  5913.0    0.12       0  6795.2    0.05       0
  6956.1    0.12       0  7129.6    0.16       0  7356.7    0.12       0
  7365.1    0.16       0
Bank Sta=4904.8,6586.7
Exp/Cntr=0.3,0.1

Type RM Length L Ch R = 1,91099,1404,1404,1404
BEGIN DESCRIPTION:
CANEY CREEK 90.0
END DESCRIPTION:
XS GIS Cut Line= 5
      2912168.88      7050553.94      2912174.09      7052005.35
      2912345.96      7052083.47      2912418.88      7052312.64
      2912150.36      7054331.06
#Sta/Elev= 30
  3751.2  457.53  3942.3  459.67  4252.8  453.20  4352.3  449.42  4445.0  441.67
  4464.6  440.81  4972.3  438.79  4982.3  438.03  4993.0  430.63  4995.5  429.83
  5011.5  430.63  5022.3  434.43  5062.3  437.76  5424.5  435.47  5471.2  437.77
  5573.1  434.84  5997.5  438.87  6098.3  438.88  6108.4  436.60  6330.4  440.29
  6360.6  437.58  6562.4  441.68  6592.6  439.12  6673.4  442.21  6838.7  440.81
  7024.3  448.02  7068.0  445.77  7490.5  456.70  7660.7  456.20  7668.1  456.33
#Mann=7,-1,0
  3751.2    0.05       0  4252.8    0.16       0  4445.0    0.12       0
  4993.0    0.07       0  5011.5    0.12       0  7024.3    0.16       0
  7660.7    0.05       0
Bank Sta=4464.6,6838.7
Exp/Cntr=0.3,0.1

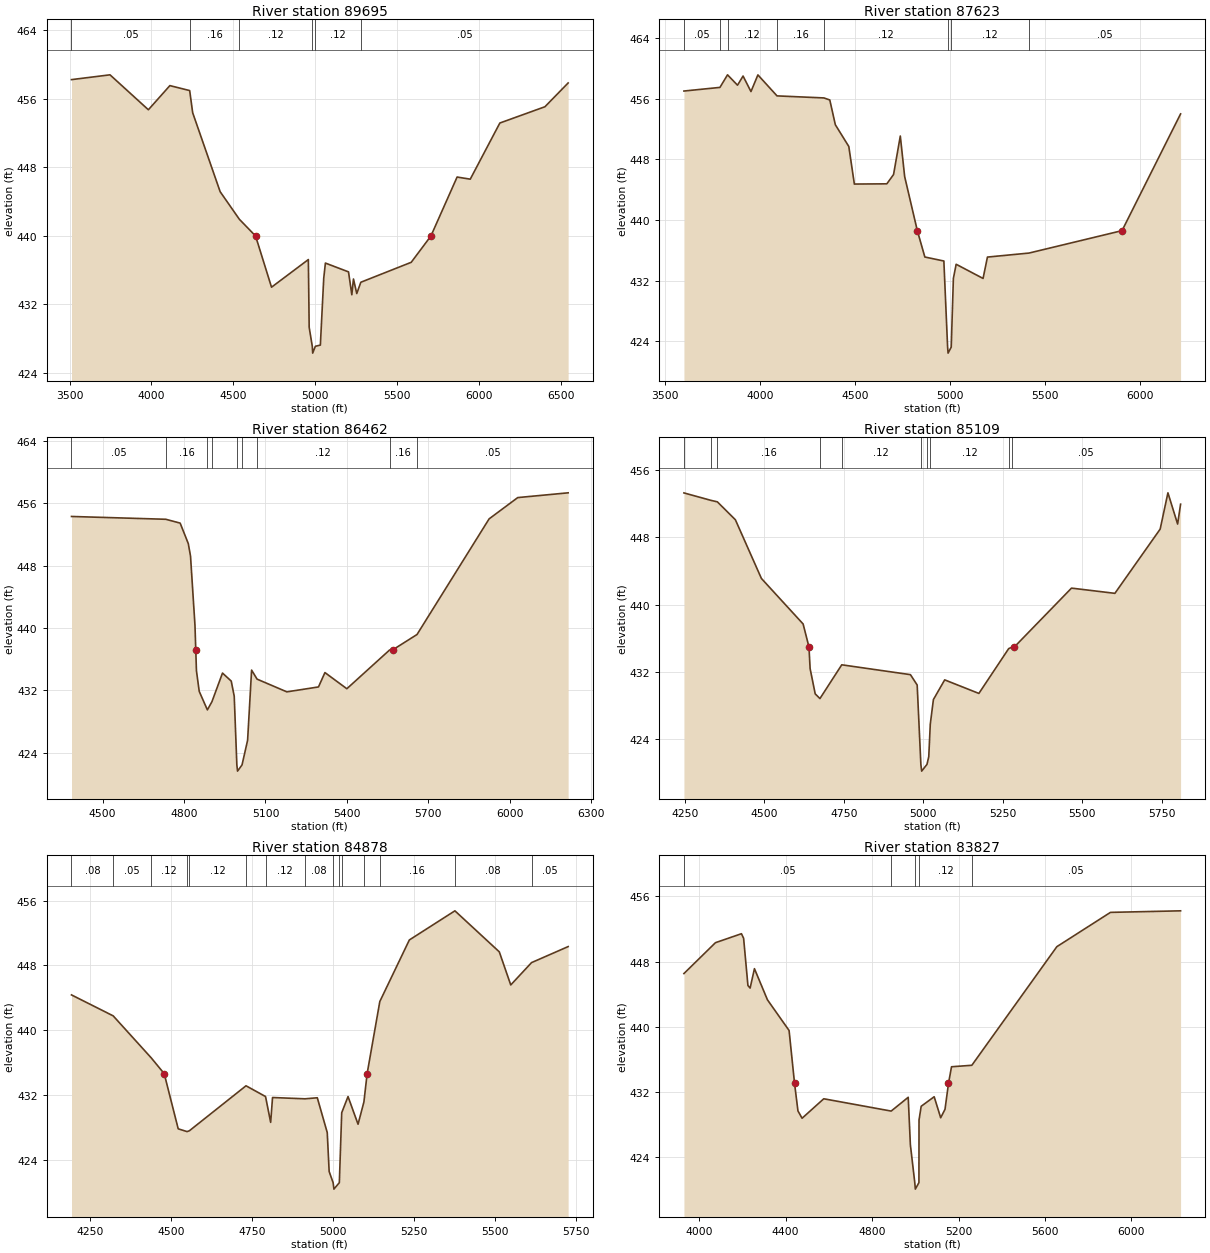
Type RM Length L Ch R = 1,89695,2072,2072,2072
BEGIN DESCRIPTION:
CANEY CREEK 89.0
END DESCRIPTION:
XS GIS Cut Line= 4
      2911733.55      7050686.33      2911325.56      7051719.32
      2911418.06      7052415.79      2911522.18      7053630.51
#Sta/Elev= 30
  3511.6  458.24  3746.7  458.80  3981.0  454.72  4112.3  457.54  4233.2  456.96
  4251.5  454.37  4419.2  445.15  4536.4  441.93  4635.6  439.97  4732.9  433.99
  4957.8  437.22  4962.8  429.30  4981.8  427.09  4984.3  426.29  5000.5  427.09
  5031.1  427.23  5051.7  435.04  5061.8  436.81  5203.0  435.78  5223.2  433.11
  5233.2  434.95  5253.4  433.25  5278.2  434.57  5585.9  436.90  5706.0  439.97
  5866.0  446.86  5946.3  446.61  6127.0  453.17  6402.2  455.07  6544.0  457.85
#Mann=6,-1,0
  3511.6    0.05       0  4233.2    0.16       0  4536.4    0.12       0
  4981.8    0.07       0  5000.5    0.12       0  5278.2    0.05       0
Bank Sta=4635.6,5706
Exp/Cntr=0.3,0.1

Type RM Length L Ch R = 1,87623,1161,1161,1161
BEGIN DESCRIPTION:
CANEY CREEK 88.0
END DESCRIPTION:
XS GIS Cut Line= 3
      2911347.75      7050652.76      2910374.92      7051957.99
      2909785.25      7052749.12
#Sta/Elev= 30
  3599.0  457.03  3788.6  457.51  3828.5  459.17  3881.1  457.80  3910.3  459.01
  3951.9  456.96  3988.4  459.16  4089.1  456.39  4335.8  456.12  4366.9  455.85
  4396.1  452.58  4467.0  449.71  4496.2  444.75  4667.2  444.78  4702.6  446.01
  4738.1  451.09  4761.0  445.74  4827.7  438.60  4867.3  435.12  4967.4  434.59
  4987.1  423.23  4989.6  422.43  5006.2  423.23  5017.5  432.29  5032.1  434.16
  5173.8  432.29  5196.8  435.11  5415.7  435.64  5905.4  438.60  6213.6  454.01
#Mann=8,-1,0
  3599.0    0.05       0  3788.6    0.16       0  3828.5    0.12       0
  4089.1    0.16       0  4335.8    0.12       0  4987.1    0.07       0
  5006.2    0.12       0  5415.7    0.05       0
Bank Sta=4827.7,5905.4
Exp/Cntr=0.3,0.1

Type RM Length L Ch R = 1,86462,1353,1353,1353
BEGIN DESCRIPTION:
CANEY CREEK 87.0
END DESCRIPTION:
XS GIS Cut Line= 3
      2909993.57      7050665.82      2909663.27      7051523.87
      2909407.66      7052397.51
#Sta/Elev= 30
  4385.5  454.30  4732.7  453.94  4785.8  453.45  4815.8  450.82  4824.0  449.22
  4840.4  440.35  4843.3  437.22  4845.8  434.53  4856.1  431.88  4886.1  429.51
  4902.8  430.55  4941.8  434.23  4974.0  433.20  4985.0  431.26  4994.7  422.46
  4997.2  421.66  5013.8  422.46  5034.3  425.62  5049.0  434.61  5069.2  433.45
  5178.9  431.82  5295.4  432.45  5319.2  434.29  5399.9  432.22  5557.2  437.18
  5569.7  437.22  5658.4  439.17  5924.0  453.99  6029.5  456.72  6215.2  457.33
#Mann=9,-1,0
  4385.5    0.05       0  4732.7    0.16       0  4886.1    0.12       0
  4902.8    0.16       0  4994.7    0.07       0  5013.8    0.16       0
  5069.2    0.12       0  5557.2    0.16       0  5658.4    0.05       0
Bank Sta=4843.3,5569.7
Exp/Cntr=0.3,0.1

Type RM Length L Ch R = 1,85109,231,231,231
BEGIN DESCRIPTION:
CANEY CREEK 86.0
END DESCRIPTION:
XS GIS Cut Line= 3
      2909333.87      7050533.84      2908917.19      7050759.54
      2907998.87      7051342.86
#Sta/Elev= 30
  4247.2  453.26  4332.7  452.37  4352.3  452.20  4409.0  450.07  4490.8  443.10
  4622.0  437.69  4640.4  434.96  4644.0  432.39  4660.0  429.39  4674.9  428.83
  4743.5  432.84  4959.5  431.67  4980.7  430.44  4992.3  421.01  4994.8  420.21
  5011.5  421.01  5017.1  421.92  5021.9  425.79  5031.7  428.71  5067.2  431.05
  5174.7  429.44  5268.4  434.76  5280.0  434.96  5286.3  434.96  5466.0  441.95
  5602.4  441.33  5744.8  448.96  5769.2  453.27  5799.7  449.56  5809.0  451.92
#Mann=11,-1,0
  4247.2    0.05       0  4332.7    0.08       0  4352.3    0.16       0
  4674.9    0.05       0  4743.5    0.12       0  4992.3    0.07       0
  5011.5    0.12       0  5021.9    0.12       0  5268.4    0.08       0
  5280.0    0.05       0  5744.8    0.08       0
Bank Sta=4640.4,5286.3
Exp/Cntr=0.3,0.1

Type RM Length L Ch R = 1,84878,1051,1051,1051
BEGIN DESCRIPTION:
CANEY CREEK 85.0
END DESCRIPTION:
XS GIS Cut Line= 3
      2909173.31      7050390.59      2908347.38      7050890.84
      2907902.43      7051240.63
#Sta/Elev= 30
  4193.2  444.35  4321.8  441.76  4439.3  436.56  4479.1  434.62  4522.3  427.80
  4549.5  427.46  4556.7  427.56  4731.4  433.12  4791.6  431.79  4807.4  428.60
  4813.2  431.67  4913.2  431.51  4951.2  431.64  4981.9  427.34  4987.8  422.52
  5000.0  421.15  5002.5  420.35  5019.2  421.15  5026.5  429.79  5046.0  431.79
  5076.9  428.37  5095.0  431.13  5104.9  434.62  5144.0  443.53  5235.1  451.14
  5375.6  454.74  5512.5  449.67  5547.8  445.58  5611.9  448.34  5724.8  450.32
#Mann=15,-1,0
  4193.2    0.08       0  4321.8    0.05       0  4439.3    0.12       0
  4549.5    0.08       0  4556.7    0.12       0  4731.4    0.05       0
  4791.6    0.12       0  4913.2    0.08       0  5000.0    0.07       0
  5019.2    0.08       0  5026.5    0.12       0  5095.0    0.05       0
  5144.0    0.16       0  5375.6    0.08       0  5611.9    0.05       0
Bank Sta=4479.1,5104.9
Exp/Cntr=0.3,0.1

Type RM Length L Ch R = 1,83827,1012,1012,1012
BEGIN DESCRIPTION:
CANEY CREEK 84.0
END DESCRIPTION:
XS GIS Cut Line= 3
      2909190.60      7050008.67      2907905.80      7049938.15
      2907246.19      7050703.11
#Sta/Elev= 30
  3930.2  446.53  4076.0  450.32  4196.2  451.42  4206.2  450.86  4226.2  445.06
  4236.3  444.75  4256.3  447.13  4316.4  443.31  4416.5  439.54  4441.8  433.04
  4457.5  429.67  4476.6  428.77  4576.8  431.16  4888.6  429.65  4967.4  431.34
  4977.4  425.52  4997.8  420.87  5000.3  420.07  5017.0  420.87  5017.4  428.55
  5027.4  430.24  5087.5  431.41  5117.6  428.83  5137.6  429.87  5153.7  433.04
  5167.7  435.09  5261.6  435.27  5654.8  449.83  5902.8  454.04  6227.0  454.23
#Mann=5,-1,0
  3930.2    0.05       0  4888.6    0.12       0  4997.8    0.07       0
  5017.0    0.12       0  5261.6    0.05       0
Bank Sta=4441.8,5153.7
Exp/Cntr=0.3,0.1

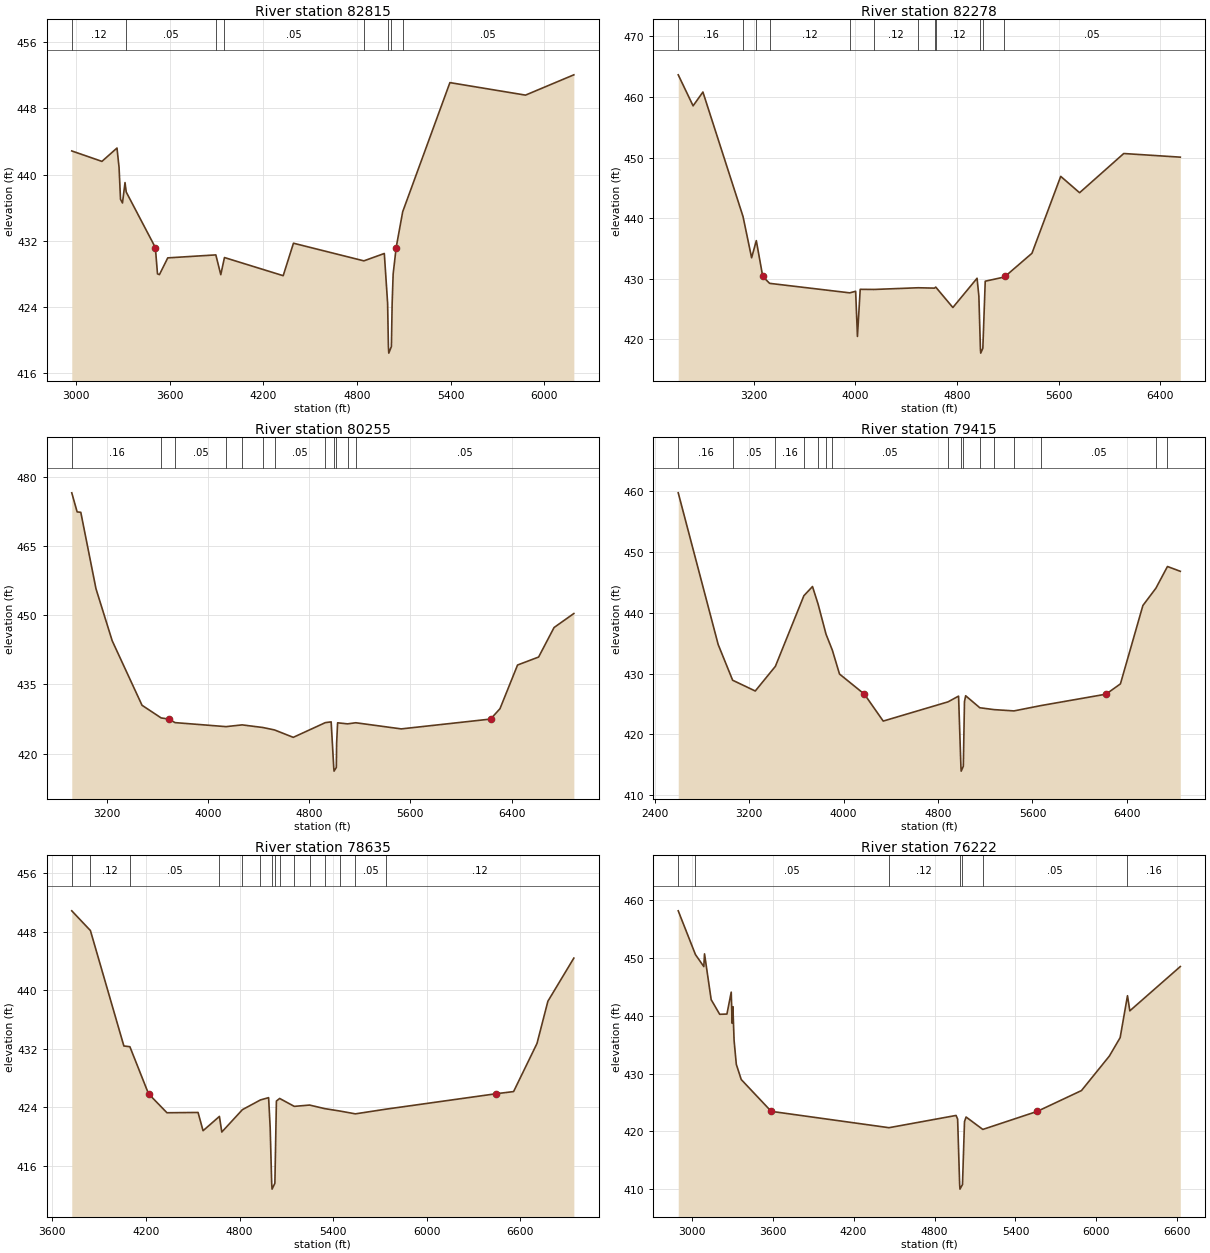
Type RM Length L Ch R = 1,82815,537,537,537
BEGIN DESCRIPTION:
CANEY CREEK 83.0
END DESCRIPTION:
XS GIS Cut Line= 3
      2909190.59      7049861.08      2907680.21      7049053.81
      2906768.77      7050251.71
#Sta/Elev= 30
  2972.7  442.86  3166.0  441.60  3262.5  443.21  3275.8  440.87  3285.2  437.02
  3297.7  436.58  3314.0  439.04  3321.7  437.90  3508.4  431.20  3522.1  428.02
  3534.6  427.93  3587.9  429.95  3896.1  430.31  3927.7  427.92  3951.3  429.99
  4327.7  427.80  4393.5  431.72  4844.8  429.59  4975.8  430.48  4997.0  424.46
  5002.0  419.25  5004.5  418.45  5021.2  419.25  5026.0  424.43  5032.4  427.99
  5051.8  431.20  5093.6  435.52  5396.2  451.11  5880.7  449.60  6190.5  452.05
#Mann=8,-1,0
  2972.7    0.12       0  3321.7    0.05       0  3896.1     0.1       0
  3951.3    0.05       0  4844.8    0.12       0  5002.0    0.07       0
  5021.2    0.12       0  5093.6    0.05       0
Bank Sta=3508.4,5051.8
Exp/Cntr=0.3,0.1

Type RM Length L Ch R = 1,82278,2023,2023,2023
BEGIN DESCRIPTION:
CANEY CREEK 82.0
END DESCRIPTION:
XS GIS Cut Line= 3
      2909216.71      7047612.82      2908096.88      7047960.06
      2906234.75      7050023.93
#Sta/Elev= 30
  2605.2  463.65  2722.2  458.53  2799.5  460.81  3115.3  440.25  3182.8  433.45
  3219.8  436.28  3270.5  430.36  3324.3  429.23  3955.3  427.66  4001.7  427.92
  4015.9  420.46  4037.6  428.24  4146.6  428.22  4493.6  428.50  4622.7  428.44
  4632.2  428.61  4767.0  425.24  4957.5  430.07  4971.7  427.13  4983.8  418.51
  4986.3  417.71  5003.0  418.51  5021.8  429.58  5166.9  430.25  5177.6  430.36
  5389.5  434.19  5616.0  446.89  5764.6  444.19  6112.1  450.66  6557.4  450.06
#Mann=12,-1,0
  2605.2    0.16       0  3115.3    0.05       0  3219.8    0.08       0
  3324.3    0.12       0  3955.3    0.07       0  4146.6    0.12       0
  4493.6     0.1       0  4622.7    0.07       0  4632.2    0.12       0
  4983.8    0.07       0  5003.0    0.12       0  5166.9    0.05       0
Bank Sta=3270.5,5177.6
Exp/Cntr=0.3,0.1

Type RM Length L Ch R = 1,80255,840,840,840
BEGIN DESCRIPTION:
CANEY CREEK 81.0
END DESCRIPTION:
XS GIS Cut Line= 3
      2908125.00      7046125.00      2906733.16      7047217.00
      2906303.48      7049378.42
#Sta/Elev= 30
  2920.3  476.49  2962.8  472.36  2991.7  472.27  3112.0  455.70  3240.3  444.43
  3476.2  430.46  3627.4  427.72  3685.7  427.47  3738.0  426.70  4140.4  425.83
  4268.6  426.21  4432.9  425.64  4525.0  425.11  4673.0  423.51  4926.8  426.70
  4972.8  426.86  4993.2  416.99  4995.7  416.19  5013.7  416.99  5016.0  422.18
  5023.8  426.66  5102.5  426.43  5167.8  426.67  5527.3  425.34  6234.3  427.47
  6308.5  429.71  6447.7  439.18  6614.3  440.91  6736.7  447.31  6893.1  450.34
#Mann=12,-1,0
  2920.3    0.16       0  3627.4    0.12       0  3738.0    0.05       0
  4140.4    0.16       0  4268.6    0.12       0  4432.9    0.16       0
  4525.0    0.05       0  4926.8    0.12       0  4993.2    0.07       0
  5013.7    0.12       0  5102.5    0.07       0  5167.8    0.05       0
Bank Sta=3685.7,6234.3
Exp/Cntr=0.3,0.1

Type RM Length L Ch R = 1,79415,780,780,780
BEGIN DESCRIPTION:
CANEY CREEK 80.0
END DESCRIPTION:
XS GIS Cut Line= 3
      2907136.82      7045563.34      2906030.04      7047021.69
      2905938.96      7049441.80
#Sta/Elev= 30
  2599.9  459.68  2938.3  434.76  3060.7  428.90  3252.4  427.13  3422.7  431.18
  3664.1  442.78  3737.1  444.29  3784.8  441.38  3851.7  436.46  3905.4  433.83
  3965.8  429.92  4176.7  426.61  4336.1  422.19  4885.3  425.35  4974.4  426.29
  4994.1  414.77  4996.6  413.97  5014.6  414.77  5024.4  425.38  5034.4  426.35
  5154.1  424.38  5276.5  424.07  5443.6  423.86  5673.0  424.74  6223.1  426.61
  6345.3  428.30  6535.5  441.17  6645.9  444.02  6743.7  447.58  6852.5  446.79
#Mann=16,-1,0
  2599.9    0.16       0  3060.7    0.05       0  3422.7    0.16       0
  3664.1    0.12       0  3784.8    0.05       0  3851.7    0.16       0
  3905.4    0.05       0  4885.3    0.12       0  4994.1    0.07       0
  5014.6    0.12       0  5154.1    0.16       0  5276.5    0.07       0
  5443.6    0.12       0  5673.0    0.05       0  6645.9    0.16       0
  6743.7    0.05       0
Bank Sta=4176.7,6223.1
Exp/Cntr=0.3,0.1

Type RM Length L Ch R = 1,78635,2413,2413,2413
BEGIN DESCRIPTION:
CANEY CREEK 79.0
END DESCRIPTION:
XS GIS Cut Line= 3
      2905925.00      7046325.00      2905392.02      7046969.61
      2905457.09      7049351.20
#Sta/Elev= 30
  3724.1  450.83  3843.6  448.14  4058.2  432.39  4096.7  432.29  4216.2  425.87
  4334.4  423.28  4533.7  423.32  4565.9  420.83  4670.7  422.78  4686.0  420.65
  4818.0  423.70  4933.8  425.03  4986.1  425.34  4996.1  421.27  5005.8  413.66
  5008.3  412.86  5026.3  413.66  5036.1  424.88  5057.0  425.23  5150.8  424.15
  5248.7  424.33  5346.7  423.84  5444.6  423.51  5542.5  423.13  5738.4  423.77
  6442.9  425.87  6556.7  426.17  6706.7  432.73  6776.7  438.50  6943.0  444.38
#Mann=15,-1,0
  3724.1    0.16       0  3843.6    0.12       0  4096.7    0.05       0
  4670.7    0.12       0  4818.0    0.05       0  4933.8    0.12       0
  5005.8    0.07       0  5026.3    0.12       0  5057.0    0.07       0
  5150.8    0.12       0  5248.7    0.16       0  5346.7    0.12       0
  5444.6    0.16       0  5542.5    0.05       0  5738.4    0.12       0
Bank Sta=4216.2,6442.9
Exp/Cntr=0.3,0.1

Type RM Length L Ch R = 1,76222,1154,1154,1154
BEGIN DESCRIPTION:
CANEY CREEK 77.0
END DESCRIPTION:
XS GIS Cut Line= 3
      2904675.00      7045025.01      2903907.64      7047174.47
      2903595.23      7048580.35
#Sta/Elev= 30
  2899.9  458.21  3027.6  450.63  3089.5  448.55  3094.8  450.76  3144.1  442.83
  3207.3  440.29  3260.9  440.33  3292.8  444.13  3299.7  438.74  3305.1  441.61
  3314.0  435.76  3330.5  431.62  3367.1  428.99  3589.4  423.48  4462.5  420.65
  4959.8  422.77  4971.4  422.14  4986.4  410.81  4988.9  410.01  5007.4  410.81
  5022.4  421.71  5034.1  422.50  5158.1  420.35  5562.2  423.48  5889.6  427.08
  6096.5  433.06  6176.4  436.25  6230.8  443.51  6248.1  440.89  6622.4  448.56
#Mann=7,-1,0
  2899.9    0.16       0  3027.6    0.05       0  4462.5    0.12       0
  4986.4    0.07       0  5007.4    0.12       0  5158.1    0.05       0
  6230.8    0.16       0
Bank Sta=3589.4,5562.2
Exp/Cntr=0.3,0.1

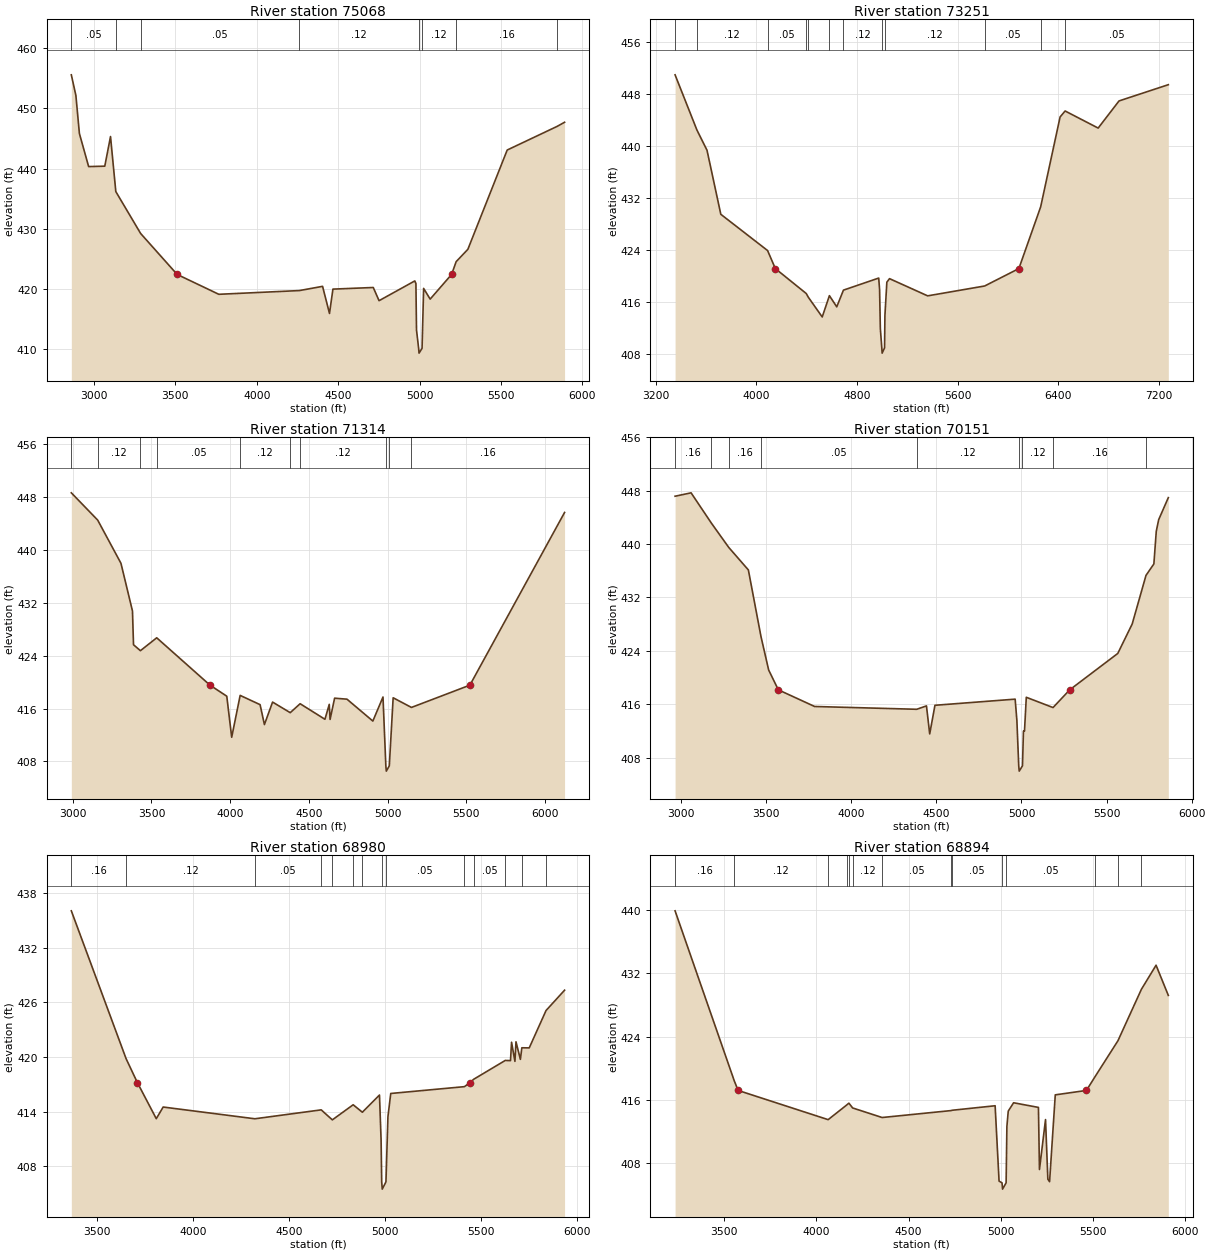
Type RM Length L Ch R = 1,75068,1817,1817,1817
BEGIN DESCRIPTION:
CANEY CREEK 76.0
END DESCRIPTION:
XS GIS Cut Line= 3
      2904475.03      7045224.97      2903025.00      7046775.00
      2902925.00      7047675.02
#Sta/Elev= 30
  2862.0  455.59  2890.1  452.15  2911.6  445.84  2968.3  440.35  3067.4  440.42
  3102.6  445.34  3135.1  436.20  3287.5  429.24  3511.7  422.44  3767.5  419.14
  4262.4  419.76  4404.5  420.46  4446.9  415.96  4468.0  420.00  4715.6  420.27
  4751.3  418.08  4970.6  421.36  4977.5  420.93  4981.1  413.21  4994.2  410.17
  4996.7  409.37  5015.2  410.17  5024.8  420.12  5065.0  418.34  5196.6  422.44
  5224.5  424.56  5296.4  426.61  5537.9  443.10  5843.1  447.01  5890.1  447.71
#Mann=8,-1,0
  2862.0    0.05       0  3135.1    0.16       0  3287.5    0.05       0
  4262.4    0.12       0  4994.2    0.07       0  5015.2    0.12       0
  5224.5    0.16       0  5843.1    0.05       0
Bank Sta=3511.7,5196.6
Exp/Cntr=0.3,0.1

Type RM Length L Ch R = 1,73251,1937,1937,1937
BEGIN DESCRIPTION:
CANEY CREEK 74.0
END DESCRIPTION:
XS GIS Cut Line= 3
      2903775.00      7044975.00      2902183.99      7045974.59
      2901325.01      7047824.98
#Sta/Elev= 30
  3354.8  451.02  3528.4  442.52  3608.6  439.40  3718.2  429.54  4089.7  423.96
  4151.5  421.18  4397.0  417.34  4413.0  416.78  4523.9  413.73  4581.0  417.01
  4639.3  415.29  4692.5  417.86  4972.8  419.72  4979.7  417.95  4985.6  411.97
  4997.3  408.96  5000.1  408.16  5019.1  408.96  5022.1  413.98  5037.4  419.09
  5058.6  419.63  5361.5  416.98  5814.7  418.50  6086.3  421.18  6259.4  430.68
  6413.9  444.53  6453.8  445.45  6716.4  442.82  6882.2  447.00  7273.8  449.50
#Mann=12,-1,0
  3354.8    0.16       0  3528.4    0.12       0  4089.7    0.05       0
  4397.0    0.16       0  4413.0    0.05       0  4581.0    0.16       0
  4692.5    0.12       0  4997.3    0.07       0  5019.1    0.12       0
  5814.7    0.05       0  6259.4    0.16       0  6453.8    0.05       0
Bank Sta=4151.5,6086.3
Exp/Cntr=0.3,0.1

Type RM Length L Ch R = 1,71314,1163,1163,1163
BEGIN DESCRIPTION:
CANEY CREEK 72.0
END DESCRIPTION:
XS GIS Cut Line= 3
      2903275.05      7044774.99      2901475.93      7045282.43
      2900470.14      7046046.00
#Sta/Elev= 30
  2991.1  448.62  3158.4  444.50  3306.2  437.97  3379.4  430.75  3386.0  425.65
  3429.8  424.75  3533.4  426.70  3871.6  419.54  3978.2  417.87  4009.4  411.66
  4063.2  417.99  4189.8  416.59  4217.2  413.58  4269.1  416.98  4381.1  415.38
  4444.0  416.73  4601.6  414.38  4629.0  416.64  4634.2  414.36  4663.0  417.57
  4741.4  417.42  4905.8  414.11  4970.2  417.75  4988.3  407.34  4991.2  406.54
  5010.3  407.34  5034.7  417.63  5151.0  416.17  5522.0  419.54  6123.2  445.65
#Mann=10,-1,0
  2991.1    0.16       0  3158.4    0.12       0  3429.8    0.16       0
  3533.4    0.05       0  4063.2    0.12       0  4381.1    0.16       0
  4444.0    0.12       0  4988.3    0.07       0  5010.3    0.12       0
  5151.0    0.16       0
Bank Sta=3871.6,5522
Exp/Cntr=0.3,0.1

Type RM Length L Ch R = 1,70151,1171,1171,1171
BEGIN DESCRIPTION:
CANEY CREEK 71.0
END DESCRIPTION:
XS GIS Cut Line= 3
      2902975.31      7044280.38      2900975.00      7044725.00
      2900374.97      7045325.03
#Sta/Elev= 30
  2965.2  447.17  3059.2  447.68  3178.7  443.13  3280.7  439.49  3395.8  436.12
  3469.7  426.15  3515.0  421.12  3571.7  418.15  3785.0  415.65  4384.8  415.23
  4442.0  415.74  4461.1  411.54  4491.9  415.83  4963.1  416.75  4973.3  413.53
  4984.1  406.76  4987.0  405.96  5006.1  406.76  5011.8  411.96  5017.9  411.96
  5028.5  417.03  5185.6  415.49  5283.8  418.15  5565.9  423.60  5650.7  428.02
  5731.8  435.31  5778.0  437.02  5792.1  441.92  5806.3  443.66  5862.9  446.96
#Mann=9,-1,0
  2965.2    0.16       0  3178.7    0.12       0  3280.7    0.16       0
  3469.7    0.05       0  4384.8    0.12       0  4984.1    0.07       0
  5006.1    0.12       0  5185.6    0.16       0  5731.8    0.05       0
Bank Sta=3571.7,5283.8
Exp/Cntr=0.3,0.1

Type RM Length L Ch R = 1,68980,86,86,86
BEGIN DESCRIPTION:
Mapping XS 5daf7598
END DESCRIPTION:
XS GIS Cut Line= 6
      2902239.69      7043266.04      2901375.09      7043651.46
      2900950.61      7044104.59      2900869.88      7044216.57
      2900786.55      7044328.55      2900484.47      7044990.00
#Sta/Elev= 30
  3365.2  436.07  3650.9  419.82  3710.0  417.18  3808.3  413.23  3844.1  414.51
  4322.4  413.22  4668.4  414.20  4726.4  413.10  4835.0  414.76  4882.9  413.94
  4972.2  415.83  4980.7  410.85  4983.8  406.29  4986.7  405.49  5006.0  406.29
  5016.3  413.44  5031.0  416.00  5415.3  416.75  5443.7  417.18  5463.5  417.56
  5628.2  419.63  5655.5  419.61  5661.0  421.63  5678.6  419.53  5684.1  421.68
  5707.1  419.75  5714.7  421.02  5753.2  421.01  5841.0  425.12  5937.5  427.35
#Mann=14,-1,0
  3365.2    0.16       0  3650.9    0.12       0  4322.4    0.05       0
  4668.4    0.12       0  4726.4    0.08       0  4835.0    0.12       0
  4882.9    0.05       0  4983.8    0.04       0  5006.0    0.05       0
  5415.3    0.16       0  5463.5    0.05       0  5628.2    0.16       0
  5714.7    0.05       0  5841.0    0.16       0
Bank Sta=3710,5443.7
Exp/Cntr=0.3,0.1

Type RM Length L Ch R = 1,68894,1323,1323,1323
BEGIN DESCRIPTION:
CANEY CREEK 70.0
END DESCRIPTION:
XS GIS Cut Line= 6
      2902247.46      7043151.48      2901299.57      7043604.59
      2900893.32      7044036.88      2900778.74      7044216.57
      2900601.65      7044594.17      2900406.34      7044945.74
#Sta/Elev= 30
  3232.8  439.92  3554.2  418.37  3574.9  417.17  4063.3  413.47  4164.2  415.33
  4175.9  415.56  4196.3  414.95  4356.2  413.74  4730.9  414.62  4736.5  414.66
  4969.3  415.23  4990.7  405.68  5006.7  405.47  5009.7  404.67  5028.9  405.47
  5033.1  412.60  5040.5  414.55  5069.5  415.61  5204.3  415.02  5209.8  407.15
  5242.7  413.48  5255.4  405.93  5264.7  405.61  5295.6  416.61  5464.6  417.17
  5512.7  418.96  5635.8  423.47  5762.9  429.98  5842.5  433.03  5909.0  429.21
#Mann=14,-1,0
  3232.8    0.16       0  3554.2    0.12       0  4063.3    0.05       0
  4164.2    0.12       0  4175.9    0.05       0  4196.3    0.12       0
  4356.2    0.05       0  4730.9    0.16       0  4736.5    0.05       0
  5006.7    0.04       0  5028.9    0.05       0  5512.7    0.12       0
  5635.8    0.05       0  5762.9    0.12       0
Bank Sta=3574.9,5464.6
Exp/Cntr=0.3,0.1

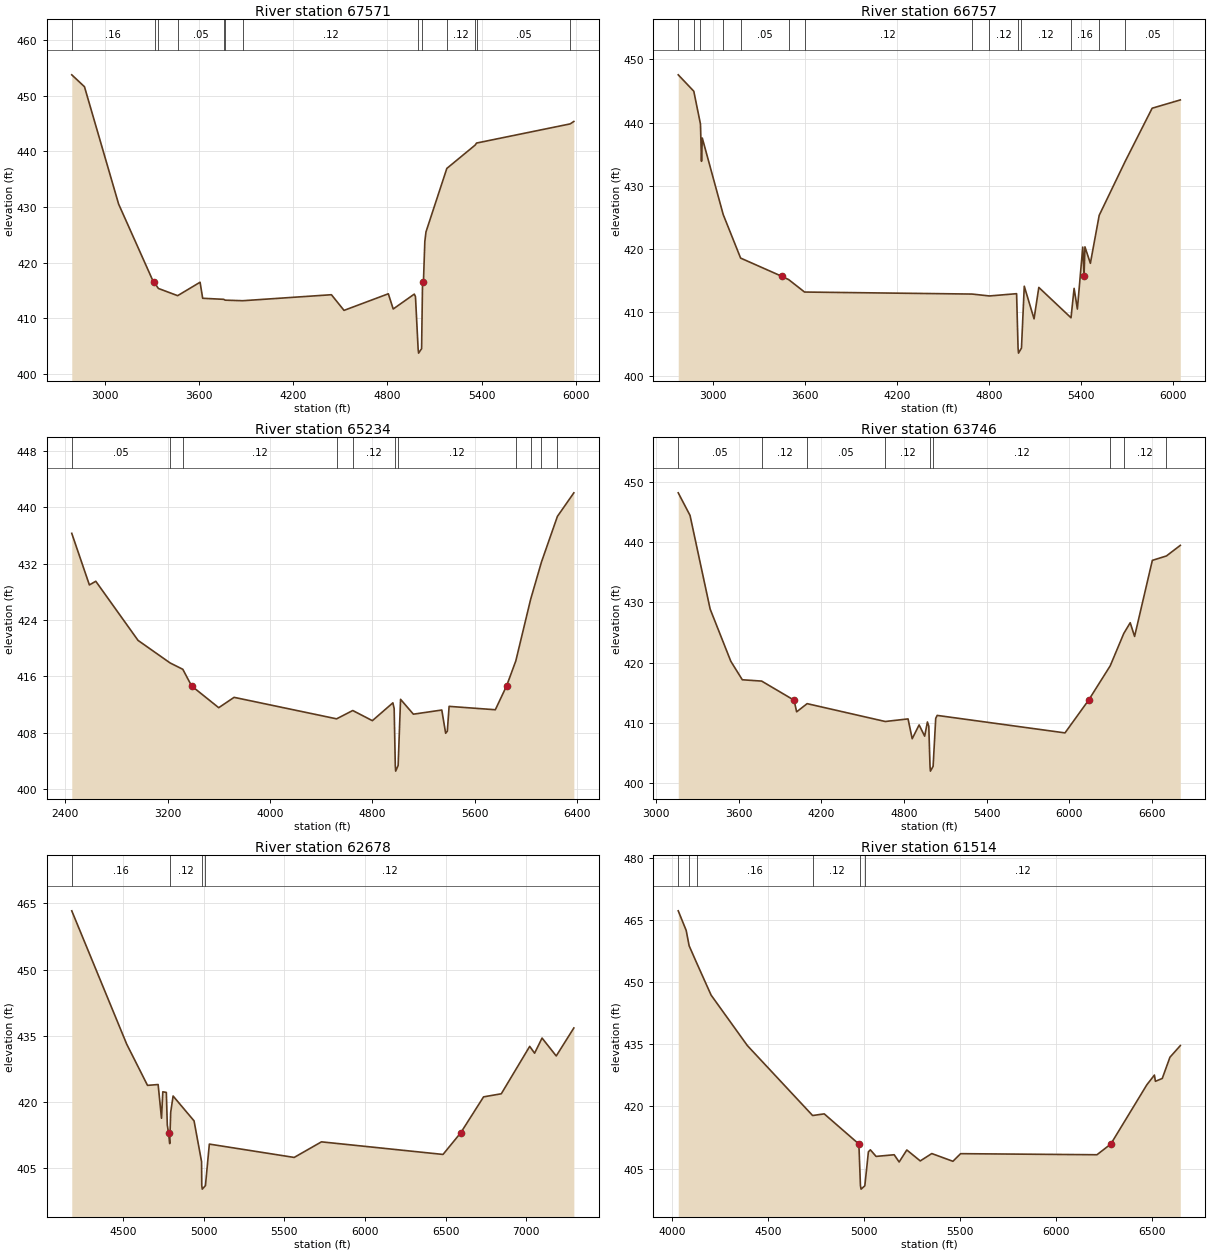
Type RM Length L Ch R = 1,67571,814,814,814
BEGIN DESCRIPTION:
CANEY CREEK 69.0
END DESCRIPTION:
XS GIS Cut Line= 3
      2902375.01      7042925.00      2900167.63      7044035.15
      2899695.70      7044590.35
#Sta/Elev= 30
  2788.9  453.81  2869.8  451.67  3087.5  430.53  3309.8  416.47  3317.9  416.29
  3340.8  415.33  3463.6  414.03  3606.5  416.45  3623.2  413.56  3756.9  413.37
  3766.7  413.22  3878.8  413.12  4443.5  414.20  4523.9  411.38  4806.2  414.37
  4837.3  411.63  4971.6  414.31  4979.2  413.85  4996.0  404.48  4999.0  403.68
  5018.2  404.48  5023.9  415.78  5030.0  416.47  5038.8  423.77  5046.2  425.52
  5179.0  436.95  5360.2  441.17  5368.3  441.52  5964.9  444.97  5988.4  445.41
#Mann=13,-1,0
  2788.9    0.16       0  3317.9    0.08       0  3340.8    0.12       0
  3463.6    0.05       0  3756.9    0.08       0  3766.7    0.05       0
  3878.8    0.12       0  4996.0    0.07       0  5018.2    0.12       0
  5179.0    0.12       0  5360.2    0.07       0  5368.3    0.05       0
  5964.9    0.16       0
Bank Sta=3309.8,5030
Exp/Cntr=0.3,0.1

Type RM Length L Ch R = 1,66757,1523,1523,1523
BEGIN DESCRIPTION:
CANEY CREEK 68.0
END DESCRIPTION:
XS GIS Cut Line= 3
      2902306.53      7042750.42      2900011.50      7043370.20
      2899369.75      7043999.71
#Sta/Elev= 30
  2773.1  447.56  2874.6  444.97  2918.2  439.77  2924.9  433.88  2930.1  437.56
  3066.6  425.46  3180.1  418.58  3448.8  415.70  3494.1  415.17  3597.4  413.21
  4691.0  412.89  4803.7  412.59  4981.0  412.95  4990.6  404.35  4993.5  403.55
  5012.8  404.35  5031.1  414.13  5094.9  408.97  5126.0  413.94  5336.1  409.14
  5356.3  413.79  5377.6  410.52  5412.8  420.32  5421.1  415.70  5427.0  420.36
  5462.4  417.75  5520.0  425.34  5688.7  433.83  5865.5  442.28  6049.3  443.59
#Mann=14,-1,0
  2773.1    0.05       0  2874.6    0.08       0  2918.2    0.05       0
  3066.6    0.16       0  3180.1    0.05       0  3494.1    0.07       0
  3597.4    0.12       0  4691.0    0.16       0  4803.7    0.12       0
  4990.6    0.07       0  5012.8    0.12       0  5336.1    0.16       0
  5520.0     0.1       0  5688.7    0.05       0
Bank Sta=3448.8,5421.1
Exp/Cntr=0.3,0.1

Type RM Length L Ch R = 1,65234,1488,1488,1488
BEGIN DESCRIPTION:
CANEY CREEK 67.0
END DESCRIPTION:
XS GIS Cut Line= 3
      2902292.63      7042347.65      2899528.74      7042424.03
      2898889.91      7043389.22
#Sta/Elev= 30
  2451.2  436.31  2588.9  428.99  2638.9  429.51  2969.0  421.12  3219.5  417.92
  3318.7  417.02  3387.7  414.65  3599.3  411.57  3719.3  413.04  4520.1  409.99
  4646.4  411.17  4799.7  409.73  4959.8  412.26  4969.8  411.45  4978.7  403.37
  4981.7  402.57  5000.9  403.37  5019.8  412.76  5119.9  410.65  5342.0  411.24
  5372.1  407.94  5385.2  408.24  5399.1  411.76  5760.2  411.28  5847.9  414.65
  5920.2  418.21  6035.8  426.93  6120.6  432.24  6245.1  438.71  6373.6  442.06
#Mann=11,-1,0
  2451.2    0.05       0  3219.5    0.16       0  3318.7    0.12       0
  4520.1    0.16       0  4646.4    0.12       0  4978.7    0.07       0
  5000.9    0.12       0  5920.2    0.16       0  6035.8    0.12       0
  6120.6    0.16       0  6245.1    0.05       0
Bank Sta=3387.7,5847.9
Exp/Cntr=0.3,0.1

Type RM Length L Ch R = 1,63746,1068,1068,1068
BEGIN DESCRIPTION:
CANEY CREEK 66.0
END DESCRIPTION:
XS GIS Cut Line= 4
      2901181.49      7041028.21      2900112.07      7041569.87
      2899334.29      7041639.31      2898744.03      7043194.84
#Sta/Elev= 30
  3162.4  448.15  3248.1  444.40  3393.9  428.88  3543.9  420.22  3627.4  417.15
  3767.8  416.93  4003.2  413.76  4021.6  411.83  4097.7  413.19  4664.7  410.23
  4830.1  410.66  4860.2  407.37  4910.4  409.66  4950.6  407.80  4970.7  410.15
  4980.7  409.44  4989.5  402.80  4992.6  402.00  5012.0  402.80  5030.9  410.75
  5041.6  411.24  5969.0  408.34  6140.0  413.76  6297.1  419.46  6395.4  424.82
  6442.3  426.61  6474.0  424.34  6602.8  436.95  6705.0  437.68  6805.8  439.44
#Mann=9,-1,0
  3162.4    0.05       0  3767.8    0.12       0  4097.7    0.05       0
  4664.7    0.12       0  4989.5    0.07       0  5012.0    0.12       0
  6297.1    0.16       0  6395.4    0.12       0  6705.0    0.05       0
Bank Sta=4003.2,6140
Exp/Cntr=0.3,0.1

Type RM Length L Ch R = 1,62678,1164,1164,1164
BEGIN DESCRIPTION:
CANEY CREEK 65.0
END DESCRIPTION:
XS GIS Cut Line= 3
      2899771.81      7040118.46      2899325.00      7040775.00
      2898751.11      7043020.67
#Sta/Elev= 30
  4182.2  463.33  4522.9  433.03  4651.7  423.68  4717.5  423.87  4738.4  416.21
  4746.5  422.22  4768.3  422.08  4774.4  414.64  4781.9  412.90  4789.3  410.45
  4791.1  412.58  4795.3  417.55  4810.3  421.26  4940.1  415.62  4986.7  406.36
  4988.0  400.91  4991.2  400.11  5010.7  400.91  5035.0  410.34  5560.7  407.31
  5729.8  410.85  6483.3  407.99  6592.9  412.90  6734.7  421.07  6844.5  421.77
  7020.6  432.54  7051.0  430.99  7097.1  434.43  7185.1  430.36  7294.2  436.72
#Mann=4,-1,0
  4182.2    0.16       0  4791.1    0.12       0  4988.0    0.07       0
  5010.7    0.12       0
Bank Sta=4781.9,6592.9
Exp/Cntr=0.3,0.1

Type RM Length L Ch R = 1,61514,1571,1571,1571
BEGIN DESCRIPTION:
CANEY CREEK 64.0
END DESCRIPTION:
XS GIS Cut Line= 3
      2898725.00      7039974.99      2898487.07      7040660.15
      2898500.96      7042549.00
#Sta/Elev= 30
  4032.2  467.23  4073.6  462.50  4089.0  458.79  4128.3  454.64  4203.4  446.88
  4392.1  434.70  4731.9  417.81  4792.3  418.21  4972.8  410.93  4981.0  400.84
  4984.2  400.04  5003.7  400.84  5022.4  409.04  5032.4  409.53  5062.4  407.94
  5156.6  408.34  5182.4  406.59  5222.4  409.49  5292.4  406.85  5352.4  408.63
  5462.4  406.76  5502.4  408.60  6212.4  408.34  6284.6  410.93  6472.4  425.25
  6511.7  427.58  6516.7  426.07  6552.4  426.76  6592.4  431.88  6646.4  434.69
#Mann=6,-1,0
  4032.2    0.05       0  4089.0    0.12       0  4128.3    0.16       0
  4731.9    0.12       0  4981.0    0.07       0  5003.7    0.12       0
Bank Sta=4972.8,6284.6
Exp/Cntr=0.3,0.1