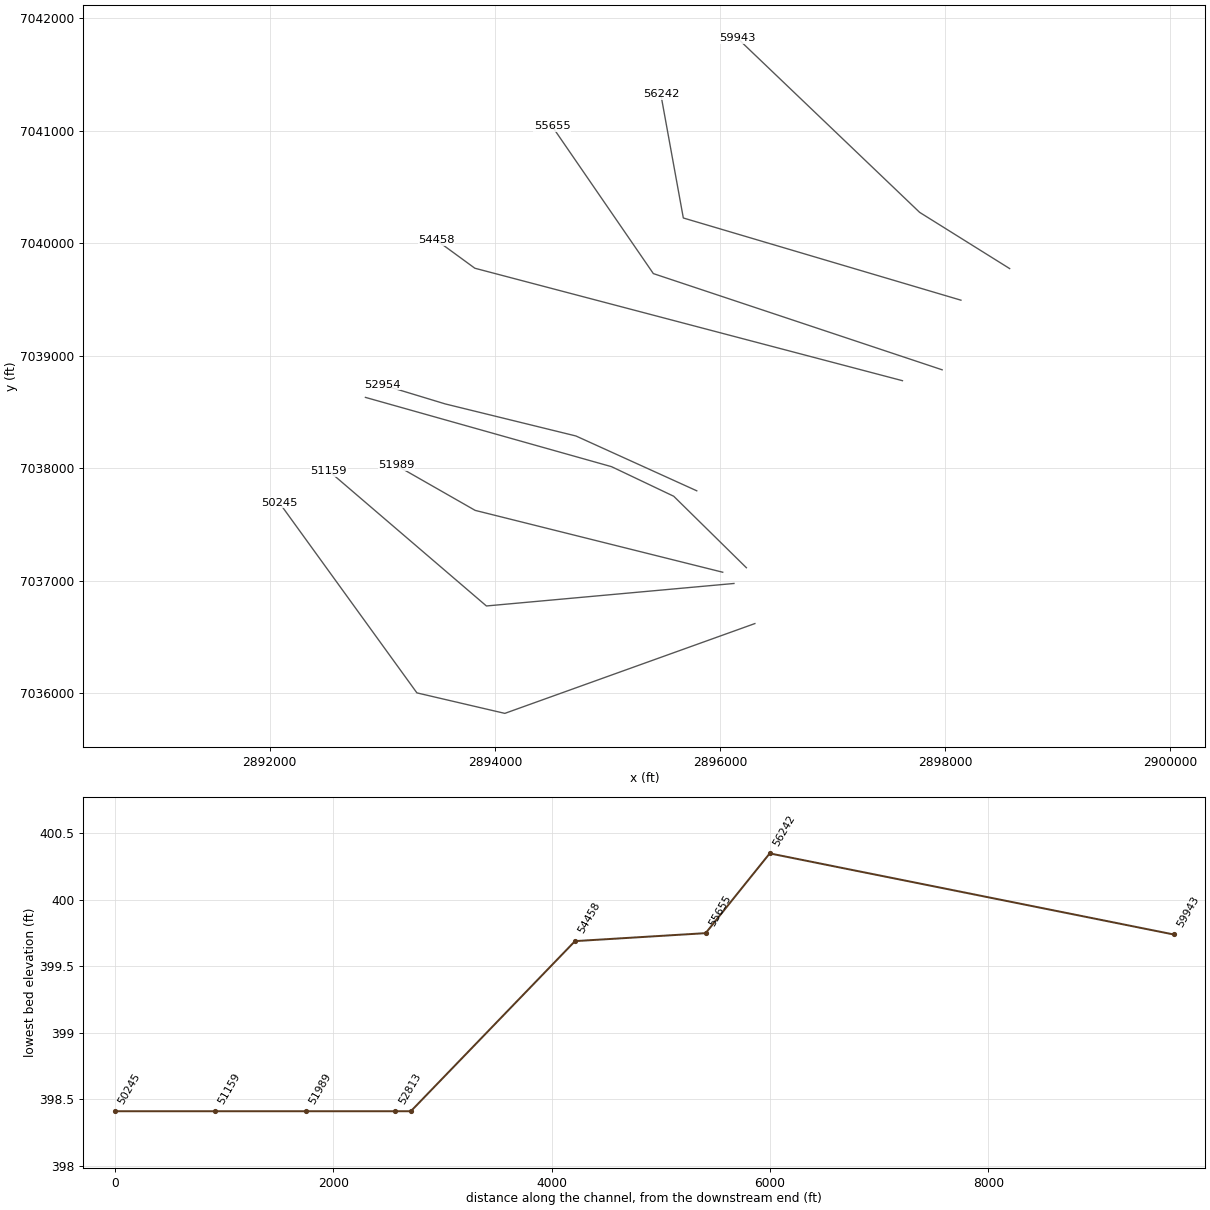
HEC-RAS study CANEY CREEK.prj: CANEY CREEK Base Level Engineering

--- CANEY CREEK.g01 (geometry) --- (continued)

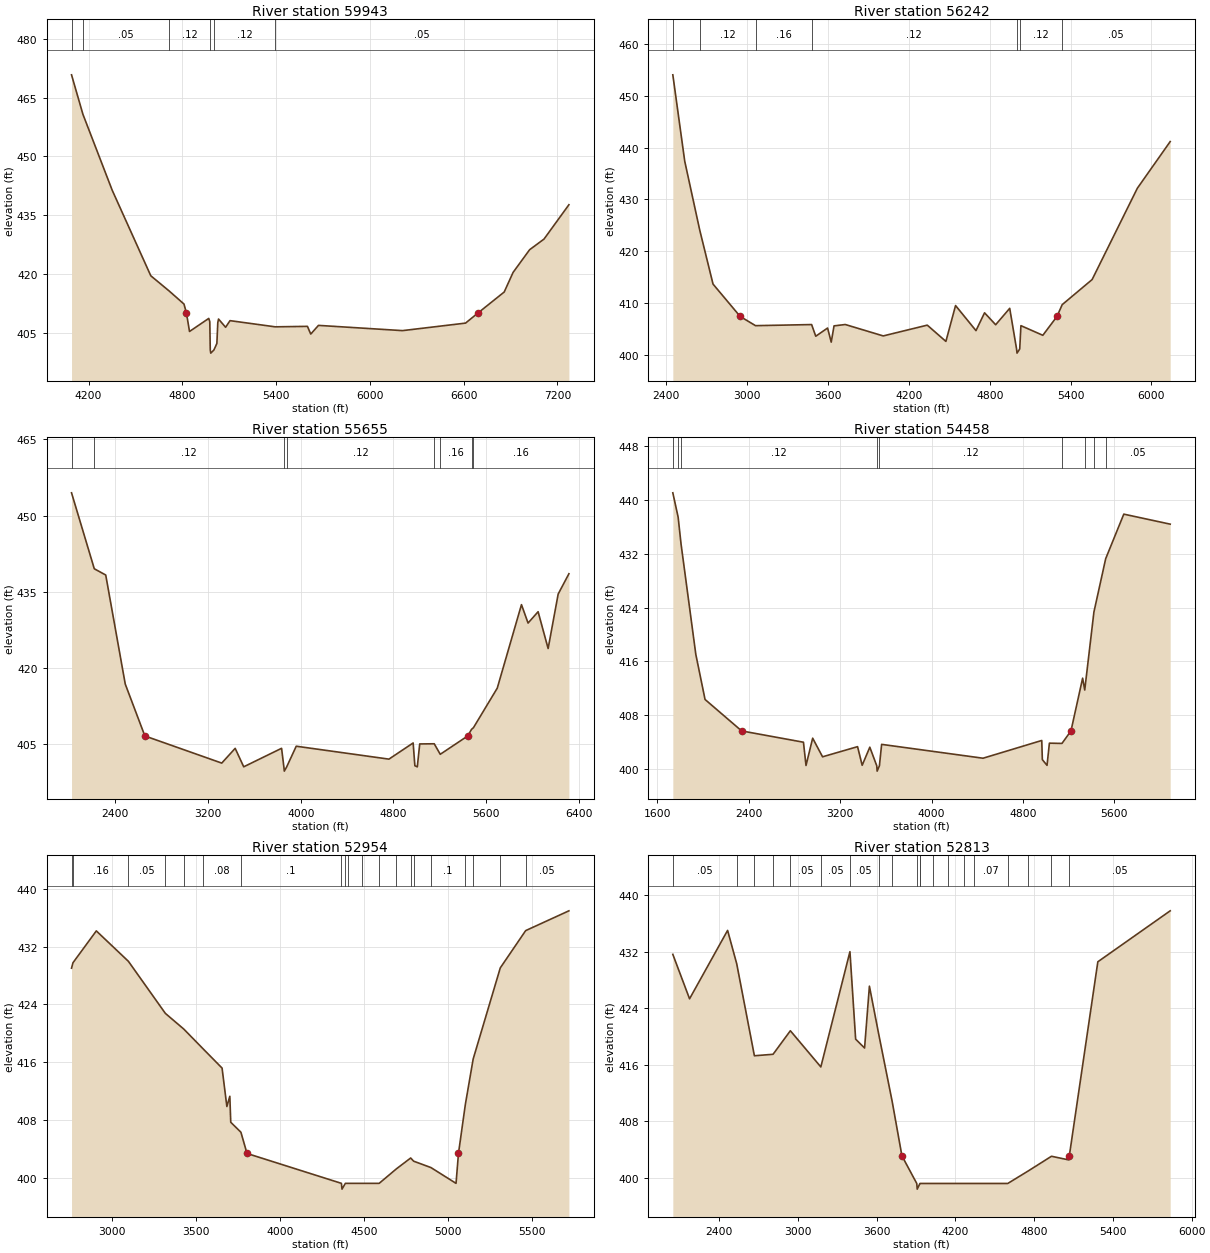
Type RM Length L Ch R = 1,59943,3701,3701,3701
BEGIN DESCRIPTION:
CANEY CREEK 63.0
END DESCRIPTION:
XS GIS Cut Line= 3
      2898575.04      7039774.98      2897775.00      7040275.00
      2896157.18      7041822.48
#Sta/Elev= 30
  4090.9  470.86  4163.7  460.78  4351.0  441.38  4598.0  419.51  4715.9  415.61
  4810.3  412.28  4826.1  410.00  4845.7  405.27  4968.9  408.61  4975.4  407.78
  4978.5  400.54  4981.8  399.74  5001.8  400.54  5020.8  402.22  5026.7  407.54
  5031.4  408.45  5076.6  406.35  5105.0  408.04  5393.9  406.46  5600.3  406.58
  5621.4  404.61  5670.9  406.83  6208.5  405.49  6611.7  407.41  6691.5  410.00
  6859.2  415.36  6915.9  420.36  7021.8  426.17  7113.7  428.88  7273.1  437.66
#Mann=6,-1,0
  4090.9    0.16       0  4163.7    0.05       0  4715.9    0.12       0
  4978.5    0.07       0  5001.8    0.12       0  5393.9    0.05       0
Bank Sta=4826.1,6691.5
Exp/Cntr=0.3,0.1

Type RM Length L Ch R = 1,56242,587,587,587
BEGIN DESCRIPTION:
CANEY CREEK 62.0
END DESCRIPTION:
XS GIS Cut Line= 3
      2898142.09      7039494.01      2895675.00      7040225.00
      2895475.01      7041324.96
#Sta/Elev= 30
  2448.3  454.05  2536.8  437.36  2647.8  424.11  2746.7  413.67  2948.0  407.43
  3061.9  405.65  3478.3  405.86  3509.1  403.61  3596.8  405.19  3623.8  402.47
  3644.7  405.61  3728.1  405.87  4009.7  403.67  4336.6  405.75  4474.8  402.61
  4546.5  409.53  4698.1  404.69  4761.6  408.13  4844.1  405.83  4948.4  408.99
  4999.3  401.15  5002.7  400.35  5022.7  401.15  5031.6  405.65  5194.2  403.79
  5299.3  407.43  5337.8  409.70  5560.1  414.55  5895.5  432.16  6139.4  441.17
#Mann=7,-1,0
  2448.3    0.16       0  2647.8    0.12       0  3061.9    0.16       0
  3478.3    0.12       0  4999.3    0.07       0  5022.7    0.12       0
  5337.8    0.05       0
Bank Sta=2948,5299.3
Exp/Cntr=0.3,0.1

Type RM Length L Ch R = 1,55655,1197,1197,1197
BEGIN DESCRIPTION:
CANEY CREEK 61.0
END DESCRIPTION:
XS GIS Cut Line= 3
      2897975.02      7038874.99      2895408.65      7039730.45
      2894509.68      7041039.50
#Sta/Elev= 30
  2022.0  454.50  2218.4  439.56  2317.2  438.33  2485.8  416.87  2655.0  406.67
  3318.6  401.33  3434.5  404.23  3508.3  400.60  3835.1  404.24  3855.0  400.55
  3858.4  399.75  3878.4  400.55  3961.6  404.65  4761.6  402.11  4970.7  405.29
  4985.6  400.81  5006.6  400.59  5027.5  405.10  5152.8  405.13  5204.7  403.06
  5441.9  406.67  5474.8  407.97  5491.4  408.30  5696.7  416.07  5905.8  432.50
  5962.7  428.88  6049.3  431.11  6135.9  423.87  6222.5  434.58  6315.2  438.58
#Mann=8,-1,0
  2022.0    0.16       0  2218.4    0.12       0  3855.0    0.07       0
  3878.4    0.12       0  5152.8    0.05       0  5204.7    0.16       0
  5474.8    0.05       0  5491.4    0.16       0
Bank Sta=2655,5441.9
Exp/Cntr=0.3,0.1

Type RM Length L Ch R = 1,54458,1504,1504,1504
BEGIN DESCRIPTION:
CANEY CREEK 60.0
END DESCRIPTION:
XS GIS Cut Line= 3
      2897622.36      7038778.16      2893822.33      7039778.17
      2893480.14      7040028.19
#Sta/Elev= 30
  1735.2  441.09  1781.6  437.48  1807.2  433.47  1936.5  417.05  2017.2  410.35
  2337.7  405.67  2878.5  403.99  2900.9  400.53  2959.2  404.59  3045.7  401.82
  3352.1  403.33  3392.4  400.56  3459.3  403.25  3520.0  400.49  3523.4  399.69
  3543.4  400.49  3562.7  403.67  4450.3  401.61  4964.2  404.25  4969.4  401.40
  5010.4  400.55  5031.1  403.85  5141.1  403.81  5219.9  405.67  5322.0  413.52
  5340.4  411.76  5420.7  423.35  5523.7  431.29  5682.3  437.92  6088.4  436.43
#Mann=9,-1,0
  1735.2    0.12       0  1781.6    0.16       0  1807.2    0.12       0
  3520.0    0.07       0  3543.4    0.12       0  5141.1    0.16       0
  5340.4    0.12       0  5420.7    0.16       0  5523.7    0.05       0
Bank Sta=2337.7,5219.9
Exp/Cntr=0.3,0.1

Type RM Length L Ch R = 1,52954,141,141,141
BEGIN DESCRIPTION:
CANEY CREEK 59.0
END DESCRIPTION:
XS GIS Cut Line= 4
      2895794.34      7037799.04      2894720.07      7038286.72
      2893559.12      7038571.60      2892999.65      7038741.61
#Sta/Elev= 30
  2758.1  429.01  2766.7  429.76  2905.6  434.17  3096.5  429.96  3316.4  422.75
  3426.3  420.57  3541.0  417.84  3654.0  415.17  3682.5  409.85  3700.1  411.27
  3705.6  407.67  3766.1  406.29  3802.3  403.35  4364.2  399.21  4367.7  398.41
  4387.7  399.21  4401.6  399.21  4486.3  399.21  4588.9  399.21  4691.5  401.22
  4776.4  402.72  4794.0  402.28  4896.6  401.40  5046.3  399.21  5060.8  403.35
  5101.7  410.13  5148.3  416.43  5309.7  429.05  5460.7  434.21  5718.0  436.95
#Mann=20,-1,0
  2758.1    0.08       0  2766.7    0.16       0  3096.5    0.05       0
  3316.4    0.08       0  3426.3    0.05       0  3541.0    0.08       0
  3766.1     0.1       0  4364.2    0.07       0  4387.7     0.1       0
  4401.6     0.1       0  4486.3    0.05       0  4588.9     0.1       0
  4691.5    0.08       0  4776.4     0.1       0  4794.0    0.05       0
  4896.6     0.1       0  5101.7    0.08       0  5148.3    0.05       0
  5309.7    0.08       0  5460.7    0.05       0
Bank Sta=3802.3,5060.8
Exp/Cntr=0.3,0.1

Type RM Length L Ch R = 1,52813,824,824,824
BEGIN DESCRIPTION:
CANEY CREEK 58.0
END DESCRIPTION:
XS GIS Cut Line= 4
      2896235.33      7037115.02      2895589.63      7037750.61
      2895037.42      7038013.44      2892849.99      7038629.74
#Sta/Elev= 30
  2046.3  431.63  2173.8  425.34  2463.7  435.02  2533.4  430.28  2667.9  417.28
  2810.1  417.49  2942.0  420.82  3174.2  415.70  3396.0  432.01  3439.4  419.63
  3507.5  418.38  3544.4  427.13  3614.3  420.43  3717.9  410.81  3792.1  403.12
  3905.2  399.21  3908.9  398.41  3929.2  399.21  3932.4  399.21  4028.6  399.21
  4146.7  399.21  4265.5  399.21  4339.4  399.21  4598.7  399.21  4753.7  400.97
  4931.8  403.06  5064.5  402.54  5067.8  403.12  5285.1  430.58  5836.5  437.79
#Mann=20,-1,0
  2046.3    0.05       0  2533.4    0.05       0  2667.9    0.16       0
  2810.1    0.08       0  2942.0    0.05       0  3174.2    0.05       0
  3396.0    0.05       0  3614.3    0.16       0  3717.9    0.12       0
  3905.2    0.07       0  3929.2    0.12       0  3932.4    0.16       0
  4028.6    0.12       0  4146.7    0.16       0  4265.5    0.08       0
  4339.4    0.07       0  4598.7    0.05       0  4753.7    0.07       0
  4931.8     0.1       0  5064.5    0.05       0
Bank Sta=3792.1,5067.8
Exp/Cntr=0.3,0.1

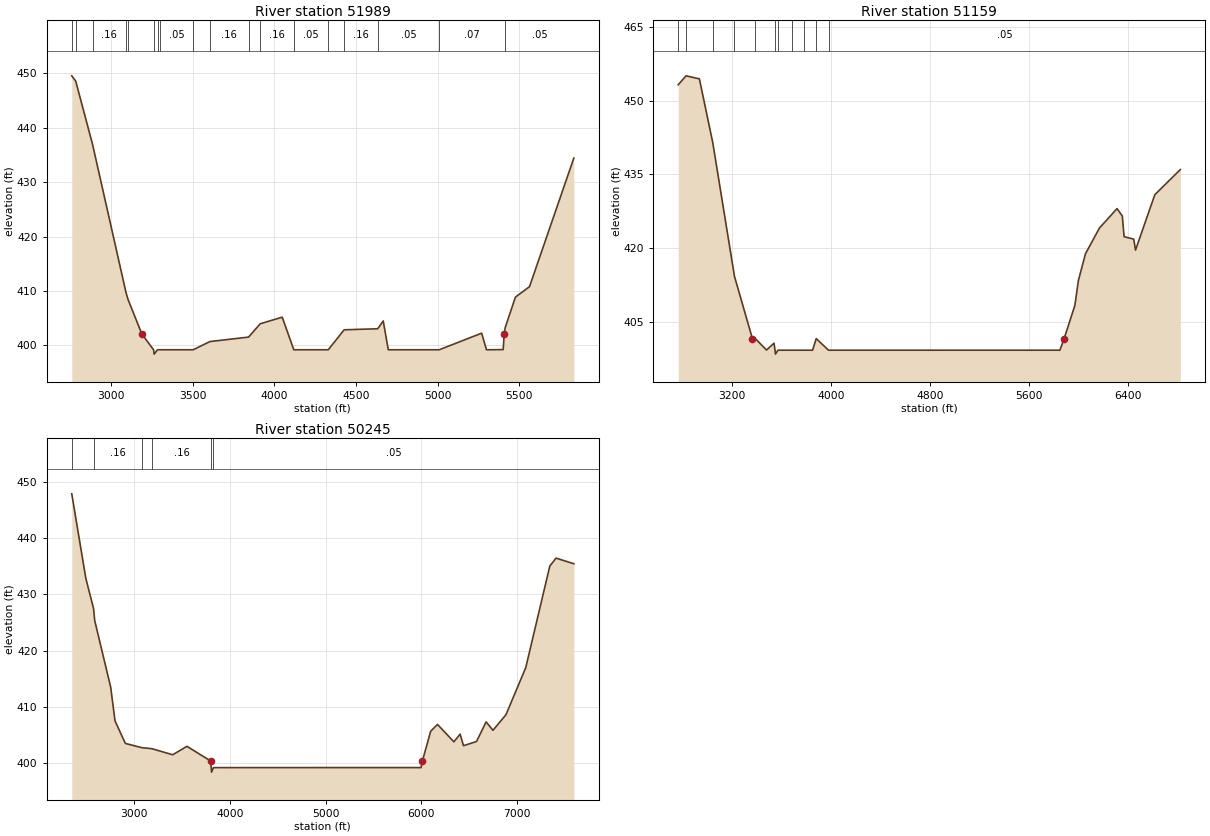
Type RM Length L Ch R = 1,51989,830,830,830
BEGIN DESCRIPTION:
CANEY CREEK 57.0
END DESCRIPTION:
XS GIS Cut Line= 3
      2896025.04      7037074.99      2893825.00      7037625.00
      2893124.98      7038025.01
#Sta/Elev= 30
  2760.4  449.55  2784.8  448.56  2887.5  436.97  3092.9  409.67  3105.1  408.44
  3189.5  402.11  3261.3  399.21  3264.9  398.41  3285.3  399.21  3297.7  399.21
  3503.7  399.21  3606.4  400.72  3842.9  401.54  3914.4  403.99  4048.9  405.20
  4119.8  399.21  4330.9  399.21  4427.9  402.88  4633.3  403.07  4667.4  404.51
  4698.3  399.21  5010.0  399.21  5270.0  402.26  5299.5  399.21  5401.7  399.24
  5408.0  402.11  5413.9  403.26  5476.6  408.88  5563.0  410.81  5834.4  434.44
#Mann=18,-1,0
  2760.4    0.05       0  2784.8    0.07       0  2887.5    0.16       0
  3092.9    0.12       0  3105.1    0.16       0  3261.3   0.033       0
  3285.3    0.16       0  3297.7    0.05       0  3503.7    0.07       0
  3606.4    0.16       0  3842.9    0.12       0  3914.4    0.16       0
  4119.8    0.05       0  4330.9    0.12       0  4427.9    0.16       0
  4633.3    0.05       0  5010.0    0.07       0  5413.9    0.05       0
Bank Sta=3189.5,5408
Exp/Cntr=0.3,0.1

Type RM Length L Ch R = 1,51159,914,914,914
BEGIN DESCRIPTION:
CANEY CREEK 56.0
END DESCRIPTION:
XS GIS Cut Line= 3
      2896124.95      7036975.00      2893925.00      7036775.00
      2892525.03      7037974.98
#Sta/Elev= 30
  2765.7  453.26  2828.5  455.08  2936.4  454.46  3044.7  441.44  3219.7  414.25
  3364.7  401.54  3383.3  401.69  3478.6  399.24  3538.8  400.64  3546.9  399.21
  3550.5  398.41  3570.9  399.21  3681.1  399.21  3780.3  399.21  3850.1  399.21
  3879.6  401.57  3978.8  399.21  5846.7  399.21  5880.4  401.54  5967.5  408.33
  5996.0  413.42  6053.1  418.85  6166.1  424.09  6307.7  428.04  6350.5  426.53
  6364.8  422.33  6442.7  421.82  6457.0  419.60  6612.8  430.87  6818.6  435.99
#Mann=11,-1,0
  2765.7    0.05       0  2828.5    0.16       0  3044.7    0.12       0
  3219.7    0.16       0  3383.3    0.05       0  3546.9   0.033       0
  3570.9    0.05       0  3681.1    0.07       0  3780.3    0.05       0
  3879.6    0.07       0  3978.8    0.05       0
Bank Sta=3364.7,5880.4
Exp/Cntr=0.3,0.1

Type RM Length L Ch R = 1,50245,0,0,0
BEGIN DESCRIPTION:
CANEY CREEK 55.0
END DESCRIPTION:
XS GIS Cut Line= 4
      2896310.87      7036618.48      2894088.63      7035819.87
      2893307.38      7036002.16      2892083.41      7037694.89
#Sta/Elev= 30
  2345.2  447.89  2491.7  432.92  2573.2  427.48  2585.2  425.36  2752.3  413.52
  2797.7  407.52  2905.9  403.51  3077.6  402.76  3182.0  402.58  3401.6  401.50
  3549.9  403.00  3797.9  400.40  3803.8  399.21  3807.4  398.41  3827.9  399.21
  5999.5  399.22  6013.5  400.40  6100.1  405.68  6171.2  406.89  6342.9  403.80
  6407.9  405.16  6443.5  403.11  6579.6  403.86  6680.2  407.34  6751.4  405.84
  6887.5  408.62  7094.8  416.99  7346.2  435.04  7411.2  436.46  7597.7  435.46
#Mann=6,-1,0
  2345.2    0.05       0  2573.2    0.16       0  3077.6    0.12       0
  3182.0    0.16       0  3803.8   0.033       0  3827.9    0.05       0
Bank Sta=3797.9,6013.5
Exp/Cntr=0.3,0.1

Chan Stop Cuts=-1