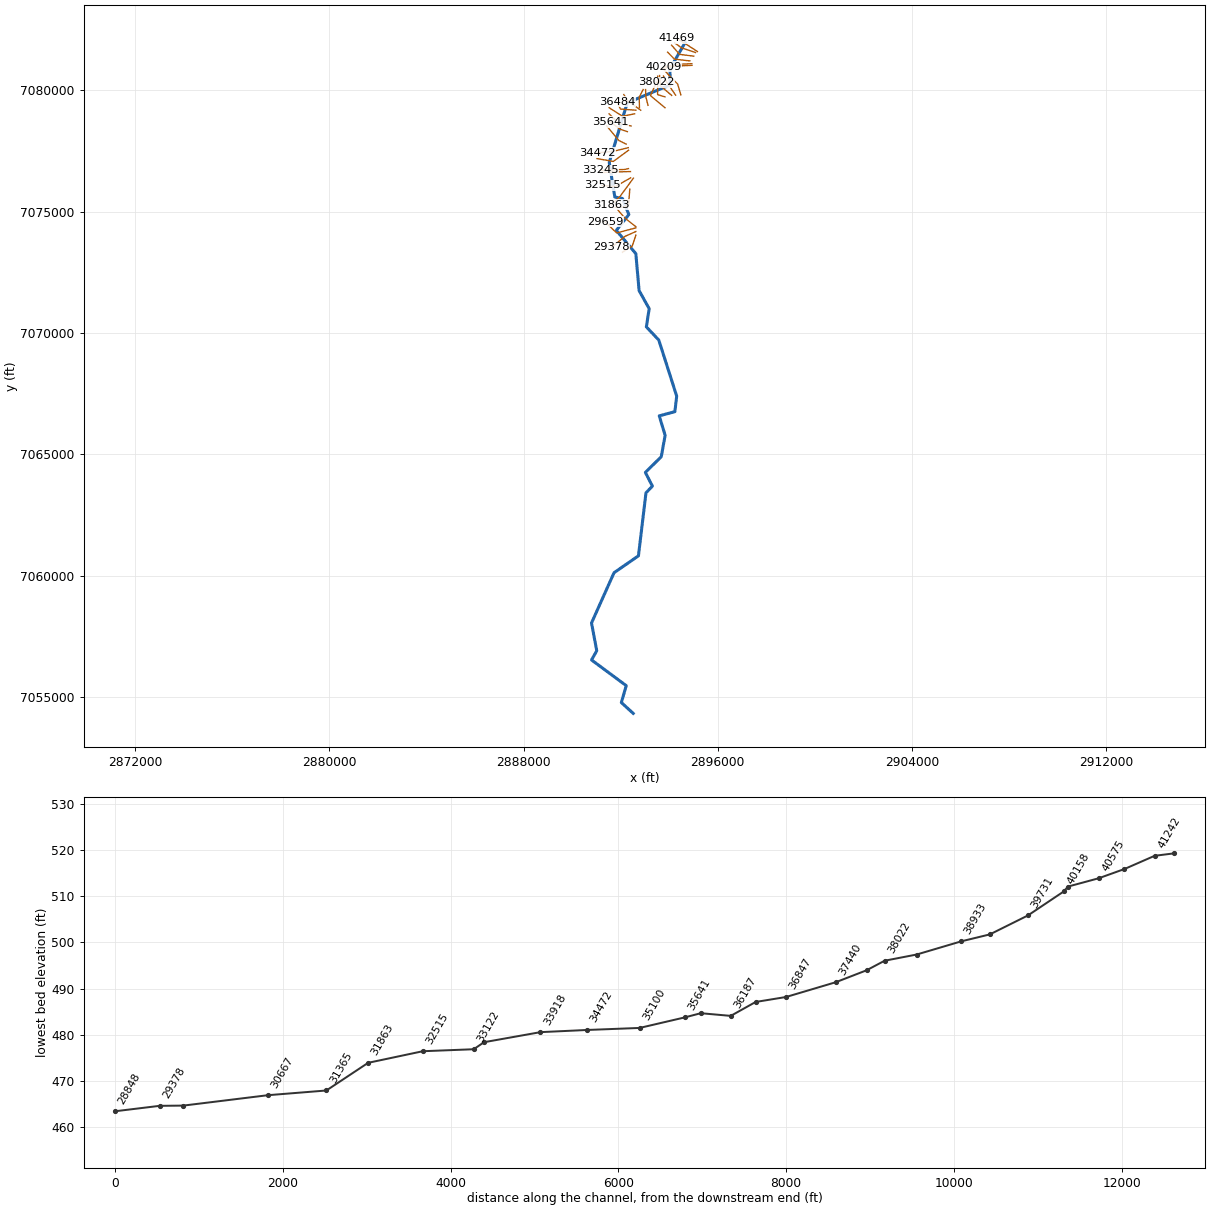
--- CARROLL CREEK.prj (project) ---

Proj Title=CARROLL CREEK Base Level Engineering
Current Plan=p01
Default Exp/Contr=0.3,0.1
English Units
Geom File=g01
Flow File=f01
Plan File=p01
BEGIN DESCRIPTION:
CARROLL CREEK
END DESCRIPTION:

--- CARROLL CREEK.p01 (plan) ---

Plan Title=Multiple Run
Short Identifier=Multiple
Geom File=g01
Flow File=f01
Subcritical Flow
K Sum by GR= 0
Std Step Tol= 0.01
Critical Tol= 0.01
Num of Std Step Trials= 20
Max Error Tol= 0.3
Flow Tol Ratio= 0.001
Split Flow NTrial= 30
Split Flow Tol= 0.02
Split Flow Ratio= 0.02
Log Output Level= 0
Friction Slope Method= 1
Unsteady Friction Slope Method= 2
Unsteady Bridges Friction Slope Method= 1
Parabolic Critical Depth
Global Vel Dist=  1 , 1 , 1
Global Log Level= 0
CheckData=True
Encroach Param= -1, 0, 0, 0
BEGIN DESCRIPTION:
Multiple Run
END DESCRIPTION:

--- CARROLL CREEK.f01 (steady flow) ---

Flow Title=Multiple
Number of Profiles=7
Profile Names=10-year,25-year,50-year,1pct_min,100-year,1pct_plu,500-year
River Rch & RM= CARROLL CREEK,Reach-1,41469
     159     191     214     120     239     476     294
River Rch & RM= CARROLL CREEK,Reach-1,38404
     448     580     684     401     800    1597    1090
River Rch & RM= CARROLL CREEK,Reach-1,36847
     747     998    1201     717    1430    2854    2022
River Rch & RM= CARROLL CREEK,Reach-1,34472
    1509    2093    2582    1574    3141    6268    4644
River Rch & RM= CARROLL CREEK,Reach-1,33245
    1581    2197    2712    1656    3304    6592    4895
River Rch & RM= CARROLL CREEK,Reach-1,30667
    1853    2595    3221    1976    3943    7867    5898
River Rch & RM= CARROLL CREEK,Reach-1,28848
    2378    3358    4189    2580    5148   10271    7764
River Rch & RM= CARROLL CREEK,Reach-1,21903
    2449    3459    4316    2658    5303   10580    7997
River Rch & RM= CARROLL CREEK,Reach-1,18986
    2812    3986    4987    3077    6139   12249    9295
River Rch & RM= CARROLL CREEK,Reach-1,12781
    3137    4463    5597    3461    6906   13779   10504
River Rch & RM= CARROLL CREEK,Reach-1,6147
    3196    4538    5683    3509    7001   13969   10618
Boundary for River Rch & Prof#=CARROLL CREEK,Reach-1,1
Up Type=0
Dn Type=3
Dn Slope=0.005
Boundary for River Rch & Prof#=CARROLL CREEK,Reach-1,2
Up Type=0
Dn Type=3
Dn Slope=0.005
Boundary for River Rch & Prof#=CARROLL CREEK,Reach-1,3
Up Type=0
Dn Type=3
Dn Slope=0.005
Boundary for River Rch & Prof#=CARROLL CREEK,Reach-1,4
Up Type=0
Dn Type=3
Dn Slope=0.005
Boundary for River Rch & Prof#=CARROLL CREEK,Reach-1,5
Up Type=0
Dn Type=3
Dn Slope=0.005
Boundary for River Rch & Prof#=CARROLL CREEK,Reach-1,6
Up Type=0
Dn Type=3
Dn Slope=0.005
Boundary for River Rch & Prof#=CARROLL CREEK,Reach-1,7
Up Type=0
Dn Type=3
Dn Slope=0.005

--- CARROLL CREEK.g01 (geometry) ---

Geom Title=Existing Conditions

River Reach=CARROLL CREEK,Reach-1
Reach XY= 30
      2894650.06      7081954.62      2894029.75      7080871.46
      2894039.26      7080218.04      2892269.30      7079479.32
      2891528.44      7077018.81      2891757.99      7075596.13
      2892072.11      7075537.31      2892334.79      7074875.75
      2891819.37      7074222.70      2892623.41      7073264.69
      2892758.41      7071741.88      2893173.93      7070994.94
      2893057.72      7070246.30      2893570.00      7069703.34
      2894307.50      7067392.83      2894232.31      7066751.86
      2893589.06      7066579.54      2893830.61      7065777.87
      2893671.55      7064895.55      2893017.59      7064249.12
      2893306.07      7063683.46      2893041.82      7063408.56
      2892731.44      7060812.44      2891725.26      7060116.20
      2890797.95      7058045.21      2891013.41      7056900.71
      2890799.07      7056522.15      2892228.15      7055462.95
      2892027.38      7054766.26      2892515.59      7054320.71

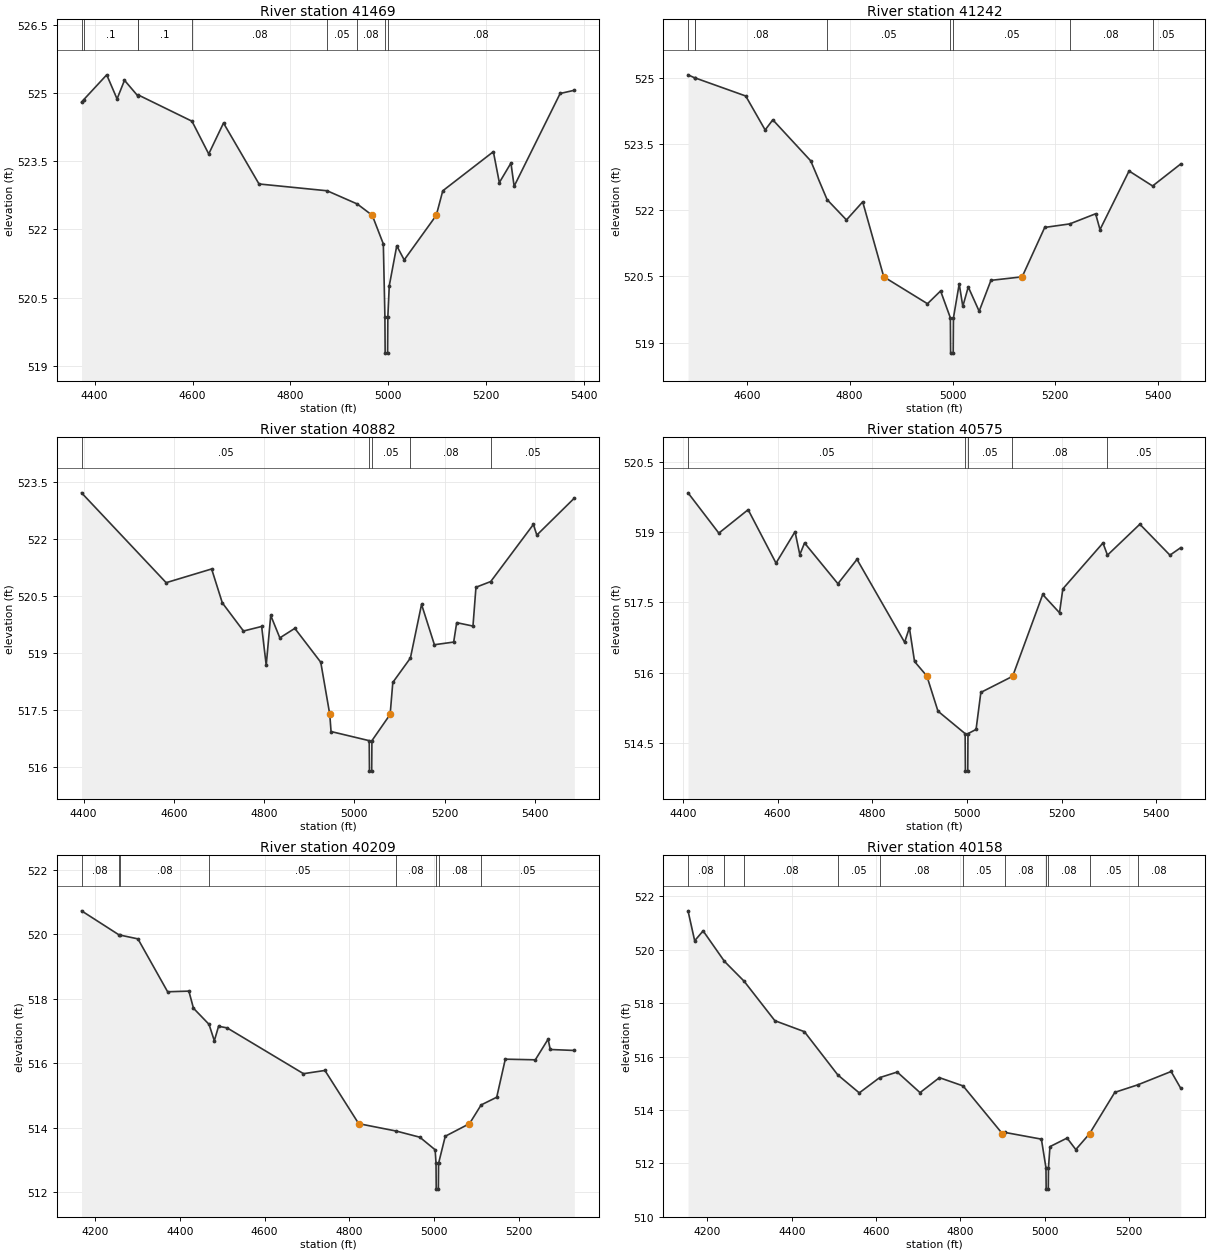
Type RM Length L Ch R = 1,41469,227,227,227
BEGIN DESCRIPTION:
CARROLL CREEK 63.0
END DESCRIPTION:
XS GIS Cut Line= 3
      2895162.15      7081591.32      2894729.83      7081872.58
      2894315.77      7082135.61
#Sta/Elev= 30
  4373.3  524.80  4377.4  524.85  4424.7  525.40  4445.8  524.87  4461.0  525.28
  4487.9  524.94  4488.6  524.96  4598.8  524.38  4633.0  523.66  4663.2  524.34
  4735.7  523.00  4874.9  522.85  4936.3  522.56  4967.0  522.31  4989.6  521.68
  4992.8  520.08  4993.3  519.28  4998.3  519.28  4998.8  520.08  5001.7  520.76
  5017.0  521.64  5032.2  521.33  5097.7  522.31  5111.0  522.85  5214.3  523.71
  5226.5  523.03  5250.2  523.46  5256.7  522.95  5350.7  524.99  5379.6  525.06
#Mann=9,-1,0
  4373.3    0.08       0  4377.4     0.1       0  4487.9    0.08       0
  4488.6     0.1       0  4598.8    0.08       0  4874.9    0.05       0
  4936.3    0.08       0  4992.8    0.07       0  4998.8    0.08       0
Bank Sta=4967,5097.7
Exp/Cntr=0.3,0.1

Type RM Length L Ch R = 1,41242,360,360,360
BEGIN DESCRIPTION:
Mapping XS e91160f7
END DESCRIPTION:
XS GIS Cut Line= 4
      2895081.40      7081552.27      2894659.52      7081692.90
      2894498.06      7081750.19      2894220.24      7081950.12
#Sta/Elev= 30
  4485.6  525.07  4498.9  525.00  4499.4  525.00  4597.8  524.59  4635.6  523.82
  4650.5  524.05  4724.2  523.12  4756.1  522.24  4793.7  521.78  4825.3  522.19
  4866.3  520.49  4951.3  519.88  4976.8  520.17  4995.8  519.56  4996.3  518.76
  5001.3  518.76  5001.8  519.56  5013.0  520.33  5020.0  519.82  5030.6  520.26
  5051.8  519.71  5074.7  520.41  5135.4  520.49  5179.3  521.61  5228.0  521.69
  5278.3  521.92  5286.8  521.56  5343.3  522.89  5389.1  522.55  5443.9  523.05
#Mann=8,-1,0
  4485.6    0.08       0  4498.9     0.1       0  4499.4    0.08       0
  4756.1    0.05       0  4995.8    0.03       0  5001.8    0.05       0
  5228.0    0.08       0  5389.1    0.05       0
Bank Sta=4866.3,5135.4
Exp/Cntr=0.3,0.1

Type RM Length L Ch R = 1,40882,307,307,307
BEGIN DESCRIPTION:
CARROLL CREEK 62.0
END DESCRIPTION:
XS GIS Cut Line= 3
      2895011.06      7081401.23      2894425.00      7081475.00
      2894096.99      7081854.39
#Sta/Elev= 30
  4395.5  523.21  4583.0  520.85  4683.8  521.21  4707.5  520.32  4754.4  519.58
  4794.7  519.70  4804.8  518.68  4814.8  519.99  4835.0  519.40  4868.2  519.65
  4925.7  518.76  4945.7  517.39  4948.5  516.94  5033.1  516.70  5033.6  515.90
  5038.6  515.90  5039.1  516.70  5079.5  517.39  5085.4  518.23  5124.4  518.87
  5149.1  520.28  5177.6  519.22  5220.3  519.29  5227.0  519.80  5263.1  519.71
  5269.7  520.73  5302.5  520.88  5397.0  522.38  5404.6  522.10  5487.7  523.07
#Mann=5,-1,0
  4395.5    0.05       0  5033.1    0.03       0  5039.1    0.05       0
  5124.4    0.08       0  5302.5    0.05       0
Bank Sta=4945.7,5079.5
Exp/Cntr=0.3,0.1

Type RM Length L Ch R = 1,40575,366,366,366
BEGIN DESCRIPTION:
CARROLL CREEK 61.0
END DESCRIPTION:
XS GIS Cut Line= 3
      2894849.64      7081205.91      2894214.21      7081278.83
      2893932.92      7081565.33
#Sta/Elev= 30
  4410.9  519.84  4476.0  518.98  4537.9  519.48  4596.8  518.34  4637.0  519.01
  4647.1  518.52  4657.1  518.77  4727.6  517.90  4767.9  518.42  4868.5  516.65
  4878.6  516.96  4889.5  516.24  4915.5  515.93  4939.0  515.18  4996.4  514.70
  4996.9  513.90  5001.9  513.90  5002.4  514.70  5019.5  514.79  5029.6  515.58
  5095.9  515.92  5097.0  515.93  5160.3  517.67  5195.8  517.28  5202.8  517.79
  5287.6  518.77  5297.1  518.51  5365.5  519.17  5429.1  518.51  5452.0  518.67
#Mann=5,-1,0
  4410.9    0.05       0  4996.4    0.03       0  5002.4    0.05       0
  5095.9    0.08       0  5297.1    0.05       0
Bank Sta=4915.5,5097
Exp/Cntr=0.3,0.1

Type RM Length L Ch R = 1,40209,51,51,51
BEGIN DESCRIPTION:
Mapping XS c70f6cd6
END DESCRIPTION:
XS GIS Cut Line= 4
      2894927.73      7081091.33      2894391.29      7081067.90
      2894138.69      7081026.23      2893774.13      7080971.55
#Sta/Elev= 30
  4168.5  520.73  4256.1  519.99  4258.5  519.98  4301.4  519.86  4371.4  518.22
  4421.5  518.24  4432.3  517.71  4469.0  517.21  4481.5  516.70  4491.5  517.15
  4511.6  517.10  4691.7  515.68  4742.2  515.78  4821.8  514.13  4910.6  513.90
  4965.9  513.71  5002.0  513.32  5004.1  512.90  5004.6  512.10  5009.6  512.10
  5010.1  512.90  5025.9  513.74  5083.0  514.13  5110.4  514.71  5147.2  514.95
  5167.4  516.13  5238.2  516.11  5268.3  516.75  5273.4  516.43  5330.1  516.40
#Mann=8,-1,0
  4168.5    0.08       0  4256.1    0.05       0  4258.5    0.08       0
  4469.0    0.05       0  4910.6    0.08       0  5004.1    0.07       0
  5010.1    0.08       0  5110.4    0.05       0
Bank Sta=4821.8,5083
Exp/Cntr=0.3,0.1

Type RM Length L Ch R = 1,40158,427,427,427
BEGIN DESCRIPTION:
CARROLL CREEK 60.0
END DESCRIPTION:
XS GIS Cut Line= 4
      2894940.80      7081022.76      2894228.97      7080993.24
      2894055.15      7080963.57      2893782.77      7080898.62
#Sta/Elev= 30
  4154.1  521.45  4169.9  520.33  4189.9  520.70  4240.5  519.56  4287.0  518.82
  4360.1  517.34  4430.1  516.93  4509.5  515.31  4560.3  514.64  4608.5  515.21
  4650.3  515.42  4704.4  514.65  4750.4  515.21  4806.6  514.90  4899.4  513.12
  4906.1  513.16  4992.3  512.91  5003.1  511.84  5003.6  511.04  5008.6  511.04
  5009.1  511.84  5012.6  512.63  5053.2  512.95  5073.9  512.52  5106.9  513.12
  5107.1  513.13  5166.4  514.66  5220.7  514.94  5300.0  515.44  5322.9  514.81
#Mann=11,-1,0
  4154.1    0.08       0  4240.5    0.05       0  4287.0    0.08       0
  4509.5    0.05       0  4608.5    0.08       0  4806.6    0.05       0
  4906.1    0.08       0  5003.1    0.07       0  5009.1    0.08       0
  5107.1    0.05       0  5220.7    0.08       0
Bank Sta=4899.4,5106.9
Exp/Cntr=0.3,0.1

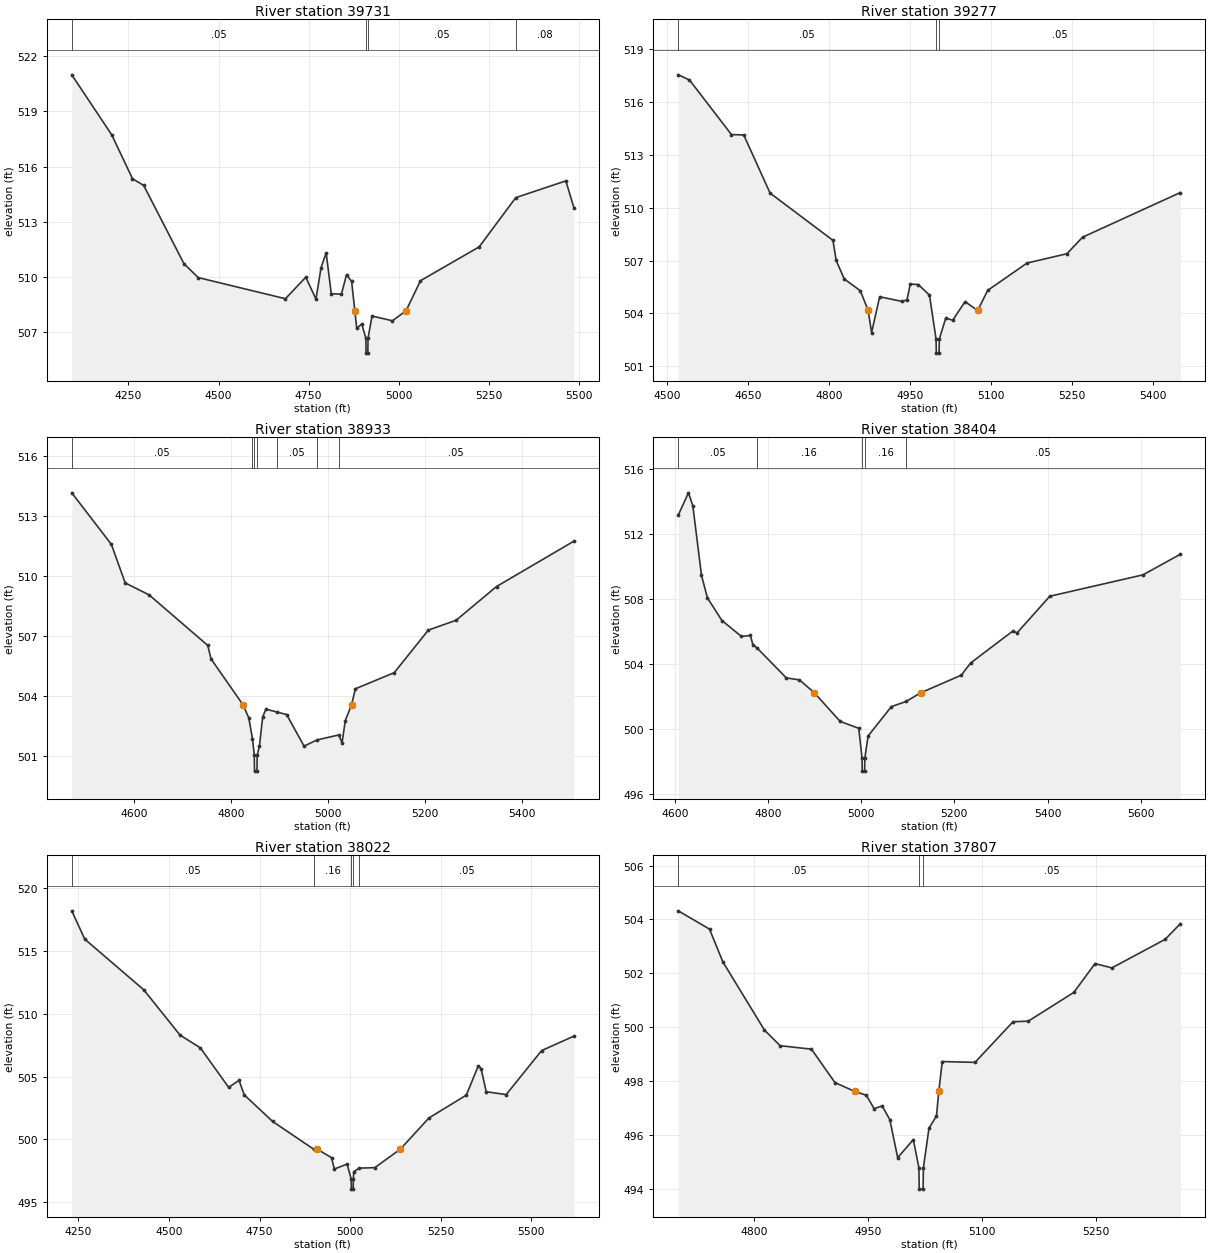
Type RM Length L Ch R = 1,39731,454,454,454
BEGIN DESCRIPTION:
CARROLL CREEK 59.0
END DESCRIPTION:
XS GIS Cut Line= 4
      2894478.31      7079808.57      2894344.95      7080255.05
      2894025.00      7080575.00      2893707.26      7080928.82
#Sta/Elev= 30
  4092.6  520.99  4203.7  517.72  4261.2  515.34  4292.4  514.97  4404.2  510.71
  4443.7  509.96  4685.8  508.81  4742.3  509.98  4770.6  508.79  4784.8  510.50
  4798.9  511.31  4813.1  509.08  4841.3  509.06  4855.5  510.12  4869.6  509.75
  4878.5  508.15  4883.8  507.20  4897.9  507.44  4909.1  506.65  4909.6  505.85
  4914.6  505.85  4915.1  506.65  4926.2  507.87  4982.8  507.61  5020.7  508.15
  5060.8  509.79  5223.7  511.63  5325.4  514.31  5464.4  515.22  5486.6  513.77
#Mann=4,-1,0
  4092.6    0.05       0  4909.1    0.03       0  4915.1    0.05       0
  5325.4    0.08       0
Bank Sta=4878.5,5020.7
Exp/Cntr=0.3,0.1

Type RM Length L Ch R = 1,39277,344,344,344
BEGIN DESCRIPTION:
CARROLL CREEK 58.0
END DESCRIPTION:
XS GIS Cut Line= 3
      2894263.04      7079794.68      2893912.84      7080306.92
      2893763.06      7080579.35
#Sta/Elev= 30
  4520.0  517.54  4540.8  517.25  4618.7  514.15  4641.5  514.13  4690.4  510.83
  4807.0  508.15  4813.0  507.01  4827.9  505.96  4857.8  505.29  4872.3  504.17
  4878.7  502.92  4893.7  504.95  4935.6  504.68  4944.4  504.78  4950.5  505.67
  4965.4  505.64  4986.1  505.04  4998.3  502.55  4998.8  501.75  5003.8  501.75
  5004.3  502.55  5016.2  503.73  5029.2  503.62  5052.1  504.67  5075.5  504.17
  5094.1  505.31  5167.0  506.86  5241.0  507.39  5270.2  508.33  5451.4  510.86
#Mann=3,-1,0
  4520.0    0.05       0  4998.3   0.035       0  5004.3    0.05       0
Bank Sta=4872.3,5075.5
Exp/Cntr=0.3,0.1

Type RM Length L Ch R = 1,38933,529,529,529
BEGIN DESCRIPTION:
CARROLL CREEK 57.0
END DESCRIPTION:
XS GIS Cut Line= 3
      2894099.30      7079784.73      2893635.43      7080180.15
      2893599.84      7080603.72
#Sta/Elev= 30
  4471.4  514.16  4553.0  511.58  4581.5  509.65  4630.9  509.05  4751.7  506.52
  4758.3  505.85  4824.3  503.55  4836.2  502.89  4843.7  501.86  4847.5  501.03
  4848.0  500.23  4853.0  500.23  4853.5  501.03  4858.1  501.48  4864.8  502.94
  4871.4  503.33  4894.0  503.19  4914.2  503.06  4950.1  501.48  4976.5  501.79
  5021.4  502.04  5028.4  501.65  5035.0  502.76  5048.0  503.55  5055.8  504.35
  5136.0  505.16  5206.2  507.29  5263.3  507.78  5346.7  509.47  5506.0  511.74
#Mann=7,-1,0
  4471.4    0.05       0  4843.7     0.1       0  4847.5    0.07       0
  4853.5     0.1       0  4894.0    0.05       0  4976.5     0.1       0
  5021.4    0.05       0
Bank Sta=4824.3,5048
Exp/Cntr=0.3,0.1

Type RM Length L Ch R = 1,38404,382,382,382
BEGIN DESCRIPTION:
CARROLL CREEK 56.0
END DESCRIPTION:
XS GIS Cut Line= 3
      2893825.00      7079725.00      2893520.71      7079814.88
      2893525.00      7080574.98
#Sta/Elev= 30
  4607.6  513.18  4629.5  514.56  4638.9  513.77  4657.5  509.47  4670.2  508.08
  4701.4  506.68  4743.2  505.70  4762.6  505.76  4767.8  505.18  4776.0  505.01
  4839.6  503.14  4867.7  503.02  4899.8  502.22  4955.0  500.46  4995.0  500.03
  5002.0  498.19  5002.5  497.39  5007.5  497.39  5008.0  498.19  5015.0  499.56
  5065.0  501.37  5096.8  501.69  5127.7  502.22  5215.0  503.31  5235.0  504.06
  5325.0  506.02  5335.0  505.93  5405.0  508.18  5605.0  509.50  5685.0  510.77
#Mann=5,-1,0
  4607.6    0.05       0  4776.0    0.16       0  5002.0    0.07       0
  5008.0    0.16       0  5096.8    0.05       0
Bank Sta=4899.8,5127.7
Exp/Cntr=0.3,0.1

Type RM Length L Ch R = 1,38022,215,215,215
BEGIN DESCRIPTION:
CARROLL CREEK 55.0
END DESCRIPTION:
XS GIS Cut Line= 3
      2893825.01      7079274.99      2893225.00      7079775.00
      2893475.00      7080325.01
#Sta/Elev= 30
  4231.9  518.19  4267.7  515.94  4430.4  511.91  4530.7  508.30  4586.6  507.29
  4664.7  504.15  4693.4  504.70  4707.7  503.55  4785.8  501.44  4899.2  499.23
  4909.5  499.22  4948.5  498.55  4956.3  497.65  4991.5  498.04  5002.8  496.85
  5003.3  496.05  5008.3  496.05  5008.8  496.85  5009.7  497.43  5024.8  497.72
  5067.9  497.76  5138.1  499.22  5217.2  501.71  5320.5  503.53  5353.5  505.86
  5361.1  505.64  5375.4  503.80  5430.4  503.57  5528.1  507.07  5617.1  508.22
#Mann=5,-1,0
  4231.9    0.05       0  4899.2    0.16       0  5002.8    0.07       0
  5008.8    0.16       0  5024.8    0.05       0
Bank Sta=4909.5,5138.1
Exp/Cntr=0.3,0.1

Type RM Length L Ch R = 1,37807,367,367,367
BEGIN DESCRIPTION:
CARROLL CREEK 54.0
END DESCRIPTION:
XS GIS Cut Line= 3
      2893124.99      7079375.04      2893039.30      7079711.93
      2893025.00      7080024.99
#Sta/Elev= 30
  4700.0  504.32  4741.2  503.64  4758.8  502.42  4813.5  499.89  4834.1  499.31
  4875.4  499.18  4906.3  497.94  4932.3  497.61  4947.6  497.47  4957.9  496.97
  4968.5  497.07  4978.6  496.56  4988.9  495.15  5009.5  495.82  5016.8  494.78
  5017.3  493.98  5022.3  493.98  5022.8  494.78  5030.1  496.24  5040.0  496.70
  5043.0  497.61  5047.6  498.72  5090.7  498.69  5140.8  500.20  5160.8  500.22
  5220.9  501.29  5248.7  502.36  5270.9  502.20  5341.0  503.26  5361.0  503.84
#Mann=3,-1,0
  4700.0    0.05       0  5016.8    0.03       0  5022.8    0.05       0
Bank Sta=4932.3,5043
Exp/Cntr=0.3,0.1

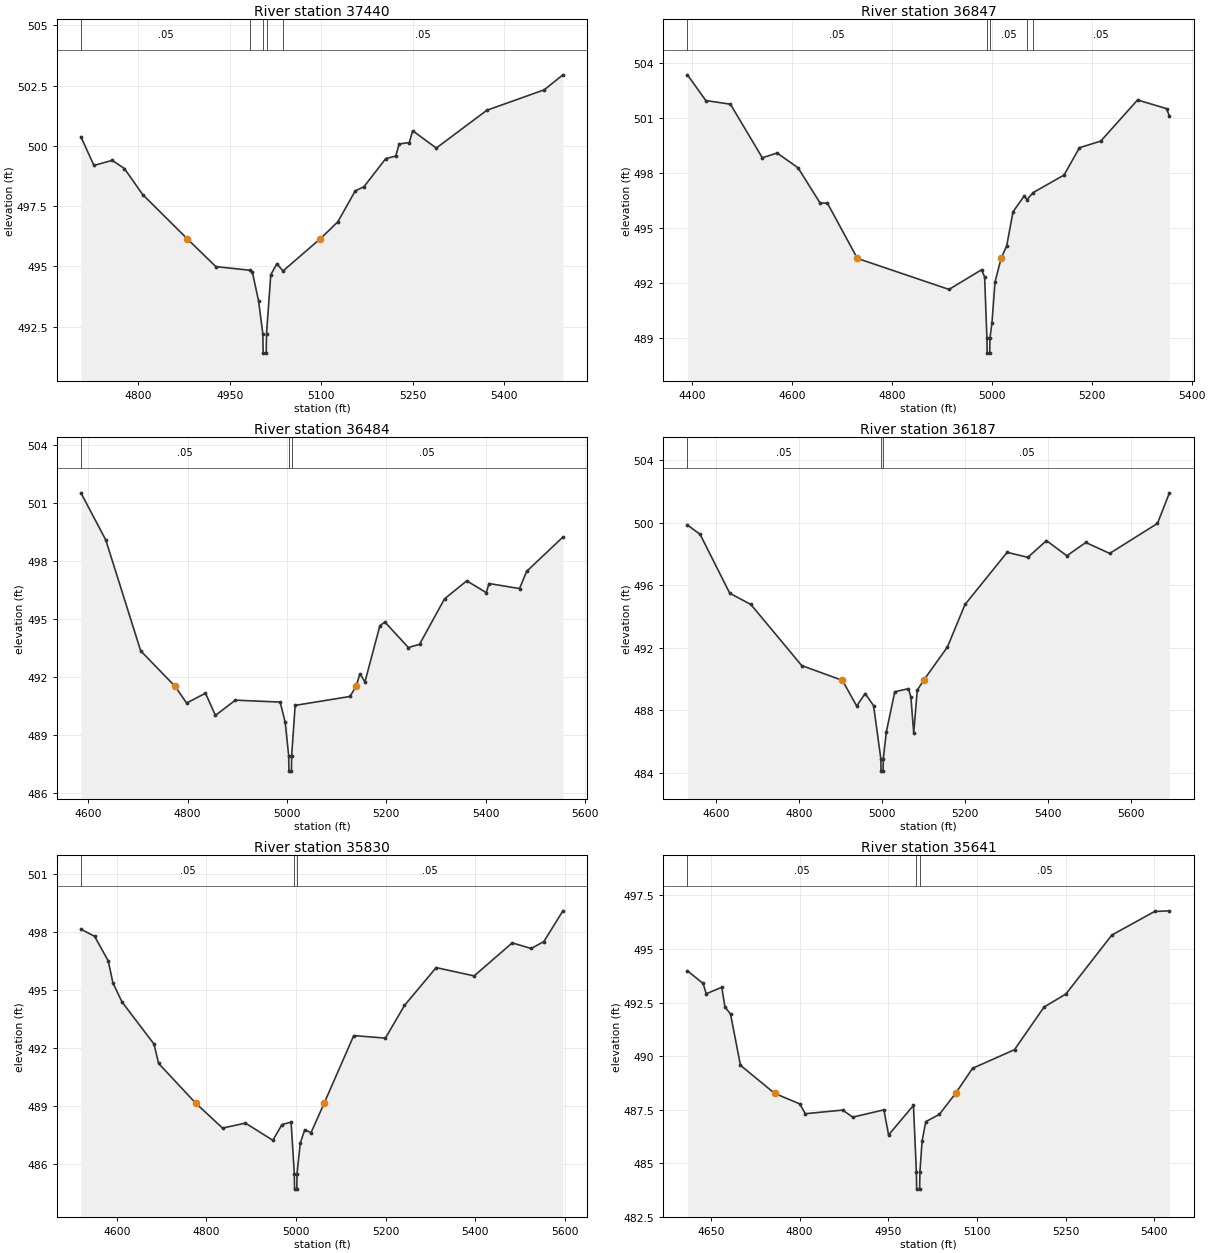
Type RM Length L Ch R = 1,37440,593,593,593
BEGIN DESCRIPTION:
CARROLL CREEK 53.0
END DESCRIPTION:
XS GIS Cut Line= 3
      2892773.24      7079273.63      2892763.20      7079711.08
      2892924.98      7080024.97
#Sta/Elev= 30
  4705.5  500.38  4726.9  499.19  4756.9  499.40  4776.9  499.06  4806.9  497.98
  4879.8  496.15  4926.9  494.99  4982.9  494.84  4986.9  494.75  4996.9  493.58
  5004.0  492.20  5004.5  491.40  5009.5  491.40  5010.0  492.20  5017.0  494.65
  5027.0  495.11  5037.1  494.81  5098.4  496.15  5127.0  496.85  5155.5  498.13
  5170.0  498.31  5205.5  499.47  5222.0  499.58  5227.6  500.08  5244.2  500.14
  5249.8  500.63  5288.5  499.91  5371.5  501.48  5465.8  502.33  5496.2  502.95
#Mann=5,-1,0
  4705.5    0.05       0  4982.9    0.16       0  5004.0    0.07       0
  5010.0    0.16       0  5037.1    0.05       0
Bank Sta=4879.8,5098.4
Exp/Cntr=0.3,0.1

Type RM Length L Ch R = 1,36847,363,363,363
BEGIN DESCRIPTION:
CARROLL CREEK 52.0
END DESCRIPTION:
XS GIS Cut Line= 3
      2892824.97      7079175.02      2892287.34      7079559.43
      2892129.25      7079818.60
#Sta/Elev= 30
  4391.0  503.36  4427.8  501.96  4477.0  501.76  4540.9  498.84  4570.4  499.10
  4612.2  498.30  4656.4  496.38  4671.1  496.37  4731.1  493.36  4914.4  491.67
  4979.5  492.74  4985.7  492.35  4990.3  489.00  4990.8  488.20  4995.8  488.20
  4996.3  489.00  5000.4  489.86  5006.5  492.08  5018.7  493.36  5029.9  494.05
  5042.5  495.90  5065.2  496.77  5070.4  496.56  5082.5  496.94  5144.6  497.90
  5175.5  499.39  5218.1  499.75  5291.7  501.99  5349.7  501.52  5355.5  501.11
#Mann=5,-1,0
  4391.0    0.05       0  4990.3    0.03       0  4996.3    0.05       0
  5070.4    0.16       0  5082.5    0.05       0
Bank Sta=4731.1,5018.7
Exp/Cntr=0.3,0.1

Type RM Length L Ch R = 1,36484,297,297,297
BEGIN DESCRIPTION:
CARROLL CREEK 51.0
END DESCRIPTION:
XS GIS Cut Line= 3
      2892625.02      7079175.00      2891992.03      7079220.37
      2891842.13      7079520.17
#Sta/Elev= 30
  4585.4  501.51  4635.5  499.07  4705.7  493.34  4775.1  491.50  4798.1  490.64
  4836.1  491.15  4856.1  490.00  4896.2  490.79  4986.4  490.69  4996.5  489.64
  5003.5  487.92  5004.0  487.12  5009.0  487.12  5009.5  487.92  5016.5  490.52
  5126.8  490.98  5139.1  491.50  5146.9  492.16  5156.9  491.73  5187.0  494.64
  5197.0  494.83  5244.4  493.51  5266.8  493.68  5317.1  496.03  5361.8  496.96
  5401.0  496.35  5406.5  496.82  5468.0  496.56  5482.3  497.45  5555.2  499.22
#Mann=3,-1,0
  4585.4    0.05       0  5003.5    0.03       0  5009.5    0.05       0
Bank Sta=4775.1,5139.1
Exp/Cntr=0.3,0.1

Type RM Length L Ch R = 1,36187,357,357,357
BEGIN DESCRIPTION:
CARROLL CREEK 50.0
END DESCRIPTION:
XS GIS Cut Line= 3
      2892575.05      7079025.01      2892075.00      7078925.00
      2891524.97      7079275.02
#Sta/Elev= 30
  4530.7  499.87  4561.3  499.27  4632.7  495.50  4683.7  494.78  4806.1  490.87
  4904.3  489.92  4938.7  488.28  4959.1  489.08  4979.5  488.30  4996.9  484.91
  4997.4  484.11  5002.4  484.11  5002.9  484.91  5010.1  486.61  5030.5  489.19
  5063.5  489.39  5069.4  488.85  5076.2  486.54  5084.7  489.29  5099.9  489.92
  5157.5  492.06  5199.8  494.78  5301.4  498.12  5351.4  497.80  5396.2  498.87
  5445.3  497.90  5491.1  498.75  5548.6  498.05  5663.8  499.97  5692.6  501.93
#Mann=3,-1,0
  4530.7    0.05       0  4996.9    0.03       0  5002.9    0.05       0
Bank Sta=4904.3,5099.9
Exp/Cntr=0.3,0.1

Type RM Length L Ch R = 1,35830,189,189,189
BEGIN DESCRIPTION:
CARROLL CREEK 49.0
END DESCRIPTION:
XS GIS Cut Line= 3
      2892425.02      7078525.00      2891925.00      7078625.00
      2891525.01      7079024.99
#Sta/Elev= 30
  4520.0  498.15  4550.6  497.78  4581.2  496.50  4591.4  495.37  4611.8  494.38
  4683.2  492.20  4693.4  491.20  4776.3  489.14  4836.2  487.85  4887.2  488.11
  4948.3  487.22  4968.7  488.03  4989.1  488.16  4996.3  485.49  4996.8  484.69
  5001.8  484.69  5002.3  485.49  5009.5  487.07  5019.7  487.77  5033.5  487.61
  5062.9  489.14  5128.9  492.64  5199.6  492.51  5242.1  494.20  5312.8  496.16
  5397.6  495.73  5482.5  497.44  5524.9  497.15  5553.2  497.51  5595.6  499.10
#Mann=3,-1,0
  4520.0    0.05       0  4996.3    0.03       0  5002.3    0.05       0
Bank Sta=4776.3,5062.9
Exp/Cntr=0.3,0.1

Type RM Length L Ch R = 1,35641,541,541,541
BEGIN DESCRIPTION:
CARROLL CREEK 48.0
END DESCRIPTION:
XS GIS Cut Line= 3
      2892274.17      7078291.30      2891974.12      7078391.32
      2891574.98      7078690.67
#Sta/Elev= 30
  4610.3  493.98  4636.8  493.39  4642.1  492.91  4668.4  493.21  4673.7  492.30
  4683.2  491.96  4700.0  489.57  4757.8  488.26  4800.2  487.77  4809.7  487.31
  4872.9  487.48  4889.8  487.15  4942.6  487.49  4950.5  486.32  4992.6  487.70
  4997.5  484.59  4998.0  483.79  5003.0  483.79  5003.5  484.59  5007.2  486.05
  5013.5  486.94  5036.4  487.28  5063.8  488.26  5092.6  489.43  5163.5  490.30
  5213.5  492.29  5250.5  492.90  5328.1  495.65  5400.5  496.75  5425.5  496.78
#Mann=3,-1,0
  4610.3    0.05       0  4997.5    0.03       0  5003.5    0.05       0
Bank Sta=4757.8,5063.8
Exp/Cntr=0.3,0.1

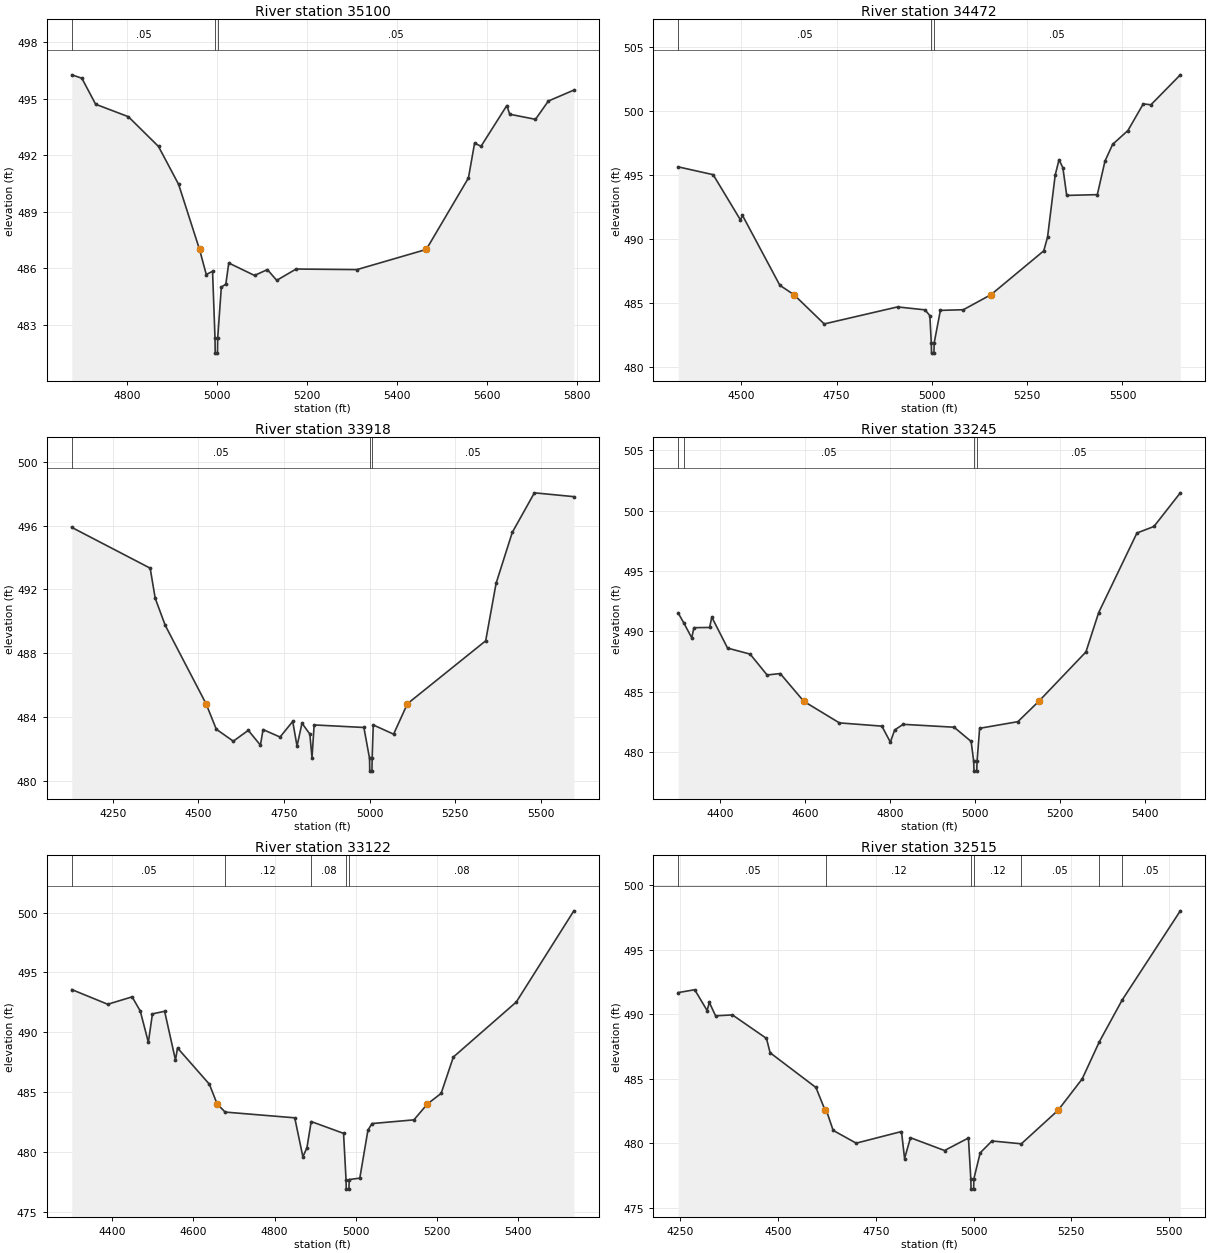
Type RM Length L Ch R = 1,35100,628,628,628
BEGIN DESCRIPTION:
CARROLL CREEK 47.0
END DESCRIPTION:
XS GIS Cut Line= 3
      2892225.02      7077774.99      2891925.00      7077925.00
      2891424.97      7078525.03
#Sta/Elev= 30
  4677.0  496.26  4699.4  496.08  4730.1  494.70  4802.8  494.04  4869.9  492.46
  4914.6  490.45  4961.1  487.00  4976.1  485.67  4990.1  485.84  4995.5  482.30
  4996.0  481.50  5001.0  481.50  5001.5  482.30  5009.6  485.00  5019.6  485.16
  5026.1  486.28  5083.4  485.62  5112.0  485.93  5132.8  485.36  5175.8  485.96
  5311.2  485.93  5465.4  487.00  5559.1  490.79  5572.8  492.64  5587.1  492.47
  5644.4  494.63  5650.9  494.17  5708.2  493.90  5736.8  494.87  5793.5  495.45
#Mann=3,-1,0
  4677.0    0.05       0  4995.5    0.03       0  5001.5    0.05       0
Bank Sta=4961.1,5465.4
Exp/Cntr=0.3,0.1

Type RM Length L Ch R = 1,34472,554,554,554
BEGIN DESCRIPTION:
CARROLL CREEK 46.0
END DESCRIPTION:
XS GIS Cut Line= 3
      2892314.05      7077629.53      2891675.00      7077475.00
      2891018.20      7077416.13
#Sta/Elev= 30
  4334.8  495.61  4426.4  495.00  4498.1  491.46  4503.3  491.82  4601.3  486.36
  4638.1  485.63  4717.7  483.34  4910.0  484.67  4982.0  484.44  4994.8  483.99
  4998.5  481.86  4999.1  481.06  5005.5  481.06  5006.1  481.86  5022.4  484.40
  5082.6  484.45  5155.3  485.63  5293.5  489.05  5303.5  490.12  5323.6  494.98
  5333.6  496.17  5343.7  495.54  5353.7  493.38  5434.0  493.44  5454.1  496.06
  5474.2  497.37  5514.3  498.45  5554.5  500.53  5574.6  500.46  5651.7  502.80
#Mann=3,-1,0
  4334.8    0.05       0  4998.5    0.03       0  5006.1    0.05       0
Bank Sta=4638.1,5155.3
Exp/Cntr=0.3,0.1

Type RM Length L Ch R = 1,33918,673,673,673
BEGIN DESCRIPTION:
CARROLL CREEK 45.0
END DESCRIPTION:
XS GIS Cut Line= 3
      2892325.00      7077525.00      2891695.11      7077062.69
      2891021.52      7077180.74
#Sta/Elev= 30
  4130.6  495.89  4359.4  493.33  4374.1  491.44  4403.4  489.74  4522.5  484.82
  4552.4  483.22  4602.0  482.47  4645.7  483.15  4681.2  482.22  4688.8  483.20
  4738.4  482.73  4775.4  483.71  4788.0  482.16  4802.4  483.60  4825.3  482.92
  4831.7  481.43  4837.9  483.49  4983.1  483.33  4999.6  481.39  5000.2  480.59
  5006.6  480.59  5007.2  481.39  5010.4  483.49  5069.8  482.91  5110.1  484.82
  5338.5  488.77  5368.9  492.38  5416.2  495.58  5480.7  498.06  5595.8  497.82
#Mann=3,-1,0
  4130.6    0.05       0  4999.6    0.03       0  5007.2    0.05       0
Bank Sta=4522.5,5110.1
Exp/Cntr=0.3,0.1

Type RM Length L Ch R = 1,33245,123,123,123
BEGIN DESCRIPTION:
Mapping XS 8831f0f6
END DESCRIPTION:
XS GIS Cut Line= 4
      2892320.10      7076767.55      2892174.28      7076732.83
      2891434.70      7076708.52      2891143.01      7076694.63
#Sta/Elev= 30
  4302.2  491.51  4316.0  490.65  4334.0  489.46  4339.1  490.30  4376.1  490.32
  4381.2  491.18  4418.3  488.61  4471.4  488.11  4511.4  486.38  4542.3  486.50
  4597.7  484.20  4681.5  482.41  4781.6  482.14  4801.6  480.81  4811.6  481.82
  4831.6  482.29  4951.6  482.05  4991.7  480.87  4997.8  479.21  4998.4  478.41
  5004.9  478.41  5005.6  479.21  5011.7  481.96  5101.7  482.51  5151.0  484.20
  5261.9  488.29  5291.9  491.55  5382.0  498.15  5422.0  498.69  5484.1  501.48
#Mann=4,-1,0
  4302.2    0.08       0  4316.0    0.05       0  4997.8    0.03       0
  5005.6    0.05       0
Bank Sta=4597.7,5151
Exp/Cntr=0.3,0.1

Type RM Length L Ch R = 1,33122,607,607,607
BEGIN DESCRIPTION:
Mapping XS 609cfb25
END DESCRIPTION:
XS GIS Cut Line= 3
      2892403.46      7076646.02      2891959.00      7076635.60
      2891168.70      7076604.41
#Sta/Elev= 30
  4301.1  493.57  4389.6  492.34  4449.6  492.96  4469.6  491.78  4489.6  489.16
  4499.6  491.54  4529.6  491.75  4556.3  487.68  4561.3  488.69  4639.7  485.66
  4658.8  484.01  4678.5  483.33  4849.8  482.85  4869.8  479.59  4879.8  480.35
  4890.3  482.54  4969.9  481.55  4976.0  477.69  4976.6  476.89  4983.1  476.89
  4983.8  477.69  5009.9  477.81  5029.9  481.82  5039.9  482.37  5143.1  482.68
  5176.3  484.01  5210.0  484.89  5240.1  487.93  5395.0  492.53  5536.6  500.15
#Mann=5,-1,0
  4301.1    0.05       0  4678.5    0.12       0  4890.3    0.08       0
  4976.0    0.07       0  4983.8    0.08       0
Bank Sta=4658.8,5176.3
Exp/Cntr=0.3,0.1

Type RM Length L Ch R = 1,32515,652,652,652
BEGIN DESCRIPTION:
CARROLL CREEK 43.0
END DESCRIPTION:
XS GIS Cut Line= 3
      2892411.01      7076388.44      2891775.00      7076025.00
      2891224.99      7076075.00
#Sta/Elev= 30
  4244.3  491.68  4286.5  491.90  4318.2  490.29  4323.9  490.92  4339.8  489.88
  4383.0  489.95  4470.1  488.13  4479.4  487.02  4596.7  484.33  4620.2  482.56
  4623.5  482.55  4640.7  481.01  4699.7  480.02  4815.6  480.92  4823.5  478.83
  4838.6  480.44  4925.7  479.45  4986.9  480.42  4993.0  477.26  4993.7  476.46
  5000.2  476.46  5000.8  477.26  5017.0  479.27  5047.1  480.19  5122.3  479.97
  5216.4  482.57  5278.1  485.00  5321.7  487.86  5380.2  491.10  5529.1  498.01
#Mann=7,-1,0
  4244.3    0.05       0  4623.5    0.12       0  4993.0    0.07       0
  5000.8    0.12       0  5122.3    0.05       0  5321.7    0.16       0
  5380.2    0.05       0
Bank Sta=4620.2,5216.4
Exp/Cntr=0.3,0.1

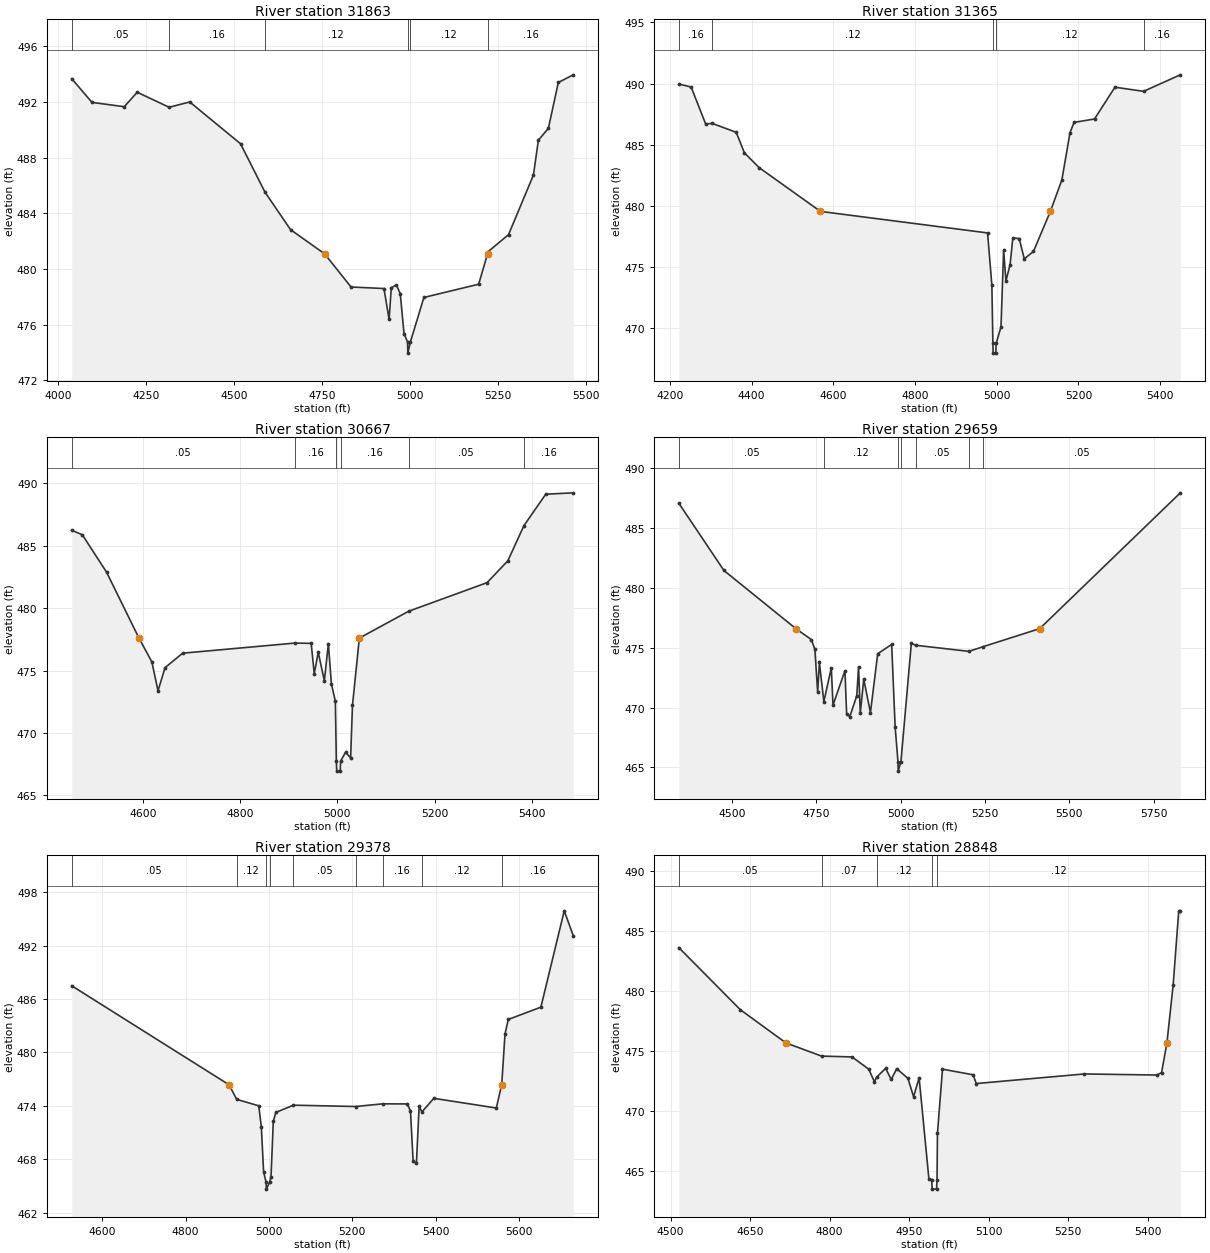
Type RM Length L Ch R = 1,31863,498,498,498
BEGIN DESCRIPTION:
CARROLL CREEK 42.0
END DESCRIPTION:
XS GIS Cut Line= 3
      2892524.98      7076374.97      2891975.00      7075625.00
      2891624.99      7075274.99
#Sta/Elev= 30
  4039.3  493.66  4096.8  491.96  4188.6  491.65  4225.3  492.69  4316.0  491.61
  4374.6  491.99  4518.9  488.99  4588.5  485.51  4661.0  482.82  4757.9  481.08
  4832.9  478.70  4926.5  478.59  4941.1  476.38  4947.3  478.65  4962.0  478.85
  4972.8  478.21  4983.5  475.35  4993.6  474.75  4994.3  473.95  5001.5  474.75
  5040.0  477.95  5195.6  478.90  5220.7  481.08  5222.0  481.23  5280.4  482.46
  5351.2  486.74  5365.3  489.25  5393.6  490.09  5421.9  493.39  5464.3  493.94
#Mann=6,-1,0
  4039.3    0.05       0  4316.0    0.16       0  4588.5    0.12       0
  4993.6    0.07       0  5001.5    0.12       0  5222.0    0.16       0
Bank Sta=4757.9,5220.7
Exp/Cntr=0.3,0.1

Type RM Length L Ch R = 1,31365,698,698,698
BEGIN DESCRIPTION:
CARROLL CREEK 41.0
END DESCRIPTION:
XS GIS Cut Line= 4
      2892375.00      7075924.97      2892325.32      7075272.76
      2892127.40      7075175.00      2891775.05      7075175.00
#Sta/Elev= 30
  4222.1  489.97  4252.2  489.72  4287.6  486.71  4304.3  486.74  4362.5  486.02
  4382.5  484.34  4418.6  483.13  4568.7  479.55  4977.6  477.79  4988.1  473.51
  4990.6  468.76  4991.2  467.96  4997.8  467.96  4998.5  468.76  5010.4  470.09
  5016.9  476.39  5022.5  473.86  5032.7  475.20  5039.4  477.38  5055.0  477.33
  5067.4  475.67  5089.9  476.28  5131.2  479.55  5159.3  482.11  5179.3  485.99
  5189.3  486.83  5239.3  487.11  5289.3  489.71  5359.3  489.37  5449.3  490.72
#Mann=5,-1,0
  4222.1    0.16       0  4304.3    0.12       0  4990.6    0.07       0
  4998.5    0.12       0  5359.3    0.16       0
Bank Sta=4568.7,5131.2
Exp/Cntr=0.3,0.1

Type RM Length L Ch R = 1,30667,1008,1008,1008
BEGIN DESCRIPTION:
CARROLL CREEK 40.0
END DESCRIPTION:
XS GIS Cut Line= 3
      2892625.01      7074374.99      2892175.00      7074725.00
      2891874.98      7075075.02
#Sta/Elev= 30
  4453.8  486.24  4475.5  485.88  4525.3  482.89  4592.0  477.60  4618.5  475.70
  4631.2  473.38  4645.6  475.23  4681.8  476.39  4912.3  477.20  4946.1  477.18
  4952.4  474.75  4960.6  476.47  4973.2  474.17  4981.4  477.15  4987.7  473.93
  4995.8  472.54  4997.8  467.74  4998.6  466.94  5005.8  466.94  5006.6  467.74
  5016.7  468.45  5027.2  468.01  5031.0  472.21  5045.1  477.60  5146.4  479.75
  5307.6  482.04  5350.4  483.79  5383.5  486.61  5428.4  489.13  5484.9  489.24
#Mann=6,-1,0
  4453.8    0.05       0  4912.3    0.16       0  4997.8    0.07       0
  5006.6    0.16       0  5146.4    0.05       0  5383.5    0.16       0
Bank Sta=4592,5045.1
Exp/Cntr=0.3,0.1

Type RM Length L Ch R = 1,29659,281,281,281
BEGIN DESCRIPTION:
CARROLL CREEK 39.0
END DESCRIPTION:
XS GIS Cut Line= 3
      2892624.98      7074325.00      2891830.96      7074116.94
      2891354.66      7074581.12
#Sta/Elev= 30
  4342.7  487.08  4476.3  481.46  4689.4  476.60  4735.5  475.68  4745.8  474.86
  4754.0  471.29  4759.1  473.77  4772.4  470.50  4794.4  473.32  4799.5  470.21
  4834.8  473.08  4839.9  469.46  4849.2  469.24  4869.9  470.99  4875.2  473.41
  4880.3  469.54  4890.6  472.38  4910.4  469.58  4931.9  474.50  4973.3  475.28
  4983.6  468.38  4991.9  465.49  4992.7  464.69  5000.8  465.49  5031.6  475.38
  5044.6  475.21  5201.9  474.70  5245.3  475.10  5411.9  476.60  5828.6  487.95
#Mann=7,-1,0
  4342.7    0.05       0  4772.4    0.12       0  4991.9    0.07       0
  5000.8    0.12       0  5044.6    0.05       0  5201.9    0.07       0
  5245.3    0.05       0
Bank Sta=4689.4,5411.9
Exp/Cntr=0.3,0.1

Type RM Length L Ch R = 1,29378,530,530,530
BEGIN DESCRIPTION:
CARROLL CREEK 38.0
END DESCRIPTION:
XS GIS Cut Line= 3
      2892624.98      7074174.99      2892175.00      7073975.00
      2891624.96      7073524.97
#Sta/Elev= 30
  4526.8  487.48  4904.2  476.36  4922.5  474.72  4975.4  474.00  4981.6  471.66
  4987.1  466.59  4992.9  465.44  4993.7  464.64  5001.8  465.44  5004.9  466.02
  5010.3  472.25  5016.5  473.26  5058.8  474.07  5207.8  473.92  5272.6  474.22
  5331.5  474.21  5339.4  473.43  5345.8  467.78  5353.7  467.56  5360.2  473.95
  5366.9  473.31  5395.4  474.84  5545.4  473.75  5558.2  476.36  5558.4  476.41
  5566.2  482.06  5574.1  483.70  5652.3  485.08  5708.3  495.90  5729.9  493.11
#Mann=9,-1,0
  4526.8    0.05       0  4922.5    0.12       0  4992.9    0.07       0
  5001.8    0.12       0  5058.8    0.05       0  5207.8    0.12       0
  5272.6    0.16       0  5366.9    0.12       0  5558.4    0.16       0
Bank Sta=4904.2,5558.2
Exp/Cntr=0.3,0.1

Type RM Length L Ch R = 1,28848,546,546,546
BEGIN DESCRIPTION:
CARROLL CREEK 37.0
END DESCRIPTION:
XS GIS Cut Line= 3
      2892625.01      7074025.04      2892475.00      7073575.00
      2892074.98      7073324.99
#Sta/Elev= 30
  4515.5  483.62  4631.5  478.44  4717.5  475.67  4784.7  474.57  4842.3  474.50
  4873.9  473.47  4884.5  472.42  4888.6  472.81  4905.6  473.55  4916.1  472.62
  4926.6  473.52  4947.7  472.71  4958.3  471.18  4968.8  472.75  4987.2  464.34
  4992.4  464.27  4993.4  463.47  5001.6  463.47  5002.6  464.27  5003.4  468.14
  5012.9  473.48  5070.7  473.01  5076.6  472.28  5280.6  473.08  5417.4  472.99
  5426.2  473.19  5436.3  475.67  5448.0  480.48  5458.6  486.69  5461.6  486.69
#Mann=5,-1,0
  4515.5    0.05       0  4784.7    0.07       0  4888.6    0.12       0
  4992.4    0.07       0  5002.6    0.12       0
Bank Sta=4717.5,5436.3
Exp/Cntr=0.3,0.1