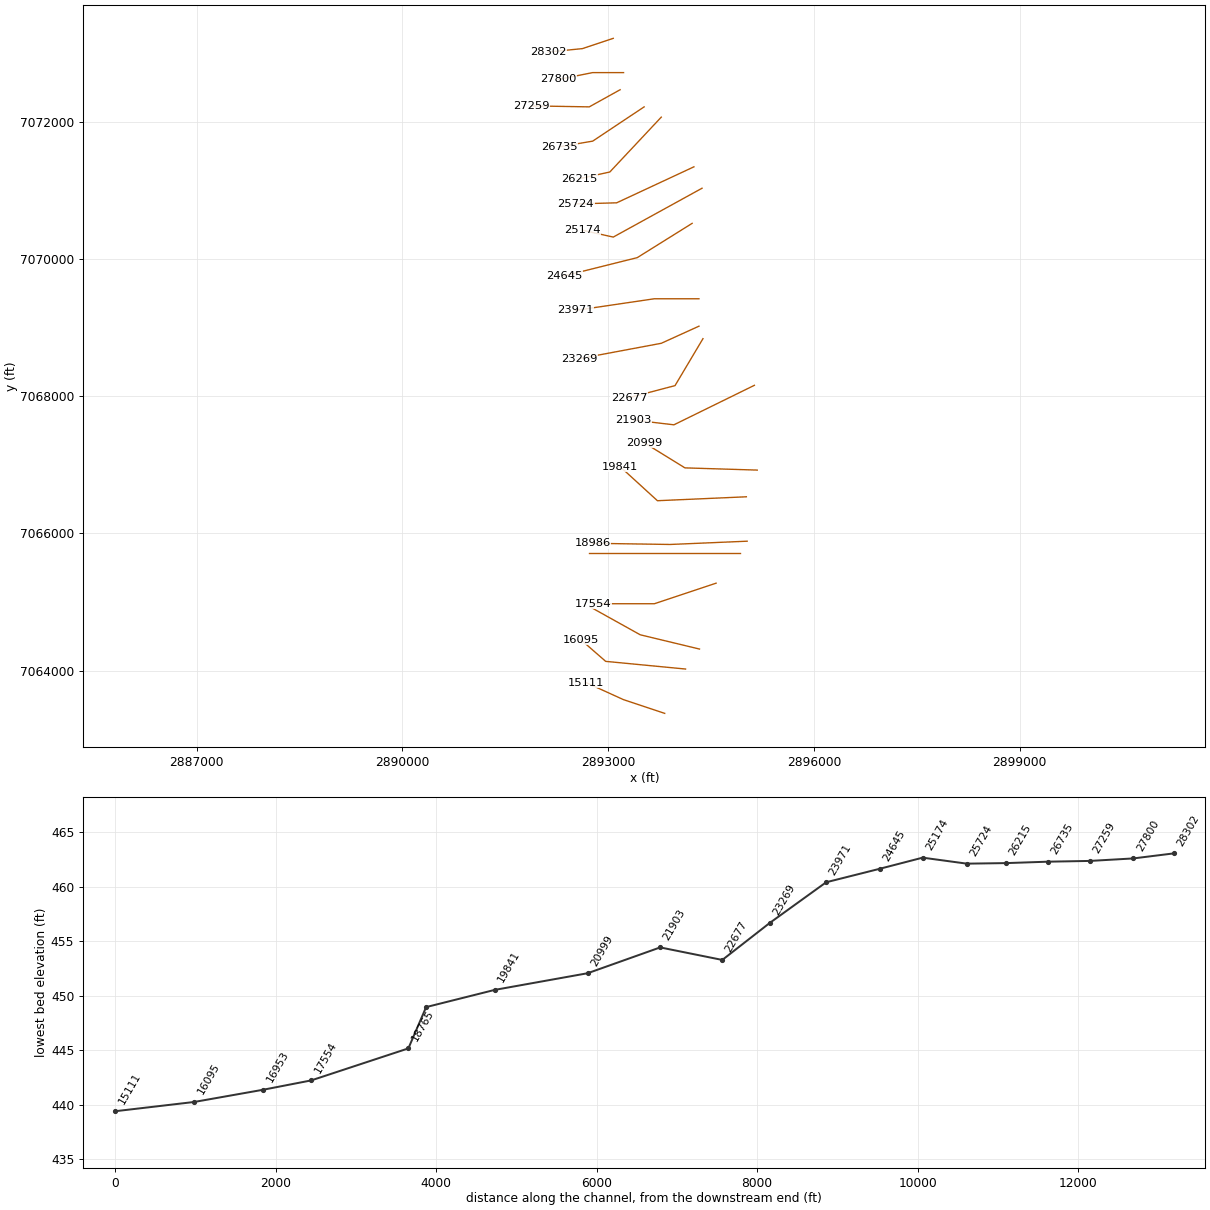
HEC-RAS study CARROLL CREEK.prj: CARROLL CREEK Base Level Engineering

--- CARROLL CREEK.g01 (geometry) --- (continued)

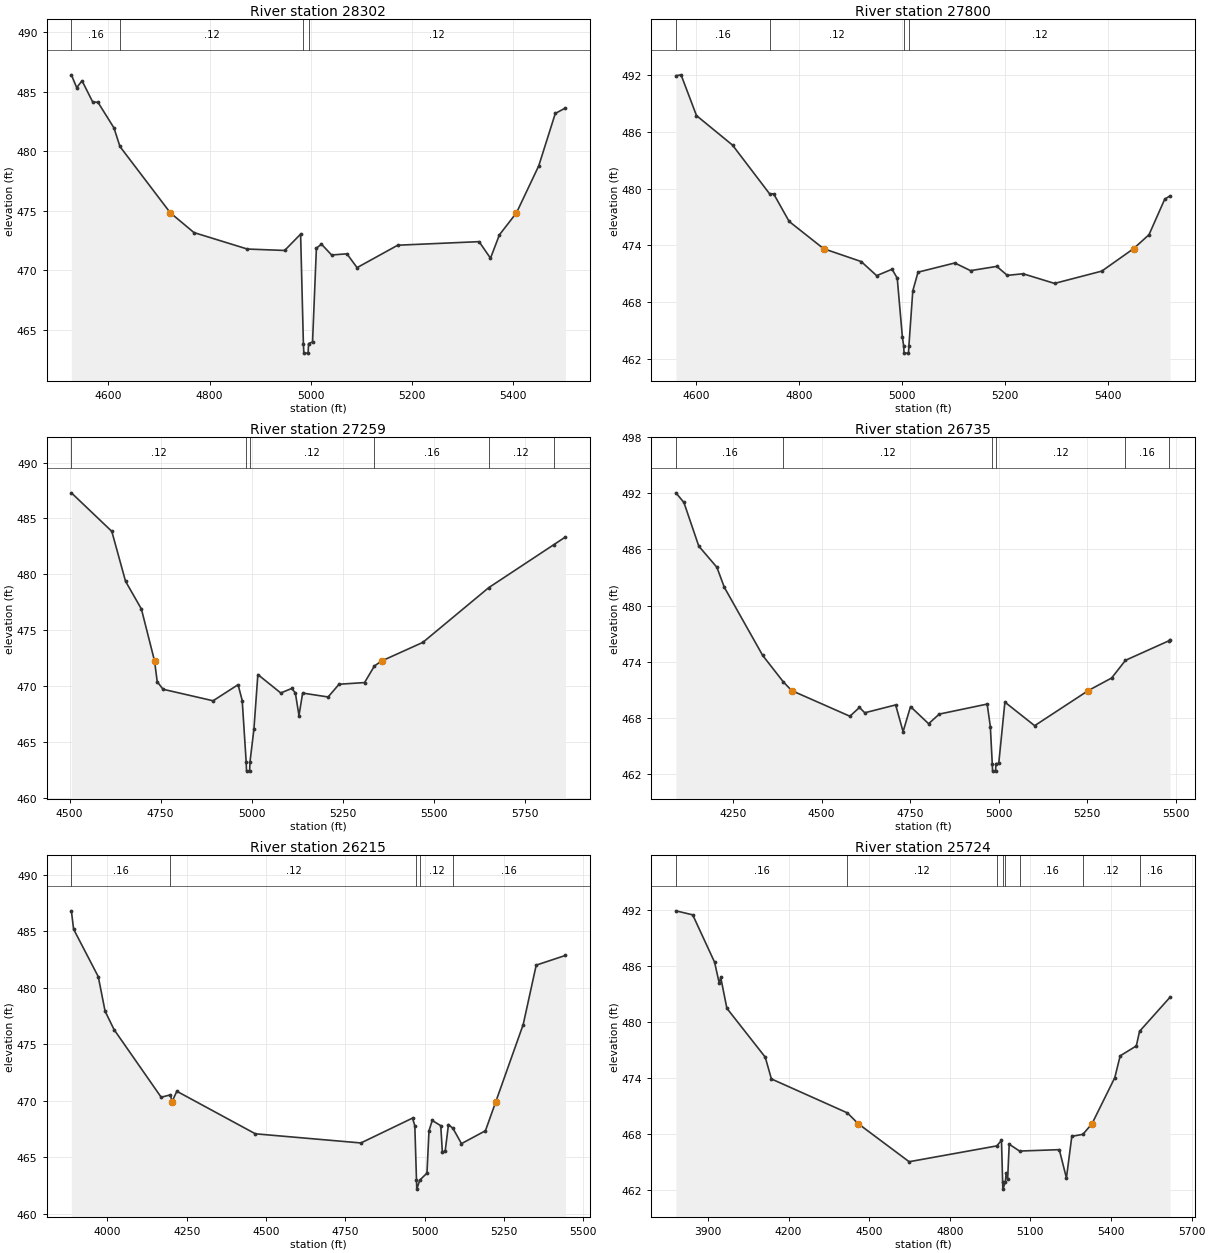
Type RM Length L Ch R = 1,28302,502,502,502
BEGIN DESCRIPTION:
CARROLL CREEK 36.0
END DESCRIPTION:
XS GIS Cut Line= 3
      2893074.97      7073224.99      2892625.00      7073075.00
      2892125.01      7073025.00
#Sta/Elev= 30
  4526.7  486.40  4537.2  485.33  4547.8  485.90  4568.8  484.13  4579.4  484.09
  4611.0  481.94  4622.7  480.39  4722.3  474.83  4769.1  473.17  4874.5  471.79
  4948.3  471.67  4979.9  473.04  4985.4  463.86  4986.3  463.06  4994.7  463.06
  4995.6  463.86  5003.5  464.00  5011.1  471.86  5021.1  472.20  5041.2  471.29
  5071.4  471.39  5091.5  470.23  5171.9  472.11  5332.7  472.41  5355.3  471.02
  5372.9  472.98  5406.7  474.83  5450.7  478.77  5483.4  483.16  5503.5  483.62
#Mann=4,-1,0
  4526.7    0.16       0  4622.7    0.12       0  4985.4    0.07       0
  4995.6    0.12       0
Bank Sta=4722.3,5406.7
Exp/Cntr=0.3,0.1

Type RM Length L Ch R = 1,27800,541,541,541
BEGIN DESCRIPTION:
CARROLL CREEK 35.0
END DESCRIPTION:
XS GIS Cut Line= 3
      2893225.03      7072725.00      2892775.00      7072725.00
      2892275.04      7072625.01
#Sta/Elev= 30
  4560.4  491.93  4570.4  492.02  4600.4  487.71  4670.4  484.59  4742.3  479.45
  4750.4  479.43  4780.4  476.52  4847.4  473.64  4920.4  472.28  4950.4  470.79
  4980.4  471.47  4990.4  470.52  5000.4  464.29  5002.8  463.40  5003.7  462.60
  5012.2  462.60  5013.1  463.40  5020.6  469.18  5030.8  471.16  5102.2  472.13
  5132.8  471.32  5183.8  471.77  5204.2  470.82  5234.8  470.99  5296.0  469.97
  5387.8  471.27  5449.4  473.64  5479.5  475.12  5510.1  478.88  5520.3  479.22
#Mann=4,-1,0
  4560.4    0.16       0  4742.3    0.12       0  5002.8    0.07       0
  5013.1    0.12       0
Bank Sta=4847.4,5449.4
Exp/Cntr=0.3,0.1

Type RM Length L Ch R = 1,27259,524,524,524
BEGIN DESCRIPTION:
CARROLL CREEK 34.0
END DESCRIPTION:
XS GIS Cut Line= 3
      2893175.02      7072475.01      2892725.00      7072225.00
      2891883.63      7072239.19
#Sta/Elev= 30
  4504.9  487.29  4615.9  483.84  4653.6  479.37  4697.1  476.89  4733.2  472.24
  4740.6  470.37  4756.6  469.70  4893.9  468.67  4962.5  470.11  4973.9  468.69
  4984.8  463.17  4985.7  462.37  4994.2  462.37  4995.1  463.17  5006.0  466.12
  5016.8  471.02  5079.7  469.37  5109.7  469.77  5119.7  469.38  5129.7  467.34
  5139.7  469.36  5209.7  469.01  5239.7  470.15  5309.7  470.30  5336.9  471.79
  5357.0  472.24  5469.8  473.90  5650.6  478.80  5828.4  482.63  5861.2  483.34
#Mann=6,-1,0
  4504.9    0.12       0  4984.8    0.07       0  4995.1    0.12       0
  5336.9    0.16       0  5650.6    0.12       0  5828.4    0.16       0
Bank Sta=4733.2,5357
Exp/Cntr=0.3,0.1

Type RM Length L Ch R = 1,26735,520,520,520
BEGIN DESCRIPTION:
CARROLL CREEK 33.0
END DESCRIPTION:
XS GIS Cut Line= 3
      2893525.02      7072225.01      2892775.00      7071725.00
      2892288.19      7071642.27
#Sta/Elev= 30
  4088.4  492.06  4111.0  491.03  4153.0  486.36  4204.1  484.10  4225.1  481.96
  4333.3  474.68  4392.2  471.82  4415.5  470.91  4579.7  468.17  4606.7  469.11
  4621.7  468.54  4708.9  469.38  4729.9  466.52  4750.9  469.20  4802.0  467.37
  4832.1  468.40  4967.3  469.47  4976.3  467.06  4981.7  463.10  4982.6  462.30
  4991.1  462.30  4992.0  463.10  5000.0  463.12  5017.4  469.68  5101.4  467.16
  5252.6  470.91  5318.8  472.26  5357.9  474.15  5479.4  476.22  5483.6  476.37
#Mann=6,-1,0
  4088.4    0.16       0  4392.2    0.12       0  4981.7    0.07       0
  4992.0    0.12       0  5357.9    0.16       0  5479.4    0.12       0
Bank Sta=4415.5,5252.6
Exp/Cntr=0.3,0.1

Type RM Length L Ch R = 1,26215,491,491,491
BEGIN DESCRIPTION:
CARROLL CREEK 32.0
END DESCRIPTION:
XS GIS Cut Line= 3
      2893775.03      7072075.03      2893025.00      7071275.00
      2892575.00      7071175.00
#Sta/Elev= 30
  3886.3  486.82  3893.4  485.19  3971.1  480.99  3992.6  477.93  4020.9  476.30
  4169.4  470.31  4198.4  470.52  4203.9  469.93  4218.7  470.84  4466.4  467.07
  4799.0  466.26  4961.7  468.46  4969.0  467.79  4974.3  462.97  4975.2  462.17
  4984.7  462.97  5007.3  463.59  5013.7  467.34  5023.9  468.25  5050.8  467.79
  5055.9  465.42  5064.9  465.58  5075.1  467.89  5089.3  467.55  5116.1  466.20
  5191.6  467.34  5224.5  469.93  5310.7  476.75  5351.7  482.01  5443.9  482.87
#Mann=5,-1,0
  3886.3    0.16       0  4198.4    0.12       0  4974.3    0.07       0
  4984.7    0.12       0  5089.3    0.16       0
Bank Sta=4203.9,5224.5
Exp/Cntr=0.3,0.1

Type RM Length L Ch R = 1,25724,550,550,550
BEGIN DESCRIPTION:
CARROLL CREEK 31.0
END DESCRIPTION:
XS GIS Cut Line= 3
      2894251.64      7071350.28      2893125.00      7070825.00
      2892529.70      7070808.64
#Sta/Elev= 30
  3780.8  491.87  3843.3  491.44  3924.7  486.38  3942.1  484.13  3947.6  484.75
  3970.5  481.45  4113.2  476.23  4136.1  473.90  4418.8  470.27  4459.0  469.12
  4648.7  465.05  4974.7  466.74  4992.3  467.33  4996.6  462.92  4997.5  462.12
  5007.0  462.92  5009.7  463.88  5015.2  463.20  5021.1  466.92  5059.6  466.19
  5207.4  466.34  5234.0  463.31  5254.0  467.76  5295.3  467.98  5329.3  469.12
  5414.0  474.04  5434.0  476.37  5494.1  477.43  5506.1  478.99  5619.4  482.63
#Mann=8,-1,0
  3780.8    0.16       0  4418.8    0.12       0  4974.7    0.16       0
  4996.6    0.07       0  5007.0    0.16       0  5059.6    0.16       0
  5295.3    0.12       0  5506.1    0.16       0
Bank Sta=4459,5329.3
Exp/Cntr=0.3,0.1

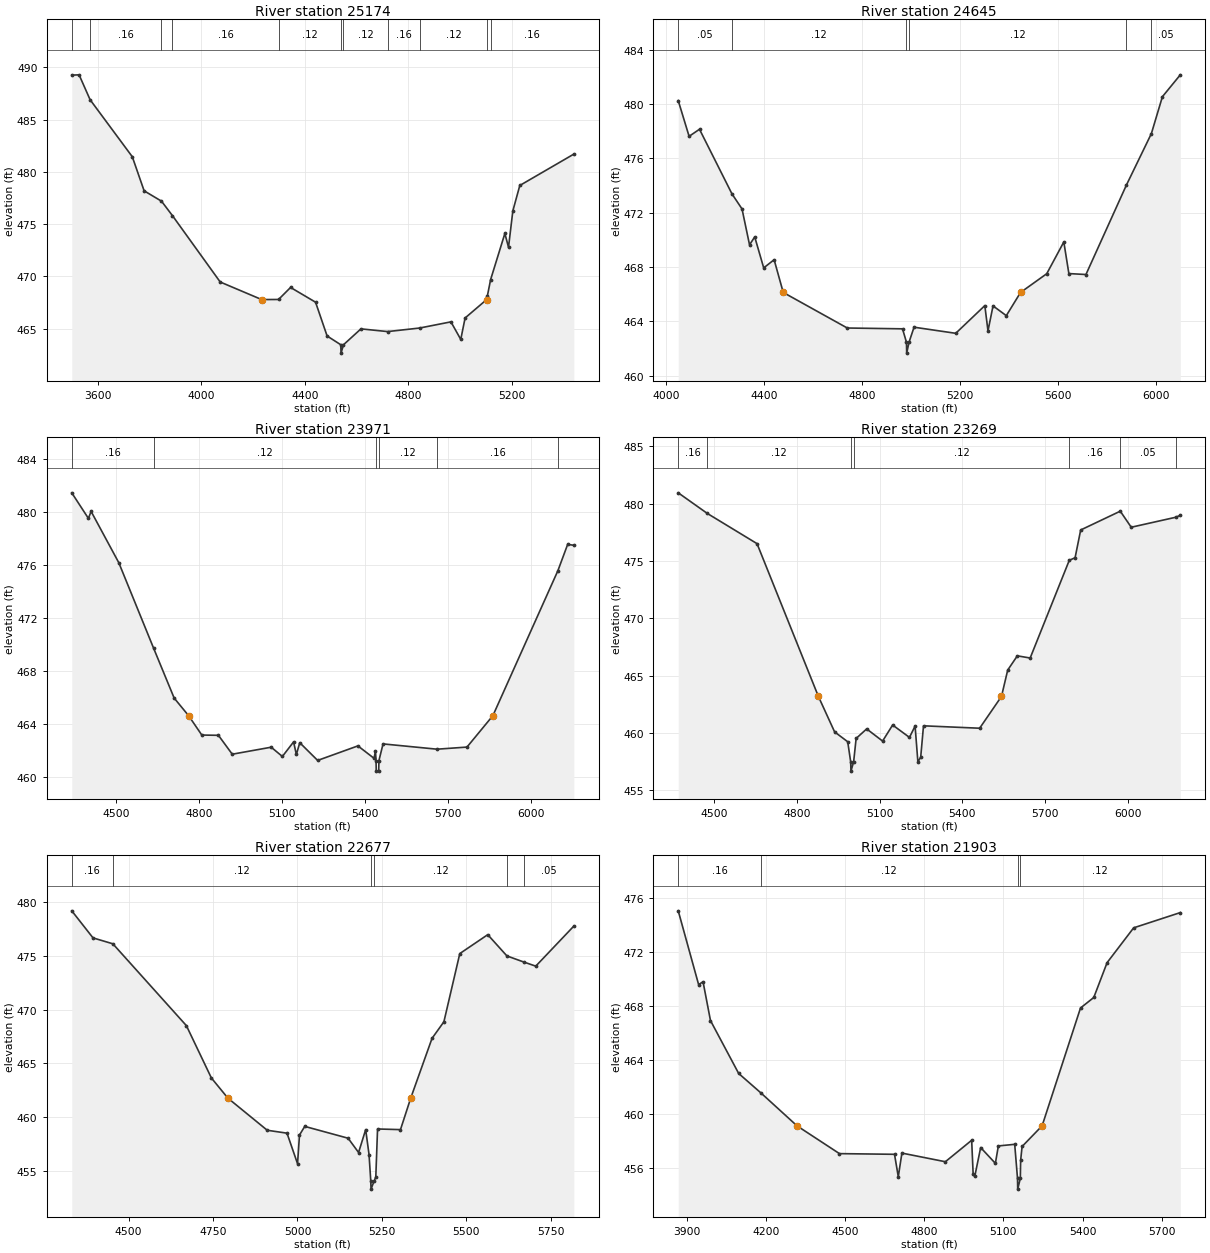
Type RM Length L Ch R = 1,25174,529,529,529
BEGIN DESCRIPTION:
CARROLL CREEK 30.0
END DESCRIPTION:
XS GIS Cut Line= 3
      2894369.76      7071037.82      2893075.00      7070325.00
      2892624.99      7070425.00
#Sta/Elev= 30
  3500.3  489.25  3528.6  489.28  3571.1  486.90  3734.0  481.45  3779.7  478.19
  3846.8  477.20  3889.3  475.81  4073.6  469.47  4233.9  467.79  4298.9  467.80
  4345.3  468.95  4441.8  467.54  4486.4  464.31  4539.3  463.47  4540.2  462.67
  4549.7  463.47  4617.1  464.99  4720.1  464.73  4843.8  465.07  4964.6  465.66
  5002.6  463.98  5019.3  466.03  5102.1  467.78  5105.5  468.16  5118.0  469.71
  5172.9  474.11  5187.0  472.79  5203.7  476.27  5230.6  478.70  5439.3  481.70
#Mann=11,-1,0
  3500.3    0.05       0  3571.1    0.16       0  3846.8    0.05       0
  3889.3    0.16       0  4298.9    0.12       0  4539.3    0.07       0
  4549.7    0.12       0  4720.1    0.16       0  4843.8    0.12       0
  5105.5    0.05       0  5118.0    0.16       0
Bank Sta=4233.9,5102.1
Exp/Cntr=0.3,0.1

Type RM Length L Ch R = 1,24645,674,674,674
BEGIN DESCRIPTION:
CARROLL CREEK 29.0
END DESCRIPTION:
XS GIS Cut Line= 3
      2894225.03      7070525.02      2893425.00      7070025.00
      2892354.19      7069757.30
#Sta/Elev= 30
  4049.9  480.26  4094.2  477.63  4136.6  478.15  4269.0  473.39  4310.0  472.28
  4340.6  469.64  4361.8  470.22  4398.4  467.94  4440.9  468.54  4478.0  466.13
  4739.2  463.51  4964.4  463.45  4980.5  462.46  4981.4  461.66  4990.9  462.46
  5011.4  463.57  5181.4  463.12  5300.0  465.16  5312.9  463.30  5333.5  465.14
  5387.6  464.42  5445.7  466.13  5552.5  467.51  5622.1  469.85  5642.7  467.52
  5712.3  467.45  5877.6  474.05  5979.1  477.83  6024.1  480.55  6097.1  482.16
#Mann=6,-1,0
  4049.9    0.05       0  4269.0    0.12       0  4980.5    0.07       0
  4990.9    0.12       0  5877.6    0.08       0  5979.1    0.05       0
Bank Sta=4478,5445.7
Exp/Cntr=0.3,0.1

Type RM Length L Ch R = 1,23971,702,702,702
BEGIN DESCRIPTION:
CARROLL CREEK 28.0
END DESCRIPTION:
XS GIS Cut Line= 3
      2894324.96      7069425.00      2893675.00      7069425.00
      2892522.93      7069254.98
#Sta/Elev= 30
  4340.8  481.47  4400.8  479.54  4410.8  480.06  4510.8  476.18  4636.6  469.71
  4710.8  465.94  4762.9  464.61  4810.8  463.14  4870.8  463.12  4920.8  461.69
  5061.5  462.22  5101.9  461.52  5142.4  462.62  5152.5  461.67  5164.8  462.56
  5229.4  461.22  5374.9  462.32  5433.2  461.38  5438.3  461.93  5440.4  461.21
  5441.2  460.41  5450.0  460.41  5450.9  461.21  5465.8  462.47  5660.9  462.07
  5769.1  462.23  5862.8  464.61  6097.7  475.58  6133.0  477.57  6155.3  477.50
#Mann=6,-1,0
  4340.8    0.16       0  4636.6    0.12       0  5440.4    0.07       0
  5450.9    0.12       0  5660.9    0.16       0  6097.7    0.05       0
Bank Sta=4762.9,5862.8
Exp/Cntr=0.3,0.1

Type RM Length L Ch R = 1,23269,592,592,592
BEGIN DESCRIPTION:
CARROLL CREEK 27.0
END DESCRIPTION:
XS GIS Cut Line= 3
      2894324.97      7069024.99      2893775.00      7068775.00
      2892580.12      7068551.06
#Sta/Elev= 30
  4370.4  480.94  4476.0  479.14  4656.0  476.51  4878.4  463.19  4937.2  460.10
  4984.7  459.24  4995.5  457.48  4996.4  456.68  5006.1  457.48  5015.2  459.53
  5053.4  460.36  5111.1  459.30  5147.5  460.70  5208.5  459.62  5228.9  460.61
  5239.0  457.49  5249.2  457.89  5259.4  460.63  5462.9  460.42  5542.0  463.19
  5564.6  465.49  5599.5  466.73  5646.0  466.54  5787.8  475.06  5808.8  475.28
  5829.1  477.70  5972.6  479.34  6012.3  477.94  6173.7  478.81  6190.2  478.98
#Mann=7,-1,0
  4370.4    0.16       0  4476.0    0.12       0  4995.5    0.07       0
  5006.1    0.12       0  5787.8    0.16       0  5972.6    0.05       0
  6173.7    0.08       0
Bank Sta=4878.4,5542
Exp/Cntr=0.3,0.1

Type RM Length L Ch R = 1,22677,774,774,774
BEGIN DESCRIPTION:
CARROLL CREEK 26.0
END DESCRIPTION:
XS GIS Cut Line= 3
      2894383.05      7068842.64      2893975.51      7068157.41
      2893308.35      7067981.97
#Sta/Elev= 30
  4331.5  479.19  4394.4  476.67  4453.2  476.12  4671.0  468.50  4745.0  463.63
  4794.0  461.75  4910.5  458.76  4969.0  458.49  5000.2  455.65  5006.0  458.32
  5021.6  459.12  5150.0  458.02  5181.0  456.69  5202.0  458.82  5212.0  456.50
  5217.0  454.08  5217.9  453.28  5227.6  454.08  5232.0  454.40  5237.2  458.88
  5305.1  458.82  5335.4  461.75  5398.6  467.32  5433.7  468.86  5480.8  475.21
  5563.6  476.97  5620.4  474.99  5670.7  474.42  5705.8  474.04  5818.6  477.77
#Mann=6,-1,0
  4331.5    0.16       0  4453.2    0.12       0  5217.0    0.07       0
  5227.6    0.12       0  5620.4    0.16       0  5670.7    0.05       0
Bank Sta=4794,5335.4
Exp/Cntr=0.3,0.1

Type RM Length L Ch R = 1,21903,904,904,904
BEGIN DESCRIPTION:
CARROLL CREEK 25.0
END DESCRIPTION:
XS GIS Cut Line= 3
      2895133.08      7068162.10      2893959.43      7067585.69
      2893369.55      7067655.09
#Sta/Elev= 30
  3868.6  475.05  3945.7  469.59  3962.6  469.79  3990.7  466.92  4097.5  463.00
  4182.2  461.55  4318.4  459.12  4479.2  457.06  4687.7  457.01  4702.0  455.35
  4715.7  457.10  4880.3  456.46  4979.9  458.05  4985.5  455.56  4991.7  455.38
  5014.0  457.51  5069.7  456.34  5081.0  457.63  5142.9  457.75  5153.5  455.23
  5154.3  454.43  5164.2  455.23  5165.4  456.56  5170.9  457.59  5246.7  459.12
  5392.1  467.85  5442.4  468.63  5492.8  471.21  5593.4  473.79  5770.1  474.92
#Mann=4,-1,0
  3868.6    0.16       0  4182.2    0.12       0  5153.5    0.07       0
  5164.2    0.12       0
Bank Sta=4318.4,5246.7
Exp/Cntr=0.3,0.1

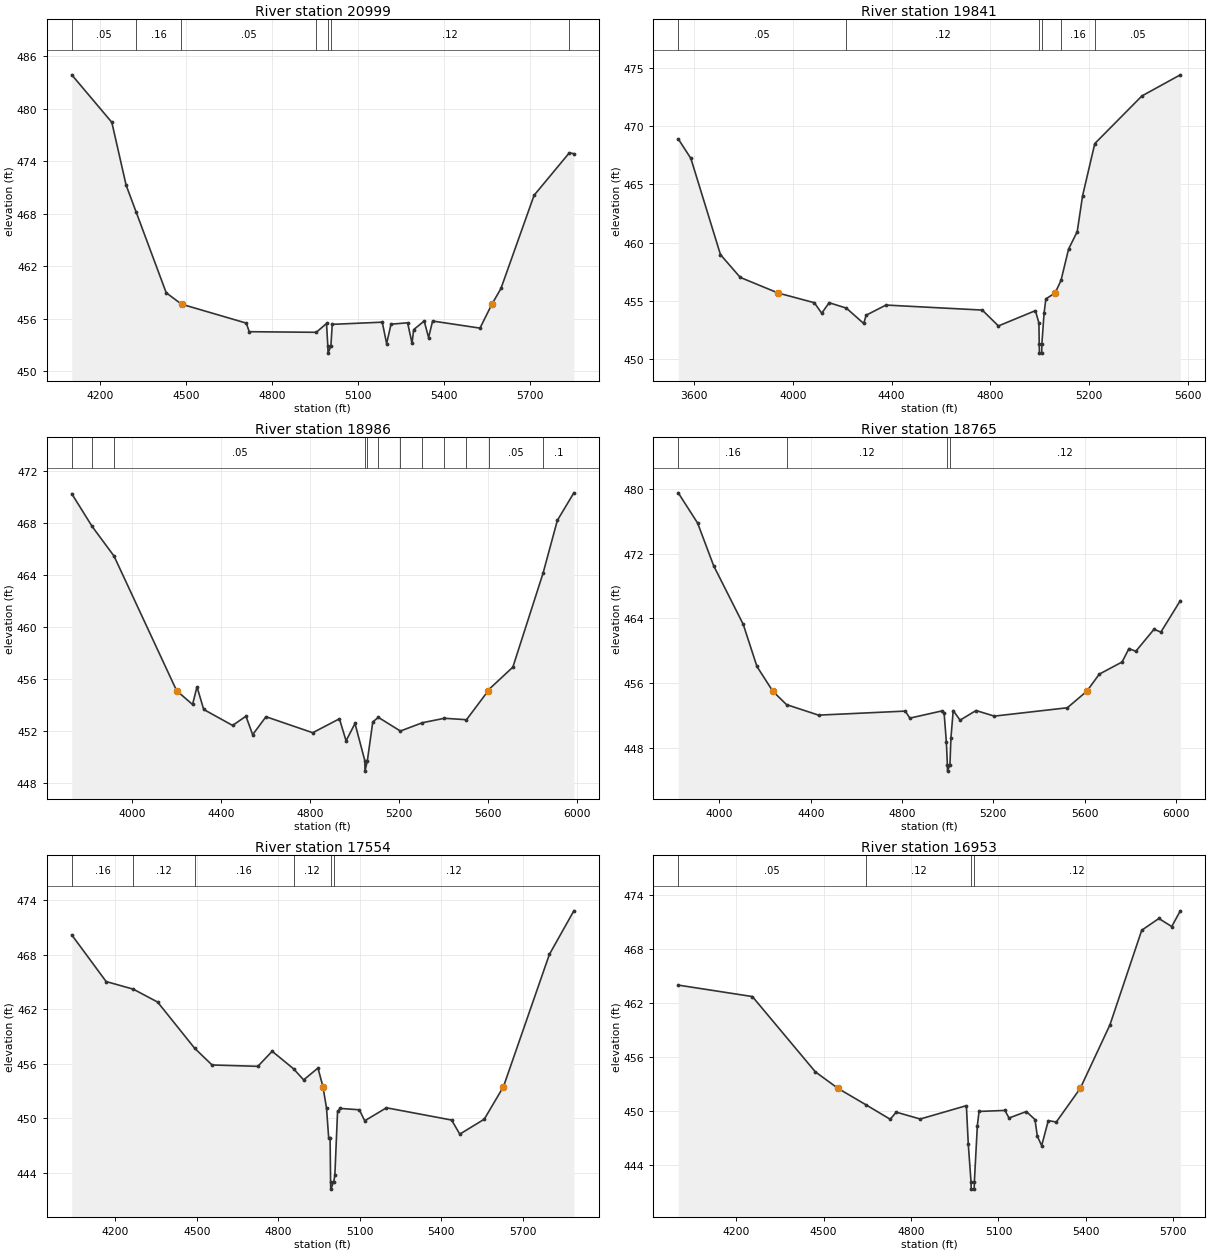
Type RM Length L Ch R = 1,20999,1158,1158,1158
BEGIN DESCRIPTION:
CARROLL CREEK 24.0
END DESCRIPTION:
XS GIS Cut Line= 3
      2895174.96      7066925.00      2894120.20      7066957.22
      2893525.01      7067324.99
#Sta/Elev= 30
  4099.9  483.88  4239.9  478.45  4289.9  471.26  4325.5  468.14  4430.0  458.96
  4482.6  457.68  4484.4  457.65  4710.1  455.49  4720.1  454.51  4954.5  454.44
  4990.3  455.45  4994.9  452.86  4995.7  452.06  5005.6  452.86  5010.3  455.35
  5185.1  455.60  5200.4  453.15  5215.8  455.37  5273.8  455.53  5289.2  453.18
  5295.0  454.75  5331.7  455.73  5347.1  453.84  5361.1  455.73  5526.7  454.92
  5568.3  457.65  5600.0  459.45  5715.9  470.11  5839.2  474.97  5854.8  474.86
#Mann=7,-1,0
  4099.9    0.05       0  4325.5    0.16       0  4482.6    0.05       0
  4954.5    0.12       0  4994.9    0.07       0  5005.6    0.12       0
  5839.2    0.16       0
Bank Sta=4484.4,5568.3
Exp/Cntr=0.3,0.1

Type RM Length L Ch R = 1,19841,855,855,855
BEGIN DESCRIPTION:
CARROLL CREEK 23.0
END DESCRIPTION:
XS GIS Cut Line= 3
      2895016.06      7066535.34      2893719.16      7066478.05
      2893175.00      7066975.00
#Sta/Elev= 30
  3535.3  468.89  3586.4  467.22  3706.5  458.97  3786.6  457.02  3940.4  455.68
  4086.9  454.85  4116.9  453.95  4147.0  454.85  4216.6  454.39  4287.1  453.07
  4297.1  453.78  4377.2  454.65  4767.6  454.22  4833.1  452.86  4983.0  454.17
  4997.2  453.12  4998.6  451.33  4999.4  450.53  5008.5  450.53  5009.3  451.33
  5018.1  453.94  5025.5  455.18  5062.8  455.68  5086.8  456.76  5117.4  459.44
  5152.6  460.95  5174.2  464.01  5223.8  468.49  5414.7  472.57  5570.4  474.38
#Mann=6,-1,0
  3535.3    0.05       0  4216.6    0.12       0  4998.6    0.07       0
  5009.3    0.12       0  5086.8    0.16       0  5223.8    0.05       0
Bank Sta=3940.4,5062.8
Exp/Cntr=0.3,0.1

Type RM Length L Ch R = 1,18986,221,221,221
BEGIN DESCRIPTION:
CARROLL CREEK 22.0
END DESCRIPTION:
XS GIS Cut Line= 3
      2895027.72      7065887.34      2893903.62      7065839.60
      2892770.77      7065856.96
#Sta/Elev= 30
  3729.1  470.26  3820.2  467.76  3919.2  465.47  4200.8  455.13  4272.3  454.07
  4292.3  455.43  4322.4  453.69  4452.5  452.46  4512.5  453.17  4542.6  451.75
  4602.6  453.13  4812.8  451.90  4932.8  452.97  4962.8  451.28  5002.9  452.61
  5047.2  449.75  5047.9  448.95  5058.5  449.75  5082.9  452.73  5108.0  453.08
  5207.1  452.03  5306.2  452.67  5405.3  453.01  5504.4  452.90  5602.3  455.13
  5603.5  455.20  5712.9  456.94  5848.8  464.16  5913.0  468.21  5987.2  470.33
#Mann=12,-1,0
  3729.1    0.05       0  3820.2    0.08       0  3919.2    0.05       0
  5047.2    0.04       0  5058.5    0.05       0  5108.0    0.08       0
  5207.1    0.05       0  5306.2    0.08       0  5405.3    0.05       0
  5504.4    0.08       0  5603.5    0.05       0  5848.8     0.1       0
Bank Sta=4200.8,5602.3
Exp/Cntr=0.3,0.1

Type RM Length L Ch R = 1,18765,1211,1211,1211
BEGIN DESCRIPTION:
CARROLL CREEK 21.0
END DESCRIPTION:
XS GIS Cut Line= 3
      2894919.90      7065712.50      2893569.88      7065712.50
      2892719.90      7065712.50
#Sta/Elev= 30
  3819.4  479.51  3904.3  475.78  3974.3  470.53  4104.3  463.27  4164.3  458.08
  4233.9  455.02  4293.9  453.37  4434.3  452.07  4814.3  452.57  4834.3  451.70
  4974.3  452.59  4984.3  452.36  4994.3  448.74  4998.7  445.96  4999.4  445.16
  5010.0  445.96  5014.3  449.25  5024.3  452.64  5054.3  451.45  5124.3  452.64
  5204.3  451.95  5524.3  452.98  5609.7  455.02  5664.3  457.13  5764.3  458.63
  5794.3  460.29  5824.3  459.95  5904.3  462.67  5934.3  462.32  6019.4  466.20
#Mann=4,-1,0
  3819.4    0.16       0  4293.9    0.12       0  4998.7    0.07       0
  5010.0    0.12       0
Bank Sta=4233.9,5609.7
Exp/Cntr=0.3,0.1

Type RM Length L Ch R = 1,17554,601,601,601
BEGIN DESCRIPTION:
CARROLL CREEK 20.0
END DESCRIPTION:
XS GIS Cut Line= 3
      2894575.00      7065275.00      2893675.00      7064975.00
      2892774.99      7064975.00
#Sta/Elev= 30
  4039.1  470.19  4165.6  465.06  4265.8  464.22  4355.3  462.80  4491.3  457.73
  4555.6  455.88  4724.3  455.73  4777.0  457.39  4855.7  455.46  4892.9  454.24
  4945.6  455.54  4964.0  453.49  4977.2  451.11  4985.2  447.81  4990.3  447.81
  4992.1  443.02  4992.7  442.22  5003.5  443.02  5007.8  443.73  5017.8  450.78
  5027.8  451.10  5097.8  450.95  5117.8  449.74  5197.8  451.17  5437.8  449.82
  5467.8  448.27  5557.8  449.91  5628.6  453.49  5797.8  468.05  5887.8  472.84
#Mann=6,-1,0
  4039.1    0.16       0  4265.8    0.12       0  4491.3    0.16       0
  4855.7    0.12       0  4992.1    0.07       0  5003.5    0.12       0
Bank Sta=4964,5628.6
Exp/Cntr=0.3,0.1

Type RM Length L Ch R = 1,16953,858,858,858
BEGIN DESCRIPTION:
CARROLL CREEK 19.0
END DESCRIPTION:
XS GIS Cut Line= 3
      2894332.41      7064313.56      2893467.86      7064521.89
      2892739.30      7064927.80
#Sta/Elev= 30
  4000.8  463.97  4255.3  462.70  4471.3  454.36  4549.0  452.53  4646.5  450.68
  4728.5  449.10  4748.9  449.89  4831.3  449.13  4989.8  450.61  4996.4  446.31
  5005.8  442.16  5006.5  441.36  5016.6  441.36  5017.2  442.16  5027.5  448.41
  5033.3  449.97  5122.3  450.08  5136.1  449.24  5195.6  449.96  5225.3  449.07
  5233.3  447.23  5248.2  446.18  5271.0  448.95  5298.5  448.80  5380.7  452.53
  5482.5  459.56  5591.7  470.05  5650.5  471.35  5694.7  470.46  5724.1  472.20
#Mann=4,-1,0
  4000.8    0.05       0  4646.5    0.12       0  5005.8    0.07       0
  5017.2    0.12       0
Bank Sta=4549,5380.7
Exp/Cntr=0.3,0.1

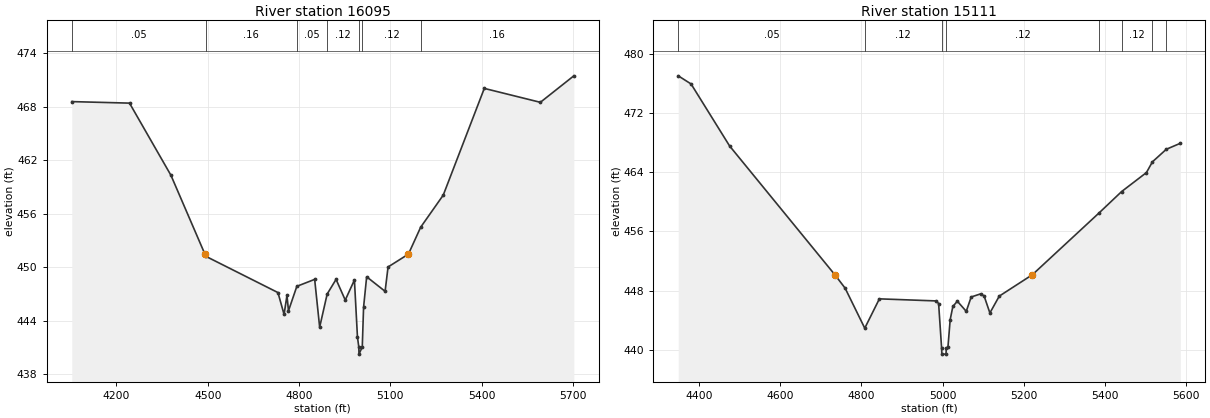
Type RM Length L Ch R = 1,16095,984,984,984
BEGIN DESCRIPTION:
CARROLL CREEK 18.0
END DESCRIPTION:
XS GIS Cut Line= 3
      2894129.32      7064021.89      2892964.66      7064133.92
      2892603.25      7064448.99
#Sta/Elev= 30
  4053.4  468.55  4243.1  468.38  4379.2  460.29  4490.7  451.46  4493.6  451.21
  4730.8  447.14  4750.9  444.69  4760.4  446.83  4765.4  445.10  4792.8  447.84
  4851.4  448.62  4867.8  443.26  4892.5  446.98  4921.7  448.62  4951.9  446.30
  4982.0  448.55  4992.0  442.15  4996.4  441.04  4997.0  440.24  5007.8  441.04
  5012.1  445.50  5022.2  448.91  5082.8  447.28  5092.5  450.01  5159.4  451.45
  5199.7  454.47  5273.9  458.07  5408.7  470.03  5592.9  468.47  5702.9  471.44
#Mann=7,-1,0
  4053.4    0.05       0  4493.6    0.16       0  4792.8    0.05       0
  4892.5    0.12       0  4996.4    0.07       0  5007.8    0.12       0
  5199.7    0.16       0
Bank Sta=4490.7,5159.4
Exp/Cntr=0.3,0.1

Type RM Length L Ch R = 1,15111,888,888,888
BEGIN DESCRIPTION:
CARROLL CREEK 17.0
END DESCRIPTION:
XS GIS Cut Line= 3
      2893825.02      7063374.99      2893225.00      7063575.00
      2892675.03      7063824.99
#Sta/Elev= 30
  4348.7  477.05  4380.3  475.95  4475.2  467.56  4734.5  450.13  4759.8  448.31
  4808.1  442.90  4844.1  446.87  4983.9  446.59  4990.0  446.24  4997.4  440.19
  4998.0  439.39  5008.2  439.39  5008.9  440.19  5013.0  440.35  5018.5  444.06
  5025.1  445.84  5036.1  446.55  5058.1  445.18  5070.2  447.12  5093.2  447.54
  5102.0  447.27  5116.3  444.96  5139.4  447.24  5220.8  450.13  5384.3  458.45
  5440.8  461.39  5501.9  463.96  5516.6  465.41  5550.8  467.11  5585.3  467.92
#Mann=8,-1,0
  4348.7    0.05       0  4808.1    0.12       0  4997.4    0.07       0
  5008.9    0.12       0  5384.3    0.16       0  5440.8    0.12       0
  5516.6    0.16       0  5550.8    0.05       0
Bank Sta=4734.5,5220.8
Exp/Cntr=0.3,0.1