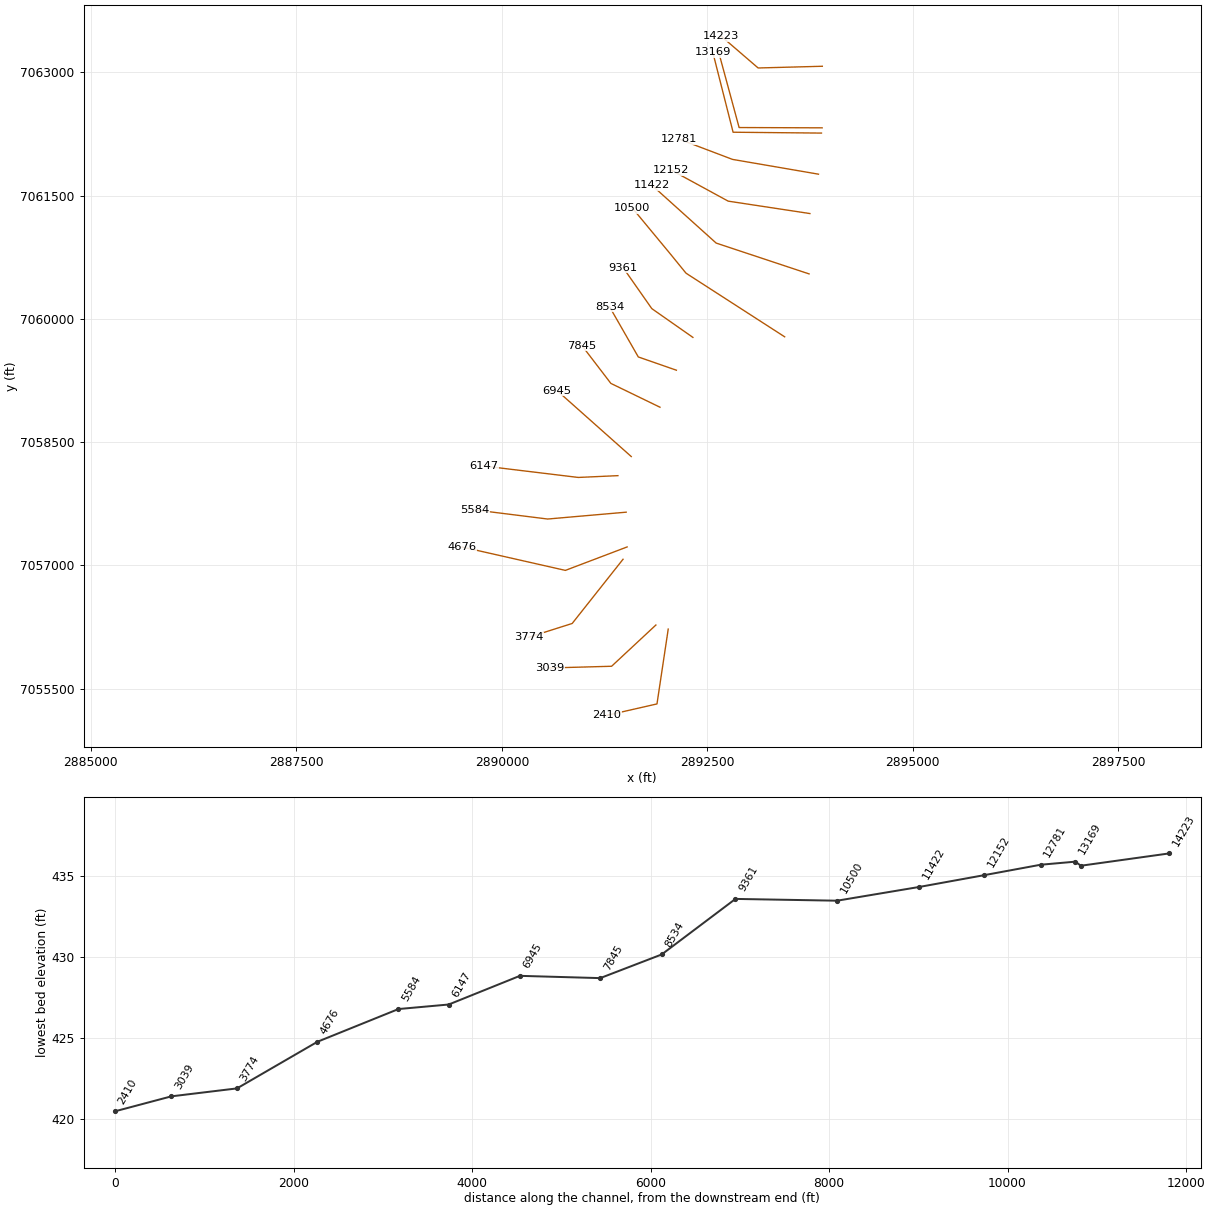
HEC-RAS study CARROLL CREEK.prj: CARROLL CREEK Base Level Engineering

--- CARROLL CREEK.g01 (geometry) --- (continued)

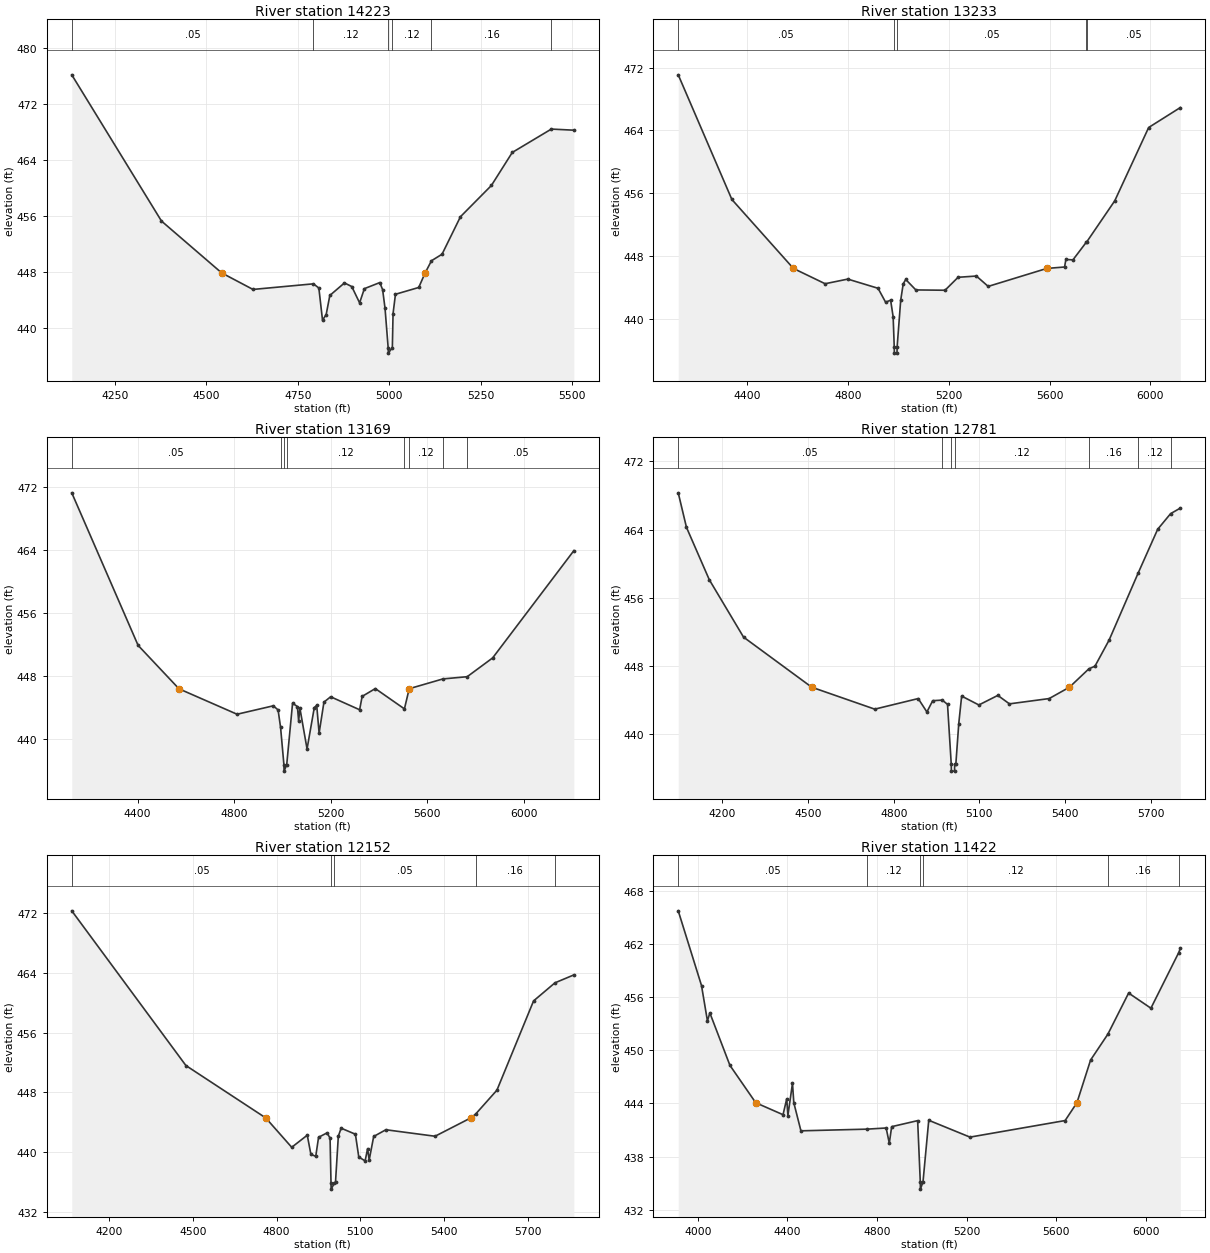
Type RM Length L Ch R = 1,14223,990,990,990
BEGIN DESCRIPTION:
CARROLL CREEK 16.0
END DESCRIPTION:
XS GIS Cut Line= 3
      2893900.11      7063073.97      2893118.90      7063053.14
      2892670.98      7063438.55
#Sta/Elev= 30
  4132.1  476.16  4377.3  455.27  4541.9  447.86  4627.4  445.50  4792.7  446.30
  4807.5  445.70  4817.5  441.11  4827.5  441.91  4837.5  444.64  4877.5  446.43
  4897.5  445.91  4918.9  443.58  4931.9  445.61  4974.1  446.48  4981.8  445.47
  4988.4  442.80  4996.9  437.20  4997.5  436.40  5008.4  437.20  5010.3  442.04
  5016.9  444.81  5080.5  445.78  5098.0  447.86  5115.4  449.60  5144.2  450.53
  5194.6  455.89  5279.1  460.35  5336.2  465.07  5443.0  468.41  5504.5  468.25
#Mann=6,-1,0
  4132.1    0.05       0  4792.7    0.12       0  4996.9    0.07       0
  5008.4    0.12       0  5115.4    0.16       0  5443.0    0.05       0
Bank Sta=4541.9,5098
Exp/Cntr=0.3,0.1

Type RM Length L Ch R = 1,13233,64,64,64
BEGIN DESCRIPTION:
Mapping XS 3204516a
END DESCRIPTION:
XS GIS Cut Line= 3
      2893897.94      7062324.84      2892887.56      7062328.31
      2892630.62      7063276.22
#Sta/Elev= 30
  4125.9  471.09  4338.8  455.21  4582.9  446.43  4708.8  444.48  4798.8  445.07
  4918.8  443.90  4948.8  442.13  4968.8  442.38  4978.8  440.26  4983.1  436.44
  4983.7  435.64  4994.0  435.64  4994.6  436.44  5008.8  442.39  5018.8  444.48
  5028.8  445.02  5068.8  443.69  5184.7  443.65  5236.5  445.30  5309.0  445.46
  5356.0  444.14  5588.8  446.43  5659.1  446.61  5664.3  447.57  5692.3  447.52
  5745.4  449.77  5747.3  449.82  5858.2  455.04  5992.8  464.38  6118.4  466.92
#Mann=5,-1,0
  4125.9    0.05       0  4983.1    0.07       0  4994.6    0.05       0
  5745.4    0.16       0  5747.3    0.05       0
Bank Sta=4582.9,5588.8
Exp/Cntr=0.3,0.1

Type RM Length L Ch R = 1,13169,388,388,388
BEGIN DESCRIPTION:
CARROLL CREEK 15.0
END DESCRIPTION:
XS GIS Cut Line= 3
      2893889.85      7062260.89      2892814.35      7062271.31
      2892566.97      7063245.24
#Sta/Elev= 30
  4126.9  471.26  4401.8  451.87  4571.3  446.35  4811.8  443.12  4961.8  444.19
  4981.8  443.67  4992.1  441.45  5006.0  436.69  5006.6  435.89  5017.5  436.69
  5041.8  444.52  5061.8  444.10  5067.0  442.25  5072.0  443.92  5101.8  438.71
  5131.8  443.96  5141.8  444.25  5151.8  440.72  5171.8  444.66  5199.6  445.34
  5319.7  443.69  5330.1  445.39  5384.7  446.38  5505.3  443.80  5525.0  446.35
  5525.6  446.37  5665.0  447.61  5765.4  447.89  5870.9  450.28  6207.3  463.91
#Mann=8,-1,0
  4126.9    0.05       0  4992.1    0.12       0  5006.0    0.07       0
  5017.5    0.12       0  5505.3    0.07       0  5525.6    0.12       0
  5665.0    0.07       0  5765.4    0.05       0
Bank Sta=4571.3,5525
Exp/Cntr=0.3,0.1

Type RM Length L Ch R = 1,12781,629,629,629
BEGIN DESCRIPTION:
CARROLL CREEK 14.0
END DESCRIPTION:
XS GIS Cut Line= 3
      2893853.37      7061760.90      2892806.91      7061940.75
      2892155.46      7062187.99
#Sta/Elev= 30
  4045.0  468.30  4073.8  464.26  4153.8  458.12  4273.7  451.40  4512.6  445.53
  4733.3  442.96  4885.5  444.20  4916.0  442.63  4936.3  443.95  4969.8  444.02
  4988.2  443.52  5001.3  436.50  5001.8  435.70  5012.7  435.70  5013.3  436.50
  5017.4  436.54  5027.6  441.27  5037.7  444.49  5098.0  443.45  5164.4  444.57
  5205.1  443.58  5344.2  444.20  5415.3  445.53  5483.2  447.68  5504.6  447.99
  5554.2  451.05  5656.2  458.92  5724.3  464.03  5769.6  465.86  5803.6  466.51
#Mann=7,-1,0
  4045.0    0.05       0  4969.8    0.12       0  5001.3    0.07       0
  5013.3    0.12       0  5483.2    0.16       0  5656.2    0.12       0
  5769.6    0.16       0
Bank Sta=4512.6,5415.3
Exp/Cntr=0.3,0.1

Type RM Length L Ch R = 1,12152,730,730,730
BEGIN DESCRIPTION:
CARROLL CREEK 13.0
END DESCRIPTION:
XS GIS Cut Line= 3
      2893749.26      7061281.72      2892754.46      7061432.77
      2892058.27      7061812.04
#Sta/Elev= 30
  4066.0  472.32  4474.9  451.61  4761.2  444.59  4854.1  440.66  4909.8  442.28
  4922.8  439.72  4940.2  439.45  4950.3  442.00  4980.6  442.59  4991.5  441.89
  4994.9  435.86  4995.4  435.06  5006.9  435.86  5011.0  436.00  5021.1  442.14
  5031.2  443.22  5082.3  442.41  5094.4  439.36  5117.1  438.84  5126.0  440.48
  5131.7  438.96  5147.8  442.11  5191.5  443.01  5367.7  442.14  5495.5  444.59
  5513.3  445.12  5589.4  448.31  5720.7  460.26  5797.3  462.68  5865.0  463.74
#Mann=5,-1,0
  4066.0    0.05       0  4994.9    0.07       0  5006.9    0.05       0
  5513.3    0.16       0  5797.3    0.05       0
Bank Sta=4761.2,5495.5
Exp/Cntr=0.3,0.1

Type RM Length L Ch R = 1,11422,922,922,922
BEGIN DESCRIPTION:
CARROLL CREEK 12.0
END DESCRIPTION:
XS GIS Cut Line= 3
      2893738.81      7060547.36      2892608.62      7060922.35
      2891828.66      7061624.32
#Sta/Elev= 30
  3912.9  465.74  4016.8  457.30  4043.2  453.31  4053.9  454.22  4143.5  448.30
  4258.7  444.08  4380.5  442.73  4397.0  444.53  4402.2  442.63  4422.6  446.27
  4428.6  444.07  4460.3  440.91  4755.2  441.10  4840.5  441.23  4854.6  439.52
  4865.2  441.38  4981.1  442.06  4992.9  435.13  4993.4  434.33  5004.9  435.13
  5030.6  442.10  5214.6  440.20  5639.1  442.07  5691.7  444.08  5752.7  448.90
  5829.8  451.82  5922.4  456.46  6021.8  454.75  6145.8  461.02  6153.0  461.49
#Mann=6,-1,0
  3912.9    0.05       0  4755.2    0.12       0  4992.9    0.07       0
  5004.9    0.12       0  5829.8    0.16       0  6145.8    0.05       0
Bank Sta=4258.7,5691.7
Exp/Cntr=0.3,0.1

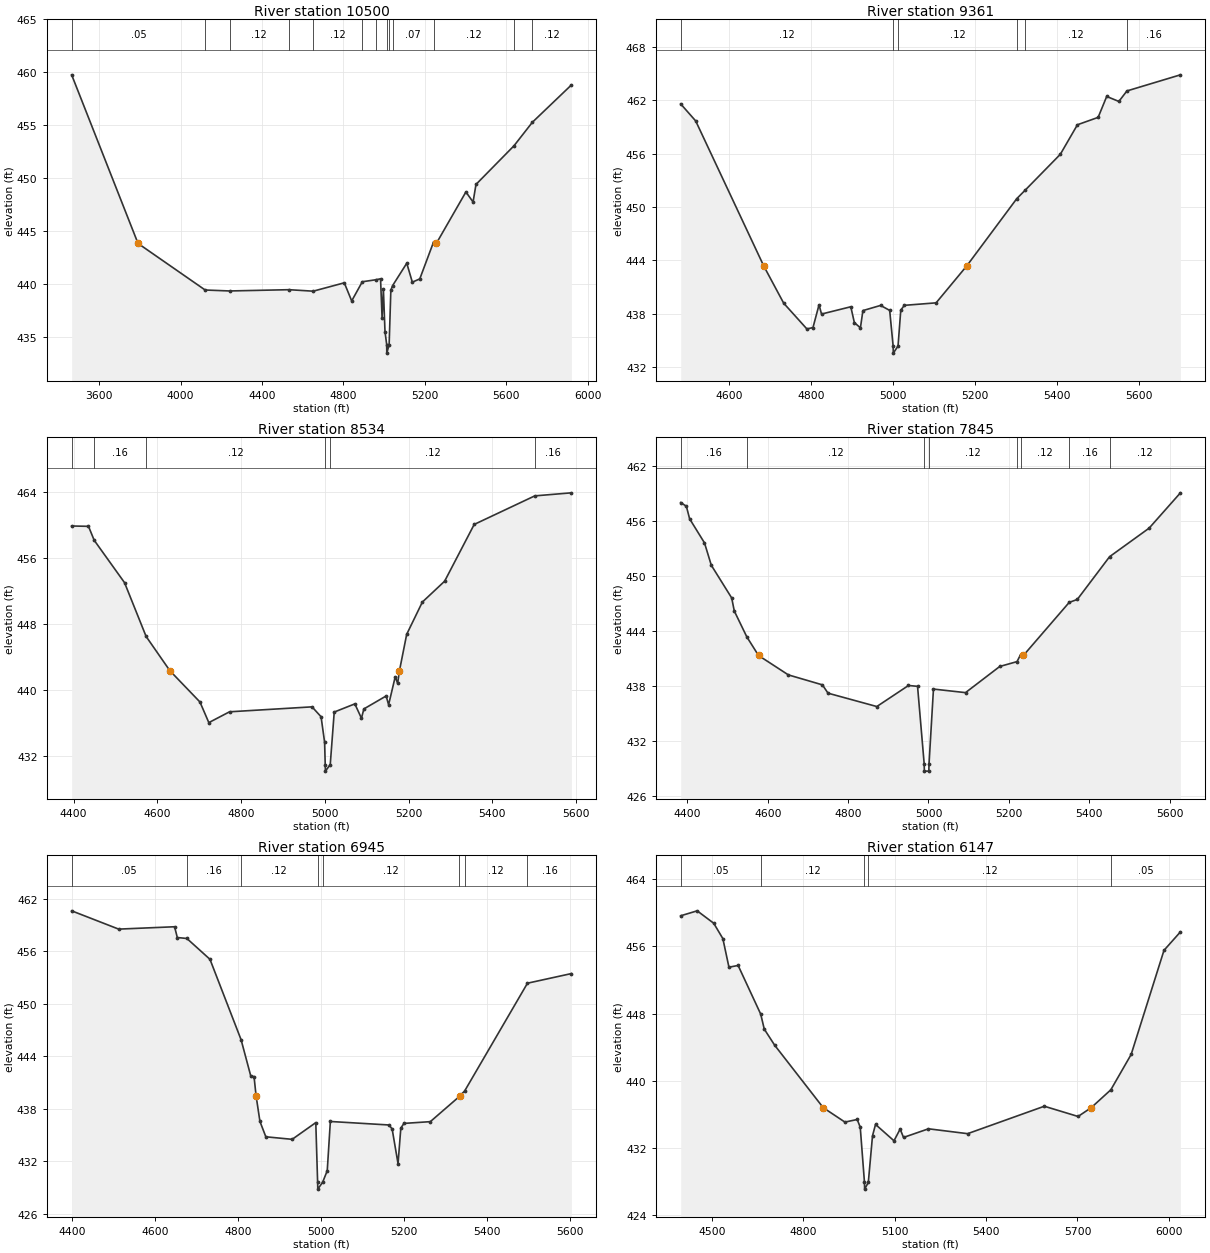
Type RM Length L Ch R = 1,10500,1139,1139,1139
BEGIN DESCRIPTION:
CARROLL CREEK 11.0
END DESCRIPTION:
XS GIS Cut Line= 4
      2893441.92      7059781.75      2892241.83      7060555.75
      2892038.72      7060804.87      2891588.87      7061348.13
#Sta/Elev= 30
  3464.7  459.76  3790.7  443.84  4120.5  439.44  4240.2  439.35  4532.3  439.47
  4651.3  439.33  4804.0  440.12  4840.3  438.41  4892.5  440.22  4959.6  440.41
  4982.1  440.50  4989.6  436.84  4996.0  439.53  5003.9  435.52  5012.3  434.28
  5012.8  433.48  5024.3  434.28  5032.7  439.42  5041.4  439.86  5110.9  441.97
  5138.2  440.18  5174.8  440.49  5242.7  443.98  5256.2  443.84  5401.4  448.70
  5436.6  447.75  5450.9  449.41  5637.6  453.06  5727.9  455.28  5919.5  458.80
#Mann=13,-1,0
  3464.7    0.05       0  4120.5    0.07       0  4240.2    0.12       0
  4532.3    0.07       0  4651.3    0.12       0  4892.5    0.07       0
  4959.6    0.12       0  5012.3    0.07       0  5024.3    0.12       0
  5041.4    0.07       0  5242.7    0.12       0  5637.6    0.16       0
  5727.9    0.12       0
Bank Sta=3790.7,5256.2
Exp/Cntr=0.3,0.1

Type RM Length L Ch R = 1,9361,827,827,827
BEGIN DESCRIPTION:
CARROLL CREEK 10.0
END DESCRIPTION:
XS GIS Cut Line= 3
      2892325.02      7059774.98      2891825.00      7060125.00
      2891474.99      7060625.01
#Sta/Elev= 30
  4481.1  461.59  4517.7  459.68  4684.1  443.37  4732.7  439.20  4789.3  436.31
  4804.2  436.46  4819.0  439.02  4825.1  437.98  4896.6  438.80  4905.3  437.02
  4920.1  436.43  4926.2  438.37  4969.4  438.95  4991.6  438.39  5000.0  434.39
  5000.5  433.59  5012.0  434.39  5018.7  438.42  5027.4  438.96  5105.0  439.24
  5179.5  443.37  5301.9  450.94  5323.2  451.93  5408.4  455.93  5450.2  459.25
  5500.8  460.08  5521.7  462.43  5551.4  461.87  5571.1  463.05  5701.8  464.86
#Mann=6,-1,0
  4481.1    0.12       0  5000.0    0.07       0  5012.0    0.12       0
  5301.9    0.16       0  5323.2    0.12       0  5571.1    0.16       0
Bank Sta=4684.1,5179.5
Exp/Cntr=0.3,0.1

Type RM Length L Ch R = 1,8534,689,689,689
BEGIN DESCRIPTION:
CARROLL CREEK 9.0
END DESCRIPTION:
XS GIS Cut Line= 3
      2892124.28      7059375.47      2891660.71      7059536.93
      2891311.75      7060146.30
#Sta/Elev= 30
  4395.4  459.87  4435.6  459.83  4449.2  458.14  4521.7  453.00  4573.2  446.48
  4630.1  442.32  4701.7  438.54  4722.9  436.04  4772.3  437.35  4969.3  437.95
  4990.9  436.75  4999.3  433.67  5000.8  430.96  5001.3  430.16  5012.8  430.96
  5022.3  437.32  5071.5  438.31  5087.3  436.57  5093.1  437.70  5146.3  439.27
  5152.1  438.20  5167.9  441.59  5173.7  440.81  5178.0  442.32  5195.3  446.74
  5232.7  450.65  5285.9  453.18  5356.5  460.06  5501.1  463.52  5588.5  463.89
#Mann=6,-1,0
  4395.4    0.05       0  4449.2    0.16       0  4573.2    0.12       0
  5000.8    0.07       0  5012.8    0.12       0  5501.1    0.16       0
Bank Sta=4630.1,5178
Exp/Cntr=0.3,0.1

Type RM Length L Ch R = 1,7845,900,900,900
BEGIN DESCRIPTION:
CARROLL CREEK 8.0
END DESCRIPTION:
XS GIS Cut Line= 3
      2891925.00      7058925.00      2891327.24      7059214.85
      2890975.01      7059674.99
#Sta/Elev= 30
  4383.3  458.06  4397.4  457.65  4405.5  456.28  4442.5  453.65  4459.5  451.20
  4510.2  447.63  4516.7  446.20  4547.8  443.38  4577.0  441.34  4651.2  439.22
  4736.0  438.13  4750.0  437.22  4871.4  435.76  4950.2  438.06  4972.8  437.97
  4989.3  429.50  4989.8  428.70  5000.9  428.70  5001.4  429.50  5012.4  437.67
  5092.2  437.28  5177.4  440.14  5220.4  440.67  5229.2  441.43  5236.2  441.34
  5350.2  447.14  5370.5  447.47  5450.8  452.14  5549.2  455.26  5627.1  459.12
#Mann=8,-1,0
  4383.3    0.16       0  4547.8    0.12       0  4989.3    0.07       0
  5001.4    0.12       0  5220.4    0.16       0  5229.2    0.12       0
  5350.2    0.16       0  5450.8    0.12       0
Bank Sta=4577,5236.2
Exp/Cntr=0.3,0.1

Type RM Length L Ch R = 1,6945,798,798,798
BEGIN DESCRIPTION:
CARROLL CREEK 7.0
END DESCRIPTION:
XS GIS Cut Line= 3
      2891575.01      7058324.99      2891125.00      7058725.00
      2890674.98      7059125.02
#Sta/Elev= 30
  4398.4  460.64  4511.7  458.55  4646.4  458.82  4653.0  457.59  4676.1  457.48
  4731.7  455.10  4806.7  445.91  4830.3  441.72  4837.9  441.70  4842.8  439.51
  4852.1  436.58  4866.3  434.82  4929.8  434.53  4986.7  436.44  4991.1  429.64
  4991.6  428.84  5003.3  429.64  5014.3  430.94  5021.8  436.57  5163.1  436.17
  5170.7  435.71  5184.9  431.75  5191.6  435.81  5199.1  436.35  5262.7  436.55
  5330.6  439.34  5333.6  439.52  5345.1  440.03  5496.8  452.37  5602.6  453.47
#Mann=8,-1,0
  4398.4    0.05       0  4676.1    0.16       0  4806.7    0.12       0
  4991.1    0.07       0  5003.3    0.12       0  5330.6    0.16       0
  5345.1    0.12       0  5496.8    0.16       0
Bank Sta=4842.8,5333.6
Exp/Cntr=0.3,0.1

Type RM Length L Ch R = 1,6147,563,563,563
BEGIN DESCRIPTION:
CARROLL CREEK 6.0
END DESCRIPTION:
XS GIS Cut Line= 3
      2891413.27      7058092.49      2890930.99      7058070.58
      2889781.35      7058209.68
#Sta/Elev= 30
  4397.3  459.65  4451.4  460.24  4505.7  458.76  4535.7  456.93  4555.7  453.52
  4585.8  453.73  4660.0  447.93  4671.7  446.14  4705.9  444.22  4865.2  436.78
  4936.5  435.06  4976.8  435.37  4986.8  434.45  5000.7  427.87  5001.2  427.07
  5013.3  427.87  5027.1  433.43  5037.0  434.78  5097.6  432.83  5117.8  434.23
  5128.9  433.23  5210.9  434.26  5339.4  433.68  5591.2  436.95  5702.0  435.73
  5745.2  436.78  5809.6  438.91  5876.3  443.12  5984.1  455.53  6038.1  457.73
#Mann=5,-1,0
  4397.3    0.05       0  4660.0    0.12       0  5000.7    0.07       0
  5013.3    0.12       0  5809.6    0.05       0
Bank Sta=4865.2,5745.2
Exp/Cntr=0.3,0.1

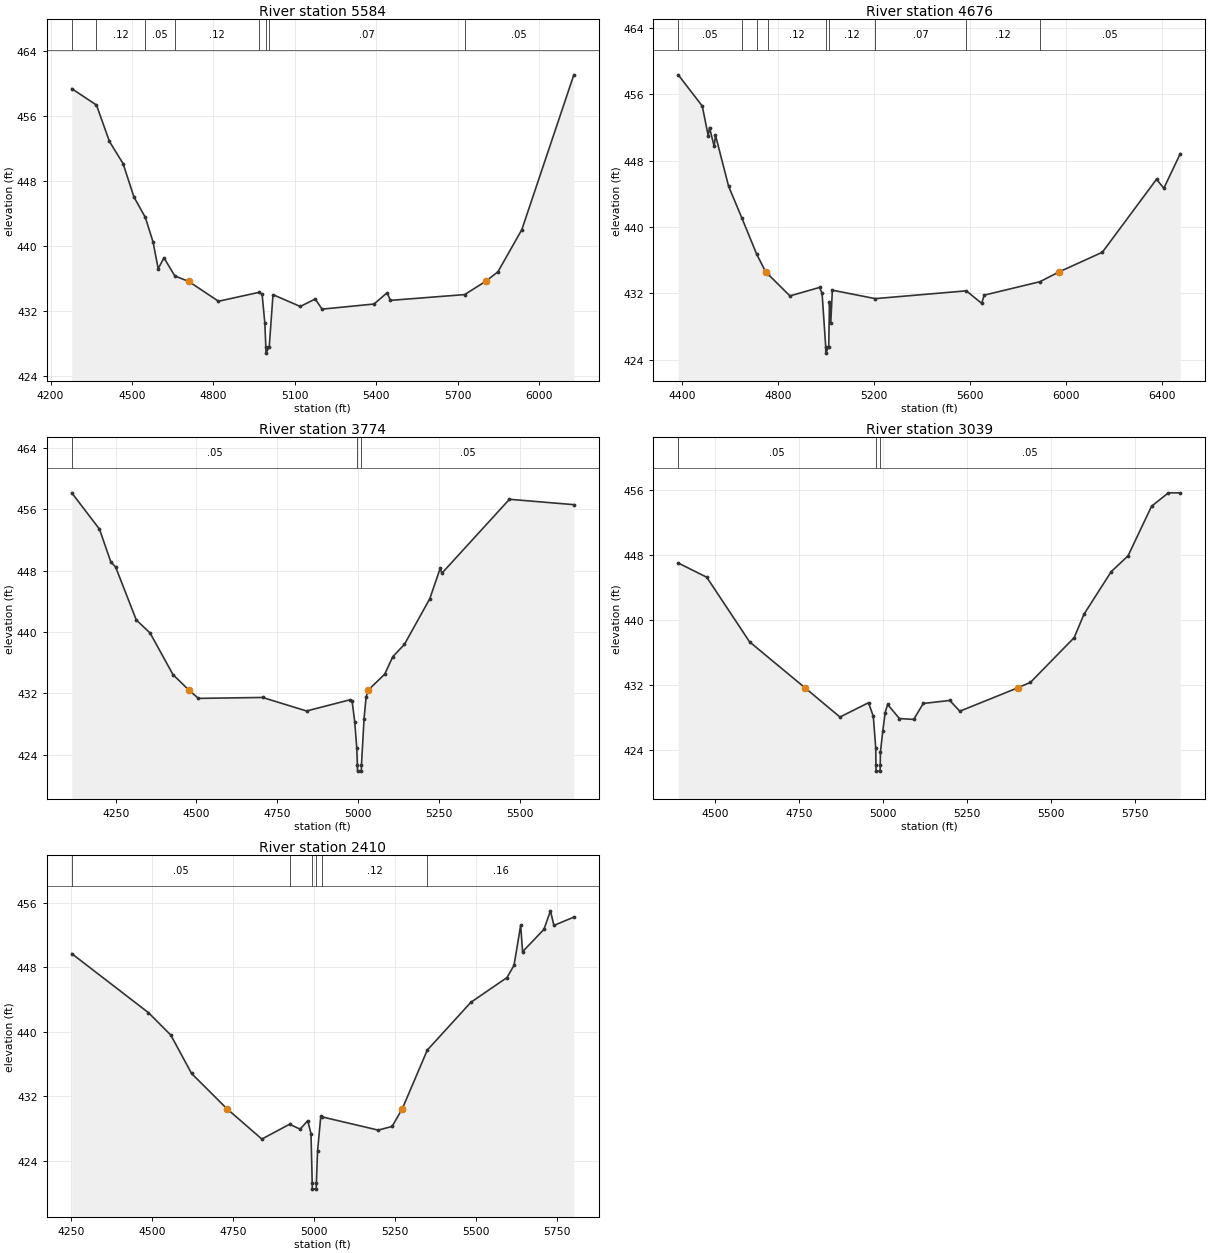
Type RM Length L Ch R = 1,5584,908,908,908
BEGIN DESCRIPTION:
CARROLL CREEK 5.0
END DESCRIPTION:
XS GIS Cut Line= 3
      2891513.11      7057648.04      2890558.26      7057564.59
      2889675.02      7057675.00
#Sta/Elev= 30
  4278.3  459.32  4369.3  457.30  4416.9  452.83  4467.1  450.11  4507.3  445.99
  4549.0  443.49  4577.5  440.48  4596.5  437.17  4617.7  438.51  4657.9  436.28
  4709.0  435.61  4818.5  433.17  4966.7  434.26  4979.1  434.05  4989.1  430.50
  4992.8  427.59  4993.3  426.79  5005.4  427.59  5019.2  433.98  5119.6  432.53
  5174.7  433.45  5199.9  432.20  5391.2  432.83  5439.1  434.21  5451.7  433.28
  5724.7  433.99  5801.8  435.61  5847.3  436.79  5935.4  441.98  6126.9  461.02
#Mann=8,-1,0
  4278.3    0.05       0  4369.3    0.12       0  4549.0    0.05       0
  4657.9    0.12       0  4966.7    0.07       0  4992.8    0.07       0
  5005.4    0.07       0  5724.7    0.05       0
Bank Sta=4709,5801.8
Exp/Cntr=0.3,0.1

Type RM Length L Ch R = 1,4676,902,902,902
BEGIN DESCRIPTION:
CARROLL CREEK 4.0
END DESCRIPTION:
XS GIS Cut Line= 3
      2891524.98      7057224.99      2890773.56      7056939.71
      2889518.31      7057224.05
#Sta/Elev= 30
  4383.7  458.37  4483.8  454.60  4508.6  451.00  4513.9  452.01  4533.4  449.73
  4538.7  451.09  4593.6  444.90  4649.4  441.04  4710.2  436.73  4747.8  434.58
  4758.8  434.27  4848.8  431.68  4972.0  432.70  4982.7  432.01  4997.8  425.57
  4998.3  424.77  5010.4  425.57  5013.5  430.92  5018.9  428.45  5025.5  432.37
  5204.2  431.35  5583.3  432.29  5647.4  430.78  5657.6  431.77  5889.6  433.39
  5969.9  434.58  6149.8  436.95  6375.4  445.76  6405.9  444.68  6474.5  448.86
#Mann=9,-1,0
  4383.7    0.05       0  4649.4    0.16       0  4710.2    0.05       0
  4758.8    0.12       0  4997.8    0.07       0  5010.4    0.12       0
  5204.2    0.07       0  5583.3    0.12       0  5889.6    0.05       0
Bank Sta=4747.8,5969.9
Exp/Cntr=0.3,0.1

Type RM Length L Ch R = 1,3774,735,735,735
BEGIN DESCRIPTION:
CARROLL CREEK 3.0
END DESCRIPTION:
XS GIS Cut Line= 3
      2891475.03      7057075.04      2890856.28      7056293.73
      2890324.97      7056124.99
#Sta/Elev= 30
  4114.0  458.12  4199.8  453.39  4235.0  449.11  4249.5  448.49  4313.6  441.58
  4356.4  439.87  4427.4  434.45  4476.6  432.44  4505.9  431.36  4704.6  431.48
  4840.8  429.72  4975.4  431.18  4981.8  430.98  4989.9  428.30  4996.2  424.89
  4998.0  422.69  4998.5  421.89  5010.2  421.89  5010.7  422.69  5018.7  428.70
  5025.1  431.56  5031.7  432.44  5082.8  434.52  5107.6  436.79  5143.5  438.38
  5222.1  444.33  5254.4  448.28  5259.6  447.65  5468.7  457.28  5668.1  456.58
#Mann=3,-1,0
  4114.0    0.05       0  4998.0    0.03       0  5010.7    0.05       0
Bank Sta=4476.6,5031.7
Exp/Cntr=0.3,0.1

Type RM Length L Ch R = 1,3039,629,629,629
BEGIN DESCRIPTION:
CARROLL CREEK 2.0
END DESCRIPTION:
XS GIS Cut Line= 3
      2891875.02      7056275.02      2891336.06      7055773.05
      2890579.56      7055752.23
#Sta/Elev= 30
  4390.9  447.02  4475.7  445.27  4603.2  437.31  4767.6  431.67  4871.9  428.06
  4956.9  429.82  4971.1  428.15  4978.4  424.21  4978.9  422.20  4979.4  421.40
  4991.2  421.40  4991.7  422.20  4992.2  423.70  4999.4  426.38  5006.3  428.59
  5013.6  429.61  5048.8  427.87  5091.3  427.77  5119.6  429.73  5198.5  430.10
  5228.5  428.78  5401.6  431.67  5438.6  432.33  5568.6  437.84  5597.6  440.71
  5678.7  445.96  5728.7  447.90  5798.7  454.01  5848.7  455.66  5884.2  455.66
#Mann=3,-1,0
  4390.9    0.05       0  4978.9    0.03       0  4991.7    0.05       0
Bank Sta=4767.6,5401.6
Exp/Cntr=0.3,0.1

Type RM Length L Ch R = 1,2410,0,0,0
BEGIN DESCRIPTION:
CARROLL CREEK 1.0
END DESCRIPTION:
XS GIS Cut Line= 3
      2892025.01      7056225.05      2891888.14      7055314.71
      2891275.02      7055175.00
#Sta/Elev= 30
  4251.7  449.69  4488.3  442.37  4557.3  439.59  4621.3  434.83  4730.3  430.46
  4838.3  426.69  4923.9  428.53  4956.3  427.92  4979.8  428.96  4990.0  427.37
  4993.7  421.28  4994.2  420.48  5006.0  420.48  5006.5  421.28  5010.2  425.22
  5020.2  429.53  5023.1  429.45  5197.3  427.80  5240.3  428.26  5271.8  430.46
  5348.9  437.73  5483.2  443.65  5594.7  446.72  5616.5  448.24  5637.0  453.21
  5642.9  449.93  5708.8  452.70  5728.9  455.00  5739.6  453.19  5801.1  454.22
#Mann=6,-1,0
  4251.7    0.05       0  4923.9    0.16       0  4993.7    0.07       0
  5006.5    0.16       0  5023.1    0.12       0  5348.9    0.16       0
Bank Sta=4730.3,5271.8
Exp/Cntr=0.3,0.1

Chan Stop Cuts=-1