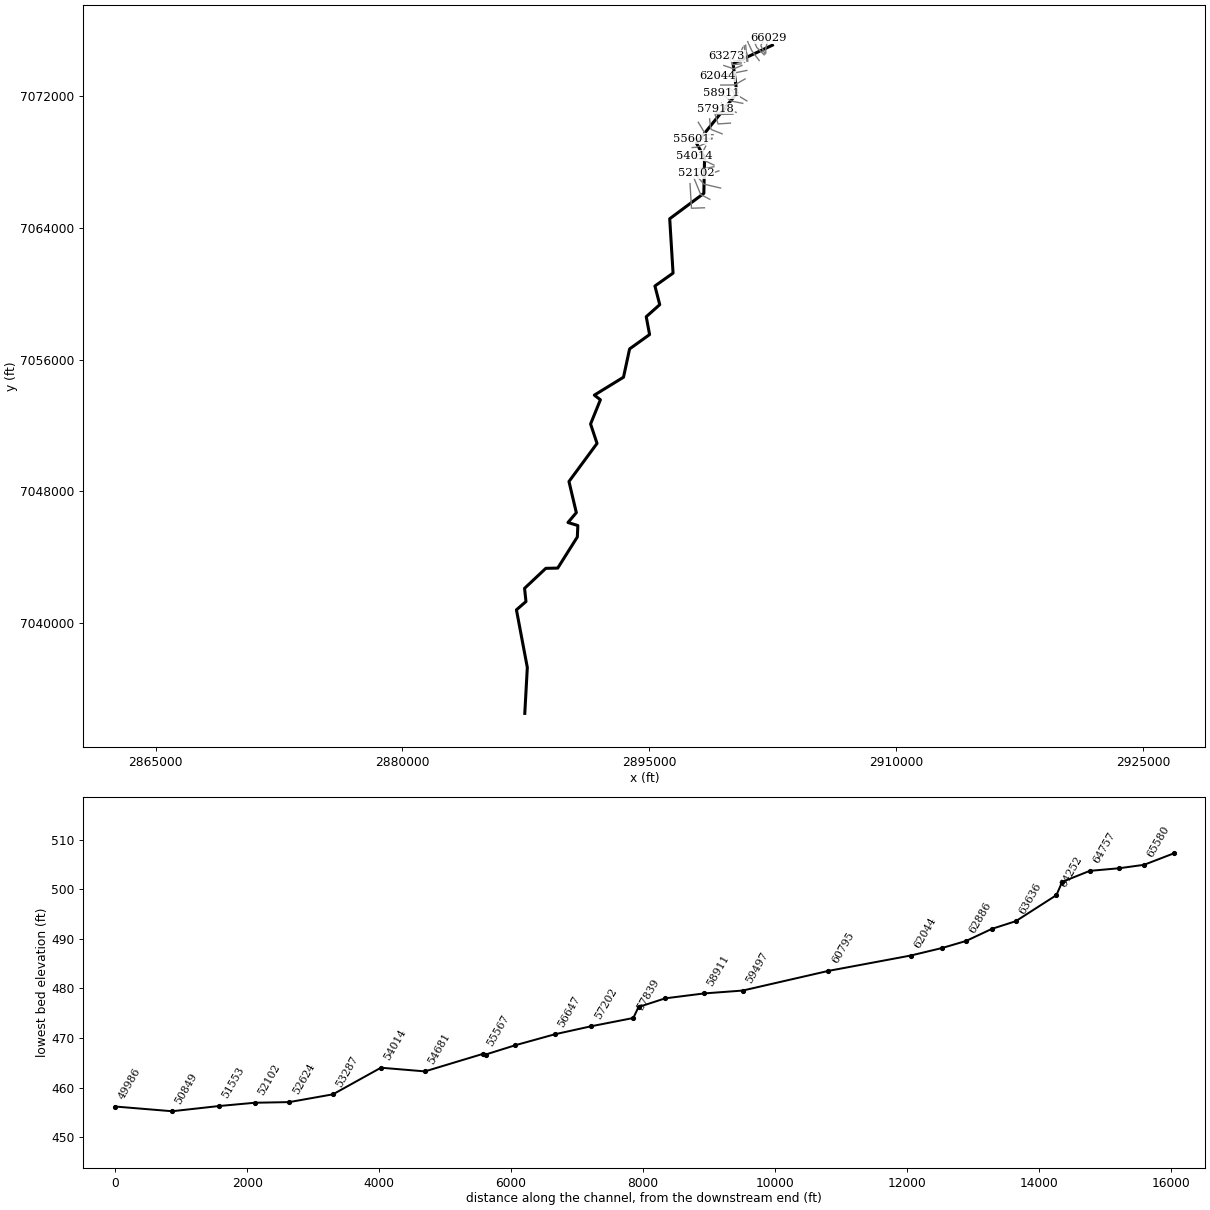
--- COFFEE CREEK.prj (project) ---

Proj Title=COFFEE CREEK Base Level Engineering
Current Plan=p01
Default Exp/Contr=0.3,0.1
English Units
Geom File=g01
Flow File=f01
Plan File=p01
BEGIN DESCRIPTION:
COFFEE CREEK
END DESCRIPTION:

--- COFFEE CREEK.p01 (plan) ---

Plan Title=Multiple Run
Short Identifier=Multiple
Geom File=g01
Flow File=f01
Subcritical Flow
K Sum by GR= 0
Std Step Tol= 0.01
Critical Tol= 0.01
Num of Std Step Trials= 20
Max Error Tol= 0.3
Flow Tol Ratio= 0.001
Split Flow NTrial= 30
Split Flow Tol= 0.02
Split Flow Ratio= 0.02
Log Output Level= 0
Friction Slope Method= 1
Unsteady Friction Slope Method= 2
Unsteady Bridges Friction Slope Method= 1
Parabolic Critical Depth
Global Vel Dist=  1 , 1 , 1
Global Log Level= 0
CheckData=True
Encroach Param= -1, 0, 0, 0
BEGIN DESCRIPTION:
Multiple Run
END DESCRIPTION:

--- COFFEE CREEK.f01 (steady flow) ---

Flow Title=Multiple
Number of Profiles=7
Profile Names=10-year,25-year,50-year,1pct_min,100-year,1pct_plu,500-year
River Rch & RM= COFFEE CREEK,Reach-1,66029
     381     488     571     332     662    1321     888
River Rch & RM= COFFEE CREEK,Reach-1,63273
     797    1071    1294     775    1546    3084    2201
River Rch & RM= COFFEE CREEK,Reach-1,60795
     884    1195    1449     870    1737    3465    2490
River Rch & RM= COFFEE CREEK,Reach-1,58911
    1364    1883    2314    1407    2807    5601    4124
River Rch & RM= COFFEE CREEK,Reach-1,53287
    2138    3007    3741    2298    4586    9149    6882
River Rch & RM= COFFEE CREEK,Reach-1,46350
    2735    3880    4855    2997    5980   11932    9066
River Rch & RM= COFFEE CREEK,Reach-1,37805
    2934    4176    5238    3242    6468   12905    9858
River Rch & RM= COFFEE CREEK,Reach-1,31065
    4910    7078    8956    5582   11138   22223   17216
River Rch & RM= COFFEE CREEK,Reach-1,24012
    4956    7139    9029    5624   11222   22390   17330
River Rch & RM= COFFEE CREEK,Reach-1,14251
    4925    7072    8925    5548   11069   22086   17024
River Rch & RM= COFFEE CREEK,Reach-1,6863
    4979    7133    8989    5579   11132   22212   17073
Boundary for River Rch & Prof#=COFFEE CREEK,Reach-1,1
Up Type=0
Dn Type=3
Dn Slope=0.005
Boundary for River Rch & Prof#=COFFEE CREEK,Reach-1,2
Up Type=0
Dn Type=3
Dn Slope=0.005
Boundary for River Rch & Prof#=COFFEE CREEK,Reach-1,3
Up Type=0
Dn Type=3
Dn Slope=0.005
Boundary for River Rch & Prof#=COFFEE CREEK,Reach-1,4
Up Type=0
Dn Type=3
Dn Slope=0.005
Boundary for River Rch & Prof#=COFFEE CREEK,Reach-1,5
Up Type=0
Dn Type=3
Dn Slope=0.005
Boundary for River Rch & Prof#=COFFEE CREEK,Reach-1,6
Up Type=0
Dn Type=3
Dn Slope=0.005
Boundary for River Rch & Prof#=COFFEE CREEK,Reach-1,7
Up Type=0
Dn Type=3
Dn Slope=0.005

--- COFFEE CREEK.g01 (geometry) ---

Geom Title=Existing Conditions

River Reach=COFFEE CREEK,Reach-1
Reach XY= 30
      2902476.09      7075109.55      2900088.04      7073984.92
      2900320.33      7072197.62      2897866.04      7069148.28
      2898355.59      7068270.71      2898311.22      7066107.80
      2896237.71      7064564.95      2896441.14      7061261.94
      2895338.88      7060479.54      2895633.04      7059346.34
      2894811.26      7058613.50      2895015.69      7057529.73
      2893801.51      7056657.66      2893430.68      7054937.96
      2891659.12      7053849.44      2892027.19      7053568.01
      2891430.47      7052096.01      2891823.17      7050916.61
      2890117.90      7048602.19      2890564.92      7046709.41
      2890057.90      7046111.82      2890656.67      7045927.13
      2890626.09      7045233.07      2889435.60      7043342.64
      2888710.96      7043327.35      2887420.48      7042113.34
      2887505.18      7041308.70      2886926.41      7040806.39
      2887587.72      7037304.26      2887433.32      7034516.07

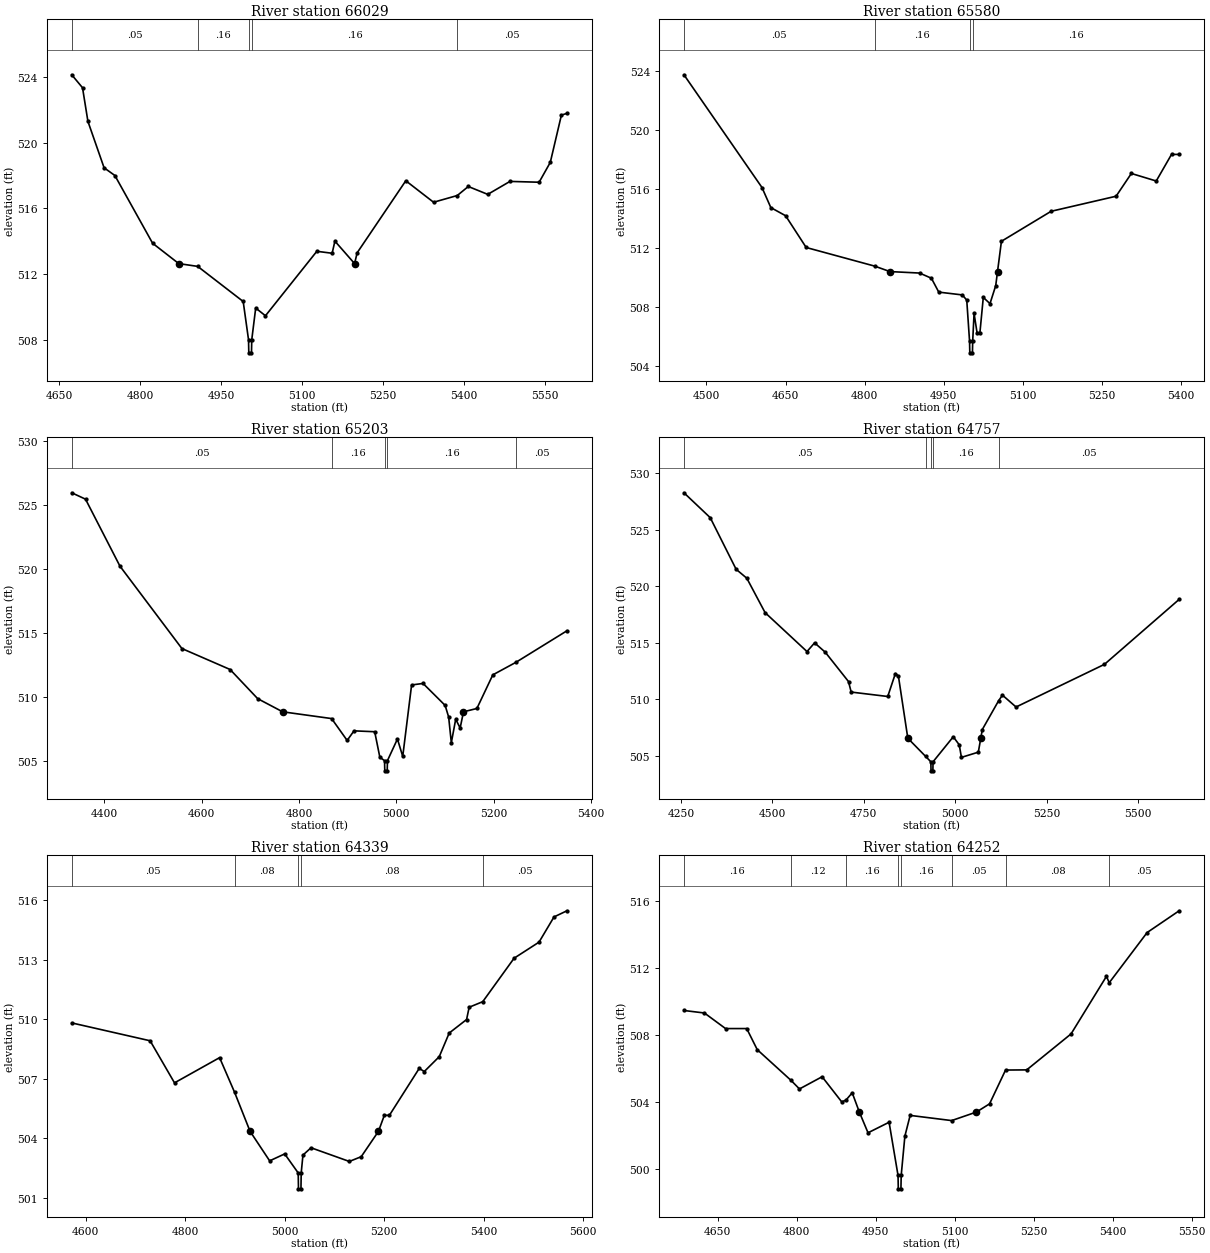
Type RM Length L Ch R = 1,66029,449,449,449
BEGIN DESCRIPTION:
COFFEE CREEK 71.0
END DESCRIPTION:
XS GIS Cut Line= 3
      2902075.00      7074624.99      2902075.00      7074925.00
      2902225.01      7075525.02
#Sta/Elev= 30
  4672.8  524.15  4692.8  523.36  4702.8  521.31  4732.8  518.48  4752.8  518.01
  4822.8  513.88  4871.3  512.64  4906.4  512.47  4990.8  510.33  5000.7  508.00
  5001.2  507.20  5006.2  507.20  5006.7  508.00  5014.0  509.93  5032.1  509.46
  5127.4  513.39  5155.8  513.27  5160.9  514.01  5197.4  512.64  5202.2  513.30
  5292.4  517.69  5343.9  516.38  5387.9  516.79  5408.3  517.34  5444.4  516.86
  5485.6  517.65  5539.7  517.60  5560.4  518.81  5581.0  521.69  5591.3  521.80
#Mann=5,-1,0
  4672.8    0.05       0  4906.4    0.16       0  5000.7    0.07       0
  5006.7    0.16       0  5387.9    0.05       0
Bank Sta=4871.3,5197.4
Exp/Cntr=0.3,0.1

Type RM Length L Ch R = 1,65580,377,377,377
BEGIN DESCRIPTION:
COFFEE CREEK 70.0
END DESCRIPTION:
XS GIS Cut Line= 3
      2902025.00      7074574.99      2901775.00      7075075.00
      2901925.00      7075424.99
#Sta/Elev= 30
  4457.2  523.72  4605.3  516.09  4622.1  514.73  4650.1  514.18  4689.2  512.03
  4819.1  510.77  4848.1  510.40  4904.4  510.30  4926.8  509.95  4940.8  509.01
  4985.5  508.82  4993.9  508.47  4999.2  505.70  4999.7  504.90  5004.7  504.90
  5005.2  505.70  5007.8  507.57  5013.4  506.27  5018.9  506.27  5025.3  508.65
  5038.0  508.23  5048.9  509.45  5052.3  510.40  5059.7  512.45  5154.0  514.48
  5277.3  515.50  5306.3  517.04  5353.5  516.53  5382.5  518.33  5397.0  518.33
#Mann=4,-1,0
  4457.2    0.05       0  4819.1    0.16       0  4999.2    0.07       0
  5005.2    0.16       0
Bank Sta=4848.1,5052.3
Exp/Cntr=0.3,0.1

Type RM Length L Ch R = 1,65203,446,446,446
BEGIN DESCRIPTION:
COFFEE CREEK 69.0
END DESCRIPTION:
XS GIS Cut Line= 3
      2901975.01      7074524.99      2901525.00      7074975.00
      2901375.00      7075325.00
#Sta/Elev= 30
  4333.4  525.97  4361.7  525.47  4432.4  520.23  4559.7  513.78  4658.7  512.14
  4715.3  509.86  4766.6  508.83  4867.2  508.30  4899.1  506.59  4913.2  507.34
  4955.7  507.27  4966.3  505.27  4975.9  505.01  4976.4  504.21  4981.4  504.21
  4981.9  505.01  5002.4  506.70  5013.3  505.34  5031.5  510.93  5055.0  511.05
  5100.4  509.33  5107.6  508.42  5113.1  506.41  5122.1  508.25  5131.2  507.56
  5138.1  508.83  5165.6  509.09  5198.3  511.72  5245.7  512.70  5350.6  515.17
#Mann=5,-1,0
  4333.4    0.05       0  4867.2    0.16       0  4975.9    0.07       0
  4981.9    0.16       0  5245.7    0.05       0
Bank Sta=4766.6,5138.1
Exp/Cntr=0.3,0.1

Type RM Length L Ch R = 1,64757,418,418,418
BEGIN DESCRIPTION:
COFFEE CREEK 68.0
END DESCRIPTION:
XS GIS Cut Line= 3
      2901675.02      7074174.97      2901225.00      7074775.00
      2900974.99      7075325.01
#Sta/Elev= 30
  4258.0  528.25  4329.9  526.05  4400.7  521.49  4429.9  520.70  4479.9  517.66
  4594.5  514.22  4615.3  514.99  4644.5  514.16  4708.0  511.57  4715.3  510.64
  4815.3  510.25  4836.2  512.28  4844.5  512.05  4870.2  506.56  4919.1  504.95
  4933.2  504.48  4933.7  503.68  4938.7  503.68  4939.2  504.48  4994.5  506.69
  5010.8  505.98  5016.8  504.87  5063.0  505.33  5069.7  506.56  5073.9  507.33
  5118.4  509.87  5128.9  510.37  5166.2  509.32  5407.9  513.09  5612.2  518.83
#Mann=5,-1,0
  4258.0    0.05       0  4919.1    0.16       0  4933.2    0.07       0
  4939.2    0.16       0  5118.4    0.05       0
Bank Sta=4870.2,5069.7
Exp/Cntr=0.3,0.1

Type RM Length L Ch R = 1,64339,87,87,87
BEGIN DESCRIPTION:
COFFEE CREEK 67.0
END DESCRIPTION:
XS GIS Cut Line= 5
      2900980.04      7074129.26      2900974.40      7074244.70
      2900934.15      7074592.90      2900884.55      7074712.58
      2900855.11      7075110.94
#Sta/Elev= 30
  4572.3  509.82  4729.8  508.92  4778.8  506.80  4869.4  508.07  4899.6  506.32
  4930.6  504.36  4970.0  502.87  5000.2  503.22  5027.4  502.26  5027.9  501.46
  5032.9  501.46  5033.4  502.26  5036.9  503.16  5053.1  503.53  5130.1  502.84
  5154.0  503.08  5188.7  504.36  5200.5  505.17  5210.5  505.16  5270.6  507.53
  5280.7  507.37  5310.8  508.12  5330.8  509.31  5365.7  509.99  5370.9  510.61
  5398.2  510.89  5461.2  513.08  5511.3  513.89  5541.4  515.16  5567.4  515.47
#Mann=5,-1,0
  4572.3    0.05       0  4899.6    0.08       0  5027.4    0.07       0
  5033.4    0.08       0  5398.2    0.05       0
Bank Sta=4930.6,5188.7
Exp/Cntr=0.3,0.1

Type RM Length L Ch R = 1,64252,616,616,616
BEGIN DESCRIPTION:
COFFEE CREEK 66.0
END DESCRIPTION:
XS GIS Cut Line= 5
      2900884.99      7074146.17      2900865.46      7074407.89
      2900861.55      7074591.48      2900813.37      7074695.65
      2900761.98      7075071.81
#Sta/Elev= 30
  4585.8  509.45  4624.7  509.30  4664.8  508.37  4705.0  508.37  4725.0  507.11
  4788.9  505.28  4805.2  504.76  4848.2  505.49  4885.4  503.99  4893.4  504.09
  4905.4  504.53  4918.9  503.38  4935.4  502.14  4975.4  502.77  4992.4  499.59
  4992.9  498.79  4997.9  498.79  4998.4  499.59  5005.4  501.94  5015.4  503.18
  5094.2  502.87  5141.3  503.38  5166.2  503.87  5196.6  505.89  5236.8  505.90
  5321.0  508.05  5388.2  511.49  5393.5  511.11  5465.5  514.11  5526.3  515.41
#Mann=8,-1,0
  4585.8    0.16       0  4788.9    0.12       0  4893.4    0.16       0
  4992.4    0.07       0  4998.4    0.16       0  5094.2    0.05       0
  5196.6    0.08       0  5393.5    0.05       0
Bank Sta=4918.9,5141.3
Exp/Cntr=0.3,0.1

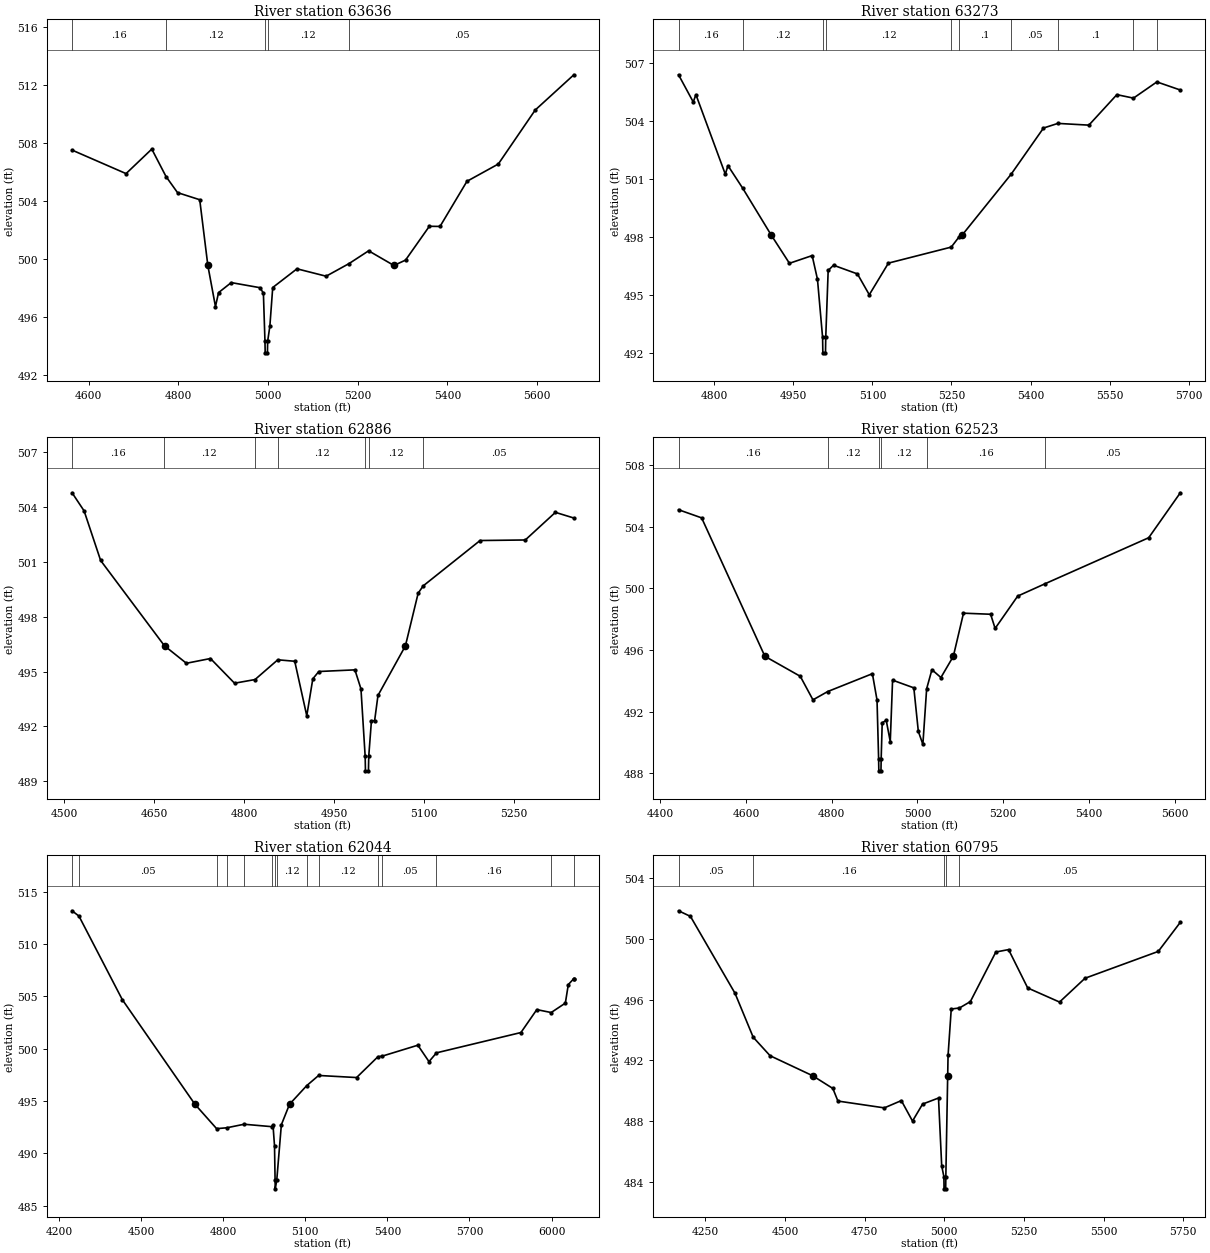
Type RM Length L Ch R = 1,63636,363,363,363
BEGIN DESCRIPTION:
COFFEE CREEK 65.0
END DESCRIPTION:
XS GIS Cut Line= 3
      2900787.36      7074077.14      2900425.00      7074375.00
      2900675.01      7074975.03
#Sta/Elev= 30
  4562.8  507.51  4683.2  505.89  4740.6  507.58  4772.3  505.69  4798.0  504.58
  4847.5  504.09  4865.6  499.56  4882.6  496.73  4889.5  497.69  4917.8  498.38
  4981.7  498.03  4989.5  497.66  4993.0  494.34  4993.5  493.54  4998.5  493.54
  4999.0  494.34  5003.9  495.37  5010.3  498.04  5064.4  499.33  5129.4  498.82
  5180.5  499.69  5224.2  500.57  5280.6  499.56  5306.5  499.93  5359.6  502.26
  5383.4  502.25  5443.5  505.36  5513.4  506.55  5595.7  510.27  5681.9  512.70
#Mann=5,-1,0
  4562.8    0.16       0  4772.3    0.12       0  4993.0    0.07       0
  4999.0    0.12       0  5180.5    0.05       0
Bank Sta=4865.6,5280.6
Exp/Cntr=0.3,0.1

Type RM Length L Ch R = 1,63273,387,387,387
BEGIN DESCRIPTION:
COFFEE CREEK 64.0
END DESCRIPTION:
XS GIS Cut Line= 3
      2900575.04      7074074.99      2900275.00      7074125.00
      2899714.26      7074449.42
#Sta/Elev= 30
  4732.2  506.40  4760.1  504.99  4765.2  505.37  4820.9  501.25  4826.0  501.69
  4854.2  500.51  4907.9  498.10  4942.6  496.63  4985.7  497.03  4995.8  495.80
  5005.5  492.79  5006.0  491.99  5011.0  491.99  5011.5  492.79  5016.1  496.26
  5026.2  496.53  5071.6  496.08  5094.1  495.00  5130.4  496.64  5249.6  497.47
  5264.2  497.99  5270.5  498.10  5363.3  501.25  5424.6  503.64  5451.9  503.88
  5510.7  503.79  5563.8  505.37  5595.3  505.19  5639.7  506.03  5684.2  505.61
#Mann=10,-1,0
  4732.2    0.16       0  4854.2    0.12       0  5005.5    0.07       0
  5011.5    0.12       0  5249.6    0.05       0  5264.2     0.1       0
  5363.3    0.05       0  5451.9     0.1       0  5595.3    0.05       0
  5639.7     0.1       0
Bank Sta=4907.9,5270.5
Exp/Cntr=0.3,0.1

Type RM Length L Ch R = 1,62886,363,363,363
BEGIN DESCRIPTION:
COFFEE CREEK 63.0
END DESCRIPTION:
XS GIS Cut Line= 3
      2900574.96      7073975.00      2900075.00      7073925.00
      2899924.98      7074225.04
#Sta/Elev= 30
  4512.7  504.77  4532.8  503.78  4560.4  501.07  4665.5  496.47  4667.2  496.40
  4703.6  495.45  4743.8  495.71  4784.0  494.36  4818.2  494.56  4856.2  495.64
  4884.5  495.56  4904.6  492.58  4914.7  494.60  4924.7  495.00  4985.0  495.09
  4995.1  494.05  5002.1  490.37  5002.6  489.57  5007.6  489.57  5008.1  490.37
  5012.6  492.31  5017.9  492.31  5023.5  493.69  5069.3  496.40  5090.6  499.28
  5099.0  499.68  5194.0  502.16  5269.5  502.19  5319.8  503.70  5350.6  503.39
#Mann=7,-1,0
  4512.7    0.16       0  4665.5    0.12       0  4818.2    0.16       0
  4856.2    0.12       0  5002.1    0.07       0  5008.1    0.12       0
  5099.0    0.05       0
Bank Sta=4667.2,5069.3
Exp/Cntr=0.3,0.1

Type RM Length L Ch R = 1,62523,479,479,479
BEGIN DESCRIPTION:
COFFEE CREEK 62.0
END DESCRIPTION:
XS GIS Cut Line= 3
      2900625.04      7073875.01      2900125.00      7073675.00
      2899525.01      7073875.00
#Sta/Elev= 30
  4442.5  505.11  4496.4  504.58  4644.0  495.59  4726.6  494.29  4756.2  492.76
  4790.6  493.30  4894.9  494.46  4905.7  492.75  4909.4  488.95  4909.9  488.15
  4914.9  488.15  4915.4  488.95  4917.8  491.27  4927.2  491.43  4936.6  490.05
  4942.0  494.04  4991.6  493.54  5002.1  490.71  5012.7  489.87  5021.5  493.48
  5033.8  494.72  5054.8  494.21  5083.8  495.59  5107.5  498.39  5170.8  498.32
  5181.3  497.40  5234.0  499.50  5298.5  500.31  5539.7  503.29  5613.5  506.21
#Mann=6,-1,0
  4442.5    0.16       0  4790.6    0.12       0  4909.4    0.07       0
  4915.4    0.12       0  5021.5    0.16       0  5298.5    0.05       0
Bank Sta=4644,5083.8
Exp/Cntr=0.3,0.1

Type RM Length L Ch R = 1,62044,1249,1249,1249
BEGIN DESCRIPTION:
COFFEE CREEK 61.0
END DESCRIPTION:
XS GIS Cut Line= 3
      2900925.00      7073575.00      2900322.30      7073453.51
      2899125.03      7073225.01
#Sta/Elev= 30
  4247.9  513.18  4273.1  512.67  4431.5  504.69  4696.8  494.70  4776.1  492.37
  4812.9  492.45  4876.6  492.79  4977.0  492.56  4982.1  492.73  4987.7  490.73
  4989.8  487.42  4990.3  486.62  4995.8  487.42  5012.7  492.74  5042.6  494.70
  5105.5  496.48  5148.9  497.45  5287.6  497.25  5365.6  499.24  5381.8  499.30
  5511.5  500.34  5552.2  498.77  5579.5  499.61  5888.2  501.55  5946.2  503.74
  5998.7  503.46  6050.5  504.36  6061.3  506.13  6081.5  506.70  6081.6  506.70
#Mann=15,-1,0
  4247.9    0.08       0  4273.1    0.05       0  4776.1    0.16       0
  4812.9    0.12       0  4876.6    0.16       0  4977.0    0.12       0
  4989.8    0.07       0  4995.8    0.12       0  5105.5    0.16       0
  5148.9    0.12       0  5365.6    0.16       0  5381.8    0.05       0
  5579.5    0.16       0  5998.7    0.05       0  6081.5    0.08       0
Bank Sta=4696.8,5042.6
Exp/Cntr=0.3,0.1

Type RM Length L Ch R = 1,60795,1298,1298,1298
BEGIN DESCRIPTION:
COFFEE CREEK 60.0
END DESCRIPTION:
XS GIS Cut Line= 3
      2900814.96      7073057.05      2900171.85      7072692.34
      2899335.79      7072687.26
#Sta/Elev= 30
  4165.7  501.86  4203.1  501.49  4343.0  496.42  4400.1  493.52  4453.1  492.30
  4586.8  490.98  4650.2  490.14  4666.1  489.31  4811.8  488.86  4865.2  489.34
  4900.3  487.99  4931.9  489.11  4981.9  489.51  4991.9  485.04  4998.8  484.32
  4999.3  483.52  5004.4  483.52  5004.9  484.32  5010.7  490.98  5011.9  492.32
  5021.9  495.38  5047.8  495.45  5081.9  495.87  5161.9  499.14  5201.9  499.30
  5261.9  496.77  5361.9  495.84  5441.9  497.41  5671.9  499.18  5741.1  501.10
#Mann=5,-1,0
  4165.7    0.05       0  4400.1    0.16       0  4998.8    0.07       0
  5004.9    0.16       0  5047.8    0.05       0
Bank Sta=4586.8,5010.7
Exp/Cntr=0.3,0.1

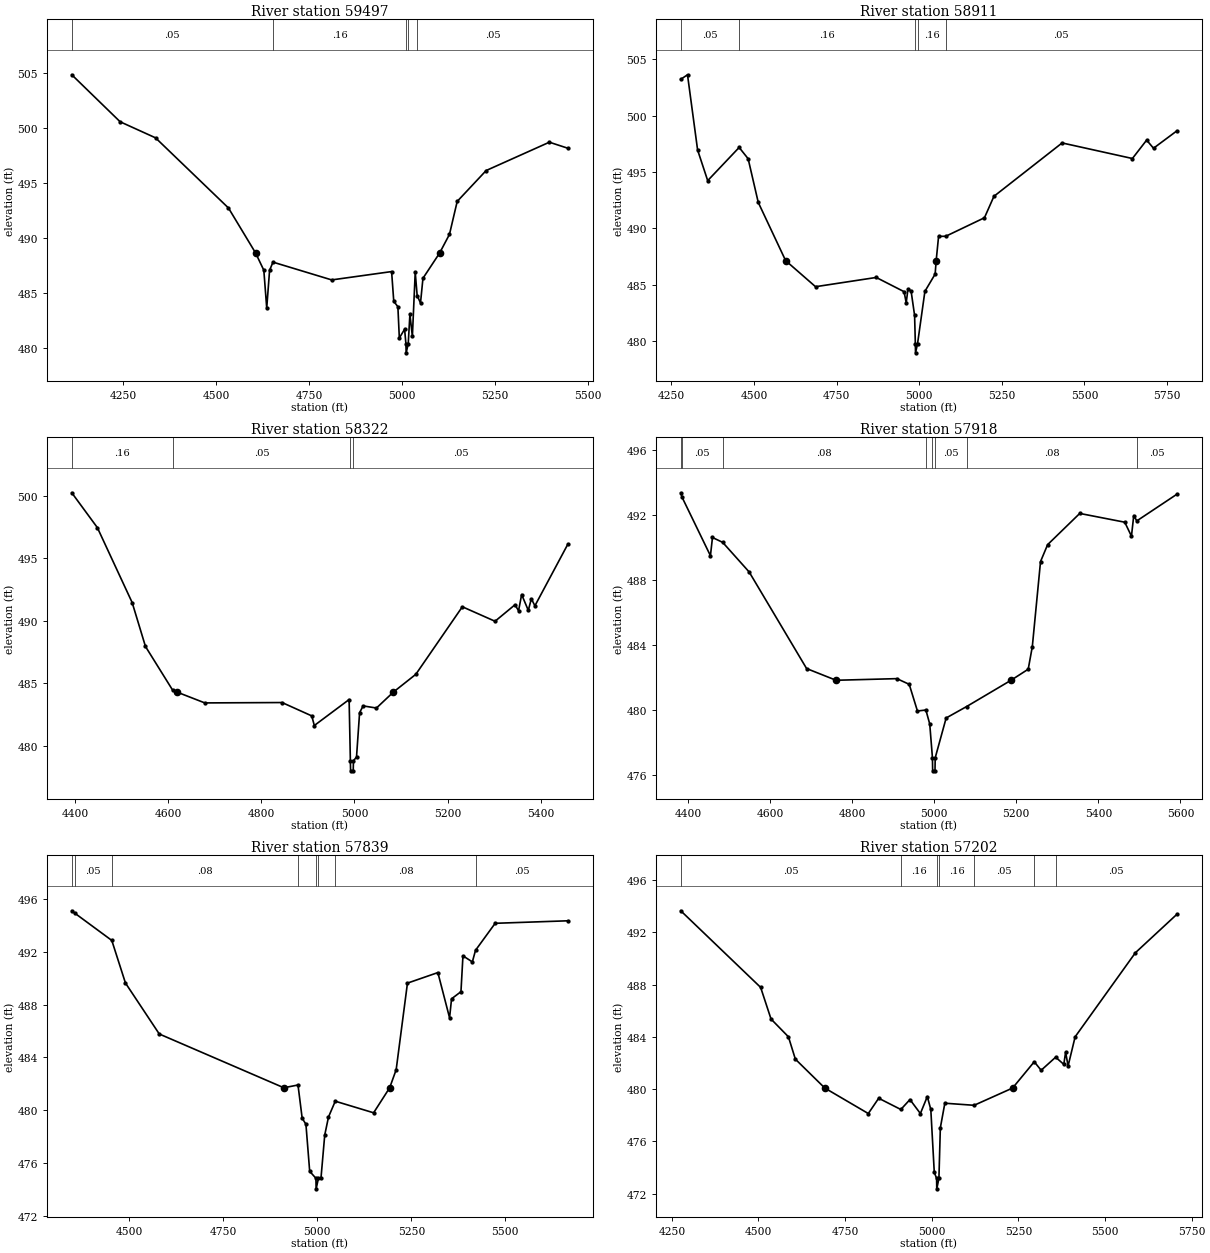
Type RM Length L Ch R = 1,59497,586,586,586
BEGIN DESCRIPTION:
COFFEE CREEK 59.0
END DESCRIPTION:
XS GIS Cut Line= 3
      2900924.98      7071725.01      2900175.00      7072175.00
      2899875.00      7072525.00
#Sta/Elev= 30
  4111.1  504.88  4241.3  500.60  4336.5  499.14  4532.9  492.75  4606.0  488.65
  4628.1  487.08  4635.9  483.64  4643.6  487.07  4652.7  487.82  4810.8  486.20
  4972.1  486.96  4977.9  484.25  4989.0  483.76  4992.9  480.91  5007.1  481.71
  5010.7  480.36  5011.2  479.56  5016.8  480.36  5021.4  483.07  5028.0  481.05
  5035.7  486.90  5040.9  484.77  5049.9  484.10  5056.5  486.35  5101.4  488.65
  5127.9  490.35  5148.7  493.35  5226.6  496.16  5396.8  498.74  5446.7  498.19
#Mann=5,-1,0
  4111.1    0.05       0  4652.7    0.16       0  5010.7    0.07       0
  5016.8    0.16       0  5040.9    0.05       0
Bank Sta=4606,5101.4
Exp/Cntr=0.3,0.1

Type RM Length L Ch R = 1,58911,589,589,589
BEGIN DESCRIPTION:
COFFEE CREEK 58.0
END DESCRIPTION:
XS GIS Cut Line= 4
      2900674.97      7071575.01      2900083.90      7071693.22
      2899913.20      7071753.38      2899355.45      7072204.79
#Sta/Elev= 30
  4278.5  503.22  4298.9  503.62  4329.5  496.95  4360.0  494.24  4455.2  497.18
  4482.4  496.18  4513.0  492.31  4595.9  487.15  4686.4  484.84  4870.0  485.66
  4954.3  484.40  4960.7  483.42  4966.0  484.61  4975.5  484.46  4986.1  482.30
  4988.4  479.78  4988.9  478.98  4995.0  479.78  5017.3  484.43  5048.3  485.96
  5051.4  487.15  5058.7  489.30  5080.4  489.31  5197.5  490.95  5226.2  492.85
  5432.5  497.58  5645.2  496.20  5688.3  497.83  5709.1  497.11  5779.8  498.65
#Mann=5,-1,0
  4278.5    0.05       0  4455.2    0.16       0  4988.4    0.07       0
  4995.0    0.16       0  5080.4    0.05       0
Bank Sta=4595.9,5051.4
Exp/Cntr=0.3,0.1

Type RM Length L Ch R = 1,58322,404,404,404
BEGIN DESCRIPTION:
COFFEE CREEK 57.0
END DESCRIPTION:
XS GIS Cut Line= 3
      2900274.99      7071025.00      2899725.00      7071275.00
      2899375.02      7071574.99
#Sta/Elev= 30
  4393.2  500.26  4448.1  497.47  4522.8  491.47  4551.4  487.95  4610.1  484.43
  4618.9  484.30  4678.8  483.43  4844.7  483.46  4908.4  482.39  4913.9  481.62
  4988.6  483.70  4991.3  478.79  4991.8  477.99  4997.4  477.99  4997.9  478.79
  5004.5  479.10  5011.1  482.65  5018.7  483.19  5047.3  483.02  5083.7  484.30
  5131.8  485.72  5231.7  491.13  5301.9  489.97  5344.7  491.29  5352.4  490.81
  5359.0  492.11  5373.3  490.84  5379.8  491.77  5387.5  491.21  5458.3  496.15
#Mann=4,-1,0
  4393.2    0.16       0  4610.1    0.05       0  4991.3    0.03       0
  4997.9    0.05       0
Bank Sta=4618.9,5083.7
Exp/Cntr=0.3,0.1

Type RM Length L Ch R = 1,57918,79,79,79
BEGIN DESCRIPTION:
Mapping XS b724a4a5
END DESCRIPTION:
XS GIS Cut Line= 4
      2900071.61      7070991.66      2899307.73      7070974.30
      2899175.35      7070972.13      2899027.78      7071247.74
#Sta/Elev= 30
  4382.3  493.34  4385.4  493.07  4454.6  489.47  4459.6  490.59  4484.5  490.29
  4549.0  488.47  4689.0  482.53  4760.8  481.81  4909.0  481.91  4939.1  481.56
  4959.1  479.92  4979.7  479.98  4989.1  479.12  4995.7  477.04  4996.2  476.24
  5001.9  476.24  5002.4  477.04  5029.1  479.49  5078.7  480.19  5187.2  481.81
  5229.1  482.49  5239.1  483.88  5259.1  489.11  5276.4  490.15  5354.7  492.07
  5464.4  491.53  5480.7  490.67  5486.3  491.94  5493.7  491.61  5591.4  493.25
#Mann=8,-1,0
  4382.3    0.08       0  4385.4    0.05       0  4484.5    0.08       0
  4979.7    0.05       0  4995.7    0.04       0  5002.4    0.05       0
  5078.7    0.08       0  5493.7    0.05       0
Bank Sta=4760.8,5187.2
Exp/Cntr=0.3,0.1

Type RM Length L Ch R = 1,57839,637,637,637
BEGIN DESCRIPTION:
COFFEE CREEK 56.0
END DESCRIPTION:
XS GIS Cut Line= 3
      2900077.65      7070913.53      2899116.76      7070903.12
      2898991.75      7071239.07
#Sta/Elev= 30
  4346.9  495.13  4354.3  494.96  4453.3  492.88  4489.6  489.65  4579.6  485.78
  4910.9  481.70  4948.5  481.91  4959.6  479.39  4969.6  478.93  4979.6  475.36
  4996.2  474.83  4996.7  474.03  5002.9  474.83  5009.6  474.83  5019.6  478.11
  5029.6  479.48  5047.6  480.68  5149.6  479.80  5192.3  481.70  5209.6  483.07
  5239.6  489.64  5320.5  490.44  5351.6  487.01  5356.9  488.45  5381.9  488.99
  5387.2  491.71  5412.2  491.25  5420.6  492.13  5472.9  494.18  5666.3  494.37
#Mann=8,-1,0
  4346.9    0.08       0  4354.3    0.05       0  4453.3    0.08       0
  4948.5    0.05       0  4996.2    0.04       0  5002.9    0.05       0
  5047.6    0.08       0  5420.6    0.05       0
Bank Sta=4910.9,5192.3
Exp/Cntr=0.3,0.1

Type RM Length L Ch R = 1,57202,555,555,555
BEGIN DESCRIPTION:
COFFEE CREEK 55.0
END DESCRIPTION:
XS GIS Cut Line= 3
      2899924.97      7070375.00      2899175.00      7070325.00
      2898975.00      7070974.99
#Sta/Elev= 30
  4275.7  493.64  4506.2  487.78  4536.2  485.36  4586.4  484.00  4606.4  482.29
  4691.4  480.08  4816.9  478.13  4846.9  479.30  4910.8  478.44  4937.1  479.20
  4967.2  478.13  4987.2  479.43  4997.3  478.44  5007.3  473.63  5014.0  473.17
  5014.5  472.37  5020.7  473.17  5024.8  477.04  5037.8  478.92  5122.2  478.76
  5233.3  480.08  5295.8  482.09  5315.7  481.44  5357.6  482.44  5381.1  481.89
  5386.3  482.82  5393.5  481.77  5413.8  484.00  5587.7  490.43  5707.4  493.37
#Mann=7,-1,0
  4275.7    0.05       0  4910.8    0.16       0  5014.0    0.07       0
  5020.7    0.16       0  5122.2    0.05       0  5295.8    0.16       0
  5357.6    0.05       0
Bank Sta=4691.4,5233.3
Exp/Cntr=0.3,0.1

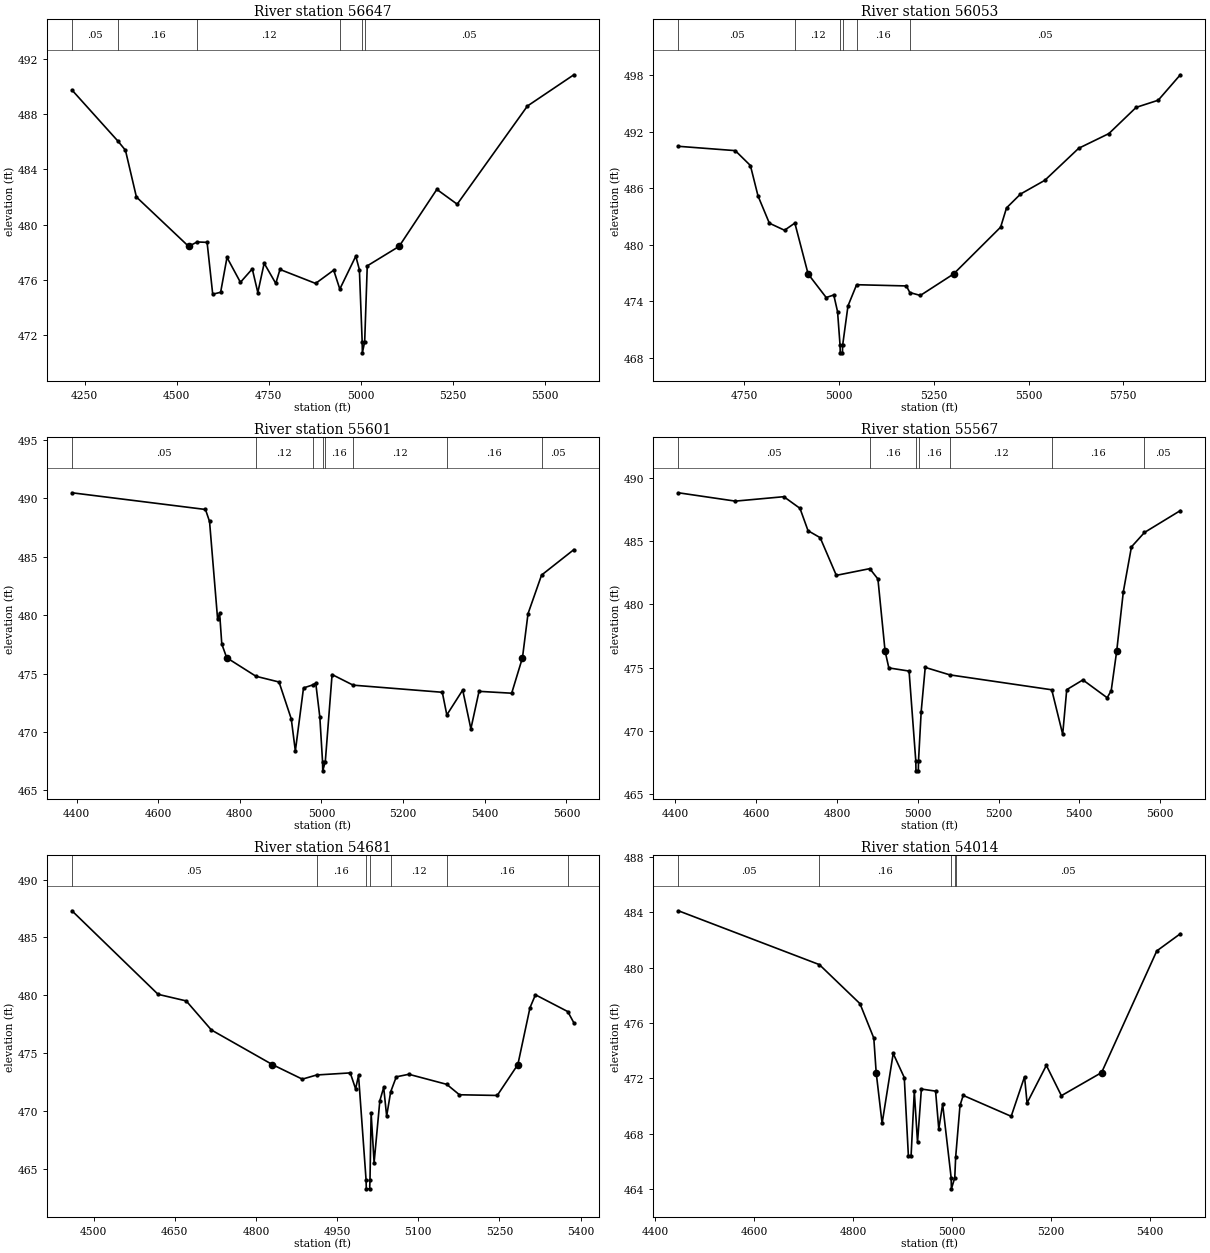
Type RM Length L Ch R = 1,56647,594,594,594
BEGIN DESCRIPTION:
COFFEE CREEK 54.0
END DESCRIPTION:
XS GIS Cut Line= 4
      2899420.90      7069724.88      2898761.20      7069985.29
      2898709.12      7070165.85      2898664.03      7070630.61
#Sta/Elev= 30
  4215.3  489.75  4340.7  486.04  4360.7  485.39  4390.5  482.01  4532.4  478.44
  4555.6  478.76  4582.6  478.73  4597.9  474.98  4619.4  475.12  4636.7  477.64
  4673.2  475.84  4705.4  476.81  4720.5  475.10  4737.7  477.22  4769.3  475.76
  4780.7  476.77  4877.5  475.76  4926.7  476.72  4943.3  475.35  4986.7  477.73
  4996.5  476.76  5004.1  471.54  5004.6  470.74  5010.9  471.54  5017.9  477.03
  5104.5  478.44  5207.0  482.56  5262.3  481.49  5453.2  488.59  5579.4  490.85
#Mann=6,-1,0
  4215.3    0.05       0  4340.7    0.16       0  4555.6    0.12       0
  4943.3    0.05       0  5004.1    0.03       0  5010.9    0.05       0
Bank Sta=4532.4,5104.5
Exp/Cntr=0.3,0.1

Type RM Length L Ch R = 1,56053,452,452,452
BEGIN DESCRIPTION:
COFFEE CREEK 53.0
END DESCRIPTION:
XS GIS Cut Line= 3
      2898874.97      7069675.00      2898425.00      7069675.00
      2897975.01      7070424.99
#Sta/Elev= 30
  4576.0  490.47  4726.0  490.01  4766.0  488.43  4786.0  485.21  4816.0  482.31
  4856.0  481.56  4883.3  482.32  4918.3  476.92  4966.0  474.42  4986.0  474.69
  4996.0  472.92  5002.6  469.35  5003.1  468.55  5008.9  468.55  5009.4  469.35
  5023.5  473.53  5046.3  475.78  5177.6  475.65  5186.7  474.95  5214.5  474.64
  5302.2  476.92  5426.4  481.89  5441.9  483.93  5478.8  485.40  5543.0  486.86
  5632.4  490.26  5712.1  491.82  5784.0  494.60  5842.3  495.36  5900.6  498.06
#Mann=6,-1,0
  4576.0    0.05       0  4883.3    0.12       0  5002.6    0.07       0
  5009.4    0.12       0  5046.3    0.16       0  5186.7    0.05       0
Bank Sta=4918.3,5302.2
Exp/Cntr=0.3,0.1

Type RM Length L Ch R = 1,55601,34,34,34
BEGIN DESCRIPTION:
Mapping XS 12202f83
END DESCRIPTION:
XS GIS Cut Line= 4
      2898811.82      7069455.05      2898311.83      7069434.21
      2898077.45      7069431.61      2897582.68      7069429.01
#Sta/Elev= 30
  4388.7  490.49  4715.8  489.06  4725.8  488.03  4745.5  479.69  4750.5  480.16
  4755.8  477.53  4767.8  476.36  4839.6  474.77  4896.0  474.28  4926.0  471.12
  4936.0  468.37  4956.0  473.77  4978.5  474.03  4986.0  474.18  4996.0  471.27
  5002.6  467.47  5003.1  466.67  5009.4  467.47  5026.0  474.92  5077.6  474.01
  5296.0  473.40  5307.1  471.46  5346.0  473.59  5366.0  470.27  5386.0  473.48
  5466.0  473.32  5492.4  476.36  5506.0  480.13  5539.2  483.44  5618.3  485.62
#Mann=8,-1,0
  4388.7    0.05       0  4839.6    0.12       0  4978.5    0.16       0
  5002.6    0.07       0  5009.4    0.16       0  5077.6    0.12       0
  5307.1    0.16       0  5539.2    0.05       0
Bank Sta=4767.8,5492.4
Exp/Cntr=0.3,0.1

Type RM Length L Ch R = 1,55567,886,886,886
BEGIN DESCRIPTION:
COFFEE CREEK 52.0
END DESCRIPTION:
XS GIS Cut Line= 3
      2898795.87      7069408.85      2898304.02      7069402.96
      2897554.06      7069371.72
#Sta/Elev= 30
  4407.6  488.82  4548.5  488.16  4668.5  488.51  4708.5  487.59  4728.5  485.82
  4758.5  485.27  4798.5  482.29  4881.3  482.82  4901.5  482.00  4919.2  476.30
  4928.5  474.97  4978.6  474.72  4995.2  467.63  4995.7  466.83  5001.5  466.83
  5002.0  467.63  5008.6  471.52  5018.6  475.01  5079.4  474.42  5331.8  473.24
  5358.9  469.72  5368.9  473.25  5408.9  474.02  5469.0  472.61  5479.0  473.17
  5492.6  476.30  5509.0  480.99  5529.1  484.54  5561.3  485.68  5650.1  487.41
#Mann=7,-1,0
  4407.6    0.05       0  4881.3    0.16       0  4995.2    0.07       0
  5002.0    0.16       0  5079.4    0.12       0  5331.8    0.16       0
  5561.3    0.05       0
Bank Sta=4919.2,5492.6
Exp/Cntr=0.3,0.1

Type RM Length L Ch R = 1,54681,667,667,667
BEGIN DESCRIPTION:
COFFEE CREEK 51.0
END DESCRIPTION:
XS GIS Cut Line= 3
      2898474.96      7069174.98      2897882.00      7068911.04
      2897604.19      7068889.34
#Sta/Elev= 30
  4459.9  487.30  4619.1  480.08  4671.1  479.51  4717.6  477.00  4830.3  474.01
  4885.7  472.75  4912.3  473.11  4974.3  473.29  4984.2  471.91  4989.6  473.07
  5003.5  464.07  5004.0  463.27  5010.2  463.27  5010.8  464.07  5012.9  469.81
  5018.4  465.54  5029.0  470.89  5036.1  472.03  5041.6  469.56  5049.0  471.65
  5059.4  472.95  5082.6  473.17  5152.7  472.30  5176.1  471.40  5246.0  471.34
  5284.1  474.01  5306.5  478.92  5316.6  480.04  5376.3  478.59  5387.6  477.62
#Mann=7,-1,0
  4459.9    0.05       0  4912.3    0.16       0  5003.5    0.07       0
  5010.8    0.16       0  5049.0    0.12       0  5152.7    0.16       0
  5376.3    0.05       0
Bank Sta=4830.3,5284.1
Exp/Cntr=0.3,0.1

Type RM Length L Ch R = 1,54014,727,727,727
BEGIN DESCRIPTION:
COFFEE CREEK 50.0
END DESCRIPTION:
XS GIS Cut Line= 4
      2898425.00      7068975.00      2898218.37      7068558.40
      2898107.79      7068465.92      2897708.14      7068395.98
#Sta/Elev= 30
  4447.2  484.10  4732.2  480.21  4814.3  477.39  4842.3  474.90  4847.1  472.41
  4859.1  468.74  4881.5  473.79  4903.9  472.05  4912.2  466.41  4917.7  466.41
  4924.2  471.05  4930.7  467.37  4938.5  471.22  4967.2  471.07  4973.7  468.33
  4981.5  470.13  4998.7  464.81  4999.2  464.01  5006.0  464.81  5007.8  466.29
  5016.6  470.04  5023.1  470.76  5120.1  469.25  5147.1  472.11  5152.2  470.21
  5191.2  472.93  5221.6  470.74  5302.9  472.41  5414.5  481.20  5462.1  482.44
#Mann=5,-1,0
  4447.2    0.05       0  4732.2    0.16       0  4998.7    0.07       0
  5006.0    0.16       0  5007.8    0.05       0
Bank Sta=4847.1,5302.9
Exp/Cntr=0.3,0.1

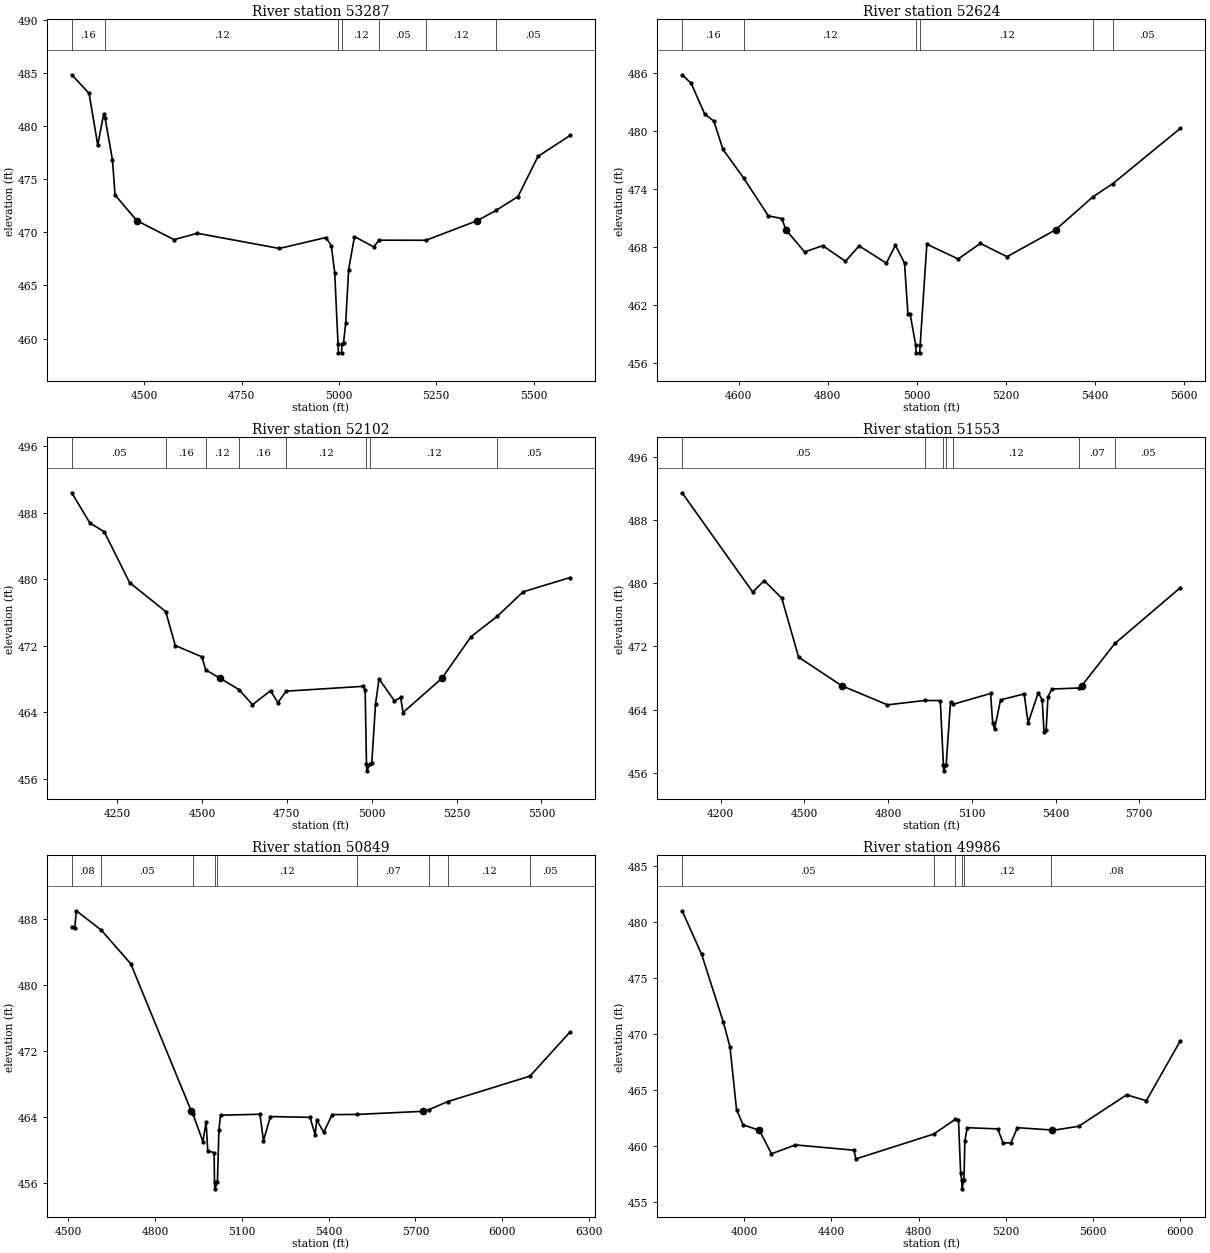
Type RM Length L Ch R = 1,53287,663,663,663
BEGIN DESCRIPTION:
COFFEE CREEK 49.0
END DESCRIPTION:
XS GIS Cut Line= 3
      2898925.02      7067824.99      2898255.76      7068148.26
      2897734.91      7068275.87
#Sta/Elev= 30
  4314.2  484.86  4358.6  483.11  4380.9  478.24  4396.1  481.17  4399.7  480.80
  4418.7  476.82  4425.3  473.53  4481.3  471.11  4576.9  469.32  4636.3  469.92
  4847.3  468.49  4966.7  469.52  4980.6  468.74  4989.3  466.21  4997.8  459.45
  4998.8  458.65  5006.8  458.65  5007.8  459.45  5011.9  459.60  5017.4  461.43
  5025.0  466.49  5040.0  469.61  5089.1  468.64  5103.4  469.27  5223.6  469.26
  5355.2  471.11  5403.7  472.08  5459.8  473.38  5511.2  477.17  5593.7  479.14
#Mann=7,-1,0
  4314.2    0.16       0  4399.7    0.12       0  4997.8    0.07       0
  5007.8    0.12       0  5103.4    0.05       0  5223.6    0.12       0
  5403.7    0.05       0
Bank Sta=4481.3,5355.2
Exp/Cntr=0.3,0.1

Type RM Length L Ch R = 1,52624,522,522,522
BEGIN DESCRIPTION:
COFFEE CREEK 48.0
END DESCRIPTION:
XS GIS Cut Line= 3
      2898925.00      7067725.00      2898425.00      7067625.00
      2897815.68      7067596.18
#Sta/Elev= 30
  4473.3  485.85  4493.7  484.96  4524.3  481.76  4544.7  481.05  4565.1  478.12
  4611.2  475.19  4667.1  471.25  4697.7  470.97  4706.3  469.81  4748.6  467.52
  4789.4  468.17  4840.4  466.55  4871.0  468.15  4932.2  466.36  4952.6  468.20
  4973.0  466.38  4980.7  461.08  4985.7  461.08  4998.2  457.88  4999.2  457.08
  5007.2  457.08  5008.2  457.88  5023.2  468.32  5093.7  466.79  5143.4  468.40
  5203.4  467.03  5312.5  469.81  5396.6  473.23  5441.0  474.58  5593.2  480.32
#Mann=6,-1,0
  4473.3    0.16       0  4611.2    0.12       0  4998.2    0.07       0
  5008.2    0.12       0  5396.6    0.16       0  5441.0    0.05       0
Bank Sta=4706.3,5312.5
Exp/Cntr=0.3,0.1

Type RM Length L Ch R = 1,52102,549,549,549
BEGIN DESCRIPTION:
COFFEE CREEK 47.0
END DESCRIPTION:
XS GIS Cut Line= 3
      2899224.96      7067474.98      2898287.01      7067132.64
      2897854.74      7067314.92
#Sta/Elev= 30
  4116.8  490.41  4170.0  486.78  4212.6  485.71  4287.1  479.60  4393.5  476.12
  4421.6  472.03  4500.0  470.67  4511.1  469.10  4553.8  468.08  4609.1  466.73
  4649.0  464.91  4702.2  466.59  4723.5  465.16  4748.3  466.54  4975.4  467.12
  4980.7  466.67  4984.7  457.75  4985.7  456.95  4994.7  457.75  5000.3  457.89
  5011.3  464.98  5021.6  468.01  5067.1  465.36  5085.5  465.78  5092.3  463.97
  5206.6  468.08  5292.6  473.10  5370.0  475.55  5445.8  478.49  5584.4  480.21
#Mann=8,-1,0
  4116.8    0.05       0  4393.5    0.16       0  4511.1    0.12       0
  4609.1    0.16       0  4748.3    0.12       0  4984.7    0.07       0
  4994.7    0.12       0  5370.0    0.05       0
Bank Sta=4553.8,5206.6
Exp/Cntr=0.3,0.1

Type RM Length L Ch R = 1,51553,704,704,704
BEGIN DESCRIPTION:
COFFEE CREEK 46.0
END DESCRIPTION:
XS GIS Cut Line= 3
      2899331.26      7066429.52      2898318.26      7066666.49
      2897824.99      7067225.01
#Sta/Elev= 30
  4061.9  491.42  4314.8  478.87  4355.9  480.32  4418.9  478.10  4479.1  470.65
  4633.5  467.04  4797.5  464.62  4930.4  465.17  4986.7  465.16  4997.9  457.08
  4998.9  456.28  5007.9  457.08  5023.4  464.97  5032.6  464.69  5167.0  466.06
  5174.4  462.38  5181.1  461.56  5202.8  465.25  5287.3  466.00  5301.5  462.34
  5337.5  466.13  5351.8  465.28  5358.4  461.20  5366.0  461.46  5372.6  465.65
  5386.9  466.62  5485.0  466.75  5493.7  467.04  5612.4  472.38  5847.4  479.44
#Mann=7,-1,0
  4061.9    0.05       0  4930.4    0.07       0  4997.9    0.07       0
  5007.9    0.07       0  5032.6    0.12       0  5485.0    0.07       0
  5612.4    0.05       0
Bank Sta=4633.5,5493.7
Exp/Cntr=0.3,0.1

Type RM Length L Ch R = 1,50849,863,863,863
BEGIN DESCRIPTION:
COFFEE CREEK 45.0
END DESCRIPTION:
XS GIS Cut Line= 3
      2898677.67      7065744.60      2898122.95      7066031.08
      2897706.28      7067046.70
#Sta/Elev= 30
  4512.4  487.05  4522.6  486.86  4528.2  488.99  4615.1  486.62  4716.3  482.55
  4925.6  464.65  4930.9  464.34  4965.6  460.98  4976.5  463.36  4982.2  459.89
  5004.3  459.61  5005.6  456.04  5006.6  455.24  5015.7  456.04  5020.8  462.34
  5026.5  464.18  5162.6  464.29  5174.8  461.08  5198.8  464.01  5335.5  463.92
  5353.5  461.81  5358.9  463.61  5382.9  462.10  5412.3  464.25  5497.3  464.27
  5725.8  464.65  5745.1  464.83  5811.5  465.83  6095.7  468.92  6234.5  474.29
#Mann=9,-1,0
  4512.4    0.08       0  4615.1    0.05       0  4930.9    0.12       0
  5005.6    0.07       0  5015.7    0.12       0  5497.3    0.07       0
  5745.1    0.05       0  5811.5    0.12       0  6095.7    0.05       0
Bank Sta=4925.6,5725.8
Exp/Cntr=0.3,0.1

Type RM Length L Ch R = 1,49986,115,115,115
BEGIN DESCRIPTION:
COFFEE CREEK 44.0
END DESCRIPTION:
XS GIS Cut Line= 3
      2898344.33      7065231.60      2897560.45      7065202.95
      2897472.00      7066701.43
#Sta/Elev= 30
  3715.3  481.01  3804.7  477.12  3904.8  471.04  3934.8  468.85  3964.8  463.26
  3994.8  461.90  4070.0  461.41  4124.9  459.32  4235.0  460.11  4503.2  459.64
  4512.0  458.86  4869.0  461.08  4966.9  462.38  4982.6  462.34  4992.6  457.57
  4997.6  456.99  4998.5  456.19  5007.7  456.99  5012.0  460.48  5022.7  461.65
  5162.9  461.54  5187.0  460.28  5223.0  460.30  5253.1  461.65  5404.8  461.45
  5413.5  461.41  5533.6  461.77  5753.9  464.58  5844.1  464.06  6000.8  469.43
#Mann=6,-1,0
  3715.3    0.05       0  4869.0    0.08       0  4966.9    0.12       0
  4997.6    0.07       0  5007.7    0.12       0  5404.8    0.08       0
Bank Sta=4070,5413.5
Exp/Cntr=0.3,0.1