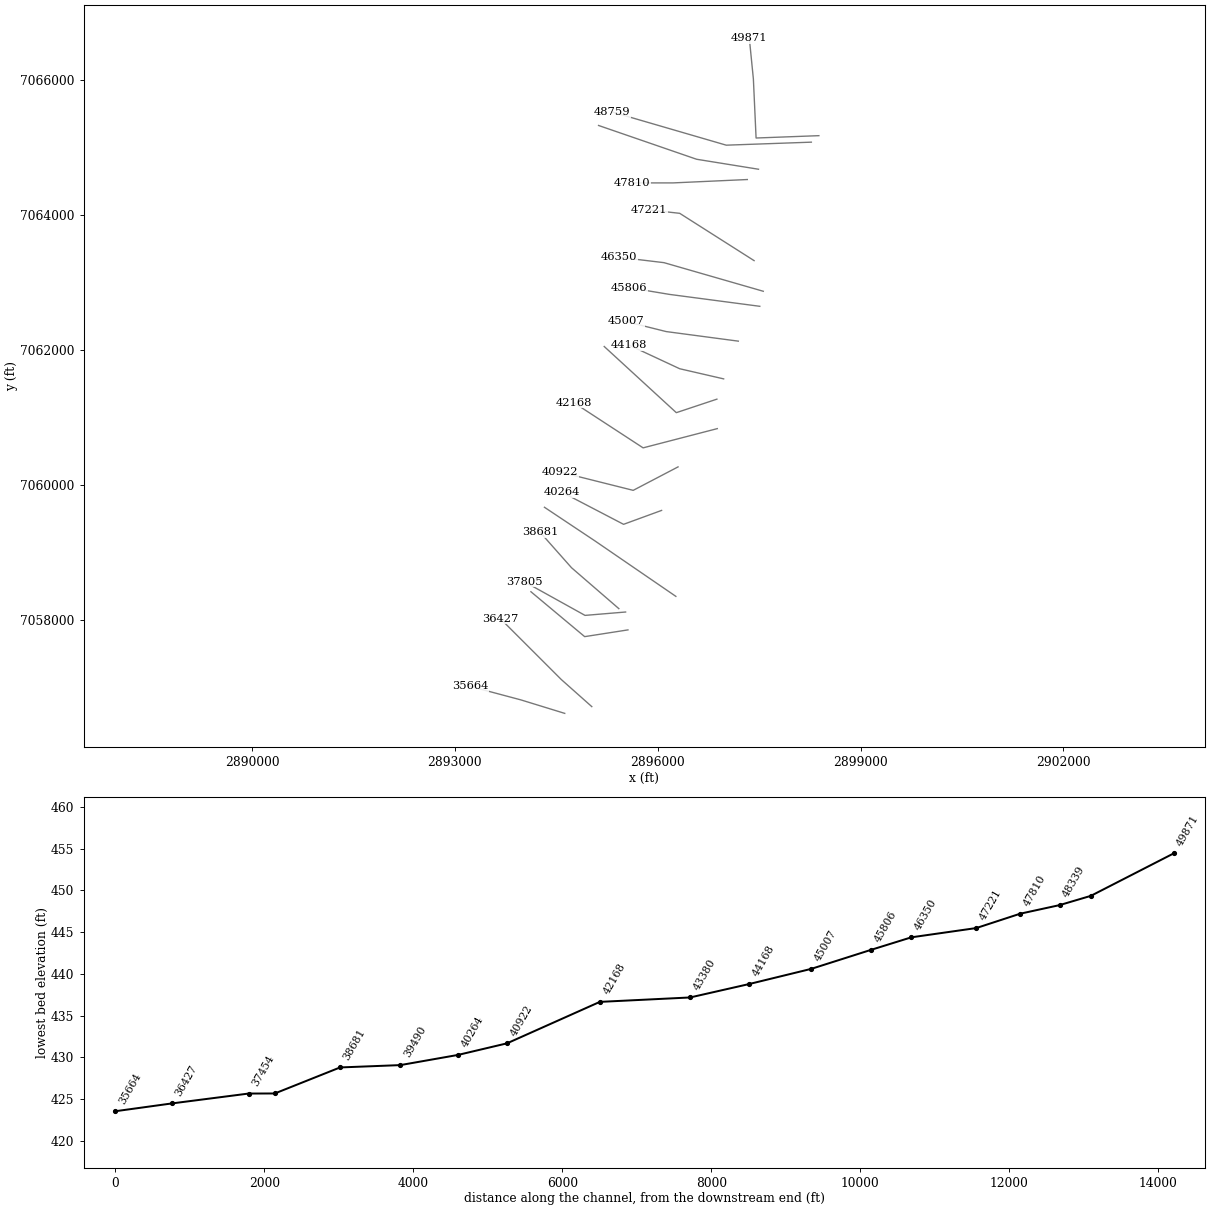
HEC-RAS study COFFEE CREEK.prj: COFFEE CREEK Base Level Engineering

--- COFFEE CREEK.g01 (geometry) --- (continued)

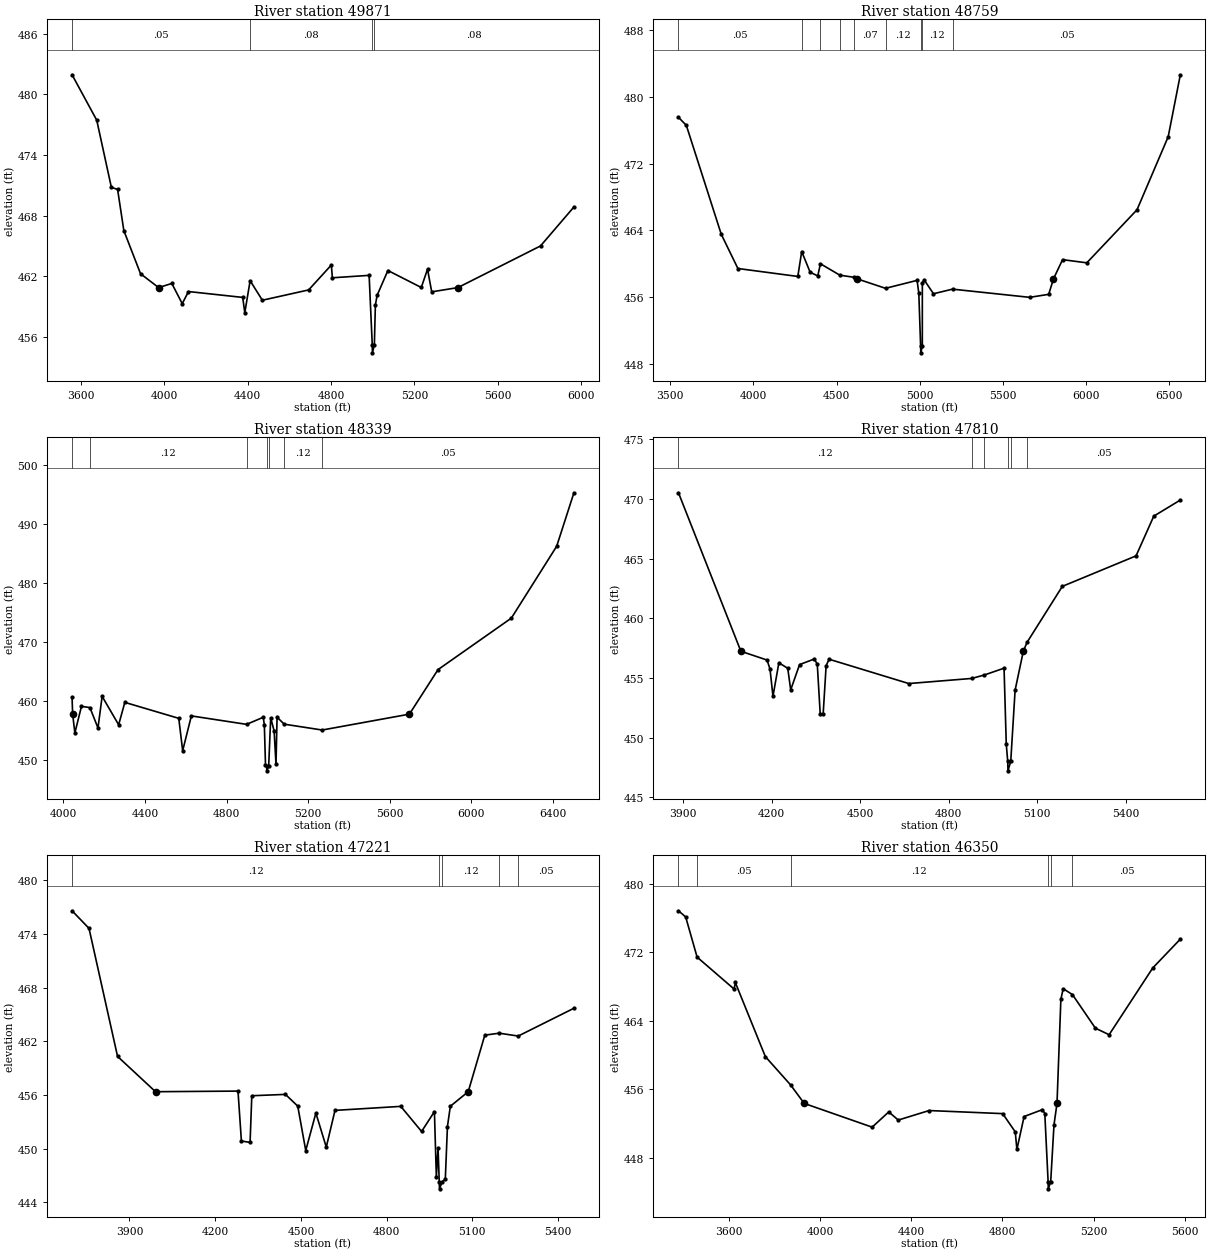
Type RM Length L Ch R = 1,49871,1112,1112,1112
BEGIN DESCRIPTION:
COFFEE CREEK 43.0
END DESCRIPTION:
XS GIS Cut Line= 4
      2898383.34      7065174.09      2897454.54      7065139.37
      2897414.61      7066012.85      2897354.72      7066614.43
#Sta/Elev= 30
  3557.2  481.93  3675.6  477.44  3745.7  470.81  3775.7  470.59  3805.7  466.52
  3885.8  462.26  3972.6  460.89  4035.9  461.30  4085.9  459.30  4115.9  460.50
  4376.1  459.92  4386.1  458.41  4411.7  461.57  4470.4  459.64  4692.5  460.66
  4801.4  463.12  4806.4  461.86  4982.8  462.10  4997.8  455.24  4998.7  454.44
  5007.9  455.24  5012.8  459.16  5021.0  460.12  5072.9  462.58  5233.1  460.90
  5263.1  462.71  5283.1  460.47  5408.7  460.89  5805.4  465.01  5965.6  468.86
#Mann=4,-1,0
  3557.2    0.05       0  4411.7    0.08       0  4997.8    0.07       0
  5007.9    0.08       0
Bank Sta=3972.6,5408.7
Exp/Cntr=0.3,0.1

Type RM Length L Ch R = 1,48759,420,420,420
BEGIN DESCRIPTION:
COFFEE CREEK 42.0
END DESCRIPTION:
XS GIS Cut Line= 3
      2898272.21      7065078.02      2897013.69      7065033.40
      2895325.00      7065525.00
#Sta/Elev= 30
  3549.4  477.53  3596.6  476.57  3806.8  463.53  3906.8  459.44  4267.1  458.49
  4290.5  461.47  4341.2  459.00  4387.1  458.55  4403.0  460.01  4520.0  458.64
  4605.2  458.39  4625.9  458.19  4794.5  457.07  4984.4  458.02  4994.8  456.48
  5005.7  450.15  5006.7  449.35  5015.9  450.15  5016.0  457.71  5026.1  458.10
  5083.1  456.42  5197.4  456.97  5661.4  455.99  5776.0  456.35  5804.4  458.19
  5859.3  460.50  6005.1  460.12  6307.1  466.47  6494.6  475.21  6567.5  482.62
#Mann=9,-1,0
  3549.4    0.05       0  4290.5    0.08       0  4403.0    0.16       0
  4520.0    0.12       0  4605.2    0.07       0  4794.5    0.12       0
  5005.7    0.07       0  5015.9    0.12       0  5197.4    0.05       0
Bank Sta=4625.9,5804.4
Exp/Cntr=0.3,0.1

Type RM Length L Ch R = 1,48339,529,529,529
BEGIN DESCRIPTION:
COFFEE CREEK 41.0
END DESCRIPTION:
XS GIS Cut Line= 3
      2897490.50      7064677.34      2896575.00      7064825.00
      2895125.02      7065324.99
#Sta/Elev= 30
  4042.6  460.66  4045.4  457.84  4056.3  454.66  4088.7  459.16  4130.1  458.95
  4169.7  455.50  4190.0  460.85  4271.0  456.04  4301.4  459.83  4565.8  457.13
  4585.0  451.65  4627.6  457.54  4898.5  456.11  4980.2  457.31  4985.5  456.03
  4991.1  449.31  4996.6  449.04  4997.5  448.24  5006.8  449.04  5016.7  457.20
  5033.4  455.01  5042.7  449.35  5047.9  457.32  5083.1  456.14  5269.2  455.15
  5697.0  457.84  5837.3  465.38  6197.0  474.10  6419.1  486.26  6503.7  495.32
#Mann=7,-1,0
  4042.6    0.08       0  4130.1    0.12       0  4898.5    0.07       0
  4996.6    0.07       0  5006.8    0.07       0  5083.1    0.12       0
  5269.2    0.05       0
Bank Sta=4045.4,5697
Exp/Cntr=0.3,0.1

Type RM Length L Ch R = 1,47810,589,589,589
BEGIN DESCRIPTION:
COFFEE CREEK 40.0
END DESCRIPTION:
XS GIS Cut Line= 3
      2897324.99      7064525.00      2896225.00      7064475.00
      2895625.02      7064475.00
#Sta/Elev= 30
  3884.6  470.53  4096.1  457.24  4184.9  456.50  4194.9  455.74  4204.9  453.46
  4224.9  456.27  4255.0  455.81  4265.0  454.00  4295.0  456.12  4345.1  456.59
  4355.1  456.15  4365.1  451.96  4375.1  452.00  4385.1  456.03  4395.1  456.57
  4665.4  454.53  4878.8  454.96  4921.7  455.25  4988.2  455.82  4995.7  449.46
  5000.6  448.01  5001.5  447.21  5010.9  448.01  5025.7  453.98  5053.5  457.24
  5066.0  457.98  5185.7  462.68  5435.7  465.24  5495.7  468.57  5585.7  469.92
#Mann=6,-1,0
  3884.6    0.12       0  4878.8    0.16       0  4921.7    0.12       0
  5000.6    0.07       0  5010.9    0.12       0  5066.0    0.05       0
Bank Sta=4096.1,5053.5
Exp/Cntr=0.3,0.1

Type RM Length L Ch R = 1,47221,871,871,871
BEGIN DESCRIPTION:
COFFEE CREEK 39.0
END DESCRIPTION:
XS GIS Cut Line= 3
      2897425.01      7063325.00      2896325.00      7064025.00
      2895875.02      7064075.00
#Sta/Elev= 30
  3699.1  476.61  3758.4  474.64  3858.3  460.31  3991.2  456.36  4279.9  456.43
  4291.8  450.84  4322.2  450.69  4328.2  455.91  4445.9  456.06  4489.0  454.75
  4517.0  449.78  4552.5  453.97  4588.9  450.16  4619.4  454.27  4849.7  454.72
  4922.5  451.91  4967.4  454.13  4974.2  446.81  4980.1  450.10  4984.3  446.29
  4985.2  445.49  4994.6  446.29  5005.5  446.55  5013.0  452.46  5023.1  454.73
  5085.7  456.36  5143.8  462.69  5194.2  462.91  5260.7  462.59  5455.7  465.70
#Mann=5,-1,0
  3699.1    0.12       0  4984.3    0.07       0  4994.6    0.12       0
  5194.2    0.16       0  5260.7    0.05       0
Bank Sta=3991.2,5085.7
Exp/Cntr=0.3,0.1

Type RM Length L Ch R = 1,46350,544,544,544
BEGIN DESCRIPTION:
COFFEE CREEK 38.0
END DESCRIPTION:
XS GIS Cut Line= 3
      2897561.04      7062871.43      2896093.00      7063294.75
      2895424.95      7063375.01
#Sta/Elev= 30
  3379.2  476.84  3410.8  476.12  3460.9  471.43  3623.2  467.70  3628.4  468.47
  3760.1  459.82  3870.6  456.52  3930.7  454.35  4228.5  451.58  4301.3  453.36
  4343.0  452.41  4478.3  453.52  4800.9  453.16  4856.0  451.03  4863.3  448.98
  4894.8  452.82  4975.5  453.63  4985.6  453.17  5000.2  445.18  5000.9  444.38
  5011.4  445.18  5025.9  451.85  5039.1  454.35  5056.1  466.51  5066.2  467.74
  5106.8  467.06  5207.4  463.14  5267.6  462.37  5459.1  470.17  5579.9  473.53
#Mann=6,-1,0
  3379.2    0.08       0  3460.9    0.05       0  3870.6    0.12       0
  5000.2    0.07       0  5011.4    0.12       0  5106.8    0.05       0
Bank Sta=3930.7,5039.1
Exp/Cntr=0.3,0.1

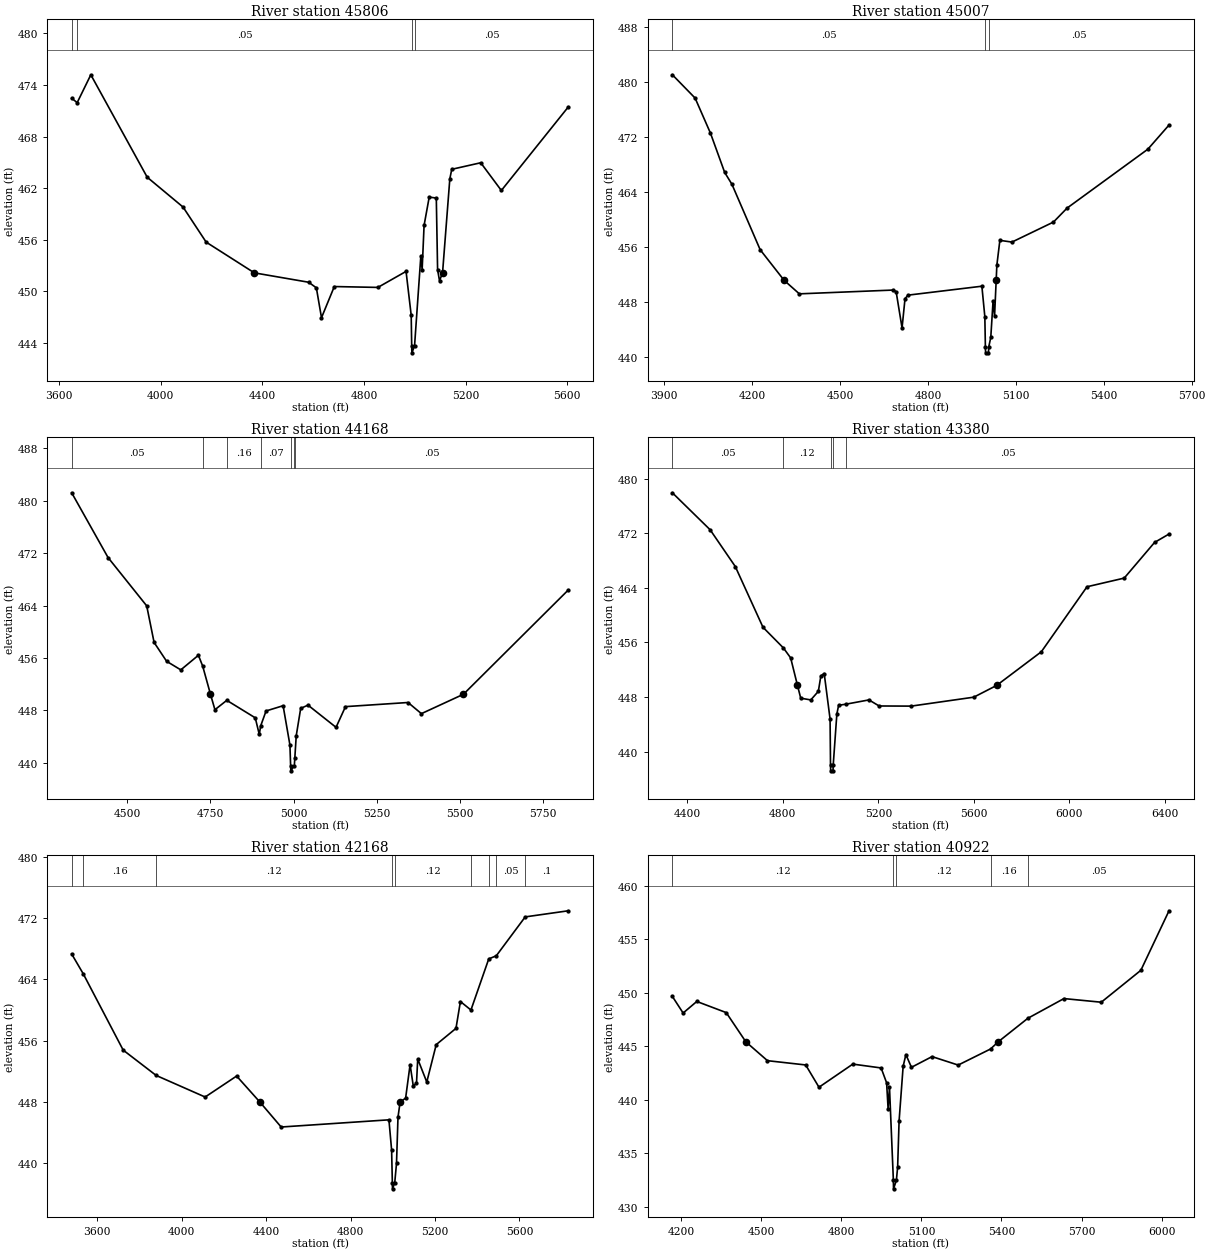
Type RM Length L Ch R = 1,45806,799,799,799
BEGIN DESCRIPTION:
COFFEE CREEK 37.0
END DESCRIPTION:
XS GIS Cut Line= 3
      2897509.64      7062648.92      2896175.00      7062825.00
      2895574.99      7062925.00
#Sta/Elev= 30
  3650.1  472.45  3671.7  471.93  3725.4  475.17  3947.3  463.27  4088.5  459.80
  4179.3  455.73  4369.0  452.16  4582.8  451.07  4613.0  450.42  4633.2  446.95
  4683.6  450.57  4855.1  450.47  4966.0  452.33  4986.2  447.24  4988.2  443.67
  4988.9  442.87  4999.4  443.67  5024.2  454.13  5029.3  452.53  5036.9  457.67
  5057.1  460.96  5085.0  460.85  5090.1  452.51  5097.7  451.24  5109.6  452.16
  5138.2  463.08  5145.8  464.19  5259.9  464.95  5341.0  461.73  5604.6  471.44
#Mann=4,-1,0
  3650.1    0.08       0  3671.7    0.05       0  4988.2    0.03       0
  4999.4    0.05       0
Bank Sta=4369,5109.6
Exp/Cntr=0.3,0.1

Type RM Length L Ch R = 1,45007,839,839,839
BEGIN DESCRIPTION:
COFFEE CREEK 36.0
END DESCRIPTION:
XS GIS Cut Line= 3
      2897191.97      7062133.29      2896125.00      7062275.00
      2895525.00      7062425.00
#Sta/Elev= 30
  3927.9  481.04  4005.5  477.65  4057.9  472.55  4106.4  466.84  4131.2  465.11
  4227.5  455.60  4309.4  451.14  4361.2  449.18  4681.4  449.73  4691.5  449.50
  4711.7  444.22  4721.8  448.47  4731.9  448.99  4984.1  450.29  4994.2  445.87
  4996.1  441.40  4996.8  440.60  5006.6  440.60  5007.3  441.40  5014.5  442.86
  5022.3  448.14  5027.4  445.95  5032.9  451.14  5035.2  453.35  5045.5  456.96
  5086.7  456.71  5228.4  459.62  5274.8  461.65  5550.6  470.22  5622.7  473.73
#Mann=3,-1,0
  3927.9    0.05       0  4996.1    0.03       0  5007.3    0.05       0
Bank Sta=4309.4,5032.9
Exp/Cntr=0.3,0.1

Type RM Length L Ch R = 1,44168,788,788,788
BEGIN DESCRIPTION:
COFFEE CREEK 35.0
END DESCRIPTION:
XS GIS Cut Line= 3
      2896975.01      7061575.00      2896325.00      7061725.00
      2895575.04      7062074.98
#Sta/Elev= 30
  4332.4  481.21  4441.9  471.32  4558.2  463.95  4580.4  458.37  4618.1  455.49
  4660.8  454.18  4713.8  456.41  4726.7  454.75  4750.1  450.46  4763.5  448.10
  4799.2  449.53  4884.9  446.86  4896.9  444.34  4901.4  445.66  4917.4  447.91
  4968.7  448.71  4989.2  442.71  4991.3  439.57  4992.0  438.77  5002.5  439.57
  5004.0  440.77  5008.2  444.13  5021.6  448.30  5043.6  448.80  5128.0  445.41
  5156.4  448.57  5344.7  449.20  5384.9  447.50  5511.5  450.46  5827.1  466.38
#Mann=7,-1,0
  4332.4    0.05       0  4726.7    0.12       0  4799.2    0.16       0
  4901.4    0.07       0  4991.3    0.07       0  5002.5    0.07       0
  5004.0    0.05       0
Bank Sta=4750.1,5511.5
Exp/Cntr=0.3,0.1

Type RM Length L Ch R = 1,43380,1212,1212,1212
BEGIN DESCRIPTION:
COFFEE CREEK 34.0
END DESCRIPTION:
XS GIS Cut Line= 3
      2896875.02      7061275.01      2896275.00      7061075.00
      2895208.80      7062054.05
#Sta/Elev= 30
  4337.2  477.94  4495.3  472.52  4600.7  467.13  4716.7  458.22  4802.2  455.19
  4832.6  453.73  4861.2  449.69  4874.8  447.82  4917.0  447.57  4948.6  448.83
  4959.1  451.09  4973.1  451.44  4997.7  444.77  4999.5  437.97  5000.2  437.17
  5010.1  437.17  5010.8  437.97  5026.1  445.51  5033.5  446.78  5063.6  446.94
  5160.5  447.57  5203.1  446.68  5337.5  446.66  5599.5  447.97  5695.2  449.69
  5882.5  454.63  6073.7  464.16  6229.6  465.43  6356.7  470.66  6417.2  471.89
#Mann=5,-1,0
  4337.2    0.05       0  4802.2    0.12       0  4999.5    0.07       0
  5010.8    0.12       0  5063.6    0.05       0
Bank Sta=4861.2,5695.2
Exp/Cntr=0.3,0.1

Type RM Length L Ch R = 1,42168,1246,1246,1246
BEGIN DESCRIPTION:
Mapping XS 49e0d73f
END DESCRIPTION:
XS GIS Cut Line= 3
      2896881.06      7060838.94      2895783.87      7060554.22
      2894763.68      7061220.47
#Sta/Elev= 30
  3479.4  467.33  3534.0  464.75  3723.3  454.77  3879.5  451.46  4111.4  448.64
  4260.5  451.38  4371.4  447.96  4471.4  444.72  4981.8  445.66  4994.5  441.71
  4998.0  437.44  4998.7  436.64  5009.3  437.44  5017.7  439.97  5024.7  446.00
  5034.6  447.96  5060.9  448.51  5082.0  452.87  5097.1  450.09  5112.3  450.42
  5118.2  453.61  5161.0  450.60  5205.8  455.49  5299.3  457.61  5320.3  461.12
  5370.2  460.01  5454.5  466.69  5490.3  467.10  5627.2  472.18  5831.4  472.98
#Mann=9,-1,0
  3479.4    0.12       0  3534.0    0.16       0  3879.5    0.12       0
  4998.0    0.07       0  5009.3    0.12       0  5370.2    0.16       0
  5454.5    0.08       0  5490.3    0.05       0  5627.2     0.1       0
Bank Sta=4371.4,5034.6
Exp/Cntr=0.3,0.1

Type RM Length L Ch R = 1,40922,658,658,658
BEGIN DESCRIPTION:
COFFEE CREEK 33.0
END DESCRIPTION:
XS GIS Cut Line= 3
      2896300.68      7060272.65      2895637.46      7059925.41
      2894558.79      7060195.94
#Sta/Elev= 30
  4166.9  449.64  4207.2  448.09  4258.4  449.17  4368.7  448.13  4442.2  445.40
  4523.2  443.64  4666.4  443.24  4716.2  441.16  4842.9  443.32  4949.0  442.96
  4969.6  441.57  4975.1  439.17  4980.3  441.19  4994.9  432.47  4995.5  431.67
  5006.2  432.47  5010.9  433.71  5016.3  438.00  5031.5  443.11  5041.8  444.21
  5062.6  443.02  5139.8  444.02  5237.7  443.23  5358.9  444.73  5387.6  445.40
  5498.8  447.60  5633.9  449.44  5773.8  449.10  5922.1  452.08  6027.6  457.64
#Mann=5,-1,0
  4166.9    0.12       0  4994.9    0.07       0  5006.2    0.12       0
  5358.9    0.16       0  5498.8    0.05       0
Bank Sta=4442.2,5387.6
Exp/Cntr=0.3,0.1

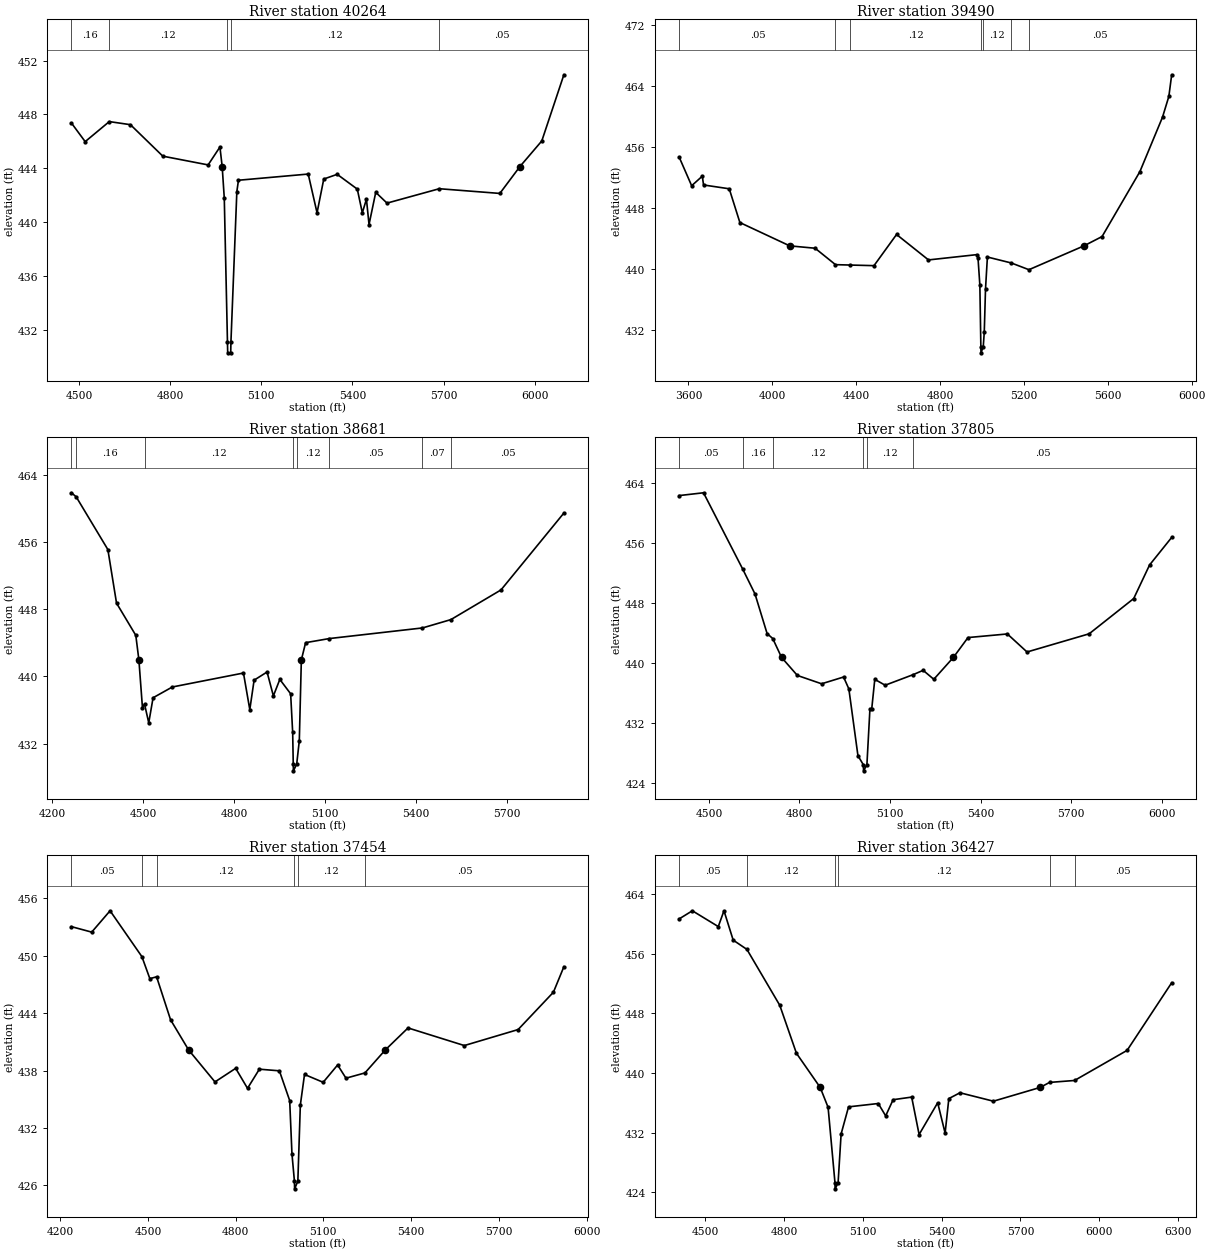
Type RM Length L Ch R = 1,40264,774,774,774
BEGIN DESCRIPTION:
COFFEE CREEK 32.0
END DESCRIPTION:
XS GIS Cut Line= 3
      2896057.39      7059628.47      2895494.99      7059422.71
      2894588.74      7059895.24
#Sta/Elev= 30
  4475.3  447.36  4520.4  445.98  4599.8  447.47  4669.4  447.24  4776.0  444.90
  4925.1  444.25  4964.0  445.58  4971.4  444.13  4978.3  441.78  4988.8  431.08
  4989.5  430.28  4999.5  430.28  5000.2  431.08  5019.7  442.27  5025.0  443.11
  5254.6  443.57  5283.7  440.69  5305.8  443.20  5350.0  443.55  5416.2  442.45
  5432.7  440.69  5446.3  441.70  5454.8  439.82  5476.9  442.21  5514.0  441.41
  5686.1  442.48  5885.4  442.13  5951.6  444.13  6023.5  446.03  6096.2  450.95
#Mann=5,-1,0
  4475.3    0.16       0  4599.8    0.12       0  4988.8    0.07       0
  5000.2    0.12       0  5686.1    0.05       0
Bank Sta=4971.4,5951.6
Exp/Cntr=0.3,0.1

Type RM Length L Ch R = 1,39490,809,809,809
BEGIN DESCRIPTION:
COFFEE CREEK 31.0
END DESCRIPTION:
XS GIS Cut Line= 3
      2896268.31      7058356.40      2895075.00      7059175.00
      2894324.99      7059675.01
#Sta/Elev= 30
  3556.2  454.64  3615.2  450.93  3666.0  452.18  3672.0  451.03  3794.5  450.53
  3845.3  446.11  4083.0  443.06  4204.0  442.75  4301.2  440.60  4371.5  440.55
  4484.9  440.47  4592.5  444.55  4744.8  441.22  4974.9  441.91  4980.9  441.51
  4989.8  437.93  4994.6  429.86  4995.3  429.06  5006.0  429.86  5010.8  431.75
  5016.8  437.43  5025.8  441.60  5139.9  440.82  5223.9  439.94  5486.2  443.06
  5572.7  444.28  5753.0  452.77  5861.1  459.91  5891.2  462.62  5904.7  465.45
#Mann=7,-1,0
  3556.2    0.05       0  4301.2    0.16       0  4371.5    0.12       0
  4994.6    0.07       0  5006.0    0.12       0  5139.9    0.07       0
  5223.9    0.05       0
Bank Sta=4083,5486.2
Exp/Cntr=0.3,0.1

Type RM Length L Ch R = 1,38681,876,876,876
BEGIN DESCRIPTION:
COFFEE CREEK 30.0
END DESCRIPTION:
XS GIS Cut Line= 3
      2895425.02      7058174.98      2894724.88      7058780.74
      2894261.43      7059304.26
#Sta/Elev= 30
  4263.4  461.84  4279.1  461.35  4383.5  455.09  4412.1  448.72  4475.7  444.89
  4485.9  441.96  4497.6  436.31  4504.4  436.73  4518.4  434.49  4532.7  437.47
  4596.3  438.75  4831.0  440.41  4851.9  436.06  4866.1  439.56  4908.9  440.53
  4929.7  437.69  4951.0  439.65  4986.7  437.94  4993.4  433.34  4995.3  429.58
  4995.9  428.78  5006.7  429.58  5015.3  432.37  5022.0  441.96  5036.1  444.02
  5114.8  444.51  5421.8  445.77  5515.5  446.76  5680.9  450.29  5888.4  459.43
#Mann=8,-1,0
  4263.4    0.05       0  4279.1    0.16       0  4504.4    0.12       0
  4995.3    0.07       0  5006.7    0.12       0  5114.8    0.05       0
  5421.8    0.07       0  5515.5    0.05       0
Bank Sta=4485.9,5022
Exp/Cntr=0.3,0.1

Type RM Length L Ch R = 1,37805,351,351,351
BEGIN DESCRIPTION:
COFFEE CREEK 29.0
END DESCRIPTION:
XS GIS Cut Line= 3
      2895524.99      7058125.00      2894925.00      7058075.00
      2894025.03      7058574.98
#Sta/Elev= 30
  4401.8  462.28  4482.1  462.65  4612.2  452.48  4652.7  449.19  4692.8  443.92
  4711.5  443.26  4740.7  440.75  4793.1  438.35  4873.4  437.24  4946.2  438.14
  4963.7  436.56  4993.8  427.68  5011.8  426.46  5012.4  425.66  5023.5  426.46
  5033.6  433.94  5039.3  433.82  5049.6  437.83  5084.0  437.05  5177.7  438.47
  5209.8  439.03  5245.2  437.84  5310.1  440.75  5358.5  443.39  5488.9  443.87
  5554.1  441.47  5760.0  443.89  5907.6  448.58  5960.2  453.05  6033.4  456.71
#Mann=6,-1,0
  4401.8    0.05       0  4612.2    0.16       0  4711.5    0.12       0
  5011.8    0.07       0  5023.5    0.12       0  5177.7    0.05       0
Bank Sta=4740.7,5310.1
Exp/Cntr=0.3,0.1

Type RM Length L Ch R = 1,37454,1027,1027,1027
BEGIN DESCRIPTION:
COFFEE CREEK 28.0
END DESCRIPTION:
XS GIS Cut Line= 3
      2895559.84      7057860.43      2894919.62      7057760.59
      2894124.96      7058425.03
#Sta/Elev= 30
  4238.7  453.04  4307.9  452.47  4370.7  454.70  4479.5  449.91  4506.7  447.61
  4529.8  447.80  4577.6  443.31  4639.3  440.16  4729.4  436.82  4800.2  438.24
  4840.7  436.15  4881.2  438.15  4949.7  437.98  4984.9  434.87  4992.7  429.29
  5001.1  426.45  5001.7  425.65  5012.8  426.45  5021.3  434.40  5035.6  437.60
  5099.4  436.78  5148.8  438.59  5177.4  437.21  5242.2  437.76  5311.8  440.16
  5389.6  442.46  5582.1  440.62  5766.0  442.29  5886.7  446.19  5922.5  448.85
#Mann=6,-1,0
  4238.7    0.05       0  4479.5    0.16       0  4529.8    0.12       0
  5001.1    0.07       0  5012.8    0.12       0  5242.2    0.05       0
Bank Sta=4639.3,5311.8
Exp/Cntr=0.3,0.1

Type RM Length L Ch R = 1,36427,763,763,763
BEGIN DESCRIPTION:
COFFEE CREEK 27.0
END DESCRIPTION:
XS GIS Cut Line= 3
      2895025.02      7056724.99      2894575.00      7057125.00
      2893675.00      7058025.00
#Sta/Elev= 30
  4401.2  460.70  4451.0  461.78  4549.7  459.66  4571.4  461.78  4606.5  457.84
  4658.7  456.60  4783.8  449.10  4847.3  442.66  4937.7  438.08  4967.8  435.41
  4994.1  425.27  4994.6  424.47  5005.9  425.27  5017.4  431.83  5045.7  435.47
  5158.9  435.92  5187.1  434.26  5215.4  436.43  5286.1  436.78  5314.4  431.76
  5385.1  436.02  5413.4  431.95  5427.6  436.58  5470.0  437.36  5597.3  436.23
  5775.7  438.08  5811.0  438.75  5906.3  439.01  6106.4  443.05  6276.1  452.12
#Mann=6,-1,0
  4401.2    0.05       0  4658.7    0.12       0  4994.1    0.07       0
  5005.9    0.12       0  5811.0    0.16       0  5906.3    0.05       0
Bank Sta=4937.7,5775.7
Exp/Cntr=0.3,0.1

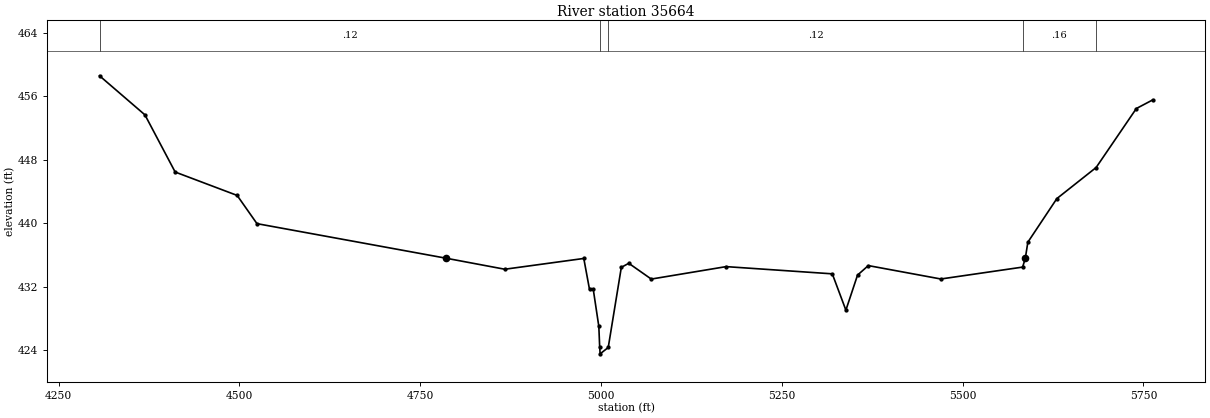
Type RM Length L Ch R = 1,35664,871,871,871
BEGIN DESCRIPTION:
COFFEE CREEK 26.0
END DESCRIPTION:
XS GIS Cut Line= 3
      2894625.00      7056625.00      2893975.00      7056825.00
      2893224.98      7057025.01
#Sta/Elev= 30
  4306.6  458.60  4369.4  453.67  4411.2  446.46  4496.9  443.51  4524.3  439.95
  4785.8  435.59  4867.0  434.20  4976.2  435.56  4984.1  431.66  4989.3  431.66
  4997.0  426.98  4998.2  424.33  4998.8  423.53  5010.0  424.33  5028.1  434.44
  5038.4  434.95  5069.5  432.96  5173.0  434.53  5319.8  433.62  5338.6  429.04
  5354.7  433.46  5369.6  434.66  5469.9  432.97  5583.0  434.47  5586.7  435.59
  5590.2  437.61  5630.3  443.11  5684.6  447.03  5740.2  454.47  5762.9  455.56
#Mann=5,-1,0
  4306.6    0.12       0  4998.2    0.07       0  5010.0    0.12       0
  5583.0    0.16       0  5684.6    0.12       0
Bank Sta=4785.8,5586.7
Exp/Cntr=0.3,0.1