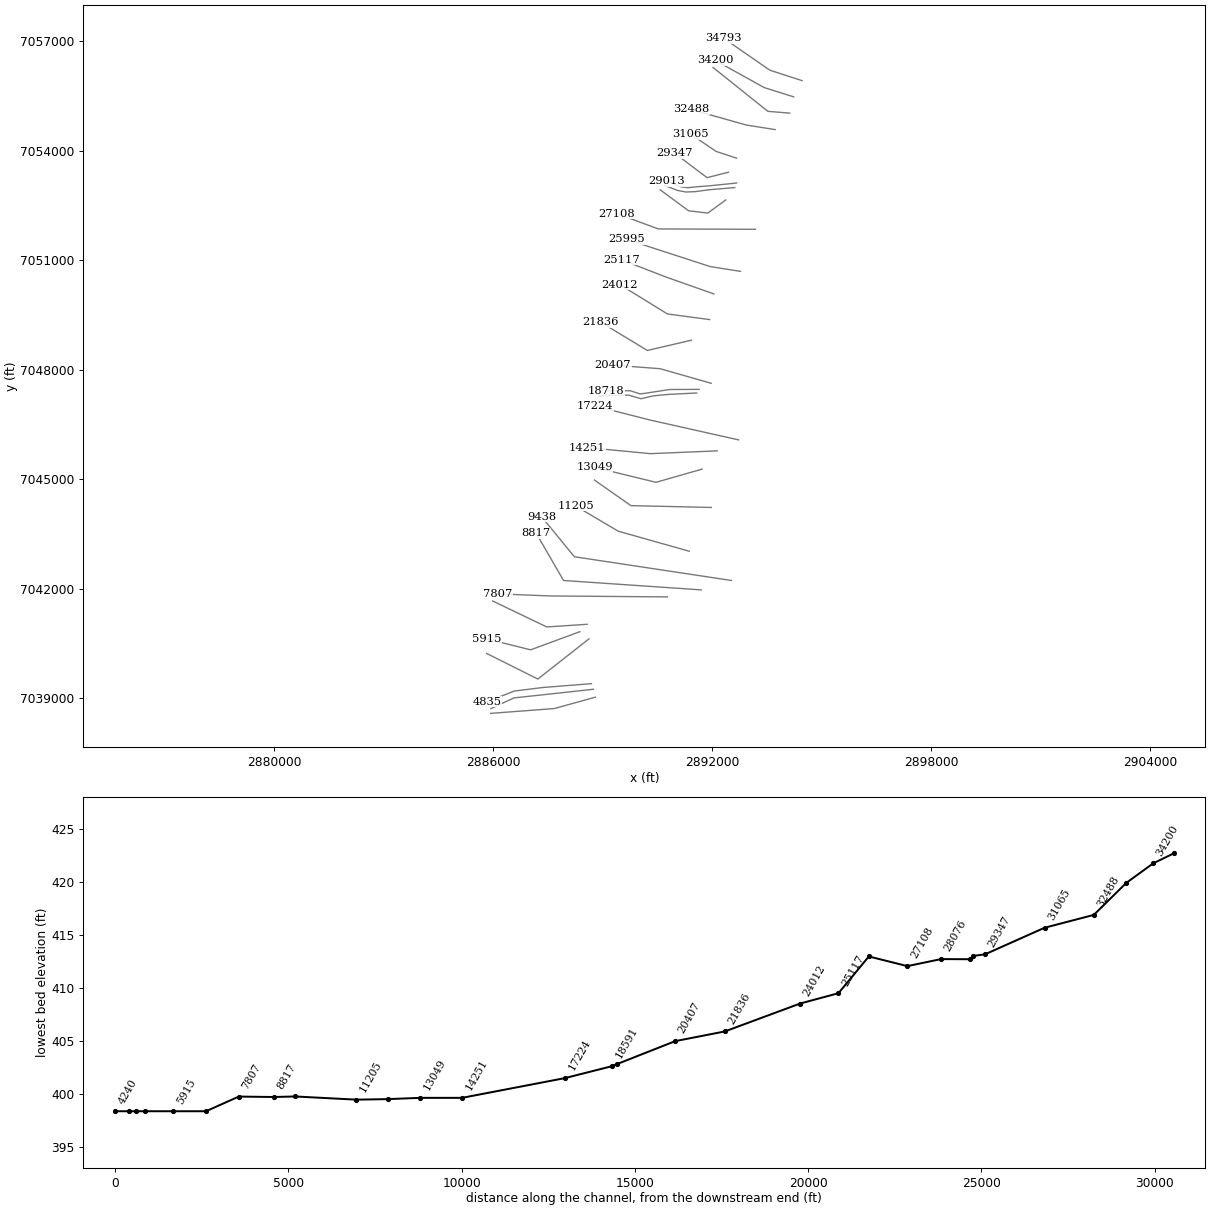
HEC-RAS study COFFEE CREEK.prj: COFFEE CREEK Base Level Engineering

--- COFFEE CREEK.g01 (geometry) --- (continued)

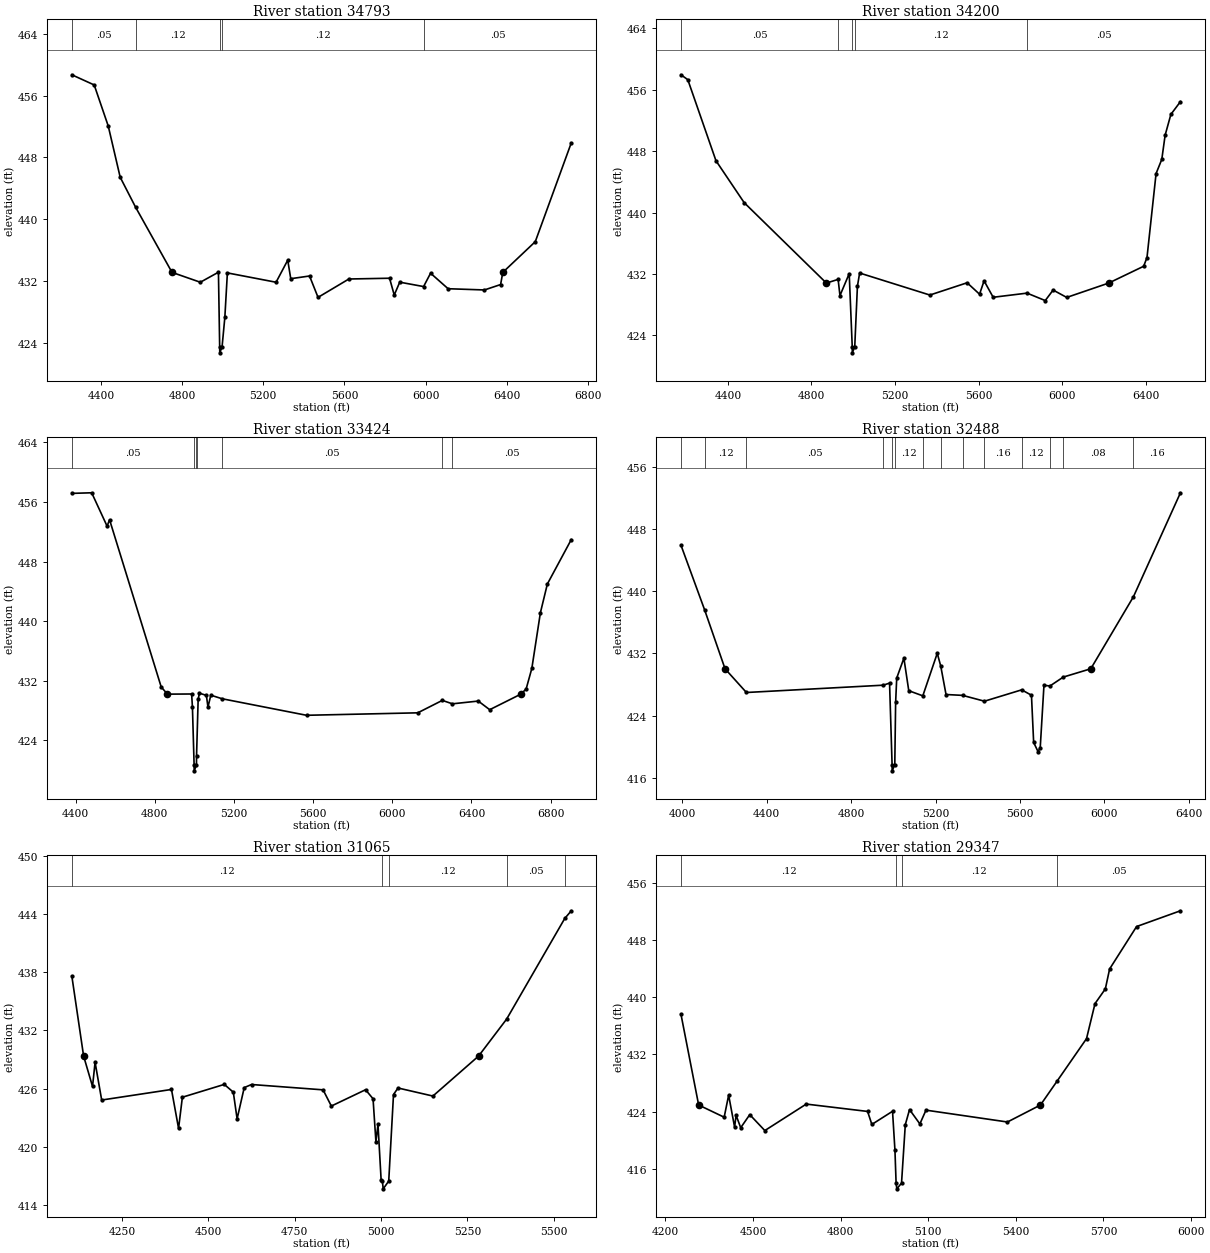
Type RM Length L Ch R = 1,34793,593,593,593
BEGIN DESCRIPTION:
COFFEE CREEK 25.0
END DESCRIPTION:
XS GIS Cut Line= 3
      2894462.78      7055915.41      2893580.85      7056200.13
      2892318.50      7057074.06
#Sta/Elev= 30
  4256.3  458.72  4366.6  457.40  4435.9  452.07  4494.7  445.44  4570.5  441.56
  4750.1  433.11  4889.7  431.83  4979.0  433.13  4985.1  423.48  4985.6  422.68
  4997.0  423.48  5010.6  427.28  5023.1  433.04  5263.1  431.83  5320.6  434.69
  5335.5  432.29  5428.1  432.64  5470.0  429.87  5622.0  432.25  5822.6  432.35
  5845.6  430.17  5872.7  431.84  5990.3  431.27  6024.7  433.00  6111.2  430.99
  6290.3  430.83  6369.9  431.53  6380.8  433.11  6540.9  437.09  6718.4  449.90
#Mann=5,-1,0
  4256.3    0.05       0  4570.5    0.12       0  4985.1    0.07       0
  4997.0    0.12       0  5990.3    0.05       0
Bank Sta=4750.1,6380.8
Exp/Cntr=0.3,0.1

Type RM Length L Ch R = 1,34200,776,776,776
BEGIN DESCRIPTION:
COFFEE CREEK 24.0
END DESCRIPTION:
XS GIS Cut Line= 3
      2894233.65      7055470.95      2893425.00      7055725.00
      2892074.97      7056475.02
#Sta/Elev= 30
  4175.0  457.97  4207.7  457.33  4342.6  446.77  4477.6  441.31  4871.4  430.83
  4927.6  431.31  4936.4  429.20  4980.7  432.06  4995.2  422.54  4995.7  421.74
  5007.2  422.54  5020.0  430.41  5030.6  432.14  5367.0  429.27  5545.4  430.87
  5604.9  429.38  5626.6  431.12  5670.1  428.98  5832.3  429.52  5919.5  428.55
  5957.2  429.92  6022.4  428.96  6223.3  430.83  6390.8  433.02  6406.8  434.16
  6450.3  445.10  6477.7  446.95  6493.7  450.10  6521.2  452.81  6567.0  454.47
#Mann=5,-1,0
  4175.0    0.05       0  4927.6    0.12       0  4995.2    0.07       0
  5007.2    0.12       0  5832.3    0.05       0
Bank Sta=4871.4,6223.3
Exp/Cntr=0.3,0.1

Type RM Length L Ch R = 1,33424,936,936,936
BEGIN DESCRIPTION:
COFFEE CREEK 23.0
END DESCRIPTION:
XS GIS Cut Line= 3
      2894124.97      7055025.00      2893525.00      7055075.00
      2892024.99      7056275.01
#Sta/Elev= 30
  4381.4  457.16  4481.7  457.24  4559.5  452.76  4572.0  453.62  4832.9  431.16
  4864.4  430.20  4986.6  430.22  4990.6  428.46  4999.1  420.70  4999.6  419.90
  5011.1  420.70  5011.4  421.87  5019.5  429.48  5025.9  430.33  5061.1  430.03
  5069.1  428.46  5083.5  430.06  5140.6  429.58  5566.9  427.36  6128.8  427.69
  6252.9  429.36  6303.9  428.90  6434.6  429.27  6492.2  428.11  6649.6  430.20
  6676.3  430.89  6705.1  433.66  6748.3  441.13  6783.5  444.99  6904.4  450.96
#Mann=7,-1,0
  4381.4    0.05       0  4999.1    0.03       0  5011.1    0.05       0
  5011.4    0.16       0  5140.6    0.05       0  6252.9    0.08       0
  6303.9    0.05       0
Bank Sta=4864.4,6649.6
Exp/Cntr=0.3,0.1

Type RM Length L Ch R = 1,32488,1423,1423,1423
BEGIN DESCRIPTION:
COFFEE CREEK 22.0
END DESCRIPTION:
XS GIS Cut Line= 3
      2893724.95      7054575.01      2892938.49      7054698.39
      2891425.04      7055124.99
#Sta/Elev= 30
  3993.0  445.89  4105.5  437.55  4201.9  430.01  4303.3  426.96  4952.6  427.90
  4982.1  428.17  4994.1  417.69  4994.6  416.89  5006.9  417.69  5010.9  425.68
  5016.1  428.82  5050.1  431.37  5073.2  427.19  5139.8  426.53  5208.3  432.00
  5224.9  430.35  5249.9  426.70  5328.5  426.59  5432.1  425.84  5608.6  427.30
  5655.0  426.61  5665.4  420.54  5686.2  419.36  5696.6  419.87  5714.3  427.88
  5742.9  427.80  5805.8  428.94  5936.4  430.01  6138.8  439.28  6361.5  452.63
#Mann=14,-1,0
  3993.0    0.05       0  4105.5    0.12       0  4303.3    0.05       0
  4952.6    0.12       0  4994.1    0.07       0  5006.9    0.12       0
  5139.8    0.07       0  5224.9    0.05       0  5328.5    0.07       0
  5432.1    0.16       0  5608.6    0.12       0  5742.9    0.16       0
  5805.8    0.08       0  6138.8    0.16       0
Bank Sta=4201.9,5936.4
Exp/Cntr=0.3,0.1

Type RM Length L Ch R = 1,31065,1718,1718,1718
BEGIN DESCRIPTION:
COFFEE CREEK 21.0
END DESCRIPTION:
XS GIS Cut Line= 3
      2892668.91      7053791.96      2892109.88      7053975.98
      2891399.07      7054454.48
#Sta/Elev= 30
  4105.1  437.61  4139.2  429.36  4165.0  426.23  4172.4  428.72  4191.5  424.83
  4393.5  425.92  4414.0  421.91  4425.0  425.12  4546.3  426.44  4572.4  425.64
  4583.4  422.89  4604.0  426.11  4625.1  426.43  4832.2  425.88  4856.1  424.21
  4955.1  425.89  4976.8  424.96  4985.1  420.53  4991.1  422.32  5000.1  416.64
  5003.7  416.48  5006.2  415.68  5022.2  416.48  5036.0  425.40  5049.1  426.07
  5150.0  425.24  5282.2  429.36  5363.4  433.17  5531.6  443.54  5550.5  444.33
#Mann=5,-1,0
  4105.1    0.12       0  5003.7    0.07       0  5022.2    0.12       0
  5363.4    0.05       0  5531.6    0.16       0
Bank Sta=4139.2,5282.2
Exp/Cntr=0.3,0.1

Type RM Length L Ch R = 1,29347,334,334,334
BEGIN DESCRIPTION:
COFFEE CREEK 20.0
END DESCRIPTION:
XS GIS Cut Line= 3
      2892443.17      7053406.53      2891859.98      7053257.95
      2890975.03      7053924.98
#Sta/Elev= 30
  4253.5  437.62  4314.0  424.92  4401.4  423.21  4416.7  426.30  4437.1  421.82
  4442.2  423.48  4458.0  421.74  4489.0  423.57  4540.6  421.34  4682.4  425.05
  4892.4  424.02  4907.0  422.20  4977.8  424.04  4986.1  418.56  4990.0  413.98
  4992.5  413.18  5008.6  413.98  5021.5  422.16  5036.0  424.28  5071.4  422.27
  5092.3  424.20  5371.2  422.54  5484.3  424.92  5540.9  428.25  5641.9  434.21
  5671.0  439.12  5706.4  441.18  5721.0  443.97  5813.3  449.91  5963.5  452.12
#Mann=4,-1,0
  4253.5    0.12       0  4990.0    0.07       0  5008.6    0.12       0
  5540.9    0.05       0
Bank Sta=4314,5484.3
Exp/Cntr=0.3,0.1

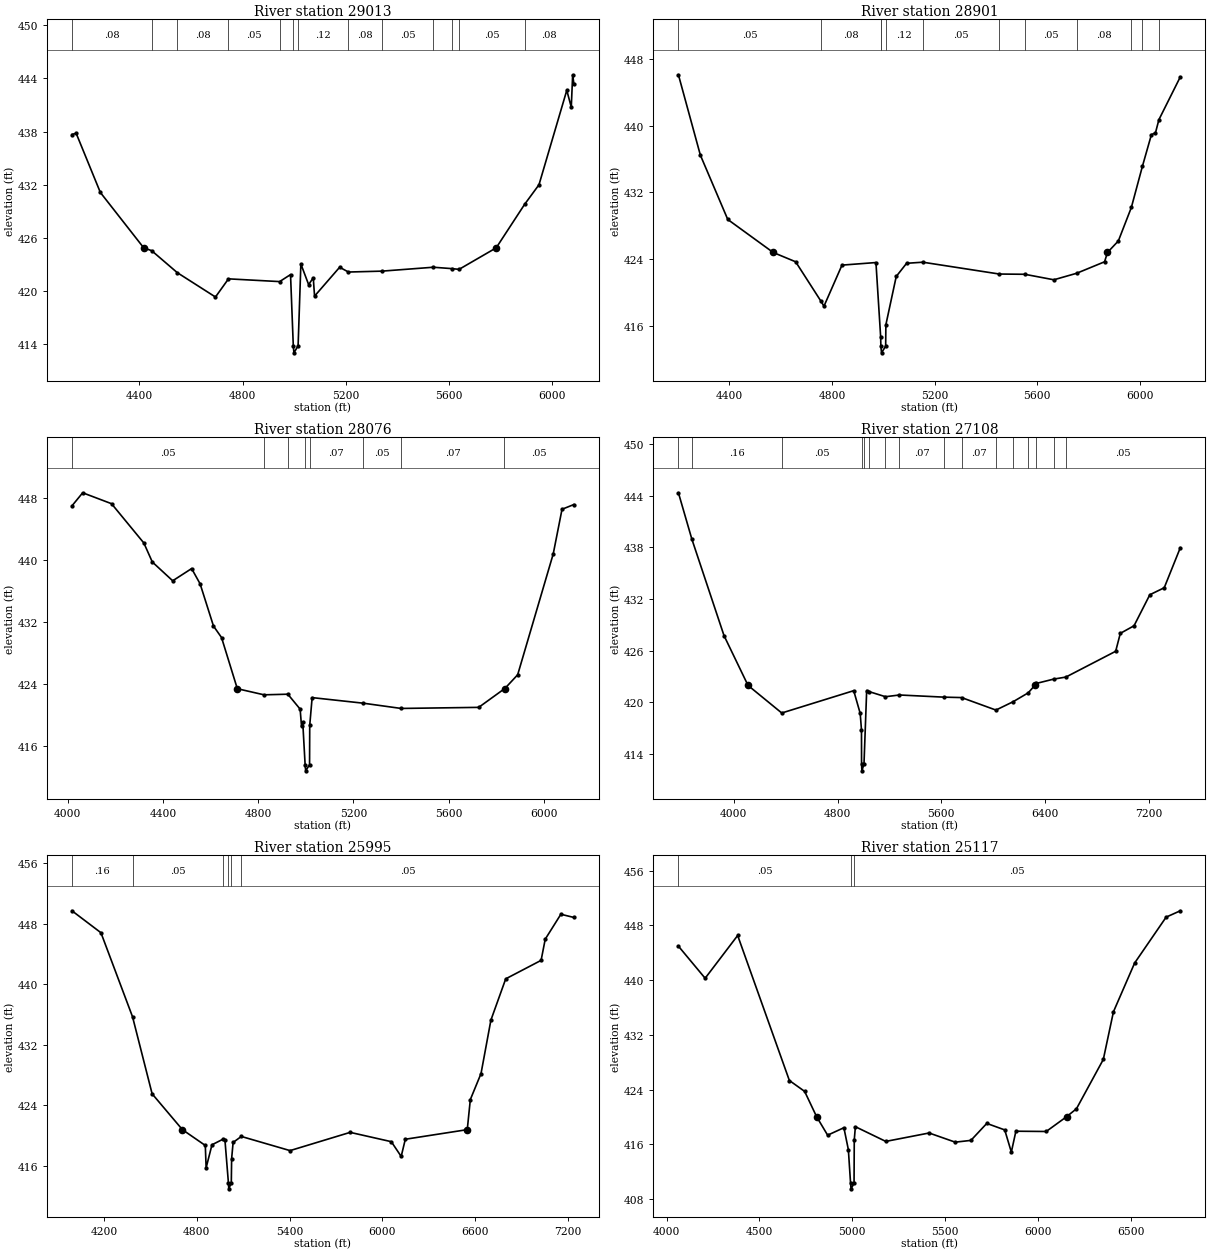
Type RM Length L Ch R = 1,29013,112,112,112
BEGIN DESCRIPTION:
Mapping XS e58b3a41
END DESCRIPTION:
XS GIS Cut Line= 6
      2892668.94      7053111.40      2891964.05      7053038.48
      2891575.16      7053007.23      2891328.63      7052982.93
      2891144.61      7053007.23      2890759.59      7053163.32
#Sta/Elev= 30
  4137.9  437.67  4154.2  437.81  4248.1  431.13  4416.4  424.88  4447.2  424.56
  4546.6  422.08  4694.8  419.33  4745.3  421.38  4943.8  421.07  4986.1  421.86
  4996.8  413.83  4999.3  413.03  5015.5  413.83  5026.2  423.06  5056.3  420.73
  5074.3  421.50  5079.3  419.43  5176.7  422.69  5210.7  422.15  5340.7  422.25
  5539.8  422.69  5614.4  422.53  5640.0  422.45  5784.2  424.88  5894.7  429.80
  5950.2  432.00  6058.1  442.66  6075.5  440.75  6080.9  444.41  6085.5  443.42
#Mann=13,-1,0
  4137.9    0.08       0  4447.2    0.05       0  4546.6    0.08       0
  4745.3    0.05       0  4943.8    0.12       0  4996.8    0.07       0
  5015.5    0.12       0  5210.7    0.08       0  5340.7    0.05       0
  5539.8    0.08       0  5614.4    0.07       0  5640.0    0.05       0
  5894.7    0.08       0
Bank Sta=4416.4,5784.2
Exp/Cntr=0.3,0.1

Type RM Length L Ch R = 1,28901,825,825,825
BEGIN DESCRIPTION:
Mapping XS 26cb23a8
END DESCRIPTION:
XS GIS Cut Line= 6
      2892620.32      7052986.40      2891884.19      7052923.90
      2891540.44      7052875.29      2891283.49      7052864.87
      2891054.33      7052906.54      2890700.12      7053045.44
#Sta/Elev= 30
  4201.3  446.10  4286.9  436.45  4393.7  428.73  4570.7  424.77  4658.3  423.65
  4756.3  418.95  4768.7  418.32  4838.9  423.25  4971.3  423.56  4989.7  414.62
  4990.5  413.52  4993.0  412.72  5009.2  413.52  5010.0  416.09  5050.4  421.89
  5090.8  423.47  5154.2  423.60  5452.2  422.18  5551.4  422.15  5664.8  421.49
  5753.6  422.27  5862.5  423.65  5873.8  424.77  5916.2  426.15  5966.9  430.17
  6010.0  435.11  6045.1  438.91  6061.0  439.14  6074.3  440.71  6157.8  445.85
#Mann=12,-1,0
  4201.3    0.05       0  4756.3    0.08       0  4989.7    0.12       0
  4990.5    0.07       0  5009.2    0.12       0  5154.2    0.05       0
  5452.2    0.07       0  5551.4    0.05       0  5753.6    0.08       0
  5966.9    0.05       0  6010.0    0.08       0  6074.3    0.05       0
Bank Sta=4570.7,5873.8
Exp/Cntr=0.3,0.1

Type RM Length L Ch R = 1,28076,968,968,968
BEGIN DESCRIPTION:
COFFEE CREEK 19.0
END DESCRIPTION:
XS GIS Cut Line= 4
      2892373.64      7052648.70      2891881.30      7052288.19
      2891353.52      7052350.69      2890575.01      7052924.99
#Sta/Elev= 30
  4017.6  446.96  4062.7  448.65  4183.9  447.24  4319.8  442.16  4355.3  439.71
  4441.0  437.28  4520.5  438.86  4556.1  436.89  4612.4  431.43  4646.2  429.95
  4712.5  423.34  4824.8  422.55  4924.8  422.63  4976.5  420.70  4982.4  418.46
  4987.5  418.98  4997.4  413.53  4999.9  412.73  5016.1  413.53  5016.8  418.60
  5026.9  422.19  5241.4  421.47  5400.9  420.79  5726.9  420.93  5833.6  423.30
  5836.0  423.34  5890.6  425.14  6040.0  440.75  6077.0  446.52  6126.7  447.13
#Mann=8,-1,0
  4017.6    0.05       0  4824.8    0.16       0  4924.8    0.07       0
  4997.4    0.07       0  5016.1    0.07       0  5241.4    0.05       0
  5400.9    0.07       0  5833.6    0.05       0
Bank Sta=4712.5,5836
Exp/Cntr=0.3,0.1

Type RM Length L Ch R = 1,27108,1113,1113,1113
BEGIN DESCRIPTION:
COFFEE CREEK 18.0
END DESCRIPTION:
XS GIS Cut Line= 3
      2893186.85      7051843.75      2890526.32      7051853.46
      2889390.69      7052271.85
#Sta/Elev= 30
  3572.7  444.33  3676.2  438.96  3924.6  427.75  4109.6  421.98  4369.7  418.78
  4924.6  421.37  4974.6  418.74  4984.6  416.80  4985.2  412.87  4987.7  412.07
  5003.9  412.87  5024.6  421.39  5043.5  421.26  5169.6  420.67  5277.7  420.87
  5621.0  420.62  5756.6  420.57  6021.4  419.12  6152.8  420.08  6270.7  421.12
  6320.8  421.98  6332.8  422.21  6466.2  422.71  6561.0  422.95  6944.9  425.94
  6980.7  428.02  7086.5  428.90  7208.3  432.50  7319.4  433.31  7443.5  437.96
#Mann=16,-1,0
  3572.7    0.05       0  3676.2    0.16       0  4369.7    0.05       0
  4985.2    0.03       0  5003.9    0.05       0  5043.5    0.07       0
  5169.6    0.05       0  5277.7    0.07       0  5621.0    0.05       0
  5756.6    0.07       0  6021.4    0.05       0  6152.8    0.16       0
  6270.7    0.05       0  6332.8    0.16       0  6466.2    0.07       0
  6561.0    0.05       0
Bank Sta=4109.6,6320.8
Exp/Cntr=0.3,0.1

Type RM Length L Ch R = 1,25995,878,878,878
BEGIN DESCRIPTION:
COFFEE CREEK 17.0
END DESCRIPTION:
XS GIS Cut Line= 3
      2892777.11      7050690.97      2891943.80      7050822.92
      2889659.56      7051565.81
#Sta/Elev= 30
  3992.7  449.71  4180.2  446.81  4384.6  435.70  4511.2  425.53  4706.9  420.80
  4855.1  418.71  4860.4  415.76  4898.2  418.80  4968.8  419.53  4982.3  419.37
  5004.5  413.78  5007.0  412.98  5023.2  413.78  5025.3  416.96  5034.9  419.11
  5088.0  419.90  5403.0  418.03  5791.9  420.44  6057.9  419.21  6121.8  417.26
  6148.5  419.53  6549.1  420.80  6568.9  424.77  6638.1  428.21  6702.0  435.27
  6797.8  440.72  7026.6  443.16  7053.3  445.96  7154.4  449.25  7238.4  448.83
#Mann=6,-1,0
  3992.7    0.16       0  4384.6    0.05       0  4968.8     0.1       0
  5004.5    0.07       0  5023.2     0.1       0  5088.0    0.05       0
Bank Sta=4706.9,6549.1
Exp/Cntr=0.3,0.1

Type RM Length L Ch R = 1,25117,1105,1105,1105
BEGIN DESCRIPTION:
COFFEE CREEK 16.0
END DESCRIPTION:
XS GIS Cut Line= 3
      2892047.95      7050072.92      2890728.52      7050538.19
      2889513.77      7051010.21
#Sta/Elev= 30
  4063.5  444.98  4207.4  440.29  4382.5  446.54  4660.9  425.35  4743.1  423.76
  4807.6  420.06  4866.9  417.36  4954.4  418.45  4978.5  415.25  4990.4  410.32
  4992.9  409.52  5009.1  410.32  5010.3  416.67  5016.3  418.60  5180.0  416.45
  5413.3  417.68  5554.0  416.34  5638.3  416.60  5723.8  419.08  5820.4  418.13
  5856.0  414.89  5880.5  417.94  6043.8  417.90  6153.4  420.06  6206.6  421.22
  6351.2  428.43  6405.7  435.39  6519.9  442.52  6689.4  449.22  6765.8  450.15
#Mann=3,-1,0
  4063.5    0.05       0  4990.4    0.03       0  5009.1    0.05       0
Bank Sta=4807.6,6153.4
Exp/Cntr=0.3,0.1

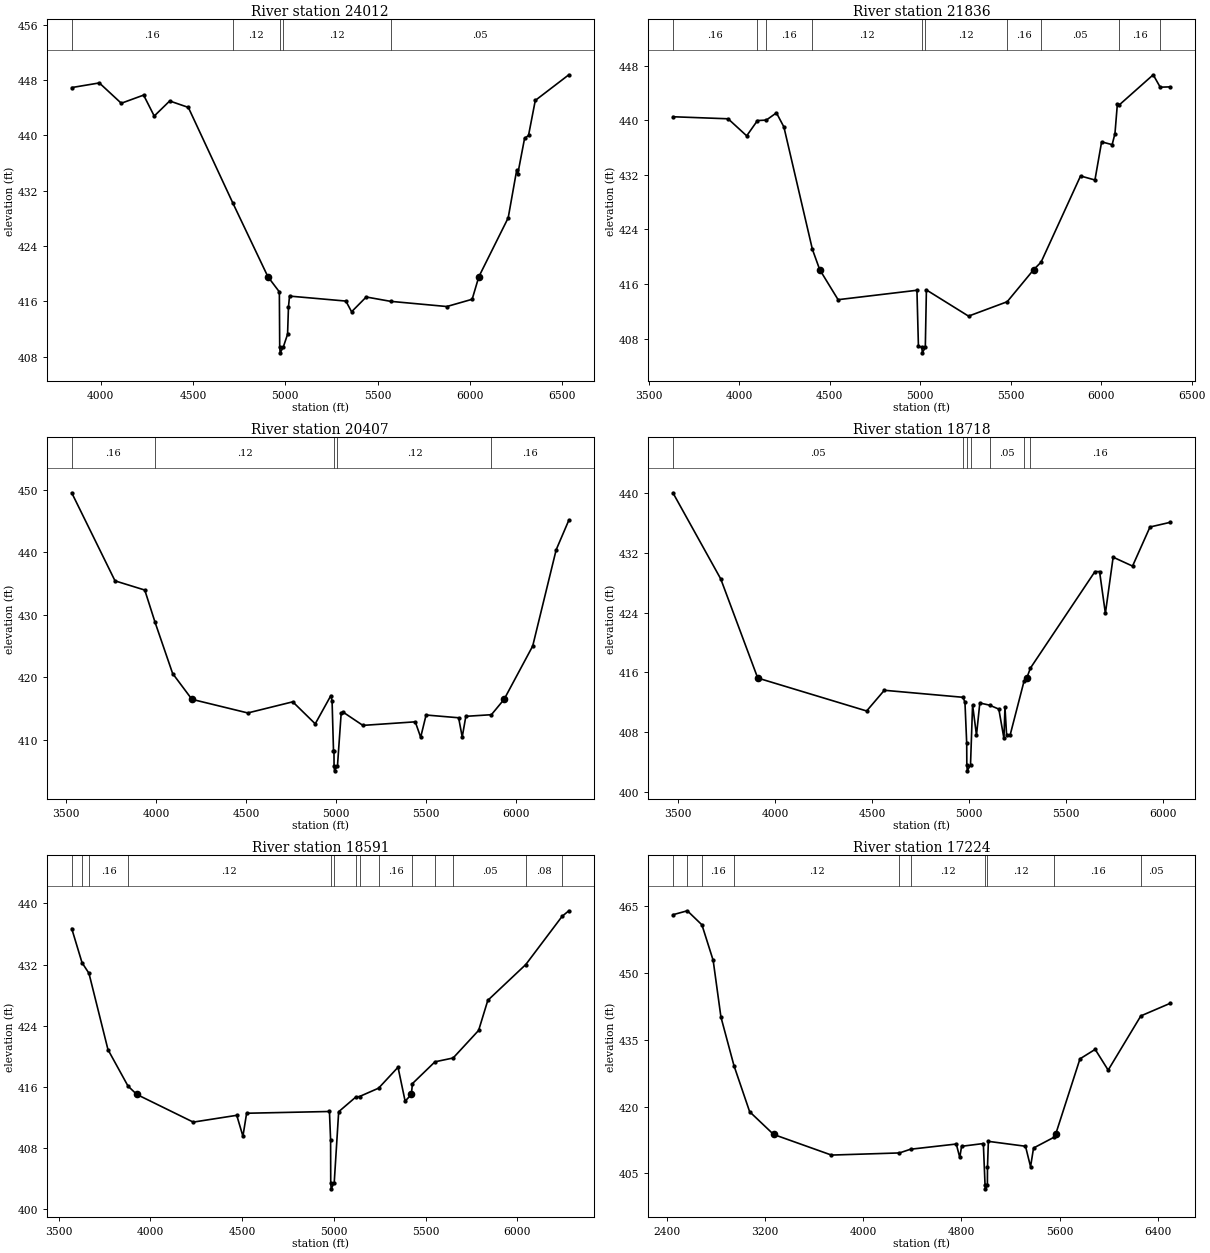
Type RM Length L Ch R = 1,24012,2176,2176,2176
BEGIN DESCRIPTION:
COFFEE CREEK 15.0
END DESCRIPTION:
XS GIS Cut Line= 3
      2891931.10      7049370.56      2890775.00      7049525.00
      2889475.00      7050325.00
#Sta/Elev= 30
  3842.9  446.93  3992.5  447.60  4111.4  444.66  4232.4  445.84  4289.9  442.81
  4373.7  444.99  4474.6  444.06  4715.1  430.26  4905.9  419.55  4967.7  417.37
  4969.6  409.35  4972.1  408.55  4988.5  409.35  5012.2  411.24  5017.0  415.15
  5022.8  416.76  5328.1  416.04  5359.0  414.49  5438.2  416.63  5570.4  416.00
  5874.9  415.25  6012.1  416.30  6048.1  419.55  6207.3  428.08  6253.5  435.01
  6259.4  434.46  6296.1  439.59  6317.4  440.00  6354.1  445.07  6535.7  448.78
#Mann=5,-1,0
  3842.9    0.16       0  4715.1    0.12       0  4969.6    0.07       0
  4988.5    0.12       0  5570.4    0.05       0
Bank Sta=4905.9,6048.1
Exp/Cntr=0.3,0.1

Type RM Length L Ch R = 1,21836,1429,1429,1429
BEGIN DESCRIPTION:
COFFEE CREEK 14.0
END DESCRIPTION:
XS GIS Cut Line= 3
      2891431.98      7048806.33      2890225.00      7048525.00
      2888936.33      7049305.43
#Sta/Elev= 30
  3634.5  440.52  3939.4  440.22  4042.1  437.72  4101.6  439.96  4150.4  440.03
  4206.4  441.09  4247.5  439.03  4405.0  421.09  4445.5  418.11  4546.9  413.71
  4982.5  415.09  4990.7  406.92  5009.8  406.72  5012.3  405.92  5028.7  406.72
  5034.8  415.14  5267.5  411.30  5481.0  413.41  5627.3  418.11  5668.2  419.21
  5886.2  431.84  5965.7  431.25  6002.6  436.84  6060.8  436.43  6076.3  438.05
  6089.7  442.41  6097.9  442.20  6287.6  446.67  6326.3  444.85  6380.4  444.90
#Mann=10,-1,0
  3634.5    0.16       0  4101.6    0.12       0  4150.4    0.16       0
  4405.0    0.12       0  5009.8    0.07       0  5028.7    0.12       0
  5481.0    0.16       0  5668.2    0.05       0  6097.9    0.16       0
  6326.3    0.05       0
Bank Sta=4445.5,5627.3
Exp/Cntr=0.3,0.1

Type RM Length L Ch R = 1,20407,1689,1689,1689
BEGIN DESCRIPTION:
COFFEE CREEK 13.0
END DESCRIPTION:
XS GIS Cut Line= 3
      2891975.01      7047625.00      2890575.00      7048025.00
      2889274.97      7048125.00
#Sta/Elev= 30
  3531.4  449.49  3771.9  435.40  3937.0  433.93  3994.5  428.74  4091.7  420.58
  4198.8  416.45  4509.0  414.27  4758.6  416.05  4883.4  412.53  4970.5  417.06
  4977.0  416.14  4984.8  408.26  4987.4  408.26  4988.0  405.81  4990.5  405.01
  5006.9  405.81  5027.5  414.25  5037.6  414.41  5147.9  412.28  5438.8  412.85
  5468.8  410.38  5498.9  413.94  5679.5  413.50  5699.5  410.42  5719.6  413.73
  5861.5  413.99  5932.1  416.45  6090.7  424.97  6221.1  440.37  6291.3  445.10
#Mann=5,-1,0
  3531.4    0.16       0  3994.5    0.12       0  4988.0    0.07       0
  5006.9    0.12       0  5861.5    0.16       0
Bank Sta=4198.8,5932.1
Exp/Cntr=0.3,0.1

Type RM Length L Ch R = 1,18718,127,127,127
BEGIN DESCRIPTION:
Mapping XS 776e8618
END DESCRIPTION:
XS GIS Cut Line= 6
      2891641.70      7047459.63      2890834.42      7047455.29
      2890164.28      7047352.00      2890021.92      7047334.63
      2889761.50      7047421.44      2889101.78      7047417.97
#Sta/Elev= 30
  3472.9  440.05  3719.6  428.52  3910.2  415.26  4471.8  410.85  4562.9  413.62
  4969.1  412.68  4978.7  412.00  4987.7  406.52  4988.3  403.64  4990.8  402.84
  5007.3  403.64  5018.0  411.66  5038.1  407.62  5055.3  411.92  5105.5  411.63
  5153.3  411.10  5179.7  407.17  5184.9  411.38  5193.3  407.70  5211.3  407.60
  5283.8  414.89  5297.4  415.26  5316.0  416.58  5648.7  429.50  5672.7  429.51
  5702.7  423.91  5742.7  431.43  5842.7  430.24  5932.7  435.47  6035.9  436.09
#Mann=7,-1,0
  3472.9    0.05       0  4969.1    0.12       0  4988.3    0.07       0
  5007.3    0.12       0  5105.5    0.05       0  5283.8    0.12       0
  5316.0    0.16       0
Bank Sta=3910.2,5297.4
Exp/Cntr=0.3,0.1

Type RM Length L Ch R = 1,18591,1367,1367,1367
BEGIN DESCRIPTION:
Mapping XS c3a3c9a4
END DESCRIPTION:
XS GIS Cut Line= 6
      2891576.56      7047359.81      2890786.68      7047320.75
      2890387.37      7047281.68      2890049.70      7047202.69
      2889711.16      7047301.65      2888893.42      7047291.23
#Sta/Elev= 30
  3571.1  436.72  3627.3  432.25  3665.1  430.86  3768.8  420.87  3878.1  416.10
  3926.0  415.01  4233.5  411.39  4470.7  412.28  4504.3  409.54  4524.4  412.55
  4975.9  412.78  4982.2  409.06  4982.9  403.46  4985.4  402.66  5001.9  403.46
  5026.2  412.75  5119.6  414.67  5139.8  414.74  5243.7  415.83  5349.7  418.57
  5388.4  414.13  5422.4  415.01  5428.2  416.43  5551.1  419.28  5650.1  419.78
  5789.0  423.39  5839.0  427.32  6046.2  432.01  6244.3  438.32  6280.6  439.04
#Mann=14,-1,0
  3571.1    0.16       0  3627.3    0.12       0  3665.1    0.16       0
  3878.1    0.12       0  4982.9    0.07       0  5001.9    0.12       0
  5119.6    0.05       0  5139.8    0.08       0  5243.7    0.16       0
  5428.2    0.05       0  5551.1    0.08       0  5650.1    0.05       0
  6046.2    0.08       0  6244.3    0.05       0
Bank Sta=3926,5422.4
Exp/Cntr=0.3,0.1

Type RM Length L Ch R = 1,17224,2973,2973,2973
BEGIN DESCRIPTION:
COFFEE CREEK 12.0
END DESCRIPTION:
XS GIS Cut Line= 3
      2892724.97      7046075.01      2890275.00      7046625.00
      2888784.35      7047005.11
#Sta/Elev= 30
  2450.2  463.06  2567.8  463.95  2686.7  460.79  2778.1  452.83  2841.5  440.09
  2947.6  429.19  3075.4  418.84  3270.4  413.74  3741.5  409.11  4295.8  409.59
  4385.8  410.42  4758.5  411.59  4786.9  408.57  4801.8  411.08  4979.0  411.70
  4992.9  402.33  4995.4  401.53  5011.9  402.33  5012.7  406.36  5019.9  412.19
  5322.3  411.09  5363.6  406.49  5387.8  410.69  5557.3  413.15  5567.5  413.74
  5766.1  430.71  5889.9  432.84  5995.7  428.18  6261.8  440.35  6499.5  443.16
#Mann=10,-1,0
  2450.2    0.16       0  2567.8    0.12       0  2686.7    0.16       0
  2947.6    0.12       0  4295.8    0.07       0  4385.8    0.12       0
  4992.9    0.07       0  5011.9    0.12       0  5557.3    0.16       0
  6261.8    0.05       0
Bank Sta=3270.4,5567.5
Exp/Cntr=0.3,0.1

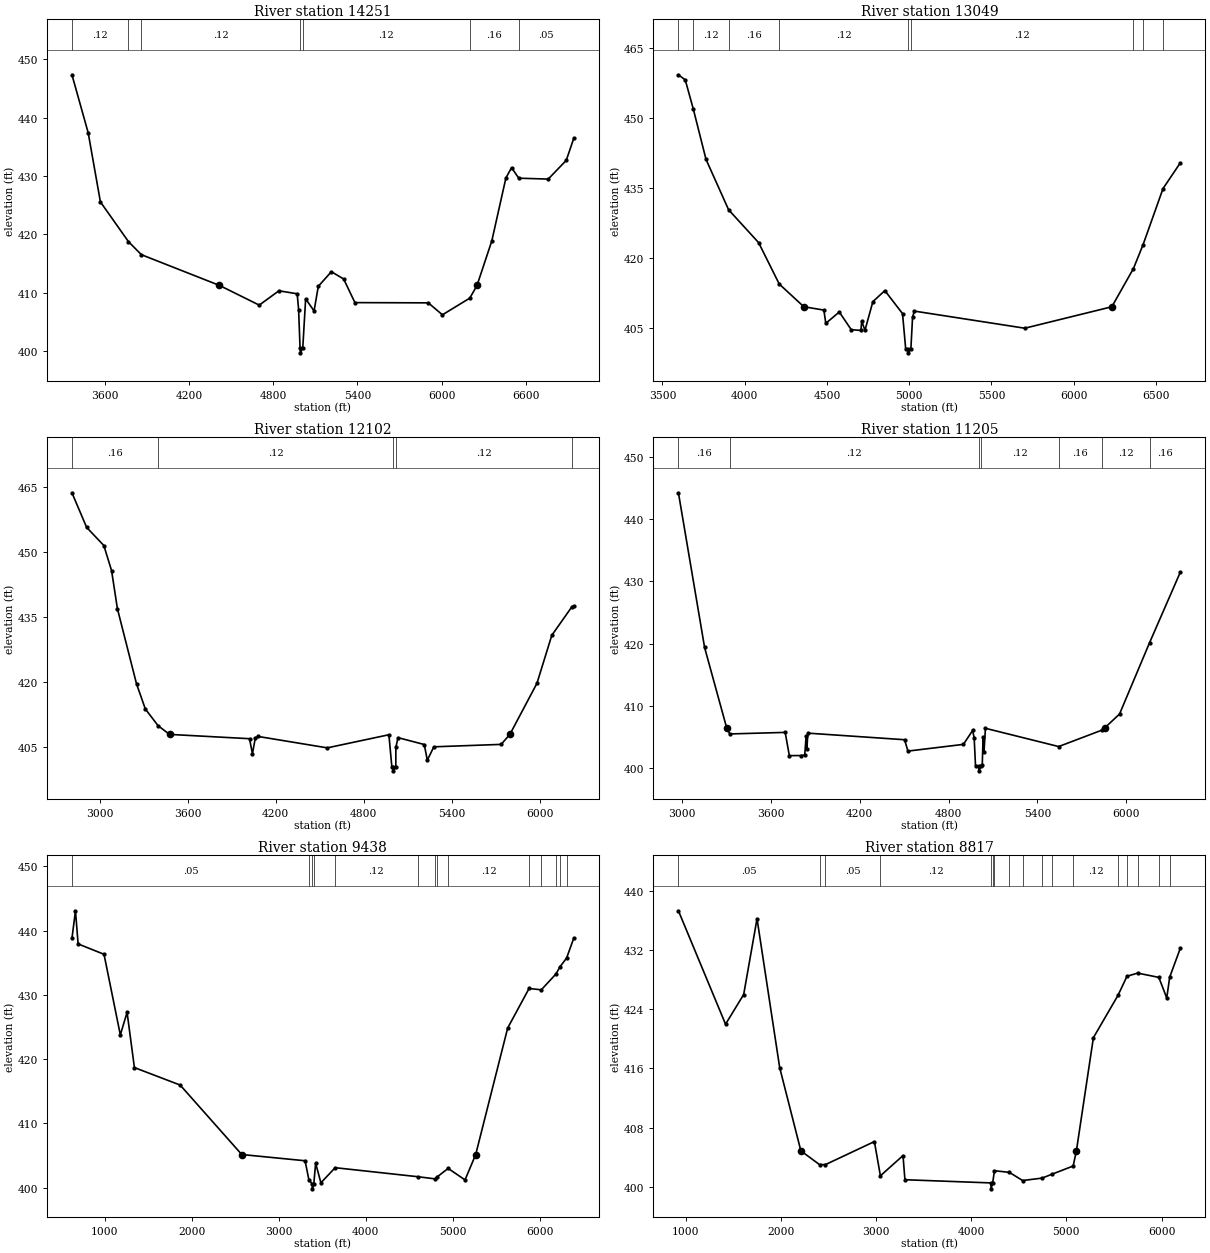
Type RM Length L Ch R = 1,14251,1202,1202,1202
BEGIN DESCRIPTION:
COFFEE CREEK 11.0
END DESCRIPTION:
XS GIS Cut Line= 3
      2892137.40      7045774.74      2890310.98      7045698.35
      2888573.35      7045864.87
#Sta/Elev= 30
  3367.4  447.34  3482.9  437.41  3570.0  425.55  3769.6  418.74  3861.7  416.50
  4417.5  411.23  4701.0  407.85  4841.1  410.31  4971.2  409.79  4981.2  407.09
  4991.6  400.47  4994.1  399.67  5010.8  400.47  5031.3  408.93  5091.3  406.85
  5121.3  411.07  5214.6  413.58  5301.9  412.33  5382.2  408.28  5904.6  408.24
  6005.1  406.19  6200.2  409.05  6251.5  411.23  6356.7  418.85  6457.1  429.64
  6497.3  431.42  6548.8  429.61  6758.5  429.46  6887.0  432.67  6941.0  436.49
#Mann=7,-1,0
  3367.4    0.12       0  3769.6    0.16       0  3861.7    0.12       0
  4991.6    0.07       0  5010.8    0.12       0  6200.2    0.16       0
  6548.8    0.05       0
Bank Sta=4417.5,6251.5
Exp/Cntr=0.3,0.1

Type RM Length L Ch R = 1,13049,947,947,947
BEGIN DESCRIPTION:
COFFEE CREEK 10.0
END DESCRIPTION:
XS GIS Cut Line= 3
      2891725.02      7045275.00      2890459.82      7044913.52
      2888774.97      7045325.01
#Sta/Elev= 30
  3597.4  459.30  3639.0  458.20  3687.7  451.98  3765.1  441.16  3902.4  430.35
  4084.9  423.30  4210.0  414.43  4359.7  409.55  4481.4  408.84  4493.1  405.99
  4575.0  408.43  4647.8  404.63  4706.3  404.48  4711.5  406.46  4731.0  404.49
  4779.1  410.64  4851.9  413.02  4959.4  408.08  4978.7  400.48  4990.9  400.47
  4993.4  399.67  5010.1  400.47  5020.4  407.37  5031.4  408.62  5702.4  404.95
  6231.3  409.55  6362.8  417.75  6421.0  422.84  6542.6  434.91  6647.6  440.41
#Mann=9,-1,0
  3597.4    0.16       0  3687.7    0.12       0  3902.4    0.16       0
  4210.0    0.12       0  4990.9    0.07       0  5010.1    0.12       0
  6362.8    0.16       0  6421.0    0.12       0  6542.6    0.05       0
Bank Sta=4359.7,6231.3
Exp/Cntr=0.3,0.1

Type RM Length L Ch R = 1,12102,897,897,897
BEGIN DESCRIPTION:
COFFEE CREEK 9.0
END DESCRIPTION:
XS GIS Cut Line= 3
      2891974.96      7044225.00      2889775.00      7044275.00
      2888774.99      7044975.01
#Sta/Elev= 30
  2812.0  463.57  2912.0  455.61  3029.5  451.42  3082.0  445.66  3122.0  436.86
  3252.1  419.58  3312.1  413.80  3399.2  409.94  3477.3  407.94  4022.3  406.95
  4042.3  403.50  4062.3  407.19  4082.3  407.46  4552.4  404.84  4972.5  407.86
  4992.5  400.49  5000.4  400.35  5002.9  399.55  5019.6  400.35  5019.9  404.98
  5034.8  407.19  5213.5  405.61  5234.4  402.01  5278.9  405.08  5737.5  405.64
  5797.1  407.94  5981.6  419.70  6082.8  430.75  6220.2  437.34  6233.2  437.51
#Mann=5,-1,0
  2812.0    0.16       0  3399.2    0.12       0  5000.4    0.07       0
  5019.6    0.12       0  6220.2    0.16       0
Bank Sta=3477.3,5797.1
Exp/Cntr=0.3,0.1

Type RM Length L Ch R = 1,11205,1767,1767,1767
BEGIN DESCRIPTION:
COFFEE CREEK 8.0
END DESCRIPTION:
XS GIS Cut Line= 3
      2891374.99      7043025.00      2889425.00      7043575.00
      2888255.45      7044267.78
#Sta/Elev= 30
  2978.1  444.27  3154.7  419.36  3303.2  406.45  3324.3  405.44  3698.3  405.69
  3726.2  401.95  3805.5  401.96  3830.1  402.05  3839.5  405.05  3844.7  402.95
  3850.9  405.57  4503.5  404.51  4526.2  402.68  4900.3  403.76  4962.6  406.00
  4973.0  404.81  4982.0  400.34  5002.4  400.30  5004.9  399.50  5021.6  400.30
  5027.4  400.41  5033.4  404.99  5039.2  402.49  5049.0  406.35  5543.0  403.41
  5836.3  406.07  5855.2  406.45  5953.6  408.65  6155.7  420.11  6363.5  431.49
#Mann=7,-1,0
  2978.1    0.16       0  3324.3    0.12       0  5002.4    0.07       0
  5021.6    0.12       0  5543.0    0.16       0  5836.3    0.12       0
  6155.7    0.16       0
Bank Sta=3303.2,5855.2
Exp/Cntr=0.3,0.1

Type RM Length L Ch R = 1,9438,621,621,621
BEGIN DESCRIPTION:
COFFEE CREEK 7.0
END DESCRIPTION:
XS GIS Cut Line= 3
      2892525.00      7042225.00      2888225.00      7042875.00
      2887325.01      7043974.99
#Sta/Elev= 30
   623.1  438.77   663.6  443.07   693.9  437.91   991.7  436.30  1179.3  423.76
  1256.9  427.26  1341.2  418.67  1867.1  415.95  2575.2  405.14  3303.2  404.17
  3348.3  401.12  3384.6  400.60  3387.1  399.80  3403.9  400.60  3424.6  403.79
  3485.2  400.74  3649.0  403.09  4597.8  401.69  4798.6  401.35  4814.5  401.58
  4948.1  402.98  5142.1  401.19  5264.8  405.14  5632.3  424.82  5878.2  430.98
  6019.0  430.77  6185.8  433.21  6235.7  434.39  6309.8  435.71  6393.2  438.84
#Mann=14,-1,0
   623.1    0.05       0  3348.3    0.07       0  3384.6    0.07       0
  3403.9    0.07       0  3649.0    0.12       0  4597.8    0.07       0
  4798.6    0.12       0  4814.5    0.07       0  4948.1    0.12       0
  5878.2    0.16       0  6019.0    0.12       0  6185.8    0.05       0
  6235.7    0.16       0  6309.8    0.05       0
Bank Sta=2575.2,5264.8
Exp/Cntr=0.3,0.1

Type RM Length L Ch R = 1,8817,1010,1010,1010
BEGIN DESCRIPTION:
COFFEE CREEK 6.0
END DESCRIPTION:
XS GIS Cut Line= 3
      2891699.01      7041967.45      2887928.07      7042224.56
      2887180.76      7043516.96
#Sta/Elev= 30
   925.0  437.28  1420.2  421.97  1610.6  425.98  1750.9  436.21  1989.0  416.10
  2211.3  404.88  2407.4  403.02  2469.6  403.02  2983.8  406.13  3046.9  401.51
  3284.5  404.24  3304.5  400.98  4207.0  400.55  4209.5  399.75  4226.3  400.55
  4245.0  402.20  4402.5  401.97  4540.9  400.87  4745.3  401.20  4848.8  401.72
  5071.8  402.83  5105.9  404.88  5284.4  420.15  5543.9  425.89  5637.1  428.44
  5748.8  428.87  5971.8  428.29  6055.1  425.51  6085.8  428.32  6197.6  432.22
#Mann=17,-1,0
   925.0    0.05       0  2407.4    0.07       0  2469.6    0.05       0
  3046.9    0.12       0  4207.0    0.07       0  4226.3    0.12       0
  4245.0    0.07       0  4402.5    0.12       0  4540.9    0.07       0
  4745.3    0.12       0  4848.8    0.07       0  5071.8    0.12       0
  5543.9    0.16       0  5637.1    0.12       0  5748.8    0.16       0
  5971.8    0.12       0  6085.8    0.16       0
Bank Sta=2211.3,5105.9
Exp/Cntr=0.3,0.1

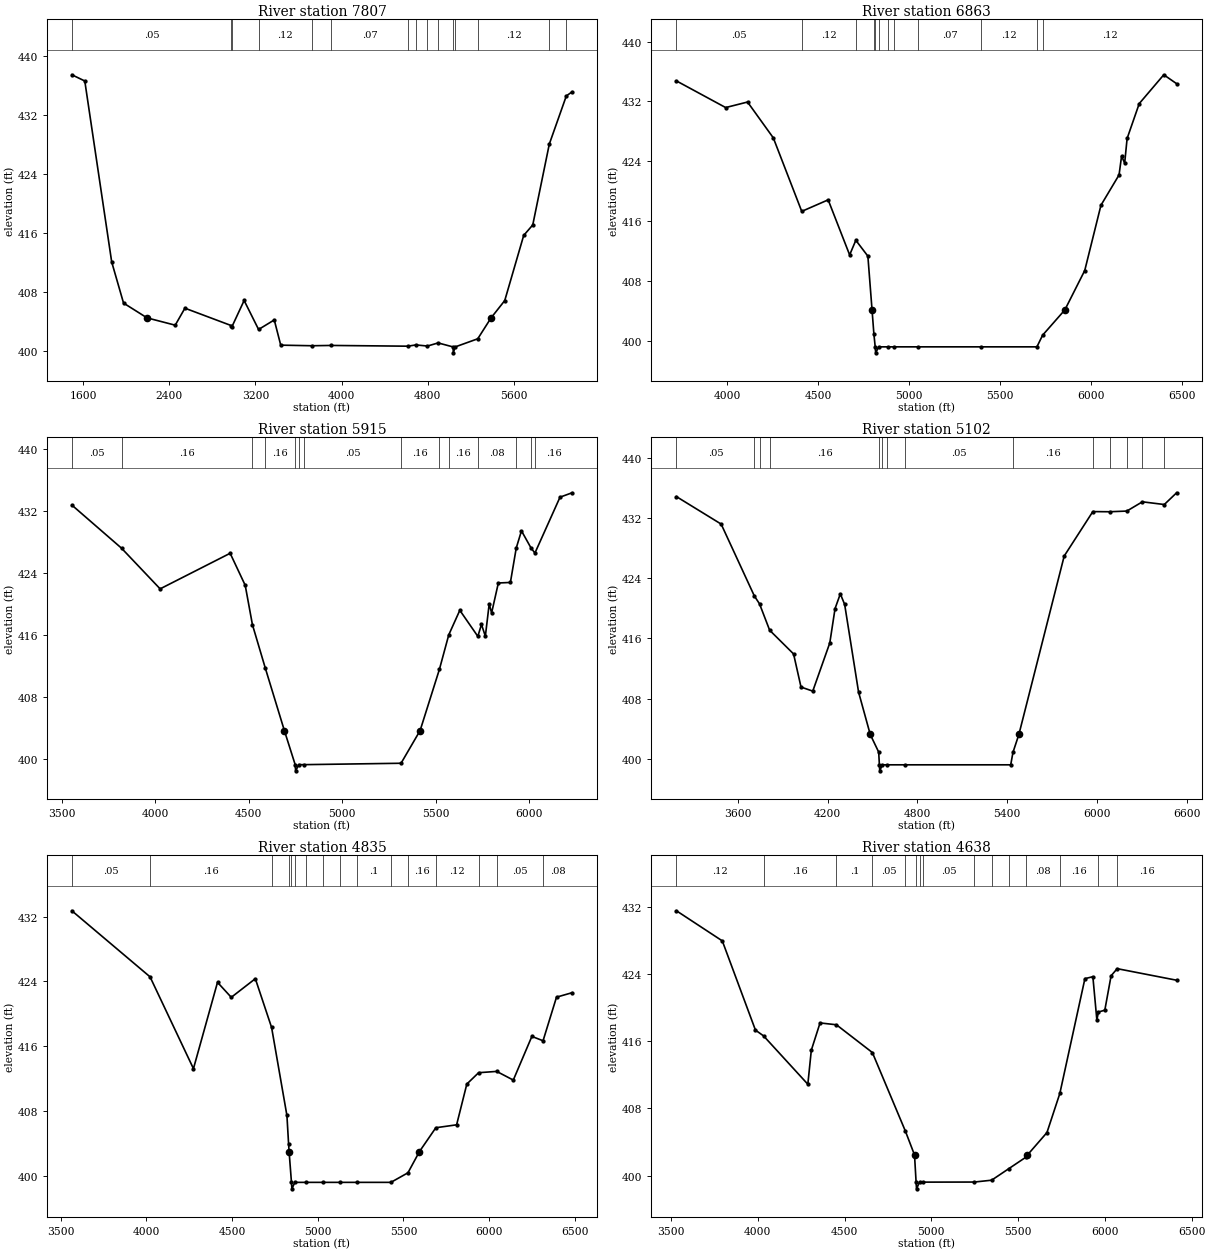
Type RM Length L Ch R = 1,7807,944,944,944
BEGIN DESCRIPTION:
COFFEE CREEK 5.0
END DESCRIPTION:
XS GIS Cut Line= 3
      2890774.98      7041775.00      2887574.00      7041800.78
      2886130.40      7041857.64
#Sta/Elev= 30
  1495.0  437.40  1615.0  436.56  1865.0  412.08  1975.0  406.52  2193.3  404.52
  2455.0  403.53  2545.0  405.83  2975.0  403.48  2982.0  403.33  3095.0  406.87
  3229.3  402.95  3375.0  404.24  3435.0  400.83  3723.5  400.75  3906.0  400.79
  4614.7  400.69  4691.8  400.86  4797.8  400.71  4897.0  401.13  5035.7  400.59
  5038.2  399.79  5055.0  400.59  5264.9  401.69  5388.7  404.52  5515.7  406.86
  5691.7  415.67  5775.9  417.09  5929.7  428.03  6087.7  434.54  6140.8  435.09
#Mann=15,-1,0
  1495.0    0.05       0  2975.0    0.12       0  2982.0    0.05       0
  3229.3    0.12       0  3723.5    0.16       0  3906.0    0.07       0
  4614.7    0.12       0  4691.8    0.07       0  4797.8    0.12       0
  4897.0    0.07       0  5035.7    0.07       0  5055.0    0.07       0
  5264.9    0.12       0  5929.7    0.16       0  6087.7    0.12       0
Bank Sta=2193.3,5388.7
Exp/Cntr=0.3,0.1

Type RM Length L Ch R = 1,6863,948,948,948
BEGIN DESCRIPTION:
COFFEE CREEK 4.0
END DESCRIPTION:
XS GIS Cut Line= 3
      2888575.03      7041025.00      2887470.06      7040951.71
      2885989.71      7041662.16
#Sta/Elev= 30
  3720.8  434.74  3991.4  431.18  4111.7  431.92  4253.3  427.13  4409.6  417.31
  4554.8  418.85  4672.9  411.49  4706.9  413.45  4773.1  411.33  4796.0  404.15
  4806.1  400.95  4813.4  399.21  4815.9  398.41  4833.0  399.21  4885.4  399.21
  4917.4  399.21  5047.5  399.21  5396.3  399.21  5702.3  399.21  5733.7  400.77
  5855.9  404.15  5965.2  409.41  6054.3  418.13  6153.8  422.18  6167.6  424.68
  6184.7  423.77  6198.1  427.05  6264.7  431.71  6399.6  435.56  6470.2  434.37
#Mann=12,-1,0
  3720.8    0.05       0  4409.6    0.12       0  4706.9    0.16       0
  4806.1    0.05       0  4813.4    0.07       0  4833.0    0.05       0
  4885.4    0.07       0  4917.4    0.12       0  5047.5    0.07       0
  5396.3    0.12       0  5702.3    0.07       0  5733.7    0.12       0
Bank Sta=4796,5855.9
Exp/Cntr=0.3,0.1

Type RM Length L Ch R = 1,5915,813,813,813
BEGIN DESCRIPTION:
COFFEE CREEK 3.0
END DESCRIPTION:
XS GIS Cut Line= 3
      2888375.26      7040822.46      2887025.00      7040325.00
      2885825.01      7040625.00
#Sta/Elev= 30
  3553.8  432.76  3819.4  427.19  4026.0  421.93  4400.6  426.53  4481.2  422.39
  4519.8  417.30  4588.4  411.71  4690.6  403.62  4748.5  399.21  4751.0  398.41
  4768.1  399.21  4797.7  399.21  5314.9  399.39  5416.9  403.62  5520.3  411.54
  5570.2  415.99  5629.3  419.16  5725.7  415.79  5745.2  417.33  5765.9  415.81
  5786.5  419.98  5799.4  418.82  5835.4  422.69  5899.9  422.76  5931.1  427.20
  5959.1  429.43  6010.4  427.21  6031.1  426.56  6165.3  433.78  6229.7  434.35
#Mann=14,-1,0
  3553.8    0.05       0  3819.4    0.16       0  4519.8    0.12       0
  4588.4    0.16       0  4748.5   0.033       0  4768.1    0.16       0
  4797.7    0.05       0  5314.9    0.16       0  5520.3    0.12       0
  5570.2    0.16       0  5725.7    0.08       0  5931.1    0.16       0
  6010.4    0.05       0  6031.1    0.16       0
Bank Sta=4690.6,5416.9
Exp/Cntr=0.3,0.1

Type RM Length L Ch R = 1,5102,267,267,267
BEGIN DESCRIPTION:
COFFEE CREEK 2.0
END DESCRIPTION:
XS GIS Cut Line= 3
      2888624.98      7040624.99      2887225.00      7039525.00
      2885824.98      7040225.01
#Sta/Elev= 30
  3187.9  434.84  3487.0  431.19  3709.1  421.64  3743.8  420.59  3811.4  417.09
  3971.4  413.94  4021.2  409.54  4099.8  409.00  4213.7  415.40  4248.9  419.97
  4284.2  421.92  4313.1  420.52  4406.2  408.87  4484.3  403.24  4540.8  400.90
  4545.4  399.21  4547.9  398.41  4565.1  399.21  4593.2  399.21  4716.9  399.21
  5423.9  399.21  5439.0  400.87  5478.5  403.24  5781.7  426.95  5973.1  432.85
  6085.2  432.83  6200.5  432.92  6304.6  434.15  6451.2  433.79  6533.6  435.35
#Mann=14,-1,0
  3187.9    0.05       0  3709.1    0.16       0  3743.8    0.12       0
  3811.4    0.16       0  4545.4   0.033       0  4565.1    0.16       0
  4593.2    0.12       0  4716.9    0.05       0  5439.0    0.16       0
  5973.1    0.08       0  6085.2    0.16       0  6200.5    0.05       0
  6304.6    0.16       0  6451.2    0.05       0
Bank Sta=4484.3,5478.5
Exp/Cntr=0.3,0.1

Type RM Length L Ch R = 1,4835,197,197,197
BEGIN DESCRIPTION:
Mapping XS b03713f5
END DESCRIPTION:
XS GIS Cut Line= 4
      2888692.21      7039398.15      2887365.79      7039293.98
      2886581.06      7039196.76      2885839.01      7038905.48
#Sta/Elev= 30
  3565.5  432.72  4021.6  424.57  4274.9  413.24  4415.3  423.89  4495.6  422.04
  4636.0  424.34  4730.9  418.32  4820.3  407.46  4830.1  403.92  4833.0  403.00
  4846.8  399.21  4849.3  398.41  4866.5  399.21  4929.3  399.21  5028.9  399.21
  5128.4  399.21  5227.9  399.21  5427.0  399.21  5526.5  400.39  5593.3  403.00
  5689.1  405.95  5810.4  406.31  5870.0  411.34  5938.7  412.74  6044.2  412.90
  6141.1  411.83  6249.5  417.22  6314.7  416.68  6393.2  422.06  6483.9  422.61
#Mann=16,-1,0
  3565.5    0.05       0  4021.6    0.16       0  4730.9    0.08       0
  4830.1    0.15       0  4846.8   0.033       0  4866.5    0.15       0
  4929.3    0.05       0  5028.9     0.1       0  5128.4    0.15       0
  5227.9     0.1       0  5427.0    0.05       0  5526.5    0.16       0
  5689.1    0.12       0  5938.7    0.08       0  6044.2    0.05       0
  6314.7    0.08       0
Bank Sta=4833,5593.3
Exp/Cntr=0.3,0.1

Type RM Length L Ch R = 1,4638,398,398,398
BEGIN DESCRIPTION:
Mapping XS cebcd2cf
END DESCRIPTION:
XS GIS Cut Line= 4
      2888747.72      7039245.37      2887351.90      7039092.59
      2886574.12      7039009.26      2885942.17      7038717.59
#Sta/Elev= 30
  3531.0  431.56  3795.3  427.97  3986.4  417.33  4032.8  416.65  4288.2  410.88
  4308.3  414.94  4358.6  418.19  4452.9  417.97  4660.1  414.66  4850.4  405.29
  4903.0  402.45  4912.1  399.21  4914.6  398.41  4931.8  399.21  4949.8  399.21
  5247.9  399.22  5347.3  399.44  5446.7  400.82  5546.0  402.20  5553.9  402.45
  5666.2  405.12  5740.4  409.78  5884.9  423.47  5930.8  423.70  5953.7  418.56
  5963.0  419.49  5999.6  419.71  6035.8  423.81  6070.9  424.66  6413.4  423.28
#Mann=15,-1,0
  3531.0    0.12       0  4032.8    0.16       0  4452.9     0.1       0
  4660.1    0.05       0  4850.4    0.07       0  4912.1   0.033       0
  4931.8    0.07       0  4949.8    0.05       0  5247.9     0.1       0
  5347.3    0.15       0  5446.7    0.16       0  5546.0    0.08       0
  5740.4    0.16       0  5963.0    0.08       0  6070.9    0.16       0
Bank Sta=4903,5553.9
Exp/Cntr=0.3,0.1

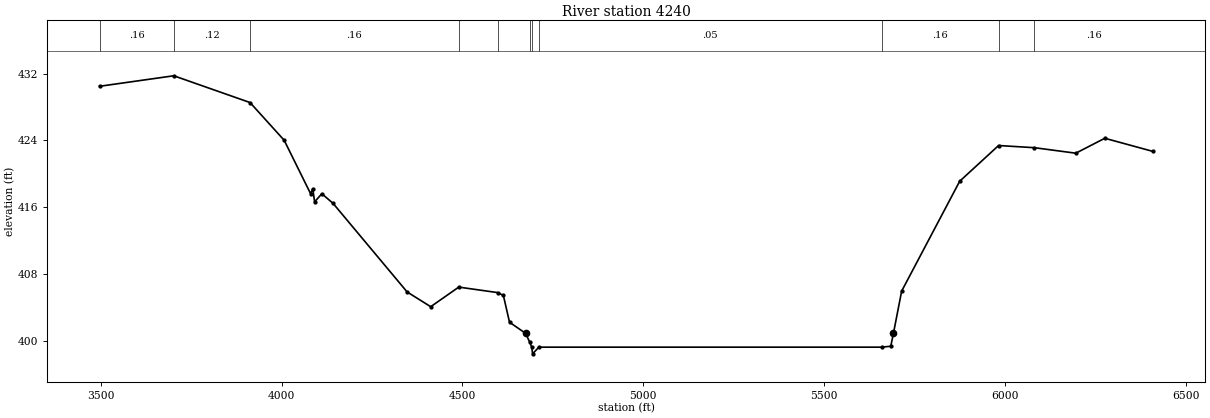
Type RM Length L Ch R = 1,4240,0,0,0
BEGIN DESCRIPTION:
COFFEE CREEK 1.0
END DESCRIPTION:
XS GIS Cut Line= 3
      2888797.39      7039027.49      2887675.04      7038716.79
      2885932.80      7038584.78
#Sta/Elev= 30
  3496.8  430.48  3702.1  431.74  3913.0  428.53  4007.3  424.01  4080.3  417.61
  4086.3  418.19  4091.5  416.63  4111.5  417.60  4142.6  416.44  4347.2  405.83
  4412.4  404.06  4490.0  406.41  4597.6  405.75  4613.3  405.41  4630.3  402.20
  4674.6  400.87  4686.6  399.77  4691.7  399.21  4694.2  398.41  4711.4  399.21
  5658.7  399.21  5684.3  399.32  5691.7  400.87  5714.4  405.93  5874.9  419.10
  5982.4  423.38  6081.5  423.12  6195.8  422.46  6276.0  424.25  6408.6  422.68
#Mann=11,-1,0
  3496.8    0.16       0  3702.1    0.12       0  3913.0    0.16       0
  4490.0    0.05       0  4597.6    0.07       0  4686.6    0.05       0
  4691.7   0.033       0  4711.4    0.05       0  5658.7    0.16       0
  5982.4    0.08       0  6081.5    0.16       0
Bank Sta=4674.6,5691.7
Exp/Cntr=0.3,0.1

Chan Stop Cuts=-1