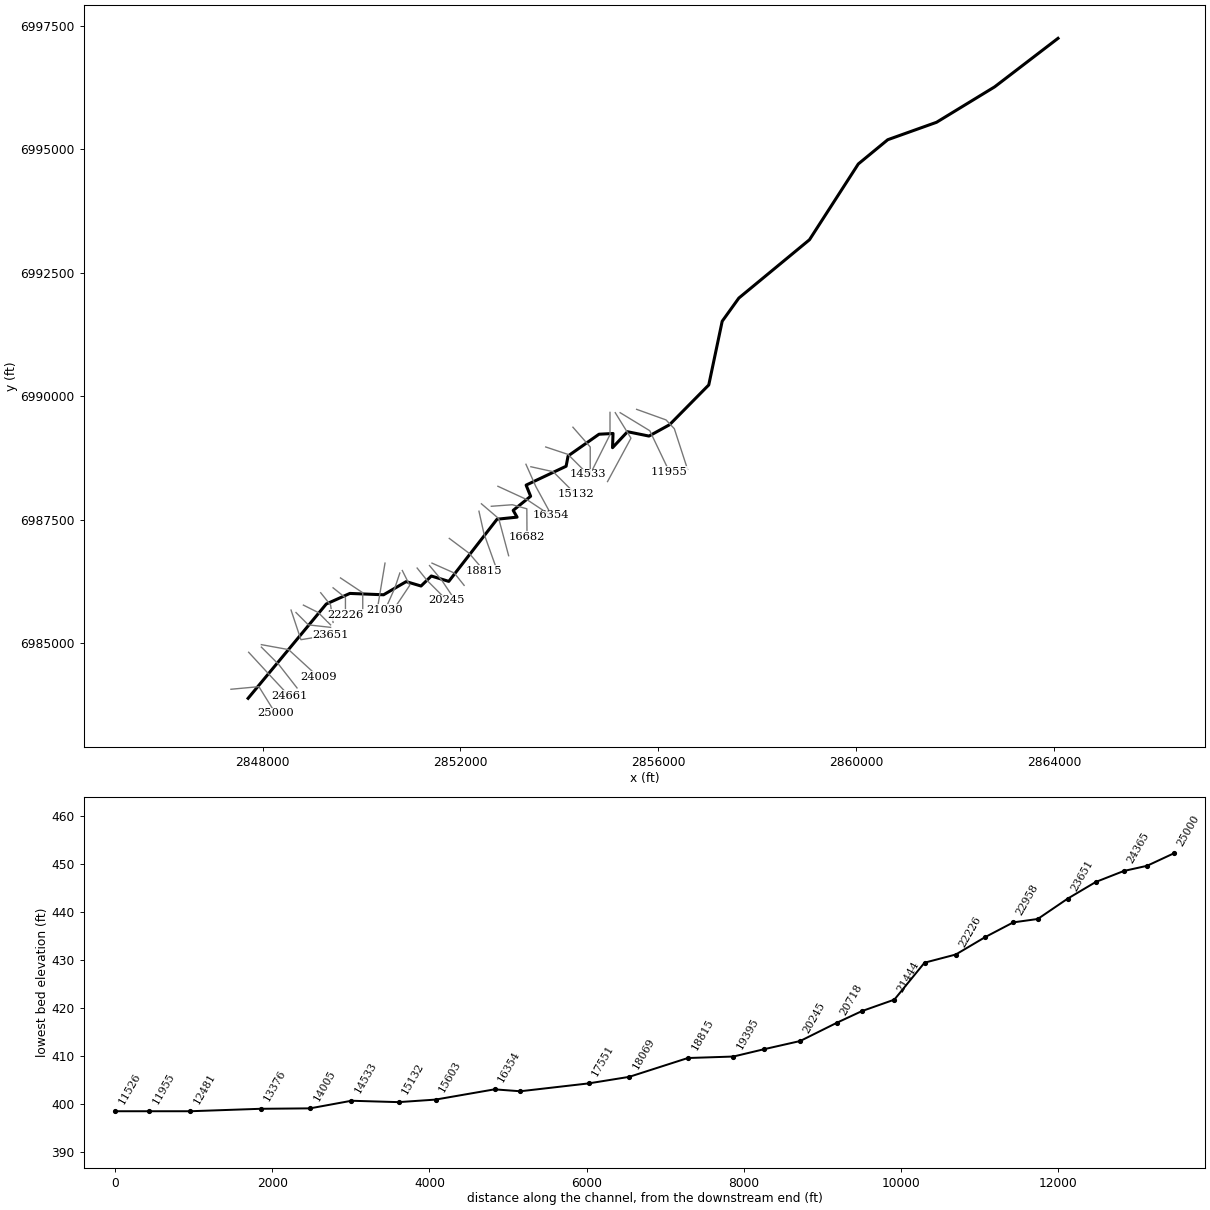
--- DALE CREEK.prj (project) ---

Proj Title=DALE CREEK Base Level Engineering
Current Plan=p01
Default Exp/Contr=0.3,0.1
English Units
Geom File=g01
Flow File=f01
Plan File=p01
BEGIN DESCRIPTION:
DALE CREEK
END DESCRIPTION:

--- DALE CREEK.p01 (plan) ---

Plan Title=Multiple Run
Short Identifier=Multiple
Geom File=g01
Flow File=f01
Subcritical Flow
K Sum by GR= 0
Std Step Tol= 0.01
Critical Tol= 0.01
Num of Std Step Trials= 20
Max Error Tol= 0.3
Flow Tol Ratio= 0.001
Split Flow NTrial= 30
Split Flow Tol= 0.02
Split Flow Ratio= 0.02
Log Output Level= 0
Friction Slope Method= 1
Unsteady Friction Slope Method= 2
Unsteady Bridges Friction Slope Method= 1
Parabolic Critical Depth
Global Vel Dist=  1 , 1 , 1
Global Log Level= 0
CheckData=True
Encroach Param= -1, 0, 0, 0
BEGIN DESCRIPTION:
Multiple Run
END DESCRIPTION:

--- DALE CREEK.f01 (steady flow) ---

Flow Title=Multiple
Number of Profiles=7
Profile Names=10-year,25-year,50-year,1pct_min,100-year,1pct_plu,500-year
River Rch & RM= DALE CREEK,Reach-1,25000
     129     156     175      99     197     393     248
River Rch & RM= DALE CREEK,Reach-1,23270
     234     296     344     199     398     794     531
River Rch & RM= DALE CREEK,Reach-1,20718
     454     600     718     427     853    1702    1205
River Rch & RM= DALE CREEK,Reach-1,20245
     678     917    1112     671    1338    2669    1939
River Rch & RM= DALE CREEK,Reach-1,15603
     967    1328    1628     990    1975    3940    2913
River Rch & RM= DALE CREEK,Reach-1,11955
    1132    1562    1920    1170    2334    4657    3459
Boundary for River Rch & Prof#=DALE CREEK,Reach-1,1
Up Type=0
Dn Type=3
Dn Slope=0.005
Boundary for River Rch & Prof#=DALE CREEK,Reach-1,2
Up Type=0
Dn Type=3
Dn Slope=0.005
Boundary for River Rch & Prof#=DALE CREEK,Reach-1,3
Up Type=0
Dn Type=3
Dn Slope=0.005
Boundary for River Rch & Prof#=DALE CREEK,Reach-1,4
Up Type=0
Dn Type=3
Dn Slope=0.005
Boundary for River Rch & Prof#=DALE CREEK,Reach-1,5
Up Type=0
Dn Type=3
Dn Slope=0.005
Boundary for River Rch & Prof#=DALE CREEK,Reach-1,6
Up Type=0
Dn Type=3
Dn Slope=0.005
Boundary for River Rch & Prof#=DALE CREEK,Reach-1,7
Up Type=0
Dn Type=3
Dn Slope=0.005

--- DALE CREEK.g01 (geometry) ---

Geom Title=Existing Conditions

River Reach=DALE CREEK,Reach-1
Reach XY= 30
      2847706.54      6983889.14      2849287.29      6985797.41
      2849764.71      6986011.51      2850445.85      6985984.19
      2850903.50      6986250.55      2851203.72      6986161.39
      2851411.69      6986364.00      2851764.49      6986255.32
      2852740.59      6987513.19      2853145.83      6987555.40
      2853066.78      6987692.02      2853419.83      6987977.53
      2853328.50      6988203.18      2854137.45      6988585.40
      2854177.36      6988793.40      2854802.88      6989233.18
      2855086.09      6989247.76      2855076.12      6988960.71
      2855378.51      6989283.83      2855813.19      6989195.72
      2856228.98      6989424.91      2857022.02      6990230.12
      2857293.62      6991519.36      2857630.06      6991988.18
      2859058.58      6993168.50      2860045.86      6994701.81
      2860641.53      6995192.69      2861628.81      6995545.68
      2862803.62      6996262.70      2864084.43      6997244.17

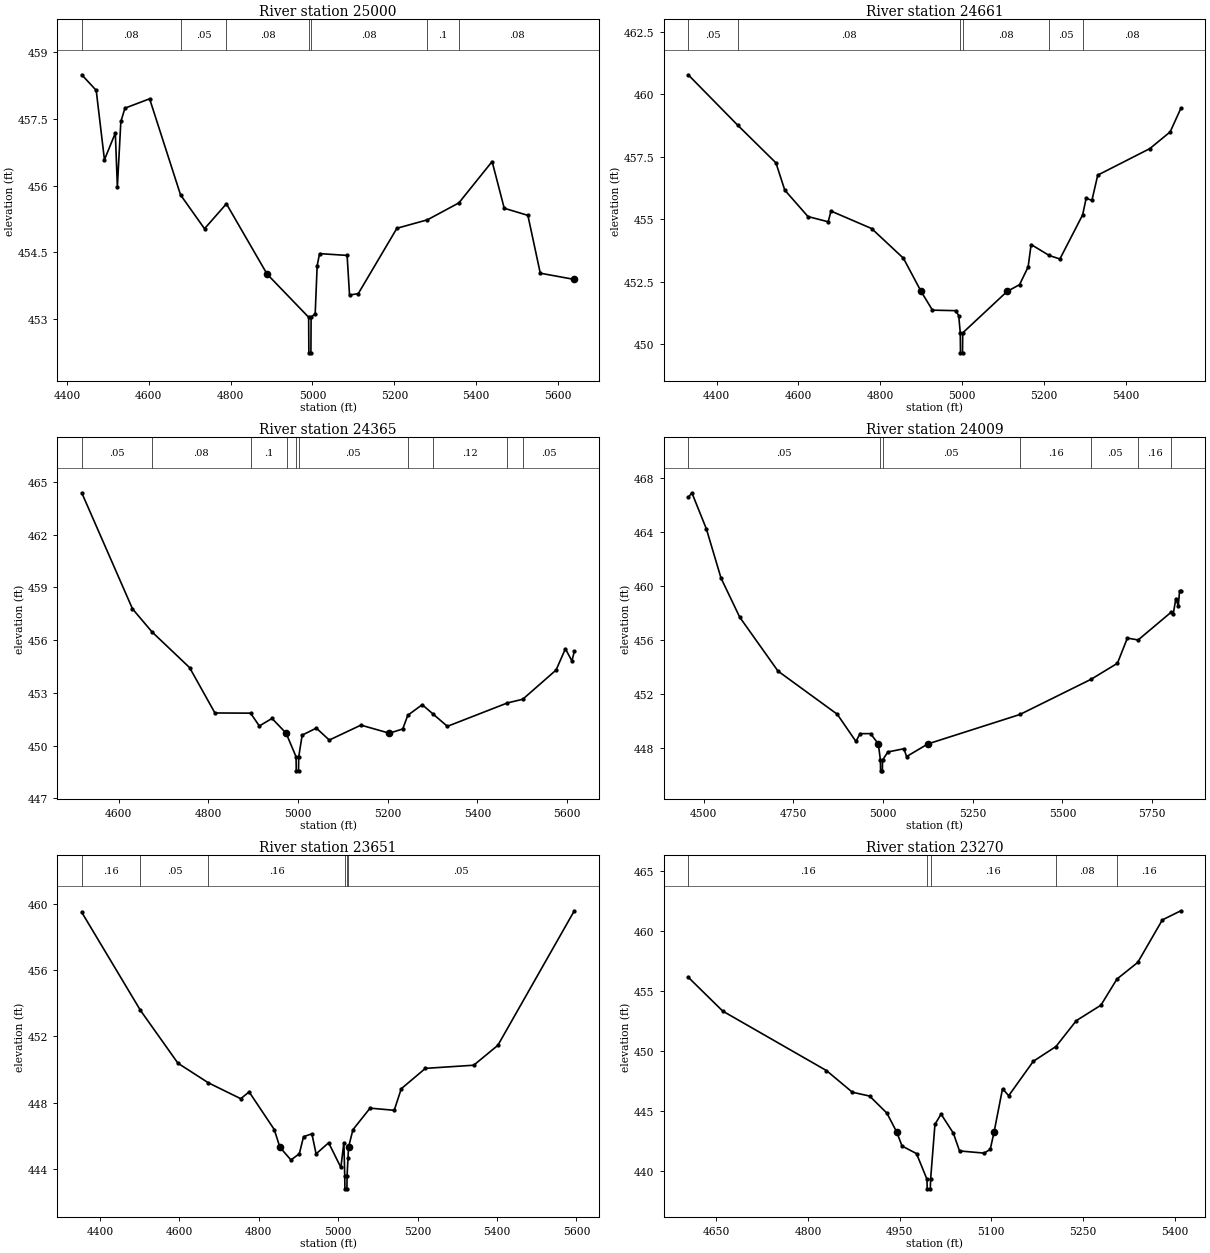
Type RM Length L Ch R = 1,25000,339,339,339
BEGIN DESCRIPTION:
DALE CREEK 47.0
END DESCRIPTION:
XS GIS Cut Line= 3
      2847359.77      6984072.23      2847925.00      6984125.00
      2848260.21      6983584.25
#Sta/Elev= 30
  4436.0  458.49  4471.4  458.14  4491.5  456.58  4518.1  457.18  4523.1  455.97
  4531.6  457.44  4541.7  457.74  4601.9  457.95  4677.5  455.79  4736.1  455.03
  4789.6  455.59  4889.0  454.01  4990.6  453.04  4991.1  452.24  4996.1  452.24
  4996.6  453.04  5006.6  453.12  5011.4  454.20  5017.3  454.47  5084.6  454.43
  5090.5  453.54  5111.8  453.57  5206.3  455.04  5280.9  455.23  5357.7  455.61
  5439.0  456.54  5468.6  455.49  5526.4  455.33  5556.7  454.03  5639.9  453.89
#Mann=7,-1,0
  4436.0    0.08       0  4677.5    0.05       0  4789.6    0.08       0
  4990.6    0.07       0  4996.6    0.08       0  5280.9     0.1       0
  5357.7    0.08       0
Bank Sta=4889,5639.9
Exp/Cntr=0.3,0.1

Type RM Length L Ch R = 1,24661,296,296,296
BEGIN DESCRIPTION:
DALE CREEK 46.0
END DESCRIPTION:
XS GIS Cut Line= 3
      2847717.87      6984820.92      2848175.00      6984325.00
      2848535.61      6983938.73
#Sta/Elev= 30
  4330.8  460.79  4451.7  458.77  4545.1  457.26  4566.6  456.17  4623.3  455.11
  4672.7  454.90  4679.5  455.33  4778.7  454.63  4856.4  453.44  4899.5  452.11
  4927.3  451.36  4984.0  451.34  4991.4  451.14  4995.2  450.45  4995.7  449.65
  5000.7  449.65  5001.2  450.45  5109.6  452.11  5139.9  452.38  5160.9  453.09
  5168.2  453.99  5212.4  453.55  5238.5  453.41  5294.1  455.18  5302.5  455.84
  5316.7  455.76  5330.9  456.77  5457.9  457.83  5507.7  458.50  5533.7  459.44
#Mann=6,-1,0
  4330.8    0.05       0  4451.7    0.08       0  4995.2    0.07       0
  5001.2    0.08       0  5212.4    0.05       0  5294.1    0.08       0
Bank Sta=4899.5,5109.6
Exp/Cntr=0.3,0.1

Type RM Length L Ch R = 1,24365,356,356,356
BEGIN DESCRIPTION:
DALE CREEK 45.0
END DESCRIPTION:
XS GIS Cut Line= 3
      2847974.97      6984925.03      2848325.00      6984575.00
      2848695.94      6984099.11
#Sta/Elev= 30
  4517.9  464.38  4631.1  457.78  4674.6  456.47  4758.4  454.44  4814.9  451.86
  4894.4  451.85  4913.9  451.12  4942.2  451.55  4973.7  450.71  4974.8  450.64
  4995.8  449.37  4996.3  448.57  5001.3  448.57  5001.8  449.37  5009.4  450.60
  5041.0  451.00  5069.9  450.32  5140.5  451.17  5203.7  450.71  5233.7  450.95
  5245.0  451.73  5277.1  452.33  5300.9  451.81  5333.2  451.10  5467.0  452.43
  5501.3  452.64  5575.6  454.30  5596.4  455.51  5610.9  454.82  5616.3  455.36
#Mann=10,-1,0
  4517.9    0.05       0  4674.6    0.08       0  4894.4     0.1       0
  4974.8    0.05       0  4995.8    0.04       0  5001.8    0.05       0
  5245.0    0.16       0  5300.9    0.12       0  5467.0    0.16       0
  5501.3    0.05       0
Bank Sta=4973.7,5203.7
Exp/Cntr=0.3,0.1

Type RM Length L Ch R = 1,24009,358,358,358
BEGIN DESCRIPTION:
DALE CREEK 44.0
END DESCRIPTION:
XS GIS Cut Line= 3
      2847975.01      6984975.00      2848525.00      6984875.00
      2849124.97      6984325.03
#Sta/Elev= 30
  4457.0  466.56  4467.2  466.91  4507.8  464.22  4548.5  460.58  4600.6  457.68
  4707.3  453.68  4872.4  450.48  4924.5  448.46  4936.0  449.04  4965.2  449.04
  4986.9  448.28  4992.7  447.08  4993.2  446.28  4998.2  446.28  4998.7  447.08
  5013.5  447.68  5058.2  447.92  5065.6  447.34  5125.3  448.28  5381.5  450.46
  5580.4  453.08  5653.3  454.26  5681.0  456.13  5711.0  455.99  5803.5  458.06
  5808.7  457.88  5816.1  459.06  5822.9  458.50  5826.6  459.64  5829.9  459.64
#Mann=7,-1,0
  4457.0    0.05       0  4992.7    0.03       0  4998.7    0.05       0
  5381.5    0.16       0  5580.4    0.05       0  5711.0    0.16       0
  5803.5    0.05       0
Bank Sta=4986.9,5125.3
Exp/Cntr=0.3,0.1

Type RM Length L Ch R = 1,23651,381,381,381
BEGIN DESCRIPTION:
DALE CREEK 43.0
END DESCRIPTION:
XS GIS Cut Line= 3
      2848575.00      6985674.99      2848775.00      6985075.00
      2849374.98      6985175.00
#Sta/Elev= 30
  4354.0  459.49  4501.9  453.57  4596.4  450.38  4672.8  449.20  4754.5  448.24
  4775.6  448.65  4838.9  446.38  4853.1  445.31  4881.0  444.54  4902.1  444.92
  4912.7  445.95  4933.7  446.12  4944.3  444.91  4975.9  445.58  5006.7  444.09
  5014.3  445.59  5016.4  443.60  5016.9  442.80  5021.9  442.80  5022.4  443.60
  5024.6  444.65  5026.0  445.31  5037.1  446.37  5080.2  447.67  5141.1  447.54
  5158.8  448.84  5219.6  450.07  5341.3  450.26  5402.1  451.46  5594.7  459.58
#Mann=6,-1,0
  4354.0    0.16       0  4501.9    0.05       0  4672.8    0.16       0
  5016.4    0.07       0  5022.4    0.16       0  5024.6    0.05       0
Bank Sta=4853.1,5026
Exp/Cntr=0.3,0.1

Type RM Length L Ch R = 1,23270,312,312,312
BEGIN DESCRIPTION:
DALE CREEK 42.0
END DESCRIPTION:
XS GIS Cut Line= 3
      2848674.99      6985625.01      2848925.00      6985375.00
      2849374.97      6985325.00
#Sta/Elev= 30
  4603.8  456.14  4660.4  453.32  4830.1  448.38  4872.5  446.58  4900.8  446.26
  4929.1  444.84  4945.3  443.25  4953.8  442.11  4977.5  441.48  4994.6  439.35
  4995.1  438.55  5000.1  438.55  5000.6  439.35  5007.7  443.91  5017.7  444.76
  5037.9  443.17  5047.9  441.70  5088.2  441.52  5098.2  441.83  5104.4  443.25
  5118.3  446.87  5128.4  446.29  5168.7  449.15  5205.8  450.38  5239.1  452.53
  5279.3  453.81  5305.7  455.99  5339.7  457.37  5379.9  460.90  5410.1  461.66
#Mann=5,-1,0
  4603.8    0.16       0  4994.6    0.07       0  5000.6    0.16       0
  5205.8    0.08       0  5305.7    0.16       0
Bank Sta=4945.3,5104.4
Exp/Cntr=0.3,0.1

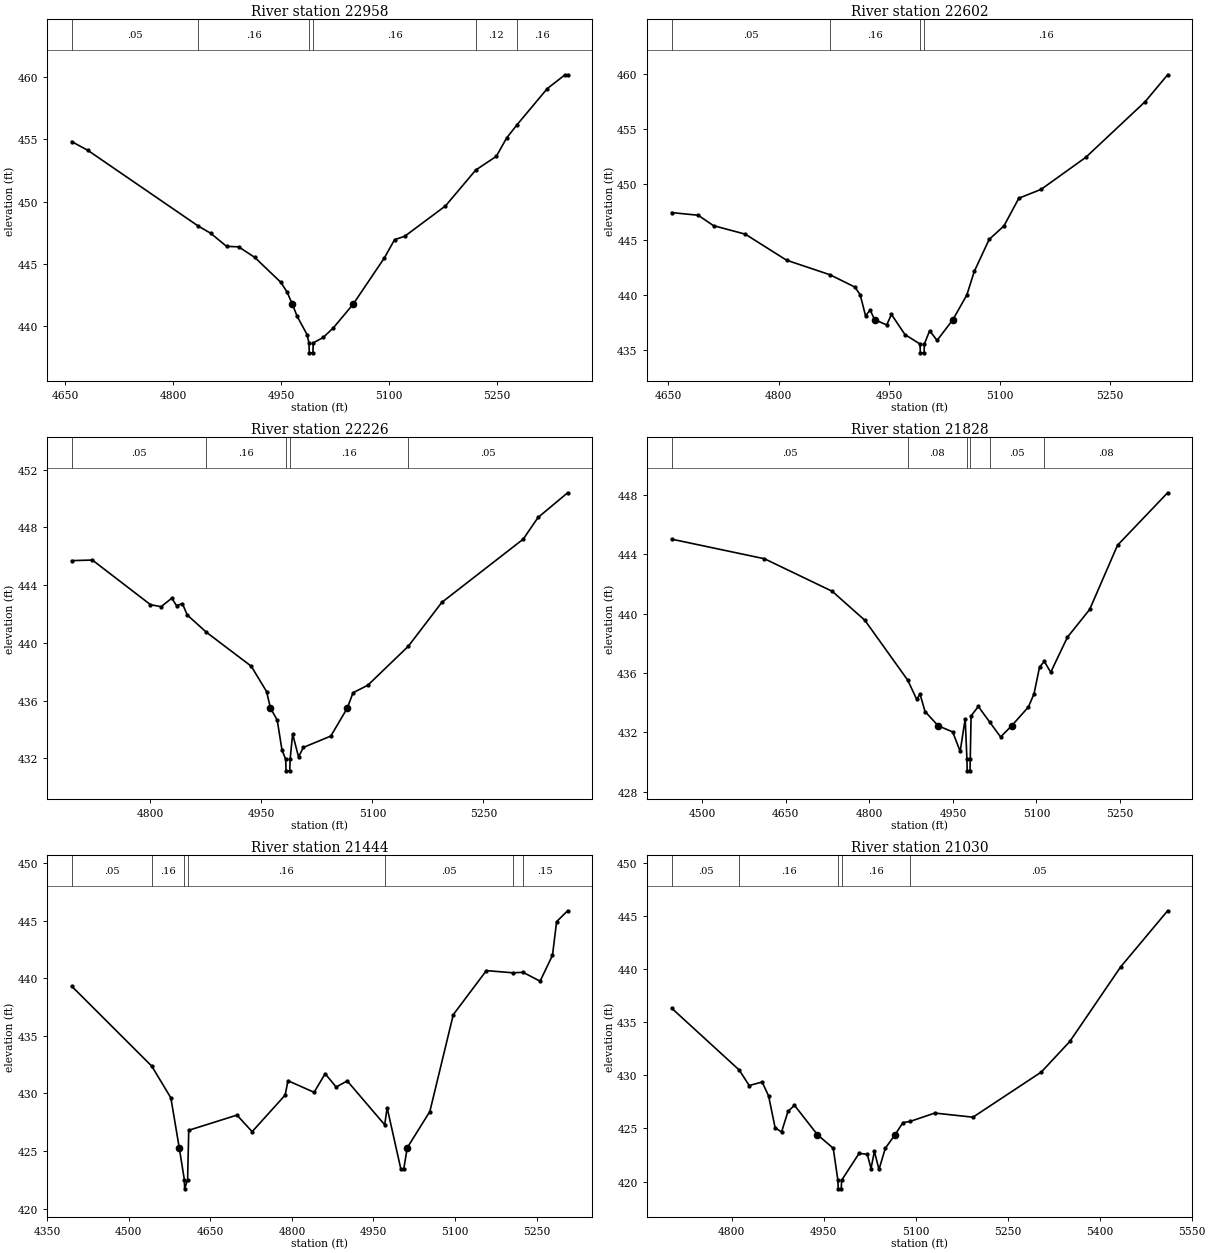
Type RM Length L Ch R = 1,22958,356,356,356
BEGIN DESCRIPTION:
DALE CREEK 41.0
END DESCRIPTION:
XS GIS Cut Line= 3
      2848824.99      6985775.01      2849125.00      6985625.00
      2849375.01      6985374.99
#Sta/Elev= 30
  4659.2  454.82  4681.6  454.12  4835.3  448.02  4852.1  447.46  4874.4  446.40
  4891.2  446.36  4913.6  445.51  4949.9  443.50  4958.3  442.74  4965.9  441.74
  4972.3  440.79  4986.2  439.31  4988.8  438.64  4989.3  437.84  4994.3  437.84
  4994.8  438.64  5008.8  439.08  5022.9  439.86  5050.1  441.74  5093.6  445.47
  5107.8  446.94  5121.9  447.21  5178.5  449.65  5220.5  452.53  5249.2  453.64
  5263.3  455.10  5277.7  456.16  5319.9  459.08  5344.6  460.19  5348.2  460.19
#Mann=6,-1,0
  4659.2    0.05       0  4835.3    0.16       0  4988.8    0.07       0
  4994.8    0.16       0  5220.5    0.12       0  5277.7    0.16       0
Bank Sta=4965.9,5050.1
Exp/Cntr=0.3,0.1

Type RM Length L Ch R = 1,22602,376,376,376
BEGIN DESCRIPTION:
DALE CREEK 40.0
END DESCRIPTION:
XS GIS Cut Line= 3
      2849174.97      6986025.03      2849375.00      6985775.00
      2849425.01      6985424.95
#Sta/Elev= 30
  4654.4  447.45  4690.5  447.21  4711.3  446.27  4754.5  445.50  4810.5  443.15
  4869.7  441.83  4903.4  440.72  4910.6  440.02  4917.8  438.13  4924.2  438.64
  4930.1  437.78  4946.6  437.30  4953.0  438.25  4971.4  436.43  4991.8  435.58
  4992.3  434.78  4997.3  434.78  4997.8  435.58  5004.9  436.78  5015.0  435.90
  5036.5  437.78  5055.4  440.00  5065.5  442.13  5085.7  445.02  5105.9  446.25
  5126.1  448.75  5156.4  449.55  5217.0  452.44  5297.8  457.48  5328.2  459.90
#Mann=4,-1,0
  4654.4    0.05       0  4869.7    0.16       0  4991.8    0.07       0
  4997.8    0.16       0
Bank Sta=4930.1,5036.5
Exp/Cntr=0.3,0.1

Type RM Length L Ch R = 1,22226,398,398,398
BEGIN DESCRIPTION:
DALE CREEK 39.0
END DESCRIPTION:
XS GIS Cut Line= 3
      2849424.97      6986125.02      2849675.00      6985925.00
      2849675.00      6985574.99
#Sta/Elev= 30
  4693.6  445.69  4721.6  445.73  4800.1  442.64  4814.5  442.50  4828.9  443.09
  4835.3  442.57  4843.3  442.71  4849.7  441.93  4875.4  440.74  4936.2  438.38
  4957.0  436.62  4962.2  435.48  4971.4  434.64  4977.8  432.57  4982.8  431.93
  4983.3  431.13  4988.3  431.13  4988.8  431.93  4992.2  433.68  5000.2  432.09
  5006.6  432.75  5043.8  433.54  5066.1  435.48  5073.8  436.54  5093.8  437.06
  5148.5  439.76  5193.8  442.80  5303.8  447.18  5323.8  448.68  5363.8  450.39
#Mann=5,-1,0
  4693.6    0.05       0  4875.4    0.16       0  4982.8    0.07       0
  4988.8    0.16       0  5148.5    0.05       0
Bank Sta=4962.2,5066.1
Exp/Cntr=0.3,0.1

Type RM Length L Ch R = 1,21828,384,384,384
BEGIN DESCRIPTION:
DALE CREEK 38.0
END DESCRIPTION:
XS GIS Cut Line= 3
      2849574.97      6986325.02      2850025.00      6986025.00
      2850025.00      6985674.97
#Sta/Elev= 30
  4444.8  445.01  4611.6  443.69  4733.3  441.50  4791.9  439.55  4868.9  435.52
  4885.0  434.23  4891.0  434.58  4900.0  433.41  4923.7  432.45  4949.6  432.04
  4963.1  430.73  4972.1  432.93  4975.2  430.22  4975.7  429.42  4980.7  429.42
  4981.2  430.22  4982.7  433.12  4995.7  433.75  5016.5  432.68  5035.7  431.70
  5055.6  432.45  5085.7  433.72  5095.7  434.60  5105.7  436.41  5114.3  436.78
  5125.7  436.05  5155.7  438.41  5195.7  440.28  5245.7  444.60  5335.7  448.13
#Mann=6,-1,0
  4444.8    0.05       0  4868.9    0.08       0  4975.2    0.07       0
  4981.2    0.08       0  5016.5    0.05       0  5114.3    0.08       0
Bank Sta=4923.7,5055.6
Exp/Cntr=0.3,0.1

Type RM Length L Ch R = 1,21444,414,414,414
BEGIN DESCRIPTION:
DALE CREEK 37.0
END DESCRIPTION:
XS GIS Cut Line= 3
      2850475.00      6986624.97      2850375.00      6986025.00
      2850325.00      6985724.99
#Sta/Elev= 30
  4394.8  439.33  4542.1  432.38  4577.3  429.62  4592.7  425.28  4602.1  422.51
  4602.6  421.71  4608.1  422.51  4610.2  426.80  4698.9  428.12  4726.8  426.68
  4787.6  429.86  4792.7  431.11  4840.8  430.10  4861.1  431.72  4881.4  430.56
  4901.7  431.09  4970.6  427.28  4975.2  428.75  5000.5  423.40  5005.6  423.40
  5012.1  425.28  5053.7  428.43  5096.8  436.85  5157.7  440.68  5206.0  440.49
  5225.2  440.53  5256.5  439.76  5279.3  442.01  5286.9  444.94  5307.2  445.88
#Mann=7,-1,0
  4394.8    0.05       0  4542.1    0.16       0  4602.1    0.03       0
  4608.1    0.16       0  4970.6    0.05       0  5206.0     0.1       0
  5225.2    0.15       0
Bank Sta=4592.7,5012.1
Exp/Cntr=0.3,0.1

Type RM Length L Ch R = 1,21030,312,312,312
BEGIN DESCRIPTION:
DALE CREEK 36.0
END DESCRIPTION:
XS GIS Cut Line= 3
      2850775.00      6986425.01      2850675.00      6986125.00
      2850474.99      6985674.98
#Sta/Elev= 30
  4702.1  436.31  4812.3  430.49  4828.6  429.03  4849.7  429.36  4860.2  428.05
  4870.8  425.07  4881.3  424.65  4891.8  426.59  4902.4  427.17  4939.9  424.40
  4965.6  423.13  4973.2  420.11  4973.7  419.31  4978.7  419.31  4979.2  420.11
  5007.8  422.65  5021.1  422.56  5027.2  421.22  5032.7  422.84  5040.2  421.13
  5050.5  423.13  5066.4  424.40  5079.2  425.54  5090.8  425.65  5131.2  426.44
  5193.4  426.05  5304.9  430.30  5351.4  433.18  5434.2  440.19  5510.8  445.47
#Mann=5,-1,0
  4702.1    0.05       0  4812.3    0.16       0  4973.2    0.07       0
  4979.2    0.16       0  5090.8    0.05       0
Bank Sta=4939.9,5066.4
Exp/Cntr=0.3,0.1

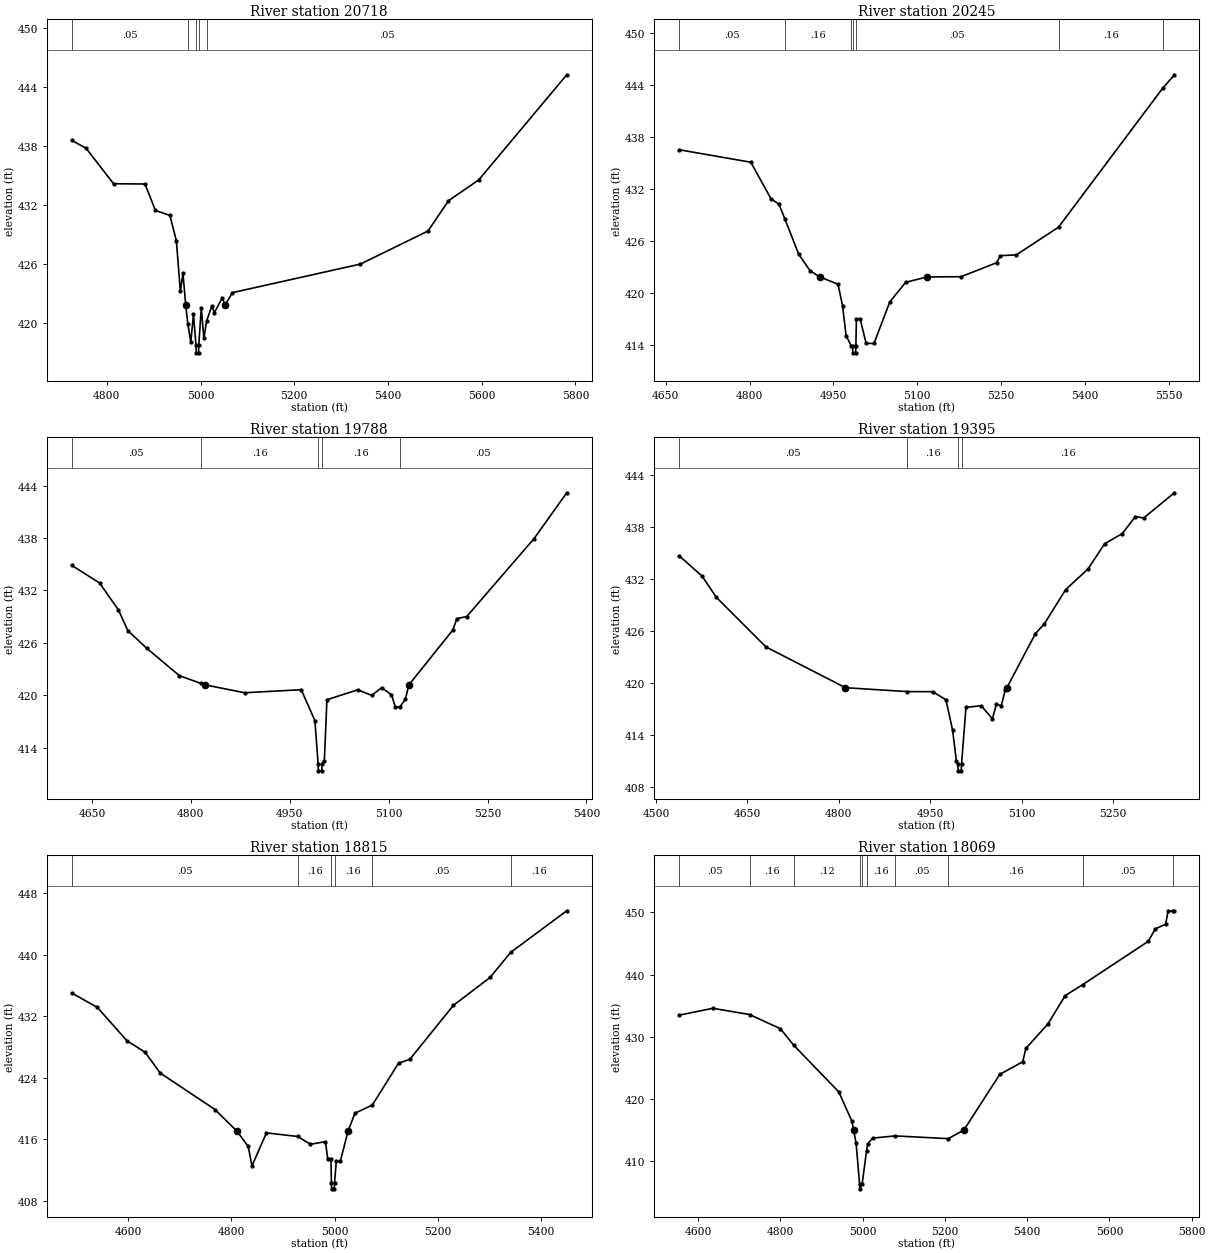
Type RM Length L Ch R = 1,20718,473,473,473
BEGIN DESCRIPTION:
DALE CREEK 35.0
END DESCRIPTION:
XS GIS Cut Line= 3
      2850824.99      6986475.03      2850975.00      6986175.00
      2850574.97      6985574.96
#Sta/Elev= 30
  4724.8  438.54  4755.6  437.74  4814.3  434.13  4881.4  434.10  4903.7  431.41
  4934.5  430.91  4948.4  428.32  4956.8  423.18  4962.4  425.00  4968.3  421.80
  4972.8  419.87  4979.2  418.01  4984.8  420.85  4990.2  417.73  4990.7  416.93
  4995.7  416.93  4996.2  417.73  5001.5  421.47  5007.1  418.41  5012.7  420.14
  5023.9  421.68  5029.5  421.03  5046.3  422.51  5052.6  421.80  5067.8  423.05
  5341.2  425.96  5485.4  429.32  5529.0  432.40  5593.6  434.52  5781.4  445.21
#Mann=5,-1,0
  4724.8    0.05       0  4972.8    0.16       0  4990.2    0.07       0
  4996.2    0.16       0  5012.7    0.05       0
Bank Sta=4968.3,5052.6
Exp/Cntr=0.3,0.1

Type RM Length L Ch R = 1,20245,457,457,457
BEGIN DESCRIPTION:
DALE CREEK 34.0
END DESCRIPTION:
XS GIS Cut Line= 3
      2851125.00      6986525.00      2851325.00      6986275.00
      2851724.97      6985875.03
#Sta/Elev= 30
  4674.2  436.52  4802.3  435.08  4838.3  430.87  4852.7  430.22  4862.9  428.58
  4887.9  424.46  4908.7  422.52  4925.6  421.84  4958.3  420.99  4966.3  418.53
  4972.7  415.07  4981.9  413.88  4984.2  413.87  4984.7  413.07  4989.7  413.07
  4990.2  413.87  4991.2  416.98  4997.9  416.98  5008.5  414.17  5022.6  414.15
  5050.9  418.95  5079.2  421.21  5117.5  421.84  5178.2  421.86  5241.8  423.47
  5248.9  424.29  5277.2  424.38  5352.7  427.58  5539.0  443.62  5560.0  445.18
#Mann=7,-1,0
  4674.2    0.05       0  4862.9    0.16       0  4981.9    0.05       0
  4984.2    0.03       0  4990.2    0.05       0  5352.7    0.16       0
  5539.0    0.05       0
Bank Sta=4925.6,5117.5
Exp/Cntr=0.3,0.1

Type RM Length L Ch R = 1,19788,393,393,393
BEGIN DESCRIPTION:
DALE CREEK 33.0
END DESCRIPTION:
XS GIS Cut Line= 3
      2851374.97      6986575.03      2851625.00      6986275.00
      2851824.99      6985975.01
#Sta/Elev= 30
  4619.1  434.88  4661.5  432.85  4690.1  429.78  4704.4  427.41  4733.0  425.39
  4782.5  422.26  4815.2  421.37  4821.8  421.20  4881.4  420.30  4967.4  420.65
  4988.2  417.10  4993.0  412.17  4993.5  411.37  4998.5  411.37  4999.0  412.17
  5002.5  412.54  5006.4  419.50  5053.2  420.64  5074.3  420.00  5089.3  420.88
  5104.3  420.07  5110.3  418.64  5117.1  418.69  5125.3  419.55  5130.7  421.20
  5197.4  427.48  5203.5  428.77  5218.5  429.02  5320.6  437.93  5370.2  443.17
#Mann=5,-1,0
  4619.1    0.05       0  4815.2    0.16       0  4993.0    0.07       0
  4999.0    0.16       0  5117.1    0.05       0
Bank Sta=4821.8,5130.7
Exp/Cntr=0.3,0.1

Type RM Length L Ch R = 1,19395,580,580,580
BEGIN DESCRIPTION:
DALE CREEK 32.0
END DESCRIPTION:
XS GIS Cut Line= 3
      2851425.01      6986625.00      2851875.00      6986425.00
      2852075.00      6986174.99
#Sta/Elev= 30
  4538.2  434.66  4575.8  432.31  4599.1  429.87  4680.5  424.14  4811.0  419.43
  4912.8  418.98  4954.0  418.97  4975.9  418.04  4986.9  414.49  4993.0  410.96
  4995.5  410.63  4996.0  409.83  5001.0  409.83  5001.5  410.63  5008.8  417.16
  5033.8  417.35  5052.2  415.84  5058.7  417.52  5066.7  417.36  5073.1  419.14
  5075.9  419.43  5122.7  425.67  5137.1  426.77  5172.3  430.75  5209.1  433.14
  5236.3  436.06  5265.2  437.22  5286.8  439.19  5300.4  439.03  5350.8  441.94
#Mann=4,-1,0
  4538.2    0.05       0  4912.8    0.16       0  4995.5    0.07       0
  5001.5    0.16       0
Bank Sta=4811,5075.9
Exp/Cntr=0.3,0.1

Type RM Length L Ch R = 1,18815,746,746,746
BEGIN DESCRIPTION:
DALE CREEK 31.0
END DESCRIPTION:
XS GIS Cut Line= 3
      2851775.02      6987124.98      2852175.00      6986825.00
      2852474.97      6986475.04
#Sta/Elev= 30
  4489.8  435.00  4539.8  433.12  4597.1  428.79  4632.5  427.28  4661.6  424.59
  4767.9  419.84  4810.4  417.04  4832.5  415.04  4839.8  412.51  4867.9  416.80
  4928.6  416.33  4953.3  415.32  4982.5  415.66  4986.6  413.46  4993.1  413.46
  4993.9  410.32  4994.4  409.52  4999.5  409.52  5000.0  410.32  5003.5  413.10
  5011.2  413.09  5026.3  417.04  5039.7  419.36  5073.4  420.42  5124.2  425.86
  5146.2  426.37  5230.7  433.39  5302.0  437.02  5341.7  440.27  5450.7  445.69
#Mann=6,-1,0
  4489.8    0.05       0  4928.6    0.16       0  4993.9    0.07       0
  5000.0    0.16       0  5073.4    0.05       0  5341.7    0.16       0
Bank Sta=4810.4,5026.3
Exp/Cntr=0.3,0.1

Type RM Length L Ch R = 1,18069,518,518,518
BEGIN DESCRIPTION:
DALE CREEK 30.0
END DESCRIPTION:
XS GIS Cut Line= 3
      2852375.00      6987674.98      2852475.00      6987225.00
      2852725.01      6986524.97
#Sta/Elev= 30
  4553.7  433.48  4635.6  434.58  4724.7  433.58  4799.5  431.31  4832.4  428.63
  4941.7  421.16  4973.7  416.46  4977.8  415.03  4983.9  412.92  4992.3  406.39
  4992.8  405.59  4998.6  406.39  5009.4  411.73  5012.1  412.84  5024.7  413.74
  5078.5  414.09  5208.1  413.65  5246.0  415.03  5333.2  423.96  5389.0  425.99
  5396.9  428.15  5450.6  432.08  5492.5  436.63  5534.8  438.37  5694.3  445.33
  5711.8  447.35  5736.7  448.07  5742.6  450.16  5755.3  450.24  5758.0  450.24
#Mann=10,-1,0
  4553.7    0.05       0  4724.7    0.16       0  4832.4    0.12       0
  4992.3    0.07       0  4998.6    0.12       0  5009.4    0.16       0
  5078.5    0.05       0  5208.1    0.16       0  5534.8    0.05       0
  5755.3    0.16       0
Bank Sta=4977.8,5246
Exp/Cntr=0.3,0.1

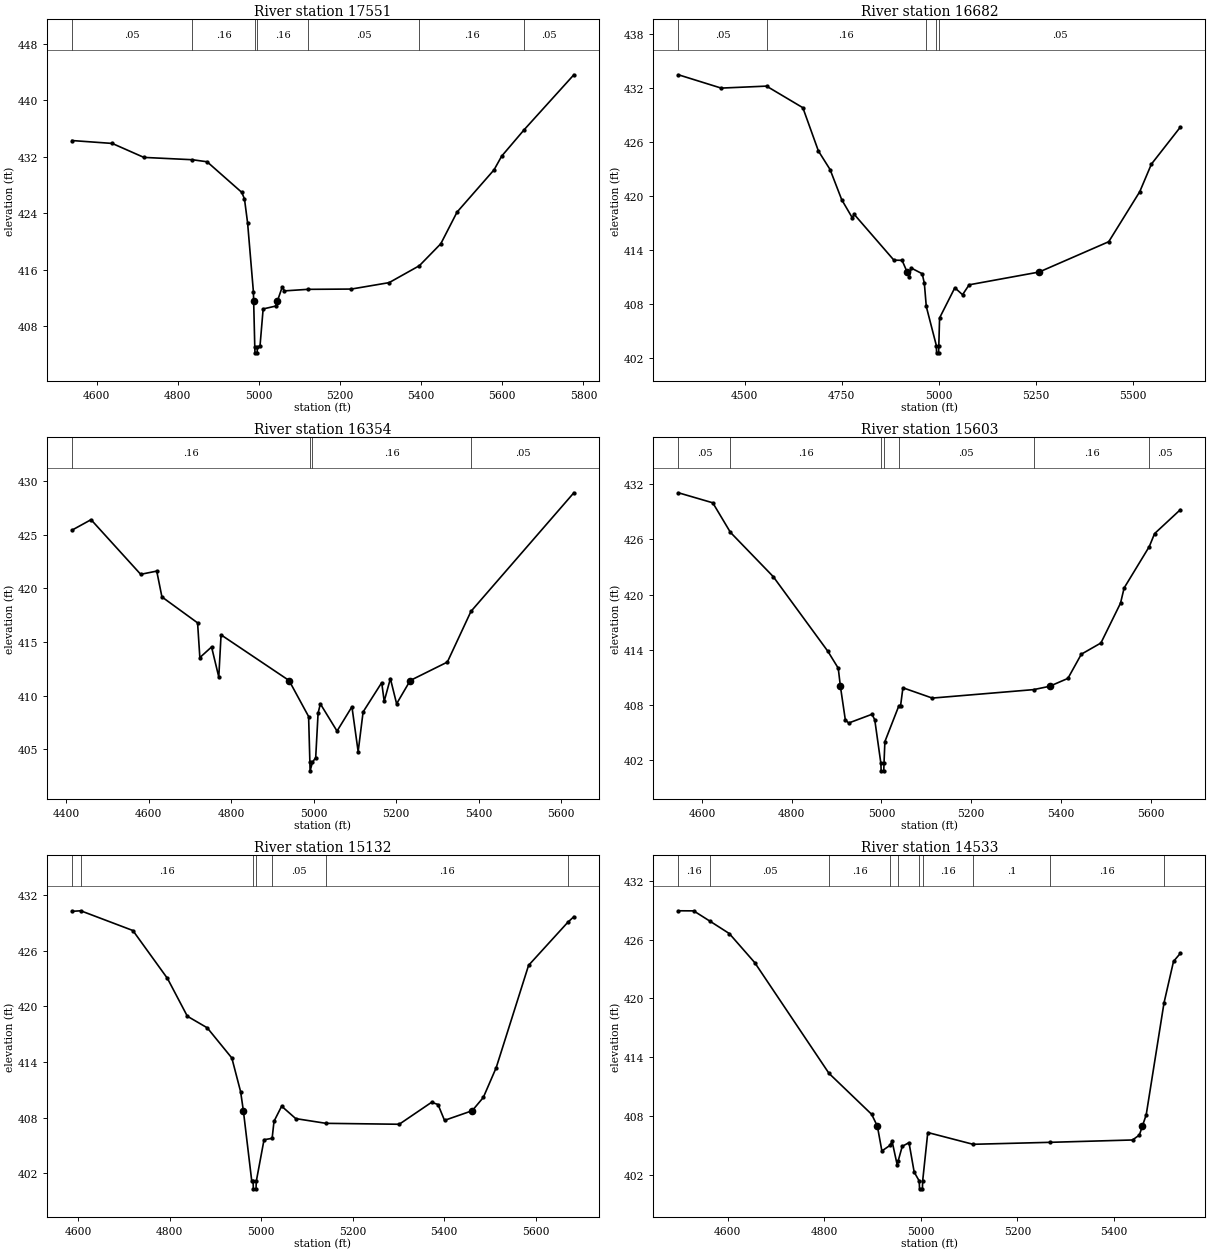
Type RM Length L Ch R = 1,17551,869,869,869
BEGIN DESCRIPTION:
DALE CREEK 29.0
END DESCRIPTION:
XS GIS Cut Line= 3
      2852425.00      6987825.00      2852775.00      6987525.00
      2852975.00      6986774.99
#Sta/Elev= 30
  4539.3  434.31  4638.6  433.90  4716.6  431.92  4836.0  431.59  4872.4  431.30
  4958.0  426.96  4964.6  426.02  4972.3  422.62  4986.6  412.86  4987.2  411.59
  4990.0  405.02  4990.5  404.22  4995.8  404.22  4996.3  405.02  5002.9  405.21
  5010.6  410.44  5041.7  410.85  5045.9  411.59  5057.8  413.57  5063.0  413.00
  5120.5  413.22  5228.0  413.26  5321.1  414.17  5395.7  416.57  5448.5  419.68
  5488.6  424.17  5579.8  430.16  5598.6  432.10  5654.0  435.84  5776.5  443.63
#Mann=7,-1,0
  4539.3    0.05       0  4836.0    0.16       0  4990.0    0.07       0
  4996.3    0.16       0  5120.5    0.05       0  5395.7    0.16       0
  5654.0    0.05       0
Bank Sta=4987.2,5045.9
Exp/Cntr=0.3,0.1

Type RM Length L Ch R = 1,16682,328,328,328
BEGIN DESCRIPTION:
DALE CREEK 28.0
END DESCRIPTION:
XS GIS Cut Line= 4
      2852624.95      6987775.00      2853049.93      6987806.26
      2853343.17      6987724.07      2853346.80      6987160.45
#Sta/Elev= 30
  4328.7  433.48  4439.0  432.00  4555.9  432.22  4649.6  429.82  4689.7  425.01
  4719.8  422.95  4749.8  419.60  4776.9  417.60  4782.0  417.97  4884.4  412.88
  4905.5  412.86  4918.5  411.56  4923.7  410.96  4928.8  412.01  4957.4  411.37
  4962.9  410.31  4967.9  407.73  4993.9  403.38  4994.4  402.58  4999.7  402.58
  5000.2  403.38  5002.2  406.46  5041.5  409.81  5061.4  409.04  5078.4  410.14
  5258.9  411.56  5438.4  414.93  5518.4  420.49  5548.4  423.55  5623.0  427.66
#Mann=5,-1,0
  4328.7    0.05       0  4555.9    0.16       0  4967.9    0.05       0
  4993.9    0.03       0  5000.2    0.05       0
Bank Sta=4918.5,5258.9
Exp/Cntr=0.3,0.1

Type RM Length L Ch R = 1,16354,751,751,751
BEGIN DESCRIPTION:
DALE CREEK 27.0
END DESCRIPTION:
XS GIS Cut Line= 3
      2852758.29      6988179.52      2853346.80      6987908.69
      2853820.36      6987593.86
#Sta/Elev= 30
  4414.0  425.44  4460.3  426.42  4580.6  421.32  4619.5  421.62  4632.1  419.21
  4718.5  416.79  4724.0  413.55  4752.4  414.54  4769.9  411.74  4775.4  415.67
  4940.2  411.41  4987.6  408.05  4990.7  403.78  4991.2  402.98  4997.0  403.78
  5004.8  404.22  5010.6  408.37  5016.1  409.23  5056.5  406.69  5092.6  408.96
  5107.7  404.77  5119.7  408.48  5164.8  411.21  5170.8  409.47  5185.8  411.59
  5200.9  409.24  5233.9  411.41  5323.9  413.13  5381.1  417.86  5630.5  428.93
#Mann=4,-1,0
  4414.0    0.16       0  4990.7    0.07       0  4997.0    0.16       0
  5381.1    0.05       0
Bank Sta=4940.2,5233.9
Exp/Cntr=0.3,0.1

Type RM Length L Ch R = 1,15603,471,471,471
BEGIN DESCRIPTION:
DALE CREEK 26.0
END DESCRIPTION:
XS GIS Cut Line= 3
      2853325.00      6988625.01      2853525.00      6988175.00
      2853824.98      6987625.04
#Sta/Elev= 30
  4547.4  431.07  4624.0  429.98  4663.3  426.77  4758.7  421.96  4880.5  413.84
  4903.7  412.00  4908.5  410.03  4919.5  406.38  4927.0  406.04  4979.0  406.99
  4985.1  406.39  4998.8  401.64  4999.3  400.84  5005.2  400.84  5005.7  401.64
  5007.7  404.02  5039.0  407.93  5042.7  407.93  5047.9  409.87  5113.4  408.75
  5339.3  409.67  5374.8  410.03  5415.7  410.89  5445.6  413.52  5489.3  414.74
  5533.0  419.07  5541.0  420.72  5597.1  425.22  5608.9  426.63  5666.3  429.23
#Mann=7,-1,0
  4547.4    0.05       0  4663.3    0.16       0  4998.8    0.07       0
  5005.7    0.16       0  5039.0    0.05       0  5339.3    0.16       0
  5597.1    0.05       0
Bank Sta=4908.5,5374.8
Exp/Cntr=0.3,0.1

Type RM Length L Ch R = 1,15132,599,599,599
BEGIN DESCRIPTION:
DALE CREEK 25.0
END DESCRIPTION:
XS GIS Cut Line= 3
      2853424.96      6988575.01      2853875.00      6988475.00
      2854324.99      6988025.01
#Sta/Elev= 30
  4586.2  430.26  4605.4  430.32  4719.4  428.19  4795.0  423.02  4838.5  418.94
  4882.0  417.69  4935.8  414.43  4955.0  410.79  4961.0  408.74  4979.4  401.12
  4982.3  401.11  4982.8  400.31  4988.7  400.31  4989.2  401.11  5006.2  405.61
  5023.9  405.76  5028.0  407.60  5044.7  409.23  5075.5  407.89  5141.6  407.38
  5301.8  407.28  5372.5  409.65  5386.6  409.41  5400.8  407.70  5461.3  408.74
  5485.6  410.17  5513.9  413.40  5584.6  424.43  5670.4  429.08  5683.6  429.68
#Mann=7,-1,0
  4586.2    0.05       0  4605.4    0.16       0  4982.3    0.07       0
  4989.2    0.16       0  5023.9    0.05       0  5141.6    0.16       0
  5670.4    0.05       0
Bank Sta=4961,5461.3
Exp/Cntr=0.3,0.1

Type RM Length L Ch R = 1,14533,528,528,528
BEGIN DESCRIPTION:
DALE CREEK 24.0
END DESCRIPTION:
XS GIS Cut Line= 3
      2853725.03      6988974.99      2854175.00      6988825.00
      2854575.00      6988425.00
#Sta/Elev= 30
  4497.6  428.94  4529.2  428.93  4563.3  427.87  4603.0  426.62  4655.7  423.66
  4809.6  412.37  4898.1  408.19  4909.9  406.98  4919.2  404.46  4936.0  405.03
  4940.3  405.46  4950.8  403.07  4952.8  403.42  4961.4  404.93  4975.4  405.31
  4986.1  402.31  4996.6  401.40  4997.2  400.60  5003.2  400.60  5003.7  401.40
  5014.3  406.34  5108.1  405.14  5267.4  405.34  5438.6  405.58  5452.7  406.08
  5458.9  406.98  5466.9  408.14  5503.8  419.55  5523.5  423.78  5537.6  424.60
#Mann=10,-1,0
  4497.6    0.16       0  4563.3    0.05       0  4809.6    0.16       0
  4936.0    0.12       0  4952.8    0.16       0  4996.6    0.07       0
  5003.7    0.16       0  5108.1     0.1       0  5267.4    0.16       0
  5503.8    0.05       0
Bank Sta=4909.9,5458.9
Exp/Cntr=0.3,0.1

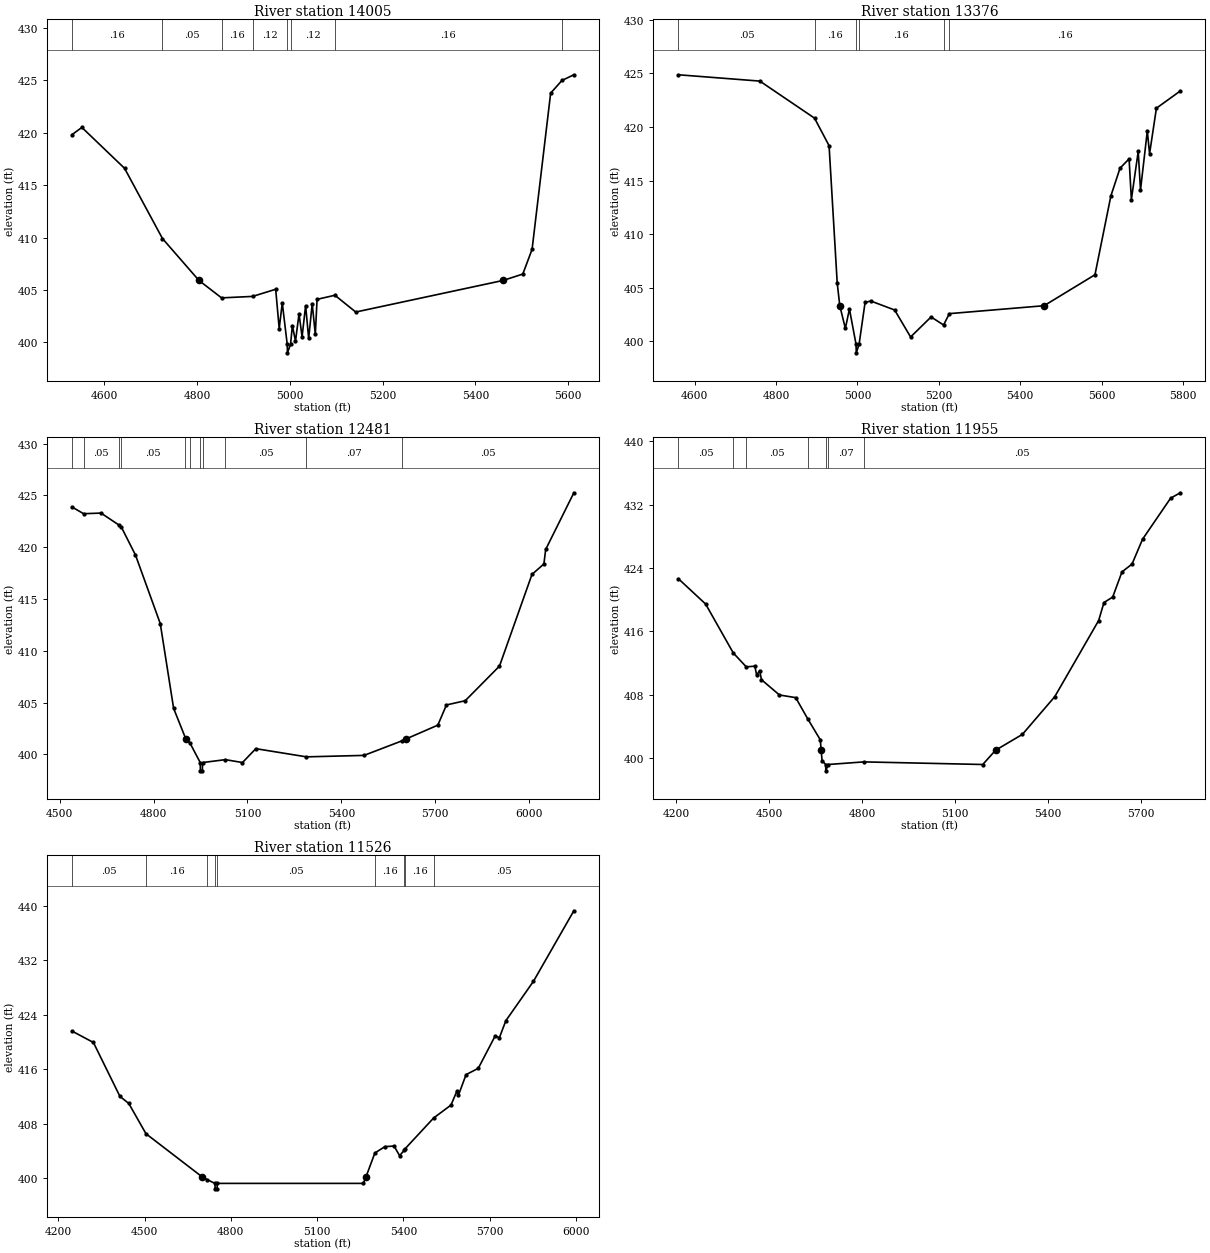
Type RM Length L Ch R = 1,14005,629,629,629
BEGIN DESCRIPTION:
DALE CREEK 23.0
END DESCRIPTION:
XS GIS Cut Line= 3
      2854275.00      6989375.00      2854625.00      6988975.00
      2854625.00      6988425.00
#Sta/Elev= 30
  4530.5  419.81  4551.9  420.50  4643.9  416.60  4725.5  409.91  4804.2  405.91
  4852.9  404.25  4919.8  404.39  4969.5  405.07  4977.1  401.32  4983.7  403.77
  4994.4  399.81  4994.9  399.01  5001.5  399.81  5005.5  401.61  5012.2  400.12
  5019.8  402.73  5026.4  400.54  5034.0  403.51  5040.6  400.38  5048.2  403.69
  5054.9  400.77  5058.7  404.11  5097.1  404.50  5142.0  402.90  5459.3  405.91
  5502.0  406.52  5522.0  408.88  5562.0  423.77  5586.4  424.98  5612.0  425.52
#Mann=8,-1,0
  4530.5    0.16       0  4725.5    0.05       0  4852.9    0.16       0
  4919.8    0.12       0  4994.4    0.07       0  5001.5    0.12       0
  5097.1    0.16       0  5586.4    0.05       0
Bank Sta=4804.2,5459.3
Exp/Cntr=0.3,0.1

Type RM Length L Ch R = 1,13376,895,895,895
BEGIN DESCRIPTION:
DALE CREEK 22.0
END DESCRIPTION:
XS GIS Cut Line= 3
      2855025.00      6989674.97      2855025.00      6989225.00
      2854675.00      6988524.99
#Sta/Elev= 30
  4560.5  424.88  4760.5  424.29  4894.8  420.83  4930.5  418.26  4950.5  405.43
  4956.8  403.32  4970.5  401.20  4980.5  403.01  4996.7  399.72  4997.3  398.92
  5004.2  399.72  5018.9  403.62  5032.8  403.76  5091.5  402.92  5130.7  400.40
  5181.0  402.27  5211.7  401.52  5225.9  402.58  5458.5  403.32  5583.5  406.21
  5622.6  413.58  5645.0  416.16  5667.3  417.03  5672.9  413.23  5689.7  417.73
  5695.3  414.12  5712.0  419.62  5717.6  417.52  5734.4  421.76  5793.1  423.37
#Mann=6,-1,0
  4560.5    0.05       0  4894.8    0.16       0  4996.7    0.07       0
  5004.2    0.16       0  5211.7    0.05       0  5225.9    0.16       0
Bank Sta=4956.8,5458.5
Exp/Cntr=0.3,0.1

Type RM Length L Ch R = 1,12481,526,526,526
BEGIN DESCRIPTION:
DALE CREEK 21.0
END DESCRIPTION:
XS GIS Cut Line= 3
      2855131.07      6989668.81      2855448.79      6989153.17
      2854975.00      6988274.99
#Sta/Elev= 30
  4539.4  423.88  4576.6  423.23  4632.3  423.29  4689.9  422.13  4697.5  421.92
  4742.4  419.24  4821.6  412.62  4864.2  404.44  4901.5  401.62  4903.3  401.47
  4916.5  401.09  4949.2  399.21  4949.8  398.41  4956.1  398.41  4956.7  399.21
  5029.8  399.49  5084.2  399.21  5126.8  400.55  5288.6  399.76  5472.5  399.90
  5594.2  401.31  5605.5  401.47  5708.3  402.82  5735.9  404.77  5795.9  405.18
  5905.3  408.52  6009.1  417.37  6047.2  418.38  6052.9  419.78  6142.9  425.25
#Mann=11,-1,0
  4539.4    0.08       0  4576.6    0.05       0  4689.9    0.08       0
  4697.5    0.05       0  4901.5    0.16       0  4916.5    0.07       0
  4949.2    0.07       0  4956.7    0.07       0  5029.8    0.05       0
  5288.6    0.07       0  5594.2    0.05       0
Bank Sta=4903.3,5605.5
Exp/Cntr=0.3,0.1

Type RM Length L Ch R = 1,11955,429,429,429
BEGIN DESCRIPTION:
DALE CREEK 20.0
END DESCRIPTION:
XS GIS Cut Line= 3
      2855230.04      6989668.79      2855828.99      6989304.21
      2856225.00      6988475.00
#Sta/Elev= 30
  4206.7  422.65  4294.5  419.46  4383.9  413.28  4425.8  411.53  4453.4  411.62
  4459.3  410.49  4468.9  411.06  4474.8  409.91  4532.9  407.98  4585.2  407.65
  4624.3  404.96  4664.6  402.33  4667.5  401.01  4670.4  399.71  4681.9  399.21
  4682.6  398.41  4690.0  399.21  4805.5  399.54  5189.1  399.21  5230.4  401.01
  5317.0  403.01  5421.5  407.77  5563.2  417.38  5580.3  419.65  5608.5  420.34
  5638.4  423.51  5671.0  424.51  5704.9  427.64  5795.5  432.82  5826.8  433.50
#Mann=7,-1,0
  4206.7    0.05       0  4383.9    0.16       0  4425.8    0.05       0
  4624.3    0.07       0  4681.9   0.033       0  4690.0    0.07       0
  4805.5    0.05       0
Bank Sta=4667.5,5230.4
Exp/Cntr=0.3,0.1

Type RM Length L Ch R = 1,11526,0,0,0
BEGIN DESCRIPTION:
DALE CREEK 19.0
END DESCRIPTION:
XS GIS Cut Line= 4
      2855563.33      6989736.51      2856157.12      6989522.96
      2856325.85      6989344.54      2856594.26      6988518.86
#Sta/Elev= 30
  4247.7  421.58  4322.3  419.90  4414.4  411.99  4445.2  410.95  4505.1  406.50
  4699.6  400.19  4717.3  399.77  4744.8  399.21  4745.5  398.41  4752.3  398.41
  4753.0  399.21  5260.5  399.21  5270.1  400.19  5300.7  403.67  5335.6  404.61
  5367.5  404.69  5386.7  403.28  5402.8  404.07  5406.6  404.33  5505.0  408.81
  5565.4  410.71  5585.9  412.75  5591.1  412.14  5617.8  415.18  5660.3  416.11
  5718.9  420.86  5733.7  420.61  5756.1  423.10  5852.0  428.88  5992.5  439.24
#Mann=9,-1,0
  4247.7    0.05       0  4505.1    0.16       0  4717.3    0.05       0
  4744.8   0.033       0  4753.0    0.05       0  5300.7    0.16       0
  5402.8    0.05       0  5406.6    0.16       0  5505.0    0.05       0
Bank Sta=4699.6,5270.1
Exp/Cntr=0.3,0.1

Chan Stop Cuts=-1