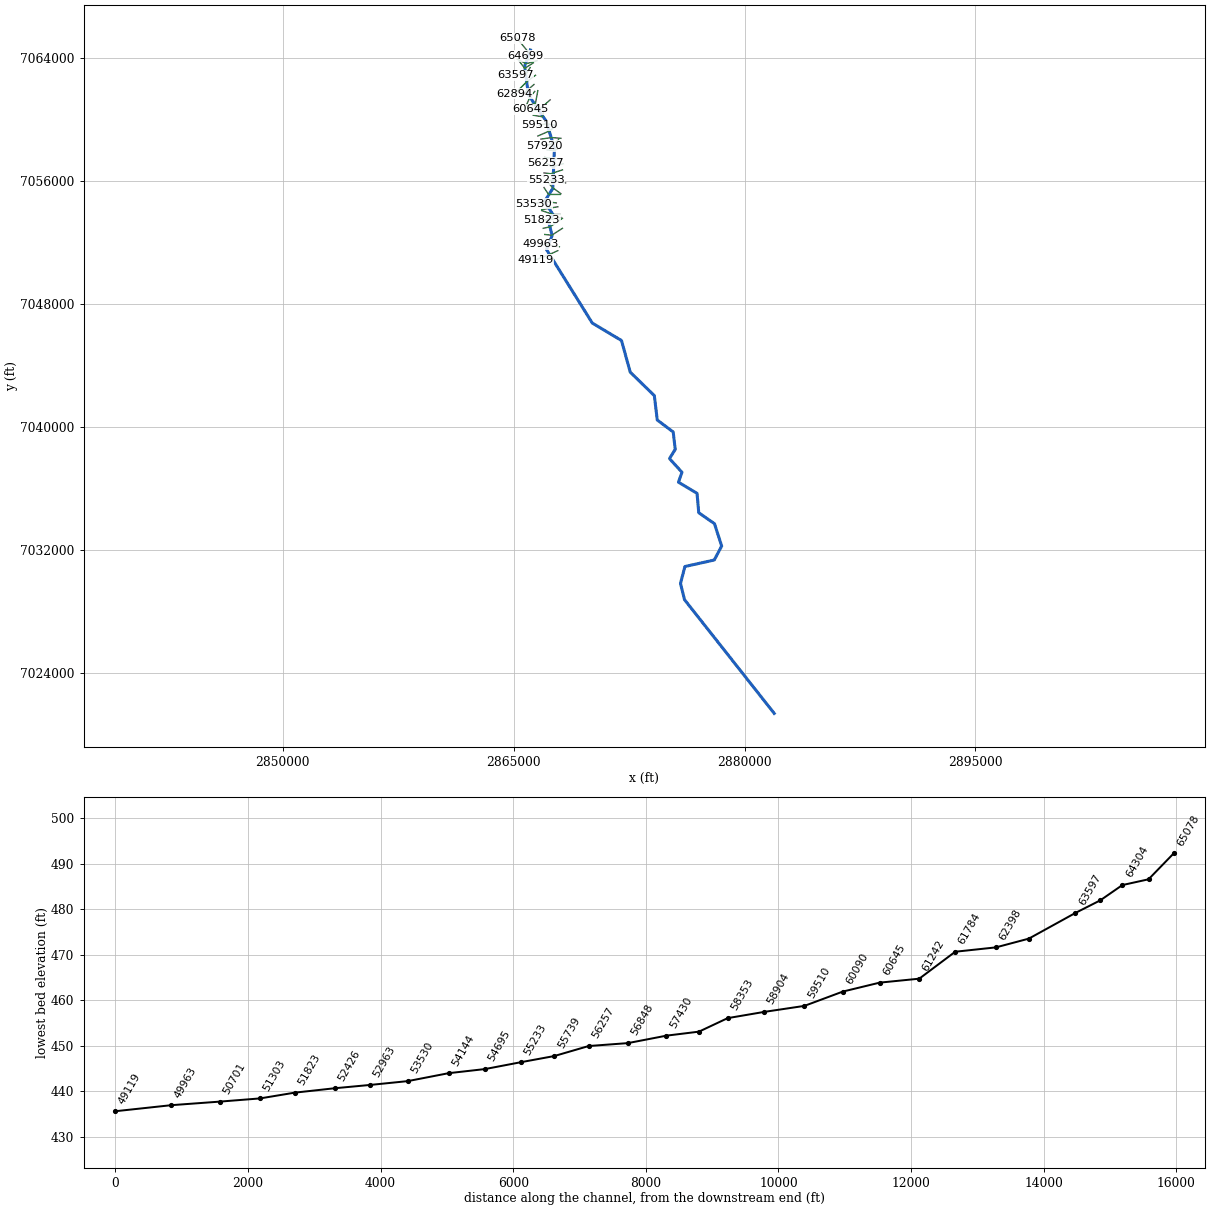
--- GLADE CREEK.prj (project) ---

Proj Title=GLADE CREEK Base Level Engineering
Current Plan=p01
Default Exp/Contr=0.3,0.1
English Units
Geom File=g01
Flow File=f01
Plan File=p01
BEGIN DESCRIPTION:
GLADE CREEK
END DESCRIPTION:

--- GLADE CREEK.p01 (plan) ---

Plan Title=Multiple Run
Short Identifier=Multiple
Geom File=g01
Flow File=f01
Subcritical Flow
K Sum by GR= 0
Std Step Tol= 0.01
Critical Tol= 0.01
Num of Std Step Trials= 20
Max Error Tol= 0.3
Flow Tol Ratio= 0.001
Split Flow NTrial= 30
Split Flow Tol= 0.02
Split Flow Ratio= 0.02
Log Output Level= 0
Friction Slope Method= 1
Unsteady Friction Slope Method= 2
Unsteady Bridges Friction Slope Method= 1
Parabolic Critical Depth
Global Vel Dist=  1 , 1 , 1
Global Log Level= 0
CheckData=True
Encroach Param= -1, 0, 0, 0
BEGIN DESCRIPTION:
Multiple Run
END DESCRIPTION:

--- GLADE CREEK.f01 (steady flow) ---

Flow Title=Multiple
Number of Profiles=7
Profile Names=10-year,25-year,50-year,1pct_min,100-year,1pct_plu,500-year
River Rch & RM= GLADE CREEK,Reach-1,65078
     634     842    1010     601    1199    2391    1684
River Rch & RM= GLADE CREEK,Reach-1,62894
     863    1170    1420     855    1705    3402    2453
River Rch & RM= GLADE CREEK,Reach-1,61784
    1399    1941    2394    1461    2916    5817    4319
River Rch & RM= GLADE CREEK,Reach-1,56848
    1502    2089    2582    1579    3150    6286    4688
River Rch & RM= GLADE CREEK,Reach-1,52963
    2263    3210    4019    2487    4963    9902    7572
River Rch & RM= GLADE CREEK,Reach-1,49119
    2315    3274    4092    2527    5041   10059    7662
River Rch & RM= GLADE CREEK,Reach-1,40773
    2472    3506    4388    2714    5414   10803    8255
River Rch & RM= GLADE CREEK,Reach-1,38051
    2584    3662    4582    2832    5650   11274    8606
River Rch & RM= GLADE CREEK,Reach-1,31699
    2637    3735    4672    2886    5759   11490    8764
River Rch & RM= GLADE CREEK,Reach-1,23113
    3192    4553    5724    3553    7089   14145   10894
River Rch & RM= GLADE CREEK,Reach-1,21264
    3341    4775    6010    3735    7452   14868   11477
River Rch & RM= GLADE CREEK,Reach-1,20391
    3283    4678    5876    3644    7270   14506   11150
River Rch & RM= GLADE CREEK,Reach-1,18461
    3470    4956    6236    3873    7728   15419   11890
River Rch & RM= GLADE CREEK,Reach-1,10624
    3397    4833    6062    3754    7490   14945   11455
Boundary for River Rch & Prof#=GLADE CREEK,Reach-1,1
Up Type=0
Dn Type=3
Dn Slope=0.005
Boundary for River Rch & Prof#=GLADE CREEK,Reach-1,2
Up Type=0
Dn Type=3
Dn Slope=0.005
Boundary for River Rch & Prof#=GLADE CREEK,Reach-1,3
Up Type=0
Dn Type=3
Dn Slope=0.005
Boundary for River Rch & Prof#=GLADE CREEK,Reach-1,4
Up Type=0
Dn Type=3
Dn Slope=0.005
Boundary for River Rch & Prof#=GLADE CREEK,Reach-1,5
Up Type=0
Dn Type=3
Dn Slope=0.005
Boundary for River Rch & Prof#=GLADE CREEK,Reach-1,6
Up Type=0
Dn Type=3
Dn Slope=0.005
Boundary for River Rch & Prof#=GLADE CREEK,Reach-1,7
Up Type=0
Dn Type=3
Dn Slope=0.005

--- GLADE CREEK.g01 (geometry) ---

Geom Title=Existing Conditions

River Reach=GLADE CREEK,Reach-1
Reach XY= 30
      2866089.57      7064519.92      2865715.43      7063470.69
      2865963.95      7061598.12      2867119.28      7059883.64
      2867653.04      7058116.13      2867544.61      7055510.99
      2867005.78      7054667.27      2867585.45      7053780.70
      2867245.67      7053485.99      2867504.40      7052450.05
      2867137.29      7051546.05      2870113.65      7046764.02
      2872009.55      7045631.45      2872578.03      7043571.71
      2874141.90      7042049.18      2874331.95      7040465.01
      2875368.38      7039684.13      2875499.54      7038555.73
      2875128.22      7037954.98      2875937.27      7037064.42
      2875707.84      7036419.90      2876916.88      7035695.38
      2877027.07      7034435.01      2878048.95      7033724.07
      2878516.87      7032267.48      2878030.84      7031360.32
      2876128.97      7030939.19      2875841.13      7029839.90
      2876102.87      7028782.01      2881929.20      7021392.07

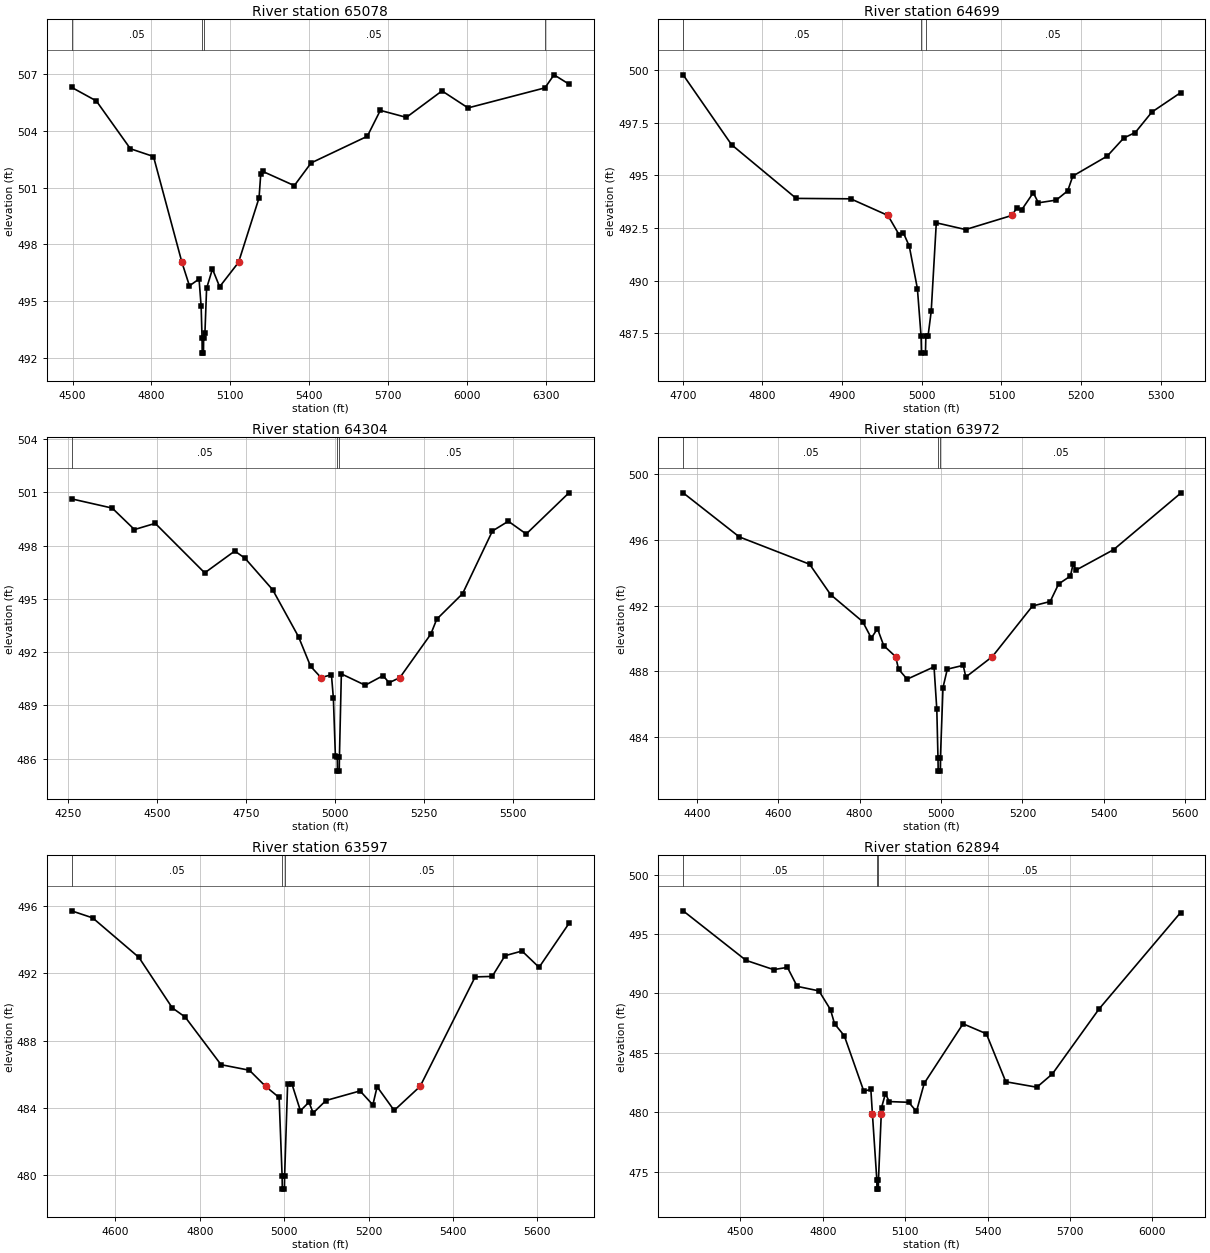
Type RM Length L Ch R = 1,65078,379,379,379
BEGIN DESCRIPTION:
GLADE CREEK 66.0
END DESCRIPTION:
XS GIS Cut Line= 3
      2866524.99      7064424.99      2866125.00      7064175.00
      2865224.97      7065275.03
#Sta/Elev= 30
  4495.7  506.31  4590.0  505.59  4719.7  503.06  4807.6  502.65  4915.8  497.05
  4944.4  495.81  4981.0  496.17  4988.9  494.73  4992.4  493.05  4992.9  492.25
  4997.9  492.25  4998.4  493.05  5003.3  493.30  5009.7  495.68  5032.0  496.70
  5059.3  495.76  5131.2  497.05  5209.3  500.46  5215.8  501.73  5223.6  501.86
  5343.5  501.11  5407.4  502.31  5621.3  503.72  5670.8  505.09  5769.9  504.72
  5905.6  506.12  6004.6  505.22  6297.2  506.28  6331.9  506.97  6388.7  506.48
#Mann=4,-1,0
  4495.7    0.05       0  4992.4    0.03       0  4998.4    0.05       0
  6297.2    0.16       0
Bank Sta=4915.8,5131.2
Exp/Cntr=0.3,0.1

Type RM Length L Ch R = 1,64699,395,395,395
BEGIN DESCRIPTION:
GLADE CREEK 65.0
END DESCRIPTION:
XS GIS Cut Line= 3
      2866274.95      7063924.99      2865975.00      7063875.00
      2865775.03      7064124.96
#Sta/Elev= 30
  4700.5  499.78  4761.3  496.46  4842.4  493.91  4910.8  493.89  4957.5  493.10
  4971.6  492.18  4976.7  492.29  4984.3  491.64  4994.5  489.62  4999.1  487.36
  4999.6  486.56  5004.6  486.56  5005.1  487.36  5007.8  487.36  5011.8  488.54
  5018.2  492.75  5055.0  492.43  5113.0  493.10  5119.0  493.44  5125.4  493.37
  5139.9  494.18  5146.3  493.70  5168.7  493.83  5183.1  494.27  5189.5  494.97
  5232.7  495.92  5253.5  496.78  5267.9  497.04  5288.7  498.01  5324.7  498.93
#Mann=3,-1,0
  4700.5    0.05       0  4999.1    0.03       0  5005.1    0.05       0
Bank Sta=4957.5,5113
Exp/Cntr=0.3,0.1

Type RM Length L Ch R = 1,64304,332,332,332
BEGIN DESCRIPTION:
GLADE CREEK 64.0
END DESCRIPTION:
XS GIS Cut Line= 3
      2866525.05      7063825.01      2865825.00      7063625.00
      2865224.98      7063925.01
#Sta/Elev= 30
  4258.6  500.63  4373.0  500.11  4435.5  498.90  4494.0  499.25  4633.1  496.46
  4717.6  497.69  4746.2  497.29  4824.2  495.51  4897.0  492.86  4930.8  491.20
  4960.1  490.56  4989.5  490.72  4995.0  489.40  5000.6  486.16  5006.0  486.09
  5006.5  485.29  5011.5  485.29  5012.0  486.09  5017.4  490.77  5084.5  490.13
  5134.8  490.67  5151.6  490.27  5182.0  490.56  5269.0  493.01  5285.7  493.85
  5358.4  495.29  5442.3  498.82  5487.0  499.37  5537.3  498.65  5657.5  500.97
#Mann=3,-1,0
  4258.6    0.05       0  5006.0    0.03       0  5012.0    0.05       0
Bank Sta=4960.1,5182
Exp/Cntr=0.3,0.1

Type RM Length L Ch R = 1,63972,375,375,375
BEGIN DESCRIPTION:
GLADE CREEK 63.0
END DESCRIPTION:
XS GIS Cut Line= 3
      2866275.02      7063675.01      2865725.00      7063325.00
      2865375.02      7063774.98
#Sta/Elev= 30
  4366.4  498.86  4504.4  496.18  4677.1  494.52  4728.8  492.67  4807.5  491.03
  4828.7  490.03  4843.9  490.60  4859.2  489.57  4888.5  488.90  4895.6  488.14
  4916.7  487.53  4982.8  488.28  4989.6  485.70  4992.5  482.74  4993.0  481.94
  4998.0  481.94  4998.5  482.74  5004.8  487.02  5015.4  488.14  5054.5  488.37
  5060.9  487.66  5126.0  488.90  5224.7  491.98  5268.1  492.25  5288.9  493.32
  5317.9  493.80  5324.2  494.51  5332.3  494.17  5423.7  495.40  5588.4  498.83
#Mann=3,-1,0
  4366.4    0.05       0  4992.5    0.03       0  4998.5    0.05       0
Bank Sta=4888.5,5126
Exp/Cntr=0.3,0.1

Type RM Length L Ch R = 1,63597,703,703,703
BEGIN DESCRIPTION:
GLADE CREEK 62.0
END DESCRIPTION:
XS GIS Cut Line= 3
      2866074.97      7063374.96      2865825.00      7062975.00
      2865124.96      7062874.99
#Sta/Elev= 30
  4496.1  495.72  4546.2  495.30  4655.8  492.95  4734.8  489.95  4765.5  489.40
  4850.4  486.57  4917.6  486.24  4956.0  485.28  4988.0  484.62  4995.1  479.97
  4995.6  479.17  5000.6  479.17  5001.1  479.97  5008.2  485.44  5018.3  485.43
  5038.5  483.83  5058.7  484.34  5068.8  483.70  5099.1  484.44  5179.9  485.01
  5210.2  484.18  5220.3  485.26  5260.7  483.85  5322.2  485.28  5452.6  491.79
  5493.0  491.82  5523.3  493.05  5563.7  493.33  5604.1  492.36  5674.9  494.97
#Mann=3,-1,0
  4496.1    0.05       0  4995.1    0.03       0  5001.1    0.05       0
Bank Sta=4956,5322.2
Exp/Cntr=0.3,0.1

Type RM Length L Ch R = 1,62894,496,496,496
BEGIN DESCRIPTION:
GLADE CREEK 61.0
END DESCRIPTION:
XS GIS Cut Line= 3
      2866424.97      7062874.98      2865875.00      7062475.00
      2865075.00      7061675.00
#Sta/Elev= 30
  4291.2  496.95  4520.3  492.78  4620.8  492.00  4671.0  492.19  4706.5  490.59
  4785.8  490.21  4827.9  488.63  4842.6  487.44  4878.1  486.43  4949.2  481.76
  4974.8  481.92  4980.5  479.85  4996.5  474.32  4997.0  473.52  5002.1  473.52
  5002.6  474.32  5012.7  479.85  5013.7  480.38  5027.8  481.55  5041.9  480.89
  5112.7  480.83  5140.9  480.06  5169.2  482.43  5310.6  487.44  5395.5  486.60
  5466.2  482.56  5579.3  482.10  5635.9  483.22  5805.6  488.68  6102.6  496.80
#Mann=3,-1,0
  4291.2    0.05       0  4996.5    0.03       0  5002.6    0.05       0
Bank Sta=4980.5,5012.7
Exp/Cntr=0.3,0.1

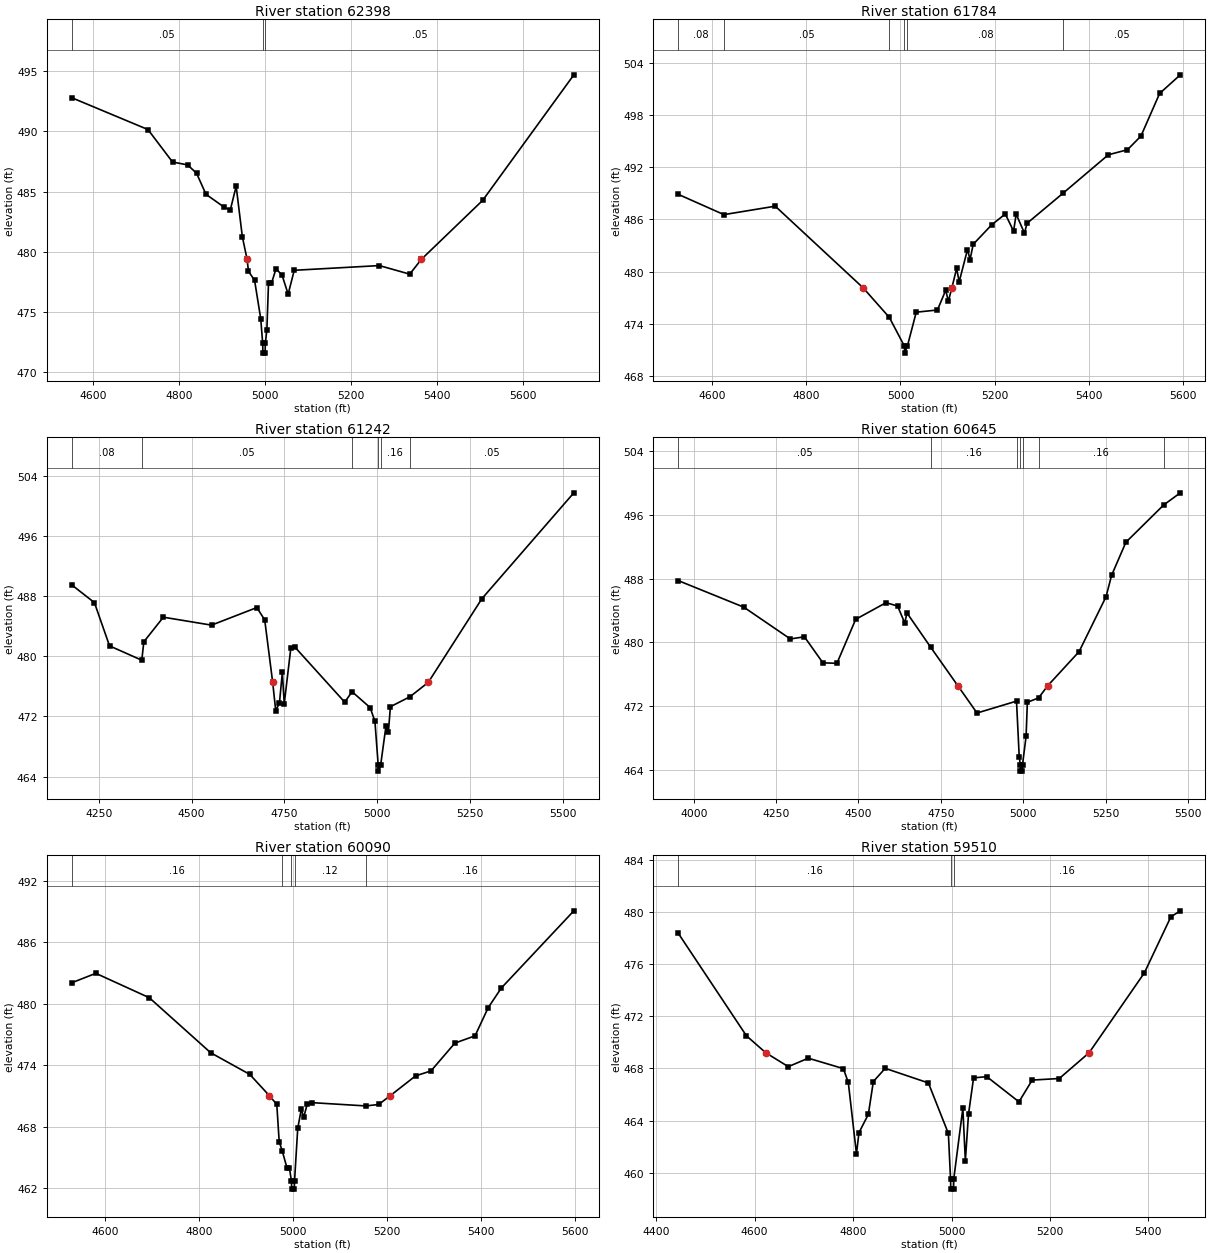
Type RM Length L Ch R = 1,62398,614,614,614
BEGIN DESCRIPTION:
GLADE CREEK 60.0
END DESCRIPTION:
XS GIS Cut Line= 3
      2866325.03      7062275.02      2865975.00      7061975.00
      2865475.02      7061475.02
#Sta/Elev= 30
  4549.6  492.78  4726.9  490.14  4784.0  487.45  4819.1  487.21  4839.9  486.52
  4861.9  484.77  4904.7  483.69  4918.4  483.47  4932.1  485.44  4946.4  481.26
  4957.5  479.38  4960.7  478.39  4974.9  477.64  4989.2  474.46  4993.8  472.40
  4994.3  471.60  4999.4  471.60  4999.9  472.40  5003.5  473.54  5007.3  477.39
  5014.2  477.39  5024.8  478.60  5038.9  478.06  5053.0  476.49  5067.2  478.47
  5265.2  478.86  5335.9  478.15  5363.0  479.38  5505.6  484.27  5717.7  494.68
#Mann=3,-1,0
  4549.6    0.05       0  4993.8    0.03       0  4999.9    0.05       0
Bank Sta=4957.5,5363
Exp/Cntr=0.3,0.1

Type RM Length L Ch R = 1,61784,542,542,542
BEGIN DESCRIPTION:
GLADE CREEK 59.0
END DESCRIPTION:
XS GIS Cut Line= 3
      2866374.97      7061824.97      2866075.00      7061475.00
      2865825.00      7060924.99
#Sta/Elev= 30
  4528.5  488.87  4625.4  486.54  4734.3  487.51  4920.7  478.14  4976.3  474.74
  5008.3  471.44  5008.8  470.64  5014.6  471.44  5033.4  475.34  5078.4  475.59
  5096.0  477.87  5101.5  476.58  5109.0  478.14  5119.1  480.36  5124.5  478.83
  5142.1  482.53  5147.6  481.38  5154.2  483.13  5193.8  485.39  5222.3  486.61
  5239.9  484.65  5245.4  486.60  5263.0  484.41  5268.4  485.54  5345.7  489.04
  5440.9  493.41  5481.5  493.99  5510.1  495.56  5549.7  500.45  5593.6  502.59
#Mann=6,-1,0
  4528.5    0.08       0  4625.4    0.05       0  4976.3    0.08       0
  5008.3    0.07       0  5014.6    0.08       0  5345.7    0.05       0
Bank Sta=4920.7,5109
Exp/Cntr=0.3,0.1

Type RM Length L Ch R = 1,61242,597,597,597
BEGIN DESCRIPTION:
GLADE CREEK 58.0
END DESCRIPTION:
XS GIS Cut Line= 3
      2866574.99      7061874.96      2866425.00      7061075.00
      2865925.02      7060875.01
#Sta/Elev= 30
  4177.2  489.52  4238.2  487.16  4278.9  481.40  4365.8  479.49  4371.3  481.94
  4423.9  485.22  4553.6  484.16  4675.7  486.50  4696.9  484.86  4718.4  476.54
  4726.6  472.75  4736.7  473.84  4744.4  477.87  4749.5  473.68  4767.3  481.13
  4777.4  481.28  4912.3  473.91  4932.3  475.29  4980.9  473.18  4993.8  471.35
  5002.6  465.52  5003.1  464.72  5009.2  465.52  5023.4  470.68  5030.1  469.98
  5035.5  473.30  5088.0  474.62  5137.5  476.54  5281.9  487.68  5529.6  501.78
#Mann=6,-1,0
  4177.2    0.08       0  4365.8    0.05       0  4932.3    0.16       0
  5002.6    0.07       0  5009.2    0.16       0  5088.0    0.05       0
Bank Sta=4718.4,5137.5
Exp/Cntr=0.3,0.1

Type RM Length L Ch R = 1,60645,555,555,555
BEGIN DESCRIPTION:
GLADE CREEK 57.0
END DESCRIPTION:
XS GIS Cut Line= 3
      2867375.01      7061275.01      2866575.00      7060575.00
      2866125.00      7060675.00
#Sta/Elev= 30
  3952.9  487.75  4151.8  484.42  4293.2  480.43  4335.9  480.70  4391.9  477.44
  4434.6  477.37  4491.5  482.89  4583.6  484.98  4618.7  484.56  4640.5  482.43
  4647.2  483.69  4719.7  479.36  4801.6  474.56  4859.8  471.14  4979.7  472.63
  4987.9  465.67  4991.3  464.65  4991.8  463.85  4997.4  463.85  4997.9  464.65
  5008.8  468.23  5012.6  472.48  5046.8  473.04  5074.4  474.56  5169.6  478.84
  5251.5  485.73  5268.2  488.40  5311.7  492.56  5426.2  497.23  5476.9  498.76
#Mann=7,-1,0
  3952.9    0.05       0  4719.7    0.16       0  4979.7    0.12       0
  4991.3    0.07       0  4997.9    0.12       0  5046.8    0.16       0
  5426.2    0.05       0
Bank Sta=4801.6,5074.4
Exp/Cntr=0.3,0.1

Type RM Length L Ch R = 1,60090,580,580,580
BEGIN DESCRIPTION:
GLADE CREEK 56.0
END DESCRIPTION:
XS GIS Cut Line= 3
      2866974.99      7060624.96      2866875.00      7060175.00
      2866275.01      7060275.00
#Sta/Elev= 30
  4529.2  482.03  4580.4  482.95  4694.3  480.57  4825.0  475.20  4908.2  473.09
  4949.8  471.02  4965.8  470.16  4970.9  466.53  4977.5  465.60  4987.6  463.95
  4992.7  463.95  4997.0  462.69  4997.5  461.89  5003.1  461.89  5003.6  462.69
  5010.4  467.82  5018.0  469.69  5023.1  468.90  5030.7  470.20  5040.8  470.33
  5155.2  470.01  5182.8  470.15  5207.7  471.02  5261.3  472.94  5294.3  473.43
  5345.0  476.14  5388.0  476.85  5415.9  479.59  5443.8  481.51  5598.4  489.05
#Mann=5,-1,0
  4529.2    0.16       0  4977.5    0.12       0  4997.0    0.07       0
  5003.6    0.12       0  5155.2    0.16       0
Bank Sta=4949.8,5207.7
Exp/Cntr=0.3,0.1

Type RM Length L Ch R = 1,59510,606,606,606
BEGIN DESCRIPTION:
GLADE CREEK 55.0
END DESCRIPTION:
XS GIS Cut Line= 3
      2867674.97      7059625.00      2867125.00      7059725.00
      2866674.97      7059624.99
#Sta/Elev= 30
  4444.8  478.38  4583.3  470.51  4622.5  469.21  4668.4  468.14  4709.0  468.79
  4780.2  467.99  4790.3  466.93  4806.9  461.44  4811.9  463.07  4831.0  464.48
  4841.2  467.00  4865.3  468.01  4953.0  466.89  4993.6  463.01  4998.0  459.54
  4998.5  458.74  5004.1  458.74  5004.6  459.54  5023.0  464.94  5028.1  460.92
  5034.5  464.49  5044.8  467.28  5071.7  467.37  5137.0  465.44  5163.9  467.11
  5218.9  467.23  5279.6  469.21  5391.8  475.34  5445.6  479.64  5464.8  480.10
#Mann=3,-1,0
  4444.8    0.16       0  4998.0    0.07       0  5004.6    0.16       0
Bank Sta=4622.5,5279.6
Exp/Cntr=0.3,0.1

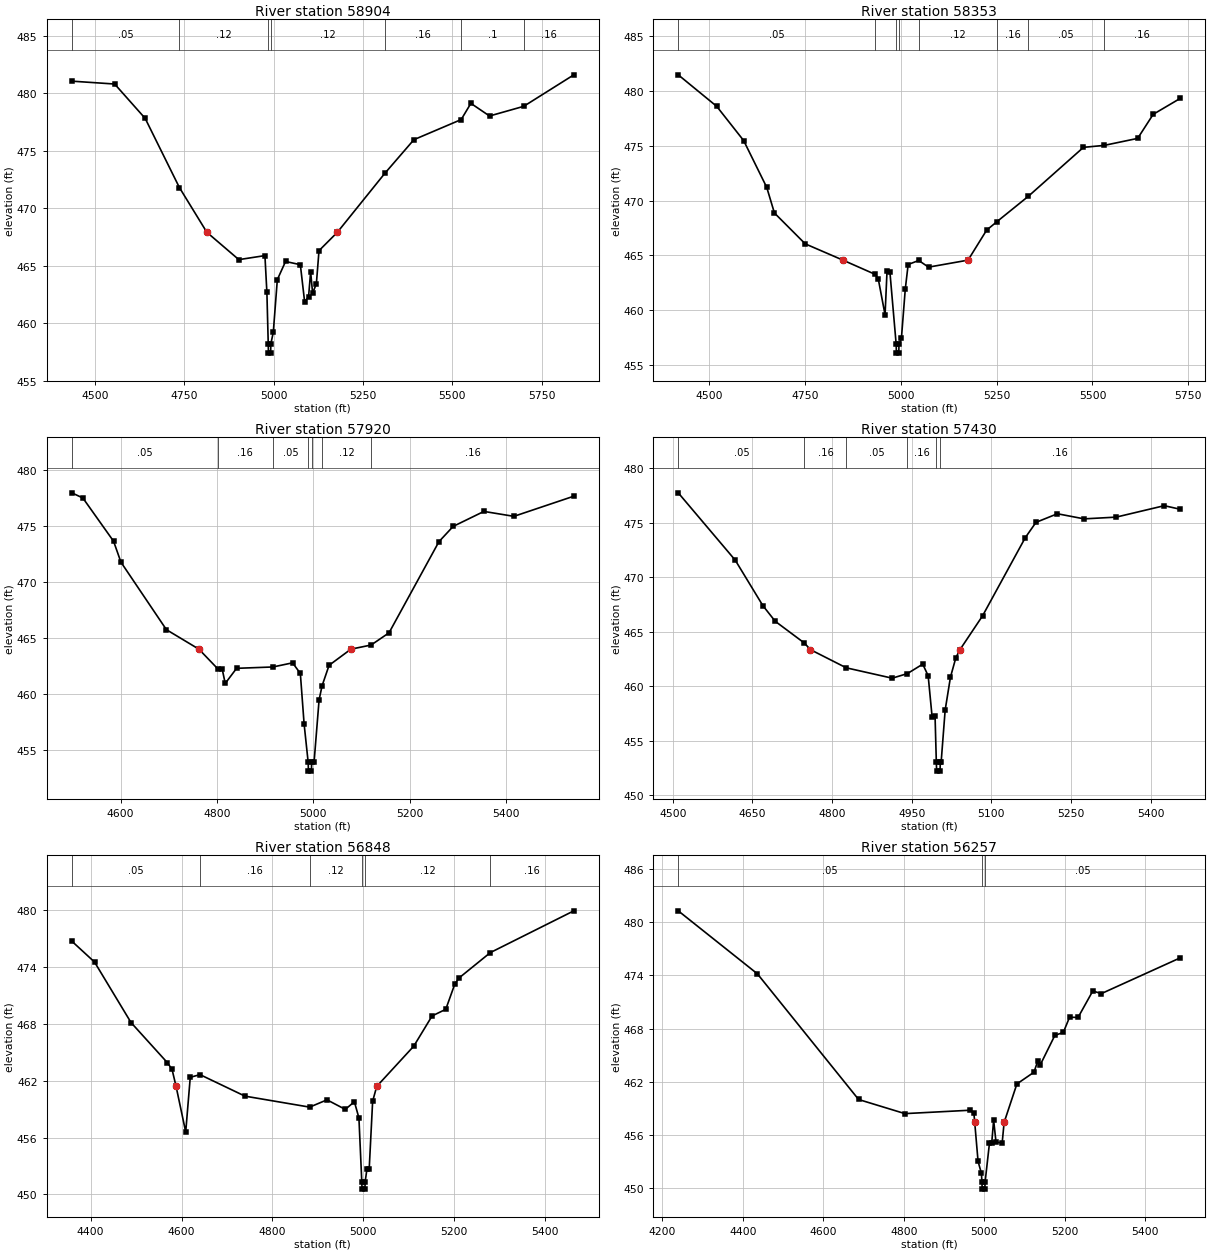
Type RM Length L Ch R = 1,58904,551,551,551
BEGIN DESCRIPTION:
GLADE CREEK 54.0
END DESCRIPTION:
XS GIS Cut Line= 3
      2867774.97      7059624.98      2867375.00      7059275.00
      2866574.98      7058924.99
#Sta/Elev= 30
  4435.6  481.07  4555.6  480.82  4641.0  477.83  4736.7  471.82  4813.5  467.93
  4903.0  465.55  4976.0  465.90  4981.5  462.70  4985.3  458.22  4985.8  457.42
  4992.0  457.42  4992.5  458.22  4999.4  459.23  5010.7  463.81  5033.7  465.39
  5075.1  465.11  5087.1  461.88  5098.1  462.32  5103.9  464.49  5109.4  462.64
  5119.9  463.44  5127.3  466.33  5178.7  467.93  5311.1  473.04  5392.8  475.98
  5525.1  477.73  5552.2  479.14  5604.4  478.04  5700.0  478.88  5840.3  481.62
#Mann=7,-1,0
  4435.6    0.05       0  4736.7    0.12       0  4985.3    0.07       0
  4992.5    0.12       0  5311.1    0.16       0  5525.1     0.1       0
  5700.0    0.16       0
Bank Sta=4813.5,5178.7
Exp/Cntr=0.3,0.1

Type RM Length L Ch R = 1,58353,433,433,433
BEGIN DESCRIPTION:
GLADE CREEK 53.0
END DESCRIPTION:
XS GIS Cut Line= 3
      2868074.98      7058775.00      2867475.00      7058825.00
      2866774.96      7058724.99
#Sta/Elev= 30
  4419.9  481.49  4520.2  478.61  4590.5  475.48  4650.7  471.20  4670.7  468.86
  4751.0  466.04  4849.4  464.55  4934.1  463.24  4941.7  462.80  4959.2  459.55
  4964.3  463.53  4971.8  463.49  4988.2  456.85  4988.8  456.05  4995.0  456.05
  4995.5  456.85  5001.9  457.43  5011.9  461.89  5019.4  464.15  5047.0  464.52
  5072.5  463.91  5175.6  464.55  5224.0  467.29  5250.3  468.05  5332.9  470.39
  5476.5  474.86  5530.7  475.04  5617.9  475.68  5658.4  477.88  5729.1  479.34
#Mann=8,-1,0
  4419.9    0.05       0  4934.1    0.16       0  4988.2    0.07       0
  4995.5    0.16       0  5047.0    0.12       0  5250.3    0.16       0
  5332.9    0.05       0  5530.7    0.16       0
Bank Sta=4849.4,5175.6
Exp/Cntr=0.3,0.1

Type RM Length L Ch R = 1,57920,490,490,490
BEGIN DESCRIPTION:
GLADE CREEK 52.0
END DESCRIPTION:
XS GIS Cut Line= 3
      2867925.02      7058675.01      2867525.00      7058425.00
      2866975.01      7058275.00
#Sta/Elev= 30
  4498.7  477.93  4521.7  477.47  4585.4  473.61  4600.7  471.74  4695.1  465.71
  4762.5  463.97  4801.1  462.24  4810.6  462.24  4817.1  460.91  4840.7  462.26
  4916.1  462.38  4956.9  462.75  4973.0  461.80  4980.8  457.29  4989.2  453.88
  4989.8  453.08  4996.0  453.08  4996.5  453.88  5001.5  453.90  5011.9  459.45
  5018.1  460.70  5032.6  462.53  5077.9  463.97  5119.8  464.34  5157.0  465.43
  5260.6  473.57  5290.0  474.93  5353.9  476.27  5416.1  475.83  5540.5  477.63
#Mann=7,-1,0
  4498.7    0.05       0  4801.1    0.16       0  4916.1    0.05       0
  4989.2    0.03       0  4996.5    0.05       0  5018.1    0.12       0
  5119.8    0.16       0
Bank Sta=4762.5,5077.9
Exp/Cntr=0.3,0.1

Type RM Length L Ch R = 1,57430,582,582,582
BEGIN DESCRIPTION:
GLADE CREEK 51.0
END DESCRIPTION:
XS GIS Cut Line= 3
      2868074.97      7058174.99      2867625.00      7057975.00
      2867174.98      7058025.00
#Sta/Elev= 30
  4510.4  477.74  4617.7  471.56  4669.7  467.39  4693.0  465.95  4748.0  463.95
  4759.2  463.35  4826.8  461.68  4913.2  460.73  4941.8  461.15  4970.7  462.02
  4980.9  460.95  4988.4  457.15  4993.9  457.22  4996.3  453.00  4996.9  452.20
  5003.2  452.20  5003.8  453.00  5005.3  453.00  5012.9  457.80  5022.9  460.83
  5033.0  462.60  5040.8  463.35  5083.3  466.45  5163.8  473.63  5183.9  475.03
  5224.2  475.82  5274.5  475.35  5334.8  475.51  5425.4  476.56  5455.6  476.23
#Mann=6,-1,0
  4510.4    0.05       0  4748.0    0.16       0  4826.8    0.05       0
  4941.8    0.16       0  4996.3    0.07       0  5003.8    0.16       0
Bank Sta=4759.2,5040.8
Exp/Cntr=0.3,0.1

Type RM Length L Ch R = 1,56848,591,591,591
BEGIN DESCRIPTION:
GLADE CREEK 50.0
END DESCRIPTION:
XS GIS Cut Line= 3
      2868124.98      7057425.00      2867475.00      7057475.00
      2867024.97      7057525.00
#Sta/Elev= 30
  4358.5  476.75  4408.6  474.54  4488.9  468.15  4569.1  463.90  4579.1  463.21
  4588.0  461.41  4609.2  456.59  4619.2  462.37  4640.7  462.65  4739.6  460.38
  4881.9  459.22  4920.1  459.99  4960.3  458.98  4980.3  459.79  4990.3  458.08
  4996.6  451.36  4997.2  450.56  5003.5  450.56  5004.1  451.36  5007.9  452.66
  5012.9  452.66  5020.5  459.84  5029.5  461.41  5111.0  465.66  5151.3  468.85
  5181.4  469.55  5201.6  472.26  5211.6  472.90  5279.5  475.54  5463.2  479.95
#Mann=6,-1,0
  4358.5    0.05       0  4640.7    0.16       0  4881.9    0.12       0
  4996.6    0.07       0  5004.1    0.12       0  5279.5    0.16       0
Bank Sta=4588,5029.5
Exp/Cntr=0.3,0.1

Type RM Length L Ch R = 1,56257,518,518,518
BEGIN DESCRIPTION:
GLADE CREEK 49.0
END DESCRIPTION:
XS GIS Cut Line= 3
      2868225.01      7057125.00      2867475.00      7056925.00
      2867075.02      7057174.99
#Sta/Elev= 30
  4239.5  481.25  4436.2  474.16  4687.8  460.01  4802.9  458.42  4964.0  458.80
  4974.3  458.52  4976.4  457.43  4984.7  453.05  4993.1  451.69  4994.3  450.72
  4995.0  449.92  5001.6  449.92  5002.2  450.72  5013.1  455.11  5018.7  455.11
  5023.4  457.69  5029.3  455.22  5044.6  455.11  5049.5  457.43  5081.2  461.76
  5123.6  463.08  5133.1  464.33  5139.0  463.88  5175.5  467.22  5196.7  467.57
  5212.1  469.27  5233.3  469.25  5269.9  472.23  5291.1  471.93  5487.4  475.96
#Mann=3,-1,0
  4239.5    0.05       0  4994.3    0.03       0  5002.2    0.05       0
Bank Sta=4976.4,5049.5
Exp/Cntr=0.3,0.1

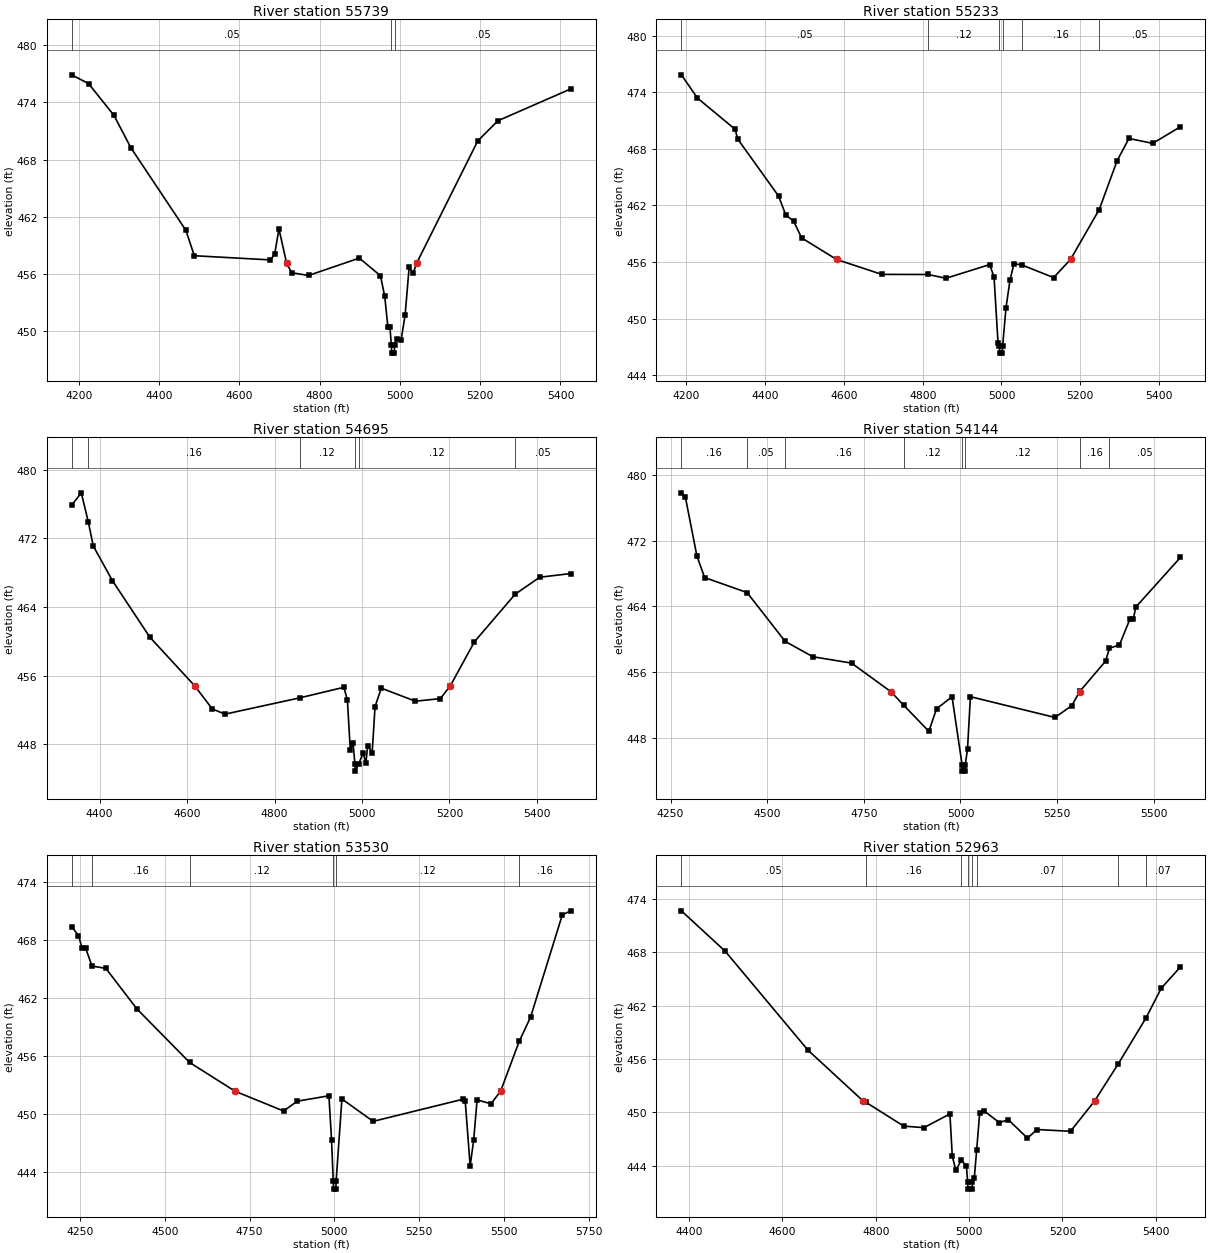
Type RM Length L Ch R = 1,55739,506,506,506
BEGIN DESCRIPTION:
GLADE CREEK 48.0
END DESCRIPTION:
XS GIS Cut Line= 3
      2868175.04      7056725.01      2867425.00      7056475.00
      2866974.98      7056525.00
#Sta/Elev= 30
  4182.0  476.89  4224.2  475.97  4287.5  472.64  4329.6  469.25  4466.6  460.60
  4487.7  457.93  4677.5  457.49  4688.0  458.11  4698.5  460.74  4717.7  457.15
  4730.2  456.15  4772.3  455.86  4898.8  457.68  4951.5  455.83  4962.1  453.68
  4970.0  450.44  4975.1  450.44  4978.7  448.52  4979.4  447.72  4986.0  447.72
  4986.6  448.52  4992.7  449.25  5002.8  449.08  5012.9  451.70  5022.9  456.71
  5033.0  456.11  5041.6  457.15  5194.0  469.97  5244.3  472.08  5425.4  475.41
#Mann=3,-1,0
  4182.0    0.05       0  4978.7    0.03       0  4986.6    0.05       0
Bank Sta=4717.7,5041.6
Exp/Cntr=0.3,0.1

Type RM Length L Ch R = 1,55233,538,538,538
BEGIN DESCRIPTION:
GLADE CREEK 47.0
END DESCRIPTION:
XS GIS Cut Line= 3
      2868375.05      7055874.99      2867575.00      7056025.00
      2867124.96      7056075.00
#Sta/Elev= 30
  4187.5  475.84  4228.2  473.38  4324.1  470.06  4330.0  469.06  4434.3  462.99
  4452.1  461.02  4472.4  460.33  4492.8  458.56  4581.5  456.28  4696.3  454.70
  4813.5  454.69  4859.0  454.29  4970.1  455.74  4981.1  454.41  4991.3  447.40
  4994.8  447.16  4995.5  446.36  5002.3  446.36  5003.0  447.16  5011.5  451.19
  5021.6  454.09  5031.7  455.84  5052.5  455.69  5132.3  454.36  5175.2  456.28
  5248.1  461.57  5293.3  466.72  5323.5  469.10  5383.8  468.58  5454.3  470.34
#Mann=6,-1,0
  4187.5    0.05       0  4813.5    0.12       0  4994.8    0.07       0
  5003.0    0.12       0  5052.5    0.16       0  5248.1    0.05       0
Bank Sta=4581.5,5175.2
Exp/Cntr=0.3,0.1

Type RM Length L Ch R = 1,54695,551,551,551
BEGIN DESCRIPTION:
GLADE CREEK 46.0
END DESCRIPTION:
XS GIS Cut Line= 3
      2868075.03      7055174.98      2867525.00      7055575.00
      2867224.99      7055925.01
#Sta/Elev= 30
  4336.1  475.85  4358.2  477.30  4374.3  473.90  4385.6  471.10  4429.3  467.07
  4515.0  460.47  4617.2  454.82  4657.6  452.12  4686.6  451.50  4857.7  453.40
  4958.6  454.63  4966.7  453.14  4973.3  447.29  4979.5  448.18  4983.9  445.66
  4984.6  444.86  4992.1  445.66  5002.7  446.97  5008.9  445.81  5013.1  447.82
  5023.3  447.02  5029.9  452.38  5044.2  454.53  5122.1  453.01  5179.2  453.31
  5202.2  454.82  5257.1  459.94  5350.2  465.48  5406.4  467.46  5477.2  467.89
#Mann=6,-1,0
  4336.1    0.05       0  4374.3    0.16       0  4857.7    0.12       0
  4983.9    0.07       0  4992.1    0.12       0  5350.2    0.05       0
Bank Sta=4617.2,5202.2
Exp/Cntr=0.3,0.1

Type RM Length L Ch R = 1,54144,614,614,614
BEGIN DESCRIPTION:
GLADE CREEK 45.0
END DESCRIPTION:
XS GIS Cut Line= 3
      2868025.00      7055125.00      2867275.00      7055125.00
      2866975.02      7055574.97
#Sta/Elev= 30
  4278.2  477.82  4288.2  477.36  4318.2  470.16  4338.2  467.51  4448.1  465.68
  4546.4  459.75  4618.2  457.87  4718.2  457.10  4820.0  453.62  4852.7  451.99
  4918.2  448.80  4938.2  451.54  4978.2  453.00  5004.1  444.75  5004.8  443.95
  5011.7  443.95  5012.4  444.75  5018.2  446.61  5025.7  453.01  5244.5  450.48
  5288.1  451.93  5308.1  453.62  5309.1  453.68  5375.2  457.33  5385.4  458.90
  5411.3  459.32  5438.3  462.45  5447.3  462.52  5453.4  463.91  5569.0  469.96
#Mann=8,-1,0
  4278.2    0.16       0  4448.1    0.05       0  4546.4    0.16       0
  4852.7    0.12       0  5004.1    0.07       0  5012.4    0.12       0
  5309.1    0.16       0  5385.4    0.05       0
Bank Sta=4820,5308.1
Exp/Cntr=0.3,0.1

Type RM Length L Ch R = 1,53530,567,567,567
BEGIN DESCRIPTION:
GLADE CREEK 44.0
END DESCRIPTION:
XS GIS Cut Line= 3
      2867774.99      7054575.00      2867025.00      7054675.00
      2866325.02      7054525.00
#Sta/Elev= 30
  4224.9  469.41  4245.1  468.48  4255.2  467.24  4266.5  467.15  4285.1  465.32
  4325.8  465.08  4417.8  460.87  4573.1  455.33  4707.3  452.35  4850.4  450.30
  4890.7  451.32  4984.1  451.88  4991.8  447.32  4996.9  443.01  4997.7  442.21
  5004.6  442.21  5005.3  443.01  5022.4  451.55  5114.5  449.23  5380.4  451.53
  5386.3  451.31  5400.8  444.61  5411.1  447.27  5421.3  451.46  5462.2  451.05
  5490.6  452.35  5545.8  457.54  5579.0  460.02  5672.7  470.62  5697.4  471.04
#Mann=6,-1,0
  4224.9    0.05       0  4285.1    0.16       0  4573.1    0.12       0
  4996.9    0.07       0  5005.3    0.12       0  5545.8    0.16       0
Bank Sta=4707.3,5490.6
Exp/Cntr=0.3,0.1

Type RM Length L Ch R = 1,52963,537,537,537
BEGIN DESCRIPTION:
GLADE CREEK 43.0
END DESCRIPTION:
XS GIS Cut Line= 3
      2867875.01      7054325.00      2867275.00      7054225.00
      2866824.97      7054124.99
#Sta/Elev= 30
  4383.7  472.65  4477.5  468.11  4654.9  456.99  4773.0  451.28  4779.4  451.12
  4860.2  448.45  4903.3  448.28  4959.0  449.82  4964.1  445.07  4971.7  443.48
  4983.5  444.64  4994.5  443.92  4997.0  442.17  4997.9  441.37  5006.5  441.37
  5007.4  442.17  5011.2  442.59  5016.4  445.80  5022.7  449.89  5033.0  450.13
  5065.0  448.85  5084.2  449.17  5125.2  447.10  5145.6  448.07  5217.4  447.87
  5269.1  451.28  5319.8  455.46  5378.6  460.56  5412.0  463.96  5453.0  466.35
#Mann=8,-1,0
  4383.7    0.05       0  4779.4    0.16       0  4983.5    0.12       0
  4997.0    0.07       0  5007.4    0.12       0  5016.4    0.07       0
  5319.8    0.16       0  5378.6    0.07       0
Bank Sta=4773,5269.1
Exp/Cntr=0.3,0.1

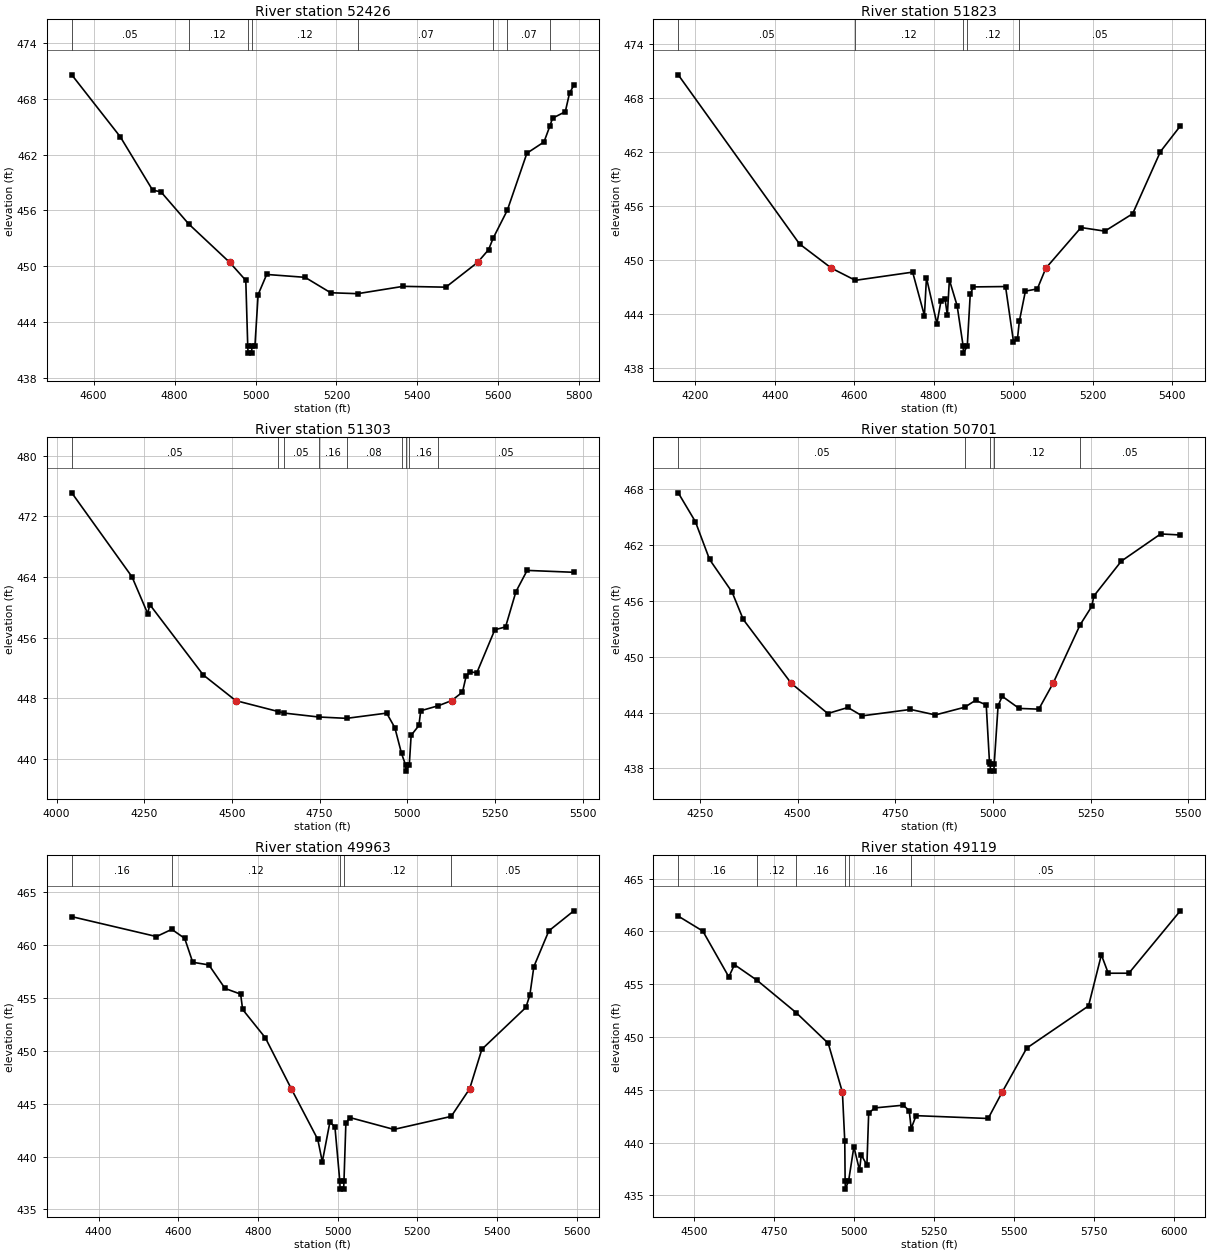
Type RM Length L Ch R = 1,52426,603,603,603
BEGIN DESCRIPTION:
GLADE CREEK 42.0
END DESCRIPTION:
XS GIS Cut Line= 3
      2868025.01      7053825.00      2867575.00      7053825.00
      2866824.98      7054075.01
#Sta/Elev= 30
  4545.9  470.60  4665.9  463.92  4745.9  458.17  4765.9  458.02  4834.7  454.55
  4936.3  450.40  4975.9  448.47  4980.7  441.44  4981.6  440.64  4990.3  440.64
  4991.1  441.44  4998.5  441.44  5006.4  446.94  5027.5  449.11  5122.4  448.80
  5185.6  447.14  5252.2  447.04  5364.8  447.83  5470.2  447.74  5548.5  450.40
  5575.7  451.77  5587.4  453.04  5622.1  456.02  5670.5  462.16  5712.7  463.37
  5727.3  465.09  5733.8  465.93  5765.4  466.63  5775.9  468.64  5786.5  469.48
#Mann=8,-1,0
  4545.9    0.05       0  4834.7    0.12       0  4980.7    0.07       0
  4991.1    0.12       0  5252.2    0.07       0  5587.4    0.16       0
  5622.1    0.07       0  5727.3    0.05       0
Bank Sta=4936.3,5548.5
Exp/Cntr=0.3,0.1

Type RM Length L Ch R = 1,51823,520,520,520
BEGIN DESCRIPTION:
GLADE CREEK 41.0
END DESCRIPTION:
XS GIS Cut Line= 3
      2868075.03      7053625.01      2867275.00      7053475.00
      2866824.97      7053475.00
#Sta/Elev= 30
  4156.9  470.56  4462.2  451.79  4542.6  449.10  4602.8  447.75  4747.0  448.66
  4776.7  443.83  4781.8  448.03  4808.1  442.95  4818.3  445.43  4828.4  445.70
  4834.4  443.91  4839.5  447.80  4859.0  444.94  4874.1  440.47  4875.0  439.67
  4884.6  440.47  4892.0  446.18  4899.7  447.02  4980.9  447.06  5000.9  440.95
  5010.9  441.25  5015.6  443.20  5030.9  446.55  5060.9  446.80  5082.4  449.10
  5170.9  453.61  5230.9  453.21  5300.9  455.14  5370.9  462.04  5420.9  464.88
#Mann=5,-1,0
  4156.9    0.05       0  4602.8    0.12       0  4874.1    0.07       0
  4884.6    0.12       0  5015.6    0.05       0
Bank Sta=4542.6,5082.4
Exp/Cntr=0.3,0.1

Type RM Length L Ch R = 1,51303,602,602,602
BEGIN DESCRIPTION:
GLADE CREEK 40.0
END DESCRIPTION:
XS GIS Cut Line= 3
      2868174.98      7053574.98      2867375.00      7053025.00
      2866924.97      7052924.99
#Sta/Elev= 30
  4043.3  475.11  4215.1  464.03  4259.8  459.19  4265.8  460.37  4418.1  451.10
  4510.9  447.71  4632.7  446.26  4648.1  446.07  4747.1  445.55  4826.9  445.37
  4941.3  446.06  4964.7  444.13  4983.7  440.74  4995.3  439.21  4996.2  438.41
  5005.8  439.21  5011.1  443.13  5033.3  444.43  5038.4  446.37  5089.1  447.04
  5126.6  447.71  5157.5  448.83  5167.8  450.90  5179.3  451.50  5198.5  451.38
  5249.7  457.05  5280.4  457.43  5309.9  462.07  5341.9  464.88  5475.1  464.63
#Mann=9,-1,0
  4043.3    0.05       0  4632.7    0.16       0  4648.1    0.05       0
  4747.1    0.16       0  4826.9    0.08       0  4983.7    0.16       0
  4995.3    0.07       0  5005.8    0.16       0  5089.1    0.05       0
Bank Sta=4510.9,5126.6
Exp/Cntr=0.3,0.1

Type RM Length L Ch R = 1,50701,738,738,738
BEGIN DESCRIPTION:
GLADE CREEK 39.0
END DESCRIPTION:
XS GIS Cut Line= 3
      2868174.99      7052925.00      2867475.00      7052475.00
      2867025.03      7052525.00
#Sta/Elev= 30
  4194.4  467.62  4238.3  464.52  4274.6  460.46  4332.1  456.96  4360.8  454.01
  4483.6  447.15  4577.1  443.90  4628.6  444.55  4665.0  443.65  4788.8  444.34
  4852.5  443.75  4927.7  444.58  4955.2  445.32  4982.6  444.83  4990.9  438.68
  4992.6  438.51  4993.5  437.71  5002.2  437.71  5003.1  438.51  5013.0  444.76
  5023.6  445.75  5066.8  444.45  5117.1  444.37  5153.7  447.15  5222.7  453.42
  5252.9  455.43  5258.0  456.53  5328.4  460.28  5429.0  463.20  5479.3  463.09
#Mann=5,-1,0
  4194.4    0.05       0  4927.7    0.12       0  4992.6    0.07       0
  5003.1    0.12       0  5222.7    0.05       0
Bank Sta=4483.6,5153.7
Exp/Cntr=0.3,0.1

Type RM Length L Ch R = 1,49963,844,844,844
BEGIN DESCRIPTION:
GLADE CREEK 38.0
END DESCRIPTION:
XS GIS Cut Line= 3
      2867975.00      7051725.00      2867325.00      7051825.00
      2866725.02      7051875.00
#Sta/Elev= 30
  4332.9  462.66  4545.4  460.78  4583.8  461.46  4616.2  460.61  4636.4  458.35
  4676.9  458.10  4717.4  455.88  4756.6  455.34  4761.6  453.89  4818.5  451.22
  4883.7  446.40  4950.1  441.62  4961.5  439.50  4980.4  443.23  4993.1  442.82
  5005.3  437.72  5006.2  436.92  5015.0  436.92  5015.9  437.72  5020.6  443.14
  5030.7  443.68  5141.1  442.56  5284.9  443.79  5331.2  446.40  5361.8  450.13
  5472.2  454.08  5482.2  455.25  5492.3  457.94  5529.9  461.32  5592.6  463.21
#Mann=5,-1,0
  4332.9    0.16       0  4583.8    0.12       0  5005.3    0.07       0
  5015.9    0.12       0  5284.9    0.05       0
Bank Sta=4883.7,5331.2
Exp/Cntr=0.3,0.1

Type RM Length L Ch R = 1,49119,754,754,754
BEGIN DESCRIPTION:
GLADE CREEK 37.0
END DESCRIPTION:
XS GIS Cut Line= 3
      2867875.01      7051475.00      2867325.00      7051225.00
      2866425.02      7050875.01
#Sta/Elev= 30
  4451.0  461.45  4527.9  460.03  4609.2  455.69  4626.8  456.85  4697.4  455.37
  4819.9  452.30  4920.0  449.40  4964.3  444.77  4971.7  440.13  4972.8  436.39
  4973.6  435.59  4983.8  436.39  5000.2  439.60  5017.8  437.38  5023.3  438.83
  5040.9  437.87  5046.4  442.76  5064.7  443.28  5154.4  443.54  5173.2  443.03
  5179.3  441.33  5194.6  442.55  5420.0  442.28  5463.7  444.77  5540.7  448.95
  5733.8  452.94  5774.0  457.78  5795.5  456.04  5859.9  456.04  6020.8  461.95
#Mann=6,-1,0
  4451.0    0.16       0  4697.4    0.12       0  4819.9    0.16       0
  4972.8    0.07       0  4983.8    0.16       0  5179.3    0.05       0
Bank Sta=4964.3,5463.7
Exp/Cntr=0.3,0.1