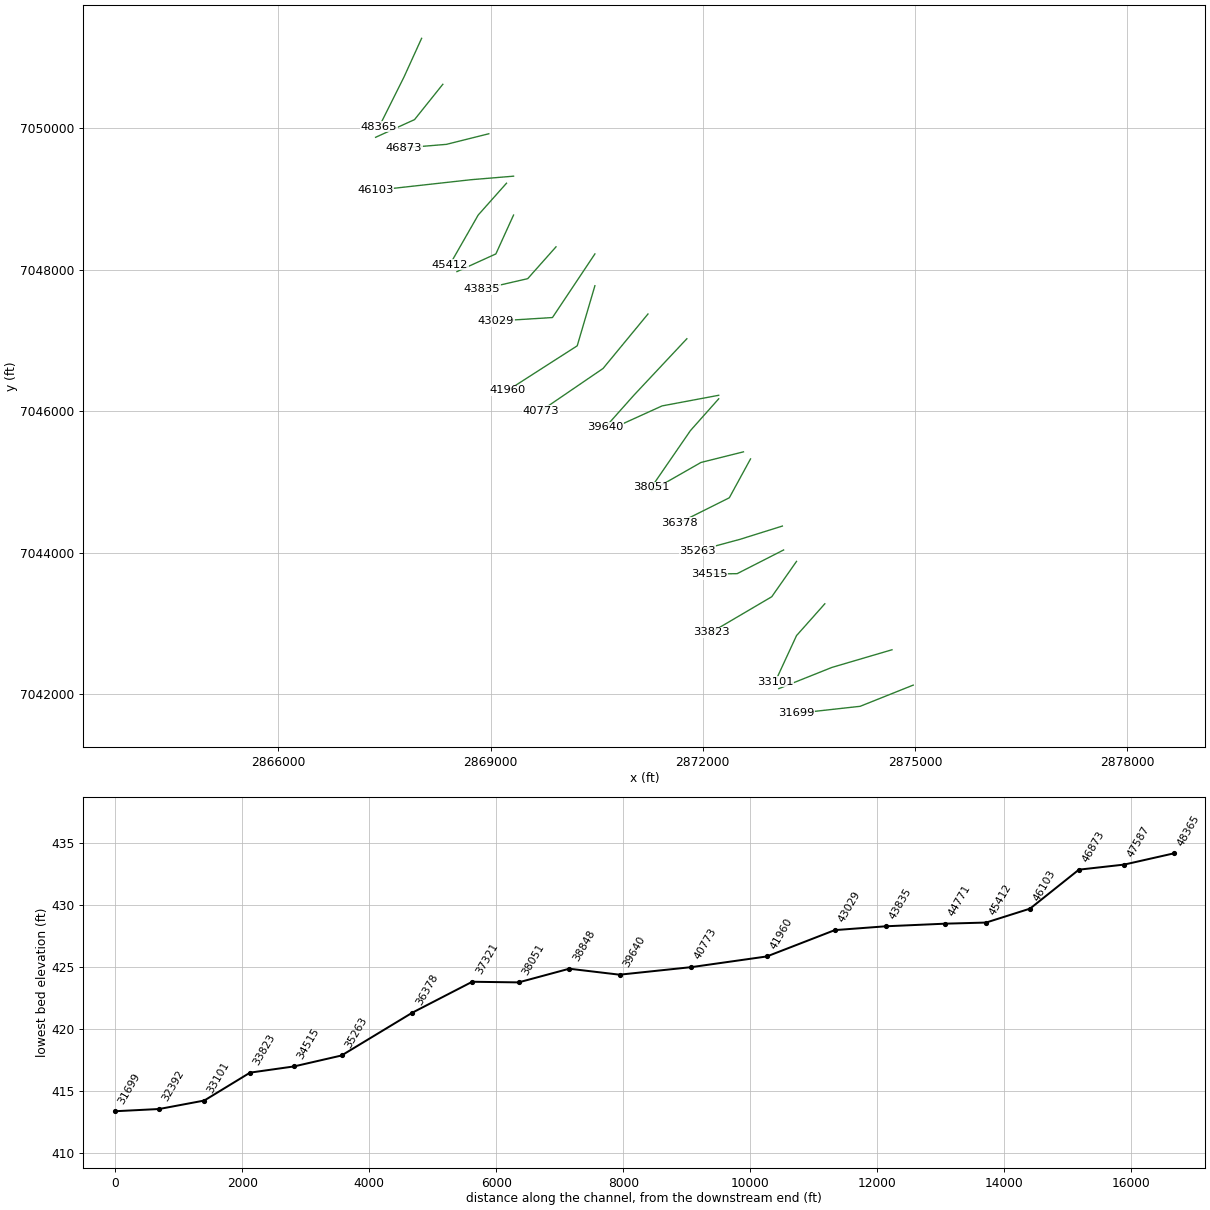
HEC-RAS study GLADE CREEK.prj: GLADE CREEK Base Level Engineering

--- GLADE CREEK.g01 (geometry) --- (continued)

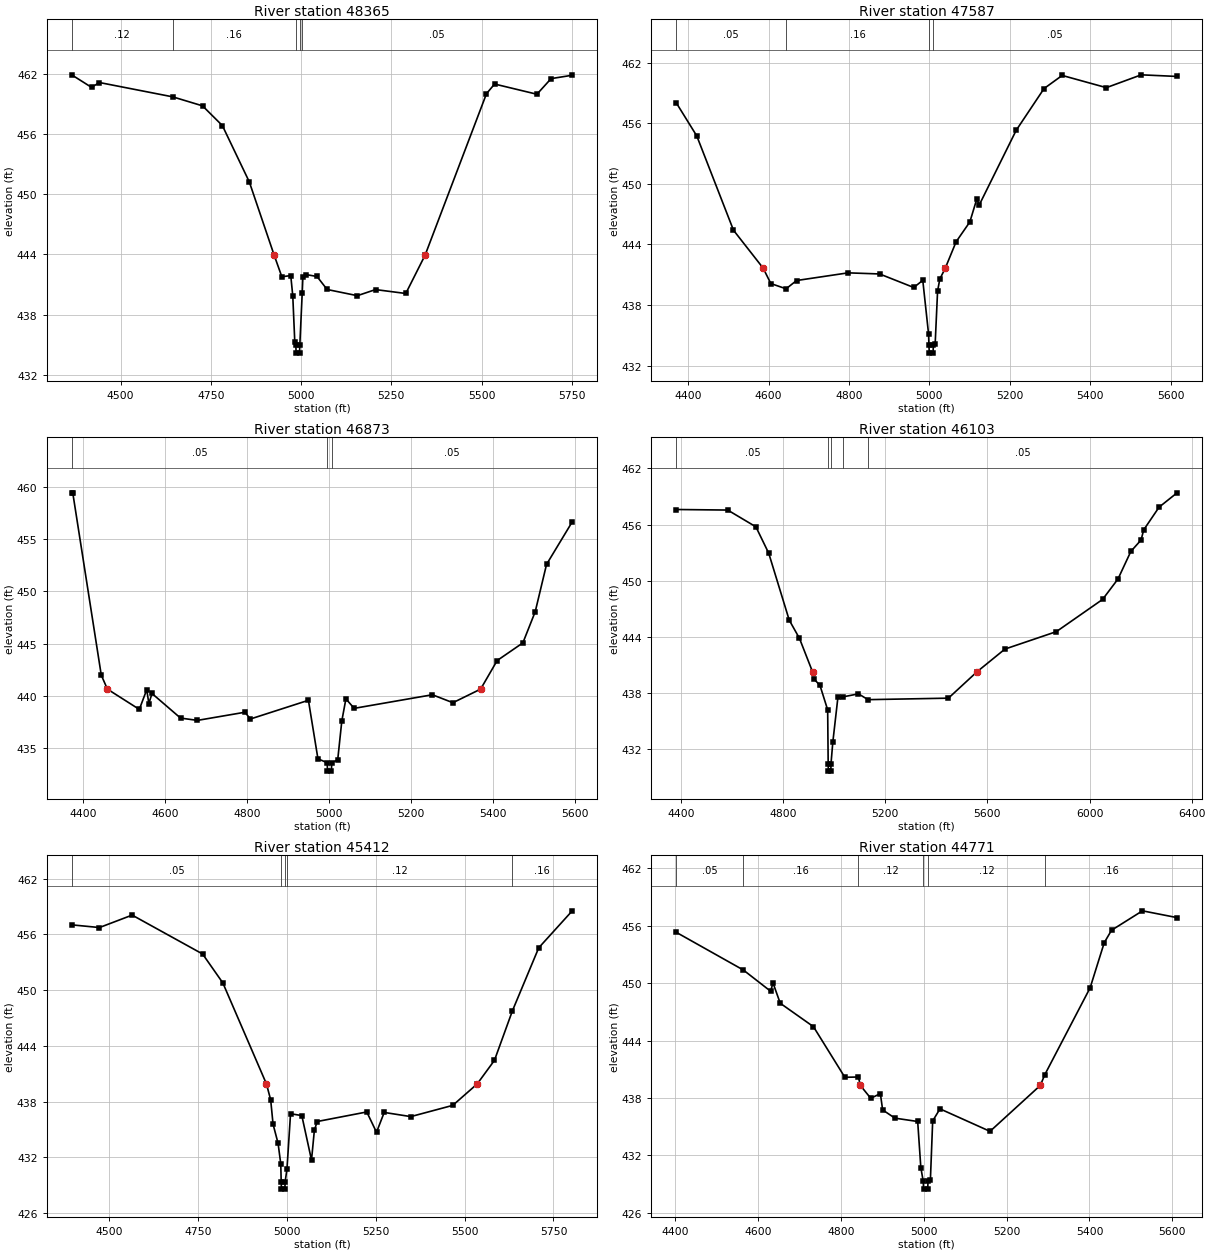
Type RM Length L Ch R = 1,48365,778,778,778
BEGIN DESCRIPTION:
GLADE CREEK 36.0
END DESCRIPTION:
XS GIS Cut Line= 3
      2868025.00      7051275.00      2867775.00      7050725.00
      2867424.99      7050024.98
#Sta/Elev= 30
  4364.5  461.95  4419.4  460.70  4441.4  461.18  4644.3  459.75  4727.0  458.85
  4781.9  456.88  4856.6  451.25  4925.3  443.94  4946.7  441.77  4971.4  441.89
  4977.0  439.86  4982.6  435.23  4985.5  434.94  4986.3  434.14  4995.7  434.14
  4996.5  434.94  5003.1  440.10  5005.0  441.75  5013.4  441.99  5044.1  441.80
  5072.1  440.50  5155.9  439.88  5206.2  440.49  5290.1  440.10  5343.7  443.94
  5513.7  460.07  5536.1  461.03  5653.4  460.01  5692.6  461.57  5751.3  461.91
#Mann=5,-1,0
  4364.5    0.12       0  4644.3    0.16       0  4985.5    0.07       0
  4996.5    0.16       0  5003.1    0.05       0
Bank Sta=4925.3,5343.7
Exp/Cntr=0.3,0.1

Type RM Length L Ch R = 1,47587,714,714,714
BEGIN DESCRIPTION:
GLADE CREEK 35.0
END DESCRIPTION:
XS GIS Cut Line= 3
      2868325.00      7050625.00      2867925.00      7050125.00
      2867374.97      7049874.98
#Sta/Elev= 30
  4371.2  457.99  4421.6  454.75  4512.9  445.41  4586.6  441.66  4605.7  440.13
  4643.7  439.61  4669.7  440.43  4797.8  441.19  4876.2  441.08  4961.1  439.74
  4983.5  440.45  4997.9  435.13  4998.8  434.04  4999.6  433.24  5009.1  433.24
  5009.8  434.04  5014.3  434.17  5020.3  439.38  5025.8  440.57  5039.5  441.66
  5066.4  444.27  5100.5  446.23  5118.1  448.54  5123.6  447.89  5215.8  455.31
  5285.0  459.44  5330.1  460.74  5439.9  459.53  5526.7  460.80  5615.7  460.64
#Mann=4,-1,0
  4371.2    0.05       0  4643.7    0.16       0  4998.8    0.07       0
  5009.8    0.05       0
Bank Sta=4586.6,5039.5
Exp/Cntr=0.3,0.1

Type RM Length L Ch R = 1,46873,770,770,770
BEGIN DESCRIPTION:
GLADE CREEK 34.0
END DESCRIPTION:
XS GIS Cut Line= 3
      2868974.99      7049925.00      2868375.00      7049775.00
      2867775.04      7049725.00
#Sta/Elev= 30
  4372.2  459.43  4374.8  459.43  4444.3  442.01  4459.2  440.67  4537.1  438.73
  4555.2  440.62  4560.3  439.29  4568.0  440.25  4637.6  437.90  4678.8  437.68
  4794.8  438.46  4807.7  437.81  4949.4  439.60  4972.6  434.01  4995.2  433.63
  4995.9  432.83  5005.4  432.83  5006.2  433.63  5020.8  433.91  5030.8  437.62
  5040.8  439.74  5060.9  438.83  5251.6  440.13  5301.7  439.37  5369.3  440.67
  5409.6  443.40  5472.3  445.09  5502.4  448.07  5530.0  452.59  5592.7  456.66
#Mann=3,-1,0
  4372.2    0.05       0  4995.2    0.03       0  5006.2    0.05       0
Bank Sta=4459.2,5369.3
Exp/Cntr=0.3,0.1

Type RM Length L Ch R = 1,46103,691,691,691
BEGIN DESCRIPTION:
GLADE CREEK 33.0
END DESCRIPTION:
XS GIS Cut Line= 3
      2869324.96      7049325.00      2868725.00      7049275.00
      2867375.04      7049125.00
#Sta/Elev= 30
  4382.6  457.62  4583.2  457.56  4693.6  455.77  4743.8  452.95  4824.1  445.81
  4864.2  443.86  4915.4  440.29  4921.9  439.50  4944.5  438.84  4974.6  436.23
  4976.6  430.49  4977.3  429.69  4987.0  429.69  4987.7  430.49  4994.7  432.77
  5014.8  437.59  5033.3  437.61  5095.3  437.94  5132.7  437.32  5447.5  437.48
  5559.2  440.29  5668.8  442.72  5870.1  444.58  6051.2  448.02  6111.5  450.20
  6161.8  453.14  6202.1  454.37  6212.1  455.44  6272.5  457.87  6342.9  459.40
#Mann=5,-1,0
  4382.6    0.05       0  4976.6    0.03       0  4987.7    0.05       0
  5033.3    0.16       0  5132.7    0.05       0
Bank Sta=4915.4,5559.2
Exp/Cntr=0.3,0.1

Type RM Length L Ch R = 1,45412,641,641,641
BEGIN DESCRIPTION:
GLADE CREEK 32.0
END DESCRIPTION:
XS GIS Cut Line= 3
      2869224.97      7049224.97      2868825.00      7048775.00
      2868424.98      7048074.97
#Sta/Elev= 30
  4394.6  457.03  4472.7  456.74  4564.7  458.08  4762.9  453.89  4819.8  450.78
  4942.5  439.90  4954.4  438.19  4961.1  435.57  4975.3  433.49  4982.8  431.29
  4984.0  429.37  4984.7  428.57  4994.4  428.57  4995.1  429.37  5000.2  430.70
  5010.3  436.69  5042.0  436.49  5069.3  431.70  5077.3  434.89  5085.2  435.85
  5224.8  436.88  5252.2  434.69  5273.8  436.83  5348.6  436.38  5466.7  437.59
  5535.5  439.90  5584.0  442.44  5634.6  447.78  5708.6  454.56  5802.9  458.54
#Mann=5,-1,0
  4394.6    0.05       0  4984.0    0.03       0  4995.1    0.05       0
  5000.2    0.12       0  5634.6    0.16       0
Bank Sta=4942.5,5535.5
Exp/Cntr=0.3,0.1

Type RM Length L Ch R = 1,44771,936,936,936
BEGIN DESCRIPTION:
GLADE CREEK 31.0
END DESCRIPTION:
XS GIS Cut Line= 3
      2869324.99      7048774.97      2869075.00      7048225.00
      2868524.98      7047974.99
#Sta/Elev= 30
  4403.1  455.31  4564.6  451.38  4630.5  449.16  4635.9  450.05  4653.5  447.91
  4733.7  445.46  4809.5  440.17  4842.1  440.20  4846.9  439.32  4872.1  437.97
  4895.2  438.47  4900.7  436.76  4930.3  435.90  4985.3  435.55  4992.9  430.72
  4998.8  429.28  4999.5  428.48  5009.5  428.48  5010.2  429.28  5016.0  429.47
  5021.5  435.61  5039.1  436.87  5159.9  434.52  5281.3  439.32  5292.1  440.44
  5401.6  449.53  5435.6  454.24  5453.2  455.54  5527.9  457.57  5611.4  456.86
#Mann=6,-1,0
  4403.1    0.05       0  4564.6    0.16       0  4842.1    0.12       0
  4998.8    0.07       0  5010.2    0.12       0  5292.1    0.16       0
Bank Sta=4846.9,5281.3
Exp/Cntr=0.3,0.1

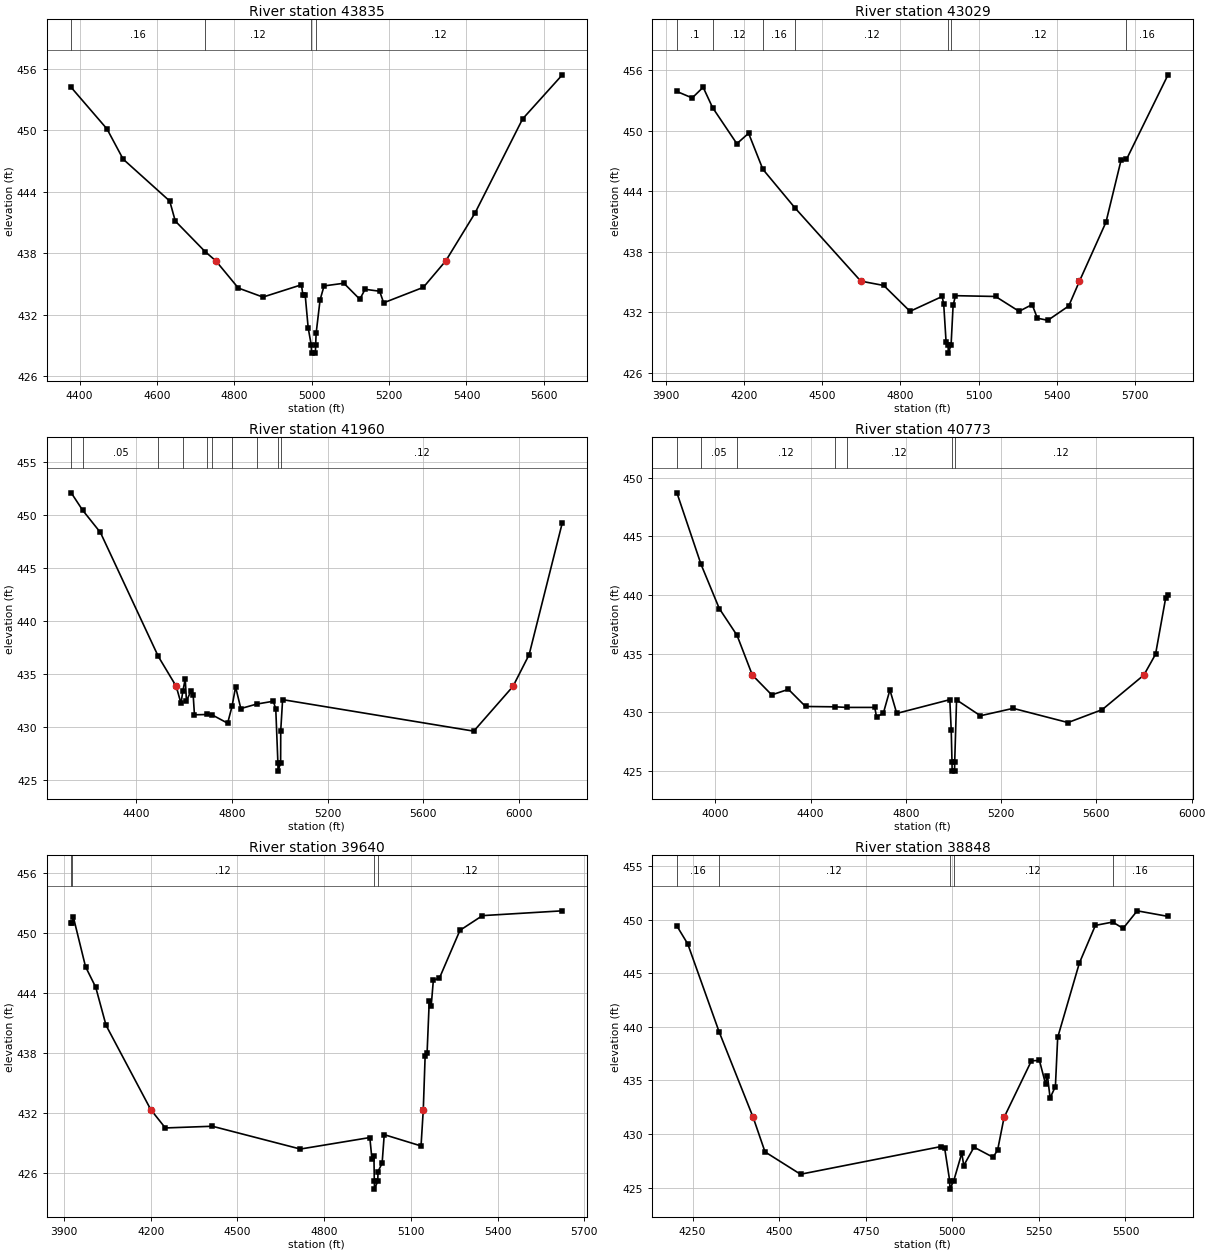
Type RM Length L Ch R = 1,43835,806,806,806
BEGIN DESCRIPTION:
GLADE CREEK 30.0
END DESCRIPTION:
XS GIS Cut Line= 3
      2869925.01      7048325.01      2869525.00      7047875.00
      2868874.98      7047725.00
#Sta/Elev= 30
  4378.5  454.20  4470.9  450.15  4512.7  447.20  4633.1  443.11  4647.4  441.16
  4724.4  438.18  4752.4  437.27  4810.4  434.62  4874.0  433.74  4973.5  434.94
  4977.3  433.93  4983.2  433.93  4990.9  430.73  4998.8  429.07  4999.5  428.27
  5009.5  428.27  5010.2  429.07  5011.4  430.19  5021.6  433.46  5031.9  434.83
  5083.2  435.09  5124.3  433.53  5138.0  434.50  5175.6  434.31  5185.9  433.18
  5288.5  434.69  5346.4  437.27  5421.9  441.93  5545.1  451.13  5647.7  455.43
#Mann=4,-1,0
  4378.5    0.16       0  4724.4    0.12       0  4998.8    0.07       0
  5010.2    0.12       0
Bank Sta=4752.4,5346.4
Exp/Cntr=0.3,0.1

Type RM Length L Ch R = 1,43029,1069,1069,1069
BEGIN DESCRIPTION:
GLADE CREEK 29.0
END DESCRIPTION:
XS GIS Cut Line= 3
      2870474.99      7048224.99      2869875.00      7047325.00
      2869075.02      7047275.00
#Sta/Elev= 30
  3943.2  453.87  4001.8  453.23  4043.8  454.29  4079.9  452.28  4173.0  448.70
  4218.1  449.73  4272.7  446.17  4395.6  442.35  4648.3  435.09  4736.4  434.66
  4837.1  432.10  4960.3  433.57  4966.3  432.80  4975.3  429.09  4983.1  428.76
  4983.8  427.96  4994.5  428.76  5002.3  432.68  5011.3  433.65  5165.1  433.57
  5255.3  432.10  5305.4  432.77  5325.4  431.42  5365.5  431.21  5445.7  432.63
  5486.9  435.09  5588.5  440.93  5646.1  447.04  5667.0  447.14  5826.4  455.52
#Mann=7,-1,0
  3943.2     0.1       0  4079.9    0.12       0  4272.7    0.16       0
  4395.6    0.12       0  4983.1    0.07       0  4994.5    0.12       0
  5667.0    0.16       0
Bank Sta=4648.3,5486.9
Exp/Cntr=0.3,0.1

Type RM Length L Ch R = 1,41960,1187,1187,1187
BEGIN DESCRIPTION:
GLADE CREEK 28.0
END DESCRIPTION:
XS GIS Cut Line= 3
      2870475.01      7047775.03      2870225.00      7046925.00
      2869243.53      7046294.81
#Sta/Elev= 30
  4128.7  452.08  4176.1  450.45  4250.7  448.34  4492.7  436.65  4567.6  433.83
  4587.4  432.23  4595.4  433.40  4605.1  434.54  4610.3  432.44  4629.1  433.41
  4638.4  433.01  4643.7  431.15  4698.1  431.18  4715.4  431.17  4782.3  430.36
  4800.7  431.94  4815.6  433.78  4837.5  431.74  4903.4  432.16  4973.0  432.43
  4983.5  431.72  4992.4  426.64  4993.0  425.84  5003.8  426.64  5004.3  429.67
  5012.1  432.58  5811.0  429.61  5974.9  433.83  6042.3  436.82  6181.1  449.27
#Mann=10,-1,0
  4128.7    0.12       0  4176.1    0.05       0  4492.7    0.16       0
  4595.4    0.07       0  4698.1    0.16       0  4715.4    0.07       0
  4800.7    0.16       0  4903.4    0.12       0  4992.4    0.07       0
  5003.8    0.12       0
Bank Sta=4567.6,5974.9
Exp/Cntr=0.3,0.1

Type RM Length L Ch R = 1,40773,1133,1133,1133
BEGIN DESCRIPTION:
GLADE CREEK 27.0
END DESCRIPTION:
XS GIS Cut Line= 3
      2871224.99      7047374.99      2870590.08      7046604.03
      2869711.72      7046004.16
#Sta/Elev= 30
  3838.3  448.70  3939.5  442.61  4016.2  438.84  4090.9  436.55  4155.0  433.17
  4236.4  431.48  4306.7  431.95  4378.4  430.49  4503.5  430.46  4551.3  430.41
  4669.0  430.41  4676.9  429.58  4705.5  429.94  4732.8  431.90  4761.5  429.90
  4984.3  431.07  4990.3  428.45  4993.5  425.78  4994.1  424.98  5004.3  424.98
  5004.9  425.78  5012.7  431.05  5112.9  429.70  5250.4  430.33  5480.7  429.12
  5624.3  430.22  5799.4  433.17  5848.3  434.94  5890.5  439.70  5900.7  440.03
#Mann=7,-1,0
  3838.3    0.12       0  3939.5    0.05       0  4090.9    0.12       0
  4503.5    0.16       0  4551.3    0.12       0  4993.5    0.07       0
  5004.9    0.12       0
Bank Sta=4155,5799.4
Exp/Cntr=0.3,0.1

Type RM Length L Ch R = 1,39640,792,792,792
BEGIN DESCRIPTION:
GLADE CREEK 26.0
END DESCRIPTION:
XS GIS Cut Line= 3
      2871774.98      7047024.98      2871025.00      7046225.00
      2870625.02      7045775.03
#Sta/Elev= 30
  3925.0  450.97  3928.3  450.97  3932.1  451.62  3974.5  446.62  4009.7  444.57
  4045.4  440.76  4200.0  432.33  4250.5  430.49  4413.2  430.66  4717.5  428.38
  4957.8  429.53  4965.1  427.38  4972.0  427.73  4973.3  425.17  4973.9  424.37
  4985.2  425.17  4986.1  426.13  5000.3  426.96  5007.6  429.82  5134.9  428.69
  5142.7  432.33  5149.1  437.70  5155.8  437.97  5163.3  443.17  5170.0  442.67
  5177.5  445.28  5198.4  445.47  5269.5  450.26  5347.3  451.73  5623.6  452.21
#Mann=4,-1,0
  3925.0    0.16       0  3928.3    0.12       0  4973.3    0.07       0
  4985.2    0.12       0
Bank Sta=4200,5142.7
Exp/Cntr=0.3,0.1

Type RM Length L Ch R = 1,38848,797,797,797
BEGIN DESCRIPTION:
GLADE CREEK 25.0
END DESCRIPTION:
XS GIS Cut Line= 3
      2872224.99      7046225.00      2871425.00      7046075.00
      2870874.99      7045825.00
#Sta/Elev= 30
  4204.7  449.43  4236.1  447.75  4326.3  439.57  4424.9  431.55  4459.1  428.33
  4561.6  426.24  4967.8  428.83  4977.9  428.66  4992.3  425.65  4992.9  424.85
  5004.2  425.65  5027.4  428.22  5032.9  427.05  5062.6  428.77  5117.5  427.83
  5130.7  428.49  5149.4  431.55  5228.4  436.84  5251.5  436.87  5269.1  434.69
  5274.6  435.46  5282.3  433.37  5297.6  434.43  5304.2  439.02  5366.8  445.97
  5413.0  449.49  5463.0  449.80  5493.2  449.21  5533.8  450.85  5622.8  450.33
#Mann=5,-1,0
  4204.7    0.16       0  4326.3    0.12       0  4992.3    0.07       0
  5004.2    0.12       0  5463.0    0.16       0
Bank Sta=4424.9,5149.4
Exp/Cntr=0.3,0.1

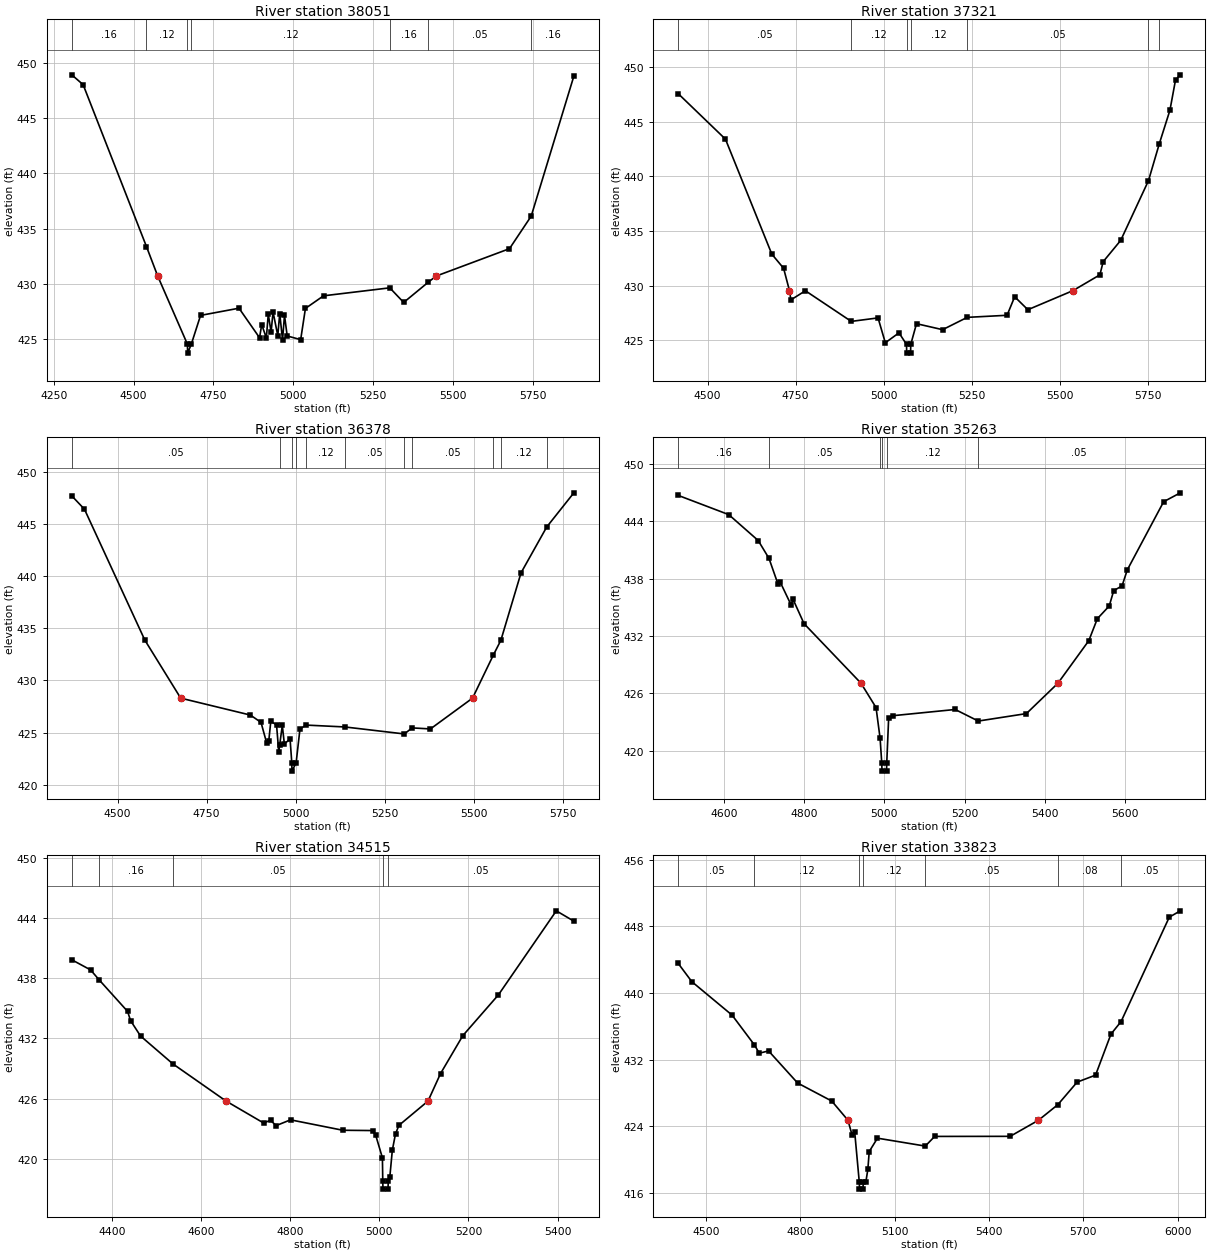
Type RM Length L Ch R = 1,38051,730,730,730
BEGIN DESCRIPTION:
GLADE CREEK 24.0
END DESCRIPTION:
XS GIS Cut Line= 3
      2872225.03      7046175.03      2871825.00      7045725.00
      2871275.03      7044925.04
#Sta/Elev= 30
  4306.1  448.90  4341.7  448.01  4540.1  433.38  4575.4  430.71  4668.5  424.55
  4669.0  423.75  4680.5  424.55  4709.6  427.16  4830.0  427.81  4894.4  425.14
  4901.1  426.33  4915.7  425.12  4921.7  427.28  4930.6  425.64  4936.6  427.48
  4951.5  425.33  4957.6  427.33  4966.4  424.94  4972.5  427.17  4981.0  425.30
  5023.2  424.97  5038.1  427.79  5094.9  428.93  5302.4  429.65  5345.9  428.33
  5423.0  430.16  5447.4  430.71  5677.4  433.19  5745.4  436.13  5879.0  448.78
#Mann=7,-1,0
  4306.1    0.16       0  4540.1    0.12       0  4668.5    0.07       0
  4680.5    0.12       0  5302.4    0.16       0  5423.0    0.05       0
  5745.4    0.16       0
Bank Sta=4575.4,5447.4
Exp/Cntr=0.3,0.1

Type RM Length L Ch R = 1,37321,943,943,943
BEGIN DESCRIPTION:
GLADE CREEK 23.0
END DESCRIPTION:
XS GIS Cut Line= 3
      2872575.04      7045425.01      2871975.00      7045275.00
      2871275.03      7044875.02
#Sta/Elev= 30
  4416.8  447.59  4550.8  443.42  4682.3  432.88  4715.8  431.58  4732.4  429.53
  4736.4  428.68  4777.6  429.52  4907.8  426.71  4983.8  427.03  5004.4  424.75
  5043.2  425.66  5064.6  424.60  5065.1  423.80  5076.1  423.80  5076.6  424.60
  5092.9  426.50  5167.0  425.95  5236.8  427.08  5349.9  427.27  5371.5  428.97
  5408.9  427.78  5536.9  429.53  5613.3  430.98  5622.7  432.19  5672.4  434.14
  5751.2  439.62  5781.8  442.99  5812.0  446.07  5827.9  448.85  5841.5  449.32
#Mann=7,-1,0
  4416.8    0.05       0  4907.8    0.12       0  5064.6    0.07       0
  5076.6    0.12       0  5236.8    0.05       0  5751.2    0.16       0
  5781.8    0.12       0
Bank Sta=4732.4,5536.9
Exp/Cntr=0.3,0.1

Type RM Length L Ch R = 1,36378,1115,1115,1115
BEGIN DESCRIPTION:
GLADE CREEK 22.0
END DESCRIPTION:
XS GIS Cut Line= 3
      2872674.98      7045324.97      2872375.00      7044775.00
      2871674.99      7044424.99
#Sta/Elev= 30
  4371.4  447.67  4407.0  446.39  4576.4  433.86  4677.1  428.30  4872.6  426.68
  4902.5  425.98  4918.1  424.04  4924.3  424.21  4930.0  426.07  4946.1  425.74
  4952.3  423.17  4954.8  423.80  4962.3  425.68  4968.0  423.92  4984.1  424.38
  4988.9  422.11  4989.4  421.31  5001.1  422.11  5011.8  425.33  5028.5  425.72
  5137.9  425.54  5304.9  424.87  5326.4  425.45  5378.0  425.35  5496.2  428.30
  5554.2  432.40  5575.8  433.85  5632.3  440.30  5704.4  444.69  5780.5  447.96
#Mann=11,-1,0
  4371.4    0.05       0  4954.8     0.1       0  4988.9    0.07       0
  5001.1     0.1       0  5028.5    0.12       0  5137.9    0.05       0
  5304.9    0.16       0  5326.4    0.05       0  5554.2    0.16       0
  5575.8    0.12       0  5704.4    0.16       0
Bank Sta=4677.1,5496.2
Exp/Cntr=0.3,0.1

Type RM Length L Ch R = 1,35263,748,748,748
BEGIN DESCRIPTION:
GLADE CREEK 21.0
END DESCRIPTION:
XS GIS Cut Line= 3
      2873125.00      7044375.00      2872527.93      7044187.70
      2871924.96      7044024.99
#Sta/Elev= 30
  4486.7  446.71  4612.5  444.70  4685.8  441.99  4712.7  440.12  4735.1  437.43
  4740.4  437.66  4767.6  435.26  4772.8  435.82  4800.0  433.29  4941.8  427.06
  4979.3  424.51  4989.4  421.29  4993.6  418.66  4994.1  417.86  5005.4  417.86
  5005.9  418.66  5010.7  423.43  5021.2  423.66  5176.4  424.31  5233.9  423.10
  5353.7  423.88  5432.3  427.06  5509.1  431.51  5530.4  433.81  5560.0  435.14
  5571.2  436.75  5591.9  437.24  5605.0  438.92  5695.5  446.05  5737.0  446.98
#Mann=6,-1,0
  4486.7    0.16       0  4712.7    0.05       0  4989.4    0.12       0
  4993.6    0.07       0  5005.9    0.12       0  5233.9    0.05       0
Bank Sta=4941.8,5432.3
Exp/Cntr=0.3,0.1

Type RM Length L Ch R = 1,34515,692,692,692
BEGIN DESCRIPTION:
GLADE CREEK 20.0
END DESCRIPTION:
XS GIS Cut Line= 3
      2873142.49      7044036.65      2872486.26      7043701.59
      2872095.62      7043696.38
#Sta/Elev= 30
  4309.1  439.85  4351.3  438.84  4370.7  437.84  4434.5  434.70  4441.0  433.79
  4463.5  432.25  4536.1  429.47  4655.6  425.76  4740.1  423.57  4755.4  423.85
  4767.9  423.31  4800.3  423.89  4917.8  422.85  4984.5  422.82  4991.2  422.42
  5006.7  420.10  5007.5  417.78  5008.0  416.98  5019.3  416.98  5019.8  417.78
  5023.3  418.18  5029.0  420.87  5036.1  422.49  5043.8  423.34  5109.1  425.76
  5137.2  428.50  5187.2  432.28  5267.2  436.35  5397.2  444.73  5436.6  443.70
#Mann=5,-1,0
  4309.1    0.12       0  4370.7    0.16       0  4536.1    0.05       0
  5007.5    0.03       0  5019.8    0.05       0
Bank Sta=4655.6,5109.1
Exp/Cntr=0.3,0.1

Type RM Length L Ch R = 1,33823,722,722,722
BEGIN DESCRIPTION:
GLADE CREEK 19.0
END DESCRIPTION:
XS GIS Cut Line= 3
      2873324.99      7043874.98      2872975.00      7043375.00
      2872124.97      7042874.98
#Sta/Elev= 30
  4412.3  443.54  4455.4  441.36  4583.6  437.34  4654.8  433.76  4669.9  432.78
  4699.6  433.05  4792.0  429.20  4900.5  427.04  4952.0  424.74  4964.6  423.03
  4973.3  423.38  4988.1  417.28  4988.6  416.48  4999.9  416.48  5000.4  417.28
  5009.1  417.39  5015.2  418.84  5019.6  420.99  5045.8  422.59  5197.9  421.64
  5227.7  422.80  5467.8  422.81  5557.8  424.74  5619.4  426.61  5680.7  429.31
  5739.3  430.15  5788.3  435.07  5820.4  436.57  5973.7  449.09  6008.8  449.85
#Mann=7,-1,0
  4412.3    0.05       0  4654.8    0.12       0  4988.1    0.07       0
  5000.4    0.12       0  5197.9    0.05       0  5619.4    0.08       0
  5820.4    0.05       0
Bank Sta=4952,5557.8
Exp/Cntr=0.3,0.1

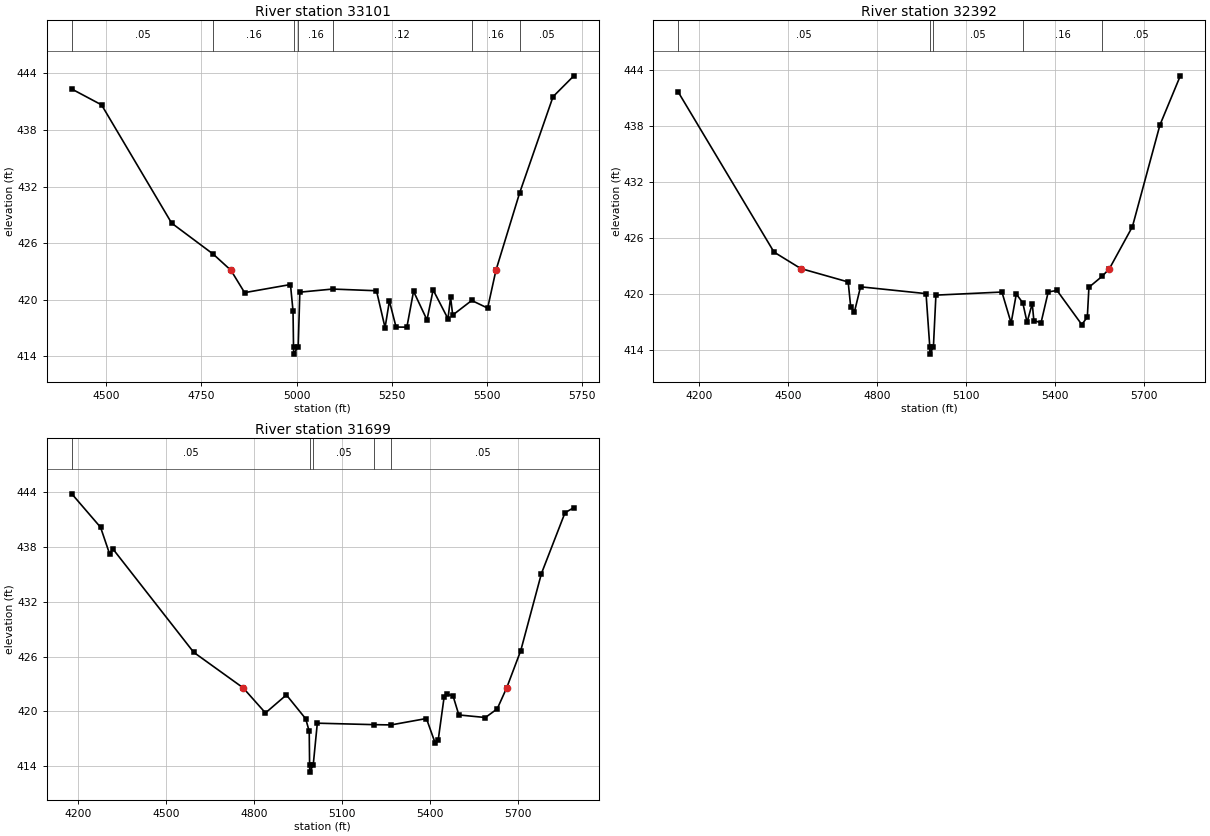
Type RM Length L Ch R = 1,33101,709,709,709
BEGIN DESCRIPTION:
GLADE CREEK 18.0
END DESCRIPTION:
XS GIS Cut Line= 3
      2873725.00      7043275.00      2873325.00      7042825.00
      2873024.99      7042174.98
#Sta/Elev= 30
  4409.6  442.34  4487.8  440.66  4671.8  428.12  4781.0  424.83  4827.4  423.12
  4863.3  420.75  4983.7  421.61  4990.4  418.81  4991.7  415.03  4992.2  414.23
  5004.0  415.03  5008.3  420.80  5094.3  421.13  5209.5  420.95  5232.0  417.04
  5243.4  419.86  5260.9  417.10  5289.3  417.09  5306.8  420.89  5342.1  417.86
  5358.2  421.04  5397.2  417.98  5404.0  420.27  5409.6  418.37  5459.5  419.92
  5501.3  419.11  5523.1  423.12  5585.1  431.30  5673.0  441.53  5727.6  443.74
#Mann=7,-1,0
  4409.6    0.05       0  4781.0    0.16       0  4991.7    0.07       0
  5004.0    0.16       0  5094.3    0.12       0  5459.5    0.16       0
  5585.1    0.05       0
Bank Sta=4827.4,5523.1
Exp/Cntr=0.3,0.1

Type RM Length L Ch R = 1,32392,693,693,693
BEGIN DESCRIPTION:
GLADE CREEK 17.0
END DESCRIPTION:
XS GIS Cut Line= 3
      2874675.02      7042625.00      2873825.00      7042375.00
      2873074.99      7042075.00
#Sta/Elev= 30
  4129.6  441.62  4452.7  424.48  4542.8  422.72  4702.9  421.28  4711.3  418.65
  4723.8  418.05  4744.6  420.76  4965.6  420.03  4978.2  414.35  4978.7  413.55
  4990.5  414.35  4998.9  419.87  5221.6  420.20  5252.6  416.88  5270.1  419.99
  5292.0  419.04  5306.4  416.96  5323.9  418.97  5329.3  417.15  5353.5  416.91
  5377.8  420.21  5407.4  420.37  5490.9  416.72  5509.7  417.51  5515.1  420.71
  5560.2  421.90  5584.5  422.72  5661.8  427.20  5754.7  438.10  5823.4  443.36
#Mann=5,-1,0
  4129.6    0.05       0  4978.2    0.03       0  4990.5    0.05       0
  5292.0    0.16       0  5560.2    0.05       0
Bank Sta=4542.8,5584.5
Exp/Cntr=0.3,0.1

Type RM Length L Ch R = 1,31699,725,725,725
BEGIN DESCRIPTION:
GLADE CREEK 16.0
END DESCRIPTION:
XS GIS Cut Line= 3
      2874974.98      7042124.99      2874225.00      7041825.00
      2873324.99      7041725.00
#Sta/Elev= 30
  4178.3  443.79  4276.6  440.13  4307.5  437.21  4318.3  437.78  4594.3  426.47
  4762.8  422.59  4839.3  419.84  4910.7  421.81  4976.6  419.20  4988.6  417.82
  4989.9  414.17  4990.4  413.37  5002.3  414.17  5016.2  418.72  5209.4  418.56
  5267.9  418.53  5388.5  419.23  5418.7  416.52  5428.8  416.89  5448.9  421.58
  5458.9  421.86  5479.1  421.73  5499.2  419.62  5589.7  419.34  5630.0  420.28
  5662.5  422.59  5710.5  426.66  5780.9  435.07  5861.4  441.72  5891.6  442.28
#Mann=5,-1,0
  4178.3    0.05       0  4989.9    0.03       0  5002.3    0.05       0
  5209.4    0.16       0  5267.9    0.05       0
Bank Sta=4762.8,5662.5
Exp/Cntr=0.3,0.1