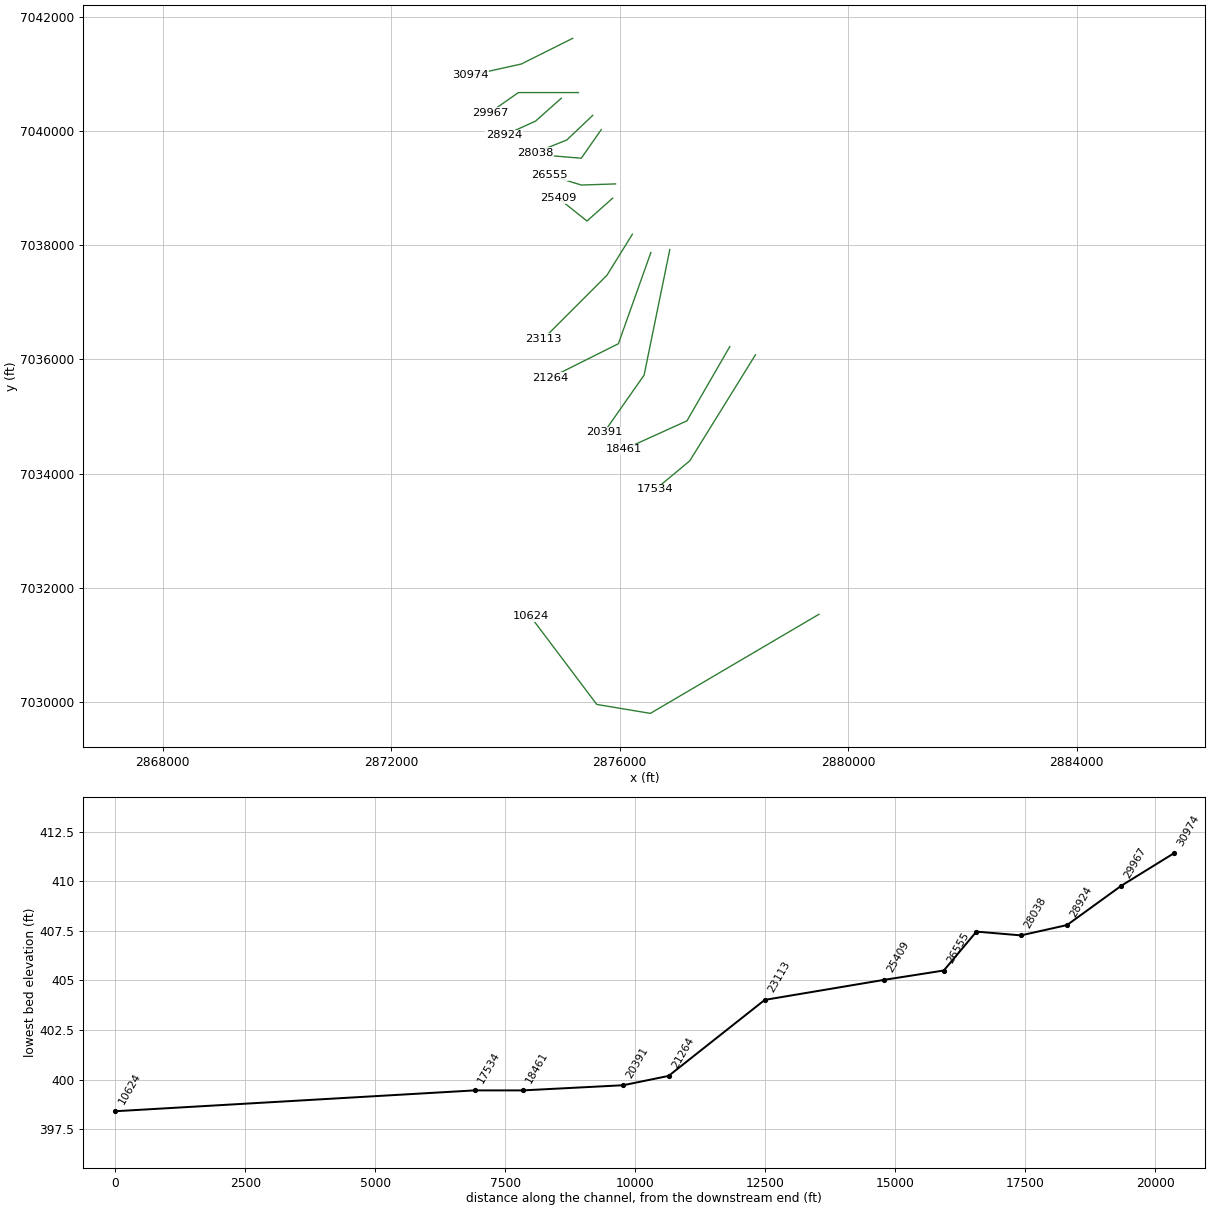
HEC-RAS study GLADE CREEK.prj: GLADE CREEK Base Level Engineering

--- GLADE CREEK.g01 (geometry) --- (continued)

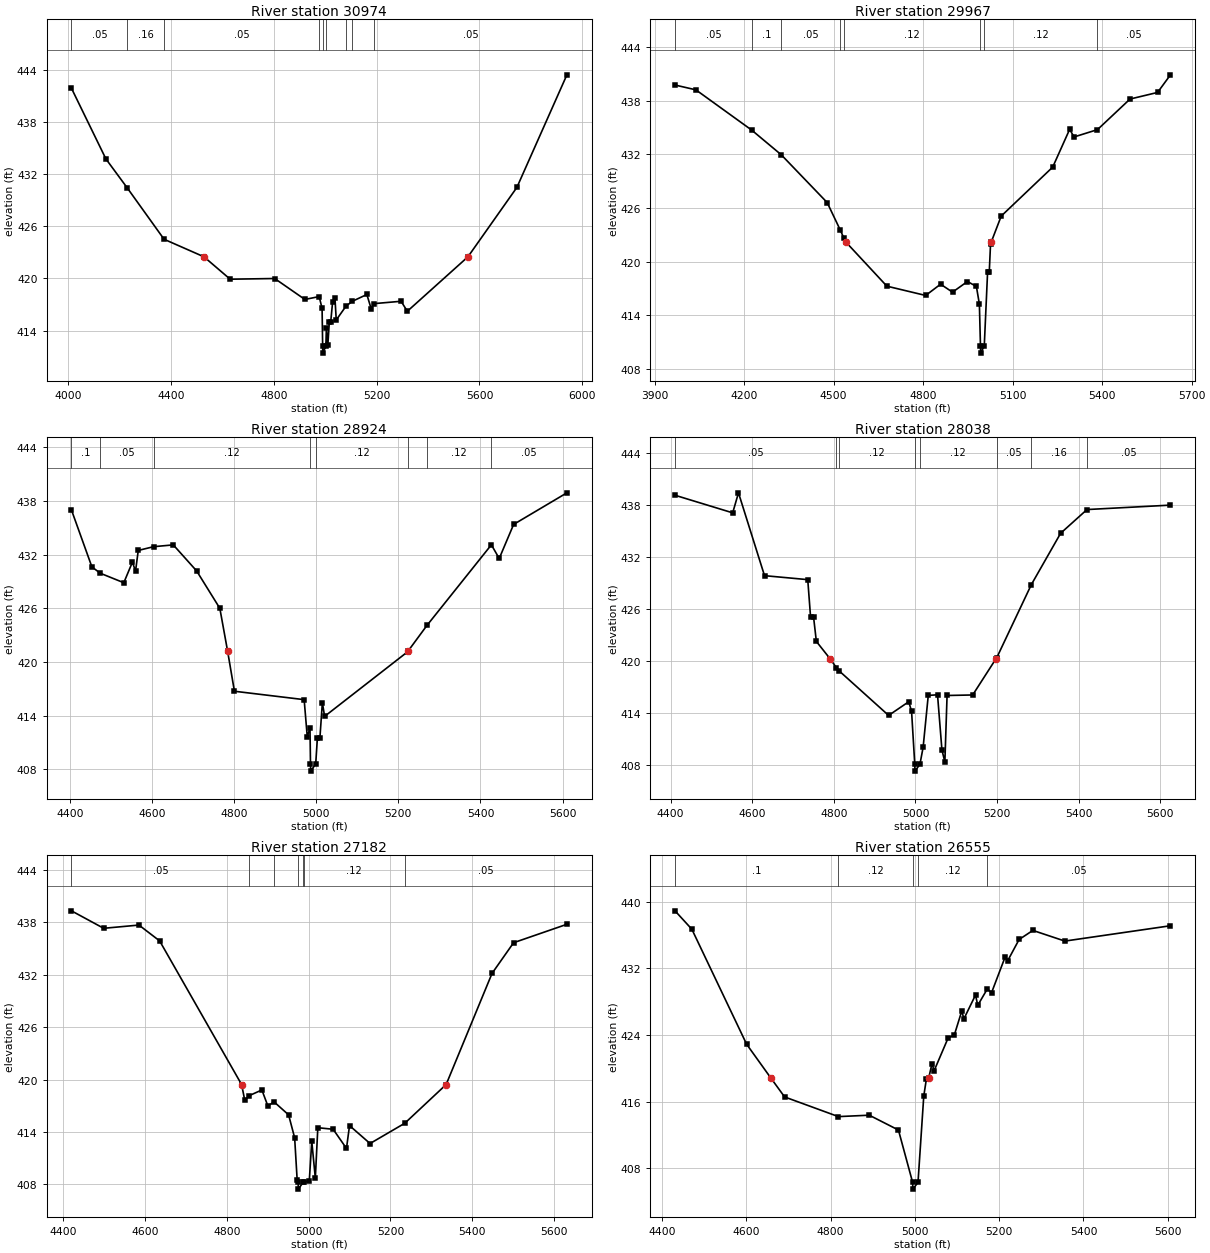
Type RM Length L Ch R = 1,30974,1007,1007,1007
BEGIN DESCRIPTION:
GLADE CREEK 15.0
END DESCRIPTION:
XS GIS Cut Line= 3
      2875174.96      7041624.98      2874275.00      7041175.00
      2873375.04      7040975.01
#Sta/Elev= 30
  4012.1  441.90  4146.2  433.76  4229.3  430.42  4372.5  424.51  4527.8  422.49
  4629.8  419.91  4803.1  419.99  4920.5  417.58  4976.1  417.91  4987.5  416.55
  4989.7  412.20  4990.2  411.40  5002.2  412.20  5004.3  414.34  5009.9  412.32
  5015.5  414.95  5020.9  414.95  5028.5  417.31  5037.5  417.78  5042.6  415.22
  5080.4  416.80  5104.6  417.36  5161.7  418.15  5178.4  416.52  5190.0  417.10
  5294.9  417.37  5319.2  416.22  5555.1  422.49  5745.6  430.48  5940.2  443.44
#Mann=9,-1,0
  4012.1    0.05       0  4229.3    0.16       0  4372.5    0.05       0
  4976.1    0.12       0  4989.7    0.07       0  5002.2    0.12       0
  5080.4    0.16       0  5104.6    0.12       0  5190.0    0.05       0
Bank Sta=4527.8,5555.1
Exp/Cntr=0.3,0.1

Type RM Length L Ch R = 1,29967,1043,1043,1043
BEGIN DESCRIPTION:
GLADE CREEK 14.0
END DESCRIPTION:
XS GIS Cut Line= 3
      2875275.05      7040675.00      2874225.00      7040675.00
      2873724.98      7040324.99
#Sta/Elev= 30
  3968.6  439.76  4038.6  439.22  4225.5  434.72  4324.6  431.96  4478.6  426.61
  4522.7  423.52  4533.7  422.70  4541.6  422.18  4678.6  417.26  4808.6  416.22
  4858.6  417.48  4898.6  416.59  4948.6  417.78  4978.6  417.23  4988.6  415.26
  4992.3  410.57  4992.8  409.77  5005.0  410.57  5016.1  418.81  5021.7  418.81
  5026.1  422.03  5028.2  422.18  5061.8  425.10  5234.4  430.58  5291.1  434.80
  5305.9  433.95  5384.4  434.77  5493.4  438.19  5585.8  438.93  5629.0  440.90
#Mann=8,-1,0
  3968.6    0.05       0  4225.5     0.1       0  4324.6    0.05       0
  4522.7    0.16       0  4533.7    0.12       0  4992.3    0.07       0
  5005.0    0.12       0  5384.4    0.05       0
Bank Sta=4541.6,5028.2
Exp/Cntr=0.3,0.1

Type RM Length L Ch R = 1,28924,886,886,886
BEGIN DESCRIPTION:
GLADE CREEK 13.0
END DESCRIPTION:
XS GIS Cut Line= 3
      2874975.02      7040575.02      2874525.00      7040175.00
      2873974.96      7039924.98
#Sta/Elev= 30
  4404.2  436.99  4454.0  430.62  4474.5  429.91  4531.7  428.85  4552.7  431.16
  4560.2  430.13  4566.9  432.46  4604.3  432.88  4652.2  433.08  4709.0  430.17
  4765.5  425.99  4784.5  421.18  4801.0  416.72  4970.8  415.78  4978.3  411.65
  4985.0  412.59  4986.2  408.59  4986.7  407.79  4998.9  408.59  5003.0  411.48
  5009.1  411.48  5015.1  415.44  5020.6  413.91  5222.9  421.14  5223.5  421.19
  5269.8  424.08  5426.6  433.09  5445.7  431.56  5480.8  435.37  5610.5  438.90
#Mann=8,-1,0
  4404.2     0.1       0  4474.5    0.05       0  4604.3    0.12       0
  4986.2    0.07       0  4998.9    0.12       0  5222.9    0.16       0
  5269.8    0.12       0  5426.6    0.05       0
Bank Sta=4784.5,5223.5
Exp/Cntr=0.3,0.1

Type RM Length L Ch R = 1,28038,856,856,856
BEGIN DESCRIPTION:
GLADE CREEK 12.0
END DESCRIPTION:
XS GIS Cut Line= 3
      2875525.02      7040275.02      2875072.20      7039844.24
      2874524.98      7039624.99
#Sta/Elev= 30
  4410.6  439.11  4552.0  437.08  4566.2  439.39  4630.0  429.83  4736.0  429.37
  4742.9  425.06  4750.2  425.07  4757.1  422.24  4791.5  420.19  4806.2  419.21
  4813.4  418.82  4934.2  413.70  4983.6  415.28  4990.5  414.16  4998.3  408.07
  4998.8  407.27  5011.0  408.07  5018.8  410.02  5031.4  416.01  5054.1  416.08
  5064.9  409.71  5072.1  408.33  5077.5  416.00  5140.3  416.06  5196.7  420.19
  5198.9  420.32  5284.1  428.80  5355.8  434.72  5420.5  437.46  5625.1  437.97
#Mann=8,-1,0
  4410.6    0.05       0  4806.2    0.16       0  4813.4    0.12       0
  4998.3    0.07       0  5011.0    0.12       0  5198.9    0.05       0
  5284.1    0.16       0  5420.5    0.05       0
Bank Sta=4791.5,5196.7
Exp/Cntr=0.3,0.1

Type RM Length L Ch R = 1,27182,627,627,627
BEGIN DESCRIPTION:
GLADE CREEK 11.0
END DESCRIPTION:
XS GIS Cut Line= 3
      2875674.98      7040024.97      2875325.00      7039525.00
      2874724.97      7039575.00
#Sta/Elev= 30
  4419.5  439.31  4498.4  437.31  4584.7  437.68  4635.3  435.87  4835.9  419.43
  4843.6  417.63  4855.0  418.17  4885.5  418.81  4900.3  416.96  4915.0  417.46
  4950.9  415.96  4965.7  413.33  4971.8  408.54  4974.2  408.26  4974.7  407.46
  4986.9  408.26  4988.2  408.28  5001.5  408.40  5007.6  412.92  5016.3  408.73
  5022.4  414.49  5059.9  414.31  5092.5  412.12  5100.0  414.73  5150.2  412.68
  5235.2  415.00  5336.4  419.43  5448.7  432.15  5501.4  435.66  5631.9  437.77
#Mann=7,-1,0
  4419.5    0.05       0  4855.0    0.16       0  4915.0     0.1       0
  4974.2    0.07       0  4986.9     0.1       0  4988.2    0.12       0
  5235.2    0.05       0
Bank Sta=4835.9,5336.4
Exp/Cntr=0.3,0.1

Type RM Length L Ch R = 1,26555,1146,1146,1146
BEGIN DESCRIPTION:
GLADE CREEK 10.0
END DESCRIPTION:
XS GIS Cut Line= 3
      2875924.96      7039075.00      2875327.21      7039055.36
      2874775.05      7039224.99
#Sta/Elev= 30
  4430.8  438.89  4470.8  436.68  4600.8  422.88  4658.1  418.84  4690.9  416.56
  4818.5  414.20  4891.8  414.37  4961.0  412.59  4994.7  406.30  4995.2  405.50
  5007.4  406.30  5021.1  416.67  5027.5  418.77  5032.9  418.84  5040.5  420.54
  5045.8  419.72  5078.5  423.59  5093.9  424.04  5111.2  426.86  5116.4  425.94
  5143.9  428.79  5149.2  427.55  5172.0  429.53  5181.9  429.06  5214.6  433.41
  5219.8  432.86  5247.3  435.45  5280.0  436.54  5355.9  435.26  5606.5  437.10
#Mann=5,-1,0
  4430.8     0.1       0  4818.5    0.12       0  4994.7    0.07       0
  5007.4    0.12       0  5172.0    0.05       0
Bank Sta=4658.1,5032.9
Exp/Cntr=0.3,0.1

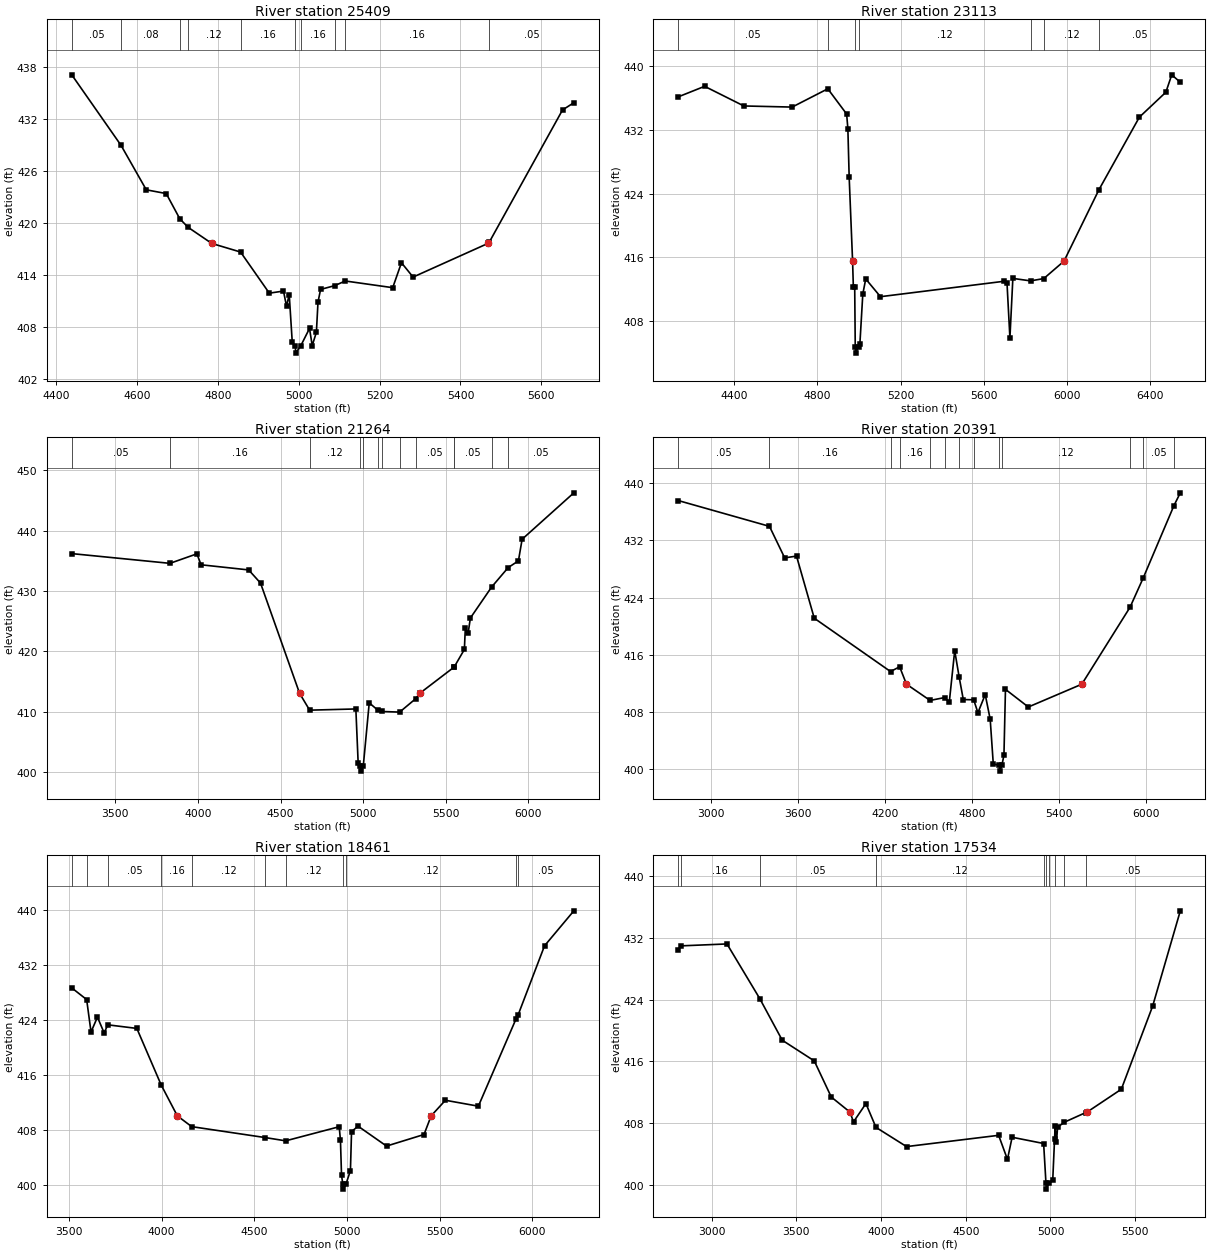
Type RM Length L Ch R = 1,25409,2296,2296,2296
BEGIN DESCRIPTION:
GLADE CREEK 9.0
END DESCRIPTION:
XS GIS Cut Line= 3
      2875874.99      7038824.99      2875425.00      7038425.00
      2874924.98      7038825.01
#Sta/Elev= 30
  4438.2  437.05  4560.2  428.93  4622.6  423.82  4671.9  423.39  4705.5  420.49
  4725.9  419.51  4784.7  417.65  4855.9  416.66  4927.0  411.93  4962.1  412.17
  4969.6  410.43  4976.3  411.77  4983.8  406.28  4991.6  405.83  4992.1  405.03
  5004.4  405.83  5026.5  407.87  5033.2  405.90  5043.5  407.43  5047.5  410.90
  5053.9  412.36  5088.5  412.79  5115.0  413.33  5232.4  412.56  5254.0  415.43
  5282.8  413.78  5467.9  417.65  5471.1  417.78  5652.6  433.01  5680.6  433.84
#Mann=10,-1,0
  4438.2    0.05       0  4560.2    0.08       0  4705.5    0.05       0
  4725.9    0.12       0  4855.9    0.16       0  4991.6    0.07       0
  5004.4    0.16       0  5088.5    0.12       0  5115.0    0.16       0
  5471.1    0.05       0
Bank Sta=4784.7,5467.9
Exp/Cntr=0.3,0.1

Type RM Length L Ch R = 1,23113,1849,1849,1849
BEGIN DESCRIPTION:
GLADE CREEK 8.0
END DESCRIPTION:
XS GIS Cut Line= 3
      2876219.60      7038193.20      2875775.00      7037475.00
      2874665.88      7036365.88
#Sta/Elev= 30
  4131.0  436.12  4257.8  437.44  4446.4  434.98  4678.5  434.84  4849.9  437.13
  4940.4  433.97  4946.3  432.15  4952.6  426.05  4969.0  415.54  4972.7  412.26
  4979.2  412.26  4981.8  404.82  4983.5  404.02  4997.8  404.82  5004.0  405.14
  5018.1  411.42  5032.2  413.31  5103.0  411.09  5696.9  413.02  5711.1  412.84
  5725.2  405.92  5739.3  413.38  5824.6  413.07  5888.0  413.36  5985.1  415.54
  6153.3  424.50  6347.5  433.58  6474.7  436.70  6503.0  438.88  6544.2  437.95
#Mann=7,-1,0
  4131.0    0.05       0  4849.9    0.12       0  4981.8    0.07       0
  4997.8    0.12       0  5824.6    0.16       0  5888.0    0.12       0
  6153.3    0.05       0
Bank Sta=4969,5985.1
Exp/Cntr=0.3,0.1

Type RM Length L Ch R = 1,21264,873,873,873
BEGIN DESCRIPTION:
GLADE CREEK 7.0
END DESCRIPTION:
XS GIS Cut Line= 3
      2876543.61      7037873.59      2875975.00      7036275.00
      2874775.04      7035675.02
#Sta/Elev= 30
  3236.5  436.19  3830.5  434.58  3993.6  436.15  4019.1  434.34  4307.0  433.49
  4378.6  431.32  4615.2  413.06  4676.0  410.28  4955.6  410.48  4969.5  401.58
  4983.5  400.99  4985.5  400.19  5000.4  400.99  5036.6  411.49  5088.9  410.27
  5111.2  410.06  5220.7  409.96  5318.4  412.19  5342.0  413.06  5547.9  417.36
  5549.1  417.35  5612.4  420.33  5618.0  423.83  5634.8  422.98  5648.7  425.53
  5777.5  430.67  5877.5  433.88  5939.4  434.99  5961.8  438.57  6274.8  446.25
#Mann=13,-1,0
  3236.5    0.05       0  3830.5    0.16       0  4676.0    0.12       0
  4983.5    0.07       0  5000.4    0.12       0  5088.9    0.16       0
  5111.2    0.12       0  5220.7    0.16       0  5318.4    0.05       0
  5547.9    0.08       0  5549.1    0.05       0  5777.5    0.08       0
  5877.5    0.05       0
Bank Sta=4615.2,5342
Exp/Cntr=0.3,0.1

Type RM Length L Ch R = 1,20391,1930,1930,1930
BEGIN DESCRIPTION:
GLADE CREEK 6.0
END DESCRIPTION:
XS GIS Cut Line= 3
      2876875.00      7037925.01      2876425.00      7035725.00
      2875725.01      7034725.01
#Sta/Elev= 30
  2773.6  437.57  3403.5  433.96  3508.5  429.55  3590.2  429.80  3712.7  421.11
  4239.3  413.65  4302.0  414.32  4349.3  411.88  4512.4  409.61  4612.7  410.01
  4644.9  409.38  4682.3  416.57  4713.0  412.88  4741.6  409.73  4813.4  409.70
  4842.5  407.89  4893.0  410.43  4927.3  406.97  4948.6  400.73  4990.4  400.52
  4992.6  399.72  5007.7  400.52  5022.2  401.94  5032.7  411.16  5190.5  408.69
  5559.8  411.88  5892.6  422.64  5984.3  426.77  6196.0  436.87  6239.8  438.65
#Mann=13,-1,0
  2773.6    0.05       0  3403.5    0.16       0  4239.3    0.08       0
  4302.0    0.16       0  4512.4    0.05       0  4612.7    0.08       0
  4713.0    0.16       0  4813.4    0.12       0  4990.4    0.07       0
  5007.7    0.12       0  5892.6    0.16       0  5984.3    0.05       0
  6196.0    0.08       0
Bank Sta=4349.3,5559.8
Exp/Cntr=0.3,0.1

Type RM Length L Ch R = 1,18461,927,927,927
BEGIN DESCRIPTION:
GLADE CREEK 5.0
END DESCRIPTION:
XS GIS Cut Line= 3
      2877924.99      7036224.99      2877175.00      7034925.00
      2876075.02      7034425.01
#Sta/Elev= 30
  3515.1  428.67  3595.4  426.98  3619.0  422.27  3653.6  424.43  3689.6  422.15
  3709.9  423.31  3866.2  422.79  3997.5  414.58  4084.6  410.10  4162.3  408.53
  4559.9  406.94  4669.2  406.47  4958.2  408.52  4964.9  406.53  4970.7  401.44
  4977.4  400.26  4979.9  399.46  4995.5  400.26  5018.7  402.15  5024.7  407.81
  5059.9  408.60  5213.6  405.71  5415.8  407.39  5454.3  410.10  5531.1  412.36
  5709.0  411.50  5911.4  424.12  5922.8  424.70  6066.0  434.78  6224.2  439.86
#Mann=11,-1,0
  3515.1    0.05       0  3595.4    0.08       0  3709.9    0.05       0
  3997.5    0.16       0  4162.3    0.12       0  4559.9    0.16       0
  4669.2    0.12       0  4977.4    0.07       0  4995.5    0.12       0
  5911.4    0.07       0  5922.8    0.05       0
Bank Sta=4084.6,5454.3
Exp/Cntr=0.3,0.1

Type RM Length L Ch R = 1,17534,6910,6910,6910
BEGIN DESCRIPTION:
GLADE CREEK 4.0
END DESCRIPTION:
XS GIS Cut Line= 3
      2878373.84      7036080.82      2877225.00      7034225.00
      2876624.97      7033724.97
#Sta/Elev= 30
  2802.9  430.45  2816.9  430.97  3090.6  431.22  3283.9  424.15  3416.8  418.75
  3605.9  416.07  3706.3  411.39  3816.5  409.44  3837.5  408.17  3910.8  410.54
  3970.1  407.46  4150.5  404.97  4694.2  406.43  4746.2  403.31  4773.8  406.18
  4959.8  405.37  4973.5  400.26  4976.0  399.46  4991.6  400.26  5013.5  400.60
  5024.4  405.98  5027.8  407.61  5035.6  405.56  5042.2  407.48  5082.2  408.13
  5208.7  409.38  5216.3  409.44  5418.4  412.40  5603.2  423.16  5766.6  435.51
#Mann=10,-1,0
  2802.9    0.08       0  2816.9    0.16       0  3283.9    0.05       0
  3970.1    0.12       0  4959.8    0.16       0  4973.5    0.07       0
  4991.6    0.16       0  5024.4    0.12       0  5082.2    0.16       0
  5208.7    0.05       0
Bank Sta=3816.5,5216.3
Exp/Cntr=0.3,0.1

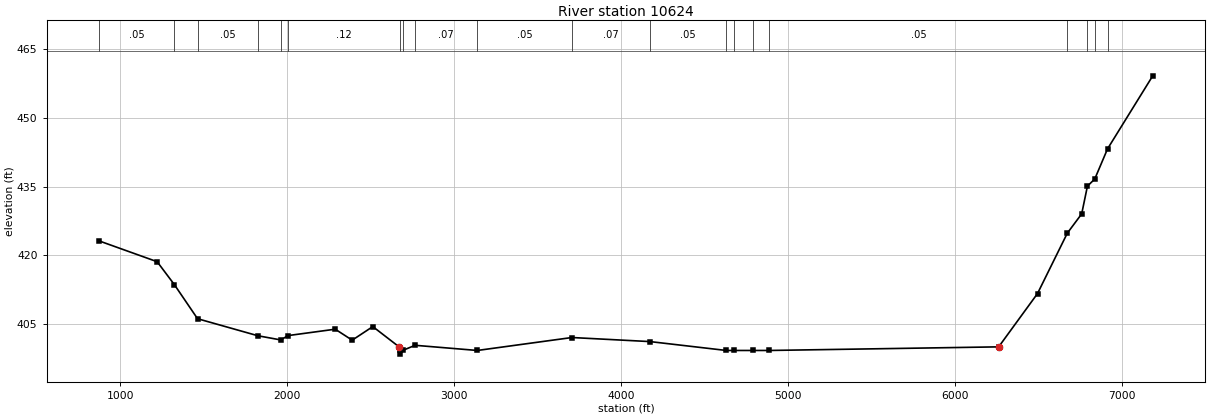
Type RM Length L Ch R = 1,10624,0,0,0
BEGIN DESCRIPTION:
GLADE CREEK 2.0
END DESCRIPTION:
XS GIS Cut Line= 4
      2879486.33      7031536.78      2876534.93      7029800.67
      2875597.43      7029956.92      2874435.03      7031501.00
#Sta/Elev= 30
   876.1  423.14  1222.3  418.61  1325.4  413.60  1464.1  406.15  1826.0  402.42
  1962.8  401.51  2005.5  402.46  2288.5  403.86  2390.1  401.46  2513.5  404.43
  2670.8  400.00  2673.9  399.21  2676.4  398.41  2692.1  399.21  2766.6  400.34
  3139.1  399.21  3705.9  402.04  4173.3  401.15  4630.1  399.21  4679.0  399.21
  4788.4  399.21  4887.5  399.21  6260.9  400.00  6493.6  411.66  6672.0  424.86
  6758.0  429.07  6792.3  435.13  6836.1  436.68  6912.6  443.27  7183.4  459.24
#Mann=20,-1,0
   876.1    0.05       0  1325.4    0.16       0  1464.1    0.05       0
  1826.0    0.16       0  1962.8     0.1       0  2005.5    0.12       0
  2673.9   0.033       0  2692.1    0.12       0  2766.6    0.07       0
  3139.1    0.05       0  3705.9    0.07       0  4173.3    0.05       0
  4630.1    0.07       0  4679.0    0.05       0  4788.4    0.07       0
  4887.5    0.05       0  6672.0    0.08       0  6792.3    0.05       0
  6836.1    0.08       0  6912.6    0.05       0
Bank Sta=2670.8,6260.9
Exp/Cntr=0.3,0.1

Chan Stop Cuts=-1