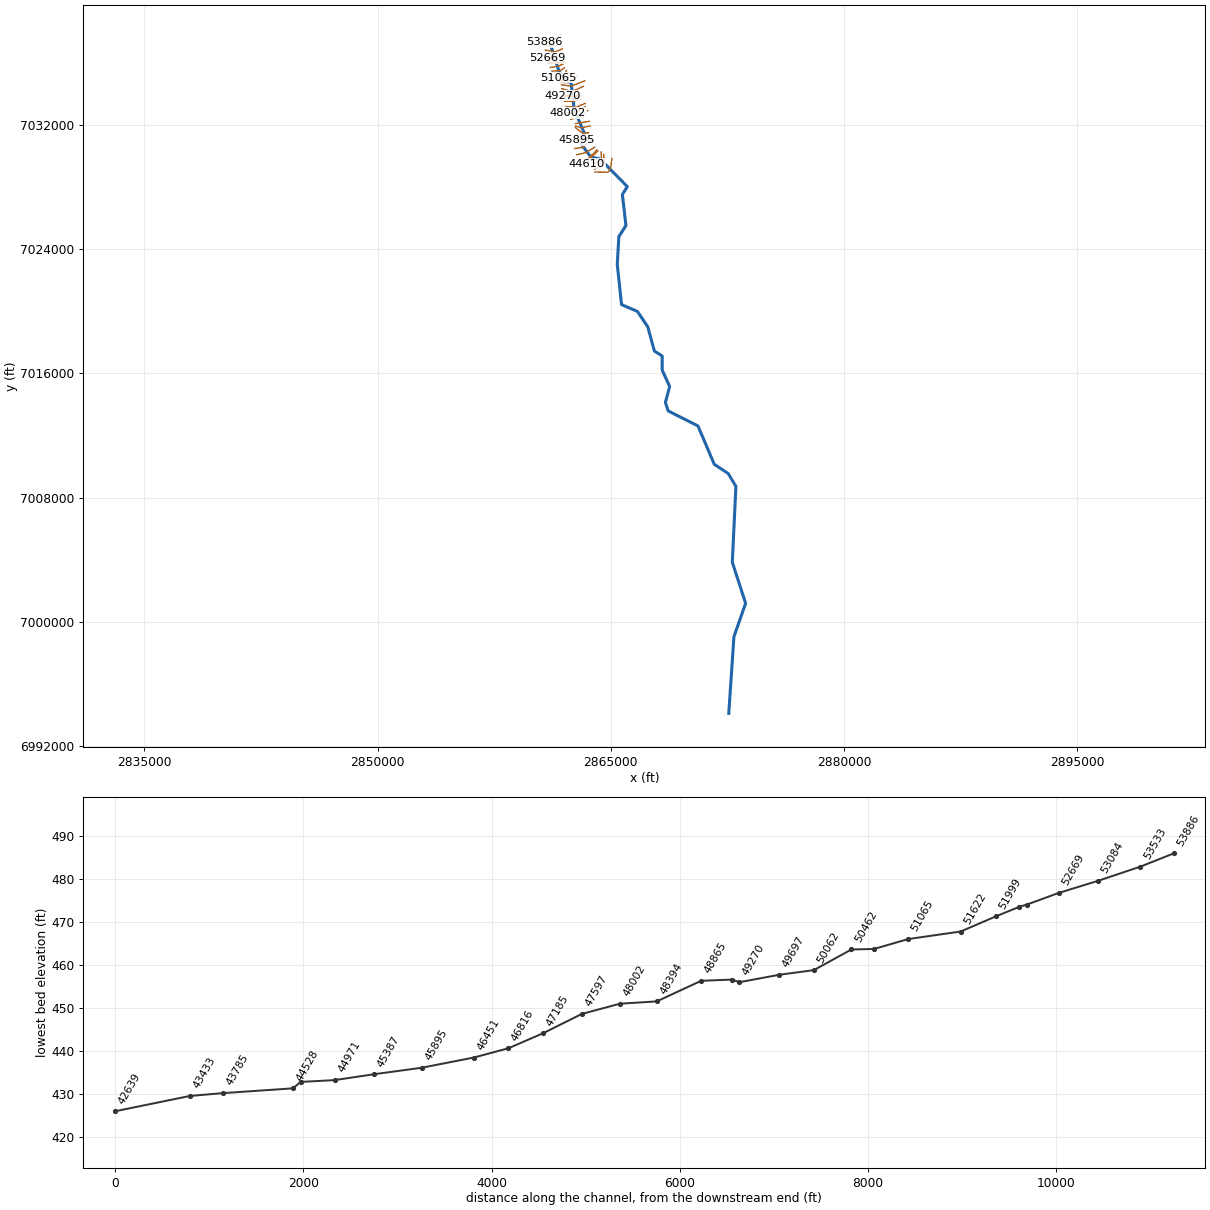
--- LITTLE CANEY CREEK.prj (project) ---

Proj Title=LITTLE CANEY CREEK Base Level Engineering
Current Plan=p01
Default Exp/Contr=0.3,0.1
English Units
Geom File=g01
Flow File=f01
Plan File=p01
BEGIN DESCRIPTION:
LITTLE CANEY CREEK
END DESCRIPTION:

--- LITTLE CANEY CREEK.p01 (plan) ---

Plan Title=Multiple Run
Short Identifier=Multiple
Geom File=g01
Flow File=f01
Subcritical Flow
K Sum by GR= 0
Std Step Tol= 0.01
Critical Tol= 0.01
Num of Std Step Trials= 20
Max Error Tol= 0.3
Flow Tol Ratio= 0.001
Split Flow NTrial= 30
Split Flow Tol= 0.02
Split Flow Ratio= 0.02
Log Output Level= 0
Friction Slope Method= 1
Unsteady Friction Slope Method= 2
Unsteady Bridges Friction Slope Method= 1
Parabolic Critical Depth
Global Vel Dist=  1 , 1 , 1
Global Log Level= 0
CheckData=True
Encroach Param= -1, 0, 0, 0
BEGIN DESCRIPTION:
Multiple Run
END DESCRIPTION:

--- LITTLE CANEY CREEK.f01 (steady flow) ---

Flow Title=Multiple
Number of Profiles=7
Profile Names=10-year,25-year,50-year,1pct_min,100-year,1pct_plu,500-year
River Rch & RM= LITTLE CANEY CRE,Reach-1,53886
     337     436     513     301     601    1199     824
River Rch & RM= LITTLE CANEY CRE,Reach-1,48394
     503     666     797     475     947    1890    1339
River Rch & RM= LITTLE CANEY CRE,Reach-1,45895
     852    1161    1416     858    1711    3415    2504
River Rch & RM= LITTLE CANEY CRE,Reach-1,42639
     949    1297    1585     961    1918    3827    2813
River Rch & RM= LITTLE CANEY CRE,Reach-1,40045
    1204    1661    2041    1243    2481    4950    3674
River Rch & RM= LITTLE CANEY CRE,Reach-1,35092
    1352    1873    2309    1410    2814    5614    4188
River Rch & RM= LITTLE CANEY CRE,Reach-1,31592
    1792    2508    3113    1912    3816    7613    5747
Boundary for River Rch & Prof#=LITTLE CANEY CRE,Reach-1,1
Up Type=0
Dn Type=3
Dn Slope=0.005
Boundary for River Rch & Prof#=LITTLE CANEY CRE,Reach-1,2
Up Type=0
Dn Type=3
Dn Slope=0.005
Boundary for River Rch & Prof#=LITTLE CANEY CRE,Reach-1,3
Up Type=0
Dn Type=3
Dn Slope=0.005
Boundary for River Rch & Prof#=LITTLE CANEY CRE,Reach-1,4
Up Type=0
Dn Type=3
Dn Slope=0.005
Boundary for River Rch & Prof#=LITTLE CANEY CRE,Reach-1,5
Up Type=0
Dn Type=3
Dn Slope=0.005
Boundary for River Rch & Prof#=LITTLE CANEY CRE,Reach-1,6
Up Type=0
Dn Type=3
Dn Slope=0.005
Boundary for River Rch & Prof#=LITTLE CANEY CRE,Reach-1,7
Up Type=0
Dn Type=3
Dn Slope=0.005

--- LITTLE CANEY CREEK.g01 (geometry) ---

Geom Title=Existing Conditions

River Reach=LITTLE CANEY CRE,Reach-1
Reach XY= 30
      2861029.02      7037470.33      2861679.54      7035406.91
      2862455.59      7034650.71      2862647.67      7032986.66
      2863284.09      7031494.84      2863077.86      7030784.26
      2863730.85      7029912.10      2864306.35      7029805.13
      2866064.42      7028020.28      2865746.66      7027510.27
      2865975.63      7025510.68      2865518.65      7024799.46
      2865418.19      7023008.93      2865691.52      7020426.41
      2866718.35      7019980.86      2867381.06      7018989.59
      2867803.21      7017435.78      2868305.86      7017117.52
      2868308.67      7016203.95      2868786.98      7015151.85
      2868512.29      7014122.43      2868696.25      7013580.24
      2870608.43      7012612.05      2871658.92      7010143.15
      2872554.50      7009552.56      2873048.28      7008724.75
      2872815.91      7003845.05      2873672.76      7001197.04
      2872920.86      6999047.54      2872589.25      6994113.91

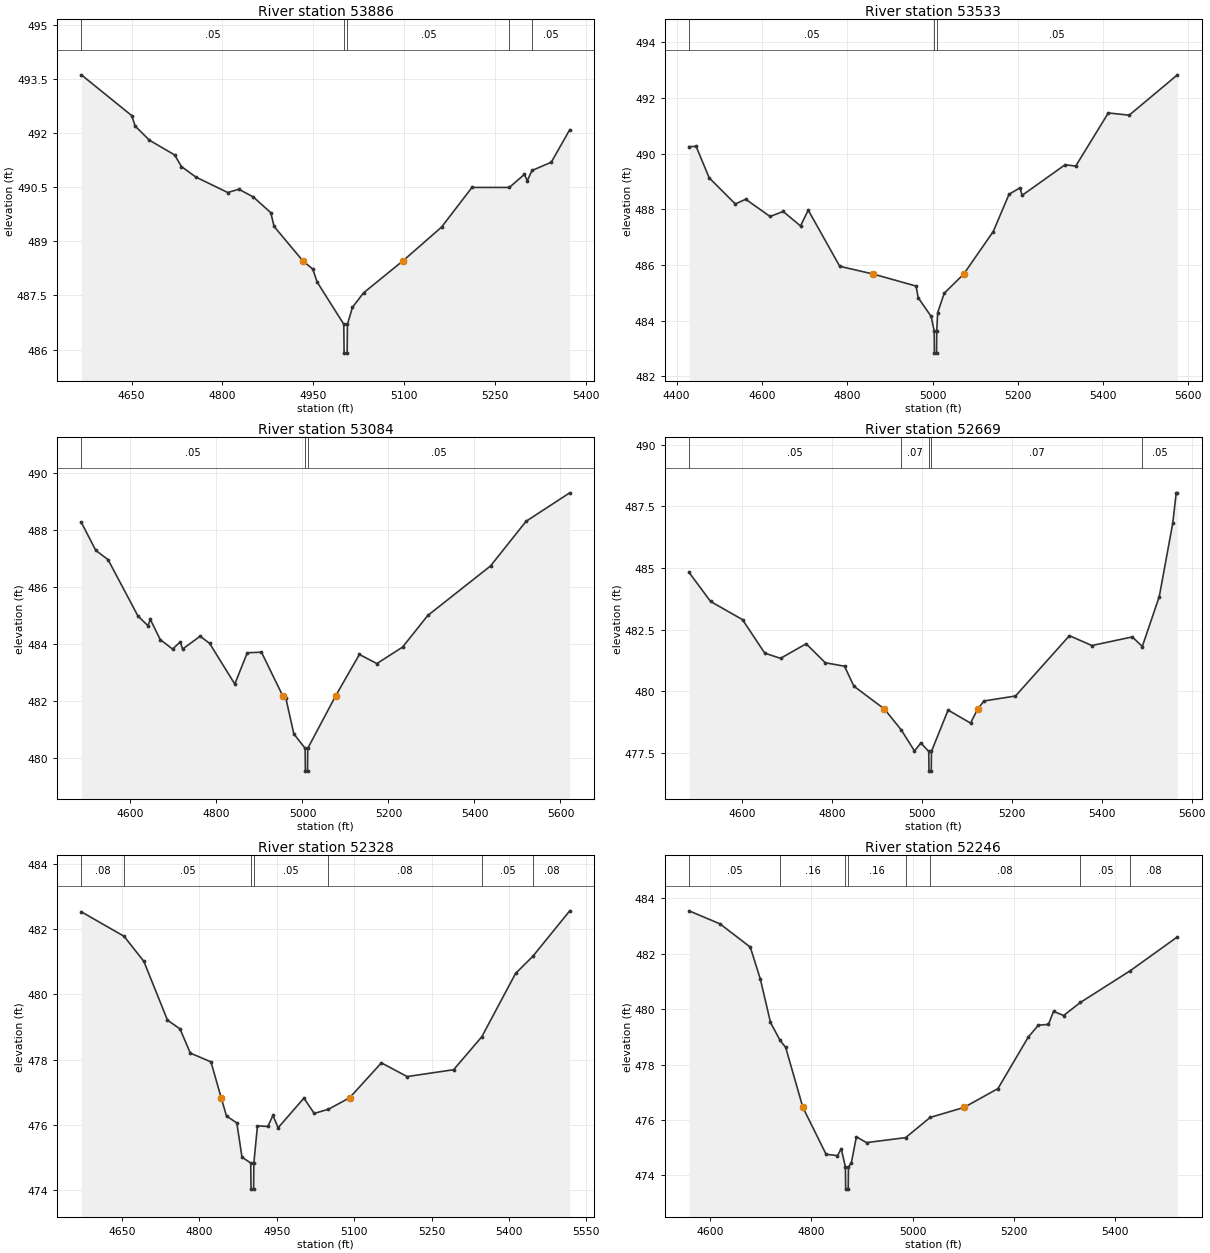
Type RM Length L Ch R = 1,53886,353,353,353
BEGIN DESCRIPTION:
LITTLE CANEY CREEK 66.0
END DESCRIPTION:
XS GIS Cut Line= 3
      2861496.91      7037562.26      2861003.89      7037353.94
      2860734.83      7037320.96
#Sta/Elev= 30
  4567.0  493.61  4650.2  492.48  4655.9  492.19  4679.3  491.80  4721.1  491.39
  4732.2  491.07  4755.9  490.78  4808.7  490.35  4827.0  490.44  4850.7  490.23
  4879.8  489.79  4885.2  489.41  4932.5  488.46  4949.0  488.23  4956.3  487.87
  5000.3  486.70  5000.8  485.90  5005.8  485.90  5006.3  486.70  5014.6  487.17
  5032.9  487.57  5098.2  488.46  5161.6  489.39  5211.9  490.49  5273.6  490.49
  5298.3  490.85  5303.3  490.68  5311.1  490.96  5342.9  491.19  5373.3  492.09
#Mann=5,-1,0
  4567.0    0.05       0  5000.3   0.035       0  5006.3    0.05       0
  5273.6    0.07       0  5311.1    0.05       0
Bank Sta=4932.5,5098.2
Exp/Cntr=0.3,0.1

Type RM Length L Ch R = 1,53533,449,449,449
BEGIN DESCRIPTION:
LITTLE CANEY CREEK 65.0
END DESCRIPTION:
XS GIS Cut Line= 3
      2861781.27      7037186.30      2861154.93      7037058.80
      2860654.89      7037136.93
#Sta/Elev= 30
  4429.0  490.25  4445.6  490.26  4476.2  489.13  4537.5  488.19  4561.9  488.36
  4619.1  487.74  4649.7  487.92  4690.5  487.40  4708.5  487.97  4782.4  485.95
  4861.3  485.67  4961.4  485.24  4966.5  484.82  4996.7  484.15  5003.9  483.63
  5004.4  482.83  5009.4  482.83  5009.9  483.63  5012.0  484.28  5027.3  484.98
  5073.1  485.67  5142.4  487.20  5179.5  488.54  5205.1  488.77  5210.2  488.50
  5311.0  489.60  5335.7  489.55  5412.2  491.46  5461.2  491.38  5574.3  492.83
#Mann=3,-1,0
  4429.0    0.05       0  5003.9   0.035       0  5009.9    0.05       0
Bank Sta=4861.3,5073.1
Exp/Cntr=0.3,0.1

Type RM Length L Ch R = 1,53084,415,415,415
BEGIN DESCRIPTION:
LITTLE CANEY CREEK 64.0
END DESCRIPTION:
XS GIS Cut Line= 3
      2861877.18      7036885.21      2861443.12      7036690.75
      2860793.80      7036808.81
#Sta/Elev= 30
  4485.9  488.28  4519.4  487.30  4548.1  486.97  4617.6  484.99  4640.8  484.65
  4646.3  484.87  4669.5  484.16  4698.1  483.83  4715.8  484.08  4721.3  483.83
  4762.2  484.28  4784.2  484.03  4842.7  482.60  4871.8  483.70  4904.7  483.72
  4954.4  482.18  4961.5  482.10  4980.0  480.85  5006.3  480.34  5006.8  479.54
  5011.8  479.54  5012.3  480.34  5077.0  482.18  5132.4  483.64  5173.1  483.32
  5232.9  483.90  5291.4  485.01  5437.3  486.75  5520.0  488.32  5621.5  489.32
#Mann=3,-1,0
  4485.9    0.05       0  5006.3   0.035       0  5012.3    0.05       0
Bank Sta=4954.4,5077
Exp/Cntr=0.3,0.1

Type RM Length L Ch R = 1,52669,341,341,341
BEGIN DESCRIPTION:
LITTLE CANEY CREEK 63.0
END DESCRIPTION:
XS GIS Cut Line= 3
      2861868.32      7036649.53      2861460.48      7036294.10
      2860914.57      7036294.10
#Sta/Elev= 30
  4481.5  484.82  4529.4  483.64  4600.6  482.90  4650.0  481.54  4685.1  481.33
  4742.1  481.92  4784.8  481.15  4827.5  481.01  4848.4  480.20  4916.4  479.27
  4953.9  478.42  4983.2  477.57  4997.4  477.89  5015.0  477.55  5015.5  476.75
  5020.5  476.75  5021.0  477.55  5058.0  479.23  5108.0  478.70  5123.8  479.27
  5138.0  479.60  5208.0  479.80  5328.0  482.25  5378.0  481.85  5468.0  482.20
  5490.2  481.81  5528.0  483.84  5558.0  486.82  5565.7  488.05  5568.4  488.05
#Mann=5,-1,0
  4481.5    0.05       0  4953.9    0.07       0  5015.0    0.07       0
  5021.0    0.07       0  5490.2    0.05       0
Bank Sta=4916.4,5123.8
Exp/Cntr=0.3,0.1

Type RM Length L Ch R = 1,52328,82,82,82
BEGIN DESCRIPTION:
Mapping XS ab9f5db4
END DESCRIPTION:
XS GIS Cut Line= 3
      2861936.13      7036044.91      2861403.19      7036029.29
      2860989.97      7036025.82
#Sta/Elev= 30
  4571.3  482.53  4654.1  481.78  4692.5  481.01  4738.2  479.21  4762.5  478.94
  4782.5  478.20  4822.5  477.93  4842.3  476.83  4852.6  476.27  4872.6  476.06
  4882.6  475.01  4899.6  474.83  4900.1  474.03  4905.1  474.03  4905.6  474.83
  4912.6  475.97  4932.6  475.95  4942.6  476.29  4952.6  475.91  5002.6  476.82
  5022.6  476.35  5050.2  476.48  5091.2  476.83  5152.7  477.90  5202.7  477.48
  5292.7  477.69  5347.3  478.70  5412.7  480.64  5446.4  481.17  5517.7  482.56
#Mann=7,-1,0
  4571.3    0.08       0  4654.1    0.05       0  4899.6    0.04       0
  4905.6    0.05       0  5050.2    0.08       0  5347.3    0.05       0
  5446.4    0.08       0
Bank Sta=4842.3,5091.2
Exp/Cntr=0.3,0.1

Type RM Length L Ch R = 1,52246,247,247,247
BEGIN DESCRIPTION:
LITTLE CANEY CREEK 62.0
END DESCRIPTION:
XS GIS Cut Line= 3
      2861936.16      7035975.47      2861644.74      7035970.35
      2860969.84      7035956.81
#Sta/Elev= 30
  4557.7  483.55  4618.9  483.08  4678.9  482.24  4698.9  481.08  4718.9  479.52
  4737.9  478.87  4748.9  478.62  4783.0  476.45  4828.9  474.76  4851.5  474.71
  4858.9  474.96  4867.2  474.30  4867.7  473.50  4872.7  473.50  4873.2  474.30
  4878.9  474.45  4888.9  475.39  4908.9  475.18  4986.3  475.36  5035.0  476.09
  5101.8  476.45  5169.0  477.13  5229.0  478.99  5249.0  479.42  5269.0  479.45
  5279.0  479.92  5299.0  479.77  5332.1  480.24  5431.1  481.39  5524.2  482.61
#Mann=8,-1,0
  4557.7    0.05       0  4737.9    0.16       0  4867.2    0.04       0
  4873.2    0.16       0  4986.3    0.05       0  5035.0    0.08       0
  5332.1    0.05       0  5431.1    0.08       0
Bank Sta=4783,5101.8
Exp/Cntr=0.3,0.1

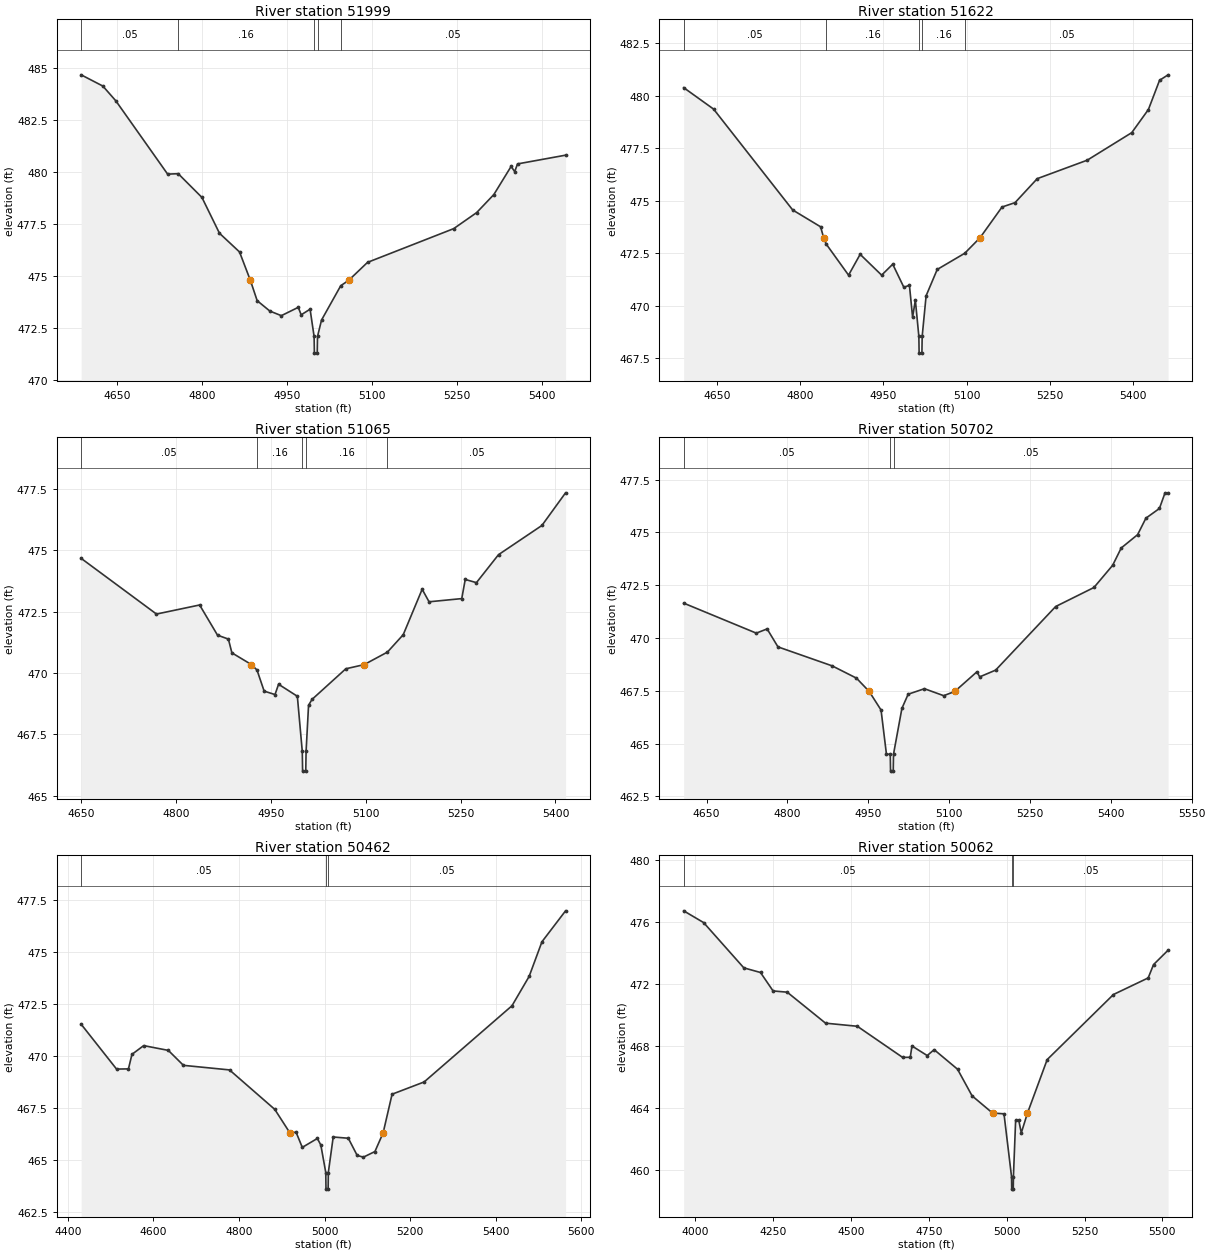
Type RM Length L Ch R = 1,51999,377,377,377
BEGIN DESCRIPTION:
LITTLE CANEY CREEK 61.0
END DESCRIPTION:
XS GIS Cut Line= 3
      2861927.94      7035904.73      2861643.55      7035771.64
      2861110.18      7035685.97
#Sta/Elev= 30
  4587.2  484.66  4625.5  484.12  4648.4  483.41  4739.7  479.89  4758.4  479.91
  4800.2  478.77  4831.1  477.05  4866.5  476.15  4885.7  474.78  4897.6  473.81
  4920.0  473.31  4940.2  473.09  4970.1  473.49  4975.2  473.13  4990.9  473.40
  4998.0  472.09  4998.5  471.29  5003.5  471.29  5004.0  472.09  5011.1  472.88
  5045.0  474.53  5058.7  474.78  5092.2  475.65  5244.1  477.27  5284.6  478.04
  5315.0  478.91  5345.4  480.26  5351.7  480.01  5356.7  480.38  5441.4  480.80
#Mann=5,-1,0
  4587.2    0.05       0  4758.4    0.16       0  4998.0    0.07       0
  5004.0    0.16       0  5045.0    0.05       0
Bank Sta=4885.7,5058.7
Exp/Cntr=0.3,0.1

Type RM Length L Ch R = 1,51622,557,557,557
BEGIN DESCRIPTION:
LITTLE CANEY CREEK 60.0
END DESCRIPTION:
XS GIS Cut Line= 3
      2862021.67      7035672.94      2861759.65      7035485.63
      2861209.59      7035451.62
#Sta/Elev= 30
  4589.9  480.38  4643.8  479.36  4786.4  474.56  4836.7  473.76  4842.2  473.24
  4846.5  472.95  4887.1  471.46  4908.0  472.45  4946.7  471.46  4966.7  471.98
  4986.8  470.88  4996.8  470.98  5002.5  469.46  5007.5  470.27  5013.8  468.55
  5014.3  467.75  5019.3  467.75  5019.8  468.55  5026.9  470.48  5046.9  471.73
  5096.5  472.50  5124.1  473.24  5163.7  474.70  5187.2  474.91  5227.2  476.05
  5317.4  476.93  5397.6  478.24  5427.6  479.34  5447.7  480.73  5463.1  480.99
#Mann=5,-1,0
  4589.9    0.05       0  4846.5    0.16       0  5013.8    0.07       0
  5019.8    0.16       0  5096.5    0.05       0
Bank Sta=4842.2,5124.1
Exp/Cntr=0.3,0.1

Type RM Length L Ch R = 1,51065,363,363,363
BEGIN DESCRIPTION:
LITTLE CANEY CREEK 59.0
END DESCRIPTION:
XS GIS Cut Line= 3
      2862151.90      7035495.88      2862014.74      7035206.81
      2861608.34      7035023.49
#Sta/Elev= 30
  4650.2  474.67  4769.3  472.40  4837.5  472.77  4865.8  471.54  4883.0  471.38
  4888.5  470.82  4919.5  470.34  4928.2  470.12  4939.5  469.26  4956.7  469.12
  4962.3  469.54  4992.0  469.05  4999.8  466.80  5000.3  466.00  5005.3  466.00
  5005.8  466.80  5009.7  468.68  5015.1  468.92  5068.6  470.17  5097.6  470.34
  5134.4  470.85  5159.4  471.56  5189.3  473.41  5200.2  472.90  5251.9  473.03
  5257.4  473.81  5275.1  473.68  5310.0  474.82  5378.6  476.01  5416.0  477.34
#Mann=5,-1,0
  4650.2    0.05       0  4928.2    0.16       0  4999.8    0.07       0
  5005.8    0.16       0  5134.4    0.05       0
Bank Sta=4919.5,5097.6
Exp/Cntr=0.3,0.1

Type RM Length L Ch R = 1,50702,240,240,240
BEGIN DESCRIPTION:
LITTLE CANEY CREEK 58.0
END DESCRIPTION:
XS GIS Cut Line= 3
      2862266.38      7035338.80      2862214.39      7034883.89
      2861779.12      7034813.45
#Sta/Elev= 30
  4607.5  471.65  4742.2  470.23  4762.3  470.43  4782.4  469.58  4883.1  468.68
  4928.1  468.10  4951.7  467.47  4973.7  466.59  4983.7  464.50  4990.8  464.50
  4991.3  463.70  4996.3  463.70  4996.8  464.50  5012.4  466.67  5024.0  467.34
  5054.2  467.60  5089.9  467.27  5110.4  467.47  5151.6  468.40  5156.7  468.16
  5186.3  468.48  5297.7  471.49  5368.7  472.39  5403.4  473.44  5419.3  474.26
  5449.7  474.89  5465.1  475.67  5490.2  476.13  5500.3  476.85  5506.3  476.87
#Mann=3,-1,0
  4607.5    0.05       0  4990.8    0.03       0  4996.8    0.05       0
Bank Sta=4951.7,5110.4
Exp/Cntr=0.3,0.1

Type RM Length L Ch R = 1,50462,400,400,400
BEGIN DESCRIPTION:
LITTLE CANEY CREEK 57.0
END DESCRIPTION:
XS GIS Cut Line= 3
      2862800.31      7035115.65      2862271.90      7034704.01
      2861809.90      7034725.03
#Sta/Elev= 30
  4431.0  471.52  4513.8  469.36  4541.6  469.37  4549.8  470.07  4577.2  470.49
  4634.8  470.26  4670.1  469.54  4777.8  469.32  4883.6  467.42  4918.9  466.29
  4933.4  466.32  4947.9  465.59  4983.2  466.02  4991.3  465.70  5002.8  464.38
  5003.3  463.58  5008.3  463.58  5008.8  464.38  5020.2  466.09  5055.5  466.03
  5076.3  465.20  5090.8  465.12  5117.7  465.39  5136.9  466.29  5157.8  468.15
  5232.7  468.74  5438.1  472.41  5478.1  473.82  5508.1  475.49  5563.3  476.98
#Mann=3,-1,0
  4431.0    0.05       0  5002.8    0.03       0  5008.8    0.05       0
Bank Sta=4918.9,5136.9
Exp/Cntr=0.3,0.1

Type RM Length L Ch R = 1,50062,365,365,365
BEGIN DESCRIPTION:
LITTLE CANEY CREEK 56.0
END DESCRIPTION:
XS GIS Cut Line= 3
      2863325.05      7034825.02      2862432.96      7034478.43
      2861841.83      7034577.38
#Sta/Elev= 30
  3962.1  476.74  4026.2  475.98  4155.3  473.06  4208.9  472.76  4249.3  471.57
  4294.7  471.49  4417.9  469.49  4520.0  469.29  4665.6  467.28  4690.1  467.29
  4695.5  468.02  4744.5  467.40  4766.8  467.78  4841.9  466.52  4888.7  464.80
  4954.4  463.69  4991.2  463.64  5015.5  459.58  5016.0  458.78  5021.0  458.78
  5021.5  459.58  5028.6  463.21  5038.7  463.22  5046.8  462.41  5066.7  463.69
  5130.0  467.14  5342.9  471.34  5454.5  472.41  5471.7  473.27  5518.5  474.20
#Mann=3,-1,0
  3962.1    0.05       0  5015.5    0.03       0  5021.5    0.05       0
Bank Sta=4954.4,5066.7
Exp/Cntr=0.3,0.1

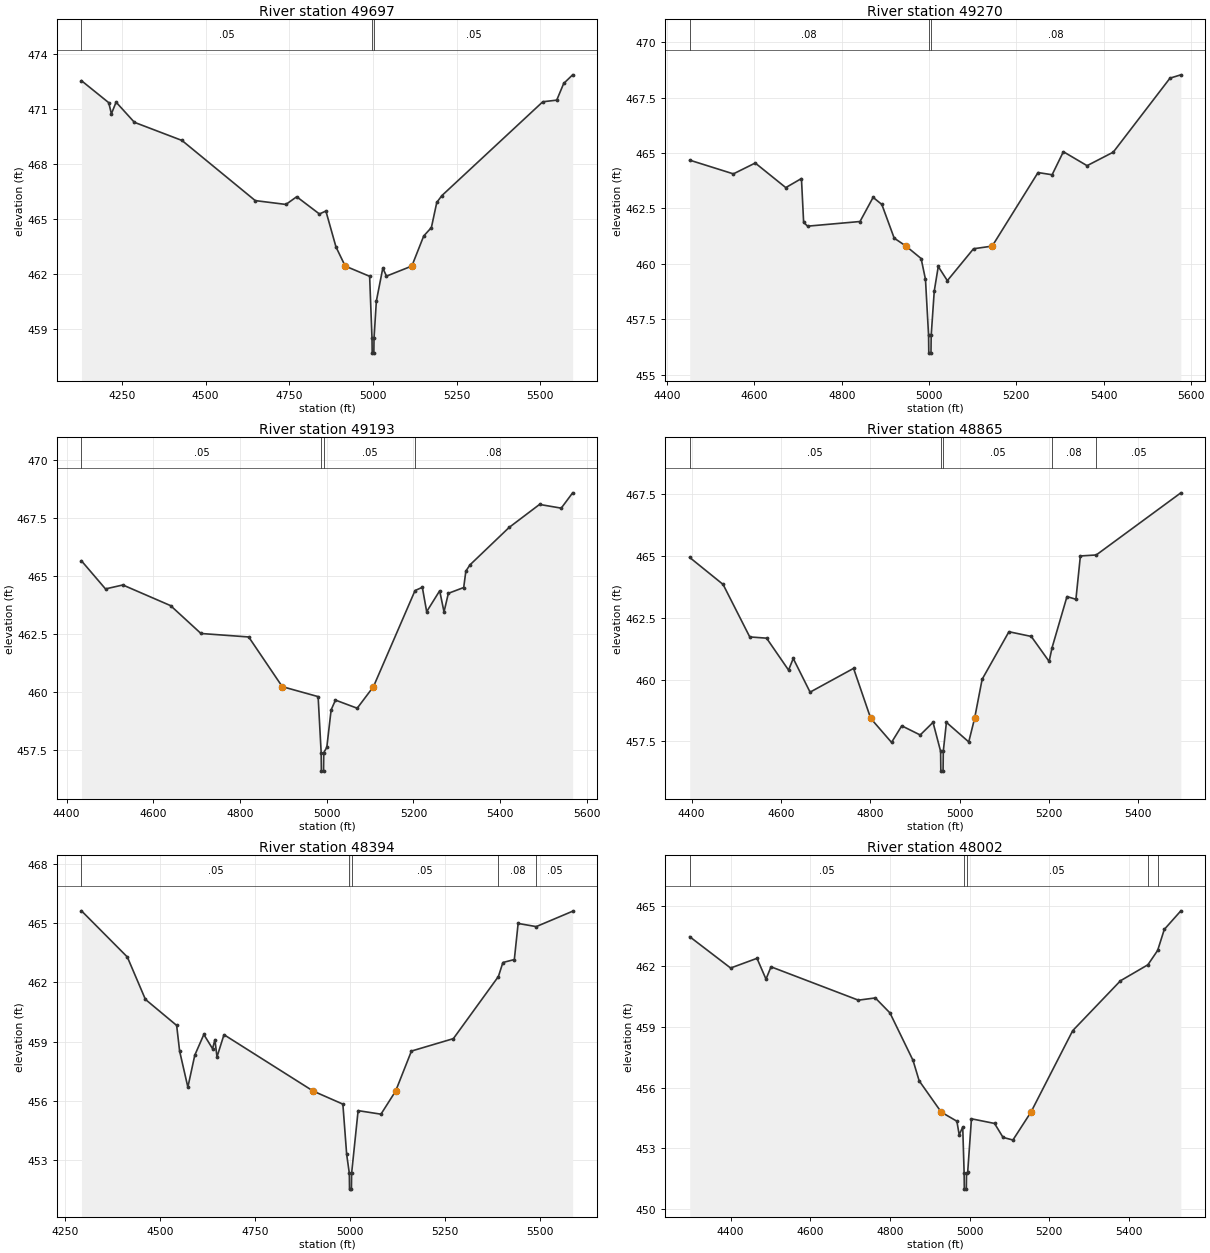
Type RM Length L Ch R = 1,49697,427,427,427
BEGIN DESCRIPTION:
LITTLE CANEY CREEK 55.0
END DESCRIPTION:
XS GIS Cut Line= 4
      2863239.54      7034467.21      2862651.77      7034206.42
      2862356.32      7034176.42      2861849.29      7034321.60
#Sta/Elev= 30
  4129.4  472.57  4210.9  471.37  4218.8  470.76  4232.8  471.40  4287.5  470.30
  4429.7  469.31  4648.5  466.03  4740.2  465.82  4772.4  466.24  4840.3  465.30
  4859.6  465.46  4889.8  463.50  4917.3  462.46  4990.3  461.90  4997.4  458.51
  4997.9  457.71  5002.9  457.71  5003.4  458.51  5010.4  460.55  5029.7  462.35
  5040.6  461.91  5116.4  462.46  5151.9  464.10  5174.8  464.56  5190.9  465.93
  5206.0  466.30  5507.6  471.42  5549.3  471.51  5570.1  472.42  5596.8  472.89
#Mann=3,-1,0
  4129.4    0.05       0  4997.4    0.03       0  5003.4    0.05       0
Bank Sta=4917.3,5116.4
Exp/Cntr=0.3,0.1

Type RM Length L Ch R = 1,49270,77,77,77
BEGIN DESCRIPTION:
Mapping XS 986eca7c
END DESCRIPTION:
XS GIS Cut Line= 4
      2863055.10      7033907.33      2862583.31      7033893.87
      2862254.72      7033881.37      2861930.13      7033873.47
#Sta/Elev= 30
  4451.5  464.68  4551.6  464.06  4601.7  464.55  4671.7  463.44  4707.6  463.85
  4712.6  461.87  4721.7  461.70  4841.8  461.91  4871.8  463.00  4891.8  462.68
  4920.1  461.16  4947.2  460.80  4981.8  460.24  4991.8  459.30  4998.9  456.77
  4999.4  455.97  5004.4  455.97  5004.9  456.77  5011.9  458.77  5021.1  459.88
  5041.9  459.24  5101.9  460.68  5144.7  460.80  5249.7  464.12  5282.0  464.02
  5307.8  465.06  5362.1  464.43  5422.1  465.04  5552.1  468.38  5577.0  468.53
#Mann=3,-1,0
  4451.5    0.08       0  4998.9    0.07       0  5004.9    0.08       0
Bank Sta=4947.2,5144.7
Exp/Cntr=0.3,0.1

Type RM Length L Ch R = 1,49193,328,328,328
BEGIN DESCRIPTION:
LITTLE CANEY CREEK 54.0
END DESCRIPTION:
XS GIS Cut Line= 3
      2863070.34      7033835.71      2862618.90      7033820.52
      2861938.77      7033788.03
#Sta/Elev= 30
  4434.5  465.65  4489.9  464.44  4529.9  464.61  4640.0  463.72  4710.0  462.52
  4820.1  462.37  4897.5  460.23  4980.2  459.80  4987.2  457.39  4987.7  456.59
  4992.7  456.59  4993.2  457.39  5000.2  457.61  5010.2  459.23  5020.2  459.65
  5070.3  459.30  5107.8  460.23  5203.7  464.37  5220.5  464.51  5230.5  463.46
  5260.5  464.36  5270.5  463.45  5280.5  464.25  5315.9  464.50  5320.9  465.21
  5330.6  465.48  5420.7  467.09  5490.8  468.08  5540.8  467.92  5567.1  468.58
#Mann=4,-1,0
  4434.5    0.05       0  4987.2    0.03       0  4993.2    0.05       0
  5203.7    0.08       0
Bank Sta=4897.5,5107.8
Exp/Cntr=0.3,0.1

Type RM Length L Ch R = 1,48865,471,471,471
BEGIN DESCRIPTION:
LITTLE CANEY CREEK 53.0
END DESCRIPTION:
XS GIS Cut Line= 3
      2863096.35      7033670.79      2862603.71      7033516.70
      2862020.00      7033512.36
#Sta/Elev= 30
  4395.6  464.93  4470.4  463.84  4530.1  461.72  4567.8  461.67  4617.0  460.38
  4627.5  460.85  4665.2  459.49  4762.6  460.45  4801.0  458.43  4847.6  457.46
  4870.5  458.13  4911.8  457.76  4940.5  458.27  4957.5  457.10  4958.0  456.30
  4963.0  456.30  4963.5  457.10  4970.5  458.27  5020.5  457.48  5033.6  458.43
  5050.5  460.01  5110.5  461.93  5160.5  461.74  5200.5  460.73  5207.0  461.28
  5240.5  463.35  5260.5  463.24  5270.5  464.99  5306.0  465.03  5495.5  467.54
#Mann=5,-1,0
  4395.6    0.05       0  4957.5    0.03       0  4963.5    0.05       0
  5207.0    0.08       0  5306.0    0.05       0
Bank Sta=4801,5033.6
Exp/Cntr=0.3,0.1

Type RM Length L Ch R = 1,48394,392,392,392
BEGIN DESCRIPTION:
LITTLE CANEY CREEK 52.0
END DESCRIPTION:
XS GIS Cut Line= 3
      2863363.27      7033375.65      2862775.41      7033130.00
      2862121.95      7033175.99
#Sta/Elev= 30
  4293.2  465.63  4413.8  463.29  4461.4  461.14  4543.6  459.82  4551.4  458.52
  4573.1  456.69  4591.3  458.31  4615.1  459.36  4638.1  458.64  4644.3  459.10
  4649.7  458.22  4668.1  459.35  4902.9  456.49  4980.9  455.83  4990.9  453.28
  4997.9  452.32  4998.4  451.52  5003.4  451.52  5003.9  452.32  5021.0  455.50
  5081.1  455.32  5119.7  456.49  5161.3  458.52  5271.6  459.15  5390.1  462.30
  5401.9  463.01  5432.0  463.16  5442.0  464.99  5489.6  464.83  5585.4  465.61
#Mann=5,-1,0
  4293.2    0.05       0  4997.9   0.035       0  5003.9    0.05       0
  5390.1    0.08       0  5489.6    0.05       0
Bank Sta=4902.9,5119.7
Exp/Cntr=0.3,0.1

Type RM Length L Ch R = 1,48002,405,405,405
BEGIN DESCRIPTION:
LITTLE CANEY CREEK 51.0
END DESCRIPTION:
XS GIS Cut Line= 3
      2863358.94      7033162.98      2862682.84      7032747.14
      2862243.46      7032759.32
#Sta/Elev= 30
  4297.2  463.47  4400.0  461.92  4466.2  462.40  4488.8  461.37  4501.4  461.98
  4720.7  460.33  4763.3  460.44  4800.0  459.70  4858.0  457.35  4873.4  456.34
  4928.9  454.79  4968.1  454.34  4973.9  453.67  4982.8  454.05  4986.3  451.78
  4986.8  450.98  4991.8  450.98  4992.3  451.78  4995.2  451.81  5004.7  454.46
  5062.7  454.23  5084.0  453.54  5108.8  453.41  5154.1  454.79  5258.9  458.82
  5378.9  461.29  5447.7  462.08  5472.2  462.79  5488.9  463.83  5530.5  464.75
#Mann=5,-1,0
  4297.2    0.05       0  4986.3   0.035       0  4992.3    0.05       0
  5447.7    0.08       0  5472.2    0.05       0
Bank Sta=4928.9,5154.1
Exp/Cntr=0.3,0.1

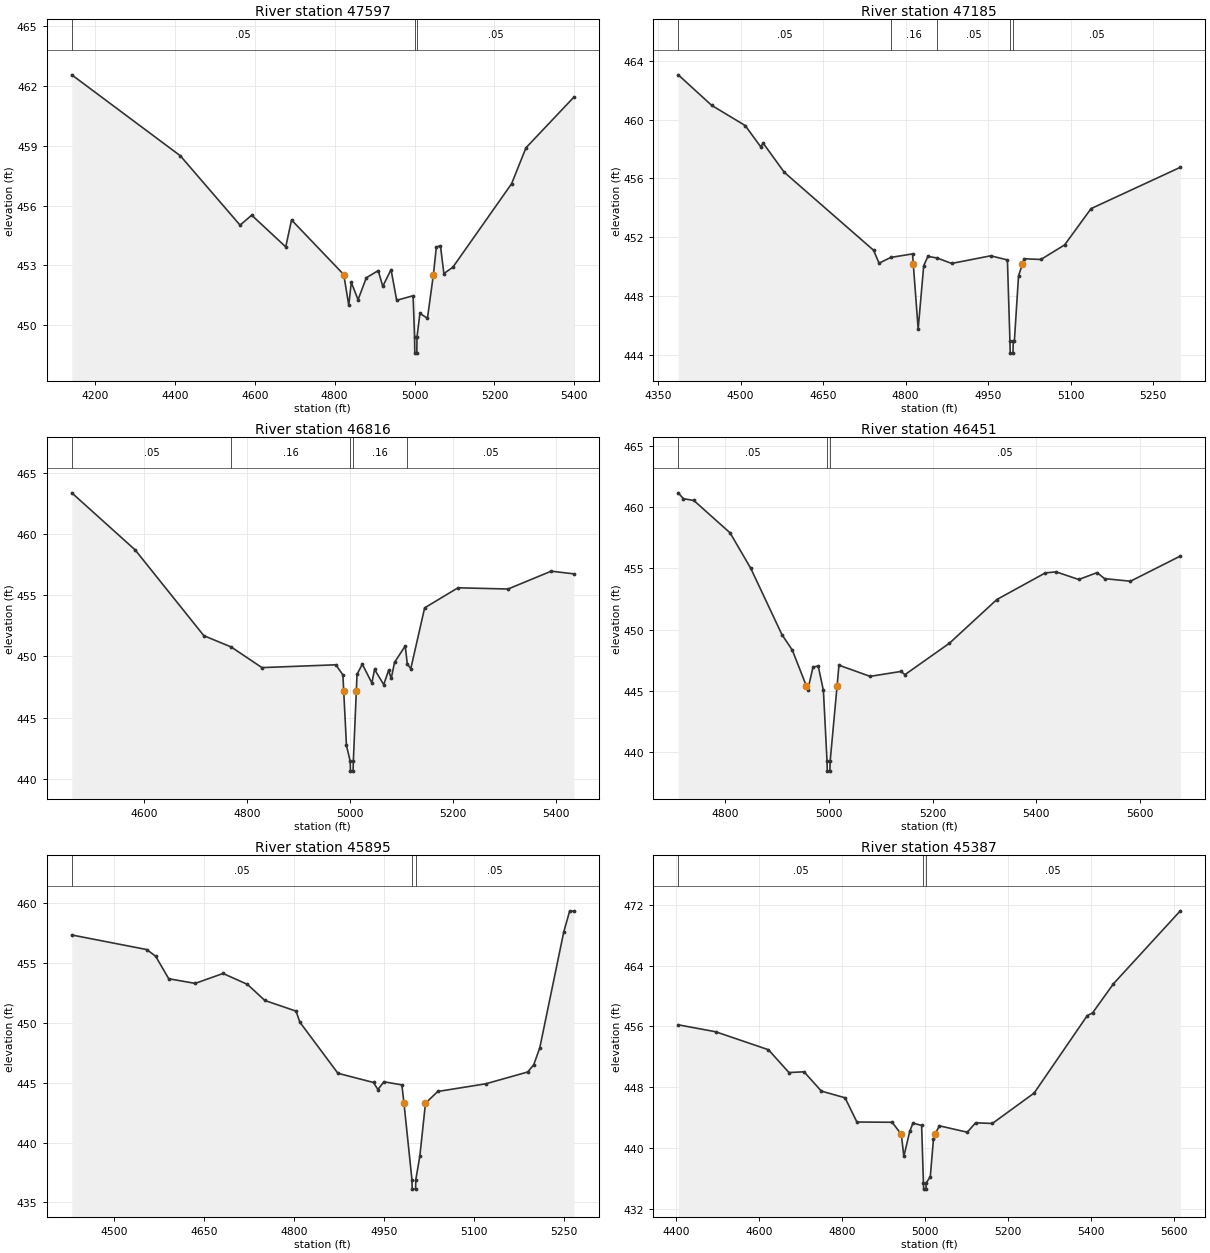
Type RM Length L Ch R = 1,47597,412,412,412
BEGIN DESCRIPTION:
LITTLE CANEY CREEK 50.0
END DESCRIPTION:
XS GIS Cut Line= 3
      2863515.17      7032915.58      2862955.28      7032485.89
      2862421.45      7032351.34
#Sta/Elev= 30
  4142.3  462.56  4413.9  458.50  4563.4  455.02  4592.5  455.52  4677.7  453.93
  4692.2  455.28  4822.9  452.54  4835.4  451.00  4841.7  452.15  4858.7  451.28
  4879.3  452.38  4909.1  452.74  4920.5  451.95  4941.2  452.79  4955.3  451.25
  4996.4  451.48  5000.1  449.40  5000.6  448.60  5005.6  448.60  5006.1  449.40
  5013.4  450.59  5032.3  450.35  5047.2  452.54  5054.6  453.93  5064.9  453.98
  5073.4  452.59  5095.9  452.91  5242.9  457.10  5278.8  458.90  5398.6  461.44
#Mann=3,-1,0
  4142.3    0.05       0  5000.1   0.035       0  5006.1    0.05       0
Bank Sta=4822.9,5047.2
Exp/Cntr=0.3,0.1

Type RM Length L Ch R = 1,47185,369,369,369
BEGIN DESCRIPTION:
LITTLE CANEY CREEK 49.0
END DESCRIPTION:
XS GIS Cut Line= 3
      2863625.03      7032225.00      2863025.00      7032125.00
      2862725.04      7032075.01
#Sta/Elev= 30
  4386.7  463.04  4447.6  460.96  4508.4  459.59  4536.3  458.16  4541.3  458.38
  4579.4  456.41  4741.6  451.11  4751.7  450.23  4773.0  450.62  4812.5  450.86
  4813.9  450.15  4822.7  445.75  4832.8  450.06  4840.4  450.69  4857.3  450.58
  4883.5  450.21  4954.5  450.73  4984.9  450.45  4989.5  444.91  4990.0  444.11
  4995.0  444.11  4995.5  444.91  4997.5  444.91  5005.1  449.36  5012.0  450.15
  5015.3  450.53  5045.7  450.48  5088.8  451.47  5136.9  453.94  5299.1  456.75
#Mann=5,-1,0
  4386.7    0.05       0  4773.0    0.16       0  4857.3    0.05       0
  4989.5   0.035       0  4995.5    0.05       0
Bank Sta=4813.9,5012
Exp/Cntr=0.3,0.1

Type RM Length L Ch R = 1,46816,365,365,365
BEGIN DESCRIPTION:
LITTLE CANEY CREEK 48.0
END DESCRIPTION:
XS GIS Cut Line= 3
      2863675.02      7031925.01      2863110.28      7031798.03
      2862733.14      7031916.68
#Sta/Elev= 30
  4460.0  463.39  4583.0  458.72  4716.3  451.70  4769.2  450.78  4829.0  449.09
  4972.5  449.32  4986.1  448.49  4987.7  447.14  4993.0  442.72  5000.3  441.42
  5000.8  440.62  5005.8  440.62  5006.3  441.42  5012.1  447.14  5013.5  448.54
  5023.8  449.37  5042.3  447.83  5047.5  448.94  5065.3  447.70  5074.7  448.86
  5079.9  448.21  5086.3  449.52  5107.0  450.86  5111.1  449.38  5117.8  449.00
  5144.7  453.98  5209.4  455.62  5306.5  455.52  5390.3  456.98  5434.2  456.76
#Mann=5,-1,0
  4460.0    0.05       0  4769.2    0.16       0  5000.3    0.07       0
  5006.3    0.16       0  5111.1    0.05       0
Bank Sta=4987.7,5012.1
Exp/Cntr=0.3,0.1

Type RM Length L Ch R = 1,46451,556,556,556
BEGIN DESCRIPTION:
LITTLE CANEY CREEK 47.0
END DESCRIPTION:
XS GIS Cut Line= 3
      2863575.01      7031475.00      2863173.26      7031473.96
      2862722.77      7031817.69
#Sta/Elev= 30
  4709.2  461.15  4719.2  460.67  4739.2  460.53  4809.2  457.89  4849.2  454.99
  4909.2  449.60  4929.2  448.34  4956.3  445.42  4959.2  445.12  4969.2  446.96
  4979.2  447.04  4989.2  445.05  4996.2  439.28  4996.7  438.48  5001.7  438.48
  5002.2  439.28  5015.6  445.42  5019.2  447.11  5079.2  446.20  5138.8  446.60
  5146.5  446.34  5232.3  448.90  5323.8  452.46  5417.3  454.63  5438.1  454.71
  5481.7  454.09  5517.1  454.65  5531.6  454.16  5581.5  453.95  5677.6  456.00
#Mann=3,-1,0
  4709.2    0.05       0  4996.2    0.03       0  5002.2    0.05       0
Bank Sta=4956.3,5015.6
Exp/Cntr=0.3,0.1

Type RM Length L Ch R = 1,45895,508,508,508
BEGIN DESCRIPTION:
LITTLE CANEY CREEK 46.0
END DESCRIPTION:
XS GIS Cut Line= 3
      2863602.95      7031221.36      2863144.61      7031018.24
      2862808.05      7031015.65
#Sta/Elev= 30
  4429.0  457.36  4554.2  456.14  4569.0  455.58  4590.8  453.70  4634.9  453.31
  4681.5  454.14  4722.1  453.23  4751.3  451.88  4803.3  450.99  4809.6  450.07
  4873.2  445.79  4932.6  445.02  4939.9  444.43  4949.9  445.08  4979.9  444.82
  4983.4  443.29  4996.7  436.90  4997.2  436.10  5002.7  436.10  5003.2  436.90
  5009.9  438.87  5019.3  443.29  5039.9  444.27  5119.9  444.91  5190.0  445.90
  5200.0  446.51  5210.0  447.91  5250.0  457.60  5260.0  459.38  5266.9  459.34
#Mann=3,-1,0
  4429.0    0.05       0  4996.7    0.03       0  5003.2    0.05       0
Bank Sta=4983.4,5019.3
Exp/Cntr=0.3,0.1

Type RM Length L Ch R = 1,45387,416,416,416
BEGIN DESCRIPTION:
LITTLE CANEY CREEK 45.0
END DESCRIPTION:
XS GIS Cut Line= 3
      2863717.56      7030979.20      2863194.09      7030533.86
      2862674.99      7030475.00
#Sta/Elev= 30
  4404.8  456.21  4494.8  455.30  4622.2  452.93  4671.6  449.93  4707.9  450.03
  4749.6  447.49  4806.7  446.61  4835.3  443.42  4920.2  443.39  4942.3  441.80
  4948.4  438.90  4962.6  442.20  4970.4  443.28  4991.2  442.97  4995.6  435.39
  4996.1  434.59  5001.7  434.59  5002.2  435.39  5012.1  436.24  5019.8  441.18
  5023.1  441.80  5034.1  442.92  5101.2  442.08  5121.3  443.32  5161.6  443.23
  5262.3  447.23  5390.3  457.42  5403.1  457.78  5453.5  461.62  5614.5  471.21
#Mann=3,-1,0
  4404.8    0.05       0  4995.6    0.03       0  5002.2    0.05       0
Bank Sta=4942.3,5023.1
Exp/Cntr=0.3,0.1

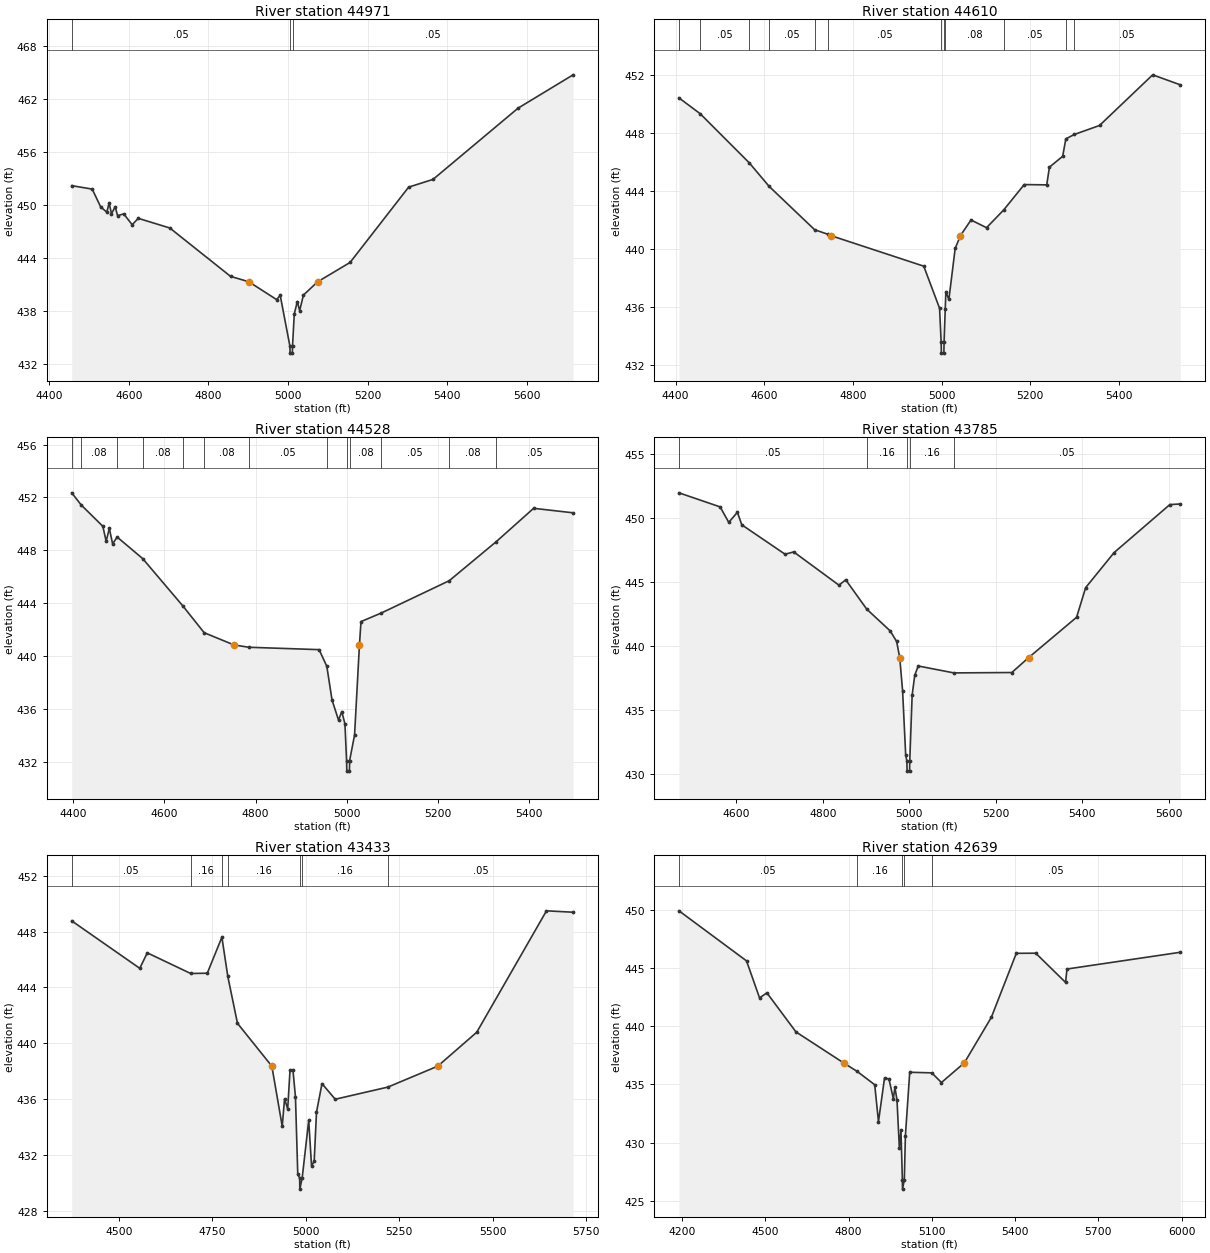
Type RM Length L Ch R = 1,44971,361,361,361
BEGIN DESCRIPTION:
LITTLE CANEY CREEK 44.0
END DESCRIPTION:
XS GIS Cut Line= 3
      2863959.75      7030549.50      2863423.06      7030216.48
      2862813.88      7030067.71
#Sta/Elev= 30
  4456.9  452.18  4508.3  451.79  4529.5  449.78  4544.9  449.18  4550.8  450.20
  4556.7  449.02  4566.1  449.78  4572.0  448.78  4587.4  448.99  4608.6  447.76
  4624.0  448.48  4703.1  447.39  4855.5  441.92  4901.7  441.30  4971.2  439.29
  4980.3  439.77  5004.6  434.03  5005.1  433.23  5010.7  433.23  5011.2  434.03
  5015.6  437.66  5023.2  439.07  5029.1  438.04  5038.6  439.80  5074.2  441.30
  5155.7  443.49  5302.7  452.01  5364.0  452.89  5577.5  460.95  5715.6  464.72
#Mann=3,-1,0
  4456.9    0.05       0  5004.6    0.03       0  5011.2    0.05       0
Bank Sta=4901.7,5074.2
Exp/Cntr=0.3,0.1

Type RM Length L Ch R = 1,44610,82,82,82
BEGIN DESCRIPTION:
Mapping XS fe709740
END DESCRIPTION:
XS GIS Cut Line= 5
      2864087.31      7030385.40      2864040.45      7030289.07
      2863553.47      7029835.94      2863470.13      7029713.55
      2863467.53      7029502.65
#Sta/Elev= 30
  4407.6  450.39  4455.5  449.30  4566.4  445.91  4610.9  444.30  4713.7  441.31
  4743.3  441.00  4749.8  440.91  4959.9  438.80  4995.6  435.90  4999.1  433.61
  4999.6  432.81  5005.3  432.81  5005.8  433.61  5008.4  435.84  5009.8  437.04
  5016.6  436.51  5030.8  440.02  5042.8  440.91  5066.5  441.98  5101.6  441.45
  5140.5  442.68  5186.6  444.42  5237.4  444.40  5243.5  445.62  5273.4  446.37
  5280.5  447.57  5299.5  447.87  5356.5  448.49  5476.5  451.98  5538.9  451.29
#Mann=12,-1,0
  4407.6    0.08       0  4455.5    0.05       0  4566.4    0.08       0
  4610.9    0.05       0  4713.7    0.08       0  4743.3    0.05       0
  4999.1    0.04       0  5005.8    0.05       0  5008.4    0.08       0
  5140.5    0.05       0  5280.5    0.08       0  5299.5    0.05       0
Bank Sta=4749.8,5042.8
Exp/Cntr=0.3,0.1

Type RM Length L Ch R = 1,44528,743,743,743
BEGIN DESCRIPTION:
LITTLE CANEY CREEK 43.0
END DESCRIPTION:
XS GIS Cut Line= 4
      2864181.05      7030325.51      2863871.18      7030026.05
      2863566.49      7029734.38      2863558.72      7029488.52
#Sta/Elev= 30
  4397.2  452.35  4418.0  451.43  4465.4  449.82  4472.6  448.69  4479.6  449.66
  4486.8  448.49  4496.7  449.01  4552.7  447.38  4641.0  443.79  4687.4  441.78
  4752.4  440.86  4785.3  440.68  4939.3  440.50  4956.2  439.24  4967.6  436.70
  4981.8  435.18  4989.0  435.82  4995.9  434.89  4999.5  432.12  5000.0  431.32
  5005.7  431.32  5006.2  432.12  5017.0  434.05  5027.7  440.86  5031.1  442.62
  5075.1  443.26  5224.5  445.71  5327.8  448.67  5409.4  451.18  5495.9  450.84
#Mann=13,-1,0
  4397.2    0.05       0  4418.0    0.08       0  4496.7    0.05       0
  4552.7    0.08       0  4641.0    0.05       0  4687.4    0.08       0
  4785.3    0.05       0  4956.2    0.08       0  4999.5    0.07       0
  5006.2    0.08       0  5075.1    0.05       0  5224.5    0.08       0
  5327.8    0.05       0
Bank Sta=4752.4,5027.7
Exp/Cntr=0.3,0.1

Type RM Length L Ch R = 1,43785,352,352,352
BEGIN DESCRIPTION:
LITTLE CANEY CREEK 42.0
END DESCRIPTION:
XS GIS Cut Line= 3
      2864381.59      7030249.98      2864403.82      7029804.67
      2863813.87      7029403.64
#Sta/Elev= 30
  4467.6  451.97  4562.7  450.87  4582.7  449.66  4602.7  450.45  4612.8  449.47
  4712.9  447.17  4732.9  447.35  4837.5  444.75  4853.1  445.17  4901.6  442.88
  4955.8  441.18  4970.8  440.35  4978.0  439.08  4984.6  436.50  4991.8  431.44
  4994.5  431.01  4995.0  430.21  5000.7  430.21  5001.2  431.01  5006.7  436.16
  5012.8  437.72  5020.8  438.43  5103.2  437.89  5237.2  437.92  5275.8  439.08
  5386.9  442.24  5407.9  444.56  5473.7  447.30  5602.5  451.05  5626.8  451.10
#Mann=5,-1,0
  4467.6    0.05       0  4901.6    0.16       0  4994.5    0.07       0
  5001.2    0.16       0  5103.2    0.05       0
Bank Sta=4978,5275.8
Exp/Cntr=0.3,0.1

Type RM Length L Ch R = 1,43433,794,794,794
BEGIN DESCRIPTION:
LITTLE CANEY CREEK 41.0
END DESCRIPTION:
XS GIS Cut Line= 4
      2864540.45      7030096.36      2864589.93      7029549.49
      2864422.41      7029323.09      2863943.18      7029145.25
#Sta/Elev= 30
  4373.7  448.77  4555.8  445.37  4575.9  446.48  4692.0  445.00  4736.5  445.02
  4775.6  447.60  4791.4  444.79  4817.3  441.43  4909.3  438.36  4937.1  434.05
  4943.3  436.02  4951.7  435.30  4957.9  438.05  4965.7  438.11  4972.5  436.16
  4978.7  430.60  4983.7  430.35  4984.2  429.55  4990.5  430.35  5008.0  434.48
  5015.5  431.23  5022.6  431.53  5028.8  435.06  5043.5  437.11  5078.9  435.99
  5219.7  436.86  5353.3  438.36  5457.7  440.79  5644.4  449.49  5715.6  449.39
#Mann=7,-1,0
  4373.7    0.05       0  4692.0    0.16       0  4775.6    0.05       0
  4791.4    0.16       0  4983.7    0.07       0  4990.5    0.16       0
  5219.7    0.05       0
Bank Sta=4909.3,5353.3
Exp/Cntr=0.3,0.1

Type RM Length L Ch R = 1,42639,522,522,522
BEGIN DESCRIPTION:
LITTLE CANEY CREEK 40.0
END DESCRIPTION:
XS GIS Cut Line= 4
      2865071.70      7029832.79      2864991.84      7029228.59
      2864829.58      7028939.50      2863964.07      7028959.50
#Sta/Elev= 30
  4189.1  449.91  4432.5  445.61  4479.4  442.43  4506.0  442.86  4610.5  439.51
  4782.0  436.85  4830.8  436.12  4894.4  434.97  4908.0  431.80  4929.7  435.53
  4945.7  435.47  4961.6  433.77  4967.3  434.75  4974.7  433.66  4983.3  429.51
  4989.0  431.08  4994.1  426.80  4994.6  426.00  5001.1  426.80  5005.0  430.58
  5020.6  436.04  5099.9  435.99  5134.9  435.16  5217.4  436.85  5314.7  440.76
  5404.7  446.26  5474.7  446.27  5582.2  443.76  5587.2  444.91  5995.8  446.35
#Mann=5,-1,0
  4189.1    0.05       0  4830.8    0.16       0  4994.1    0.07       0
  5001.1    0.16       0  5099.9    0.05       0
Bank Sta=4782,5217.4
Exp/Cntr=0.3,0.1