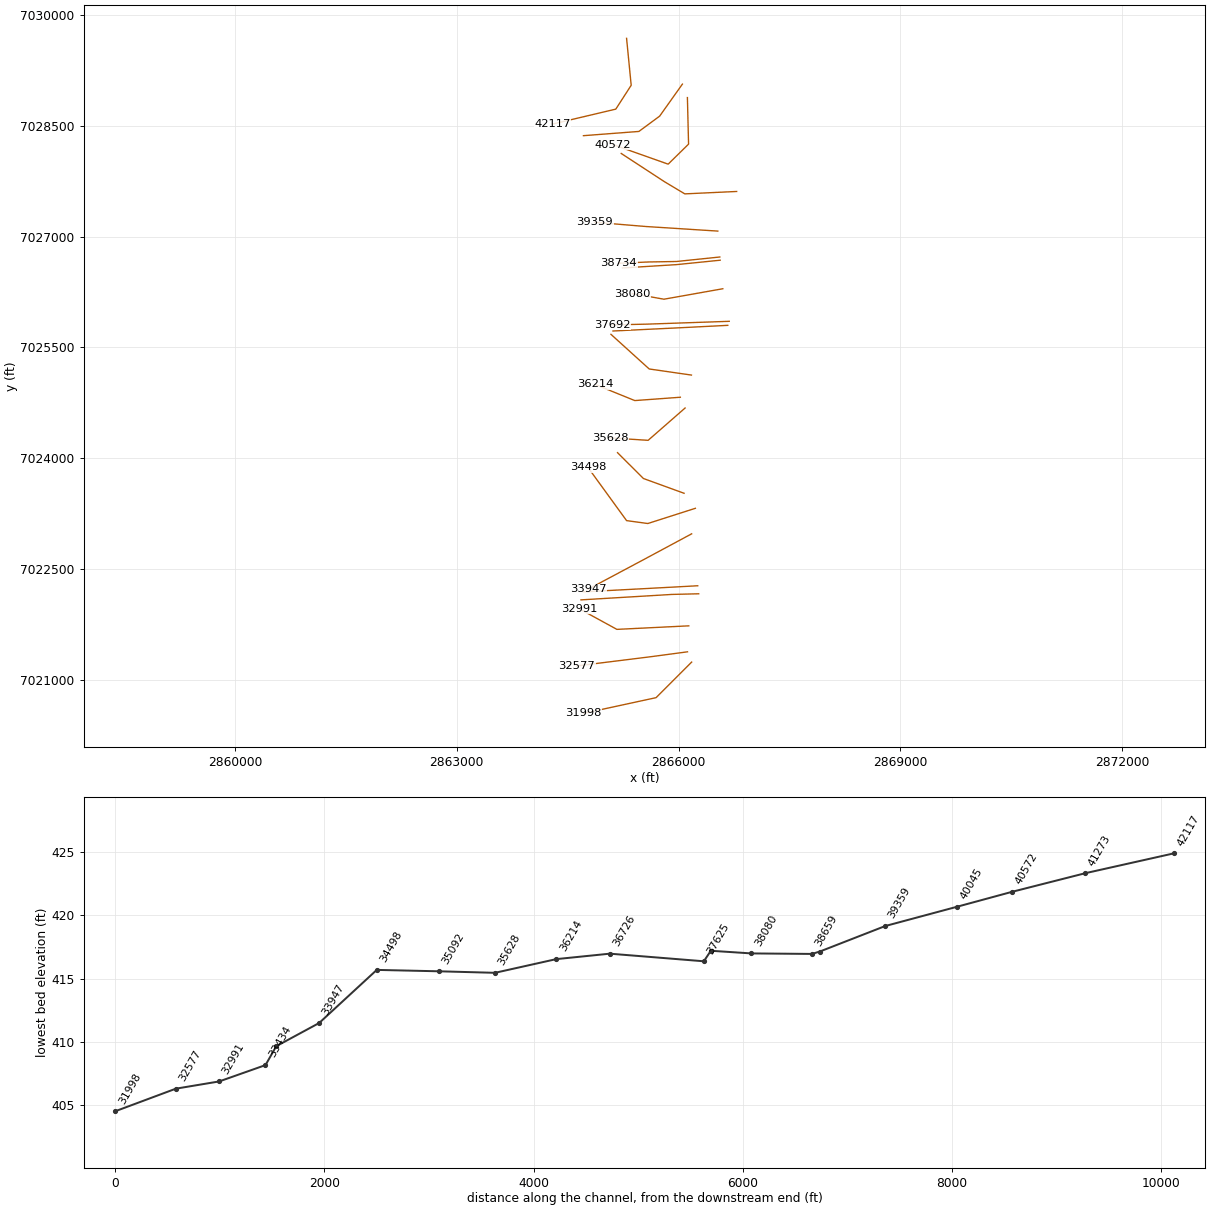
HEC-RAS study LITTLE CANEY CREEK.prj: LITTLE CANEY CREEK Base Level Engineering

--- LITTLE CANEY CREEK.g01 (geometry) --- (continued)

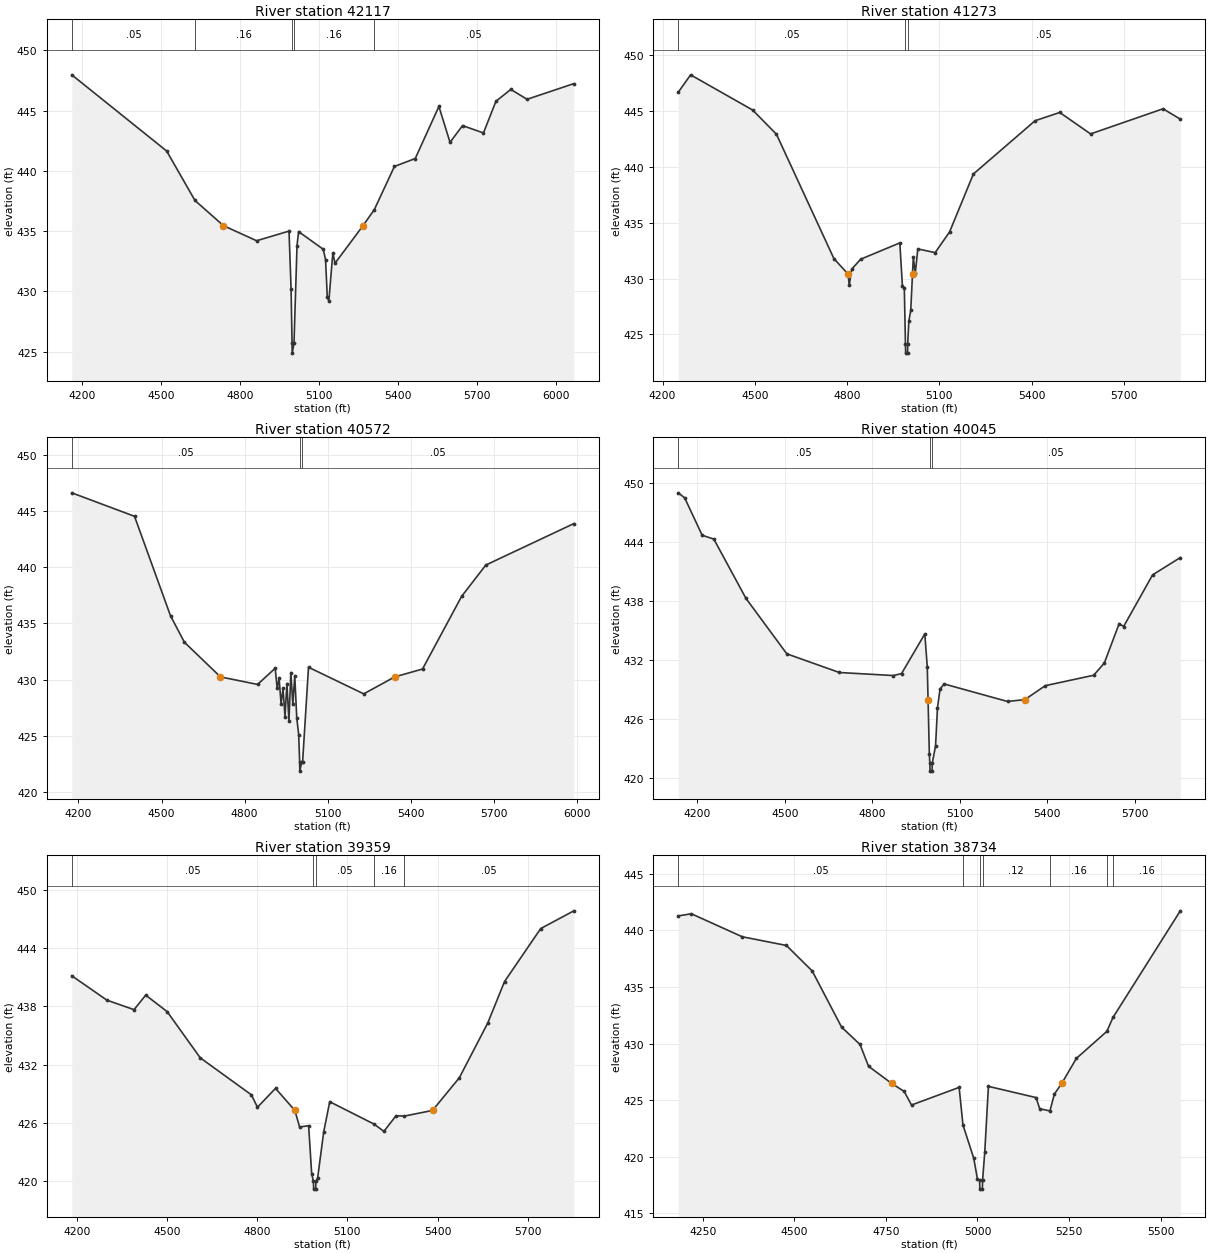
Type RM Length L Ch R = 1,42117,844,844,844
BEGIN DESCRIPTION:
LITTLE CANEY CREEK 39.0
END DESCRIPTION:
XS GIS Cut Line= 4
      2865297.39      7029683.45      2865359.89      7029048.04
      2865151.56      7028725.12      2864292.20      7028522.00
#Sta/Elev= 30
  4160.2  447.96  4520.4  441.64  4627.8  437.54  4736.1  435.45  4861.8  434.20
  4984.8  435.00  4992.7  430.18  4996.4  425.68  4996.9  424.88  5003.7  425.68
  5015.2  433.80  5021.1  434.96  5114.9  433.49  5123.6  432.62  5130.0  429.57
  5136.0  429.19  5151.2  433.21  5159.3  432.33  5265.7  435.45  5308.6  436.78
  5384.9  440.36  5464.0  441.02  5553.8  445.34  5596.0  442.36  5643.5  443.75
  5722.9  443.14  5770.3  445.77  5826.8  446.75  5888.4  445.93  6066.0  447.23
#Mann=5,-1,0
  4160.2    0.05       0  4627.8    0.16       0  4996.4    0.07       0
  5003.7    0.16       0  5308.6    0.05       0
Bank Sta=4736.1,5265.7
Exp/Cntr=0.3,0.1

Type RM Length L Ch R = 1,41273,701,701,701
BEGIN DESCRIPTION:
LITTLE CANEY CREEK 38.0
END DESCRIPTION:
XS GIS Cut Line= 4
      2866052.60      7029063.66      2865744.80      7028630.37
      2865464.06      7028423.04      2864714.03      7028365.75
#Sta/Elev= 30
  4250.8  446.68  4291.0  448.24  4492.7  445.09  4570.2  442.92  4757.1  431.78
  4803.1  430.40  4806.9  429.39  4814.8  430.84  4844.1  431.73  4971.4  433.19
  4979.8  429.35  4986.0  429.17  4989.7  424.12  4990.3  423.32  4996.5  423.32
  4997.0  424.12  5000.7  426.18  5006.9  427.15  5012.6  430.40  5015.3  431.92
  5021.5  430.46  5029.9  432.65  5086.3  432.32  5133.3  434.18  5210.6  439.36
  5411.2  444.13  5491.4  444.87  5591.7  442.95  5827.5  445.20  5883.5  444.27
#Mann=3,-1,0
  4250.8    0.05       0  4989.7    0.03       0  4997.0    0.05       0
Bank Sta=4803.1,5012.6
Exp/Cntr=0.3,0.1

Type RM Length L Ch R = 1,40572,527,527,527
BEGIN DESCRIPTION:
LITTLE CANEY CREEK 37.0
END DESCRIPTION:
XS GIS Cut Line= 4
      2866120.31      7028881.39      2866135.93      7028251.16
      2865859.89      7027980.33      2865109.97      7028245.93
#Sta/Elev= 30
  4176.0  446.63  4402.5  444.54  4532.5  435.68  4582.5  433.33  4712.9  430.24
  4846.8  429.57  4910.4  431.01  4917.6  429.23  4924.6  430.11  4931.7  427.83
  4938.7  429.22  4945.8  426.70  4952.8  429.65  4960.0  426.31  4967.0  430.63
  4974.1  427.79  4981.1  430.34  4988.3  426.60  4995.3  425.08  4998.8  422.65
  4999.3  421.85  5006.1  422.65  5009.4  422.66  5030.7  431.10  5230.1  428.73
  5341.9  430.24  5442.3  430.94  5583.5  437.41  5670.9  440.20  5988.7  443.89
#Mann=3,-1,0
  4176.0    0.05       0  4998.8    0.03       0  5006.1    0.05       0
Bank Sta=4712.9,5341.9
Exp/Cntr=0.3,0.1

Type RM Length L Ch R = 1,40045,686,686,686
BEGIN DESCRIPTION:
LITTLE CANEY CREEK 36.0
END DESCRIPTION:
XS GIS Cut Line= 4
      2866786.97      7027610.54      2866085.13      7027577.93
      2865813.02      7027740.75      2865225.03      7028124.98
#Sta/Elev= 30
  4134.2  449.00  4156.2  448.49  4216.3  444.68  4256.3  444.29  4366.4  438.26
  4506.6  432.61  4686.8  430.71  4871.9  430.40  4900.1  430.60  4979.9  434.63
  4988.4  431.30  4991.1  427.95  4995.5  422.38  4997.2  421.47  4997.9  420.67
  5004.7  420.67  5005.4  421.47  5016.8  423.24  5023.4  427.13  5032.4  429.05
  5046.7  429.54  5263.6  427.76  5323.0  427.95  5393.3  429.37  5559.2  430.43
  5595.4  431.66  5646.7  435.69  5661.8  435.39  5761.3  440.65  5856.3  442.41
#Mann=3,-1,0
  4134.2    0.05       0  4997.2    0.03       0  5005.4    0.05       0
Bank Sta=4991.1,5323
Exp/Cntr=0.3,0.1

Type RM Length L Ch R = 1,39359,625,625,625
BEGIN DESCRIPTION:
LITTLE CANEY CREEK 35.0
END DESCRIPTION:
XS GIS Cut Line= 3
      2866531.73      7027074.08      2865552.60      7027136.58
      2864865.11      7027193.87
#Sta/Elev= 30
  4182.6  441.17  4299.6  438.65  4389.8  437.67  4428.7  439.17  4500.0  437.47
  4610.2  432.70  4780.5  428.88  4800.6  427.60  4860.7  429.55  4925.1  427.27
  4940.9  425.56  4970.9  425.70  4981.0  420.76  4986.9  419.95  4987.6  419.15
  4994.4  419.15  4995.1  419.95  5001.0  420.32  5021.0  425.04  5041.1  428.17
  5188.7  425.86  5221.5  425.11  5261.7  426.72  5289.8  426.69  5383.2  427.27
  5472.4  430.64  5566.9  436.28  5622.9  440.57  5743.3  446.04  5853.6  447.87
#Mann=5,-1,0
  4182.6    0.05       0  4986.9    0.03       0  4995.1    0.05       0
  5188.7    0.16       0  5289.8    0.05       0
Bank Sta=4925.1,5383.2
Exp/Cntr=0.3,0.1

Type RM Length L Ch R = 1,38734,75,75,75
BEGIN DESCRIPTION:
Mapping XS fc6d1700
END DESCRIPTION:
XS GIS Cut Line= 4
      2866558.71      7026723.39      2865972.74      7026662.62
      2865595.13      7026656.11      2865191.48      7026638.75
#Sta/Elev= 30
  4183.1  441.28  4219.0  441.47  4357.7  439.44  4478.4  438.67  4548.8  436.42
  4629.2  431.45  4679.5  429.92  4702.6  428.00  4765.4  426.49  4800.0  425.77
  4820.0  424.57  4950.0  426.13  4960.5  422.81  4990.0  419.86  5000.0  418.02
  5005.8  417.94  5006.6  417.14  5013.4  417.14  5014.1  417.94  5020.0  420.42
  5030.0  426.22  5160.0  425.23  5170.0  424.24  5197.9  424.05  5210.1  425.54
  5230.4  426.49  5270.1  428.69  5353.4  431.08  5370.1  432.31  5553.9  441.73
#Mann=7,-1,0
  4183.1    0.05       0  4960.5    0.12       0  5005.8    0.07       0
  5014.1    0.12       0  5197.9    0.16       0  5353.4    0.05       0
  5370.1    0.16       0
Bank Sta=4765.4,5230.4
Exp/Cntr=0.3,0.1

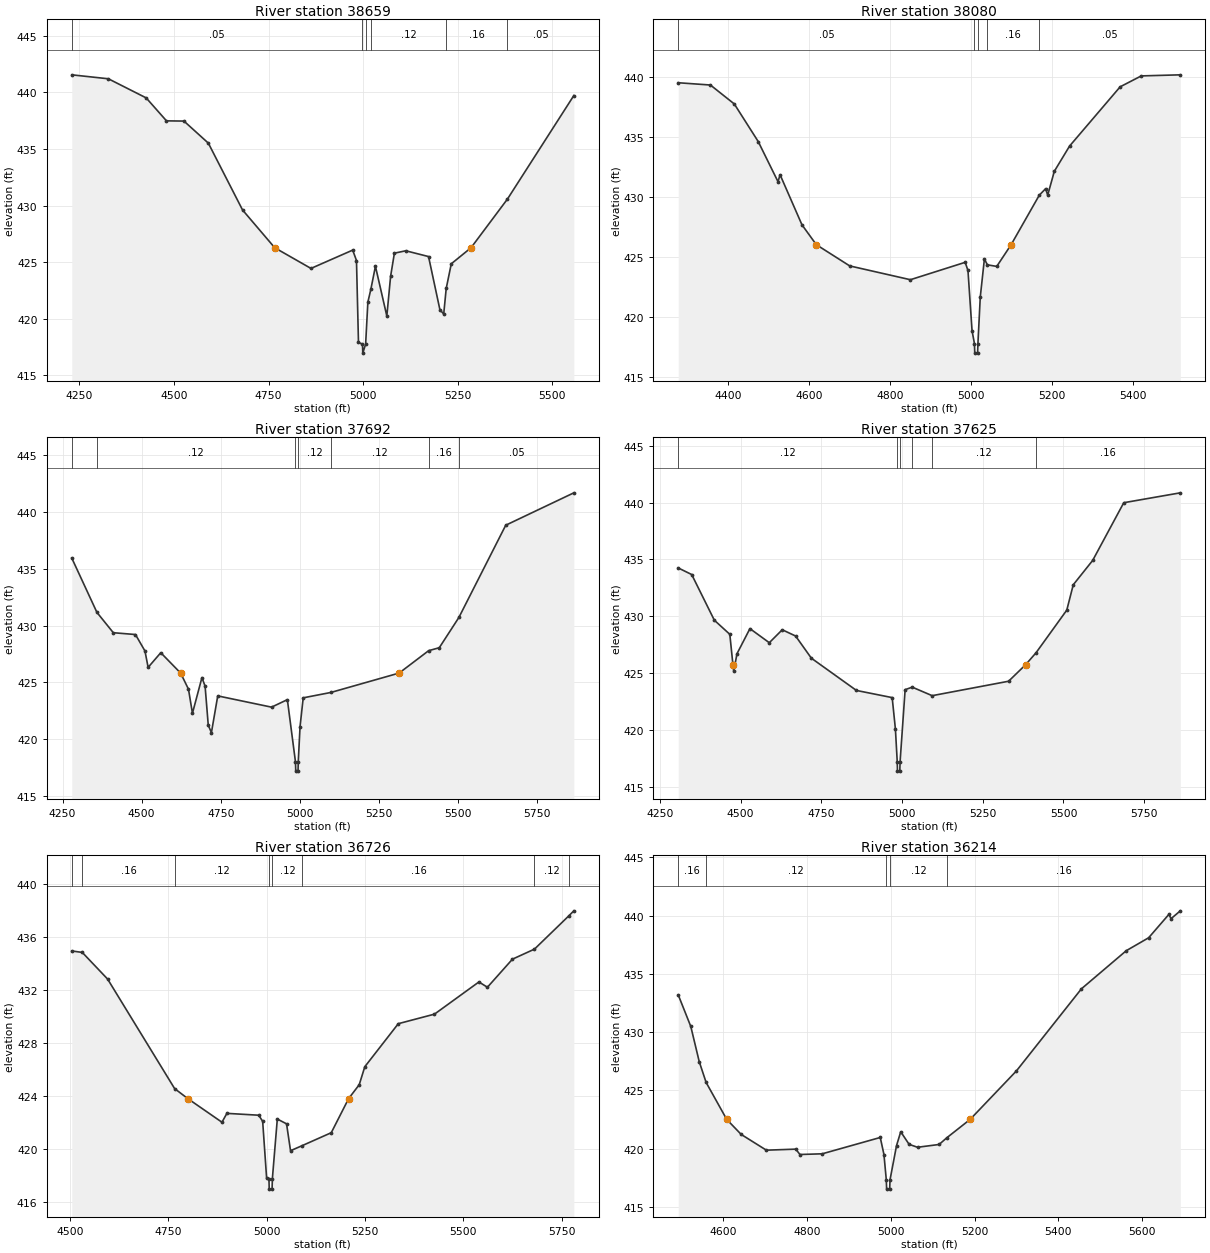
Type RM Length L Ch R = 1,38659,579,579,579
BEGIN DESCRIPTION:
LITTLE CANEY CREEK 34.0
END DESCRIPTION:
XS GIS Cut Line= 3
      2866563.91      7026679.99      2865972.74      7026620.09
      2865241.83      7026574.95
#Sta/Elev= 30
  4230.2  441.56  4326.9  441.21  4426.8  439.52  4480.4  437.49  4526.6  437.47
  4591.0  435.52  4681.4  429.61  4766.4  426.27  4862.2  424.44  4972.4  426.06
  4982.4  425.14  4987.7  417.89  4998.3  417.75  4999.1  416.95  5006.6  417.75
  5012.5  421.46  5020.3  422.58  5032.5  424.63  5062.6  420.23  5072.6  423.75
  5082.6  425.79  5112.7  426.00  5172.8  425.49  5202.9  420.78  5212.9  420.41
  5219.5  422.67  5232.9  424.85  5285.1  426.27  5381.4  430.58  5556.7  439.73
#Mann=6,-1,0
  4230.2    0.05       0  4998.3    0.03       0  5006.6    0.05       0
  5020.3    0.12       0  5219.5    0.16       0  5381.4    0.05       0
Bank Sta=4766.4,5285.1
Exp/Cntr=0.3,0.1

Type RM Length L Ch R = 1,38080,388,388,388
BEGIN DESCRIPTION:
LITTLE CANEY CREEK 33.0
END DESCRIPTION:
XS GIS Cut Line= 3
      2866599.44      7026293.69      2865802.97      7026152.12
      2865378.66      7026227.48
#Sta/Elev= 30
  4276.1  439.53  4355.6  439.34  4414.6  437.76  4473.6  434.63  4522.5  431.28
  4527.6  431.86  4581.6  427.69  4617.1  426.03  4699.6  424.26  4849.4  423.11
  4984.7  424.56  4991.6  423.88  5001.7  418.85  5007.6  417.79  5008.4  416.99
  5015.4  416.99  5016.2  417.79  5022.0  421.67  5032.2  424.84  5039.6  424.35
  5062.7  424.22  5098.2  426.03  5167.8  430.16  5183.4  430.70  5188.5  430.16
  5204.9  432.15  5242.5  434.25  5367.4  439.19  5419.6  440.10  5516.0  440.19
#Mann=5,-1,0
  4276.1    0.05       0  5007.6    0.03       0  5016.2    0.05       0
  5039.6    0.16       0  5167.8    0.05       0
Bank Sta=4617.1,5098.2
Exp/Cntr=0.3,0.1

Type RM Length L Ch R = 1,37692,67,67,67
BEGIN DESCRIPTION:
Mapping XS b34199f3
END DESCRIPTION:
XS GIS Cut Line= 3
      2866686.23      7025852.72      2865571.70      7025814.53
      2865099.70      7025804.12
#Sta/Elev= 30
  4279.2  435.95  4358.7  431.17  4410.5  429.38  4480.6  429.22  4510.6  427.77
  4520.6  426.33  4560.6  427.62  4623.3  425.83  4648.2  424.41  4660.7  422.29
  4690.7  425.43  4700.7  424.68  4710.7  421.24  4720.7  420.59  4740.7  423.82
  4910.8  422.83  4960.8  423.49  4986.5  418.00  4987.3  417.20  4994.5  417.20
  4995.2  418.00  5000.9  421.12  5010.9  423.65  5097.9  424.12  5314.2  425.83
  5407.5  427.80  5441.1  428.06  5503.0  430.72  5651.2  438.84  5866.5  441.69
#Mann=7,-1,0
  4279.2    0.05       0  4358.7    0.12       0  4986.5    0.07       0
  4995.2    0.12       0  5097.9    0.12       0  5407.5    0.16       0
  5503.0    0.05       0
Bank Sta=4623.3,5314.2
Exp/Cntr=0.3,0.1

Type RM Length L Ch R = 1,37625,899,899,899
BEGIN DESCRIPTION:
LITTLE CANEY CREEK 32.0
END DESCRIPTION:
XS GIS Cut Line= 3
      2866666.68      7025798.24      2866111.15      7025770.03
      2865113.87      7025721.56
#Sta/Elev= 30
  4307.1  434.25  4348.8  433.67  4418.9  429.65  4466.8  428.41  4476.5  425.73
  4479.0  425.16  4489.0  426.70  4529.1  428.91  4589.1  427.67  4629.2  428.81
  4670.5  428.26  4719.3  426.31  4858.9  423.47  4969.6  422.84  4979.6  420.07
  4985.3  417.17  4986.0  416.37  4993.2  416.37  4994.0  417.17  5009.7  423.54
  5031.7  423.76  5093.4  423.01  5330.0  424.28  5382.6  425.73  5414.9  426.78
  5510.3  430.54  5530.3  432.77  5590.4  434.91  5686.7  439.99  5861.8  440.86
#Mann=6,-1,0
  4307.1    0.12       0  4985.3    0.07       0  4994.0    0.12       0
  5031.7    0.16       0  5093.4    0.12       0  5414.9    0.16       0
Bank Sta=4476.5,5382.6
Exp/Cntr=0.3,0.1

Type RM Length L Ch R = 1,36726,512,512,512
BEGIN DESCRIPTION:
LITTLE CANEY CREEK 31.0
END DESCRIPTION:
XS GIS Cut Line= 3
      2866175.05      7025124.99      2865603.48      7025207.67
      2865086.16      7025676.39
#Sta/Elev= 30
  4505.1  434.95  4531.8  434.84  4596.1  432.83  4766.4  424.56  4799.6  423.81
  4886.7  422.02  4899.2  422.69  4980.0  422.55  4990.1  422.09  5000.2  417.78
  5006.0  417.77  5006.8  416.97  5014.0  416.97  5014.8  417.77  5027.3  422.26
  5050.8  421.90  5060.9  419.87  5091.0  420.26  5164.4  421.23  5208.6  423.81
  5235.4  424.85  5249.6  426.21  5334.7  429.46  5426.6  430.18  5539.5  432.61
  5561.1  432.21  5624.7  434.33  5680.7  435.09  5767.2  437.58  5780.7  437.98
#Mann=8,-1,0
  4505.1    0.05       0  4531.8    0.16       0  4766.4    0.12       0
  5006.0    0.07       0  5014.8    0.12       0  5091.0    0.16       0
  5680.7    0.12       0  5767.2    0.16       0
Bank Sta=4799.6,5208.6
Exp/Cntr=0.3,0.1

Type RM Length L Ch R = 1,36214,586,586,586
BEGIN DESCRIPTION:
LITTLE CANEY CREEK 30.0
END DESCRIPTION:
XS GIS Cut Line= 3
      2866024.96      7024825.00      2865408.50      7024779.81
      2864870.27      7024998.57
#Sta/Elev= 30
  4492.0  433.20  4522.0  430.49  4542.1  427.48  4558.6  425.69  4607.8  422.52
  4642.4  421.23  4702.5  419.88  4772.7  419.97  4782.7  419.51  4835.9  419.57
  4974.5  420.97  4983.3  419.51  4988.9  417.34  4989.7  416.54  4997.0  416.54
  4997.8  417.34  5013.4  420.28  5023.4  421.46  5043.4  420.38  5063.5  420.13
  5115.0  420.37  5133.6  420.95  5189.1  422.52  5299.7  426.68  5454.9  433.72
  5562.0  436.99  5615.5  438.10  5663.7  440.10  5669.1  439.74  5691.1  440.41
#Mann=5,-1,0
  4492.0    0.16       0  4558.6    0.12       0  4988.9    0.07       0
  4997.8    0.12       0  5133.6    0.16       0
Bank Sta=4607.8,5189.1
Exp/Cntr=0.3,0.1

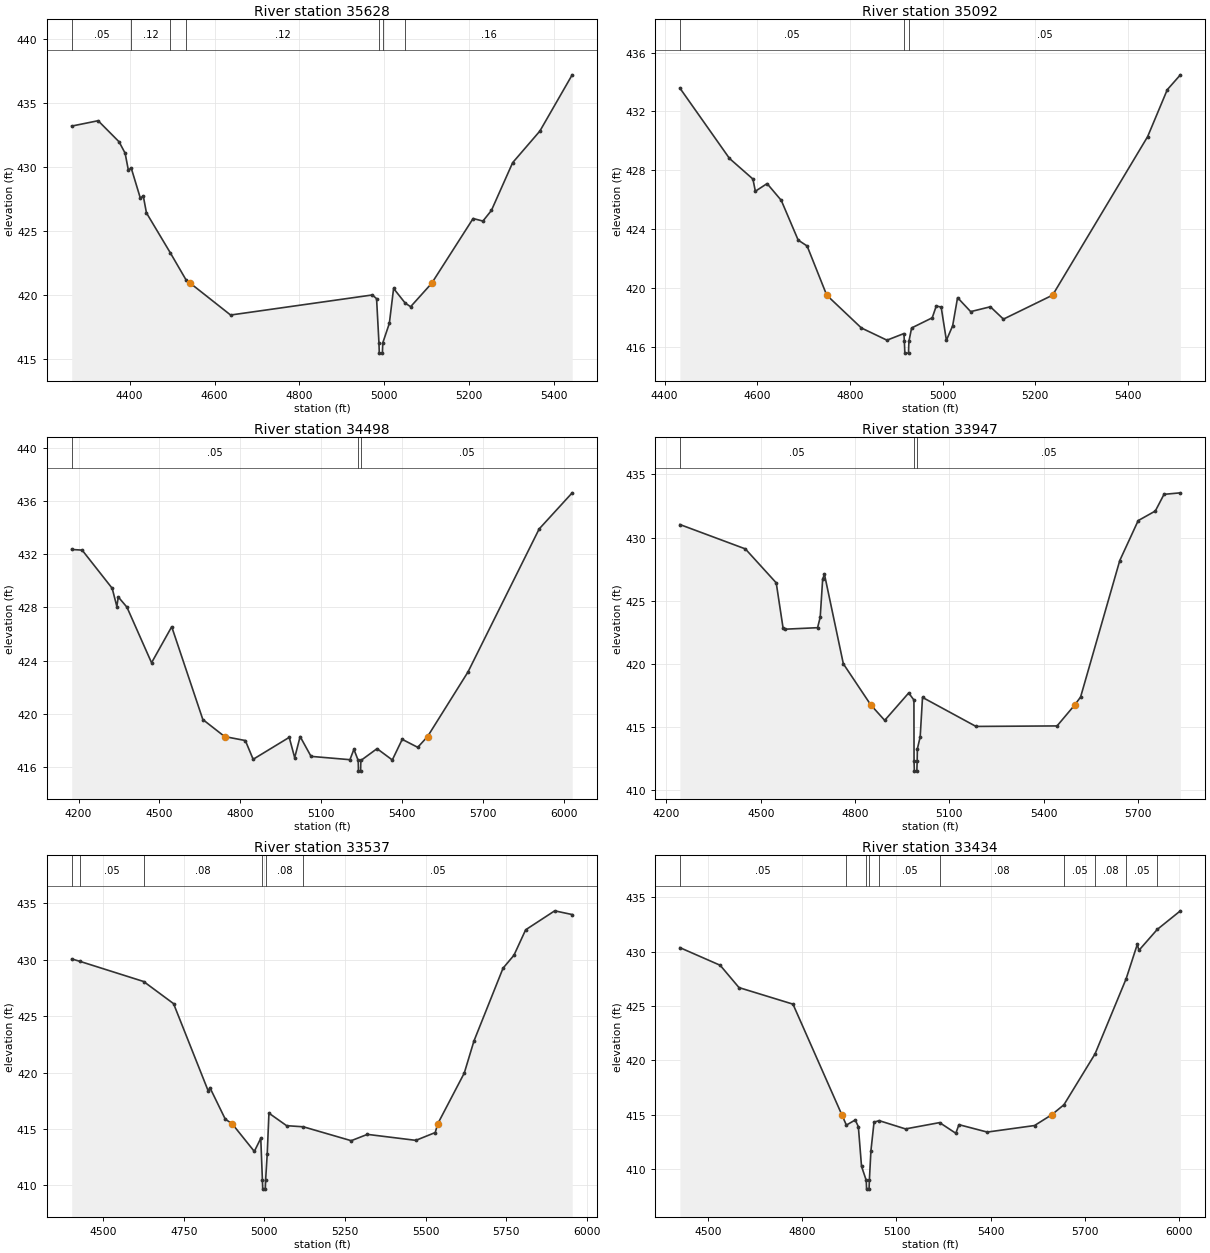
Type RM Length L Ch R = 1,35628,536,536,536
BEGIN DESCRIPTION:
LITTLE CANEY CREEK 29.0
END DESCRIPTION:
XS GIS Cut Line= 3
      2866089.04      7024679.10      2865589.06      7024241.62
      2865075.00      7024275.00
#Sta/Elev= 30
  4263.4  433.22  4325.7  433.64  4375.1  431.99  4389.3  431.10  4396.9  429.78
  4403.7  429.94  4425.3  427.57  4432.0  427.77  4439.6  426.43  4495.4  423.33
  4532.7  421.20  4543.2  420.92  4637.9  418.44  4971.9  420.01  4981.9  419.72
  4987.5  416.26  4988.3  415.46  4995.6  415.46  4996.5  416.26  5012.0  417.79
  5022.0  420.52  5049.2  419.38  5062.1  419.09  5111.7  420.92  5209.4  425.99
  5232.5  425.79  5252.5  426.62  5302.6  430.36  5366.7  432.83  5442.9  437.23
#Mann=7,-1,0
  4263.4    0.05       0  4403.7    0.12       0  4495.4    0.16       0
  4532.7    0.12       0  4987.5    0.07       0  4996.5    0.12       0
  5049.2    0.16       0
Bank Sta=4543.2,5111.7
Exp/Cntr=0.3,0.1

Type RM Length L Ch R = 1,35092,594,594,594
BEGIN DESCRIPTION:
LITTLE CANEY CREEK 28.0
END DESCRIPTION:
XS GIS Cut Line= 3
      2866074.97      7023525.01      2865525.00      7023725.00
      2865174.98      7024075.02
#Sta/Elev= 30
  4432.9  433.59  4539.9  428.81  4590.5  427.41  4595.8  426.58  4621.1  427.10
  4651.7  425.96  4688.2  423.26  4707.5  422.86  4749.8  419.52  4824.6  417.29
  4879.8  416.46  4916.4  416.91  4917.4  416.38  4918.4  415.58  4926.3  415.58
  4927.2  416.38  4933.0  417.29  4977.5  417.98  4986.2  418.78  4996.8  418.71
  5008.1  416.45  5021.6  417.44  5032.2  419.35  5060.5  418.40  5103.0  418.73
  5131.2  417.89  5237.3  419.52  5442.4  430.29  5484.8  433.48  5513.1  434.49
#Mann=3,-1,0
  4432.9    0.05       0  4917.4    0.03       0  4927.2    0.05       0
Bank Sta=4749.8,5237.3
Exp/Cntr=0.3,0.1

Type RM Length L Ch R = 1,34498,551,551,551
BEGIN DESCRIPTION:
LITTLE CANEY CREEK 27.0
END DESCRIPTION:
XS GIS Cut Line= 4
      2866227.96      7023321.48      2865584.77      7023115.57
      2865297.39      7023154.81      2864775.00      7023875.01
#Sta/Elev= 30
  4174.6  432.36  4213.4  432.31  4324.7  429.44  4342.0  428.07  4347.2  428.79
  4379.4  428.02  4470.6  423.84  4545.3  426.55  4660.7  419.57  4741.5  418.29
  4818.2  417.99  4847.2  416.58  4980.9  418.23  5001.1  416.70  5021.3  418.29
  5061.7  416.80  5205.9  416.55  5220.6  417.33  5236.6  416.49  5237.5  415.69
  5245.4  415.69  5246.4  416.49  5306.4  417.38  5362.9  416.53  5399.7  418.08
  5457.2  417.48  5493.6  418.29  5643.5  423.15  5907.1  433.90  6029.7  436.62
#Mann=3,-1,0
  4174.6    0.05       0  5236.6    0.03       0  5246.4    0.05       0
Bank Sta=4741.5,5493.6
Exp/Cntr=0.3,0.1

Type RM Length L Ch R = 1,33947,410,410,410
BEGIN DESCRIPTION:
LITTLE CANEY CREEK 26.0
END DESCRIPTION:
XS GIS Cut Line= 3
      2866177.89      7022976.07      2865525.00      7022625.00
      2864775.00      7022225.00
#Sta/Elev= 30
  4243.1  431.03  4451.2  429.10  4549.4  426.41  4571.3  422.81  4577.0  422.74
  4680.9  422.86  4689.2  423.68  4697.1  426.72  4702.8  427.08  4762.8  420.00
  4850.2  416.74  4894.3  415.52  4970.6  417.69  4987.2  417.13  4987.6  412.30
  4988.6  411.50  4996.5  411.50  4997.5  412.30  4998.2  413.27  5007.1  414.21
  5014.5  417.34  5184.5  415.04  5442.3  415.08  5498.4  416.74  5517.1  417.37
  5641.7  428.18  5700.2  431.34  5754.7  432.10  5782.3  433.42  5834.4  433.54
#Mann=3,-1,0
  4243.1    0.05       0  4987.6    0.03       0  4997.5    0.05       0
Bank Sta=4850.2,5498.4
Exp/Cntr=0.3,0.1

Type RM Length L Ch R = 1,33537,103,103,103
BEGIN DESCRIPTION:
Mapping XS 381b93b6
END DESCRIPTION:
XS GIS Cut Line= 3
      2866260.36      7022272.92      2865535.49      7022233.86
      2864710.86      7022190.46
#Sta/Elev= 30
  4402.7  430.06  4427.6  429.85  4625.7  428.06  4718.5  426.10  4826.2  418.35
  4831.2  418.66  4878.8  415.87  4900.1  415.46  4968.9  413.01  4988.9  414.17
  4994.0  410.47  4995.0  409.67  5002.9  409.67  5003.9  410.47  5008.9  412.78
  5014.2  416.40  5069.0  415.29  5121.0  415.19  5269.3  413.96  5319.4  414.52
  5469.6  413.99  5529.7  414.68  5537.6  415.46  5619.8  419.95  5649.8  422.79
  5740.0  429.24  5773.9  430.39  5810.1  432.64  5900.2  434.32  5954.4  433.99
#Mann=6,-1,0
  4402.7    0.08       0  4427.6    0.05       0  4625.7    0.08       0
  4994.0    0.07       0  5003.9    0.08       0  5121.0    0.05       0
Bank Sta=4900.1,5537.6
Exp/Cntr=0.3,0.1

Type RM Length L Ch R = 1,33434,443,443,443
BEGIN DESCRIPTION:
LITTLE CANEY CREEK 25.0
END DESCRIPTION:
XS GIS Cut Line= 3
      2866273.37      7022164.42      2865913.09      7022155.73
      2864680.48      7022081.95
#Sta/Elev= 30
  4409.7  430.36  4538.1  428.74  4598.1  426.69  4770.1  425.17  4925.7  415.02
  4940.3  414.06  4968.5  414.53  4978.5  413.92  4988.6  410.28  5003.7  408.98
  5004.7  408.18  5012.6  408.18  5013.6  408.98  5018.6  411.71  5028.5  414.33
  5044.8  414.47  5128.8  413.71  5237.5  414.29  5289.1  413.31  5299.1  414.10
  5389.3  413.42  5540.0  414.02  5595.3  415.02  5633.8  415.93  5732.9  420.60
  5832.0  427.50  5867.7  430.67  5872.7  430.11  5931.1  432.03  6004.9  433.74
#Mann=10,-1,0
  4409.7    0.05       0  4940.3    0.16       0  5003.7    0.07       0
  5013.6    0.16       0  5044.8    0.05       0  5237.5    0.08       0
  5633.8    0.05       0  5732.9    0.08       0  5832.0    0.05       0
  5931.1    0.08       0
Bank Sta=4925.7,5595.3
Exp/Cntr=0.3,0.1

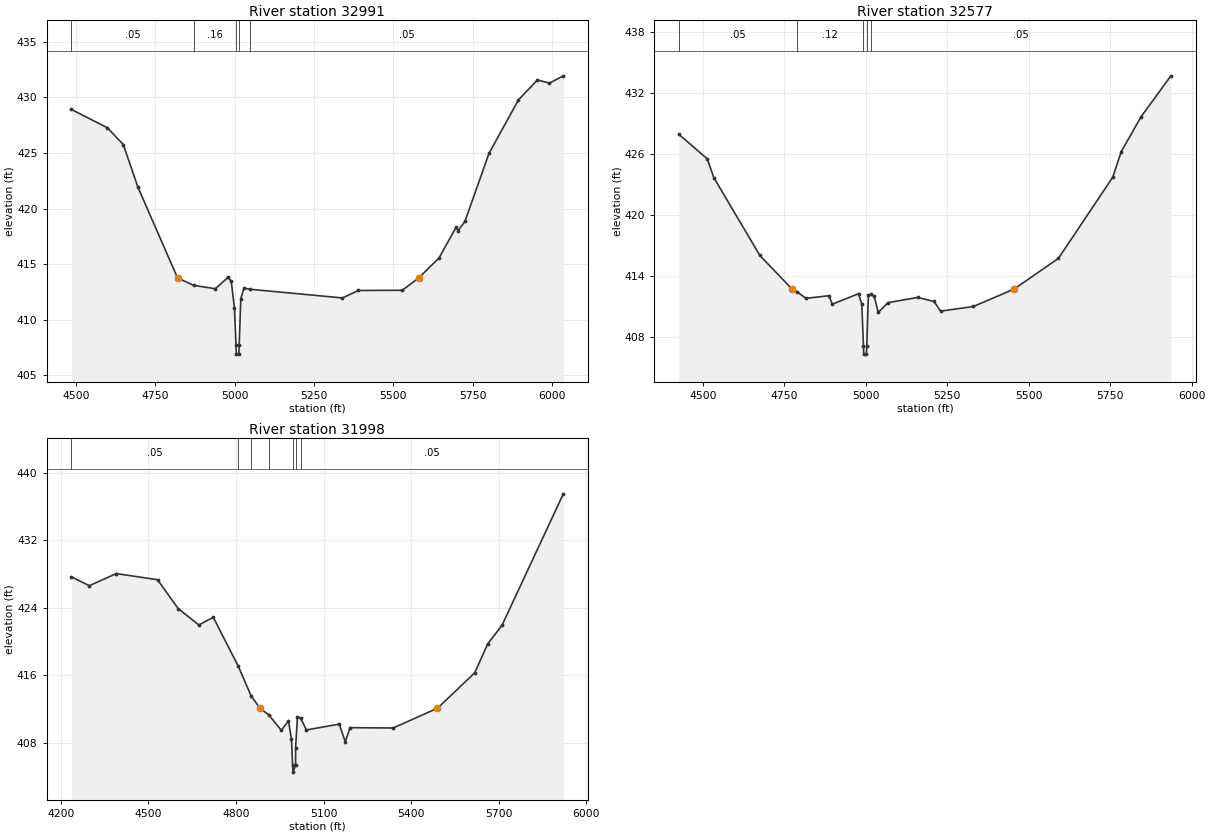
Type RM Length L Ch R = 1,32991,414,414,414
BEGIN DESCRIPTION:
LITTLE CANEY CREEK 24.0
END DESCRIPTION:
XS GIS Cut Line= 3
      2866138.77      7021730.39      2865166.56      7021682.64
      2864659.80      7021959.85
#Sta/Elev= 30
  4484.5  428.93  4598.4  427.27  4648.5  425.76  4694.9  421.90  4819.6  413.75
  4870.4  413.08  4938.8  412.78  4978.9  413.81  4988.9  413.43  4998.9  411.02
  5003.9  407.69  5004.9  406.89  5012.9  406.89  5013.8  407.69  5018.9  411.89
  5028.9  412.83  5048.3  412.73  5339.3  411.95  5389.4  412.62  5528.0  412.64
  5579.6  413.75  5643.8  415.55  5697.9  418.34  5703.6  417.99  5725.4  418.84
  5801.3  424.97  5894.2  429.79  5954.0  431.58  5991.9  431.29  6035.5  431.95
#Mann=5,-1,0
  4484.5    0.05       0  4870.4    0.16       0  5003.9    0.07       0
  5013.8    0.16       0  5048.3    0.05       0
Bank Sta=4819.6,5579.6
Exp/Cntr=0.3,0.1

Type RM Length L Ch R = 1,32577,579,579,579
BEGIN DESCRIPTION:
Mapping XS 93d7a570
END DESCRIPTION:
XS GIS Cut Line= 3
      2866121.44      7021378.83      2865635.31      7021313.72
      2864623.98      7021187.85
#Sta/Elev= 30
  4426.7  427.95  4513.9  425.54  4534.1  423.68  4675.3  416.03  4773.7  412.73
  4789.1  412.47  4816.6  411.81  4887.2  412.07  4897.3  411.23  4977.9  412.27
  4988.0  411.22  4993.1  407.12  4994.1  406.32  5002.1  406.32  5003.1  407.12
  5008.2  412.11  5015.9  412.19  5025.8  412.03  5038.4  410.43  5068.6  411.39
  5159.3  411.90  5209.7  411.50  5229.9  410.55  5330.6  411.01  5455.7  412.73
  5591.3  415.75  5757.9  423.73  5784.1  426.26  5844.6  429.67  5936.3  433.71
#Mann=5,-1,0
  4426.7    0.05       0  4789.1    0.12       0  4993.1    0.07       0
  5003.1    0.12       0  5015.9    0.05       0
Bank Sta=4773.7,5455.7
Exp/Cntr=0.3,0.1

Type RM Length L Ch R = 1,31998,406,406,406
BEGIN DESCRIPTION:
LITTLE CANEY CREEK 23.0
END DESCRIPTION:
XS GIS Cut Line= 3
      2866177.88      7021239.97      2865696.08      7020758.17
      2864715.14      7020545.48
#Sta/Elev= 30
  4236.1  427.69  4298.2  426.63  4390.1  428.07  4531.6  427.34  4602.3  423.92
  4673.0  421.98  4722.5  422.89  4807.6  417.12  4852.0  413.58  4882.6  412.11
  4914.5  411.26  4955.2  409.50  4980.0  410.59  4990.2  408.49  4994.3  405.34
  4995.3  404.54  5004.3  405.34  5004.4  407.44  5010.7  411.11  5021.8  410.91
  5041.4  409.54  5153.9  410.23  5174.4  408.13  5190.9  409.81  5338.4  409.77
  5490.3  412.11  5618.1  416.32  5662.2  419.73  5711.3  421.94  5921.2  437.52
#Mann=7,-1,0
  4236.1    0.05       0  4807.6    0.12       0  4852.0    0.05       0
  4914.5    0.16       0  4994.3    0.07       0  5004.3    0.16       0
  5021.8    0.05       0
Bank Sta=4882.6,5490.3
Exp/Cntr=0.3,0.1