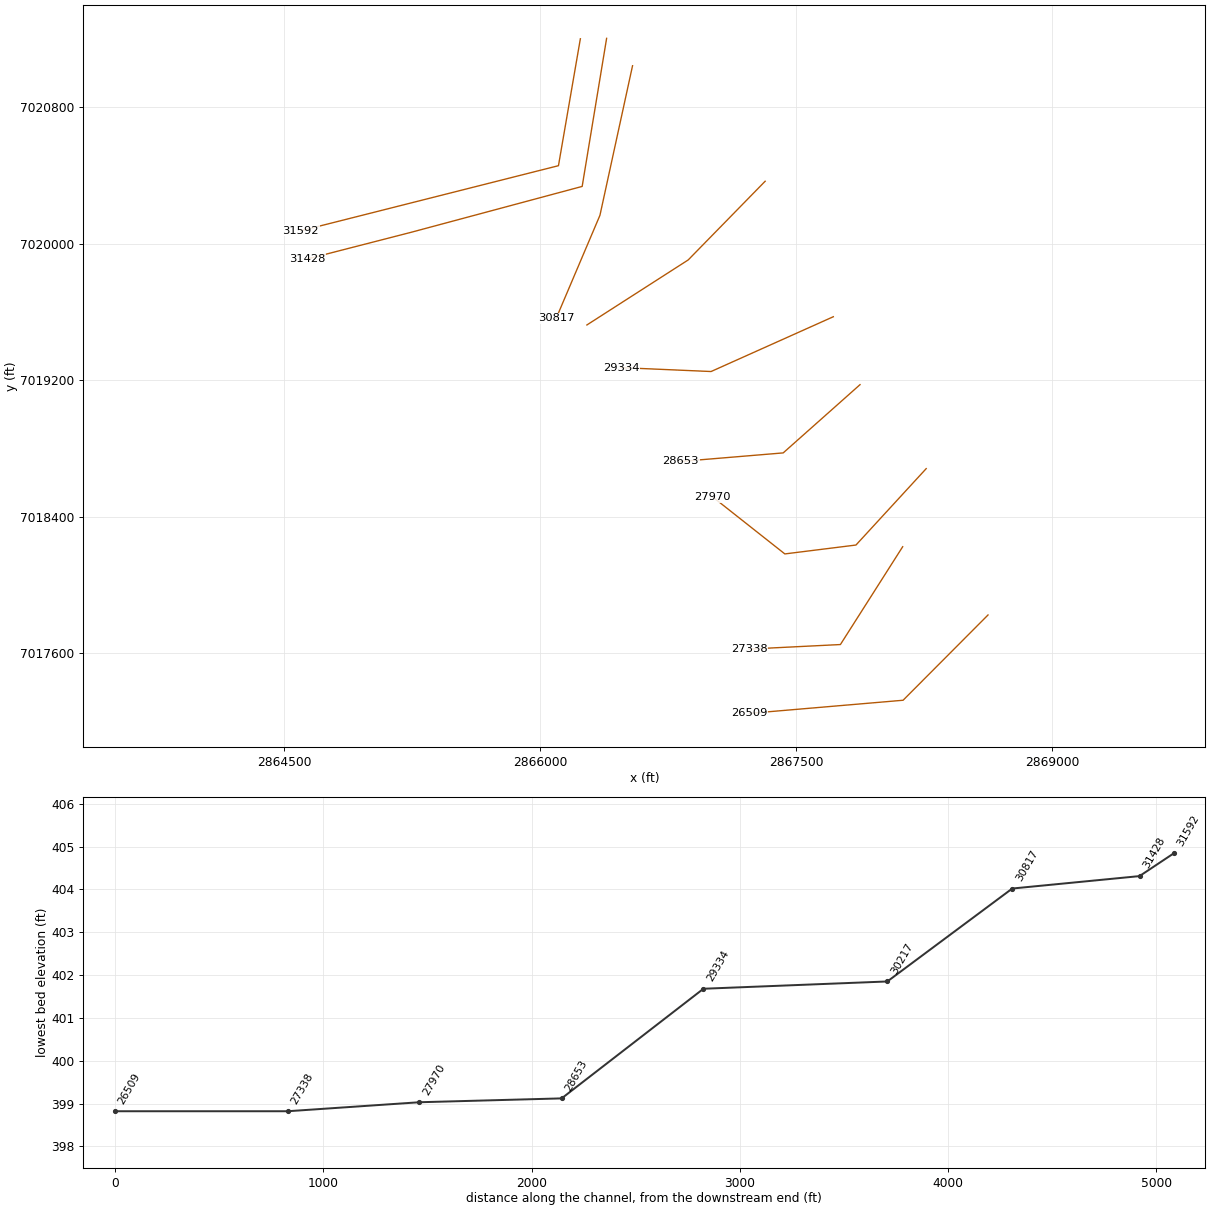
HEC-RAS study LITTLE CANEY CREEK.prj: LITTLE CANEY CREEK Base Level Engineering

--- LITTLE CANEY CREEK.g01 (geometry) --- (continued)

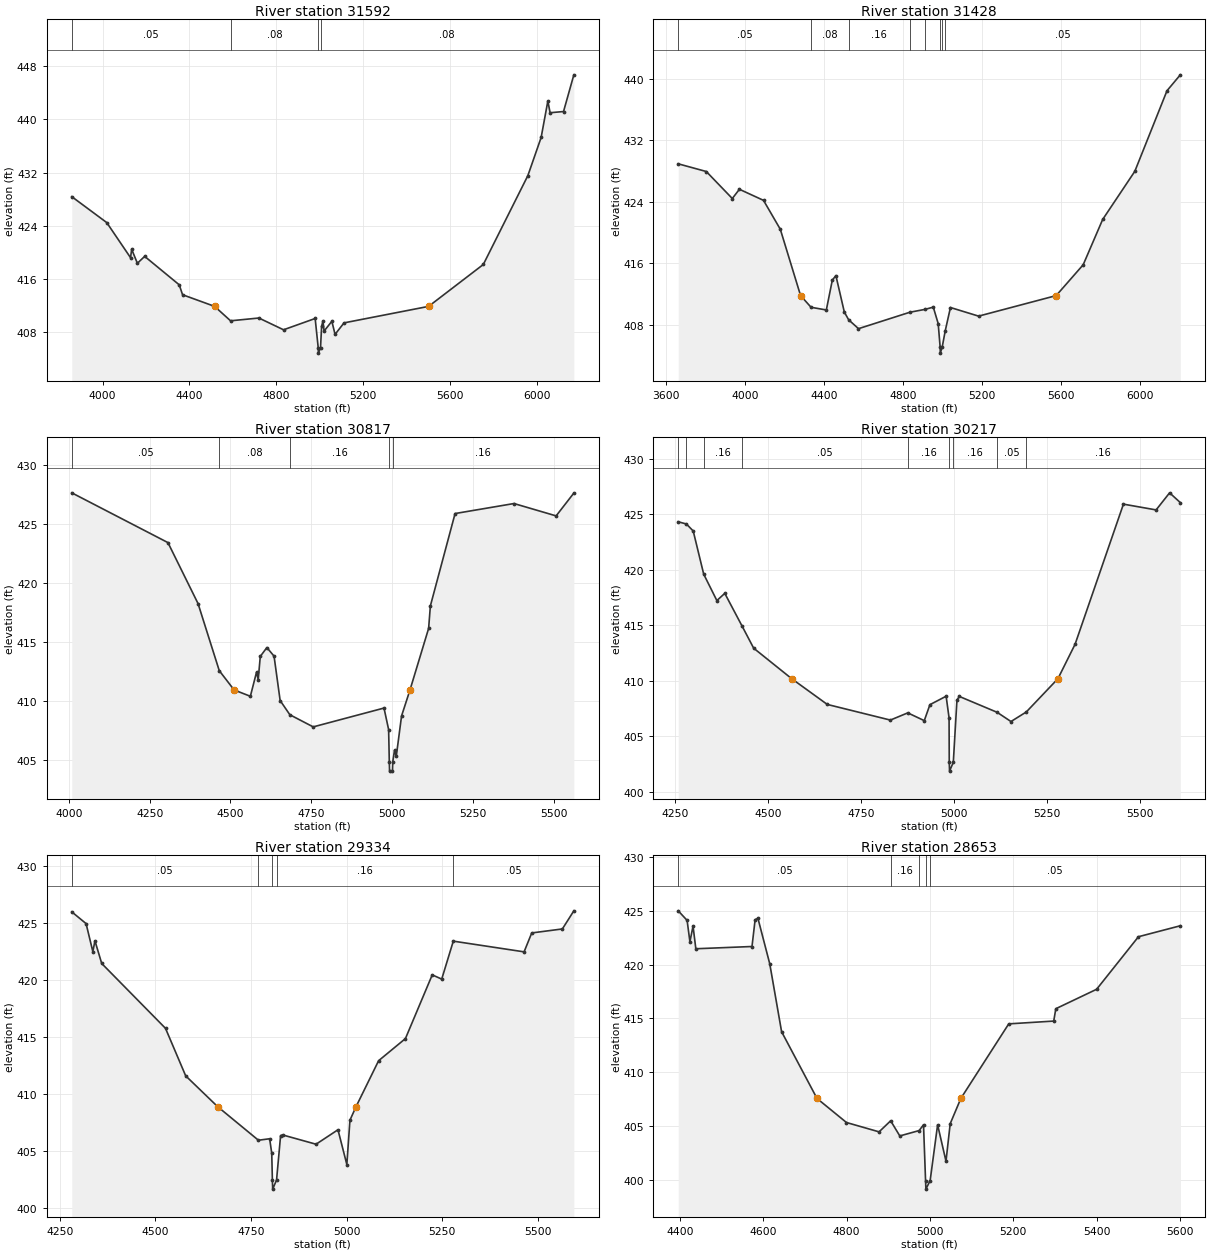
Type RM Length L Ch R = 1,31592,164,164,164
BEGIN DESCRIPTION:
LITTLE CANEY CREEK 22.0
END DESCRIPTION:
XS GIS Cut Line= 3
      2866236.70      7021202.75      2866108.40      7020458.69
      2864598.96      7020076.99
#Sta/Elev= 30
  3858.3  428.37  4019.4  424.47  4129.0  419.19  4134.1  420.46  4160.4  418.35
  4194.0  419.39  4353.2  415.11  4368.5  413.62  4516.1  411.87  4589.5  409.70
  4720.0  410.12  4833.5  408.35  4979.1  410.05  4993.2  405.64  4994.0  404.84
  5003.8  405.64  5008.8  408.86  5014.9  409.67  5020.1  408.15  5056.0  409.63
  5070.7  407.66  5112.0  409.39  5501.5  411.87  5753.4  418.17  5958.5  431.53
  6019.7  437.27  6050.6  442.75  6060.9  440.99  6122.8  441.17  6170.3  446.69
#Mann=4,-1,0
  3858.3    0.05       0  4589.5    0.08       0  4993.2    0.07       0
  5003.8    0.08       0
Bank Sta=4516.1,5501.5
Exp/Cntr=0.3,0.1

Type RM Length L Ch R = 1,31428,611,611,611
BEGIN DESCRIPTION:
Mapping XS f9cab44b
END DESCRIPTION:
XS GIS Cut Line= 4
      2866390.53      7021205.26      2866247.29      7020337.16
      2865244.69      7020068.06      2864638.54      7019912.19
#Sta/Elev= 30
  3661.8  428.92  3804.0  427.92  3935.7  424.41  3971.7  425.61  4093.9  424.17
  4179.0  420.41  4281.7  411.79  4334.7  410.27  4412.1  409.92  4442.5  413.80
  4460.6  414.39  4503.3  409.65  4525.3  408.64  4575.1  407.49  4836.0  409.63
  4910.8  409.99  4954.0  410.29  4978.9  408.15  4988.7  405.11  4989.6  404.31
  4999.3  405.11  5014.8  407.24  5041.0  410.24  5183.6  409.12  5576.7  411.79
  5713.6  415.80  5812.3  421.69  5975.2  427.95  6138.1  438.42  6205.6  440.49
#Mann=8,-1,0
  3661.8    0.05       0  4334.7    0.08       0  4525.3    0.16       0
  4836.0    0.08       0  4910.8    0.16       0  4988.7    0.07       0
  4999.3    0.16       0  5014.8    0.05       0
Bank Sta=4281.7,5576.7
Exp/Cntr=0.3,0.1

Type RM Length L Ch R = 1,30817,600,600,600
BEGIN DESCRIPTION:
LITTLE CANEY CREEK 21.0
END DESCRIPTION:
XS GIS Cut Line= 3
      2866542.43      7021044.62      2866351.46      7020167.89
      2866095.38      7019564.58
#Sta/Elev= 30
  4009.2  427.67  4306.6  423.44  4399.7  418.26  4465.3  412.56  4511.2  410.92
  4561.5  410.38  4580.6  412.43  4585.8  411.80  4592.2  413.77  4612.6  414.52
  4634.8  413.79  4653.6  410.02  4683.7  408.81  4755.9  407.78  4974.8  409.38
  4989.1  407.55  4991.2  404.82  4992.0  404.02  5001.0  404.02  5001.9  404.82
  5007.3  405.80  5012.7  405.27  5029.1  408.71  5055.2  410.92  5112.8  416.15
  5118.2  418.06  5194.6  425.91  5376.8  426.76  5507.1  425.71  5561.9  427.65
#Mann=5,-1,0
  4009.2    0.05       0  4465.3    0.08       0  4683.7    0.16       0
  4991.2    0.07       0  5001.9    0.16       0
Bank Sta=4511.2,5055.2
Exp/Cntr=0.3,0.1

Type RM Length L Ch R = 1,30217,883,883,883
BEGIN DESCRIPTION:
LITTLE CANEY CREEK 20.0
END DESCRIPTION:
XS GIS Cut Line= 3
      2867319.37      7020367.57      2866868.40      7019906.13
      2866274.97      7019524.98
#Sta/Elev= 30
  4258.9  424.32  4280.9  424.12  4299.2  423.49  4327.4  419.60  4362.8  417.22
  4384.1  417.87  4430.5  414.93  4461.8  412.93  4564.1  410.18  4659.8  407.86
  4829.5  406.45  4876.3  407.10  4920.7  406.40  4935.9  407.84  4979.5  408.60
  4987.4  406.65  4987.9  402.65  4988.7  401.85  4998.8  402.65  5008.6  408.26
  5015.1  408.58  5116.7  407.15  5153.9  406.32  5195.1  407.18  5280.2  410.18
  5326.3  413.28  5456.4  425.91  5544.3  425.39  5580.6  426.93  5609.4  426.05
#Mann=9,-1,0
  4258.9    0.05       0  4280.9    0.08       0  4327.4    0.16       0
  4430.5    0.05       0  4876.3    0.16       0  4987.9    0.07       0
  4998.8    0.16       0  5116.7    0.05       0  5195.1    0.16       0
Bank Sta=4564.1,5280.2
Exp/Cntr=0.3,0.1

Type RM Length L Ch R = 1,29334,681,681,681
BEGIN DESCRIPTION:
LITTLE CANEY CREEK 19.0
END DESCRIPTION:
XS GIS Cut Line= 3
      2867718.68      7019573.29      2867002.50      7019252.09
      2866475.01      7019275.00
#Sta/Elev= 30
  4281.3  426.01  4318.7  424.98  4336.4  422.52  4341.9  423.47  4359.6  421.48
  4526.4  415.79  4579.2  411.62  4663.0  408.91  4769.4  405.97  4798.7  406.10
  4804.2  404.84  4805.9  402.48  4806.7  401.68  4816.8  402.48  4827.4  406.38
  4833.3  406.43  4920.1  405.62  4977.4  406.89  5000.6  403.84  5008.7  407.73
  5024.6  408.91  5083.7  412.95  5153.8  414.89  5223.9  420.48  5248.7  420.11
  5279.0  423.44  5464.1  422.50  5484.1  424.16  5564.2  424.51  5594.2  426.10
#Mann=5,-1,0
  4281.3    0.05       0  4769.4    0.16       0  4805.9    0.07       0
  4816.8    0.16       0  5279.0    0.05       0
Bank Sta=4663,5024.6
Exp/Cntr=0.3,0.1

Type RM Length L Ch R = 1,28653,683,683,683
BEGIN DESCRIPTION:
LITTLE CANEY CREEK 18.0
END DESCRIPTION:
XS GIS Cut Line= 3
      2867875.00      7019175.00      2867425.00      7018775.00
      2866824.96      7018725.00
#Sta/Elev= 30
  4396.4  425.02  4417.7  424.13  4424.4  422.14  4431.9  423.60  4438.6  421.49
  4573.3  421.70  4580.8  424.19  4587.5  424.33  4615.9  420.09  4644.3  413.77
  4729.2  407.56  4799.9  405.32  4878.1  404.45  4905.9  405.48  4927.8  404.07
  4974.2  404.57  4984.7  405.11  4989.6  399.92  4990.4  399.12  5000.6  399.92
  5018.5  405.11  5038.6  401.72  5048.7  405.21  5074.2  407.56  5189.1  414.50
  5297.0  414.76  5302.0  415.91  5399.9  417.72  5500.2  422.61  5600.6  423.63
#Mann=5,-1,0
  4396.4    0.05       0  4905.9    0.16       0  4974.2    0.05       0
  4989.6    0.03       0  5000.6    0.05       0
Bank Sta=4729.2,5074.2
Exp/Cntr=0.3,0.1

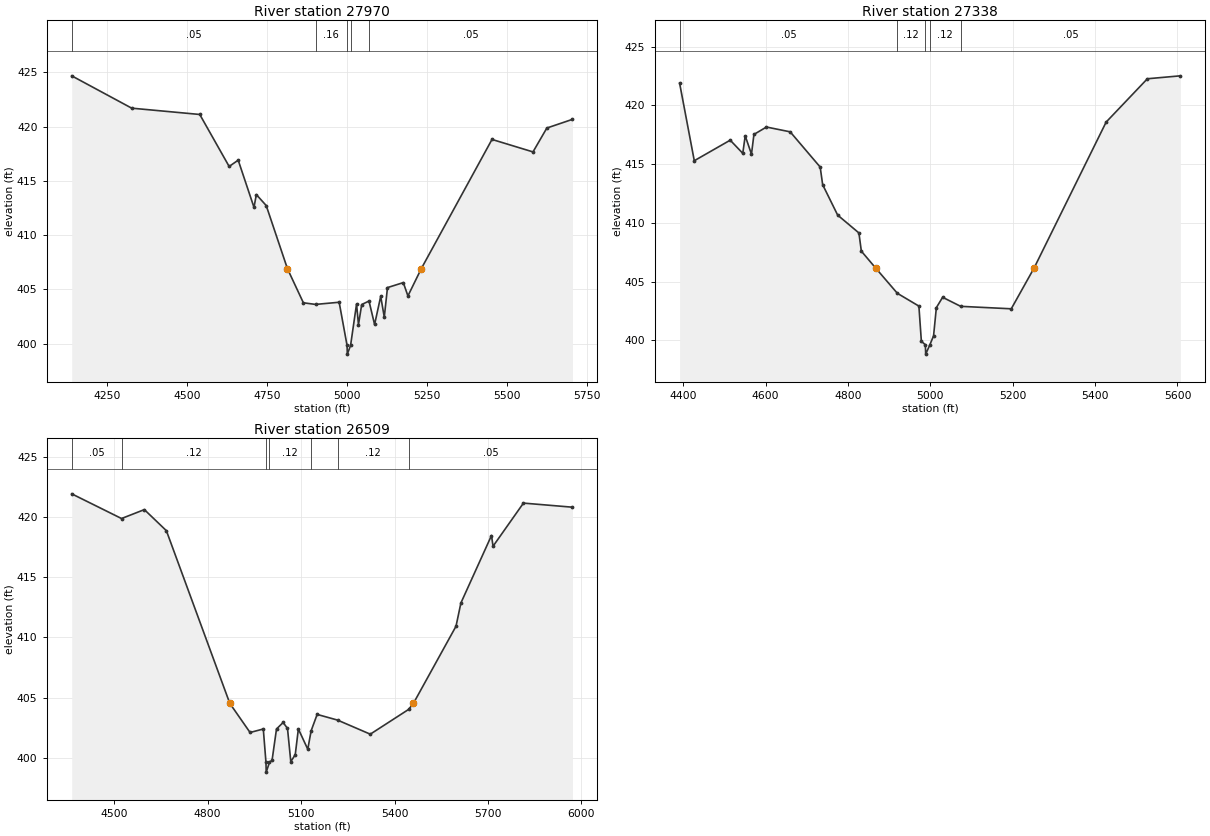
Type RM Length L Ch R = 1,27970,632,632,632
BEGIN DESCRIPTION:
LITTLE CANEY CREEK 17.0
END DESCRIPTION:
XS GIS Cut Line= 4
      2868262.75      7018682.82      2867851.28      7018234.90
      2867434.62      7018182.82      2867012.74      7018516.15
#Sta/Elev= 30
  4139.9  424.67  4327.6  421.69  4540.3  421.11  4632.2  416.32  4660.5  416.90
  4709.9  412.55  4717.2  413.73  4748.1  412.72  4814.5  406.90  4864.3  403.76
  4902.4  403.61  4976.2  403.81  5000.9  399.83  5001.7  399.03  5011.9  399.83
  5030.6  403.65  5036.6  401.75  5046.7  403.60  5069.5  403.92  5087.0  401.76
  5106.1  404.35  5117.3  402.44  5127.3  405.16  5176.8  405.62  5191.2  404.39
  5232.9  406.90  5454.1  418.81  5582.3  417.66  5625.6  419.86  5705.7  420.66
#Mann=5,-1,0
  4139.9    0.05       0  4902.4    0.16       0  5000.9    0.07       0
  5011.9    0.16       0  5069.5    0.05       0
Bank Sta=4814.5,5232.9
Exp/Cntr=0.3,0.1

Type RM Length L Ch R = 1,27338,829,829,829
BEGIN DESCRIPTION:
LITTLE CANEY CREEK 16.0
END DESCRIPTION:
XS GIS Cut Line= 3
      2868125.01      7018225.01      2867760.14      7017651.57
      2867224.98      7017625.00
#Sta/Elev= 30
  4391.5  421.89  4427.1  415.29  4514.3  417.04  4544.8  415.92  4550.7  417.41
  4565.9  415.85  4571.9  417.53  4602.3  418.16  4659.9  417.75  4732.7  414.75
  4738.7  413.25  4775.1  410.66  4826.7  409.14  4832.6  407.59  4867.1  406.16
  4920.0  404.00  4972.3  402.91  4978.3  399.91  4988.0  399.62  4988.8  398.82
  4999.0  399.62  5007.9  400.38  5014.7  402.78  5029.9  403.66  5073.7  402.89
  5196.5  402.68  5252.0  406.16  5426.8  418.58  5526.9  422.27  5607.0  422.52
#Mann=5,-1,0
  4391.5    0.05       0  4920.0    0.12       0  4988.0    0.07       0
  4999.0    0.12       0  5073.7    0.05       0
Bank Sta=4867.1,5252
Exp/Cntr=0.3,0.1

Type RM Length L Ch R = 1,26509,0,0,0
BEGIN DESCRIPTION:
LITTLE CANEY CREEK 15.0
END DESCRIPTION:
XS GIS Cut Line= 3
      2868624.98      7017824.98      2868127.33      7017325.00
      2867228.15      7017248.08
#Sta/Elev= 30
  4363.4  421.92  4523.4  419.87  4596.7  420.61  4667.4  418.86  4871.0  404.53
  4936.1  402.11  4978.6  402.40  4987.2  399.62  4987.9  398.82  4998.3  399.62
  5006.8  399.81  5021.0  402.40  5042.2  402.94  5056.3  402.45  5066.9  399.69
  5081.2  400.27  5091.2  402.40  5121.4  400.72  5132.2  402.25  5151.5  403.61
  5216.9  403.14  5322.1  401.97  5444.9  404.02  5460.7  404.53  5597.4  410.93
  5613.1  412.86  5711.3  418.46  5716.3  417.57  5813.9  421.15  5971.3  420.81
#Mann=7,-1,0
  4363.4    0.05       0  4523.4    0.12       0  4987.2    0.07       0
  4998.3    0.12       0  5132.2    0.16       0  5216.9    0.12       0
  5444.9    0.05       0
Bank Sta=4871,5460.7
Exp/Cntr=0.3,0.1

Chan Stop Cuts=-1