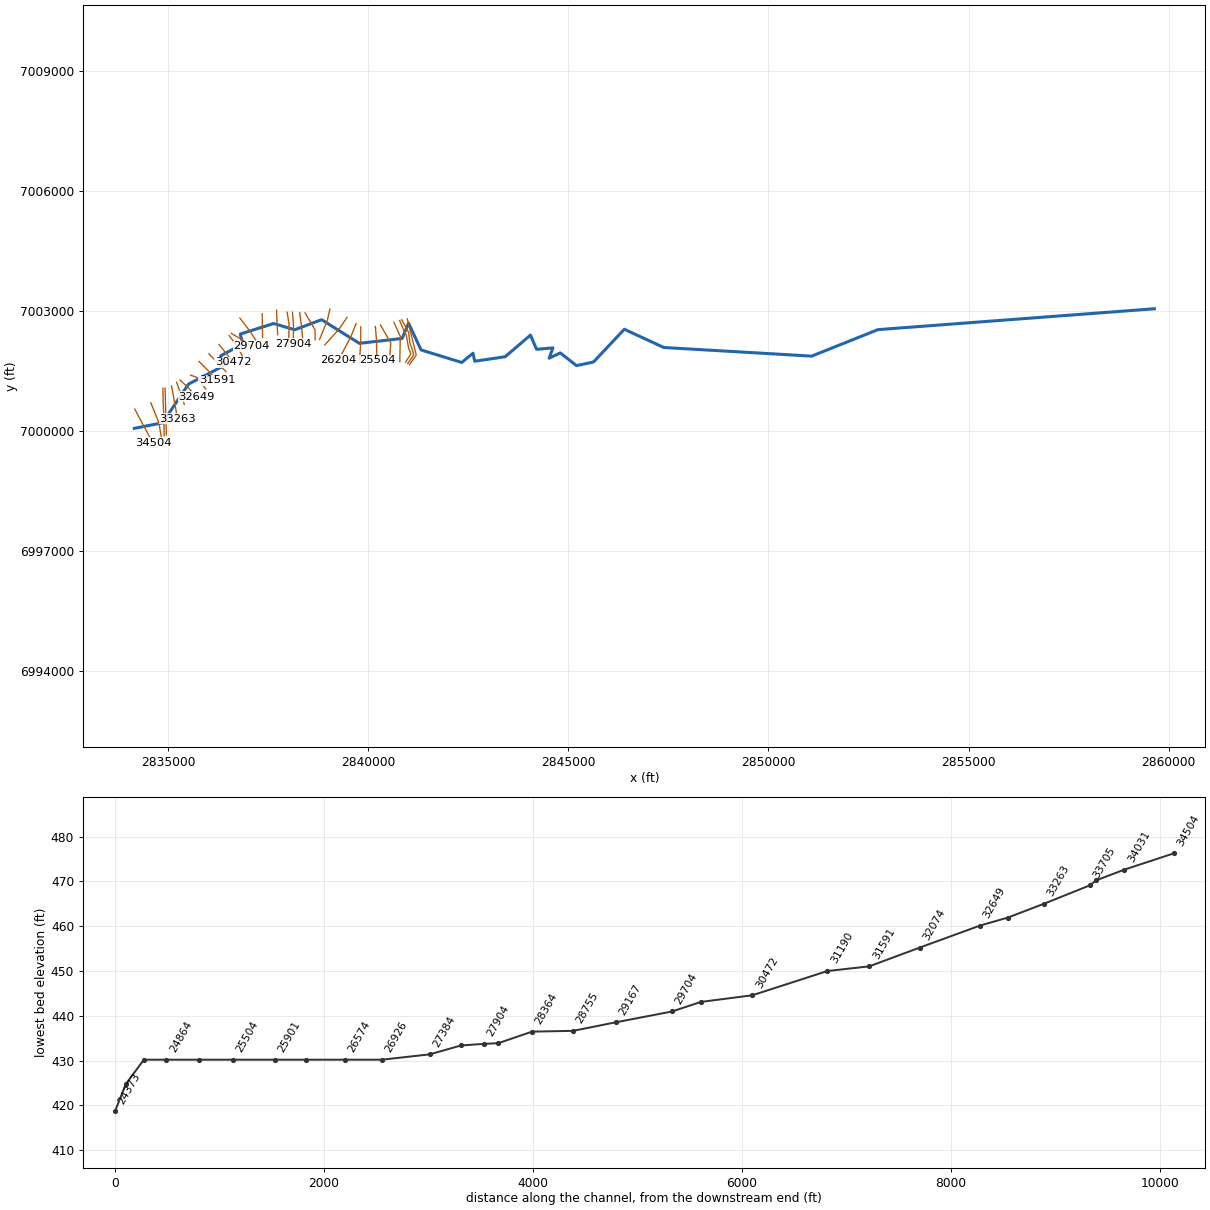
--- LITTLE MUSTANG CREEK.prj (project) ---

Proj Title=LITTLE MUSTANG CREEK Base Level Engineering
Current Plan=p01
Default Exp/Contr=0.3,0.1
English Units
Geom File=g01
Flow File=f01
Plan File=p01
BEGIN DESCRIPTION:
LITTLE MUSTANG CREEK
END DESCRIPTION:

--- LITTLE MUSTANG CREEK.p01 (plan) ---

Plan Title=Multiple Run
Short Identifier=Multiple
Geom File=g01
Flow File=f01
Subcritical Flow
K Sum by GR= 0
Std Step Tol= 0.01
Critical Tol= 0.01
Num of Std Step Trials= 20
Max Error Tol= 0.3
Flow Tol Ratio= 0.001
Split Flow NTrial= 30
Split Flow Tol= 0.02
Split Flow Ratio= 0.02
Log Output Level= 0
Friction Slope Method= 1
Unsteady Friction Slope Method= 2
Unsteady Bridges Friction Slope Method= 1
Parabolic Critical Depth
Global Vel Dist=  1 , 1 , 1
Global Log Level= 0
CheckData=True
Encroach Param= -1, 0, 0, 0
BEGIN DESCRIPTION:
Multiple Run
END DESCRIPTION:

--- LITTLE MUSTANG CREEK.f01 (steady flow) ---

Flow Title=Multiple
Number of Profiles=7
Profile Names=10-year,25-year,50-year,1pct_min,100-year,1pct_plu,500-year
River Rch & RM= LITTLE MUSTANG C,Reach-1,34504
     517     683     817     485     968    1931    1362
River Rch & RM= LITTLE MUSTANG C,Reach-1,20122
     945    1291    1578     956    1908    3807    2796
River Rch & RM= LITTLE MUSTANG C,Reach-1,18262
    1131    1551    1899    1153    2300    4589    3381
Boundary for River Rch & Prof#=LITTLE MUSTANG C,Reach-1,1
Up Type=0
Dn Type=3
Dn Slope=0.005
Boundary for River Rch & Prof#=LITTLE MUSTANG C,Reach-1,2
Up Type=0
Dn Type=3
Dn Slope=0.005
Boundary for River Rch & Prof#=LITTLE MUSTANG C,Reach-1,3
Up Type=0
Dn Type=3
Dn Slope=0.005
Boundary for River Rch & Prof#=LITTLE MUSTANG C,Reach-1,4
Up Type=0
Dn Type=3
Dn Slope=0.005
Boundary for River Rch & Prof#=LITTLE MUSTANG C,Reach-1,5
Up Type=0
Dn Type=3
Dn Slope=0.005
Boundary for River Rch & Prof#=LITTLE MUSTANG C,Reach-1,6
Up Type=0
Dn Type=3
Dn Slope=0.005
Boundary for River Rch & Prof#=LITTLE MUSTANG C,Reach-1,7
Up Type=0
Dn Type=3
Dn Slope=0.005

--- LITTLE MUSTANG CREEK.g01 (geometry) ---

Geom Title=Existing Conditions

River Reach=LITTLE MUSTANG C,Reach-1
Reach XY= 30
      2834159.32      7000077.84      2834867.65      7000217.43
      2835514.05      7001184.68      2836458.52      7001675.24
      2836315.49      7001890.73      2836873.71      7002190.94
      2836804.51      7002434.86      2837641.31      7002698.96
      2838165.16      7002542.11      2838838.01      7002794.42
      2839781.51      7002203.32      2840850.05      7002325.52
      2841010.22      7002708.93      2841321.30      7002039.35
      2842338.81      7001724.59      2842620.37      7001956.94
      2842663.35      7001755.11      2843424.55      7001869.11
      2844055.56      7002408.55      2844207.55      7002053.49
      2844616.18      7002089.62      2844522.74      7001832.98
      2844800.56      7001963.79      2845204.83      7001646.10
      2845630.28      7001737.05      2846399.95      7002554.88
      2847387.11      7002099.27      2851080.60      7001883.61
      2852735.99      7002545.77      2859641.77      7003067.76

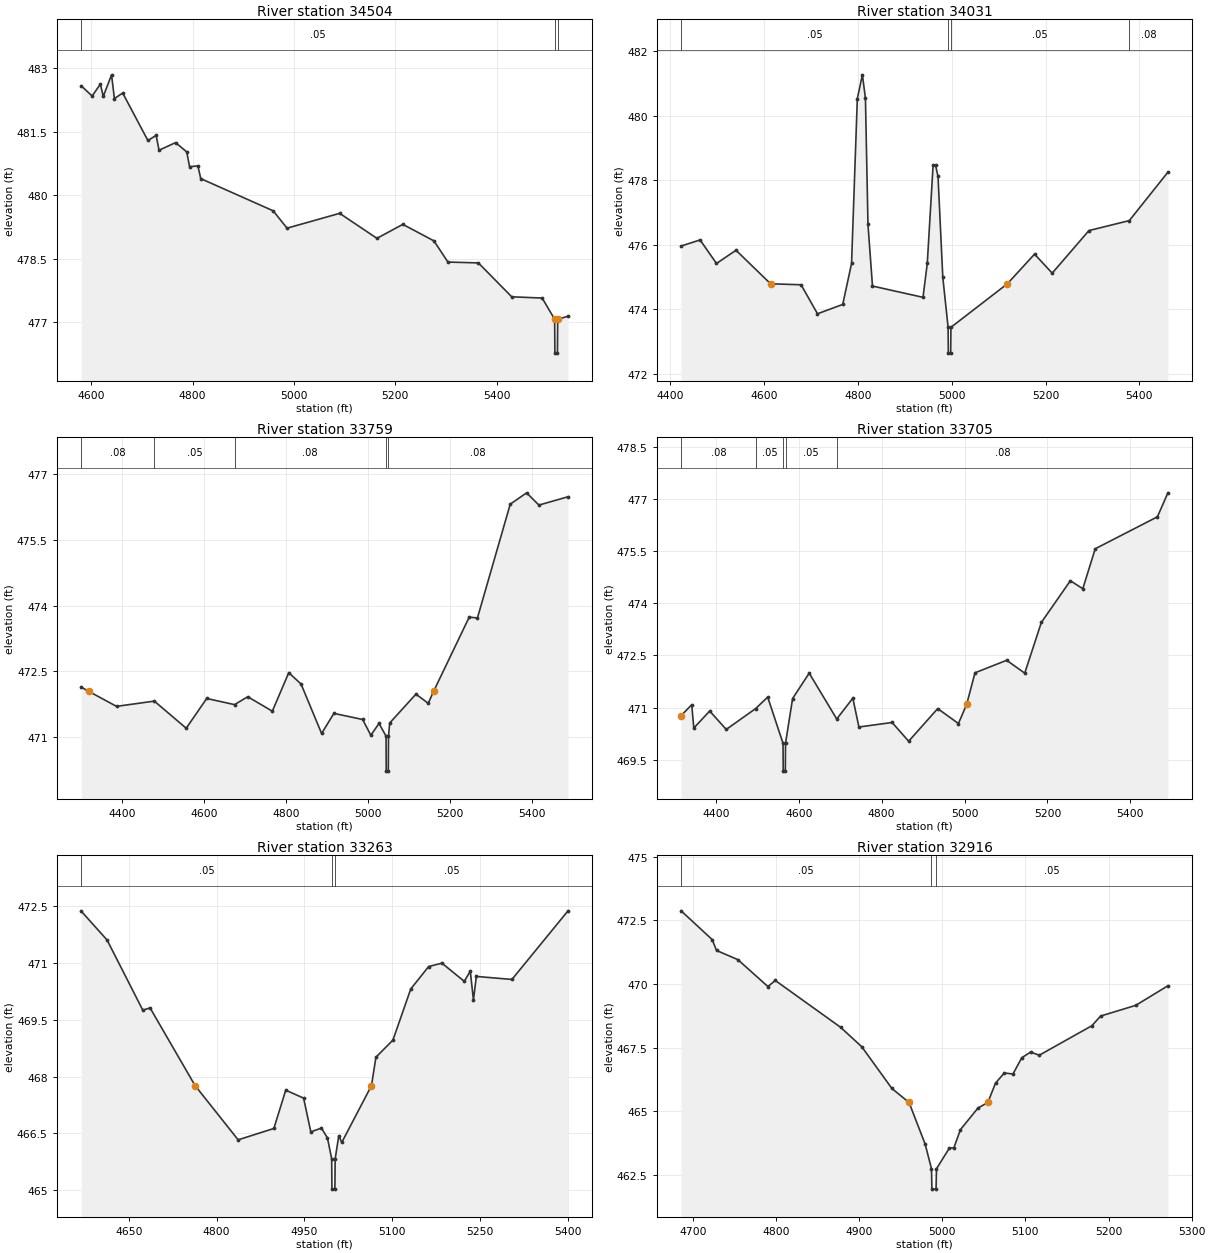
Type RM Length L Ch R = 1,34504,473,473,473
BEGIN DESCRIPTION:
LITTLE MUSTANG CREEK 51.0
END DESCRIPTION:
XS GIS Cut Line= 3
      2834170.63      7000560.20      2834345.53      7000229.65
      2834622.87      6999712.72
#Sta/Elev= 30
  4580.1  482.58  4601.5  482.34  4617.9  482.62  4623.5  482.33  4639.9  482.84
  4645.5  482.28  4661.9  482.41  4711.6  481.29  4727.9  481.41  4733.6  481.06
  4766.3  481.24  4788.3  481.02  4793.9  480.67  4810.3  480.69  4815.9  480.39
  4958.8  479.63  4986.2  479.22  5090.1  479.57  5163.6  478.98  5214.7  479.31
  5276.1  478.92  5303.7  478.42  5363.8  478.40  5429.6  477.60  5489.7  477.57
  5514.3  477.07  5514.8  476.27  5519.8  476.27  5520.3  477.07  5540.7  477.14
#Mann=3,-1,0
  4580.1    0.05       0  5514.3    0.03       0  5520.3    0.05       0
Bank Sta=5514.3,5520.3
Exp/Cntr=0.3,0.1

Type RM Length L Ch R = 1,34031,272,272,272
BEGIN DESCRIPTION:
LITTLE MUSTANG CREEK 50.0
END DESCRIPTION:
XS GIS Cut Line= 3
      2834573.38      7000713.61      2834775.21      7000210.12
      2834857.67      6999721.88
#Sta/Elev= 30
  4423.1  475.96  4463.5  476.15  4498.5  475.42  4540.1  475.83  4613.8  474.79
  4678.8  474.76  4713.8  473.86  4767.6  474.15  4786.4  475.42  4798.7  480.53
  4809.5  481.27  4816.0  480.54  4821.4  476.63  4831.0  474.72  4938.7  474.37
  4947.8  475.42  4960.2  478.46  4965.5  478.46  4970.7  478.12  4980.9  474.99
  4992.2  473.44  4992.7  472.64  4997.7  472.64  4998.2  473.44  5118.5  474.79
  5176.5  475.71  5214.1  475.12  5292.4  476.44  5378.5  476.75  5460.7  478.25
#Mann=4,-1,0
  4423.1    0.05       0  4992.2    0.03       0  4998.2    0.05       0
  5378.5    0.08       0
Bank Sta=4613.8,5118.5
Exp/Cntr=0.3,0.1

Type RM Length L Ch R = 1,33759,54,54,54
BEGIN DESCRIPTION:
Mapping XS c536f2c8
END DESCRIPTION:
XS GIS Cut Line= 4
      2834873.74      7001081.04      2834880.25      7000727.33
      2834899.78      7000328.03      2834904.12      6999894.00
#Sta/Elev= 30
  4300.9  472.14  4319.7  472.04  4387.0  471.70  4479.2  471.82  4557.0  471.20
  4607.0  471.88  4674.9  471.74  4707.1  471.92  4767.1  471.59  4807.2  472.47
  4837.2  472.21  4887.3  471.08  4917.3  471.54  4987.4  471.40  5007.4  471.04
  5027.4  471.31  5044.5  471.02  5045.0  470.22  5050.0  470.22  5050.5  471.02
  5053.5  471.32  5117.5  471.98  5147.5  471.77  5160.4  472.04  5247.5  473.74
  5267.5  473.72  5347.5  476.32  5387.5  476.58  5417.5  476.30  5488.5  476.49
#Mann=5,-1,0
  4300.9    0.08       0  4479.2    0.05       0  4674.9    0.08       0
  5044.5    0.07       0  5050.5    0.08       0
Bank Sta=4319.7,5160.4
Exp/Cntr=0.3,0.1

Type RM Length L Ch R = 1,33705,442,442,442
BEGIN DESCRIPTION:
LITTLE MUSTANG CREEK 49.0
END DESCRIPTION:
XS GIS Cut Line= 3
      2834929.29      7001083.86      2834942.31      7000579.91
      2834960.54      6999909.78
#Sta/Elev= 30
  4316.1  470.77  4341.7  471.08  4346.7  470.41  4385.0  470.90  4425.0  470.37
  4495.9  470.97  4525.0  471.30  4562.0  469.97  4562.5  469.17  4567.5  469.17
  4568.0  469.97  4585.1  471.26  4625.1  471.99  4691.6  470.67  4730.4  471.27
  4745.1  470.44  4825.2  470.57  4865.1  470.03  4935.2  470.97  4985.2  470.54
  5005.0  471.09  5025.2  472.00  5101.6  472.36  5145.2  471.99  5185.3  473.45
  5255.3  474.65  5285.3  474.42  5315.3  475.57  5465.4  476.49  5490.6  477.18
#Mann=5,-1,0
  4316.1    0.08       0  4495.9    0.05       0  4562.0    0.07       0
  4568.0    0.05       0  4691.6    0.08       0
Bank Sta=4316.1,5005
Exp/Cntr=0.3,0.1

Type RM Length L Ch R = 1,33263,347,347,347
BEGIN DESCRIPTION:
LITTLE MUSTANG CREEK 48.0
END DESCRIPTION:
XS GIS Cut Line= 3
      2835089.10      7001138.37      2835175.00      7000675.00
      2835238.40      7000320.69
#Sta/Elev= 30
  4569.0  472.36  4613.1  471.60  4674.1  469.75  4686.5  469.81  4763.4  467.76
  4836.9  466.33  4897.9  466.63  4918.2  467.64  4948.7  467.43  4961.0  466.54
  4979.2  466.64  4989.4  466.38  4996.6  465.83  4997.1  465.03  5002.1  465.03
  5002.6  465.83  5008.8  466.44  5013.8  466.26  5064.6  467.76  5072.2  468.51
  5101.2  468.96  5131.7  470.31  5162.2  470.90  5184.9  470.99  5223.1  470.51
  5233.3  470.78  5238.7  470.02  5243.7  470.64  5304.4  470.56  5400.2  472.37
#Mann=3,-1,0
  4569.0    0.05       0  4996.6    0.03       0  5002.6    0.05       0
Bank Sta=4763.4,5064.6
Exp/Cntr=0.3,0.1

Type RM Length L Ch R = 1,32916,267,267,267
BEGIN DESCRIPTION:
LITTLE MUSTANG CREEK 47.0
END DESCRIPTION:
XS GIS Cut Line= 3
      2835216.29      7001231.65      2835325.00      7000925.00
      2835407.24      7000678.29
#Sta/Elev= 30
  4686.0  472.88  4723.3  471.75  4728.6  471.32  4754.2  470.96  4790.4  469.90
  4799.2  470.14  4877.7  468.30  4903.3  467.53  4939.5  465.89  4960.1  465.34
  4979.5  463.70  4987.1  462.73  4987.6  461.93  4992.6  461.93  4993.1  462.73
  5008.7  463.55  5014.0  463.55  5021.9  464.27  5043.0  465.12  5054.9  465.34
  5064.1  466.10  5074.6  466.50  5085.1  466.46  5095.7  467.10  5106.2  467.32
  5116.8  467.20  5180.0  468.36  5190.5  468.74  5232.7  469.16  5271.4  469.93
#Mann=3,-1,0
  4686.0    0.05       0  4987.1    0.03       0  4993.1    0.05       0
Bank Sta=4960.1,5054.9
Exp/Cntr=0.3,0.1

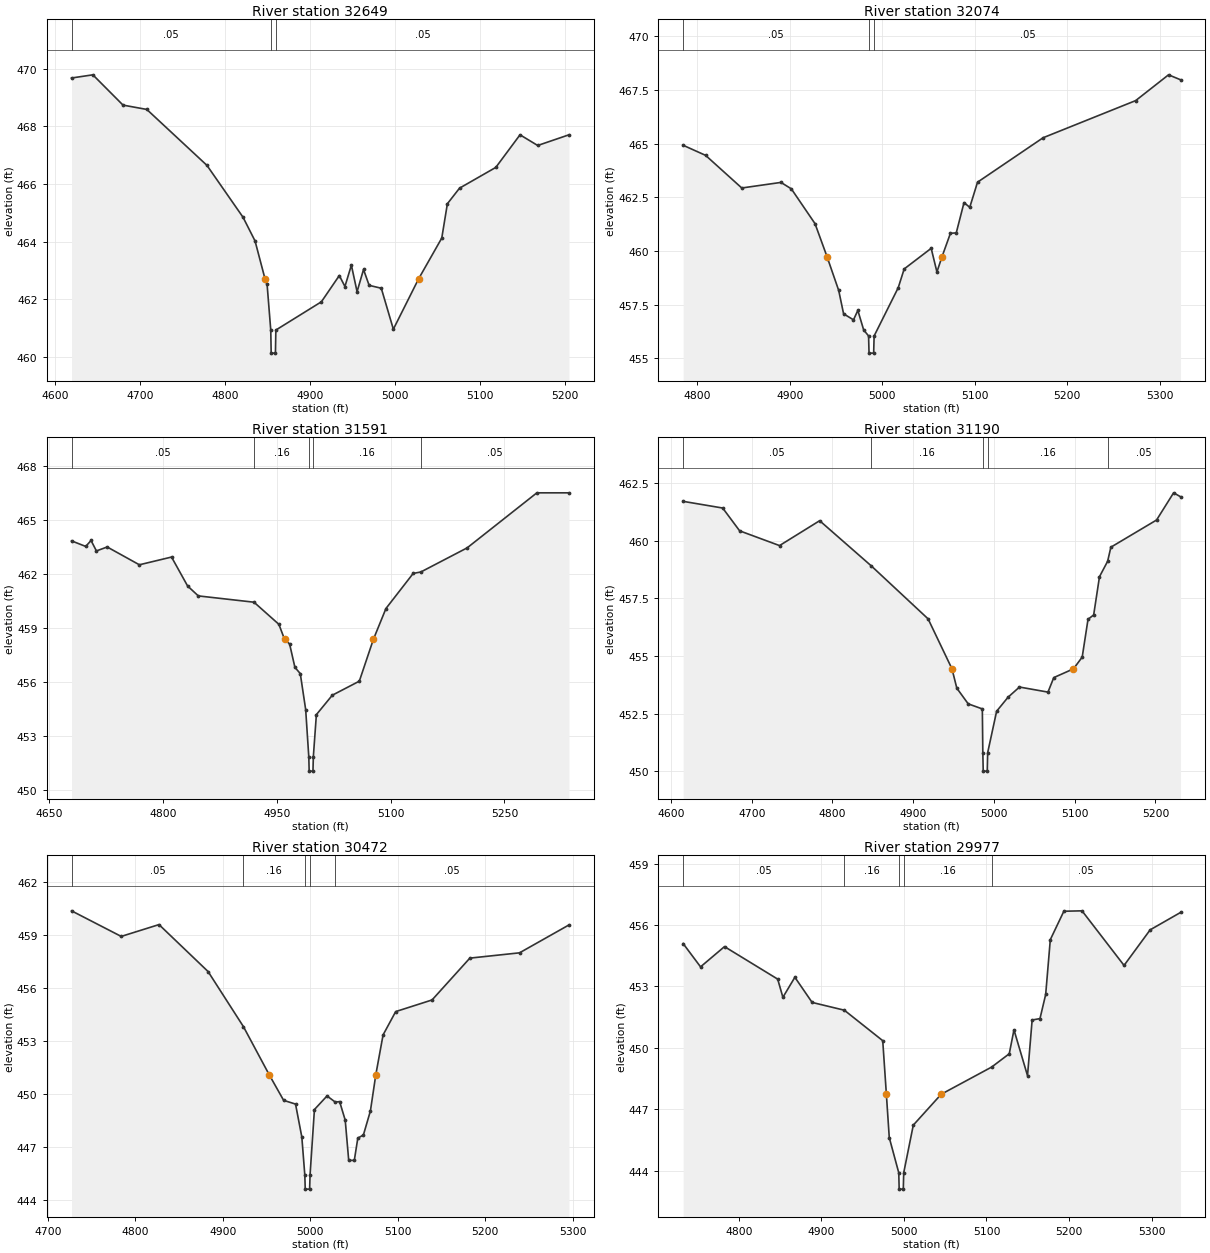
Type RM Length L Ch R = 1,32649,575,575,575
BEGIN DESCRIPTION:
LITTLE MUSTANG CREEK 46.0
END DESCRIPTION:
XS GIS Cut Line= 3
      2835300.89      7001286.39      2835525.00      7001075.00
      2835707.18      7000865.78
#Sta/Elev= 30
  4619.1  469.68  4644.2  469.79  4679.7  468.74  4707.7  468.59  4778.5  466.65
  4821.0  464.85  4835.1  464.03  4846.8  462.72  4849.3  462.52  4853.6  460.94
  4854.1  460.14  4859.1  460.14  4859.6  460.94  4913.2  461.92  4934.3  462.83
  4940.9  462.45  4948.5  463.19  4955.2  462.27  4962.8  463.04  4969.4  462.49
  4983.7  462.39  4997.9  460.97  5027.7  462.72  5054.9  464.13  5061.5  465.32
  5075.8  465.86  5118.5  466.58  5147.0  467.71  5167.8  467.34  5204.6  467.71
#Mann=3,-1,0
  4619.1    0.05       0  4853.6    0.03       0  4859.6    0.05       0
Bank Sta=4846.8,5027.7
Exp/Cntr=0.3,0.1

Type RM Length L Ch R = 1,32074,483,483,483
BEGIN DESCRIPTION:
LITTLE MUSTANG CREEK 45.0
END DESCRIPTION:
XS GIS Cut Line= 3
      2835565.23      7001407.47      2835734.50      7001347.57
      2835947.99      7001059.89
#Sta/Elev= 30
  4784.8  464.92  4809.1  464.45  4848.2  462.93  4890.6  463.19  4901.8  462.89
  4927.4  461.27  4940.4  459.73  4953.0  458.16  4958.3  457.07  4969.0  456.79
  4973.7  457.23  4980.0  456.32  4985.3  456.04  4985.8  455.24  4990.8  455.24
  4991.3  456.04  5017.4  458.29  5023.8  459.16  5053.0  460.12  5059.2  459.02
  5064.7  459.73  5073.8  460.82  5080.1  460.84  5088.5  462.25  5094.7  462.03
  5103.1  463.20  5174.0  465.27  5274.1  467.00  5309.6  468.20  5322.6  467.97
#Mann=3,-1,0
  4784.8    0.05       0  4985.3    0.03       0  4991.3    0.05       0
Bank Sta=4940.4,5064.7
Exp/Cntr=0.3,0.1

Type RM Length L Ch R = 1,31591,401,401,401
BEGIN DESCRIPTION:
LITTLE MUSTANG CREEK 44.0
END DESCRIPTION:
XS GIS Cut Line= 3
      2835776.15      7001752.54      2836019.66      7001505.13
      2836225.02      7001274.97
#Sta/Elev= 30
  4679.5  463.85  4698.2  463.54  4705.2  463.87  4712.3  463.29  4726.5  463.51
  4768.9  462.52  4811.3  462.95  4832.5  461.34  4846.6  460.79  4920.0  460.44
  4952.8  459.21  4960.3  458.37  4966.9  458.12  4973.9  456.82  4981.0  456.47
  4988.1  454.47  4992.2  451.85  4992.7  451.05  4997.7  451.05  4998.2  451.85
  5002.2  454.19  5023.2  455.27  5058.8  456.05  5077.3  458.37  5093.9  460.09
  5129.8  462.04  5139.9  462.12  5200.9  463.46  5292.8  466.52  5335.1  466.52
#Mann=5,-1,0
  4679.5    0.05       0  4920.0    0.16       0  4992.2    0.07       0
  4998.2    0.16       0  5139.9    0.05       0
Bank Sta=4960.3,5077.3
Exp/Cntr=0.3,0.1

Type RM Length L Ch R = 1,31190,718,718,718
BEGIN DESCRIPTION:
LITTLE MUSTANG CREEK 43.0
END DESCRIPTION:
XS GIS Cut Line= 3
      2836022.29      7001941.30      2836275.00      7001675.00
      2836448.06      7001496.00
#Sta/Elev= 30
  4615.0  461.71  4664.0  461.42  4685.0  460.43  4734.4  459.79  4784.1  460.87
  4848.0  458.91  4918.4  456.61  4948.0  454.44  4954.0  453.60  4968.1  452.92
  4985.6  452.70  4986.2  450.80  4986.7  450.00  4991.7  450.00  4992.2  450.80
  5003.3  452.60  5017.5  453.21  5031.6  453.65  5066.9  453.43  5074.1  454.06
  5098.5  454.44  5109.3  454.95  5116.5  456.59  5123.5  456.78  5130.7  458.44
  5140.8  459.11  5144.8  459.72  5201.4  460.90  5222.5  462.08  5231.1  461.91
#Mann=5,-1,0
  4615.0    0.05       0  4848.0    0.16       0  4986.2    0.07       0
  4992.2    0.16       0  5140.8    0.05       0
Bank Sta=4948,5098.5
Exp/Cntr=0.3,0.1

Type RM Length L Ch R = 1,30472,495,495,495
BEGIN DESCRIPTION:
LITTLE MUSTANG CREEK 42.0
END DESCRIPTION:
XS GIS Cut Line= 3
      2836275.01      7002174.98      2836475.00      7001925.00
      2836630.28      7001730.90
#Sta/Elev= 30
  4727.1  460.36  4783.9  458.91  4827.1  459.58  4883.2  456.92  4923.6  453.80
  4953.0  451.08  4969.6  449.62  4983.2  449.41  4990.4  447.54  4993.8  445.39
  4994.3  444.59  4999.3  444.59  4999.8  445.39  5004.8  449.10  5019.2  449.87
  5028.7  449.52  5033.6  449.55  5040.0  448.50  5044.0  446.22  5050.4  446.22
  5054.4  447.48  5060.8  447.66  5068.8  449.02  5075.0  451.08  5083.3  453.33
  5097.7  454.65  5139.3  455.31  5182.5  457.68  5239.3  457.98  5295.8  459.56
#Mann=5,-1,0
  4727.1    0.05       0  4923.6    0.16       0  4993.8    0.07       0
  4999.8    0.16       0  5028.7    0.05       0
Bank Sta=4953,5075
Exp/Cntr=0.3,0.1

Type RM Length L Ch R = 1,29977,273,273,273
BEGIN DESCRIPTION:
LITTLE MUSTANG CREEK 41.0
END DESCRIPTION:
XS GIS Cut Line= 3
      2836527.47      7002397.05      2836731.42      7002130.06
      2836855.59      7001894.46
#Sta/Elev= 30
  4732.7  455.10  4753.8  453.96  4782.8  454.95  4847.2  453.36  4853.5  452.47
  4868.0  453.45  4888.9  452.22  4927.9  451.84  4974.4  450.35  4978.8  447.73
  4982.3  445.61  4993.8  443.89  4994.3  443.09  4999.3  443.09  4999.8  443.89
  5011.4  446.22  5045.2  447.73  5106.3  449.06  5127.6  449.71  5133.3  450.88
  5149.7  448.64  5155.3  451.36  5164.8  451.43  5171.7  452.61  5177.3  455.29
  5193.7  456.68  5215.7  456.70  5266.6  454.03  5298.2  455.77  5335.0  456.62
#Mann=5,-1,0
  4732.7    0.05       0  4927.9    0.16       0  4993.8    0.07       0
  4999.8    0.16       0  5106.3    0.05       0
Bank Sta=4978.8,5045.2
Exp/Cntr=0.3,0.1

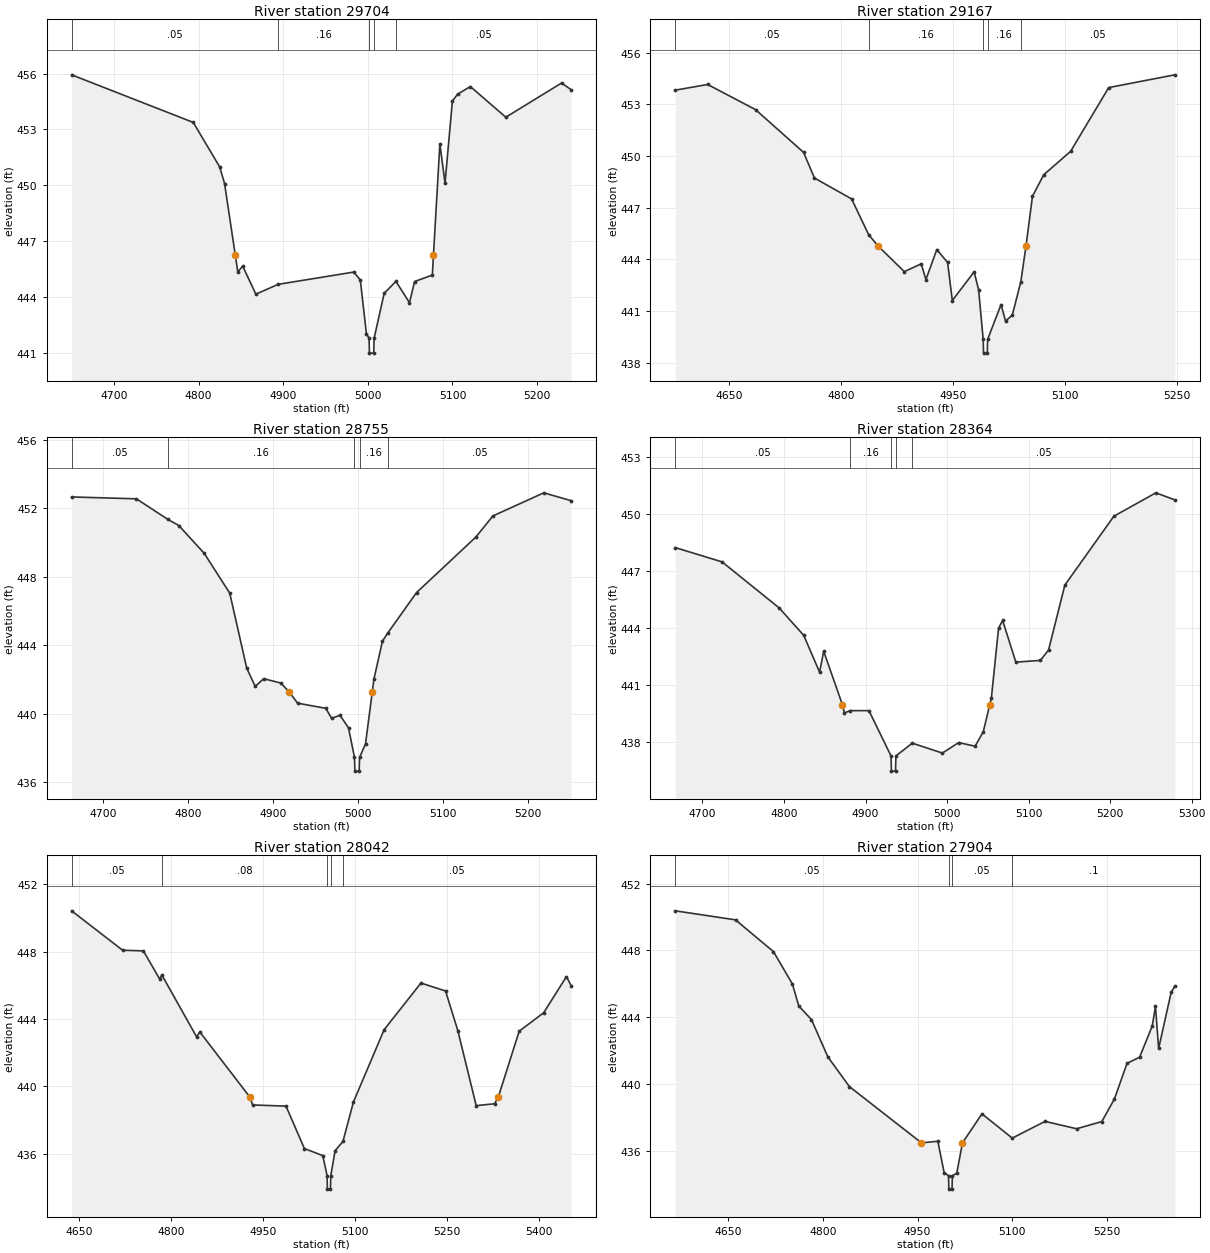
Type RM Length L Ch R = 1,29704,537,537,537
BEGIN DESCRIPTION:
LITTLE MUSTANG CREEK 40.0
END DESCRIPTION:
XS GIS Cut Line= 3
      2836583.49      7002451.72      2836834.76      7002302.00
      2837081.06      7002134.78
#Sta/Elev= 30
  4650.0  455.94  4793.7  453.38  4824.9  450.99  4830.7  450.09  4843.4  446.23
  4846.3  445.34  4852.1  445.65  4867.7  444.14  4894.0  444.67  4983.4  445.33
  4991.1  444.90  4998.3  442.02  5001.4  441.77  5001.9  440.97  5006.9  440.97
  5007.4  441.77  5019.3  444.19  5033.2  444.83  5049.2  443.68  5055.2  444.82
  5076.2  445.17  5077.5  446.23  5085.1  452.22  5091.2  450.12  5099.9  454.53
  5106.1  454.90  5121.1  455.31  5163.0  453.66  5228.9  455.50  5240.2  455.14
#Mann=5,-1,0
  4650.0    0.05       0  4894.0    0.16       0  5001.4    0.07       0
  5007.4    0.16       0  5033.2    0.05       0
Bank Sta=4843.4,5077.5
Exp/Cntr=0.3,0.1

Type RM Length L Ch R = 1,29167,412,412,412
BEGIN DESCRIPTION:
LITTLE MUSTANG CREEK 39.0
END DESCRIPTION:
XS GIS Cut Line= 3
      2836795.71      7002837.14      2837033.98      7002525.96
      2837187.63      7002294.19
#Sta/Elev= 30
  4577.6  453.82  4621.0  454.15  4685.3  452.69  4749.7  450.21  4764.3  448.72
  4814.1  447.51  4836.9  445.44  4849.3  444.79  4884.8  443.29  4907.5  443.74
  4913.8  442.83  4928.4  444.57  4942.9  443.82  4949.2  441.61  4978.5  443.28
  4984.5  442.23  4990.6  439.36  4991.1  438.56  4996.1  438.56  4996.6  439.36
  5014.6  441.38  5020.6  440.42  5029.7  440.77  5041.1  442.70  5048.1  444.79
  5056.7  447.66  5071.8  448.91  5107.9  450.27  5159.0  453.97  5247.6  454.71
#Mann=5,-1,0
  4577.6    0.05       0  4836.9    0.16       0  4990.6    0.07       0
  4996.6    0.16       0  5041.1    0.05       0
Bank Sta=4849.3,5048.1
Exp/Cntr=0.3,0.1

Type RM Length L Ch R = 1,28755,391,391,391
BEGIN DESCRIPTION:
LITTLE MUSTANG CREEK 38.0
END DESCRIPTION:
XS GIS Cut Line= 3
      2837354.29      7002941.30      2837358.20      7002641.84
      2837364.71      7002352.80
#Sta/Elev= 30
  4662.5  452.66  4738.8  452.55  4775.5  451.36  4788.8  450.99  4818.8  449.36
  4848.8  447.04  4868.8  442.66  4878.8  441.59  4888.8  442.04  4908.8  441.79
  4918.5  441.29  4928.8  440.61  4962.0  440.31  4968.8  439.73  4978.8  439.90
  4988.8  439.16  4995.8  437.44  4996.3  436.64  5001.3  436.64  5001.8  437.44
  5008.8  438.23  5016.8  441.29  5018.8  442.04  5028.8  444.24  5034.9  444.70
  5068.9  447.07  5138.9  450.32  5158.9  451.55  5218.9  452.90  5251.1  452.44
#Mann=5,-1,0
  4662.5    0.05       0  4775.5    0.16       0  4995.8    0.07       0
  5001.8    0.16       0  5034.9    0.05       0
Bank Sta=4918.5,5016.8
Exp/Cntr=0.3,0.1

Type RM Length L Ch R = 1,28364,322,322,322
BEGIN DESCRIPTION:
LITTLE MUSTANG CREEK 37.0
END DESCRIPTION:
XS GIS Cut Line= 3
      2837712.80      7003032.34      2837725.00      7002725.00
      2837741.44      7002420.43
#Sta/Elev= 30
  4666.7  448.22  4724.1  447.47  4794.1  445.05  4824.2  443.61  4843.7  441.67
  4848.7  442.77  4871.7  439.96  4874.2  439.53  4881.2  439.65  4904.2  439.65
  4931.3  437.27  4931.8  436.47  4936.8  436.47  4937.3  437.27  4957.4  437.94
  4994.3  437.42  5014.3  437.97  5034.4  437.78  5044.4  438.53  5052.4  439.96
  5054.4  440.32  5063.2  443.99  5068.2  444.39  5084.4  442.20  5114.5  442.29
  5124.5  442.84  5144.5  446.25  5204.6  449.87  5256.1  451.10  5279.3  450.73
#Mann=5,-1,0
  4666.7    0.05       0  4881.2    0.16       0  4931.3    0.03       0
  4937.3    0.16       0  4957.4    0.05       0
Bank Sta=4871.7,5052.4
Exp/Cntr=0.3,0.1

Type RM Length L Ch R = 1,28042,138,138,138
BEGIN DESCRIPTION:
Mapping XS 4b1d3124
END DESCRIPTION:
XS GIS Cut Line= 4
      2837975.81      7002980.32      2838025.30      7002688.61
      2838017.49      7002308.40      2838009.68      7002170.39
#Sta/Elev= 30
  4637.6  450.43  4720.7  448.09  4754.6  448.05  4781.1  446.38  4784.7  446.62
  4841.4  442.94  4846.5  443.24  4927.9  439.38  4932.8  438.90  4987.1  438.83
  5017.1  436.31  5047.1  435.89  5054.1  434.70  5054.6  433.90  5059.6  433.90
  5060.1  434.70  5067.1  436.18  5079.9  436.73  5097.1  439.08  5147.1  443.37
  5207.1  446.14  5247.2  445.67  5267.2  443.32  5297.2  438.86  5327.2  438.97
  5333.3  439.38  5367.3  443.28  5407.3  444.38  5444.3  446.52  5452.0  445.99
#Mann=5,-1,0
  4637.6    0.05       0  4784.7    0.08       0  5054.1    0.07       0
  5060.1    0.08       0  5079.9    0.05       0
Bank Sta=4927.9,5333.3
Exp/Cntr=0.3,0.1

Type RM Length L Ch R = 1,27904,220,220,220
BEGIN DESCRIPTION:
LITTLE MUSTANG CREEK 36.0
END DESCRIPTION:
XS GIS Cut Line= 3
      2838111.24      7002980.25      2838137.28      7002644.34
      2838129.48      7002189.33
#Sta/Elev= 30
  4565.9  450.37  4661.4  449.83  4721.6  447.93  4751.7  445.99  4761.7  444.68
  4781.8  443.87  4807.8  441.64  4842.0  439.86  4956.2  436.50  4982.2  436.59
  4992.2  434.72  4999.2  434.53  4999.7  433.73  5004.7  433.73  5005.2  434.53
  5012.2  434.68  5021.3  436.50  5052.2  438.23  5100.2  436.78  5152.2  437.78
  5202.2  437.34  5242.2  437.77  5262.2  439.12  5282.2  441.25  5302.2  441.62
  5322.2  443.49  5327.3  444.65  5332.3  442.14  5352.2  445.50  5357.9  445.86
#Mann=4,-1,0
  4565.9    0.05       0  4999.2    0.03       0  5005.2    0.05       0
  5100.2     0.1       0
Bank Sta=4956.2,5021.3
Exp/Cntr=0.3,0.1

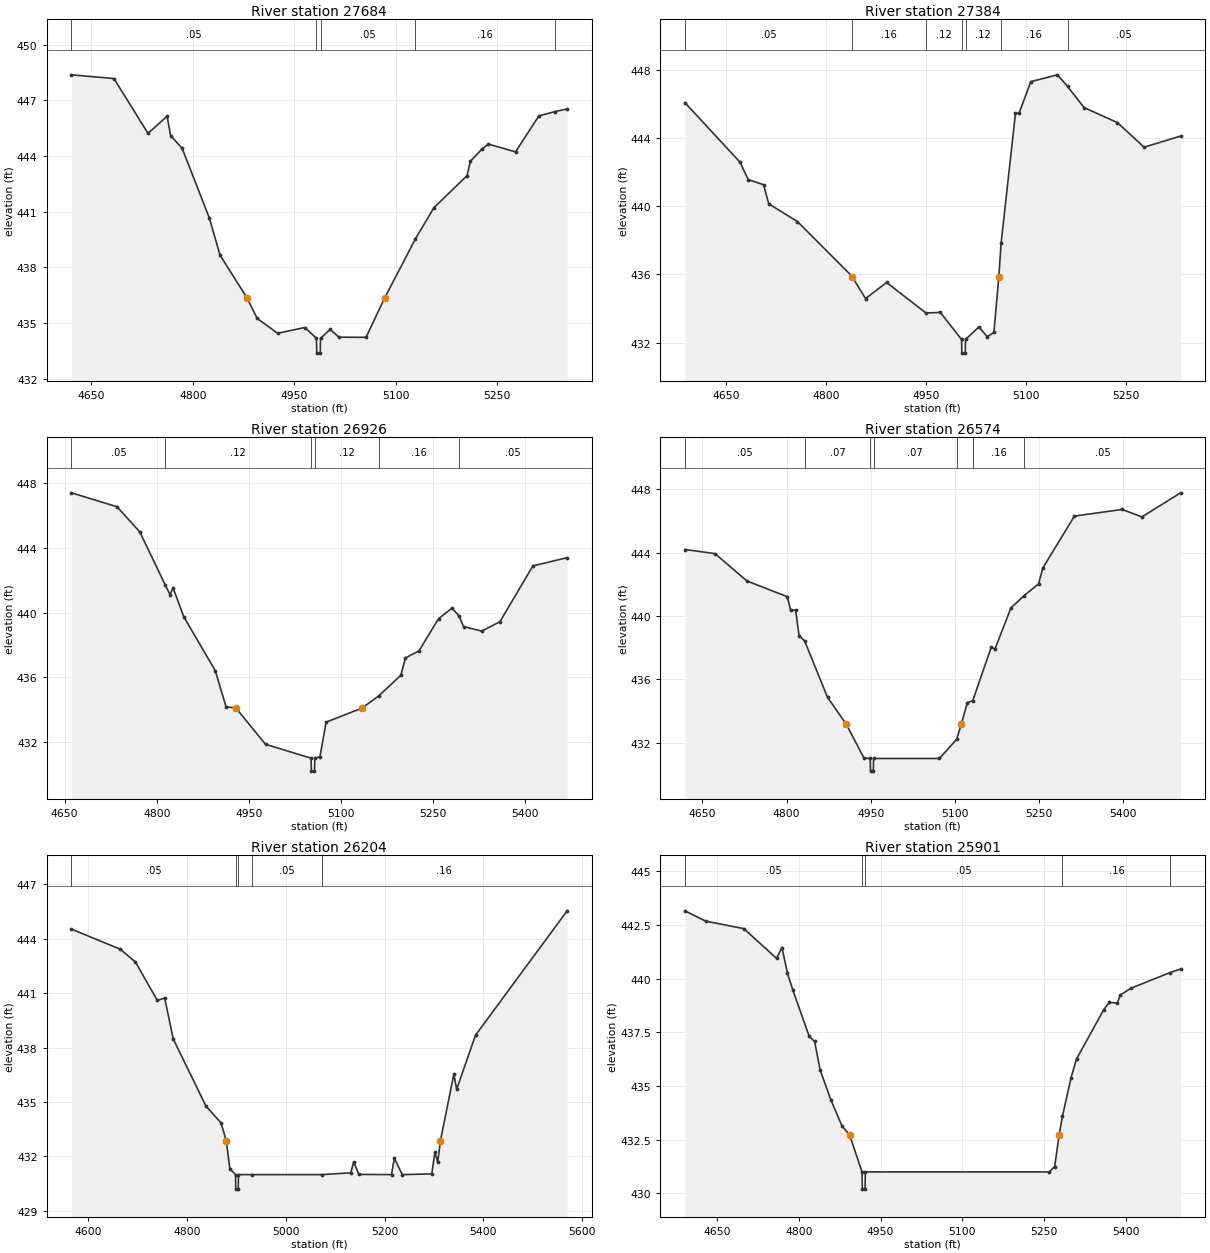
Type RM Length L Ch R = 1,27684,300,300,300
BEGIN DESCRIPTION:
LITTLE MUSTANG CREEK 35.0
END DESCRIPTION:
XS GIS Cut Line= 3
      2838290.93      7002967.23      2838335.16      7002634.77
      2838374.16      7002239.07
#Sta/Elev= 30
  4620.7  448.37  4683.5  448.17  4733.9  445.22  4762.2  446.14  4767.3  445.10
  4784.4  444.41  4824.7  440.65  4840.5  438.65  4880.1  436.37  4895.3  435.25
  4925.6  434.45  4965.9  434.76  4983.0  434.18  4983.5  433.38  4988.5  433.38
  4989.0  434.18  5003.3  434.66  5016.1  434.24  5056.3  434.23  5084.1  436.37
  5129.4  439.54  5156.8  441.22  5205.7  442.94  5210.7  443.72  5227.2  444.35
  5237.2  444.64  5277.4  444.22  5311.9  446.16  5335.8  446.39  5353.7  446.53
#Mann=5,-1,0
  4620.7    0.05       0  4983.0    0.03       0  4989.0    0.05       0
  5129.4    0.16       0  5335.8    0.05       0
Bank Sta=4880.1,5084.1
Exp/Cntr=0.3,0.1

Type RM Length L Ch R = 1,27384,458,458,458
BEGIN DESCRIPTION:
LITTLE MUSTANG CREEK 34.0
END DESCRIPTION:
XS GIS Cut Line= 3
      2838426.35      7002967.25      2838675.00      7002534.97
      2838676.34      7002290.17
#Sta/Elev= 30
  4588.6  446.07  4671.2  442.58  4683.5  441.56  4706.6  441.26  4714.3  440.14
  4757.4  439.10  4838.8  435.91  4839.5  435.86  4859.5  434.59  4891.1  435.53
  4950.2  433.74  4971.6  433.78  5003.5  432.19  5004.0  431.39  5009.0  431.39
  5009.5  432.19  5029.6  432.93  5042.0  432.35  5052.0  432.60  5059.4  435.86
  5062.8  437.82  5084.4  445.45  5089.8  445.45  5107.3  447.30  5147.3  447.70
  5162.5  447.02  5187.3  445.78  5237.3  444.90  5277.3  443.46  5332.1  444.11
#Mann=7,-1,0
  4588.6    0.05       0  4838.8    0.16       0  4950.2    0.12       0
  5003.5    0.07       0  5009.5    0.12       0  5062.8    0.16       0
  5162.5    0.05       0
Bank Sta=4839.5,5059.4
Exp/Cntr=0.3,0.1

Type RM Length L Ch R = 1,26926,352,352,352
BEGIN DESCRIPTION:
LITTLE MUSTANG CREEK 33.0
END DESCRIPTION:
XS GIS Cut Line= 3
      2839046.12      7003063.57      2838983.63      7002787.57
      2838788.31      7002300.57
#Sta/Elev= 30
  4661.1  447.41  4735.3  446.55  4772.4  445.00  4814.3  441.68  4821.6  441.12
  4826.7  441.53  4844.2  439.74  4895.5  436.41  4913.0  434.18  4929.2  434.10
  4977.3  431.86  5051.6  431.00  5052.1  430.20  5057.1  430.20  5057.6  431.00
  5066.0  431.09  5076.1  433.23  5134.6  434.10  5162.1  434.86  5197.8  436.13
  5205.4  437.20  5227.4  437.64  5259.3  439.63  5281.2  440.28  5292.8  439.79
  5300.0  439.14  5329.6  438.86  5359.2  439.44  5413.0  442.89  5468.8  443.40
#Mann=6,-1,0
  4661.1    0.05       0  4814.3    0.12       0  5051.6    0.07       0
  5057.6    0.12       0  5162.1    0.16       0  5292.8    0.05       0
Bank Sta=4929.2,5134.6
Exp/Cntr=0.3,0.1

Type RM Length L Ch R = 1,26574,370,370,370
BEGIN DESCRIPTION:
LITTLE MUSTANG CREEK 32.0
END DESCRIPTION:
XS GIS Cut Line= 3
      2839473.19      7002850.03      2839290.92      7002581.84
      2838919.28      7002163.42
#Sta/Elev= 30
  4618.8  444.20  4672.5  443.94  4729.4  442.21  4801.3  441.22  4807.3  440.36
  4816.2  440.37  4822.3  438.76  4832.3  438.42  4873.1  434.86  4906.4  433.17
  4938.1  431.02  4949.2  431.00  4949.7  430.20  4954.7  430.20  4955.2  431.00
  5072.6  431.00  5103.3  432.21  5111.7  433.17  5122.3  434.52  5132.0  434.65
  5164.9  438.02  5171.6  437.91  5200.1  440.51  5223.7  441.29  5249.4  442.03
  5256.9  443.03  5313.3  446.31  5398.2  446.73  5433.7  446.26  5502.7  447.78
#Mann=7,-1,0
  4618.8    0.05       0  4832.3    0.07       0  4949.2    0.07       0
  4955.2    0.07       0  5103.3    0.12       0  5132.0    0.16       0
  5223.7    0.05       0
Bank Sta=4906.4,5111.7
Exp/Cntr=0.3,0.1

Type RM Length L Ch R = 1,26204,303,303,303
BEGIN DESCRIPTION:
LITTLE MUSTANG CREEK 31.0
END DESCRIPTION:
XS GIS Cut Line= 3
      2839699.78      7002696.42      2839564.36      7002357.88
      2839264.87      7001792.75
#Sta/Elev= 30
  4565.8  444.53  4664.3  443.43  4695.5  442.72  4739.7  440.60  4754.7  440.73
  4772.0  438.48  4838.2  434.78  4868.9  433.85  4879.5  432.85  4886.7  431.33
  4898.2  431.00  4898.7  430.20  4903.7  430.20  4904.2  431.00  4932.1  431.00
  5072.5  431.00  5131.8  431.10  5137.5  431.70  5148.2  431.01  5214.2  431.00
  5219.8  431.90  5236.1  431.00  5295.8  431.04  5302.1  432.25  5307.8  431.68
  5313.2  432.85  5340.5  436.54  5346.1  435.70  5384.5  438.69  5570.0  445.54
#Mann=5,-1,0
  4565.8    0.05       0  4898.2   0.033       0  4904.2    0.05       0
  4932.1    0.05       0  5072.5    0.16       0
Bank Sta=4879.5,5313.2
Exp/Cntr=0.3,0.1

Type RM Length L Ch R = 1,25901,397,397,397
BEGIN DESCRIPTION:
LITTLE MUSTANG CREEK 30.0
END DESCRIPTION:
XS GIS Cut Line= 3
      2839816.97      7002613.09      2839816.89      7002273.67
      2839783.11      7001704.19
#Sta/Elev= 30
  4591.0  443.15  4629.1  442.67  4699.1  442.32  4759.1  440.94  4769.1  441.44
  4779.1  440.26  4789.1  439.46  4819.1  437.31  4829.1  437.07  4839.1  435.75
  4859.1  434.34  4879.1  433.15  4893.4  432.71  4916.1  431.00  4916.6  430.20
  4921.6  430.20  4922.1  431.00  5259.7  431.00  5269.7  431.25  5277.8  432.71
  5284.0  433.60  5299.7  435.38  5309.8  436.26  5359.8  438.55  5369.9  438.89
  5384.7  438.86  5389.9  439.23  5409.9  439.55  5481.9  440.28  5500.9  440.44
#Mann=5,-1,0
  4591.0    0.05       0  4916.1   0.033       0  4922.1    0.05       0
  5284.0    0.16       0  5481.9    0.05       0
Bank Sta=4893.4,5277.8
Exp/Cntr=0.3,0.1

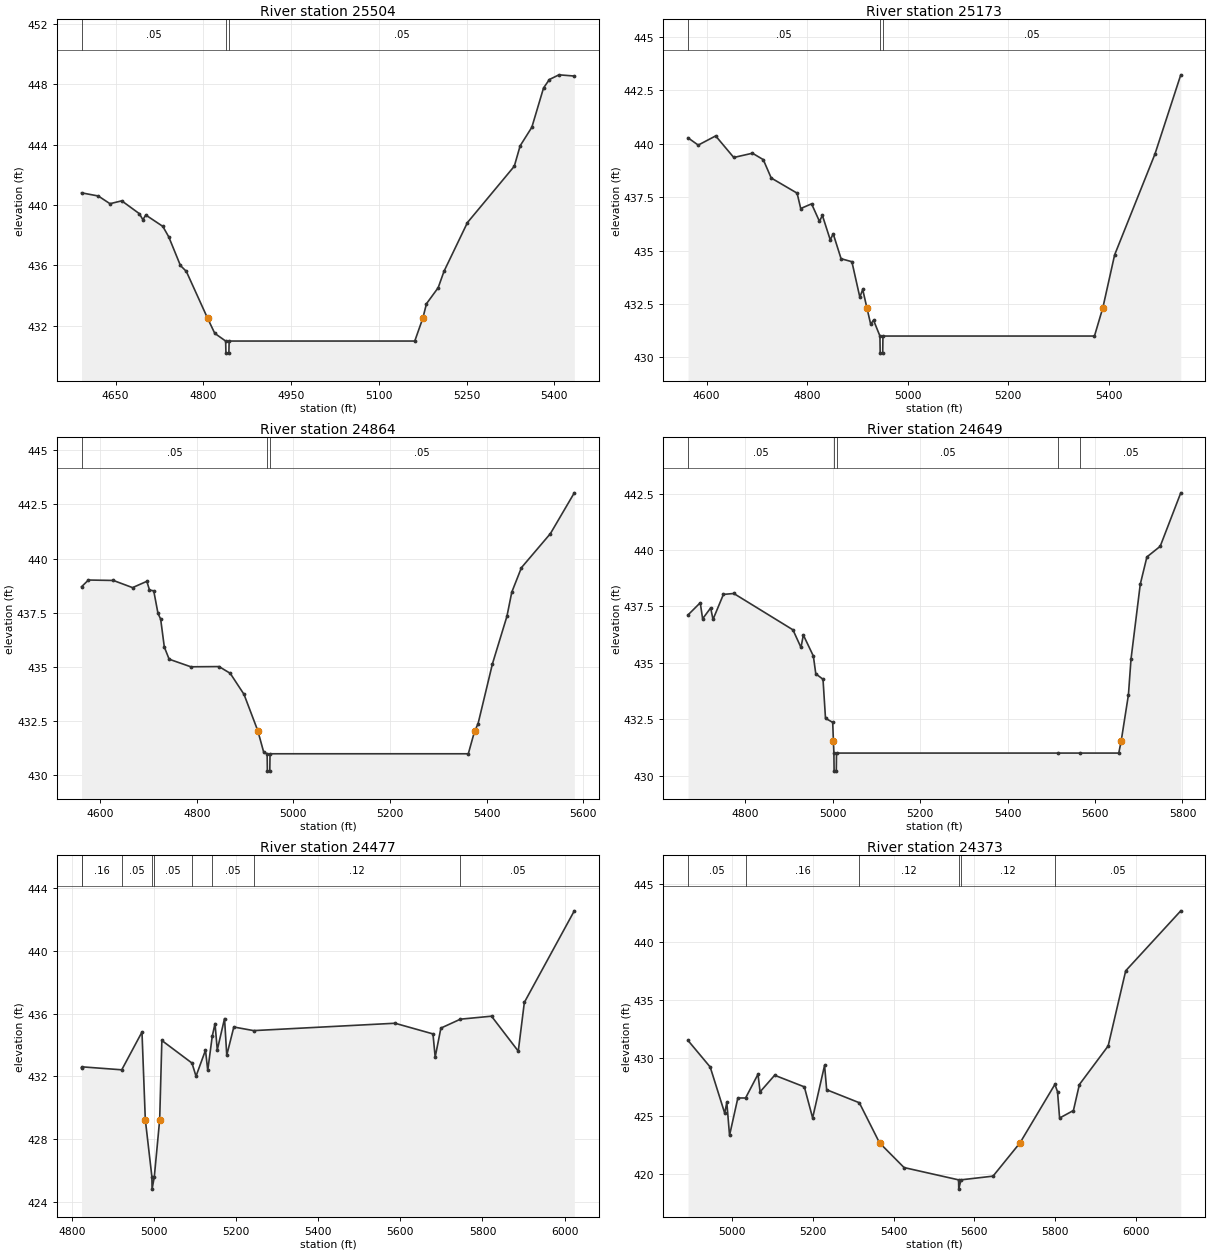
Type RM Length L Ch R = 1,25504,331,331,331
BEGIN DESCRIPTION:
LITTLE MUSTANG CREEK 29.0
END DESCRIPTION:
XS GIS Cut Line= 3
      2840181.55      7002623.49      2840208.03      7002292.89
      2840220.61      7001782.40
#Sta/Elev= 30
  4591.7  440.81  4620.3  440.60  4640.3  440.09  4660.4  440.28  4690.5  439.43
  4696.5  439.03  4701.5  439.34  4730.6  438.59  4740.7  437.90  4760.7  436.00
  4770.8  435.61  4807.0  432.52  4819.4  431.51  4838.0  431.00  4838.5  430.20
  4843.5  430.20  4844.0  431.00  5161.3  431.00  5175.1  432.52  5181.3  433.47
  5201.3  434.53  5211.3  435.62  5251.3  438.84  5331.4  442.57  5341.4  443.92
  5361.4  445.15  5381.4  447.75  5391.4  448.31  5407.8  448.62  5434.0  448.54
#Mann=3,-1,0
  4591.7    0.05       0  4838.0   0.033       0  4844.0    0.05       0
Bank Sta=4807,5175.1
Exp/Cntr=0.3,0.1

Type RM Length L Ch R = 1,25173,309,309,309
BEGIN DESCRIPTION:
LITTLE MUSTANG CREEK 28.0
END DESCRIPTION:
XS GIS Cut Line= 3
      2840306.55      7002662.58      2840566.97      7002214.65
      2840533.11      7001753.72
#Sta/Elev= 30
  4563.0  440.28  4583.3  439.94  4618.0  440.37  4654.0  439.36  4691.2  439.56
  4712.7  439.26  4728.5  438.40  4780.0  437.69  4787.2  436.97  4808.8  437.19
  4824.5  436.37  4830.3  436.65  4846.0  435.50  4851.8  435.79  4867.5  434.62
  4889.0  434.48  4904.8  432.82  4910.5  433.18  4918.8  432.33  4926.3  431.56
  4932.1  431.74  4944.8  431.00  4945.3  430.20  4950.3  430.20  4950.8  431.00
  5371.6  431.00  5388.3  432.33  5411.7  434.80  5491.9  439.52  5543.3  443.23
#Mann=3,-1,0
  4563.0    0.05       0  4944.8   0.033       0  4950.8    0.05       0
Bank Sta=4918.8,5388.3
Exp/Cntr=0.3,0.1

Type RM Length L Ch R = 1,24864,215,215,215
BEGIN DESCRIPTION:
LITTLE MUSTANG CREEK 27.0
END DESCRIPTION:
XS GIS Cut Line= 3
      2840643.35      7002731.16      2840803.82      7002376.74
      2840791.79      7001745.51
#Sta/Elev= 30
  4561.4  438.70  4575.6  439.01  4627.3  438.99  4667.0  438.66  4696.6  438.95
  4702.1  438.55  4710.9  438.51  4719.7  437.47  4725.2  437.21  4732.8  435.92
  4742.8  435.36  4787.7  435.01  4846.1  435.02  4869.2  434.71  4897.8  433.74
  4926.4  432.06  4938.5  431.08  4945.7  431.00  4946.2  430.20  4951.2  430.20
  4951.7  431.00  5362.3  431.00  5375.5  432.06  5382.3  432.37  5412.3  435.15
  5442.3  437.34  5452.3  438.45  5472.3  439.58  5532.3  441.15  5581.8  443.03
#Mann=3,-1,0
  4561.4    0.05       0  4945.7   0.033       0  4951.7    0.05       0
Bank Sta=4926.4,5375.5
Exp/Cntr=0.3,0.1

Type RM Length L Ch R = 1,24649,172,172,172
BEGIN DESCRIPTION:
Mapping XS 5f98e4a1
END DESCRIPTION:
XS GIS Cut Line= 6
      2840788.31      7002773.70      2840894.22      7002520.21
      2840953.25      7002405.63      2841010.54      7002087.92
      2841067.83      7001938.61      2840937.65      7001735.53
#Sta/Elev= 30
  4668.5  437.12  4696.5  437.66  4701.9  436.95  4720.3  437.43  4725.7  436.92
  4749.5  438.03  4773.3  438.07  4908.6  436.46  4927.0  435.68  4932.4  436.23
  4955.3  435.30  4960.9  434.51  4977.4  434.27  4983.1  432.54  4999.6  432.36
  5001.2  431.54  5002.3  431.00  5002.8  430.20  5007.8  430.20  5008.3  431.00
  5515.4  431.00  5566.6  431.00  5654.2  431.00  5659.8  431.54  5676.3  433.58
  5682.2  435.16  5703.4  438.48  5718.6  439.69  5749.0  440.16  5796.1  442.53
#Mann=5,-1,0
  4668.5    0.05       0  5002.3    0.03       0  5008.3    0.05       0
  5515.4    0.12       0  5566.6    0.05       0
Bank Sta=5001.2,5659.8
Exp/Cntr=0.3,0.1

Type RM Length L Ch R = 1,24477,104,104,104
BEGIN DESCRIPTION:
Mapping XS 0f2cc5a3
END DESCRIPTION:
XS GIS Cut Line= 6
      2840840.41      7002791.03      2841012.28      7002478.54
      2841041.79      7002223.33      2841126.86      7001975.07
      2841135.54      7001903.89      2840990.20      7001699.72
#Sta/Elev= 30
  4823.4  432.55  4824.3  432.60  4921.3  432.41  4970.6  434.82  4978.7  429.23
  4994.7  425.60  4995.2  424.80  5000.7  425.60  5013.7  429.23  5019.0  434.28
  5092.4  432.84  5102.2  432.00  5125.3  433.66  5130.8  432.37  5141.7  434.54
  5148.5  435.36  5154.0  433.68  5171.7  435.68  5177.1  433.34  5194.3  435.14
  5242.6  434.91  5586.9  435.38  5679.4  434.70  5684.8  433.22  5698.7  435.07
  5746.3  435.64  5822.0  435.83  5887.2  433.60  5902.0  436.71  6023.7  442.55
#Mann=9,-1,0
  4823.4    0.05       0  4824.3    0.16       0  4921.3    0.05       0
  4994.7    0.03       0  5000.7    0.05       0  5092.4    0.16       0
  5141.7    0.05       0  5242.6    0.12       0  5746.3    0.05       0
Bank Sta=4978.7,5013.7
Exp/Cntr=0.3,0.1

Type RM Length L Ch R = 1,24373,677,677,677
BEGIN DESCRIPTION:
LITTLE MUSTANG CREEK 26.0
END DESCRIPTION:
XS GIS Cut Line= 3
      2840977.11      7002814.96      2841202.82      7001909.97
      2841035.73      7001673.44
#Sta/Elev= 30
  4889.9  431.51  4944.9  429.22  4981.0  425.23  4986.1  426.18  4992.9  423.33
  5013.5  426.55  5032.7  426.55  5063.5  428.60  5068.7  427.08  5104.8  428.51
  5178.4  427.51  5199.0  424.83  5228.6  429.36  5233.8  427.26  5314.8  426.14
  5365.0  422.68  5425.8  420.55  5561.0  419.49  5561.5  418.69  5567.0  419.49
  5646.5  419.81  5713.4  422.68  5799.9  427.72  5806.5  427.09  5811.6  424.82
  5845.9  425.47  5860.7  427.71  5932.1  431.04  5975.6  437.52  6112.2  442.69
#Mann=6,-1,0
  4889.9    0.05       0  5032.7    0.16       0  5314.8    0.12       0
  5561.0    0.03       0  5567.0    0.12       0  5799.9    0.05       0
Bank Sta=5365,5713.4
Exp/Cntr=0.3,0.1