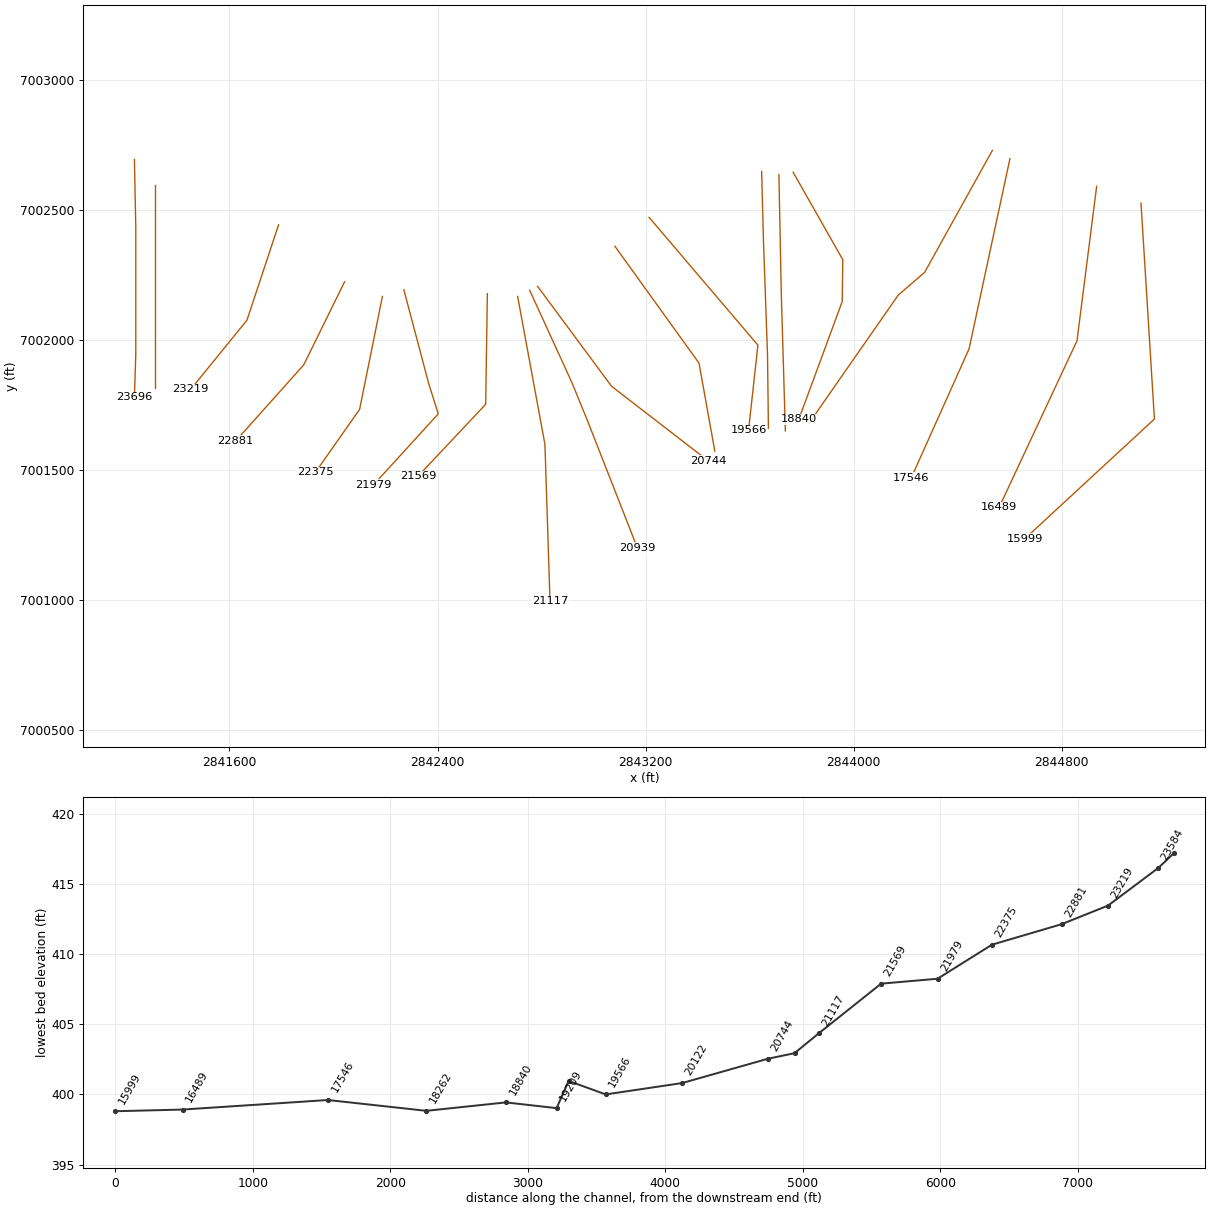
HEC-RAS study LITTLE MUSTANG CREEK.prj: LITTLE MUSTANG CREEK Base Level Engineering

--- LITTLE MUSTANG CREEK.g01 (geometry) --- (continued)

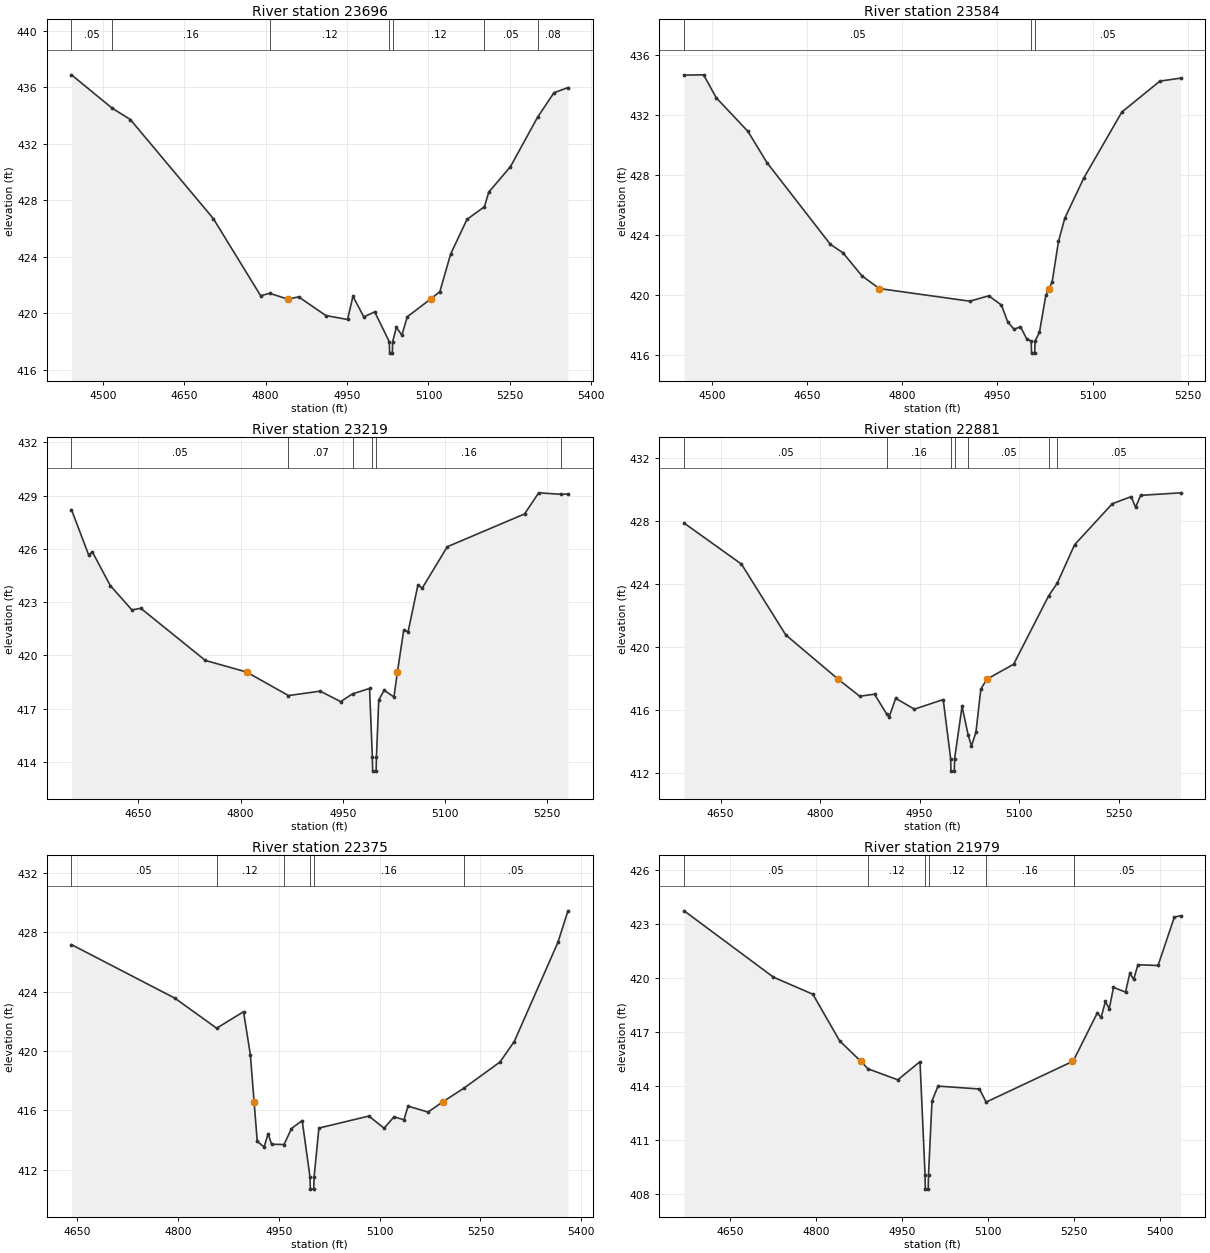
Type RM Length L Ch R = 1,23696,112,112,112
BEGIN DESCRIPTION:
Mapping XS 8b8a8f50
END DESCRIPTION:
XS GIS Cut Line= 4
      2841234.50      7002693.37      2841239.71      7002434.71
      2841239.71      7001943.39      2841234.52      7001779.20
#Sta/Elev= 30
  4442.5  436.87  4517.1  434.52  4550.9  433.71  4703.6  426.71  4790.9  421.25
  4807.6  421.42  4840.8  421.01  4860.9  421.17  4910.9  419.85  4950.9  419.57
  4960.9  421.21  4980.9  419.75  5000.9  420.11  5027.9  417.99  5028.4  417.19
  5033.4  417.19  5033.9  417.99  5040.9  419.02  5050.9  418.46  5060.9  419.76
  5103.7  421.01  5120.9  421.54  5140.9  424.21  5170.9  426.65  5203.0  427.54
  5210.9  428.57  5251.0  430.38  5301.0  433.88  5331.0  435.60  5356.8  435.97
#Mann=7,-1,0
  4442.5    0.05       0  4517.1    0.16       0  4807.6    0.12       0
  5027.9    0.07       0  5033.9    0.12       0  5203.0    0.05       0
  5301.0    0.08       0
Bank Sta=4840.8,5103.7
Exp/Cntr=0.3,0.1

Type RM Length L Ch R = 1,23584,365,365,365
BEGIN DESCRIPTION:
LITTLE MUSTANG CREEK 25.0
END DESCRIPTION:
XS GIS Cut Line= 3
      2841313.49      7002595.73      2841313.49      7002244.17
      2841313.49      7001812.33
#Sta/Elev= 30
  4455.6  434.67  4486.3  434.69  4506.3  433.16  4556.3  430.92  4586.3  428.84
  4686.3  423.40  4706.3  422.83  4736.3  421.29  4763.8  420.45  4906.3  419.61
  4936.3  419.97  4956.3  419.35  4966.3  418.22  4976.3  417.74  4986.3  417.91
  4996.3  417.09  5003.3  416.95  5003.8  416.15  5008.8  416.15  5009.3  416.95
  5016.3  417.54  5026.3  420.00  5031.3  420.45  5036.3  420.89  5046.3  423.59
  5056.3  425.14  5086.3  427.82  5146.3  432.21  5206.3  434.27  5239.0  434.47
#Mann=3,-1,0
  4455.6    0.05       0  5003.3    0.04       0  5009.3    0.05       0
Bank Sta=4763.8,5031.3
Exp/Cntr=0.3,0.1

Type RM Length L Ch R = 1,23219,338,338,338
BEGIN DESCRIPTION:
LITTLE MUSTANG CREEK 24.0
END DESCRIPTION:
XS GIS Cut Line= 3
      2841788.74      7002441.61      2841667.23      7002074.90
      2841451.05      7001809.00
#Sta/Elev= 30
  4551.6  428.21  4576.9  425.65  4582.1  425.84  4608.6  423.93  4640.3  422.56
  4653.4  422.65  4748.2  419.71  4808.6  419.06  4870.2  417.73  4916.7  417.98
  4946.8  417.39  4964.5  417.83  4989.3  418.13  4993.4  414.27  4993.9  413.47
  4998.9  413.47  4999.4  414.27  5002.8  417.48  5010.7  418.03  5025.1  417.65
  5030.2  419.06  5039.5  421.43  5045.9  421.33  5060.3  423.96  5066.7  423.79
  5103.4  426.12  5216.9  427.97  5237.7  429.16  5269.7  429.08  5280.6  429.09
#Mann=6,-1,0
  4551.6    0.05       0  4870.2    0.07       0  4964.5    0.16       0
  4993.4    0.07       0  4999.4    0.16       0  5269.7    0.05       0
Bank Sta=4808.6,5030.2
Exp/Cntr=0.3,0.1

Type RM Length L Ch R = 1,22881,506,506,506
BEGIN DESCRIPTION:
LITTLE MUSTANG CREEK 23.0
END DESCRIPTION:
XS GIS Cut Line= 3
      2842042.67      7002222.48      2841885.49      7001902.98
      2841623.84      7001610.51
#Sta/Elev= 30
  4595.0  427.87  4681.4  425.27  4748.2  420.78  4827.2  417.97  4859.7  416.89
  4882.0  417.02  4900.2  415.77  4904.2  415.59  4914.0  416.76  4942.1  416.07
  4985.6  416.68  4996.8  412.94  4997.3  412.14  5002.3  412.14  5002.8  412.94
  5014.0  416.24  5023.3  414.42  5028.2  413.74  5034.9  414.59  5042.3  417.34
  5051.3  417.97  5091.8  418.92  5144.7  423.27  5157.4  424.05  5183.7  426.50
  5240.6  429.10  5269.0  429.55  5275.7  428.87  5283.2  429.63  5343.5  429.79
#Mann=7,-1,0
  4595.0    0.05       0  4900.2    0.16       0  4996.8    0.07       0
  5002.8    0.16       0  5023.3    0.05       0  5144.7    0.16       0
  5157.4    0.05       0
Bank Sta=4827.2,5051.3
Exp/Cntr=0.3,0.1

Type RM Length L Ch R = 1,22375,396,396,396
BEGIN DESCRIPTION:
LITTLE MUSTANG CREEK 22.0
END DESCRIPTION:
XS GIS Cut Line= 3
      2842188.06      7002166.04      2842100.50      7001732.13
      2841930.25      7001489.57
#Sta/Elev= 30
  4641.3  427.18  4795.4  423.56  4857.4  421.54  4897.4  422.65  4907.6  419.74
  4913.1  416.59  4917.8  413.91  4928.0  413.52  4934.0  414.43  4939.1  413.71
  4957.7  413.69  4968.8  414.77  4984.7  415.31  4996.4  411.48  4996.9  410.68
  5001.9  410.68  5002.4  411.48  5009.6  414.80  5084.0  415.61  5106.6  414.79
  5121.4  415.56  5136.2  415.36  5142.3  416.28  5172.0  415.88  5194.7  416.59
  5225.7  417.50  5279.2  419.26  5300.4  420.64  5365.4  427.33  5380.3  429.46
#Mann=6,-1,0
  4641.3    0.05       0  4857.4    0.12       0  4957.7    0.16       0
  4996.4    0.07       0  5002.4    0.16       0  5225.7    0.05       0
Bank Sta=4913.1,5194.7
Exp/Cntr=0.3,0.1

Type RM Length L Ch R = 1,21979,410,410,410
BEGIN DESCRIPTION:
Mapping XS 778500cf
END DESCRIPTION:
XS GIS Cut Line= 4
      2842270.54      7002192.05      2842366.01      7001831.84
      2842402.90      7001714.65      2842153.34      7001441.22
#Sta/Elev= 30
  4569.6  423.73  4725.3  420.04  4794.1  419.09  4840.7  416.50  4878.0  415.35
  4890.3  414.94  4942.2  414.33  4980.9  415.34  4989.7  409.05  4990.2  408.25
  4995.2  408.25  4995.7  409.05  5001.8  413.15  5012.3  413.98  5084.6  413.82
  5096.2  413.09  5246.7  415.35  5249.1  415.44  5290.0  418.05  5296.7  417.80
  5304.2  418.69  5310.9  418.28  5318.3  419.47  5339.3  419.21  5346.7  420.25
  5353.5  419.92  5360.9  420.73  5396.0  420.69  5424.4  423.38  5435.3  423.46
#Mann=6,-1,0
  4569.6    0.05       0  4890.3    0.12       0  4989.7    0.07       0
  4995.7    0.12       0  5096.2    0.16       0  5249.1    0.05       0
Bank Sta=4878,5246.7
Exp/Cntr=0.3,0.1

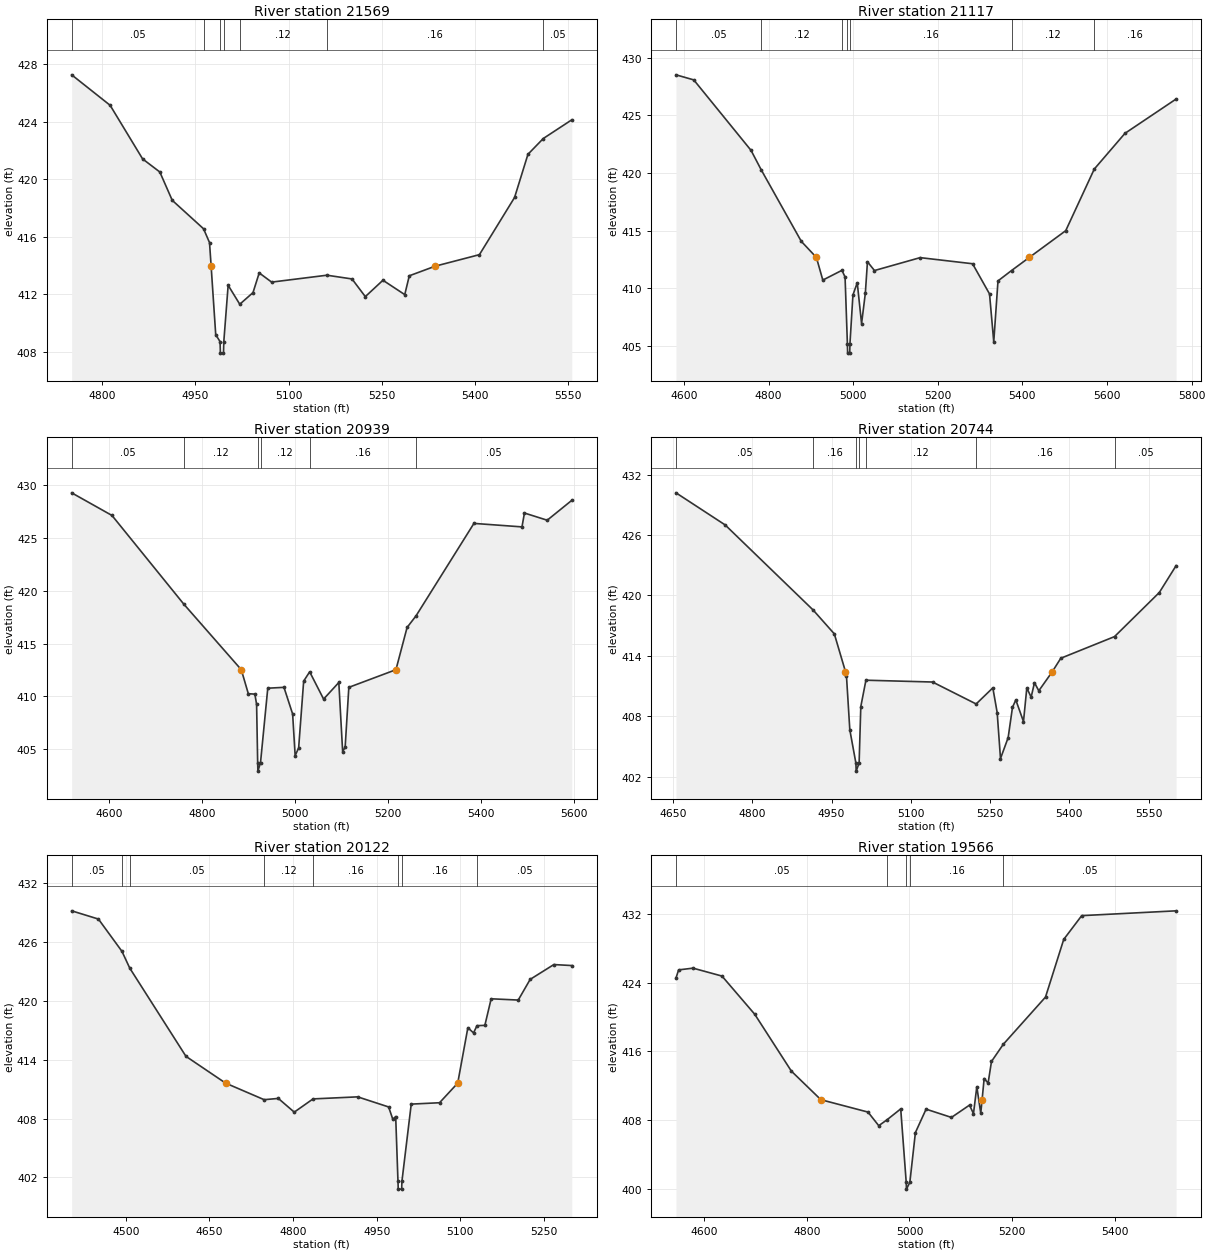
Type RM Length L Ch R = 1,21569,452,452,452
BEGIN DESCRIPTION:
LITTLE MUSTANG CREEK 21.0
END DESCRIPTION:
XS GIS Cut Line= 3
      2842591.71      7002176.89      2842585.20      7001751.55
      2842325.00      7001475.00
#Sta/Elev= 30
  4750.7  427.26  4812.6  425.14  4864.9  421.41  4892.6  420.50  4912.6  418.53
  4963.0  416.55  4972.6  415.59  4975.2  413.95  4982.6  409.18  4989.6  408.70
  4990.1  407.90  4995.1  407.90  4995.6  408.70  5002.6  412.62  5021.3  411.30
  5042.6  412.11  5052.6  413.48  5072.6  412.84  5161.6  413.32  5202.0  413.06
  5223.4  411.83  5251.8  412.97  5286.9  411.97  5294.2  413.28  5336.0  413.95
  5407.1  414.75  5463.7  418.73  5485.2  421.73  5509.9  422.83  5555.8  424.13
#Mann=7,-1,0
  4750.7    0.05       0  4963.0    0.16       0  4989.6    0.07       0
  4995.6    0.16       0  5021.3    0.12       0  5161.6    0.16       0
  5509.9    0.05       0
Bank Sta=4975.2,5336
Exp/Cntr=0.3,0.1

Type RM Length L Ch R = 1,21117,178,178,178
BEGIN DESCRIPTION:
LITTLE MUSTANG CREEK 20.0
END DESCRIPTION:
XS GIS Cut Line= 3
      2842708.16      7002166.29      2842813.06      7001597.47
      2842832.59      7000994.20
#Sta/Elev= 30
  4581.3  428.53  4623.3  428.09  4758.7  421.97  4782.6  420.29  4877.5  414.07
  4913.1  412.68  4928.3  410.71  4973.6  411.56  4980.9  410.97  4986.4  405.17
  4986.9  404.37  4991.9  404.37  4992.4  405.17  4999.5  409.42  5009.7  410.48
  5019.9  406.93  5028.8  409.57  5033.8  412.30  5050.4  411.54  5158.4  412.66
  5282.2  412.13  5322.3  409.51  5332.3  405.35  5342.3  410.64  5374.3  411.54
  5416.4  412.68  5502.4  415.00  5569.9  420.35  5642.4  423.45  5763.3  426.43
#Mann=7,-1,0
  4581.3    0.05       0  4782.6    0.12       0  4973.6    0.16       0
  4986.4    0.07       0  4992.4    0.16       0  5374.3    0.12       0
  5569.9    0.16       0
Bank Sta=4913.1,5416.4
Exp/Cntr=0.3,0.1

Type RM Length L Ch R = 1,20939,195,195,195
BEGIN DESCRIPTION:
LITTLE MUSTANG CREEK 19.0
END DESCRIPTION:
XS GIS Cut Line= 4
      2842754.47      7002189.90      2842917.23      7001834.01
      2842975.82      7001690.78      2843168.59      7001199.11
#Sta/Elev= 30
  4520.4  429.25  4607.0  427.11  4761.2  418.73  4884.7  412.53  4899.8  410.26
  4913.9  410.22  4917.6  409.25  4919.9  403.74  4920.4  402.94  4926.0  403.74
  4941.6  410.78  4976.4  410.86  4995.0  408.34  5000.4  404.41  5007.9  405.13
  5018.7  411.45  5031.6  412.33  5061.5  409.75  5094.2  411.32  5102.4  404.79
  5107.8  405.20  5115.7  410.86  5216.9  412.53  5240.8  416.52  5260.2  417.63
  5384.4  426.36  5487.6  426.03  5492.9  427.34  5541.8  426.66  5594.6  428.54
#Mann=6,-1,0
  4520.4    0.05       0  4761.2    0.12       0  4919.9    0.07       0
  4926.0    0.12       0  5031.6    0.16       0  5260.2    0.05       0
Bank Sta=4884.7,5216.9
Exp/Cntr=0.3,0.1

Type RM Length L Ch R = 1,20744,622,622,622
BEGIN DESCRIPTION:
LITTLE MUSTANG CREEK 18.0
END DESCRIPTION:
XS GIS Cut Line= 3
      2842784.83      7002205.13      2843069.14      7001820.99
      2843440.15      7001534.59
#Sta/Elev= 30
  4655.6  430.18  4748.7  426.99  4915.2  418.54  4955.3  416.17  4976.4  412.42
  4978.3  411.97  4984.6  406.64  4996.1  403.34  4996.6  402.54  5002.2  403.34
  5005.4  408.95  5015.1  411.57  5141.2  411.39  5223.7  409.21  5255.3  410.81
  5263.5  408.36  5269.8  403.79  5284.3  405.87  5292.5  408.88  5298.8  409.61
  5313.3  407.46  5319.6  410.80  5327.8  409.89  5334.1  411.32  5342.3  410.52
  5367.9  412.42  5383.9  413.75  5485.6  415.90  5570.4  420.28  5602.2  422.95
#Mann=7,-1,0
  4655.6    0.05       0  4915.2    0.16       0  4996.1    0.07       0
  5002.2    0.16       0  5015.1    0.12       0  5223.7    0.16       0
  5485.6    0.05       0
Bank Sta=4976.4,5367.9
Exp/Cntr=0.3,0.1

Type RM Length L Ch R = 1,20122,556,556,556
BEGIN DESCRIPTION:
Mapping XS 2587322d
END DESCRIPTION:
XS GIS Cut Line= 3
      2843082.16      7002359.18      2843405.51      7001909.97
      2843466.26      7001571.47
#Sta/Elev= 30
  4402.7  429.19  4450.7  428.35  4492.9  425.06  4506.9  423.35  4607.8  414.35
  4678.9  411.62  4748.1  409.93  4773.5  410.06  4802.1  408.66  4835.8  410.01
  4915.9  410.22  4971.4  409.19  4979.0  407.92  4984.1  408.21  4988.2  401.61
  4988.7  400.81  4994.8  400.81  4995.3  401.61  5012.0  409.48  5062.8  409.62
  5095.4  411.62  5113.6  417.27  5123.8  416.74  5130.0  417.48  5144.1  417.51
  5155.4  420.22  5204.0  420.09  5225.4  422.20  5267.9  423.71  5300.1  423.61
#Mann=8,-1,0
  4402.7    0.05       0  4492.9    0.16       0  4506.9    0.05       0
  4748.1    0.12       0  4835.8    0.16       0  4988.2    0.07       0
  4995.3    0.16       0  5130.0    0.05       0
Bank Sta=4678.9,5095.4
Exp/Cntr=0.3,0.1

Type RM Length L Ch R = 1,19566,270,270,270
BEGIN DESCRIPTION:
LITTLE MUSTANG CREEK 17.0
END DESCRIPTION:
XS GIS Cut Line= 3
      2843213.68      7002470.28      2843632.07      7001978.98
      2843596.05      7001652.16
#Sta/Elev= 30
  4545.2  424.52  4550.3  425.47  4578.4  425.67  4634.8  424.75  4698.5  420.32
  4769.9  413.71  4827.4  410.39  4919.2  408.95  4940.1  407.37  4955.9  408.04
  4982.9  409.32  4993.6  400.80  4994.1  400.00  5000.7  400.80  5011.5  406.57
  5032.3  409.29  5081.7  408.33  5116.9  409.76  5124.6  408.77  5131.1  411.90
  5138.8  408.82  5141.4  410.39  5145.4  412.85  5153.1  412.32  5159.7  414.83
  5182.6  416.82  5264.9  422.31  5300.4  429.01  5335.4  431.77  5519.3  432.33
#Mann=5,-1,0
  4545.2    0.05       0  4955.9    0.16       0  4993.6    0.07       0
  5000.7    0.16       0  5182.6    0.05       0
Bank Sta=4827.4,5141.4
Exp/Cntr=0.3,0.1

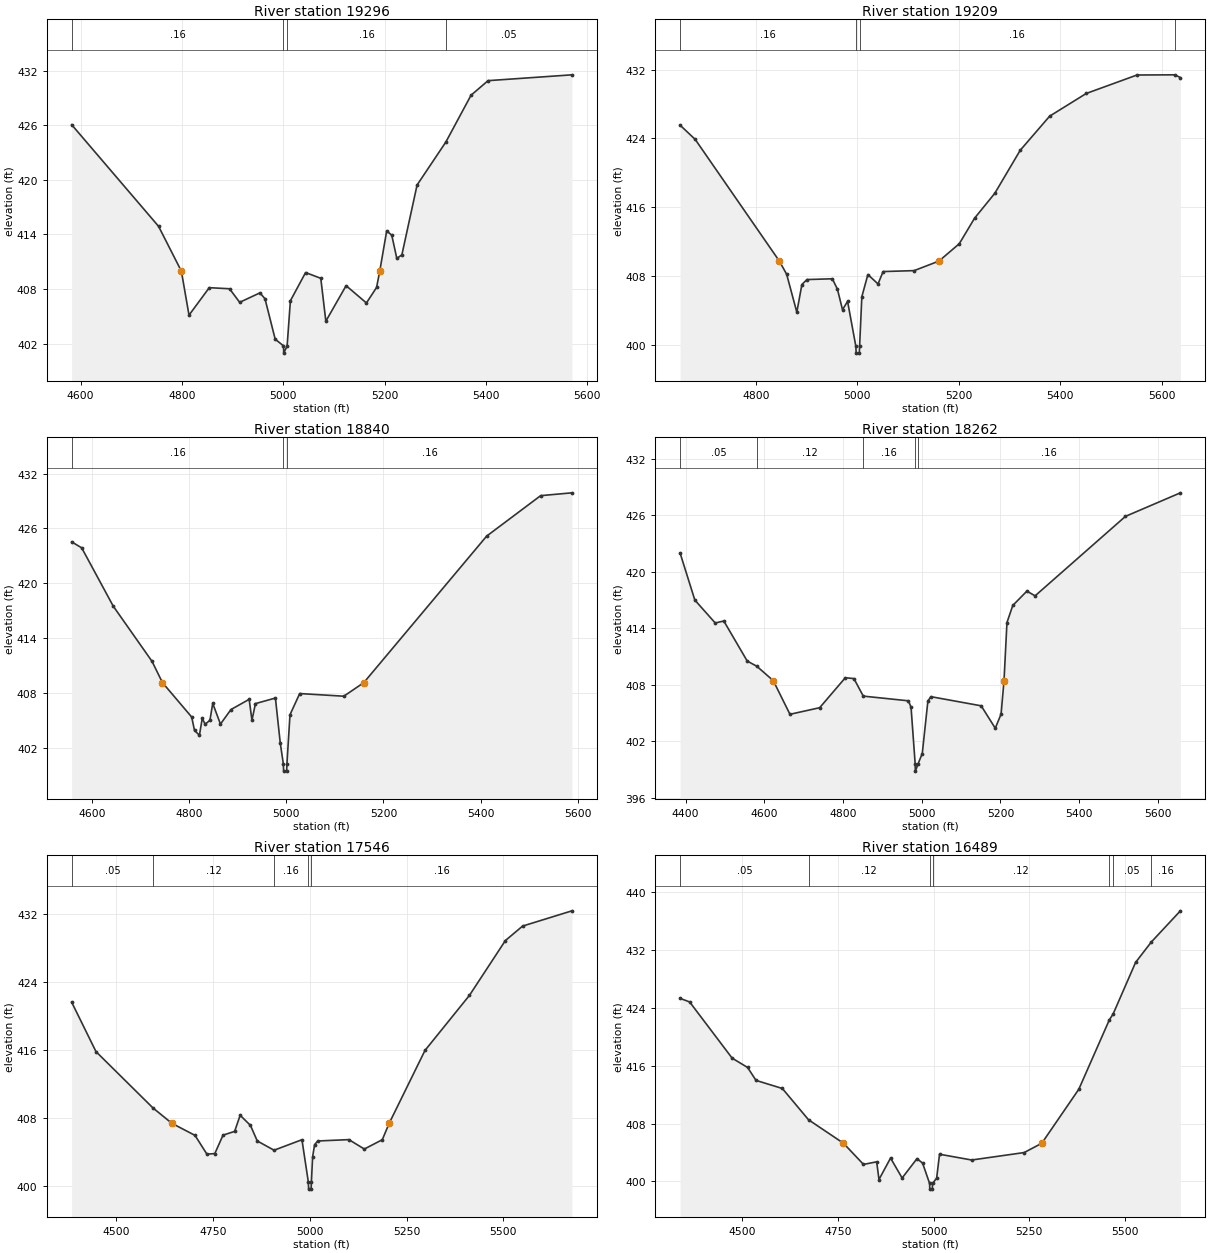
Type RM Length L Ch R = 1,19296,87,87,87
BEGIN DESCRIPTION:
Mapping XS da5010a0
END DESCRIPTION:
XS GIS Cut Line= 4
      2843646.39      7002646.48      2843653.34      7002380.89
      2843668.96      7001941.65      2843672.43      7001659.37
#Sta/Elev= 30
  4582.5  426.05  4754.0  414.89  4799.0  409.97  4814.1  405.13  4854.1  408.15
  4894.1  408.03  4914.1  406.54  4954.1  407.58  4964.1  406.93  4984.2  402.49
  5000.6  401.76  5001.1  400.96  5007.8  401.76  5014.2  406.71  5044.2  409.81
  5074.2  409.18  5084.2  404.47  5124.2  408.37  5164.3  406.47  5184.3  408.17
  5190.6  409.97  5204.3  414.38  5214.3  413.92  5224.3  411.36  5234.3  411.76
  5264.3  419.43  5321.1  424.15  5370.8  429.29  5404.4  430.89  5570.0  431.53
#Mann=4,-1,0
  4582.5    0.16       0  5000.6    0.07       0  5007.8    0.16       0
  5321.1    0.05       0
Bank Sta=4799,5190.6
Exp/Cntr=0.3,0.1

Type RM Length L Ch R = 1,19209,369,369,369
BEGIN DESCRIPTION:
LITTLE MUSTANG CREEK 16.0
END DESCRIPTION:
XS GIS Cut Line= 3
      2843712.80      7002634.84      2843721.91      7002177.76
      2843737.53      7001649.56
#Sta/Elev= 30
  4651.1  425.54  4680.9  423.88  4846.6  409.73  4861.0  408.19  4881.0  403.78
  4891.0  407.00  4901.0  407.58  4951.0  407.67  4961.0  406.46  4971.0  404.07
  4981.0  405.04  4997.3  399.82  4997.9  399.02  5004.1  399.02  5004.7  399.82
  5009.1  405.58  5021.0  408.16  5041.0  407.07  5051.0  408.51  5112.2  408.62
  5161.0  409.73  5201.1  411.75  5231.1  414.71  5271.1  417.62  5321.1  422.62
  5379.1  426.59  5451.2  429.23  5551.2  431.38  5625.8  431.40  5636.7  431.08
#Mann=4,-1,0
  4651.1    0.16       0  4997.3    0.07       0  5004.7    0.16       0
  5625.8    0.05       0
Bank Sta=4846.6,5161
Exp/Cntr=0.3,0.1

Type RM Length L Ch R = 1,18840,578,578,578
BEGIN DESCRIPTION:
Mapping XS 6ed1d785
END DESCRIPTION:
XS GIS Cut Line= 4
      2843767.50      7002643.88      2843958.46      7002307.54
      2843956.29      7002146.94      2843789.58      7001694.45
#Sta/Elev= 30
  4558.5  424.52  4579.1  423.87  4644.0  417.49  4723.9  411.44  4745.3  409.12
  4805.5  405.35  4811.3  403.88  4821.4  403.36  4827.2  405.20  4833.2  404.57
  4843.0  404.99  4848.8  406.84  4864.7  404.58  4886.3  406.17  4923.8  407.29
  4929.5  405.00  4936.7  406.82  4977.8  407.43  4987.8  402.49  4994.1  400.23
  4994.7  399.43  5000.9  399.43  5001.5  400.23  5007.8  405.60  5027.8  407.92
  5118.6  407.63  5159.8  409.12  5412.5  425.15  5523.6  429.58  5588.1  429.89
#Mann=3,-1,0
  4558.5    0.16       0  4994.1    0.07       0  5001.5    0.16       0
Bank Sta=4745.3,5159.8
Exp/Cntr=0.3,0.1

Type RM Length L Ch R = 1,18262,716,716,716
BEGIN DESCRIPTION:
LITTLE MUSTANG CREEK 15.0
END DESCRIPTION:
XS GIS Cut Line= 4
      2844533.53      7002727.65      2844273.13      7002258.92
      2844171.51      7002171.27      2843828.25      7001678.19
#Sta/Elev= 30
  4386.1  421.96  4423.5  416.98  4475.3  414.55  4497.1  414.76  4556.6  410.51
  4580.9  409.96  4622.8  408.43  4665.2  404.86  4740.7  405.56  4805.9  408.74
  4827.7  408.65  4851.5  406.79  4966.3  406.29  4972.9  405.60  4983.3  399.63
  4983.9  398.83  4991.0  399.63  5001.4  400.70  5015.7  406.28  5023.4  406.73
  5151.1  405.76  5186.9  403.38  5201.7  404.89  5209.1  408.43  5216.6  414.60
  5231.4  416.41  5267.2  417.93  5288.1  417.43  5517.6  425.86  5657.3  428.36
#Mann=5,-1,0
  4386.1    0.05       0  4580.9    0.12       0  4851.5    0.16       0
  4983.3    0.07       0  4991.0    0.16       0
Bank Sta=4622.8,5209.1
Exp/Cntr=0.3,0.1

Type RM Length L Ch R = 1,17546,1057,1057,1057
BEGIN DESCRIPTION:
LITTLE MUSTANG CREEK 14.0
END DESCRIPTION:
XS GIS Cut Line= 3
      2844601.24      7002696.38      2844443.88      7001964.44
      2844221.66      7001468.62
#Sta/Elev= 30
  4385.0  421.65  4447.8  415.82  4595.1  409.17  4643.9  407.36  4703.5  405.94
  4734.2  403.73  4754.6  403.79  4775.9  405.97  4805.8  406.41  4820.1  408.31
  4846.7  407.12  4864.3  405.28  4907.7  404.19  4979.7  405.43  4996.3  400.40
  4996.9  399.60  5003.4  399.60  5004.0  400.40  5007.3  403.44  5012.4  404.85
  5020.6  405.28  5100.9  405.44  5140.8  404.33  5187.2  405.43  5204.9  407.36
  5297.4  415.96  5412.3  422.46  5505.0  428.92  5549.5  430.63  5677.0  432.43
#Mann=5,-1,0
  4385.0    0.05       0  4595.1    0.12       0  4907.7    0.16       0
  4996.3    0.07       0  5004.0    0.16       0
Bank Sta=4643.9,5204.9
Exp/Cntr=0.3,0.1

Type RM Length L Ch R = 1,16489,490,490,490
BEGIN DESCRIPTION:
LITTLE MUSTANG CREEK 13.0
END DESCRIPTION:
XS GIS Cut Line= 3
      2844934.58      7002589.61      2844859.07      7001995.90
      2844559.78      7001355.69
#Sta/Elev= 30
  4338.9  425.32  4363.7  424.83  4474.6  417.05  4514.9  415.76  4536.9  413.97
  4605.6  412.85  4673.9  408.52  4765.1  405.27  4817.3  402.34  4851.7  402.70
  4857.7  400.25  4887.9  403.22  4918.1  400.46  4956.9  403.14  4971.5  402.52
  4989.7  399.72  4990.3  398.92  4996.8  398.92  4997.5  399.72  5008.1  400.42
  5015.7  403.75  5099.5  402.95  5236.4  403.98  5282.5  405.27  5379.1  412.75
  5458.8  422.36  5468.4  423.14  5527.2  430.30  5568.0  433.11  5644.1  437.44
#Mann=7,-1,0
  4338.9    0.05       0  4673.9    0.12       0  4989.7    0.07       0
  4997.5    0.12       0  5458.8    0.16       0  5468.4    0.05       0
  5568.0    0.16       0
Bank Sta=4765.1,5282.5
Exp/Cntr=0.3,0.1

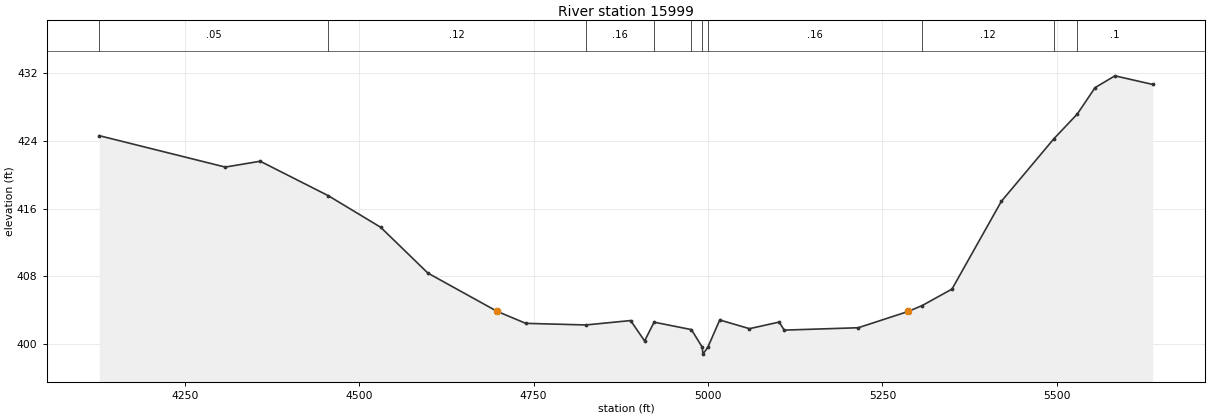
Type RM Length L Ch R = 1,15999,0,0,0
BEGIN DESCRIPTION:
LITTLE MUSTANG CREEK 12.0
END DESCRIPTION:
XS GIS Cut Line= 3
      2845105.16      7002525.11      2845156.72      7001694.89
      2844658.61      7001234.66
#Sta/Elev= 30
  4127.5  424.63  4308.0  420.92  4358.1  421.61  4455.6  417.54  4530.8  413.80
  4598.5  408.38  4697.9  403.85  4738.8  402.44  4824.9  402.25  4889.1  402.77
  4909.1  400.36  4922.7  402.58  4976.2  401.70  4991.9  399.60  4992.6  398.80
  4999.7  399.60  5016.8  402.84  5059.4  401.81  5101.9  402.59  5109.3  401.64
  5215.3  401.92  5287.1  403.85  5307.1  404.55  5349.7  406.49  5420.5  416.87
  5495.8  424.27  5529.3  427.19  5554.9  430.32  5583.3  431.71  5637.5  430.69
#Mann=10,-1,0
  4127.5    0.05       0  4455.6    0.12       0  4824.9    0.16       0
  4922.7    0.12       0  4976.2    0.16       0  4991.9    0.07       0
  4999.7    0.16       0  5307.1    0.12       0  5495.8    0.16       0
  5529.3     0.1       0
Bank Sta=4697.9,5287.1
Exp/Cntr=0.3,0.1

Chan Stop Cuts=-1