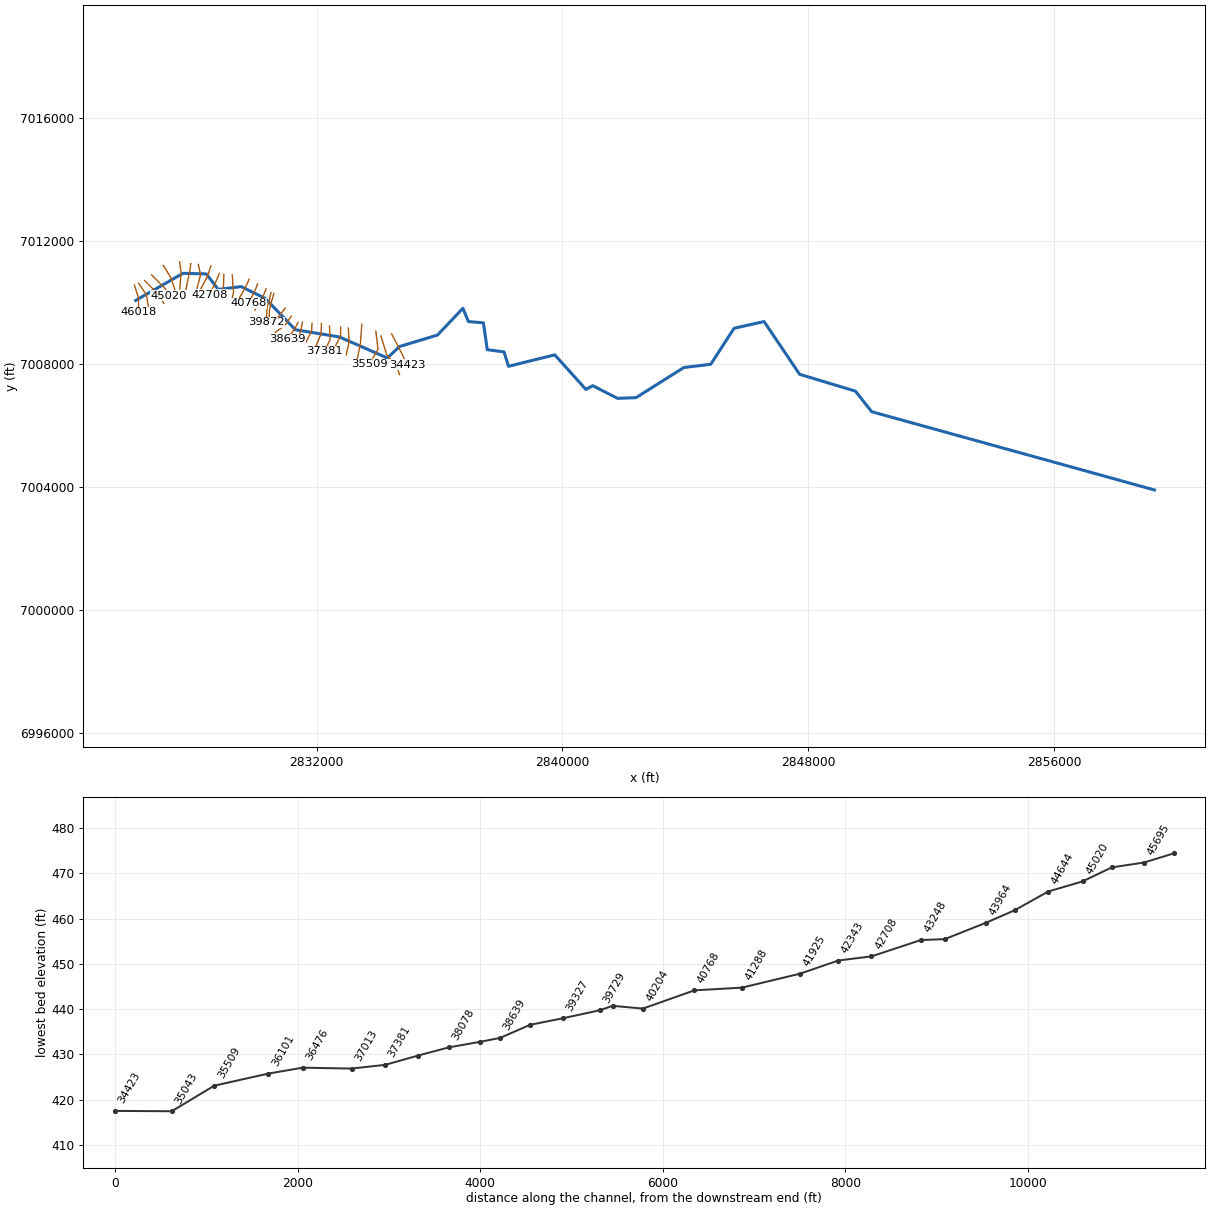
--- MUSTANG CREEK.prj (project) ---

Proj Title=MUSTANG CREEK Base Level Engineering
Current Plan=p01
Default Exp/Contr=0.3,0.1
English Units
Geom File=g01
Flow File=f01
Plan File=p01
BEGIN DESCRIPTION:
MUSTANG CREEK
END DESCRIPTION:

--- MUSTANG CREEK.p01 (plan) ---

Plan Title=Multiple Run
Short Identifier=Multiple
Geom File=g01
Flow File=f01
Subcritical Flow
K Sum by GR= 0
Std Step Tol= 0.01
Critical Tol= 0.01
Num of Std Step Trials= 20
Max Error Tol= 0.3
Flow Tol Ratio= 0.001
Split Flow NTrial= 30
Split Flow Tol= 0.02
Split Flow Ratio= 0.02
Log Output Level= 0
Friction Slope Method= 1
Unsteady Friction Slope Method= 2
Unsteady Bridges Friction Slope Method= 1
Parabolic Critical Depth
Global Vel Dist=  1 , 1 , 1
Global Log Level= 0
CheckData=True
Encroach Param= -1, 0, 0, 0
BEGIN DESCRIPTION:
Multiple Run
END DESCRIPTION:

--- MUSTANG CREEK.f01 (steady flow) ---

Flow Title=Multiple
Number of Profiles=7
Profile Names=10-year,25-year,50-year,1pct_min,100-year,1pct_plu,500-year
River Rch & RM= MUSTANG CREEK,Reach-1,46018
     493     650     776     460     918    1832    1288
River Rch & RM= MUSTANG CREEK,Reach-1,35509
     597     796     957     571    1140    2274    1620
River Rch & RM= MUSTANG CREEK,Reach-1,33838
    1285    1771    2175    1323    2639    5266    3899
River Rch & RM= MUSTANG CREEK,Reach-1,27921
    1512    2094    2580    1573    3139    6264    4660
River Rch & RM= MUSTANG CREEK,Reach-1,19765
    1617    2238    2757    1679    3351    6686    4965
Boundary for River Rch & Prof#=MUSTANG CREEK,Reach-1,1
Up Type=0
Dn Type=3
Dn Slope=0.005
Boundary for River Rch & Prof#=MUSTANG CREEK,Reach-1,2
Up Type=0
Dn Type=3
Dn Slope=0.005
Boundary for River Rch & Prof#=MUSTANG CREEK,Reach-1,3
Up Type=0
Dn Type=3
Dn Slope=0.005
Boundary for River Rch & Prof#=MUSTANG CREEK,Reach-1,4
Up Type=0
Dn Type=3
Dn Slope=0.005
Boundary for River Rch & Prof#=MUSTANG CREEK,Reach-1,5
Up Type=0
Dn Type=3
Dn Slope=0.005
Boundary for River Rch & Prof#=MUSTANG CREEK,Reach-1,6
Up Type=0
Dn Type=3
Dn Slope=0.005
Boundary for River Rch & Prof#=MUSTANG CREEK,Reach-1,7
Up Type=0
Dn Type=3
Dn Slope=0.005

--- MUSTANG CREEK.g01 (geometry) ---

Geom Title=Existing Conditions

River Reach=MUSTANG CREEK,Reach-1
Reach XY= 30
      2826110.19      7010075.53      2827651.93      7010958.19
      2828410.45      7010938.41      2828796.44      7010435.53
      2829544.66      7010525.76      2830330.28      7010140.91
      2831306.69      7009123.27      2832745.48      7008885.65
      2834301.35      7008202.51      2834693.22      7008575.12
      2835931.47      7008948.29      2836759.74      7009820.47
      2836938.58      7009388.47      2837427.13      7009347.51
      2837551.58      7008472.49      2838097.91      7008400.80
      2838243.60      7007932.84      2839748.76      7008305.28
      2840760.89      7007181.23      2840984.73      7007301.83
      2841791.35      7006889.84      2842394.38      7006913.00
      2843951.30      7007894.43      2844823.09      7007996.99
      2845582.06      7009169.63      2846559.83      7009388.43
      2847715.38      7007672.21      2849530.75      7007125.20
      2850060.66      7006455.12      2859260.43      7003909.00

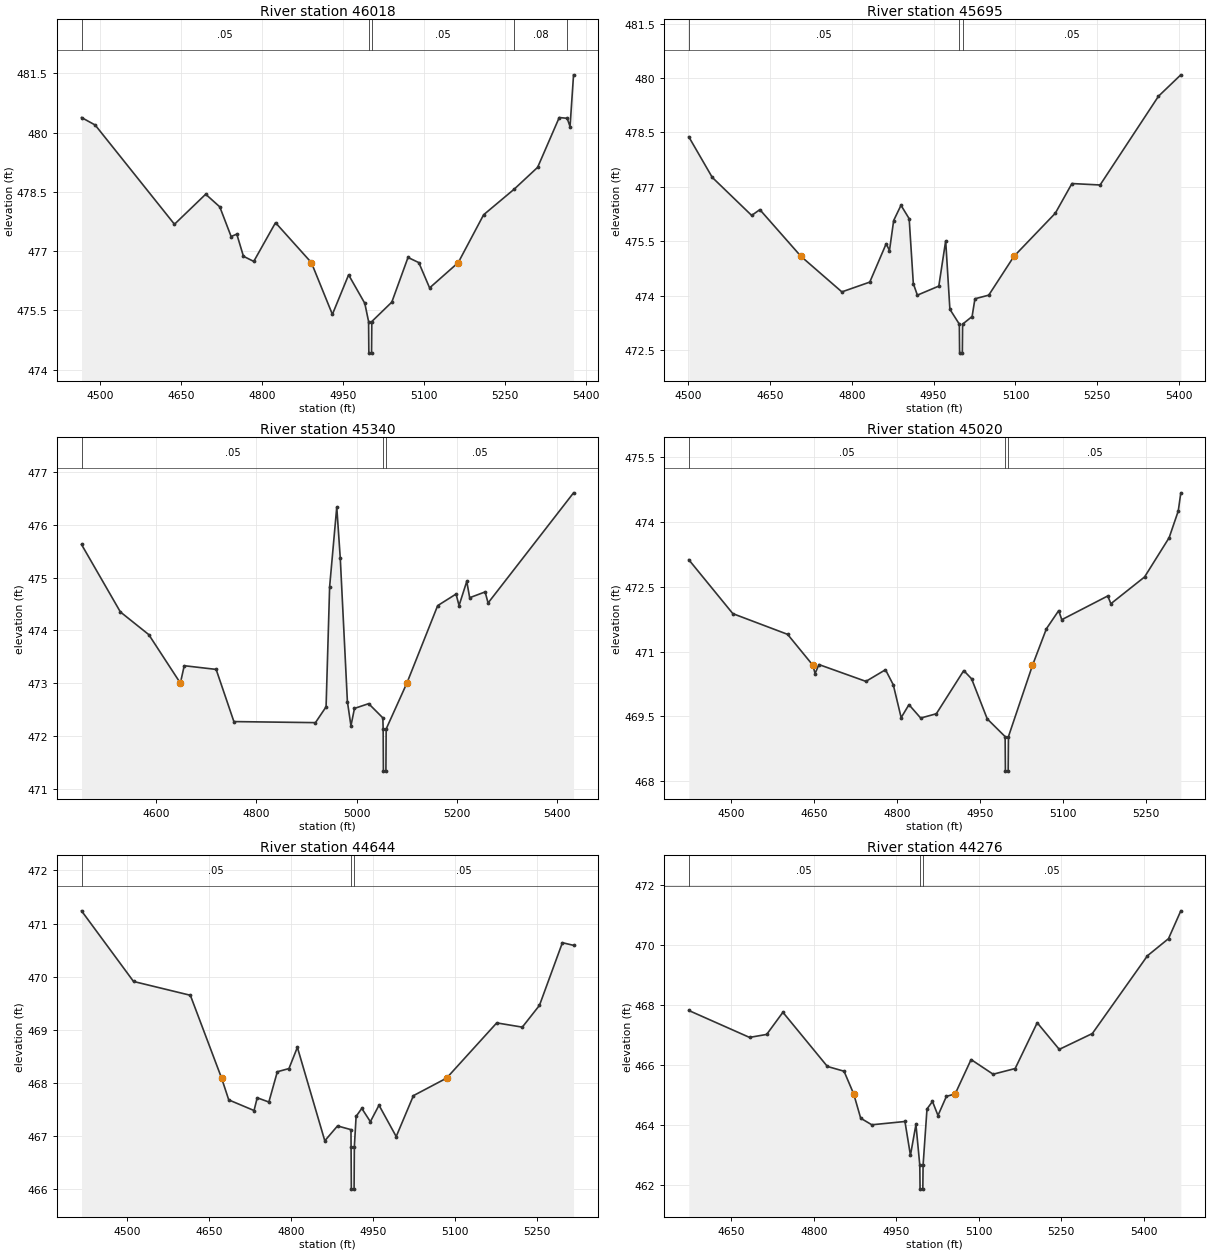
Type RM Length L Ch R = 1,46018,323,323,323
BEGIN DESCRIPTION:
MUSTANG CREEK 73.0
END DESCRIPTION:
XS GIS Cut Line= 3
      2826070.71      7010579.12      2826203.09      7010160.27
      2826205.26      7009688.55
#Sta/Elev= 30
  4466.0  480.38  4491.3  480.19  4638.1  477.68  4695.9  478.44  4722.0  478.12
  4743.0  477.37  4753.5  477.43  4765.8  476.87  4784.9  476.74  4825.2  477.72
  4891.6  476.71  4930.5  475.40  4960.5  476.40  4990.5  475.68  4997.5  475.22
  4998.0  474.42  5003.0  474.42  5003.5  475.22  5040.5  475.71  5070.5  476.84
  5090.5  476.71  5110.5  476.07  5163.5  476.71  5210.5  477.92  5267.3  478.57
  5310.5  479.12  5350.5  480.38  5365.2  480.36  5370.5  480.15  5377.0  481.46
#Mann=5,-1,0
  4466.0    0.05       0  4997.5    0.03       0  5003.5    0.05       0
  5267.3    0.08       0  5365.2    0.05       0
Bank Sta=4891.6,5163.5
Exp/Cntr=0.3,0.1

Type RM Length L Ch R = 1,45695,355,355,355
BEGIN DESCRIPTION:
MUSTANG CREEK 72.0
END DESCRIPTION:
XS GIS Cut Line= 3
      2826207.45      7010637.67      2826456.92      7010262.13
      2826537.06      7009818.67
#Sta/Elev= 30
  4501.5  478.38  4544.5  477.26  4616.7  476.21  4631.7  476.37  4707.1  475.08
  4782.0  474.10  4833.1  474.37  4863.2  475.43  4869.2  475.24  4876.9  476.07
  4890.3  476.49  4905.3  476.12  4912.9  474.33  4920.3  474.01  4959.6  474.26
  4972.2  475.51  4979.9  473.62  4997.2  473.21  4997.7  472.41  5002.7  472.41
  5003.2  473.21  5020.6  473.42  5025.8  473.91  5051.1  474.01  5097.2  475.08
  5173.0  476.27  5203.5  477.09  5255.1  477.05  5362.1  479.50  5403.0  480.09
#Mann=3,-1,0
  4501.5    0.05       0  4997.2    0.03       0  5003.2    0.05       0
Bank Sta=4707.1,5097.2
Exp/Cntr=0.3,0.1

Type RM Length L Ch R = 1,45340,320,320,320
BEGIN DESCRIPTION:
MUSTANG CREEK 71.0
END DESCRIPTION:
XS GIS Cut Line= 3
      2826402.74      7010722.34      2826835.01      7010294.96
      2827031.05      7009977.48
#Sta/Elev= 30
  4451.3  475.63  4528.8  474.35  4585.4  473.92  4648.4  473.00  4656.1  473.33
  4719.7  473.26  4755.1  472.27  4917.7  472.25  4938.9  472.55  4946.0  474.83
  4960.2  476.34  4967.2  475.37  4981.4  472.65  4988.5  472.19  4995.5  472.52
  5023.8  472.61  5052.1  472.34  5052.7  472.13  5053.2  471.33  5058.2  471.33
  5058.7  472.13  5100.0  473.00  5161.4  474.47  5198.1  474.69  5204.0  474.47
  5219.4  474.93  5225.2  474.62  5256.0  474.73  5261.9  474.52  5432.3  476.61
#Mann=3,-1,0
  4451.3    0.05       0  5052.7    0.03       0  5058.7    0.05       0
Bank Sta=4648.4,5100
Exp/Cntr=0.3,0.1

Type RM Length L Ch R = 1,45020,376,376,376
BEGIN DESCRIPTION:
MUSTANG CREEK 70.0
END DESCRIPTION:
XS GIS Cut Line= 3
      2826628.45      7010911.13      2827075.49      7010455.41
      2827190.25      7010232.38
#Sta/Elev= 30
  4423.2  473.13  4502.8  471.88  4601.8  471.40  4647.7  470.68  4651.4  470.49
  4658.4  470.70  4743.3  470.31  4778.7  470.58  4792.8  470.23  4807.0  469.47
  4821.1  469.77  4842.3  469.46  4870.6  469.56  4920.1  470.56  4934.3  470.37
  4962.6  469.44  4994.9  469.03  4995.4  468.23  5000.4  468.23  5000.9  469.03
  5044.3  470.68  5069.5  471.53  5091.7  471.95  5097.3  471.74  5180.4  472.29
  5186.0  472.11  5246.9  472.73  5291.3  473.64  5307.8  474.26  5312.4  474.68
#Mann=3,-1,0
  4423.2    0.05       0  4994.9    0.03       0  5000.9    0.05       0
Bank Sta=4647.7,5044.3
Exp/Cntr=0.3,0.1

Type RM Length L Ch R = 1,44644,368,368,368
BEGIN DESCRIPTION:
MUSTANG CREEK 69.0
END DESCRIPTION:
XS GIS Cut Line= 3
      2827012.56      7011214.94      2827268.63      7010796.12
      2827392.32      7010405.53
#Sta/Elev= 30
  4416.8  471.24  4512.0  469.91  4616.0  469.65  4673.2  468.09  4686.3  467.68
  4732.6  467.48  4738.4  467.72  4759.7  467.64  4775.2  468.21  4796.5  468.27
  4811.9  468.67  4862.1  466.91  4885.4  467.19  4910.0  467.12  4910.2  466.80
  4910.7  466.00  4915.7  466.00  4916.2  466.80  4919.4  467.37  4929.8  467.52
  4945.5  467.27  4961.3  467.58  4992.8  466.99  5024.3  467.76  5085.0  468.09
  5176.8  469.13  5223.6  469.05  5255.0  469.46  5297.0  470.64  5317.4  470.59
#Mann=3,-1,0
  4416.8    0.05       0  4910.2    0.03       0  4916.2    0.05       0
Bank Sta=4673.2,5085
Exp/Cntr=0.3,0.1

Type RM Length L Ch R = 1,44276,312,312,312
BEGIN DESCRIPTION:
MUSTANG CREEK 68.0
END DESCRIPTION:
XS GIS Cut Line= 3
      2827539.89      7011334.35      2827589.55      7010998.63
      2827548.57      7010444.52
#Sta/Elev= 30
  4572.6  467.82  4683.1  466.92  4714.3  467.02  4743.8  467.76  4824.7  465.95
  4855.0  465.79  4872.6  465.03  4885.3  464.22  4905.5  464.00  4965.8  464.11
  4975.8  462.98  4985.8  464.01  4992.8  462.65  4993.3  461.85  4998.3  461.85
  4998.8  462.65  5005.9  464.53  5015.9  464.78  5025.9  464.31  5041.2  464.95
  5057.1  465.03  5086.1  466.18  5126.2  465.69  5166.3  465.88  5206.4  467.41
  5246.5  466.52  5306.7  467.05  5407.0  469.65  5445.2  470.22  5467.6  471.15
#Mann=3,-1,0
  4572.6    0.05       0  4992.8    0.03       0  4998.8    0.05       0
Bank Sta=4872.6,5057.1
Exp/Cntr=0.3,0.1

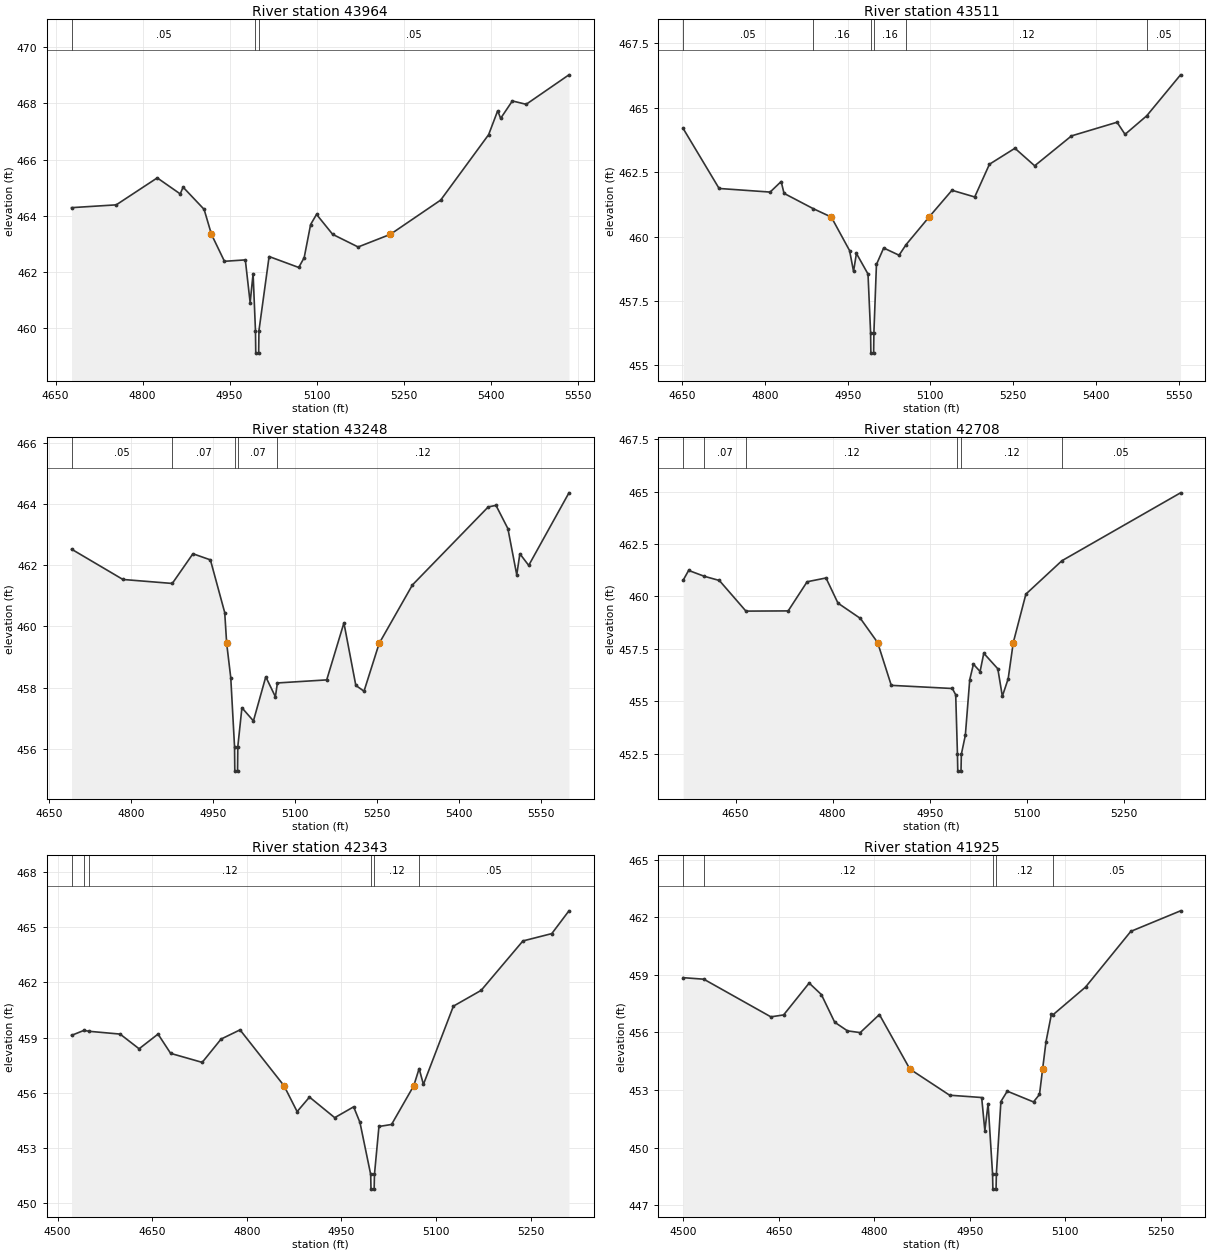
Type RM Length L Ch R = 1,43964,453,453,453
BEGIN DESCRIPTION:
MUSTANG CREEK 67.0
END DESCRIPTION:
XS GIS Cut Line= 3
      2827906.65      7011271.38      2827869.76      7011008.79
      2827743.95      7010429.66
#Sta/Elev= 30
  4677.4  464.29  4754.5  464.39  4825.2  465.35  4864.8  464.78  4869.8  465.02
  4906.0  464.23  4918.7  463.34  4941.1  462.38  4977.1  462.43  4985.4  460.91
  4990.5  461.94  4994.6  459.91  4995.1  459.11  5000.1  459.11  5000.6  459.91
  5018.1  462.55  5069.2  462.16  5078.6  462.51  5089.7  463.69  5099.9  464.05
  5127.7  463.34  5171.6  462.89  5227.2  463.34  5314.0  464.56  5396.7  466.89
  5412.3  467.74  5417.4  467.47  5437.6  468.09  5461.4  467.97  5535.2  469.02
#Mann=3,-1,0
  4677.4    0.05       0  4994.6    0.03       0  5000.6    0.05       0
Bank Sta=4918.7,5227.2
Exp/Cntr=0.3,0.1

Type RM Length L Ch R = 1,43511,263,263,263
BEGIN DESCRIPTION:
MUSTANG CREEK 66.0
END DESCRIPTION:
XS GIS Cut Line= 3
      2828147.54      7011248.37      2828225.00      7010925.00
      2828085.04      7010373.40
#Sta/Elev= 30
  4651.8  464.20  4717.0  461.87  4809.5  461.73  4829.5  462.14  4834.7  461.68
  4887.3  461.09  4920.4  460.76  4953.5  459.46  4960.7  458.65  4965.9  459.35
  4986.9  458.55  4991.6  456.28  4992.1  455.48  4997.1  455.48  4997.6  456.28
  5002.2  458.92  5015.3  459.56  5043.2  459.28  5055.9  459.69  5097.5  460.76
  5139.1  461.80  5180.3  461.54  5207.0  462.81  5253.2  463.43  5289.0  462.75
  5355.7  463.91  5438.3  464.44  5452.8  463.97  5492.1  464.69  5553.4  466.28
#Mann=6,-1,0
  4651.8    0.05       0  4887.3    0.16       0  4991.6    0.07       0
  4997.6    0.16       0  5055.9    0.12       0  5492.1    0.05       0
Bank Sta=4920.4,5097.5
Exp/Cntr=0.3,0.1

Type RM Length L Ch R = 1,43248,540,540,540
BEGIN DESCRIPTION:
MUSTANG CREEK 65.0
END DESCRIPTION:
XS GIS Cut Line= 3
      2828558.13      7011201.96      2828447.45      7010859.05
      2828184.87      7010375.13
#Sta/Elev= 30
  4691.0  462.52  4785.1  461.53  4875.5  461.40  4913.3  462.37  4945.3  462.17
  4971.5  460.45  4975.1  459.44  4982.6  458.32  4989.5  456.07  4990.0  455.27
  4995.0  455.27  4995.5  456.07  5003.0  457.34  5024.1  456.91  5046.7  458.35
  5064.3  457.70  5068.0  458.15  5158.3  458.25  5189.8  460.11  5211.6  458.07
  5226.6  457.88  5254.3  459.44  5315.2  461.35  5454.1  463.90  5468.3  463.95
  5490.1  463.19  5506.3  461.68  5512.0  462.37  5528.2  461.99  5601.9  464.36
#Mann=5,-1,0
  4691.0    0.05       0  4875.5    0.07       0  4989.5    0.07       0
  4995.5    0.07       0  5068.0    0.12       0
Bank Sta=4975.1,5254.3
Exp/Cntr=0.3,0.1

Type RM Length L Ch R = 1,42708,365,365,365
BEGIN DESCRIPTION:
MUSTANG CREEK 64.0
END DESCRIPTION:
XS GIS Cut Line= 3
      2828833.73      7010956.69      2828675.00      7010575.00
      2828501.71      7010264.45
#Sta/Elev= 30
  4568.9  460.77  4577.4  461.24  4601.7  460.96  4624.9  460.76  4666.0  459.30
  4731.3  459.31  4760.6  460.70  4789.8  460.88  4808.3  459.68  4843.0  458.95
  4869.6  457.80  4890.7  455.76  4985.1  455.61  4990.3  455.31  4993.0  452.47
  4993.5  451.67  4998.5  451.67  4999.0  452.47  5005.2  453.38  5012.0  456.03
  5017.7  456.77  5028.0  456.42  5033.7  457.29  5055.4  456.55  5062.4  455.24
  5071.4  456.07  5079.3  457.80  5098.8  460.11  5154.4  461.70  5337.9  464.94
#Mann=6,-1,0
  4568.9    0.12       0  4601.7    0.07       0  4666.0    0.12       0
  4993.0    0.07       0  4999.0    0.12       0  5154.4    0.05       0
Bank Sta=4869.6,5079.3
Exp/Cntr=0.3,0.1

Type RM Length L Ch R = 1,42343,418,418,418
BEGIN DESCRIPTION:
MUSTANG CREEK 63.0
END DESCRIPTION:
XS GIS Cut Line= 3
      2828981.30      7010922.00      2828964.35      7010393.06
      2828916.54      7010138.22
#Sta/Elev= 30
  4522.2  459.12  4541.8  459.39  4550.6  459.34  4599.2  459.19  4629.3  458.39
  4659.3  459.19  4679.3  458.14  4729.3  457.65  4759.3  458.92  4789.3  459.42
  4859.0  456.38  4879.8  454.97  4899.4  455.76  4939.4  454.64  4969.4  455.23
  4979.4  454.38  4996.4  451.55  4996.9  450.75  5001.9  450.75  5002.4  451.55
  5009.5  454.16  5029.5  454.27  5064.7  456.38  5073.2  457.31  5080.0  456.45
  5127.5  460.71  5171.5  461.57  5237.7  464.26  5283.5  464.66  5310.7  465.90
#Mann=6,-1,0
  4522.2    0.12       0  4541.8    0.07       0  4550.6    0.12       0
  4996.4    0.07       0  5002.4    0.12       0  5073.2    0.05       0
Bank Sta=4859,5064.7
Exp/Cntr=0.3,0.1

Type RM Length L Ch R = 1,41925,637,637,637
BEGIN DESCRIPTION:
MUSTANG CREEK 62.0
END DESCRIPTION:
XS GIS Cut Line= 4
      2829254.74      7010902.44      2829282.95      7010494.47
      2829297.84      7010358.19      2829246.31      7010128.85
#Sta/Elev= 30
  4499.8  458.85  4532.3  458.77  4637.6  456.81  4657.6  456.91  4697.7  458.57
  4716.9  457.97  4737.8  456.53  4757.9  456.08  4777.9  455.99  4808.0  456.93
  4855.9  454.09  4918.3  452.73  4968.6  452.61  4973.6  450.88  4978.7  452.29
  4985.7  448.64  4986.2  447.84  4991.2  447.84  4991.7  448.64  4998.8  452.40
  5008.8  452.94  5050.0  452.38  5059.4  452.77  5064.3  454.09  5069.6  455.51
  5078.2  456.96  5080.7  456.92  5131.7  458.36  5202.8  461.26  5280.9  462.33
#Mann=5,-1,0
  4499.8    0.05       0  4532.3    0.12       0  4985.7    0.07       0
  4991.7    0.12       0  5080.7    0.05       0
Bank Sta=4855.9,5064.3
Exp/Cntr=0.3,0.1

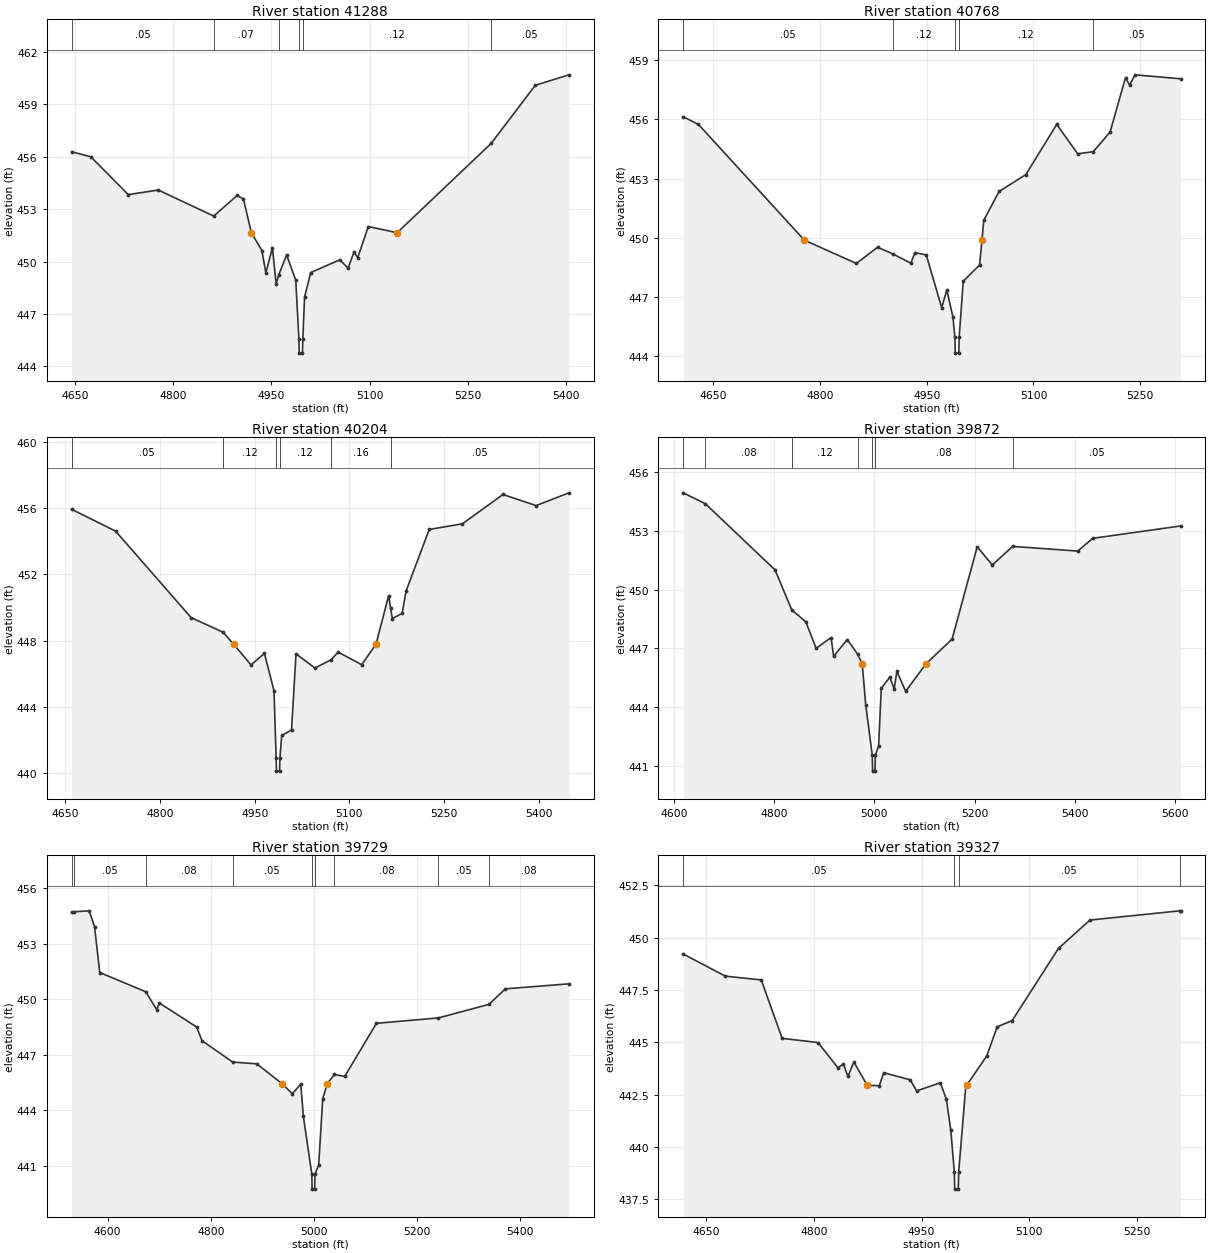
Type RM Length L Ch R = 1,41288,520,520,520
BEGIN DESCRIPTION:
MUSTANG CREEK 61.0
END DESCRIPTION:
XS GIS Cut Line= 3
      2829803.80      7010763.60      2829701.79      7010540.04
      2829452.62      7010089.37
#Sta/Elev= 30
  4644.2  456.28  4673.8  455.99  4730.9  453.83  4776.9  454.09  4861.7  452.60
  4897.5  453.78  4907.1  453.58  4919.2  451.65  4935.3  450.63  4941.4  449.35
  4951.4  450.79  4957.1  448.74  4961.2  449.25  4973.1  450.38  4987.1  448.93
  4991.9  445.56  4992.4  444.76  4997.4  444.76  4997.9  445.56  5000.6  447.97
  5010.0  449.37  5054.5  450.10  5067.1  449.62  5076.2  450.54  5081.9  450.22
  5098.0  452.00  5142.2  451.65  5286.0  456.76  5353.4  460.08  5404.9  460.68
#Mann=6,-1,0
  4644.2    0.05       0  4861.7    0.07       0  4961.2    0.12       0
  4991.9    0.07       0  4997.9    0.12       0  5286.0    0.05       0
Bank Sta=4919.2,5142.2
Exp/Cntr=0.3,0.1

Type RM Length L Ch R = 1,40768,564,564,564
BEGIN DESCRIPTION:
MUSTANG CREEK 60.0
END DESCRIPTION:
XS GIS Cut Line= 3
      2830079.50      7010615.89      2829966.55      7010329.54
      2829773.73      7009989.41
#Sta/Elev= 30
  4607.8  456.13  4629.3  455.74  4778.1  449.88  4851.2  448.70  4880.9  449.52
  4902.1  449.19  4927.7  448.71  4933.5  449.25  4949.4  449.13  4971.0  446.47
  4978.3  447.35  4986.9  445.98  4989.6  444.96  4990.1  444.16  4995.1  444.16
  4995.6  444.96  5001.3  447.80  5024.3  448.62  5027.6  449.88  5030.2  450.89
  5051.8  452.35  5089.3  453.20  5132.6  455.74  5162.2  454.25  5183.9  454.36
  5207.6  455.35  5229.3  458.11  5235.0  457.73  5242.7  458.25  5306.6  458.05
#Mann=5,-1,0
  4607.8    0.05       0  4902.1    0.12       0  4989.6    0.07       0
  4995.6    0.12       0  5183.9    0.05       0
Bank Sta=4778.1,5027.6
Exp/Cntr=0.3,0.1

Type RM Length L Ch R = 1,40204,332,332,332
BEGIN DESCRIPTION:
MUSTANG CREEK 59.0
END DESCRIPTION:
XS GIS Cut Line= 3
      2830359.34      7010459.75      2830255.18      7010201.50
      2829994.73      7009763.09
#Sta/Elev= 30
  4659.7  455.93  4729.5  454.61  4849.3  449.39  4899.8  448.51  4916.6  447.79
  4944.1  446.54  4965.5  447.23  4980.6  444.98  4984.0  440.93  4984.5  440.13
  4989.5  440.13  4990.0  440.93  4992.8  442.28  5008.4  442.61  5015.5  447.21
  5045.4  446.35  5070.6  446.84  5082.4  447.31  5119.5  446.55  5142.3  447.79
  5162.3  450.71  5165.5  449.95  5168.1  449.33  5183.7  449.65  5190.0  451.00
  5226.6  454.71  5279.2  455.05  5343.5  456.82  5396.1  456.15  5448.1  456.92
#Mann=6,-1,0
  4659.7    0.05       0  4899.8    0.12       0  4984.0    0.07       0
  4990.0    0.12       0  5070.6    0.16       0  5165.5    0.05       0
Bank Sta=4916.6,5142.3
Exp/Cntr=0.3,0.1

Type RM Length L Ch R = 1,39872,143,143,143
BEGIN DESCRIPTION:
MUSTANG CREEK 58.0
END DESCRIPTION:
XS GIS Cut Line= 4
      2830515.15      7010333.86      2830447.45      7010030.50
      2830388.86      7009862.53      2830359.34      7009360.31
#Sta/Elev= 30
  4618.7  454.93  4662.8  454.38  4802.0  451.00  4835.3  448.96  4863.4  448.35
  4883.9  447.00  4913.7  447.55  4918.8  446.59  4945.9  447.45  4966.4  446.71
  4975.8  446.22  4982.8  444.11  4995.9  441.54  4996.4  440.74  5001.4  440.74
  5001.9  441.54  5008.5  442.04  5013.8  444.96  5030.7  445.53  5039.6  444.94
  5044.9  445.83  5062.4  444.81  5103.3  446.22  5155.0  447.47  5205.1  452.18
  5235.2  451.25  5275.8  452.20  5405.5  451.96  5435.5  452.61  5610.5  453.24
#Mann=7,-1,0
  4618.7    0.05       0  4662.8    0.08       0  4835.3    0.12       0
  4966.4    0.08       0  4995.9    0.07       0  5001.9    0.08       0
  5275.8    0.05       0
Bank Sta=4975.8,5103.3
Exp/Cntr=0.3,0.1

Type RM Length L Ch R = 1,39729,402,402,402
BEGIN DESCRIPTION:
MUSTANG CREEK 57.0
END DESCRIPTION:
XS GIS Cut Line= 4
      2830606.75      7010297.90      2830526.44      7010024.42
      2830465.21      7009761.28      2830452.66      7009351.67
#Sta/Elev= 30
  4530.0  454.69  4534.9  454.72  4564.3  454.77  4574.7  453.91  4584.7  451.44
  4674.1  450.40  4695.2  449.44  4700.5  449.79  4772.7  448.50  4783.2  447.76
  4842.5  446.61  4889.5  446.51  4938.5  445.44  4958.2  444.90  4974.7  445.41
  4979.8  443.67  4996.2  440.55  4996.7  439.75  5001.7  439.75  5002.2  440.55
  5009.5  441.05  5017.3  444.63  5026.1  445.44  5040.1  445.94  5059.9  445.83
  5121.5  448.70  5241.7  448.99  5339.6  449.72  5371.6  450.56  5495.0  450.83
#Mann=9,-1,0
  4530.0    0.08       0  4534.9    0.05       0  4674.1    0.08       0
  4842.5    0.05       0  4996.2    0.03       0  5002.2    0.05       0
  5040.1    0.08       0  5241.7    0.05       0  5339.6    0.08       0
Bank Sta=4938.5,5026.1
Exp/Cntr=0.3,0.1

Type RM Length L Ch R = 1,39327,358,358,358
BEGIN DESCRIPTION:
MUSTANG CREEK 56.0
END DESCRIPTION:
XS GIS Cut Line= 3
      2830975.64      7009826.90      2830778.18      7009566.52
      2830485.19      7009347.32
#Sta/Elev= 30
  4618.0  449.22  4676.9  448.16  4726.8  447.98  4755.9  445.19  4805.9  444.99
  4833.7  443.78  4841.2  443.97  4847.5  443.37  4855.8  444.06  4874.4  442.95
  4891.2  442.93  4897.4  443.55  4934.1  443.21  4943.3  442.68  4976.2  443.07
  4984.5  442.29  4990.8  440.79  4995.7  438.79  4996.2  437.99  5001.2  437.99
  5001.7  438.79  5011.6  442.90  5012.8  442.95  5040.8  444.35  5055.4  445.74
  5076.2  446.04  5140.8  449.49  5184.6  450.84  5309.5  451.28  5310.7  451.28
#Mann=4,-1,0
  4618.0    0.05       0  4995.7    0.03       0  5001.7    0.05       0
  5309.5    0.08       0
Bank Sta=4874.4,5012.8
Exp/Cntr=0.3,0.1

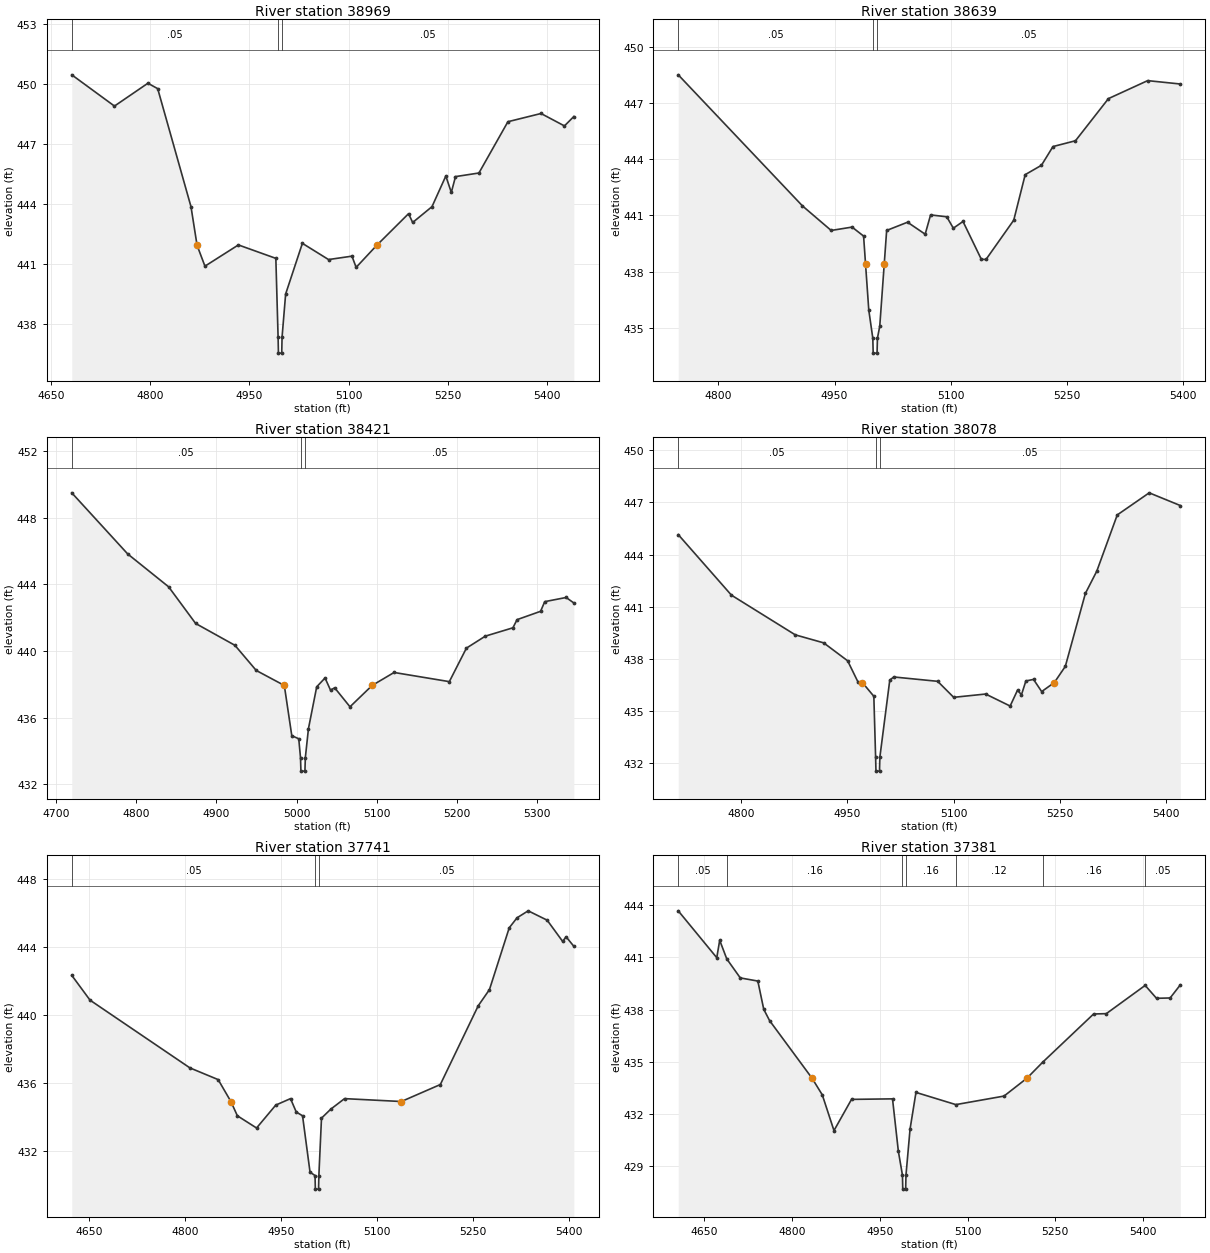
Type RM Length L Ch R = 1,38969,330,330,330
BEGIN DESCRIPTION:
MUSTANG CREEK 55.0
END DESCRIPTION:
XS GIS Cut Line= 3
      2831177.51      7009562.22      2830975.00      7009275.00
      2830648.98      7009031.25
#Sta/Elev= 30
  4681.7  450.44  4746.2  448.88  4796.7  450.02  4811.5  449.75  4861.8  443.86
  4871.0  441.93  4882.9  440.89  4933.4  441.95  4990.0  441.28  4993.4  437.35
  4993.9  436.55  4998.9  436.55  4999.4  437.35  5004.8  439.50  5030.1  442.03
  5069.6  441.22  5105.0  441.39  5111.3  440.83  5142.4  441.93  5190.5  443.51
  5196.7  443.07  5225.9  443.86  5246.8  445.39  5255.1  444.57  5261.4  445.36
  5296.8  445.54  5340.6  448.10  5390.6  448.51  5426.0  447.89  5440.2  448.36
#Mann=3,-1,0
  4681.7    0.05       0  4993.4    0.03       0  4999.4    0.05       0
Bank Sta=4871,5142.4
Exp/Cntr=0.3,0.1

Type RM Length L Ch R = 1,38639,218,218,218
BEGIN DESCRIPTION:
MUSTANG CREEK 54.0
END DESCRIPTION:
XS GIS Cut Line= 3
      2831393.06      7009361.13      2831309.27      7009193.55
      2831047.26      7008813.46
#Sta/Elev= 30
  4748.0  448.51  4908.6  441.51  4945.7  440.20  4972.7  440.38  4987.6  439.90
  4990.1  438.42  4994.3  435.95  4999.5  434.45  5000.0  433.65  5005.0  433.65
  5005.5  434.45  5008.5  435.09  5014.3  438.42  5017.4  440.20  5044.4  440.64
  5067.2  440.00  5074.2  441.03  5095.1  440.93  5103.6  440.32  5116.1  440.68
  5139.8  438.66  5145.8  438.65  5181.7  440.75  5196.5  443.18  5217.5  443.68
  5232.4  444.68  5261.5  444.99  5304.1  447.24  5354.8  448.20  5397.0  448.02
#Mann=3,-1,0
  4748.0    0.05       0  4999.5    0.03       0  5005.5    0.05       0
Bank Sta=4990.1,5014.3
Exp/Cntr=0.3,0.1

Type RM Length L Ch R = 1,38421,343,343,343
BEGIN DESCRIPTION:
MUSTANG CREEK 53.0
END DESCRIPTION:
XS GIS Cut Line= 3
      2831539.91      7009373.42      2831494.32      7009145.51
      2831390.16      7008765.76
#Sta/Elev= 30
  4719.7  449.49  4789.5  445.82  4840.5  443.85  4874.2  441.65  4923.2  440.34
  4949.8  438.83  4984.8  437.93  4994.1  434.92  5002.8  434.73  5005.0  433.59
  5005.5  432.79  5010.5  432.79  5011.0  433.59  5014.9  435.34  5025.2  437.85
  5035.6  438.38  5042.4  437.65  5047.6  437.79  5066.7  436.65  5094.3  437.93
  5121.7  438.71  5190.6  438.16  5211.9  440.17  5235.5  440.89  5269.9  441.39
  5275.1  441.88  5304.4  442.38  5309.6  442.96  5336.3  443.21  5345.9  442.88
#Mann=3,-1,0
  4719.7    0.05       0  5005.0    0.03       0  5011.0    0.05       0
Bank Sta=4984.8,5094.3
Exp/Cntr=0.3,0.1

Type RM Length L Ch R = 1,38078,337,337,337
BEGIN DESCRIPTION:
MUSTANG CREEK 52.0
END DESCRIPTION:
XS GIS Cut Line= 3
      2831850.23      7009329.96      2831837.21      7009091.26
      2831631.52      7008669.05
#Sta/Elev= 30
  4711.3  445.15  4786.4  441.67  4876.5  439.39  4916.6  438.93  4950.4  437.90
  4964.8  436.70  4971.2  436.65  4987.4  435.86  4989.9  432.36  4990.4  431.56
  4995.4  431.56  4995.9  432.36  5009.9  436.79  5015.5  436.97  5077.5  436.72
  5100.1  435.80  5145.2  435.99  5179.8  435.30  5190.2  436.21  5195.8  435.95
  5202.0  436.74  5212.8  436.83  5224.3  436.13  5242.2  436.65  5257.7  437.58
  5286.0  441.77  5302.1  443.05  5331.0  446.28  5376.1  447.55  5420.0  446.82
#Mann=3,-1,0
  4711.3    0.05       0  4989.9    0.03       0  4995.9    0.05       0
Bank Sta=4971.2,5242.2
Exp/Cntr=0.3,0.1

Type RM Length L Ch R = 1,37741,360,360,360
BEGIN DESCRIPTION:
MUSTANG CREEK 51.0
END DESCRIPTION:
XS GIS Cut Line= 3
      2832156.22      7009323.46      2832145.37      7009000.11
      2831973.94      7008572.63
#Sta/Elev= 30
  4623.3  442.34  4651.8  440.88  4807.8  436.89  4851.9  436.20  4871.8  434.91
  4881.9  434.07  4911.9  433.35  4941.9  434.70  4964.9  435.08  4973.9  434.29
  4983.7  434.07  4995.4  430.75  5003.2  430.55  5003.7  429.75  5008.7  429.75
  5009.2  430.55  5013.3  433.93  5027.8  434.46  5049.3  435.08  5138.0  434.91
  5198.9  435.91  5258.1  440.55  5275.6  441.50  5306.5  445.14  5318.7  445.73
  5336.1  446.14  5365.7  445.59  5389.9  444.34  5395.3  444.61  5407.4  444.05
#Mann=3,-1,0
  4623.3    0.05       0  5003.2    0.03       0  5009.2    0.05       0
Bank Sta=4871.8,5138
Exp/Cntr=0.3,0.1

Type RM Length L Ch R = 1,37381,368,368,368
BEGIN DESCRIPTION:
MUSTANG CREEK 50.0
END DESCRIPTION:
XS GIS Cut Line= 3
      2832416.63      7009240.99      2832437.23      7008809.17
      2832265.07      7008419.30
#Sta/Elev= 30
  4605.2  443.67  4671.1  440.98  4676.1  441.98  4688.2  440.91  4711.3  439.82
  4741.3  439.64  4751.4  438.02  4761.4  437.37  4833.9  434.07  4851.5  433.11
  4871.5  431.06  4901.5  432.85  4971.6  432.88  4981.6  429.87  4988.6  428.50
  4989.1  427.70  4994.1  427.70  4994.6  428.50  5001.6  431.15  5011.7  433.25
  5079.9  432.55  5162.3  433.04  5201.6  434.07  5228.6  434.99  5315.4  437.75
  5337.2  437.77  5403.6  439.39  5423.0  438.65  5446.3  438.67  5463.7  439.42
#Mann=7,-1,0
  4605.2    0.05       0  4688.2    0.16       0  4988.6    0.07       0
  4994.6    0.16       0  5079.9    0.12       0  5228.6    0.16       0
  5403.6    0.05       0
Bank Sta=4833.9,5201.6
Exp/Cntr=0.3,0.1

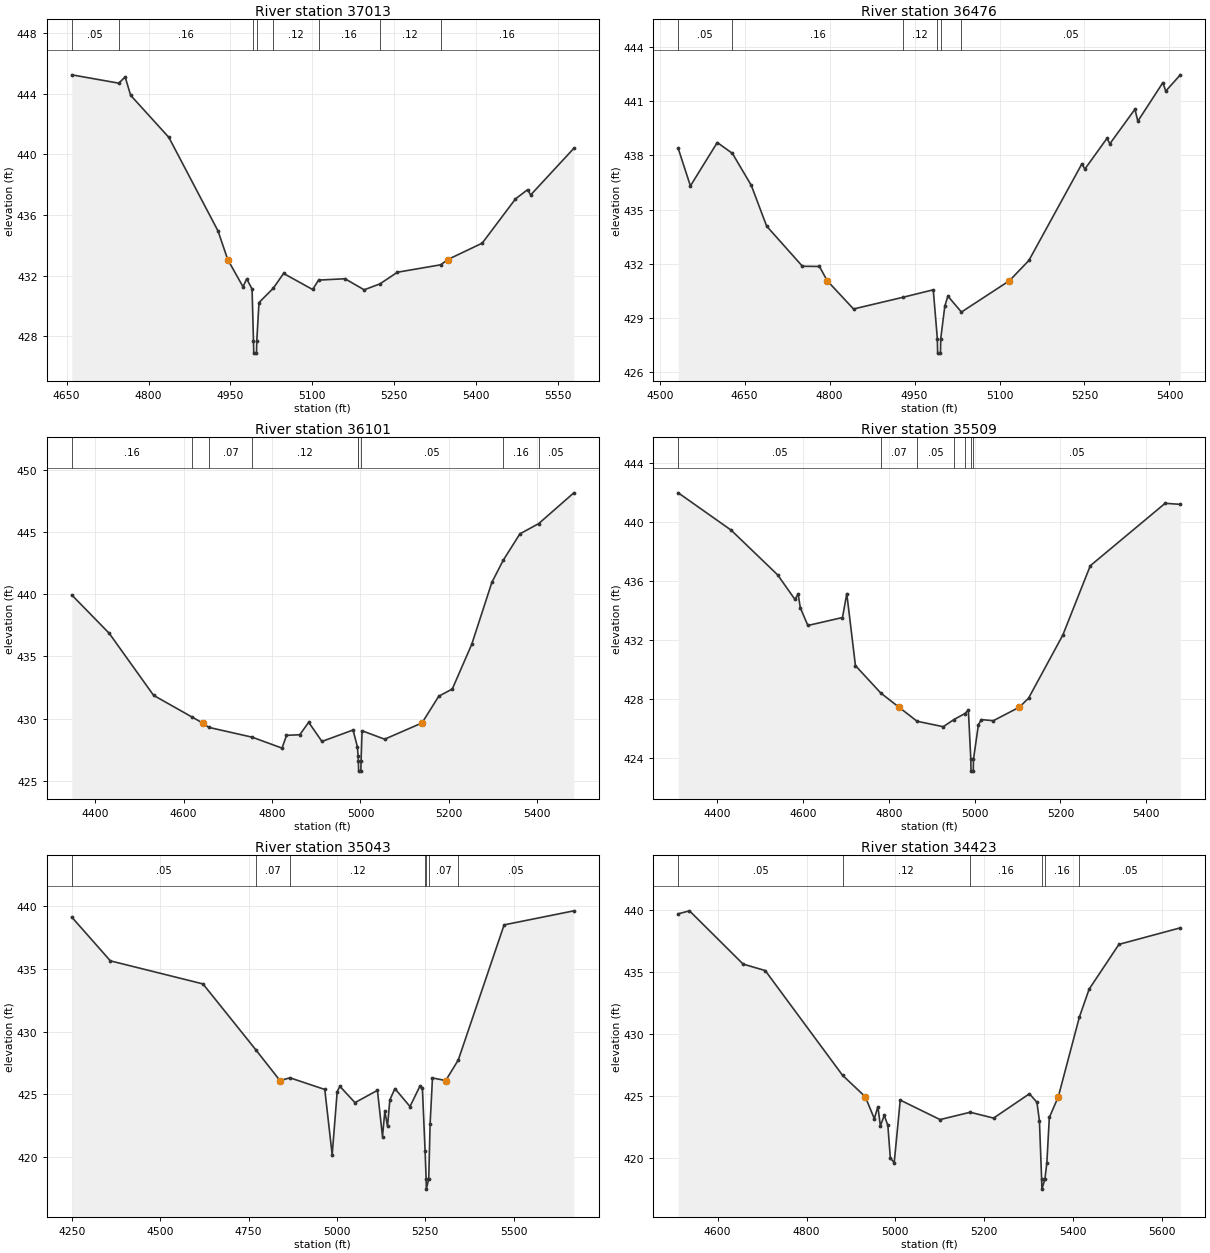
Type RM Length L Ch R = 1,37013,537,537,537
BEGIN DESCRIPTION:
MUSTANG CREEK 49.0
END DESCRIPTION:
XS GIS Cut Line= 3
      2832781.22      7009212.83      2832776.88      7008915.48
      2832492.60      7008362.11
#Sta/Elev= 30
  4659.4  445.25  4745.4  444.70  4757.2  445.11  4767.2  443.90  4837.2  441.12
  4927.3  434.94  4945.0  433.06  4973.0  431.26  4979.8  431.78  4989.6  431.11
  4992.2  427.68  4992.7  426.88  4997.7  426.88  4998.2  427.68  5002.3  430.22
  5028.4  431.16  5047.3  432.14  5100.5  431.08  5111.4  431.70  5159.7  431.79
  5194.9  431.06  5223.7  431.45  5255.8  432.22  5335.0  432.71  5348.2  433.06
  5411.1  434.14  5472.0  437.06  5494.2  437.67  5499.8  437.32  5578.9  440.40
#Mann=8,-1,0
  4659.4    0.05       0  4745.4    0.16       0  4992.2    0.07       0
  4998.2    0.16       0  5028.4    0.12       0  5111.4    0.16       0
  5223.7    0.12       0  5335.0    0.16       0
Bank Sta=4945,5348.2
Exp/Cntr=0.3,0.1

Type RM Length L Ch R = 1,36476,375,375,375
BEGIN DESCRIPTION:
MUSTANG CREEK 48.0
END DESCRIPTION:
XS GIS Cut Line= 3
      2833028.61      7009173.70      2833059.63      7008744.18
      2832963.83      7008298.50
#Sta/Elev= 30
  4532.7  438.38  4554.2  436.31  4601.6  438.71  4628.3  438.11  4661.7  436.34
  4688.8  434.09  4752.0  431.87  4782.0  431.86  4795.8  431.07  4842.2  429.51
  4928.7  430.15  4983.0  430.57  4990.2  427.87  4990.7  427.07  4995.7  427.07
  4996.2  427.87  5003.4  429.67  5008.8  430.22  5032.7  429.34  5117.4  431.07
  5151.8  432.19  5245.4  437.53  5250.6  437.24  5289.7  438.94  5294.8  438.64
  5339.1  440.55  5344.2  439.89  5388.4  442.02  5393.5  441.55  5419.2  442.45
#Mann=6,-1,0
  4532.7    0.05       0  4628.3    0.16       0  4928.7    0.12       0
  4990.2    0.07       0  4996.2    0.12       0  5032.7    0.05       0
Bank Sta=4795.8,5117.4
Exp/Cntr=0.3,0.1

Type RM Length L Ch R = 1,36101,592,592,592
BEGIN DESCRIPTION:
MUSTANG CREEK 47.0
END DESCRIPTION:
XS GIS Cut Line= 3
      2833469.15      7009299.63      2833425.00      7008675.00
      2833323.75      7008175.45
#Sta/Elev= 30
  4346.8  439.95  4431.6  436.86  4531.9  431.87  4619.1  430.12  4642.7  429.65
  4657.0  429.29  4755.2  428.50  4822.6  427.62  4832.6  428.65  4862.7  428.70
  4882.8  429.70  4912.8  428.16  4983.2  429.08  4993.2  427.70  4994.5  427.00
  4995.3  426.57  4995.8  425.77  5000.8  425.77  5001.3  426.57  5003.6  429.02
  5054.6  428.34  5139.2  429.65  5177.1  431.80  5207.7  432.38  5251.7  435.98
  5297.3  440.97  5322.7  442.73  5360.7  444.87  5403.1  445.69  5482.7  448.17
#Mann=9,-1,0
  4346.8    0.16       0  4619.1    0.05       0  4657.0    0.07       0
  4755.2    0.12       0  4994.5    0.05       0  4995.3    0.03       0
  5001.3    0.05       0  5322.7    0.16       0  5403.1    0.05       0
Bank Sta=4642.7,5139.2
Exp/Cntr=0.3,0.1

Type RM Length L Ch R = 1,35509,466,466,466
BEGIN DESCRIPTION:
MUSTANG CREEK 46.0
END DESCRIPTION:
XS GIS Cut Line= 3
      2833925.00      7009075.00      2833998.74      7008485.33
      2833700.13      7007992.27
#Sta/Elev= 30
  4308.8  441.96  4432.2  439.43  4540.6  436.40  4580.9  434.74  4588.4  435.11
  4593.4  434.17  4611.1  432.97  4691.8  433.51  4701.8  435.13  4722.0  430.25
  4781.2  428.39  4823.6  427.43  4865.7  426.48  4926.8  426.11  4951.3  426.59
  4977.0  427.00  4985.3  427.24  4991.0  423.90  4991.5  423.10  4996.7  423.10
  4997.2  423.90  5008.7  426.24  5015.5  426.59  5043.7  426.52  5103.9  427.43
  5125.6  428.04  5205.5  432.32  5269.6  437.02  5444.1  441.25  5479.5  441.18
#Mann=7,-1,0
  4308.8    0.05       0  4781.2    0.07       0  4865.7    0.05       0
  4951.3    0.12       0  4977.0    0.05       0  4991.0    0.03       0
  4997.2    0.05       0
Bank Sta=4823.6,5103.9
Exp/Cntr=0.3,0.1

Type RM Length L Ch R = 1,35043,620,620,620
BEGIN DESCRIPTION:
MUSTANG CREEK 45.0
END DESCRIPTION:
XS GIS Cut Line= 4
      2834092.49      7008919.38      2834279.99      7008308.24
      2834591.02      7007952.79      2834696.67      7007662.38
#Sta/Elev= 30
  4249.5  439.15  4358.7  435.66  4620.7  433.82  4769.8  428.58  4838.6  426.11
  4866.9  426.33  4965.4  425.40  4986.3  420.19  5000.5  425.23  5008.1  425.65
  5050.8  424.35  5114.4  425.33  5128.7  421.64  5135.3  423.67  5142.9  422.47
  5149.5  424.57  5163.8  425.47  5206.5  424.04  5235.0  425.69  5241.6  425.49
  5249.2  420.49  5252.2  418.25  5252.7  417.45  5259.5  418.25  5263.4  422.65
  5270.1  426.32  5307.5  426.11  5343.1  427.75  5472.8  438.53  5670.1  439.65
#Mann=7,-1,0
  4249.5    0.05       0  4769.8    0.07       0  4866.9    0.12       0
  5249.2    0.07       0  5252.2    0.07       0  5259.5    0.07       0
  5343.1    0.05       0
Bank Sta=4838.6,5307.5
Exp/Cntr=0.3,0.1

Type RM Length L Ch R = 1,34423,585,585,585
BEGIN DESCRIPTION:
MUSTANG CREEK 44.0
END DESCRIPTION:
XS GIS Cut Line= 3
      2834439.72      7008985.32      2834627.22      7008631.16
      2834953.18      7007979.23
#Sta/Elev= 30
  4511.4  439.69  4536.7  439.93  4657.4  435.64  4707.1  435.12  4881.0  426.69
  4932.2  424.96  4952.6  423.19  4960.6  424.16  4966.2  422.61  4974.9  423.46
  4983.0  422.66  4988.6  420.02  4997.3  419.65  5010.9  424.69  5100.4  423.12
  5168.2  423.71  5220.9  423.24  5301.6  425.20  5318.4  424.51  5324.0  423.03
  5329.0  418.32  5329.6  417.52  5336.3  418.32  5340.7  419.62  5346.3  423.29
  5366.5  424.96  5413.9  431.37  5435.8  433.62  5502.9  437.23  5641.0  438.56
#Mann=6,-1,0
  4511.4    0.05       0  4881.0    0.12       0  5168.2    0.16       0
  5329.0    0.07       0  5336.3    0.16       0  5413.9    0.05       0
Bank Sta=4932.2,5366.5
Exp/Cntr=0.3,0.1