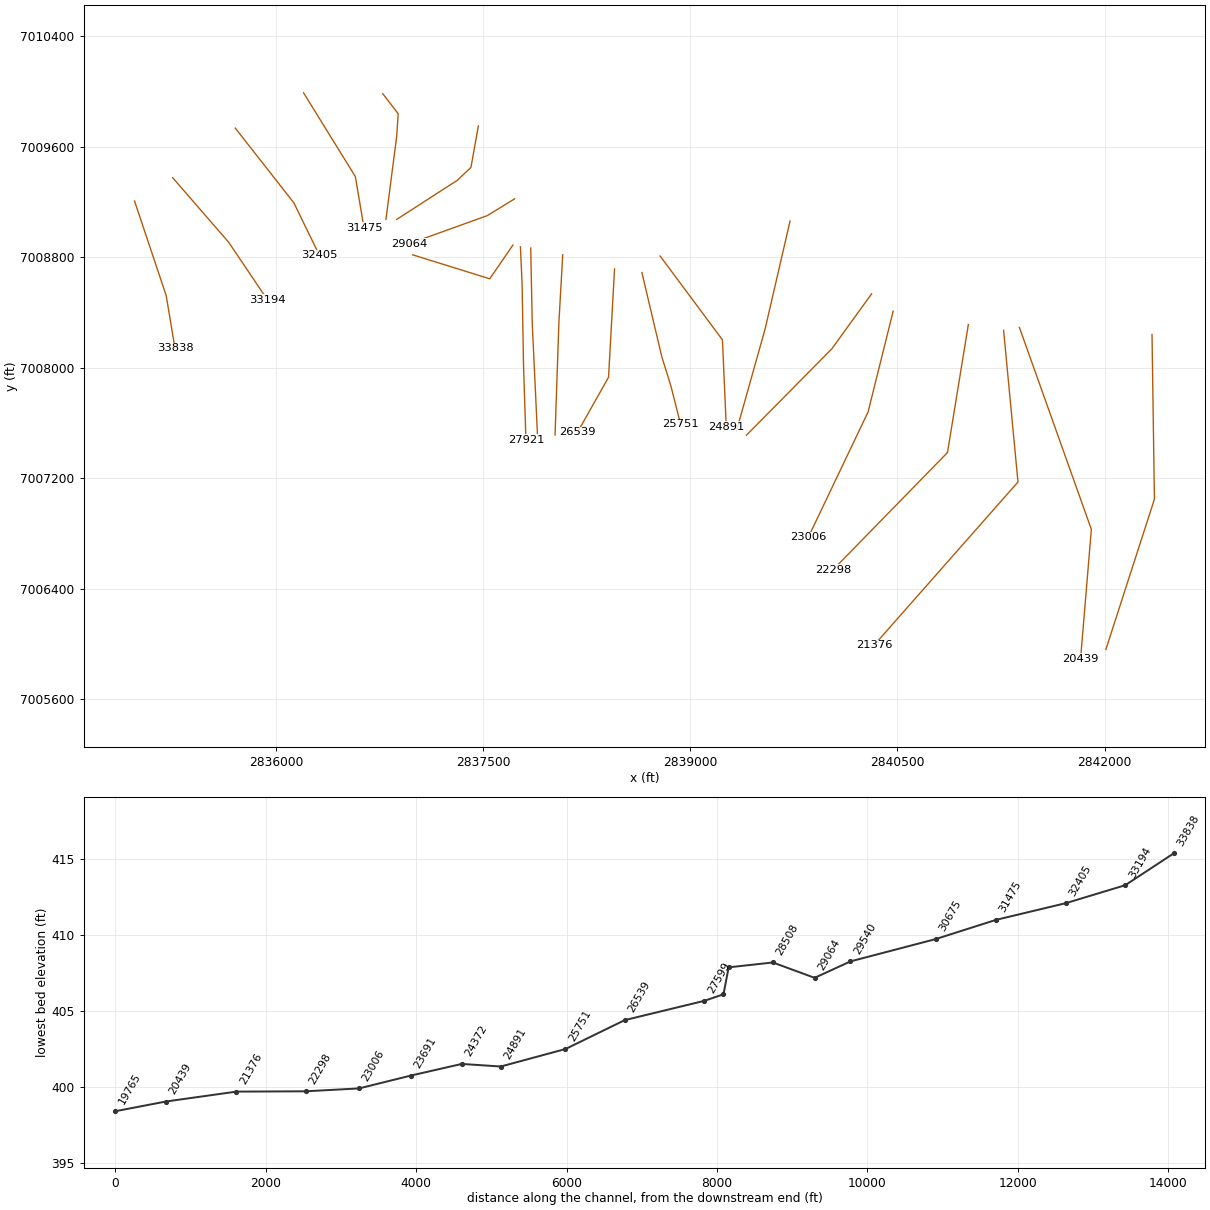
HEC-RAS study MUSTANG CREEK.prj: MUSTANG CREEK Base Level Engineering

--- MUSTANG CREEK.g01 (geometry) --- (continued)

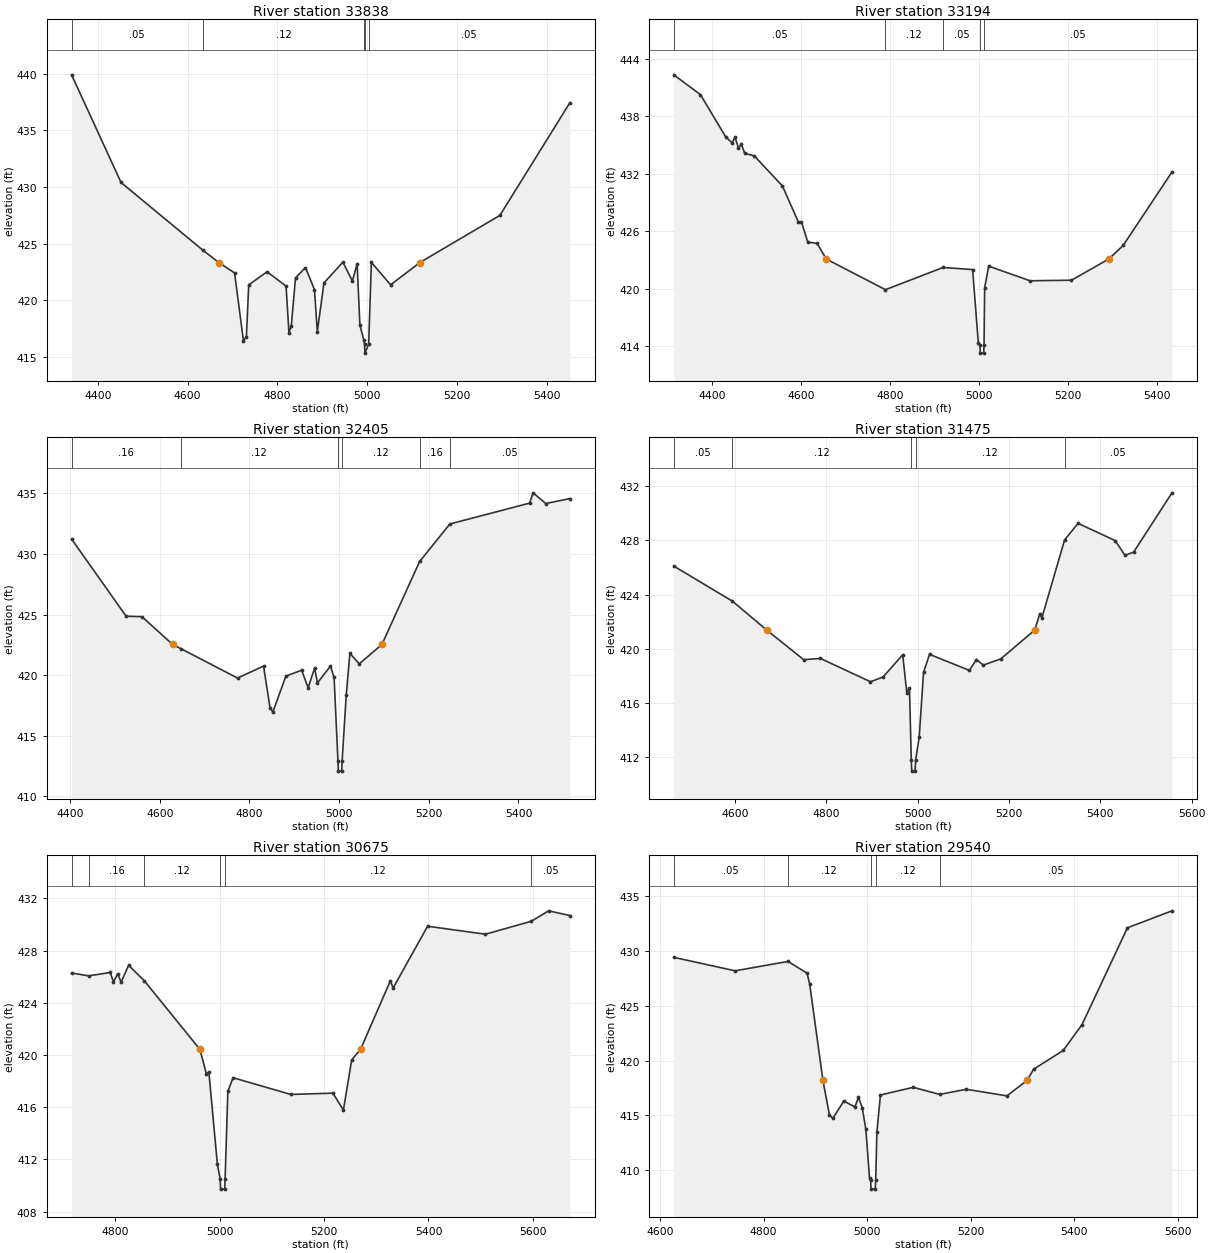
Type RM Length L Ch R = 1,33838,644,644,644
BEGIN DESCRIPTION:
MUSTANG CREEK 43.0
END DESCRIPTION:
XS GIS Cut Line= 3
      2834976.16      7009207.59      2835205.34      7008522.65
      2835268.95      7008141.59
#Sta/Elev= 30
  4341.8  439.89  4451.9  430.40  4634.0  424.43  4669.7  423.34  4704.5  422.43
  4724.2  416.46  4730.8  416.82  4736.0  421.38  4776.9  422.53  4819.1  421.27
  4825.5  417.16  4830.7  417.76  4840.1  422.00  4862.3  422.90  4882.3  420.96
  4888.6  417.24  4903.4  421.55  4945.6  423.38  4966.7  421.72  4977.2  423.23
  4983.4  417.81  4992.3  416.49  4993.7  416.16  4994.6  415.36  5002.9  416.16
  5008.9  423.36  5051.8  421.38  5116.6  423.34  5294.9  427.50  5450.4  437.42
#Mann=5,-1,0
  4341.8    0.05       0  4634.0    0.12       0  4992.3    0.05       0
  4993.7    0.03       0  5002.9    0.05       0
Bank Sta=4669.7,5116.6
Exp/Cntr=0.3,0.1

Type RM Length L Ch R = 1,33194,789,789,789
BEGIN DESCRIPTION:
MUSTANG CREEK 42.0
END DESCRIPTION:
XS GIS Cut Line= 3
      2835252.20      7009376.84      2835658.47      7008908.07
      2835937.10      7008494.02
#Sta/Elev= 30
  4314.6  442.35  4374.5  440.28  4431.5  435.85  4445.7  435.25  4452.3  435.82
  4460.0  434.71  4466.6  435.08  4474.2  434.13  4495.1  433.90  4558.7  430.74
  4594.8  426.94  4601.4  426.98  4615.7  424.87  4636.6  424.73  4657.3  423.10
  4790.2  419.90  4919.7  422.22  4986.1  422.00  4998.9  414.33  5002.5  414.07
  5003.4  413.27  5010.9  413.27  5011.7  414.07  5013.1  420.10  5022.1  422.36
  5115.1  420.83  5208.1  420.89  5291.9  423.10  5324.3  424.52  5434.0  432.20
#Mann=5,-1,0
  4314.6    0.05       0  4790.2    0.12       0  4919.7    0.05       0
  5002.5    0.03       0  5011.7    0.05       0
Bank Sta=4657.3,5291.9
Exp/Cntr=0.3,0.1

Type RM Length L Ch R = 1,32405,930,930,930
BEGIN DESCRIPTION:
MUSTANG CREEK 41.0
END DESCRIPTION:
XS GIS Cut Line= 3
      2835705.35      7009736.18      2836129.82      7009194.53
      2836314.70      7008814.35
#Sta/Elev= 30
  4403.5  431.22  4525.1  424.86  4560.4  424.82  4628.9  422.53  4646.9  422.19
  4773.7  419.76  4831.6  420.75  4846.0  417.32  4852.4  416.97  4881.3  419.92
  4916.6  420.41  4931.0  418.96  4945.5  420.59  4951.8  419.36  4980.8  420.75
  4988.9  419.81  4997.5  412.89  4998.4  412.09  5005.9  412.09  5006.7  412.89
  5016.0  418.40  5024.1  421.80  5044.9  420.93  5095.5  422.53  5179.6  429.37
  5246.9  432.46  5424.7  434.18  5432.7  435.03  5460.8  434.15  5514.4  434.55
#Mann=6,-1,0
  4403.5    0.16       0  4646.9    0.12       0  4997.5    0.07       0
  5006.7    0.12       0  5179.6    0.16       0  5246.9    0.05       0
Bank Sta=4628.9,5095.5
Exp/Cntr=0.3,0.1

Type RM Length L Ch R = 1,31475,800,800,800
BEGIN DESCRIPTION:
MUSTANG CREEK 40.0
END DESCRIPTION:
XS GIS Cut Line= 3
      2836200.13      7009991.41      2836575.13      7009384.63
      2836637.63      7009012.24
#Sta/Elev= 30
  4466.0  426.11  4594.4  423.52  4669.6  421.39  4750.4  419.21  4787.1  419.30
  4896.7  417.58  4924.2  417.93  4967.3  419.57  4976.2  416.78  4982.1  417.13
  4986.1  411.79  4987.0  410.99  4994.5  410.99  4995.4  411.79  5003.4  413.49
  5012.9  418.27  5026.0  419.60  5113.3  418.42  5128.7  419.22  5143.6  418.81
  5181.7  419.26  5256.4  421.39  5267.1  422.55  5272.2  422.31  5321.8  428.04
  5351.3  429.26  5432.4  427.99  5454.1  426.90  5473.0  427.14  5556.9  431.51
#Mann=5,-1,0
  4466.0    0.05       0  4594.4    0.12       0  4986.1    0.07       0
  4995.4    0.12       0  5321.8    0.05       0
Bank Sta=4669.6,5256.4
Exp/Cntr=0.3,0.1

Type RM Length L Ch R = 1,30675,1135,1135,1135
BEGIN DESCRIPTION:
MUSTANG CREEK 39.0
END DESCRIPTION:
XS GIS Cut Line= 4
      2836773.03      7009986.22      2836885.03      7009840.36
      2836874.61      7009678.90      2836796.49      7009074.73
#Sta/Elev= 30
  4716.0  426.28  4749.0  426.06  4790.0  426.32  4796.3  425.59  4804.5  426.23
  4810.8  425.57  4825.3  426.87  4855.5  425.68  4962.0  420.43  4974.2  418.58
  4979.2  418.68  4995.5  411.62  5000.7  410.53  5001.6  409.73  5009.4  409.73
  5010.3  410.53  5015.5  417.21  5025.5  418.26  5136.2  416.98  5216.9  417.08
  5237.0  415.78  5252.9  419.63  5269.8  420.43  5327.2  425.70  5332.2  425.12
  5398.4  429.86  5509.3  429.25  5597.2  430.24  5630.3  431.04  5670.9  430.68
#Mann=6,-1,0
  4716.0    0.05       0  4749.0    0.16       0  4855.5    0.12       0
  5000.7    0.07       0  5010.3    0.12       0  5597.2    0.05       0
Bank Sta=4962,5269.8
Exp/Cntr=0.3,0.1

Type RM Length L Ch R = 1,29540,476,476,476
BEGIN DESCRIPTION:
MUSTANG CREEK 38.0
END DESCRIPTION:
XS GIS Cut Line= 4
      2837465.76      7009751.83      2837411.86      7009451.36
      2837313.63      7009358.27      2836875.04      7009075.03
#Sta/Elev= 30
  4626.6  429.43  4745.3  428.20  4847.4  429.06  4884.1  427.98  4889.2  427.00
  4914.8  418.19  4927.5  415.00  4934.1  414.73  4955.2  416.31  4976.6  415.76
  4983.5  416.65  4990.8  415.70  4997.7  413.74  5004.9  409.26  5006.9  409.06
  5007.9  408.26  5015.8  408.26  5016.8  409.06  5019.1  413.50  5026.0  416.86
  5089.4  417.56  5140.3  416.91  5191.8  417.38  5270.3  416.78  5309.4  418.19
  5321.8  419.21  5379.2  420.93  5415.5  423.29  5503.2  432.13  5589.3  433.68
#Mann=5,-1,0
  4626.6    0.05       0  4847.4    0.12       0  5006.9    0.07       0
  5016.8    0.12       0  5140.3    0.05       0
Bank Sta=4914.8,5309.4
Exp/Cntr=0.3,0.1

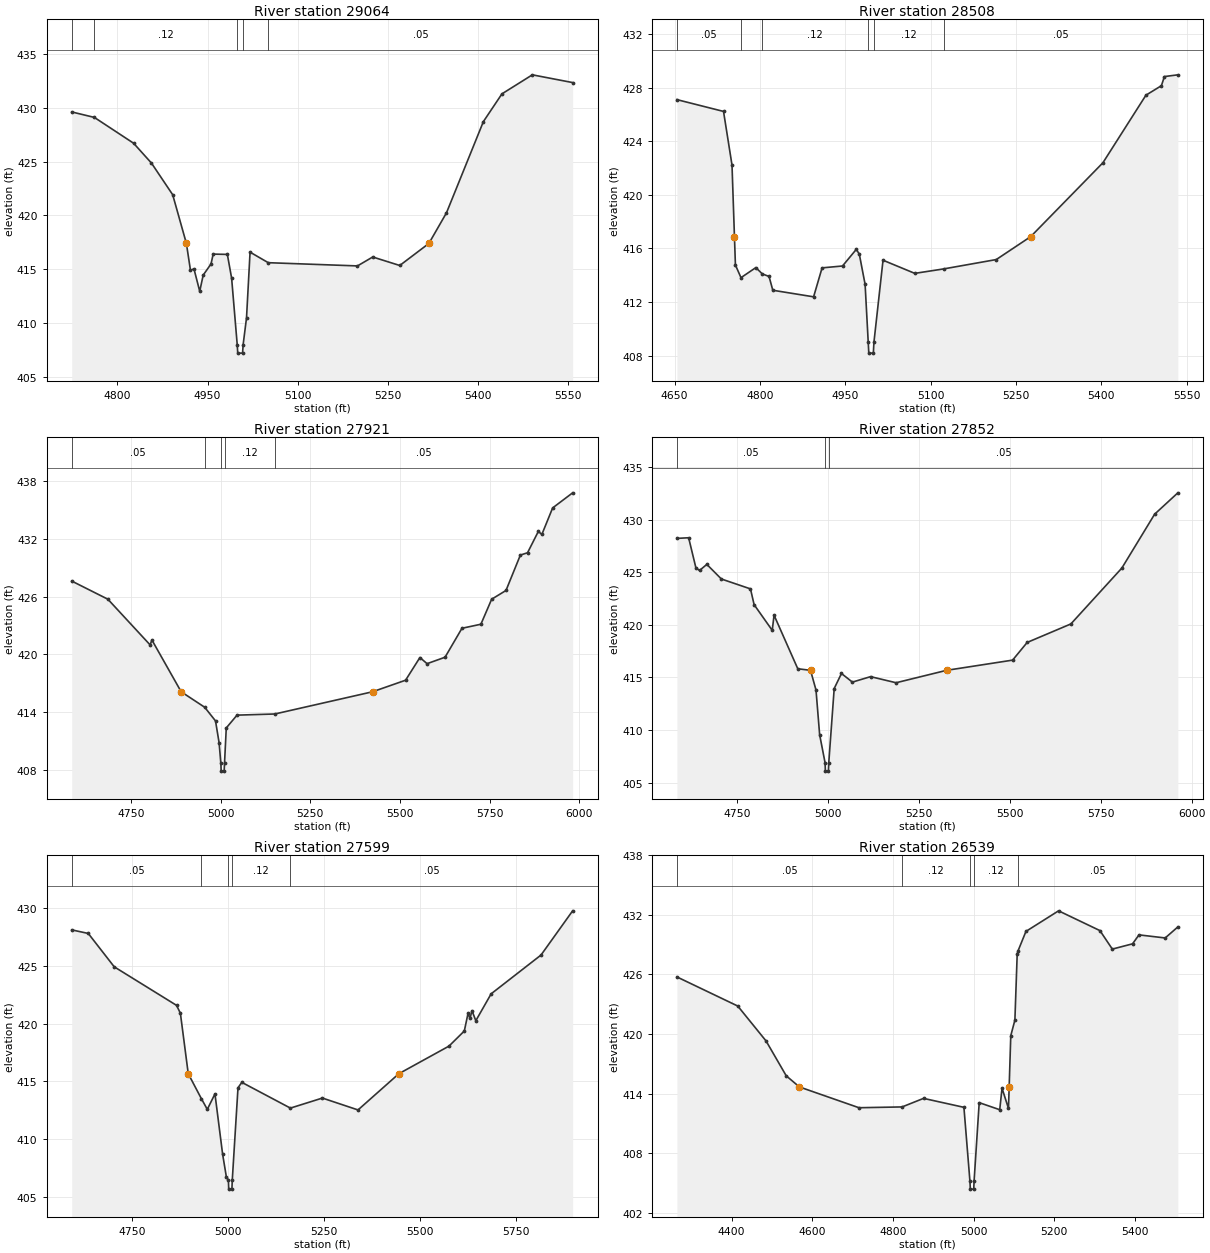
Type RM Length L Ch R = 1,29064,556,556,556
BEGIN DESCRIPTION:
MUSTANG CREEK 37.0
END DESCRIPTION:
XS GIS Cut Line= 3
      2837728.13      7009223.72      2837530.65      7009102.19
      2836964.25      7008898.20
#Sta/Elev= 30
  4723.8  429.61  4761.5  429.10  4826.8  426.70  4856.6  424.85  4891.9  421.91
  4914.7  417.38  4921.5  414.88  4927.3  415.02  4936.9  412.93  4942.7  414.44
  4955.7  415.47  4959.3  416.39  4982.9  416.36  4990.0  414.15  4999.3  407.98
  5000.2  407.18  5008.2  407.18  5009.2  407.98  5014.8  410.46  5020.7  416.57
  5051.0  415.59  5199.5  415.29  5224.9  416.12  5269.9  415.33  5318.4  417.38
  5347.7  420.23  5409.1  428.71  5440.0  431.29  5490.6  433.06  5557.7  432.34
#Mann=5,-1,0
  4723.8    0.05       0  4761.5    0.12       0  4999.3    0.07       0
  5009.2    0.12       0  5051.0    0.05       0
Bank Sta=4914.7,5318.4
Exp/Cntr=0.3,0.1

Type RM Length L Ch R = 1,28508,587,587,587
BEGIN DESCRIPTION:
MUSTANG CREEK 36.0
END DESCRIPTION:
XS GIS Cut Line= 3
      2837715.68      7008888.43      2837548.01      7008644.29
      2836990.28      7008817.90
#Sta/Elev= 30
  4654.0  427.10  4735.9  426.22  4750.8  422.22  4755.1  416.88  4756.8  414.76
  4766.6  413.82  4792.7  414.57  4804.0  414.10  4815.9  413.91  4822.5  412.88
  4894.2  412.39  4909.1  414.55  4945.0  414.69  4969.2  415.93  4974.5  415.58
  4984.7  413.32  4990.2  408.99  4991.2  408.19  4999.2  408.19  5000.2  408.99
  5016.2  415.12  5072.0  414.14  5122.5  414.47  5215.2  415.17  5275.7  416.88
  5402.6  422.39  5478.2  427.43  5505.4  428.14  5510.7  428.82  5534.3  428.95
#Mann=6,-1,0
  4654.0    0.05       0  4766.6    0.07       0  4804.0    0.12       0
  4990.2    0.07       0  5000.2    0.12       0  5122.5    0.05       0
Bank Sta=4755.1,5275.7
Exp/Cntr=0.3,0.1

Type RM Length L Ch R = 1,27921,69,69,69
BEGIN DESCRIPTION:
Mapping XS 0b9faeb6
END DESCRIPTION:
XS GIS Cut Line= 4
      2837770.08      7008875.80      2837782.23      7008605.00
      2837792.65      7008011.25      2837809.98      7007479.25
#Sta/Elev= 30
  4584.7  427.63  4685.6  425.74  4803.4  420.99  4808.4  421.50  4890.0  416.12
  4955.6  414.51  4985.8  413.09  4995.8  410.82  5000.7  408.67  5001.6  407.87
  5009.9  407.87  5010.9  408.67  5015.8  412.36  5045.8  413.69  5151.3  413.81
  5423.9  416.12  5515.9  417.32  5555.9  419.68  5575.9  419.04  5626.0  419.71
  5673.2  422.72  5726.0  423.14  5756.0  425.74  5796.0  426.65  5836.1  430.33
  5856.1  430.57  5886.1  432.78  5896.1  432.48  5926.1  435.23  5981.9  436.80
#Mann=5,-1,0
  4584.7    0.05       0  4955.6    0.12       0  5000.7    0.07       0
  5010.9    0.12       0  5151.3    0.05       0
Bank Sta=4890,5423.9
Exp/Cntr=0.3,0.1

Type RM Length L Ch R = 1,27852,253,253,253
BEGIN DESCRIPTION:
MUSTANG CREEK 35.0
END DESCRIPTION:
XS GIS Cut Line= 3
      2837844.66      7008867.18      2837855.52      7008324.63
      2837894.58      7007491.30
#Sta/Elev= 30
  4585.2  428.22  4617.4  428.28  4637.4  425.42  4647.4  425.17  4667.4  425.75
  4707.4  424.36  4787.4  423.42  4797.4  421.92  4847.2  419.48  4852.2  420.92
  4917.4  415.83  4952.4  415.68  4967.5  413.81  4977.5  409.56  4992.4  406.90
  4993.3  406.10  5001.6  406.10  5002.6  406.90  5017.5  413.95  5037.5  415.38
  5067.5  414.56  5117.5  415.08  5187.6  414.50  5326.4  415.68  5507.9  416.65
  5547.9  418.33  5668.1  420.09  5808.2  425.40  5898.3  430.52  5962.1  432.55
#Mann=3,-1,0
  4585.2    0.05       0  4992.4    0.04       0  5002.6    0.05       0
Bank Sta=4952.4,5326.4
Exp/Cntr=0.3,0.1

Type RM Length L Ch R = 1,27599,1060,1060,1060
BEGIN DESCRIPTION:
MUSTANG CREEK 34.0
END DESCRIPTION:
XS GIS Cut Line= 3
      2838076.43      7008818.09      2838048.66      7008328.53
      2838020.88      7007512.55
#Sta/Elev= 30
  4592.1  428.13  4635.3  427.82  4703.0  424.93  4865.6  421.59  4875.6  420.91
  4896.1  415.67  4930.3  413.51  4945.8  412.58  4965.8  413.92  4985.8  408.69
  4995.8  406.68  5000.8  406.47  5001.7  405.67  5010.0  405.67  5011.0  406.47
  5025.9  414.45  5035.9  414.92  5162.6  412.69  5246.1  413.56  5339.0  412.53
  5445.6  415.67  5576.3  418.06  5616.3  419.37  5626.1  420.91  5631.1  420.46
  5636.3  421.13  5646.3  420.26  5686.3  422.59  5816.4  425.95  5898.9  429.78
#Mann=5,-1,0
  4592.1    0.05       0  4930.3    0.12       0  5000.8    0.07       0
  5011.0    0.12       0  5162.6    0.05       0
Bank Sta=4896.1,5445.6
Exp/Cntr=0.3,0.1

Type RM Length L Ch R = 1,26539,788,788,788
BEGIN DESCRIPTION:
MUSTANG CREEK 33.0
END DESCRIPTION:
XS GIS Cut Line= 3
      2838451.55      7008715.66      2838408.15      7007930.97
      2838184.19      7007533.40
#Sta/Elev= 30
  4264.3  425.75  4415.2  422.82  4485.3  419.31  4535.4  415.80  4568.1  414.68
  4715.7  412.59  4822.7  412.67  4875.9  413.53  4976.0  412.63  4990.9  405.20
  4991.9  404.40  5000.3  404.40  5001.2  405.20  5013.9  413.10  5064.8  412.39
  5070.5  414.55  5086.5  412.52  5088.2  414.68  5092.2  419.84  5102.4  421.40
  5108.1  428.03  5110.2  428.37  5129.8  430.33  5210.7  432.40  5313.3  430.41
  5344.0  428.55  5394.2  429.08  5410.1  429.98  5475.1  429.67  5506.5  430.78
#Mann=5,-1,0
  4264.3    0.05       0  4822.7    0.12       0  4990.9    0.07       0
  5001.2    0.12       0  5110.2    0.05       0
Bank Sta=4568.1,5088.2
Exp/Cntr=0.3,0.1

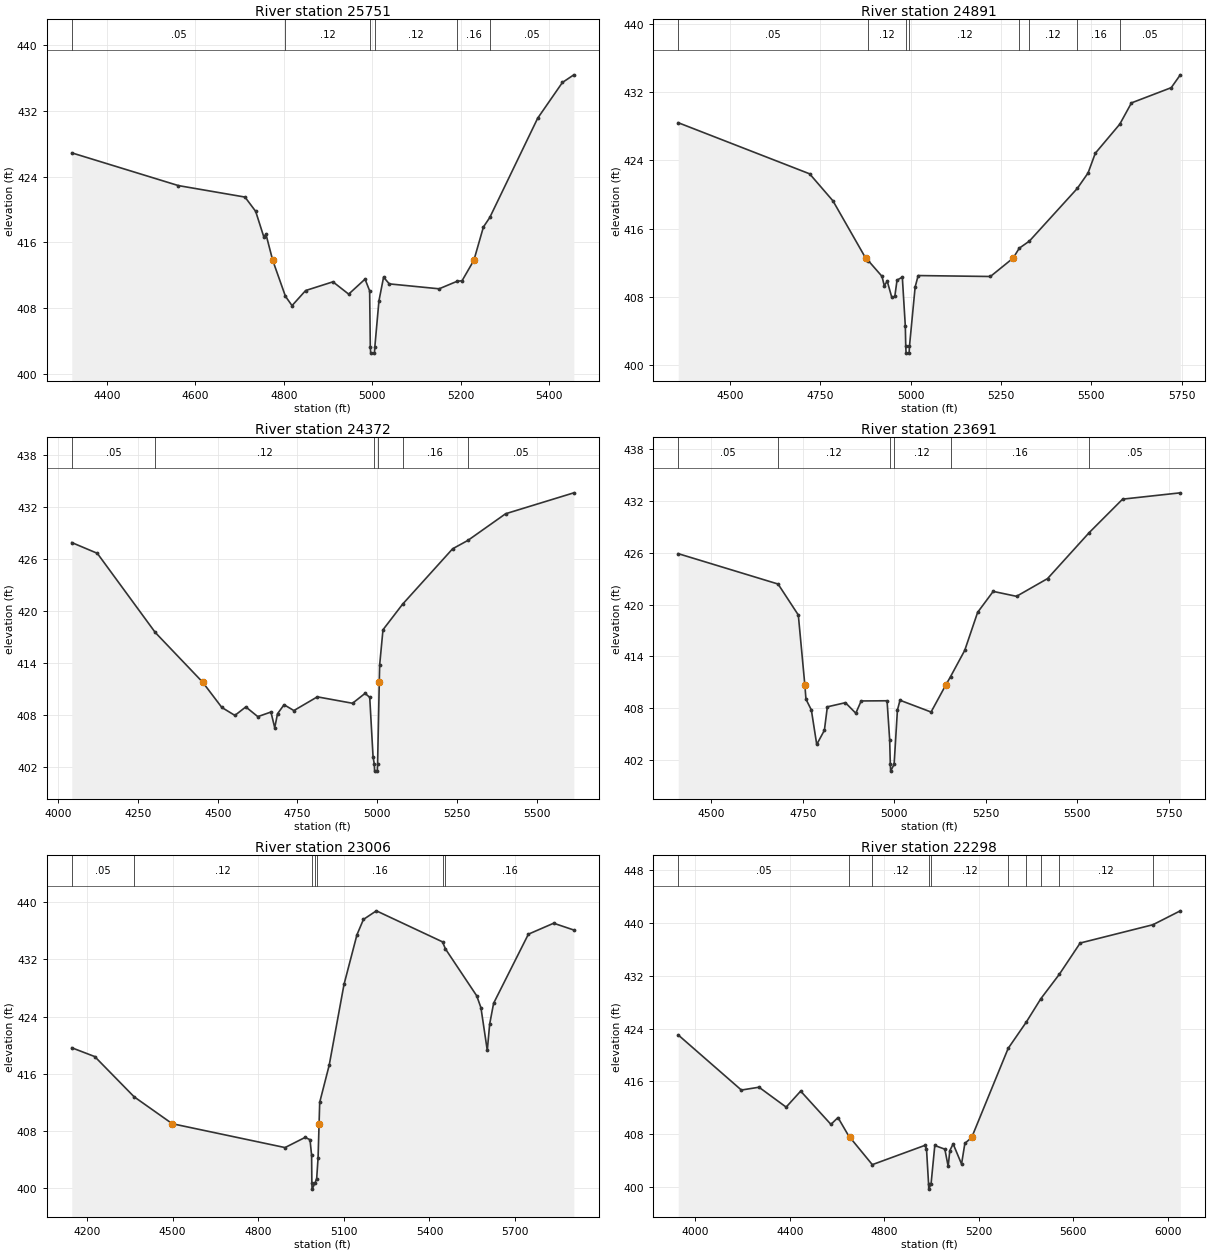
Type RM Length L Ch R = 1,25751,860,860,860
BEGIN DESCRIPTION:
MUSTANG CREEK 32.0
END DESCRIPTION:
XS GIS Cut Line= 4
      2838649.48      7008689.60      2838793.56      7008080.27
      2838857.80      7007873.67      2838930.01      7007590.01
#Sta/Elev= 30
  4320.5  426.91  4561.6  422.92  4712.2  421.52  4736.3  419.78  4754.5  416.70
  4759.6  416.98  4774.8  413.82  4803.6  409.43  4818.5  408.29  4849.3  410.13
  4911.0  411.19  4946.6  409.69  4983.6  411.52  4994.0  410.09  4995.5  403.30
  4996.4  402.50  5004.8  402.50  5005.8  403.30  5015.0  408.86  5025.5  411.76
  5038.4  410.94  5151.1  410.34  5191.9  411.26  5202.9  411.32  5229.7  413.82
  5251.2  417.87  5265.7  419.04  5373.9  431.13  5429.9  435.49  5455.7  436.42
#Mann=6,-1,0
  4320.5    0.05       0  4803.6    0.12       0  4995.5    0.07       0
  5005.8    0.12       0  5191.9    0.16       0  5265.7    0.05       0
Bank Sta=4774.8,5229.7
Exp/Cntr=0.3,0.1

Type RM Length L Ch R = 1,24891,519,519,519
BEGIN DESCRIPTION:
MUSTANG CREEK 31.0
END DESCRIPTION:
XS GIS Cut Line= 3
      2838781.41      7008809.43      2839232.80      7008201.80
      2839260.57      7007569.96
#Sta/Elev= 30
  4356.6  428.44  4720.2  422.43  4784.8  419.25  4875.3  412.52  4882.8  412.21
  4920.4  410.38  4926.7  409.29  4935.0  409.80  4947.6  407.90  4955.9  408.01
  4962.1  409.93  4976.7  410.29  4985.0  404.53  4986.2  402.15  4987.1  401.35
  4995.5  401.35  4996.5  402.15  5012.2  409.13  5020.6  410.47  5220.5  410.36
  5283.3  412.52  5300.4  413.69  5328.3  414.52  5461.0  420.72  5490.7  422.53
  5510.7  424.85  5578.5  428.27  5610.8  430.77  5720.9  432.56  5746.0  434.07
#Mann=8,-1,0
  4356.6    0.05       0  4882.8    0.12       0  4986.2    0.07       0
  4996.5    0.12       0  5300.4    0.16       0  5328.3    0.12       0
  5461.0    0.16       0  5578.5    0.05       0
Bank Sta=4875.3,5283.3
Exp/Cntr=0.3,0.1

Type RM Length L Ch R = 1,24372,681,681,681
BEGIN DESCRIPTION:
MUSTANG CREEK 30.0
END DESCRIPTION:
XS GIS Cut Line= 3
      2839722.38      7009062.90      2839541.83      7008281.66
      2839333.70      7007539.32
#Sta/Elev= 30
  4042.9  427.86  4122.9  426.62  4304.4  417.50  4452.7  411.78  4512.9  408.86
  4553.9  407.94  4588.1  408.92  4625.7  407.80  4666.8  408.33  4678.7  406.52
  4687.4  408.13  4707.9  409.17  4738.7  408.50  4812.1  410.08  4922.4  409.34
  4961.7  410.48  4976.3  410.02  4986.7  403.18  4990.6  402.32  4991.6  401.52
  5000.0  401.52  5000.9  402.32  5006.2  411.78  5007.4  413.75  5017.8  417.81
  5079.3  420.76  5235.9  427.14  5283.9  428.11  5402.0  431.18  5615.7  433.59
#Mann=6,-1,0
  4042.9    0.05       0  4304.4    0.12       0  4990.6    0.07       0
  5000.9    0.12       0  5079.3    0.16       0  5283.9    0.05       0
Bank Sta=4452.7,5006.2
Exp/Cntr=0.3,0.1

Type RM Length L Ch R = 1,23691,685,685,685
BEGIN DESCRIPTION:
MUSTANG CREEK 29.0
END DESCRIPTION:
XS GIS Cut Line= 3
      2840312.67      7008535.14      2840024.58      7008136.55
      2839406.40      7007510.81
#Sta/Elev= 30
  4409.9  425.88  4682.6  422.37  4737.9  418.79  4755.7  410.72  4758.8  409.06
  4773.5  407.82  4788.2  403.83  4809.1  405.47  4817.2  408.18  4866.6  408.66
  4894.9  407.44  4909.6  408.86  4980.3  408.88  4987.4  404.38  4989.2  401.55
  4990.1  400.75  4999.6  401.55  5008.6  407.81  5015.7  408.94  5100.5  407.58
  5140.9  410.72  5153.7  411.67  5192.4  414.70  5227.7  419.10  5270.2  421.52
  5333.9  420.95  5418.7  423.00  5532.6  428.32  5623.7  432.18  5781.3  432.91
#Mann=6,-1,0
  4409.9    0.05       0  4682.6    0.12       0  4989.2    0.07       0
  4999.6    0.12       0  5153.7    0.16       0  5532.6    0.05       0
Bank Sta=4755.7,5140.9
Exp/Cntr=0.3,0.1

Type RM Length L Ch R = 1,23006,708,708,708
BEGIN DESCRIPTION:
MUSTANG CREEK 28.0
END DESCRIPTION:
XS GIS Cut Line= 3
      2840468.92      7008410.15      2840287.29      7007679.46
      2839854.31      7006771.21
#Sta/Elev= 30
  4146.7  419.64  4227.2  418.41  4365.3  412.79  4498.7  409.04  4893.9  405.71
  4964.3  407.13  4981.4  406.81  4987.0  404.63  4987.9  400.71  4988.8  399.91
  4998.4  400.71  5004.8  401.39  5009.7  404.30  5013.2  409.04  5015.4  412.03
  5048.6  417.20  5100.5  428.47  5145.9  435.41  5168.6  437.55  5213.9  438.75
  5445.7  434.42  5455.7  433.45  5565.5  426.89  5580.3  425.23  5602.5  419.27
  5610.9  422.95  5624.7  425.85  5746.5  435.49  5835.1  437.02  5905.8  436.07
#Mann=7,-1,0
  4146.7    0.05       0  4365.3    0.12       0  4987.9    0.07       0
  4998.4    0.12       0  5004.8    0.16       0  5445.7    0.12       0
  5455.7    0.16       0
Bank Sta=4498.7,5013.2
Exp/Cntr=0.3,0.1

Type RM Length L Ch R = 1,22298,922,922,922
BEGIN DESCRIPTION:
MUSTANG CREEK 27.0
END DESCRIPTION:
XS GIS Cut Line= 3
      2841013.18      7008312.45      2840862.14      7007385.39
      2840034.05      7006536.47
#Sta/Elev= 30
  3927.3  423.03  4194.5  414.70  4269.2  415.13  4384.1  412.12  4445.5  414.54
  4573.6  409.51  4603.5  410.54  4649.2  407.74  4654.4  407.53  4748.8  403.42
  4970.9  406.33  4978.1  405.85  4986.9  400.52  4987.8  399.72  4997.5  400.52
  5013.3  406.32  5055.8  405.76  5069.9  403.16  5076.9  405.55  5091.0  406.56
  5126.5  403.51  5140.6  406.64  5169.4  407.53  5323.8  421.00  5400.4  424.97
  5462.3  428.52  5540.3  432.20  5628.6  436.93  5936.7  439.70  6052.5  441.80
#Mann=10,-1,0
  3927.3    0.05       0  4649.2    0.07       0  4748.8    0.12       0
  4986.9    0.07       0  4997.5    0.12       0  5323.8    0.16       0
  5400.4    0.12       0  5462.3    0.16       0  5540.3    0.12       0
  5936.7    0.05       0
Bank Sta=4654.4,5169.4
Exp/Cntr=0.3,0.1

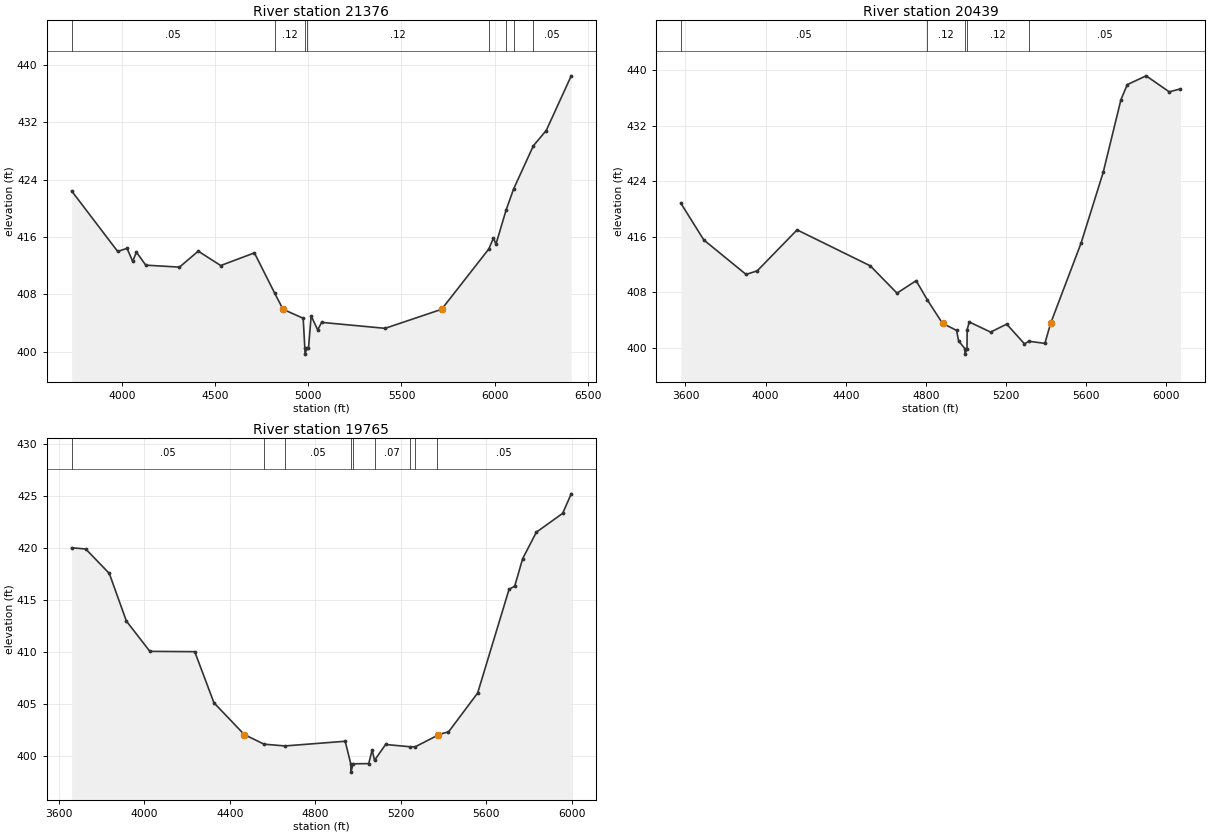
Type RM Length L Ch R = 1,21376,937,937,937
BEGIN DESCRIPTION:
MUSTANG CREEK 26.0
END DESCRIPTION:
XS GIS Cut Line= 3
      2841268.39      7008270.82      2841372.56      7007171.85
      2840331.10      7005989.80
#Sta/Elev= 30
  3731.1  422.41  3978.0  413.99  4028.3  414.42  4058.4  412.61  4078.5  413.89
  4128.7  412.08  4309.5  411.81  4410.0  414.03  4530.5  412.03  4711.3  413.79
  4819.5  408.21  4864.8  405.94  4972.9  404.69  4981.8  400.50  4982.7  399.70
  4992.4  400.50  5001.3  400.51  5015.6  405.02  5050.7  403.07  5071.6  404.12
  5412.1  403.29  5715.3  405.94  5968.3  414.33  5992.7  415.83  6007.0  415.03
  6061.5  419.78  6101.5  422.69  6207.4  428.70  6276.4  430.82  6410.4  438.43
#Mann=8,-1,0
  3731.1    0.05       0  4819.5    0.12       0  4981.8    0.07       0
  4992.4    0.12       0  5968.3    0.16       0  6061.5    0.12       0
  6101.5    0.16       0  6207.4    0.05       0
Bank Sta=4864.8,5715.3
Exp/Cntr=0.3,0.1

Type RM Length L Ch R = 1,20439,674,674,674
BEGIN DESCRIPTION:
MUSTANG CREEK 25.0
END DESCRIPTION:
XS GIS Cut Line= 3
      2841382.97      7008291.65      2841903.81      7006828.80
      2841825.68      7005890.55
#Sta/Elev= 30
  3577.0  420.83  3691.5  415.53  3902.5  410.55  3958.3  411.07  4157.3  416.98
  4522.8  411.79  4656.2  407.85  4751.7  409.65  4808.2  406.85  4883.4  403.49
  4953.4  402.48  4964.0  400.94  4994.9  399.85  4995.7  399.05  5005.5  399.85
  5006.5  402.59  5017.1  403.69  5123.5  402.23  5203.9  403.38  5292.7  400.53
  5314.5  400.91  5394.5  400.60  5423.1  403.49  5575.1  415.06  5685.5  425.27
  5774.5  435.79  5805.9  437.94  5900.0  439.21  6015.4  436.90  6071.3  437.32
#Mann=5,-1,0
  3577.0    0.05       0  4808.2    0.12       0  4994.9    0.07       0
  5005.5    0.12       0  5314.5    0.05       0
Bank Sta=4883.4,5423.1
Exp/Cntr=0.3,0.1

Type RM Length L Ch R = 1,19765,777,777,777
BEGIN DESCRIPTION:
MUSTANG CREEK 24.0
END DESCRIPTION:
XS GIS Cut Line= 3
      2842343.04      7008241.14      2842360.41      7007047.55
      2842008.83      7005958.09
#Sta/Elev= 30
  3659.5  420.00  3725.6  419.88  3835.7  417.53  3915.7  412.95  4025.7  410.03
  4235.7  410.00  4325.7  405.08  4467.4  402.03  4560.1  401.10  4657.9  400.93
  4940.0  401.38  4966.1  399.21  4966.9  398.41  4976.9  399.21  5050.1  399.23
  5066.1  400.55  5077.2  399.54  5129.1  401.07  5243.7  400.85  5268.0  400.85
  5371.5  401.94  5375.2  402.03  5423.3  402.27  5559.9  406.02  5707.0  416.00
  5733.5  416.31  5770.8  418.96  5834.9  421.50  5957.8  423.31  5998.0  425.19
#Mann=9,-1,0
  3659.5    0.05       0  4560.1    0.07       0  4657.9    0.05       0
  4966.1   0.033       0  4976.9    0.05       0  5077.2    0.07       0
  5243.7    0.05       0  5268.0    0.07       0  5371.5    0.05       0
Bank Sta=4467.4,5375.2
Exp/Cntr=0.3,0.1