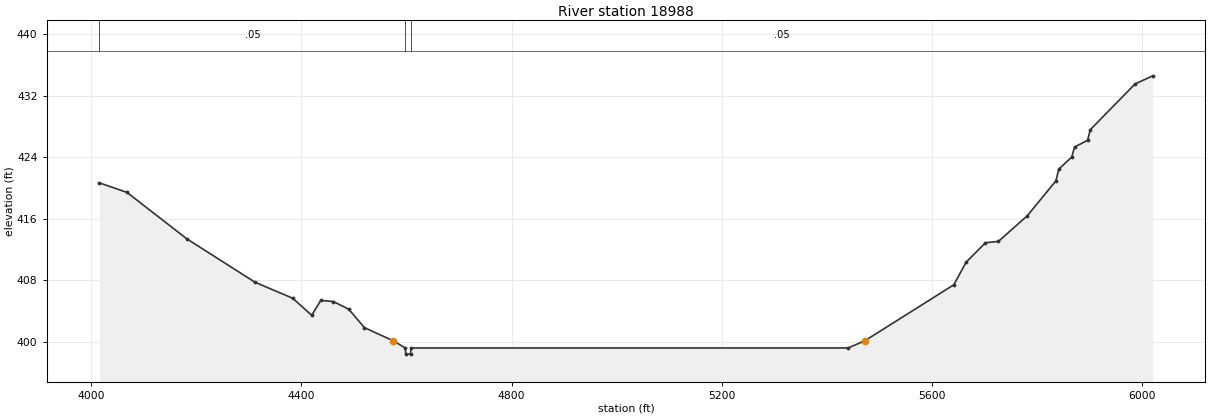
HEC-RAS study MUSTANG CREEK.prj: MUSTANG CREEK Base Level Engineering

--- MUSTANG CREEK.g01 (geometry) --- (continued)

Type RM Length L Ch R = 1,18988,0,0,0
BEGIN DESCRIPTION:
MUSTANG CREEK 23.0
END DESCRIPTION:
XS GIS Cut Line= 3
      2842590.45      7008219.41      2842915.96      7007420.81
      2843323.95      7006353.09
#Sta/Elev= 30
  4015.2  420.66  4067.8  419.42  4181.9  413.38  4311.5  407.75  4383.3  405.67
  4419.5  403.46  4436.8  405.39  4460.9  405.24  4490.3  404.23  4519.7  401.86
  4575.0  400.13  4597.7  399.21  4598.5  398.41  4607.7  398.41  4608.5  399.21
  5440.5  399.21  5472.2  400.13  5641.9  407.42  5665.3  410.35  5702.1  412.88
  5726.8  413.05  5781.6  416.37  5836.3  420.92  5841.7  422.44  5866.4  424.01
  5871.7  425.31  5896.5  426.18  5901.8  427.57  5986.7  433.49  6020.6  434.56
#Mann=3,-1,0
  4015.2    0.05       0  4597.7   0.033       0  4608.5    0.05       0
Bank Sta=4575,5472.2
Exp/Cntr=0.3,0.1

Chan Stop Cuts=-1