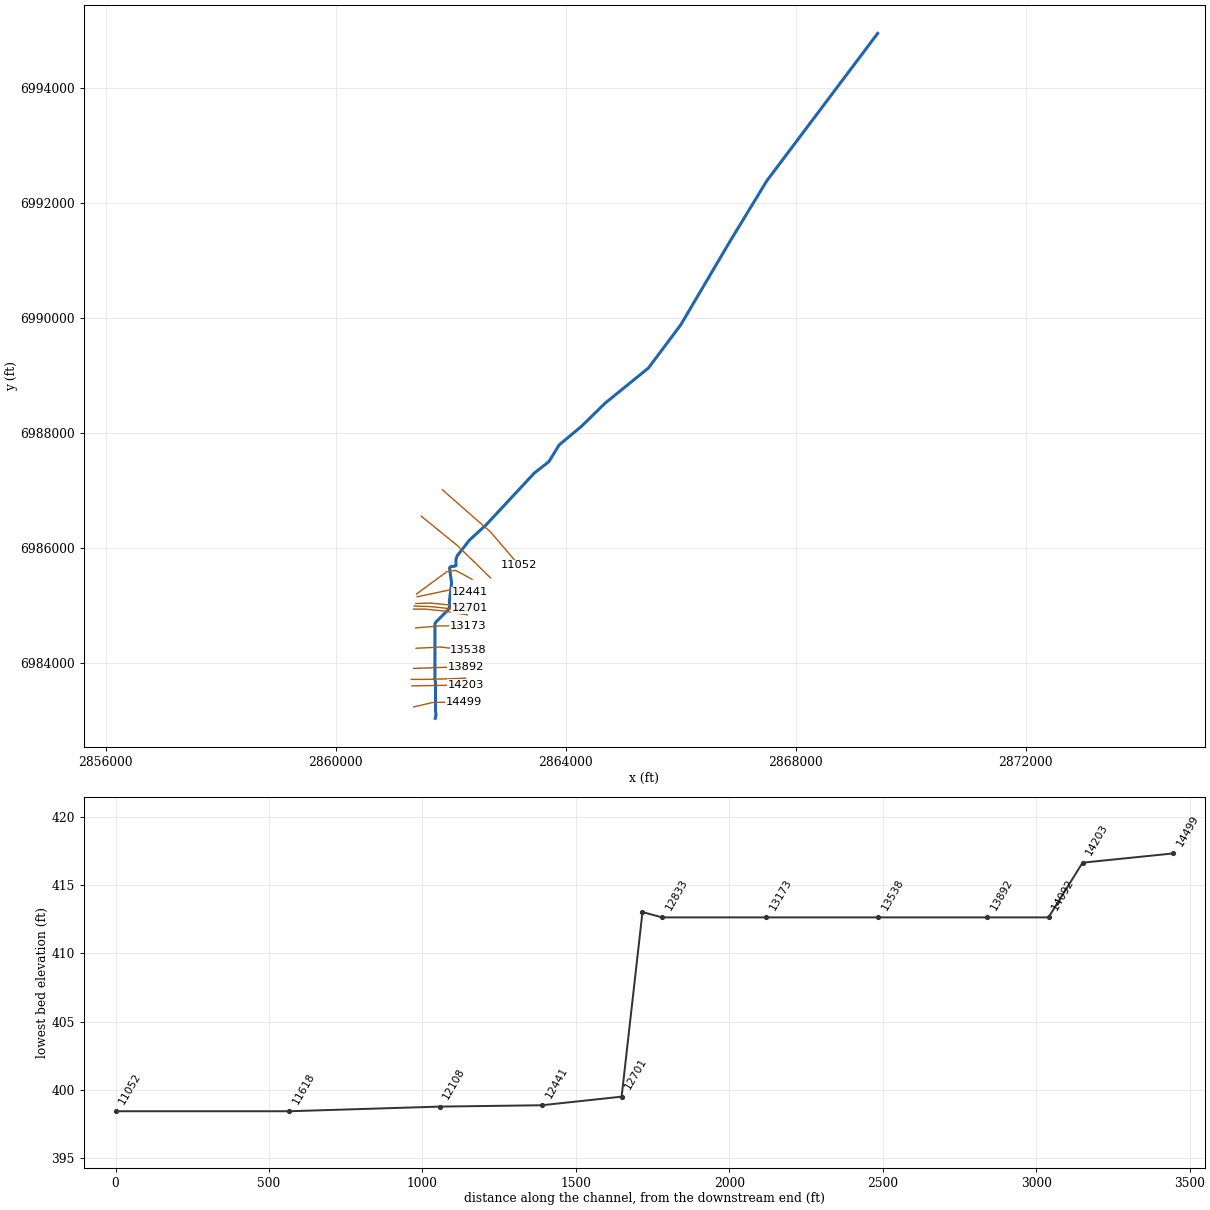
--- RAY BRANCH.prj (project) ---

Proj Title=RAY BRANCH Base Level Engineering
Current Plan=p01
Default Exp/Contr=0.3,0.1
English Units
Geom File=g01
Flow File=f01
Plan File=p01
BEGIN DESCRIPTION:
RAY BRANCH
END DESCRIPTION:

--- RAY BRANCH.p01 (plan) ---

Plan Title=Multiple Run
Short Identifier=Multiple
Geom File=g01
Flow File=f01
Subcritical Flow
K Sum by GR= 0
Std Step Tol= 0.01
Critical Tol= 0.01
Num of Std Step Trials= 20
Max Error Tol= 0.3
Flow Tol Ratio= 0.001
Split Flow NTrial= 30
Split Flow Tol= 0.02
Split Flow Ratio= 0.02
Log Output Level= 0
Friction Slope Method= 1
Unsteady Friction Slope Method= 2
Unsteady Bridges Friction Slope Method= 1
Parabolic Critical Depth
Global Vel Dist=  1 , 1 , 1
Global Log Level= 0
CheckData=True
Encroach Param= -1, 0, 0, 0
BEGIN DESCRIPTION:
Multiple Run
END DESCRIPTION:

--- RAY BRANCH.f01 (steady flow) ---

Flow Title=Multiple
Number of Profiles=7
Profile Names=10-year,25-year,50-year,1pct_min,100-year,1pct_plu,500-year
River Rch & RM= RAY BRANCH,Reach-1,14499
     379     496     589     349     696    1389     972
River Rch & RM= RAY BRANCH,Reach-1,11618
     813    1109    1354     820    1637    3265    2397
Boundary for River Rch & Prof#=RAY BRANCH,Reach-1,1
Up Type=0
Dn Type=3
Dn Slope=0.005
Boundary for River Rch & Prof#=RAY BRANCH,Reach-1,2
Up Type=0
Dn Type=3
Dn Slope=0.005
Boundary for River Rch & Prof#=RAY BRANCH,Reach-1,3
Up Type=0
Dn Type=3
Dn Slope=0.005
Boundary for River Rch & Prof#=RAY BRANCH,Reach-1,4
Up Type=0
Dn Type=3
Dn Slope=0.005
Boundary for River Rch & Prof#=RAY BRANCH,Reach-1,5
Up Type=0
Dn Type=3
Dn Slope=0.005
Boundary for River Rch & Prof#=RAY BRANCH,Reach-1,6
Up Type=0
Dn Type=3
Dn Slope=0.005
Boundary for River Rch & Prof#=RAY BRANCH,Reach-1,7
Up Type=0
Dn Type=3
Dn Slope=0.005

--- RAY BRANCH.g01 (geometry) ---

Geom Title=Existing Conditions

River Reach=RAY BRANCH,Reach-1
Reach XY= 30
      2861730.67      6983043.24      2861745.67      6983100.62
      2861735.69      6983170.44      2861735.53      6983660.95
      2861725.49      6983740.67      2861725.97      6984685.55
      2861742.94      6984718.48      2861948.17      6984923.03
      2861973.61      6984958.02      2861982.99      6985001.55
      2861976.45      6985074.66      2862015.66      6985395.72
      2861979.47      6985659.39      2862002.50      6985682.42
      2862071.58      6985689.62      2862093.17      6985701.13
      2862091.73      6985806.19      2862110.44      6985866.64
      2862324.88      6986141.53      2862615.60      6986407.79
      2863452.04      6987306.40      2863706.96      6987506.95
      2863887.07      6987798.56      2864277.31      6988124.47
      2864684.70      6988523.29      2865439.45      6989136.52
      2866001.22      6989886.98      2866846.02      6991319.29
      2867497.85      6992391.37      2869426.44      6994956.66

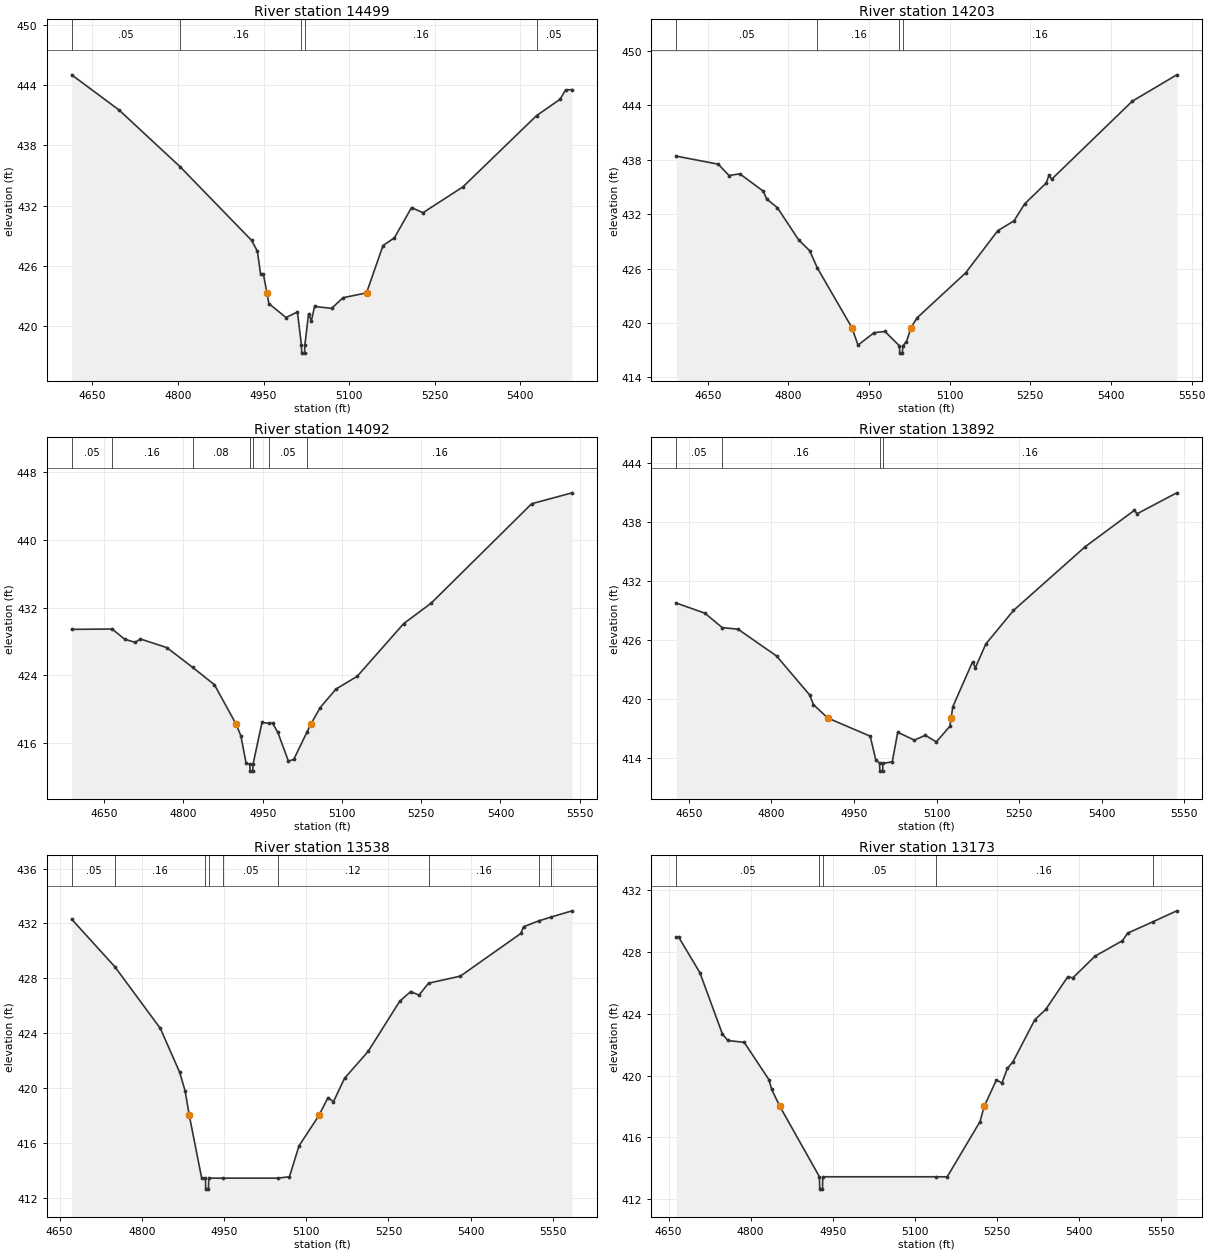
Type RM Length L Ch R = 1,14499,296,296,296
BEGIN DESCRIPTION:
RAY BRANCH 25.0
END DESCRIPTION:
XS GIS Cut Line= 3
      2861358.28      6983241.09      2861681.21      6983317.48
      2862226.34      6983333.10
#Sta/Elev= 30
  4613.7  445.02  4696.8  441.52  4803.4  435.90  4928.9  428.57  4939.2  427.49
  4944.9  425.18  4949.9  425.18  4955.9  423.34  4959.3  422.28  4989.4  420.89
  5009.4  421.44  5016.4  418.15  5016.9  417.35  5021.9  417.35  5022.4  418.15
  5028.9  421.24  5033.9  420.56  5039.4  421.99  5069.4  421.80  5089.4  422.86
  5130.5  423.34  5159.4  428.04  5179.4  428.82  5209.4  431.82  5229.5  431.31
  5299.5  433.88  5428.5  440.96  5469.6  442.58  5479.6  443.52  5490.9  443.55
#Mann=5,-1,0
  4613.7    0.05       0  4803.4    0.16       0  5016.4    0.07       0
  5022.4    0.16       0  5428.5    0.05       0
Bank Sta=4955.9,5130.5
Exp/Cntr=0.3,0.1

Type RM Length L Ch R = 1,14203,111,111,111
BEGIN DESCRIPTION:
Mapping XS 40e7afd3
END DESCRIPTION:
XS GIS Cut Line= 4
      2861327.00      6983607.41      2861649.96      6983612.62
      2862007.60      6983619.56      2862257.64      6983628.25
#Sta/Elev= 30
  4591.4  438.41  4669.4  437.52  4689.4  436.27  4709.4  436.46  4753.2  434.54
  4759.4  433.68  4779.4  432.72  4819.4  429.13  4839.4  427.98  4853.8  426.06
  4917.9  419.49  4929.4  417.56  4959.4  418.93  4979.5  419.06  5006.5  417.47
  5007.0  416.67  5012.0  416.67  5012.5  417.47  5019.5  417.92  5027.9  419.49
  5039.5  420.58  5129.5  425.52  5189.5  430.19  5219.5  431.26  5239.5  433.15
  5279.5  435.44  5284.6  436.30  5289.6  435.86  5439.6  444.47  5522.3  447.38
#Mann=4,-1,0
  4591.4    0.05       0  4853.8    0.16       0  5006.5    0.07       0
  5012.5    0.16       0
Bank Sta=4917.9,5027.9
Exp/Cntr=0.3,0.1

Type RM Length L Ch R = 1,14092,200,200,200
BEGIN DESCRIPTION:
Mapping XS 551ec3aa
END DESCRIPTION:
XS GIS Cut Line= 4
      2861314.92      6983720.26      2861557.94      6983720.26
      2861972.87      6983730.67      2862261.43      6983742.77
#Sta/Elev= 30
  4588.6  429.43  4665.2  429.47  4688.7  428.27  4708.7  427.89  4718.7  428.29
  4768.7  427.27  4817.3  424.94  4858.7  422.88  4899.4  418.24  4908.7  416.84
  4918.7  413.57  4925.7  413.45  4926.2  412.65  4931.2  412.65  4931.7  413.45
  4948.7  418.41  4961.5  418.31  4968.7  418.32  4978.7  417.23  4998.7  413.84
  5008.7  414.03  5033.8  417.26  5041.3  418.24  5058.8  420.17  5088.8  422.37
  5128.8  423.87  5216.8  430.11  5268.8  432.53  5459.0  444.30  5535.5  445.59
#Mann=7,-1,0
  4588.6    0.05       0  4665.2    0.16       0  4817.3    0.08       0
  4925.7    0.04       0  4931.7    0.08       0  4961.5    0.05       0
  5033.8    0.16       0
Bank Sta=4899.4,5041.3
Exp/Cntr=0.3,0.1

Type RM Length L Ch R = 1,13892,354,354,354
BEGIN DESCRIPTION:
RAY BRANCH 24.0
END DESCRIPTION:
XS GIS Cut Line= 3
      2861353.11      6983911.23      2861849.61      6983928.59
      2862261.37      6983942.43
#Sta/Elev= 30
  4627.3  429.77  4679.2  428.74  4710.6  427.27  4739.3  427.11  4809.3  424.38
  4869.3  420.42  4876.3  419.43  4902.3  418.06  4979.4  416.21  4989.4  413.83
  4996.4  413.45  4996.9  412.65  5001.9  412.65  5002.4  413.45  5019.4  413.59
  5029.4  416.61  5059.5  415.81  5079.5  416.30  5099.5  415.63  5124.1  417.22
  5126.3  418.06  5129.5  419.23  5165.3  423.78  5170.3  423.18  5189.5  425.61
  5239.6  429.02  5369.6  435.50  5459.2  439.22  5464.2  438.87  5536.1  441.00
#Mann=4,-1,0
  4627.3    0.05       0  4710.6    0.16       0  4996.4    0.07       0
  5002.4    0.16       0
Bank Sta=4902.3,5126.3
Exp/Cntr=0.3,0.1

Type RM Length L Ch R = 1,13538,365,365,365
BEGIN DESCRIPTION:
RAY BRANCH 23.0
END DESCRIPTION:
XS GIS Cut Line= 3
      2861398.27      6984261.93      2861814.89      6984282.76
      2862307.91      6984230.68
#Sta/Elev= 30
  4672.1  432.31  4751.0  428.84  4833.9  424.35  4869.1  421.16  4879.1  419.79
  4886.6  418.02  4909.1  413.48  4916.1  413.45  4916.6  412.65  4921.6  412.65
  4922.1  413.45  4949.0  413.45  5048.1  413.45  5069.3  413.55  5086.8  415.80
  5123.2  418.02  5139.6  419.31  5149.7  419.02  5169.8  420.72  5212.9  422.68
  5270.4  426.33  5290.5  427.04  5305.7  426.78  5323.1  427.65  5381.0  428.16
  5491.4  431.27  5496.4  431.76  5524.3  432.19  5546.9  432.47  5585.0  432.92
#Mann=9,-1,0
  4672.1    0.05       0  4751.0    0.16       0  4916.1   0.033       0
  4922.1    0.16       0  4949.0    0.05       0  5048.1    0.12       0
  5323.1    0.16       0  5524.3    0.12       0  5546.9    0.05       0
Bank Sta=4886.6,5123.2
Exp/Cntr=0.3,0.1

Type RM Length L Ch R = 1,13173,340,340,340
BEGIN DESCRIPTION:
RAY BRANCH 22.0
END DESCRIPTION:
XS GIS Cut Line= 3
      2861391.29      6984616.09      2861811.42      6984650.81
      2862304.46      6984650.81
#Sta/Elev= 30
  4664.2  428.97  4668.6  428.97  4707.3  426.67  4748.2  422.72  4758.2  422.28
  4788.3  422.16  4833.3  419.75  4838.5  419.11  4853.4  418.01  4925.8  413.45
  4926.3  412.65  4931.3  412.65  4931.8  413.45  5138.5  413.45  5159.3  413.45
  5219.3  417.03  5226.8  418.01  5249.3  419.73  5259.3  419.52  5269.3  420.48
  5279.3  420.89  5319.3  423.62  5339.3  424.29  5379.3  426.39  5389.3  426.35
  5429.3  427.74  5479.3  428.74  5489.3  429.24  5534.7  429.96  5578.8  430.68
#Mann=5,-1,0
  4664.2    0.05       0  4925.8   0.033       0  4931.8    0.05       0
  5138.5    0.16       0  5534.7    0.08       0
Bank Sta=4853.4,5226.8
Exp/Cntr=0.3,0.1

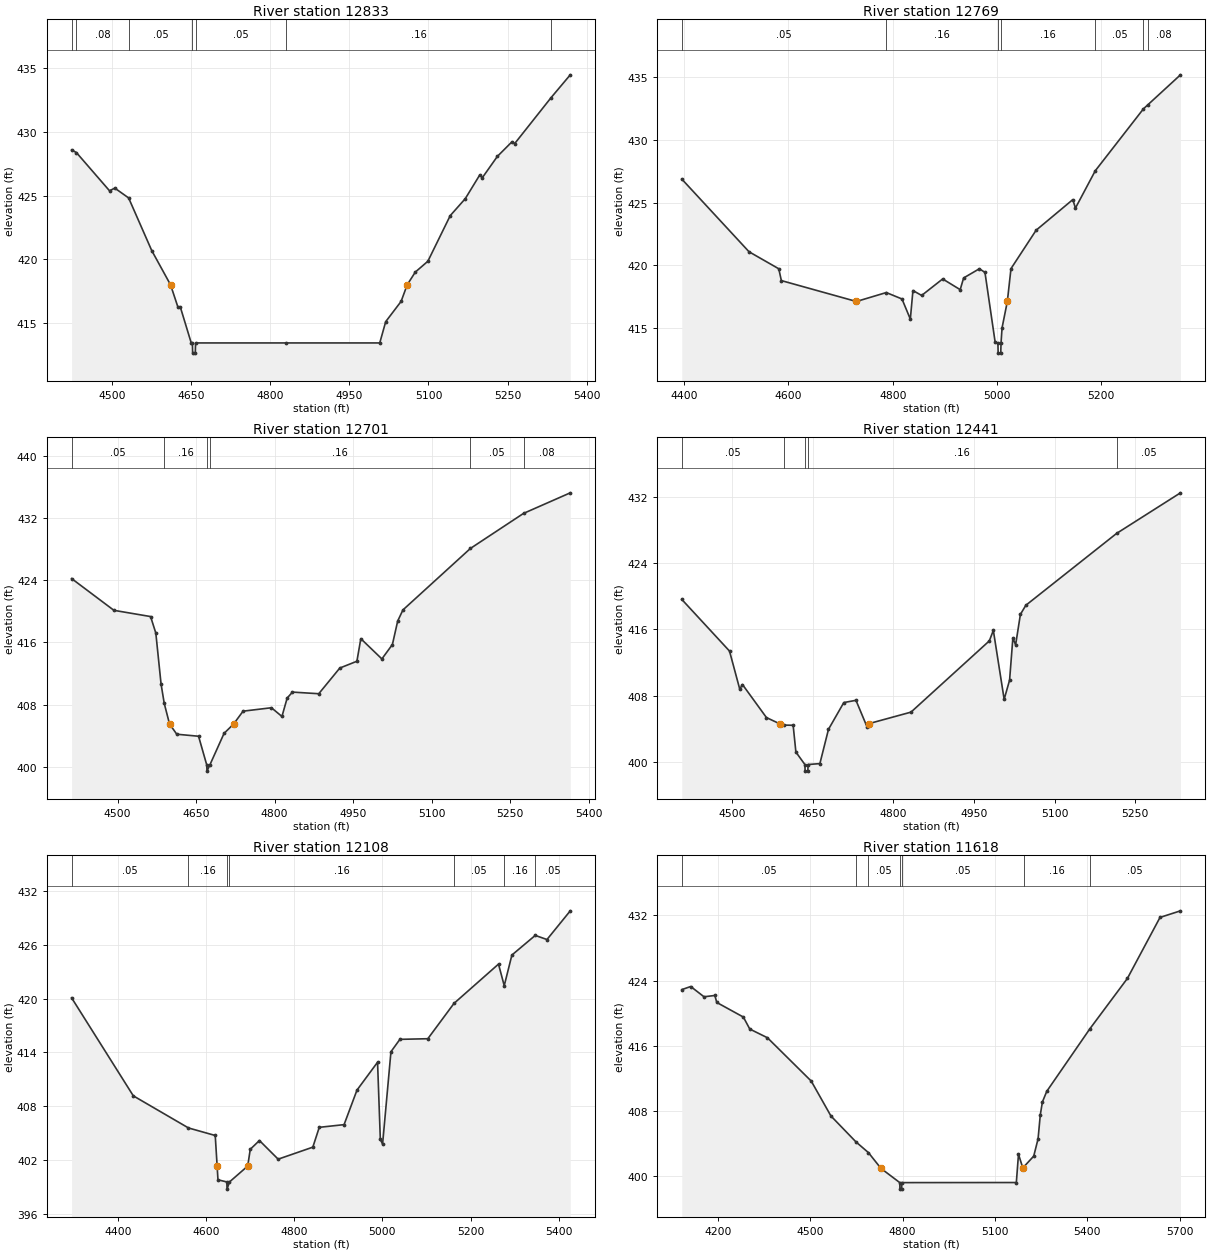
Type RM Length L Ch R = 1,12833,64,64,64
BEGIN DESCRIPTION:
Mapping XS 6beb2860
END DESCRIPTION:
XS GIS Cut Line= 4
      2861353.12      6984942.05      2861559.25      6984942.05
      2861884.77      6984909.49      2862291.40      6984842.44
#Sta/Elev= 30
  4423.4  428.60  4432.5  428.39  4495.3  425.39  4505.3  425.60  4531.5  424.83
  4575.3  420.70  4611.0  418.01  4624.9  416.27  4629.5  416.27  4650.2  413.45
  4652.4  413.45  4652.9  412.65  4657.9  412.65  4658.4  413.45  4830.1  413.45
  5007.6  413.45  5018.9  415.12  5048.1  416.71  5059.6  418.01  5075.0  419.01
  5098.8  419.86  5141.2  423.44  5169.7  424.77  5197.3  426.64  5202.3  426.43
  5230.6  428.09  5258.4  429.24  5263.5  429.10  5332.6  432.71  5368.8  434.49
#Mann=7,-1,0
  4423.4    0.05       0  4432.5    0.08       0  4531.5    0.05       0
  4652.4    0.07       0  4658.4    0.05       0  4830.1    0.16       0
  5332.6    0.08       0
Bank Sta=4611,5059.6
Exp/Cntr=0.3,0.1

Type RM Length L Ch R = 1,12769,68,68,68
BEGIN DESCRIPTION:
Mapping XS 9ec3aff8
END DESCRIPTION:
XS GIS Cut Line= 6
      2861366.14      6984994.13      2861563.59      6984989.79
      2861685.11      6984983.28      2861784.94      6984972.43
      2861941.19      6984955.07      2862316.66      6984900.81
#Sta/Elev= 30
  4395.5  426.86  4524.4  421.09  4581.4  419.74  4586.4  418.80  4730.3  417.14
  4787.6  417.85  4817.7  417.34  4833.7  415.74  4838.7  418.01  4855.4  417.62
  4895.7  418.93  4929.3  418.08  4935.9  419.01  4966.1  419.74  4976.8  419.45
  4996.4  413.89  5001.6  413.84  5002.1  413.04  5007.1  413.04  5007.6  413.84
  5009.6  415.05  5019.7  417.14  5026.7  419.75  5074.9  422.80  5145.2  425.23
  5150.3  424.56  5188.3  427.52  5280.7  432.44  5288.6  432.74  5351.7  435.14
#Mann=7,-1,0
  4395.5    0.05       0  4787.6    0.16       0  5001.6    0.07       0
  5007.6    0.16       0  5188.3    0.05       0  5280.7    0.16       0
  5288.6    0.08       0
Bank Sta=4730.3,5019.7
Exp/Cntr=0.3,0.1

Type RM Length L Ch R = 1,12701,260,260,260
BEGIN DESCRIPTION:
Mapping XS 58e23348
END DESCRIPTION:
XS GIS Cut Line= 4
      2861394.29      6985039.70      2861633.03      6985048.38
      2862140.84      6985000.64      2862340.21      6984961.63
#Sta/Elev= 30
  4412.3  424.21  4493.1  420.13  4563.1  419.33  4573.1  417.21  4583.1  410.67
  4589.2  408.17  4599.3  405.53  4613.1  404.22  4654.7  403.96  4670.3  400.28
  4670.8  399.48  4676.3  400.28  4703.4  404.33  4721.6  405.53  4739.7  407.18
  4793.8  407.62  4813.9  406.50  4823.9  408.87  4834.0  409.63  4884.2  409.42
  4924.4  412.72  4957.0  413.59  4964.5  416.49  5004.7  413.89  5024.8  415.74
  5034.9  418.76  5044.9  420.18  5173.8  428.08  5275.2  432.58  5364.4  435.22
#Mann=6,-1,0
  4412.3    0.05       0  4589.2    0.16       0  4670.3    0.07       0
  4676.3    0.16       0  5173.8    0.05       0  5275.2    0.08       0
Bank Sta=4599.3,4721.6
Exp/Cntr=0.3,0.1

Type RM Length L Ch R = 1,12441,333,333,333
BEGIN DESCRIPTION:
RAY BRANCH 21.0
END DESCRIPTION:
XS GIS Cut Line= 3
      2861418.21      6985156.90      2861975.00      6985275.00
      2862330.93      6985237.28
#Sta/Elev= 30
  4406.8  419.63  4495.5  413.38  4514.5  408.78  4519.6  409.33  4564.2  405.33
  4588.5  404.59  4597.5  404.42  4613.8  404.40  4618.9  401.16  4635.6  399.65
  4636.1  398.85  4641.1  398.85  4641.6  399.65  4663.5  399.76  4679.5  403.91
  4708.0  407.15  4730.6  407.42  4751.1  404.22  4754.2  404.59  4832.9  405.99
  4978.5  414.61  4986.0  415.88  5006.1  407.54  5016.2  409.86  5022.3  414.97
  5027.4  414.13  5036.3  417.82  5046.4  418.92  5215.2  427.62  5333.9  432.53
#Mann=5,-1,0
  4406.8    0.05       0  4597.5    0.16       0  4635.6    0.07       0
  4641.6    0.16       0  5215.2    0.05       0
Bank Sta=4588.5,4754.2
Exp/Cntr=0.3,0.1

Type RM Length L Ch R = 1,12108,490,490,490
BEGIN DESCRIPTION:
RAY BRANCH 20.0
END DESCRIPTION:
XS GIS Cut Line= 4
      2861407.36      6985206.82      2861930.06      6985591.29
      2862084.42      6985616.96      2862371.51      6985461.54
#Sta/Elev= 30
  4294.6  420.08  4434.7  409.15  4559.9  405.57  4620.6  404.73  4624.9  401.32
  4626.8  399.79  4646.9  399.55  4647.4  398.75  4652.9  399.55  4694.3  401.32
  4700.1  403.19  4720.9  404.17  4763.4  402.09  4842.1  403.43  4856.7  405.64
  4913.0  405.94  4942.3  409.79  4989.0  412.90  4995.3  404.29  5000.4  403.77
  5019.4  414.07  5039.7  415.45  5103.1  415.52  5162.5  419.46  5263.5  423.84
  5276.5  421.43  5293.9  424.85  5346.9  427.04  5373.5  426.58  5426.4  429.78
#Mann=7,-1,0
  4294.6    0.05       0  4559.9    0.16       0  4646.9    0.07       0
  4652.9    0.16       0  5162.5    0.05       0  5276.5    0.16       0
  5346.9    0.05       0
Bank Sta=4624.9,4694.3
Exp/Cntr=0.3,0.1

Type RM Length L Ch R = 1,11618,566,566,566
BEGIN DESCRIPTION:
RAY BRANCH 19.0
END DESCRIPTION:
XS GIS Cut Line= 3
      2861488.14      6986558.81      2862120.10      6986044.91
      2862696.48      6985482.42
#Sta/Elev= 30
  4082.8  422.90  4111.8  423.28  4154.9  422.02  4190.1  422.18  4196.5  421.32
  4282.8  419.53  4303.6  418.06  4361.0  416.99  4503.3  411.67  4567.2  407.39
  4648.5  404.21  4689.1  402.89  4729.9  400.95  4790.9  399.21  4791.4  398.41
  4796.9  398.41  4797.4  399.21  5169.5  399.22  5176.5  402.69  5191.0  400.95
  5192.9  401.11  5226.0  402.46  5240.1  404.58  5247.3  407.53  5254.2  409.11
  5268.4  410.42  5408.0  418.07  5530.2  424.27  5636.2  431.76  5702.7  432.57
#Mann=7,-1,0
  4082.8    0.05       0  4648.5    0.16       0  4689.1    0.05       0
  4790.9   0.033       0  4797.4    0.05       0  5192.9    0.16       0
  5408.0    0.05       0
Bank Sta=4729.9,5191
Exp/Cntr=0.3,0.1

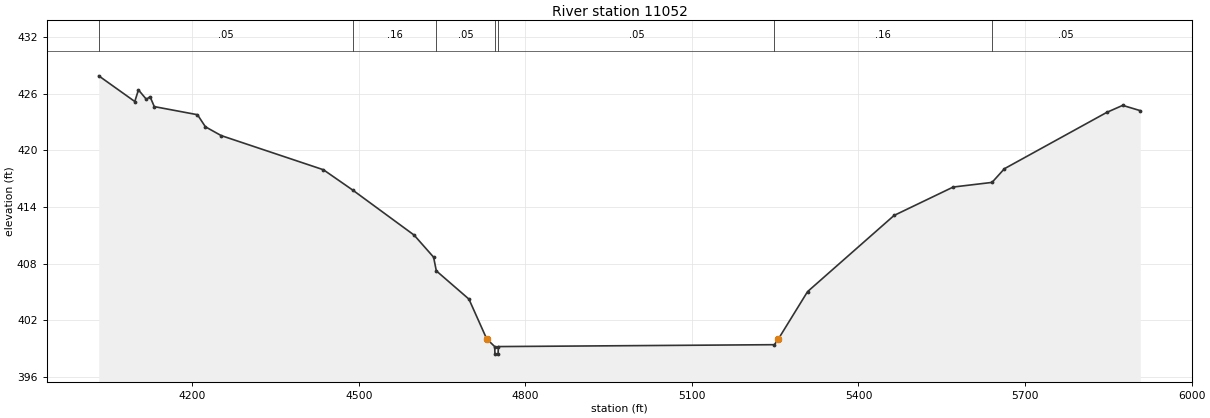
Type RM Length L Ch R = 1,11052,0,0,0
BEGIN DESCRIPTION:
RAY BRANCH 18.0
END DESCRIPTION:
XS GIS Cut Line= 3
      2861856.20      6987017.14      2862696.49      6986281.02
      2863189.53      6985704.64
#Sta/Elev= 30
  4031.9  427.89  4096.8  425.17  4103.4  426.40  4117.7  425.40  4124.3  425.68
  4131.9  424.63  4209.7  423.77  4224.0  422.49  4252.4  421.56  4436.5  417.94
  4489.2  415.79  4599.8  411.02  4634.9  408.68  4639.8  407.23  4698.5  404.24
  4730.5  400.03  4744.9  399.21  4745.4  398.41  4751.0  398.41  4751.5  399.21
  5248.6  399.41  5255.9  400.03  5308.3  405.03  5464.1  413.10  5570.6  416.11
  5640.5  416.60  5662.8  418.05  5847.2  424.02  5875.8  424.76  5907.5  424.20
#Mann=7,-1,0
  4031.9    0.05       0  4489.2    0.16       0  4639.8    0.05       0
  4744.9   0.033       0  4751.5    0.05       0  5248.6    0.16       0
  5640.5    0.05       0
Bank Sta=4730.5,5255.9
Exp/Cntr=0.3,0.1

Chan Stop Cuts=-1