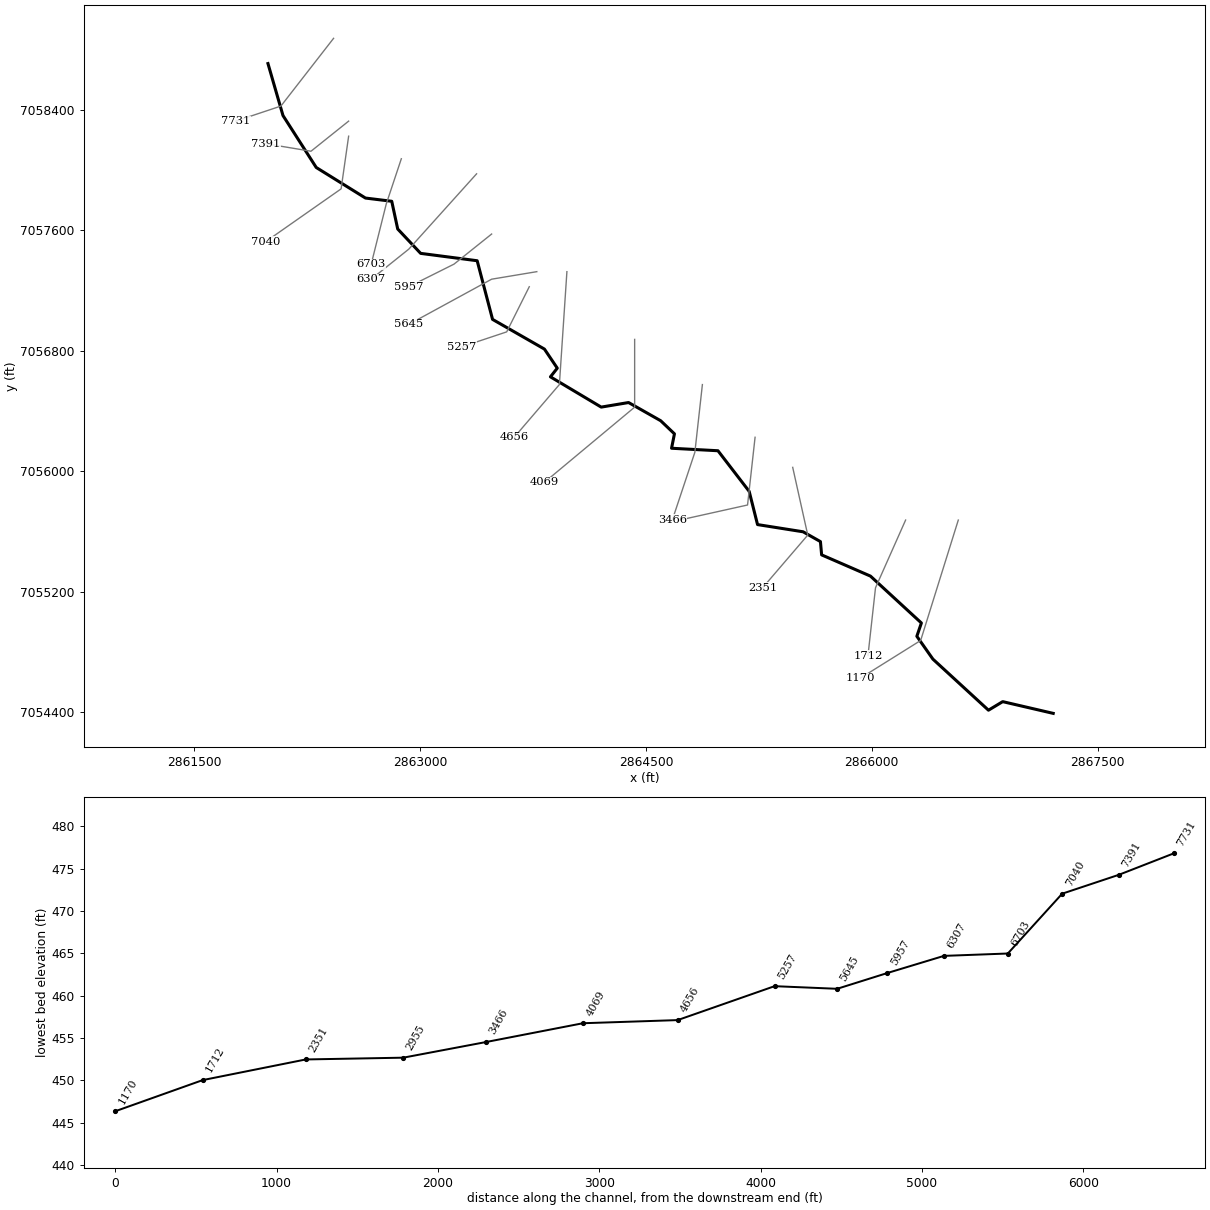
--- REPPOND BRANCH.prj (project) ---

Proj Title=REPPOND BRANCH Base Level Engineering
Current Plan=p01
Default Exp/Contr=0.3,0.1
English Units
Geom File=g01
Flow File=f01
Plan File=p01
BEGIN DESCRIPTION:
REPPOND BRANCH
END DESCRIPTION:

--- REPPOND BRANCH.p01 (plan) ---

Plan Title=Multiple Run
Short Identifier=Multiple
Geom File=g01
Flow File=f01
Subcritical Flow
K Sum by GR= 0
Std Step Tol= 0.01
Critical Tol= 0.01
Num of Std Step Trials= 20
Max Error Tol= 0.3
Flow Tol Ratio= 0.001
Split Flow NTrial= 30
Split Flow Tol= 0.02
Split Flow Ratio= 0.02
Log Output Level= 0
Friction Slope Method= 1
Unsteady Friction Slope Method= 2
Unsteady Bridges Friction Slope Method= 1
Parabolic Critical Depth
Global Vel Dist=  1 , 1 , 1
Global Log Level= 0
CheckData=True
Encroach Param= -1, 0, 0, 0
BEGIN DESCRIPTION:
Multiple Run
END DESCRIPTION:

--- REPPOND BRANCH.f01 (steady flow) ---

Flow Title=Multiple
Number of Profiles=7
Profile Names=10-year,25-year,50-year,1pct_min,100-year,1pct_plu,500-year
River Rch & RM= REPPOND BRANCH,Reach-1,7731
     645     861    1035     618    1233    2460    1747
River Rch & RM= REPPOND BRANCH,Reach-1,4656
     687     919    1108     662    1322    2637    1881
River Rch & RM= REPPOND BRANCH,Reach-1,1712
     995    1359    1660    1004    2004    3998    2921
Boundary for River Rch & Prof#=REPPOND BRANCH,Reach-1,1
Up Type=0
Dn Type=3
Dn Slope=0.005
Boundary for River Rch & Prof#=REPPOND BRANCH,Reach-1,2
Up Type=0
Dn Type=3
Dn Slope=0.005
Boundary for River Rch & Prof#=REPPOND BRANCH,Reach-1,3
Up Type=0
Dn Type=3
Dn Slope=0.005
Boundary for River Rch & Prof#=REPPOND BRANCH,Reach-1,4
Up Type=0
Dn Type=3
Dn Slope=0.005
Boundary for River Rch & Prof#=REPPOND BRANCH,Reach-1,5
Up Type=0
Dn Type=3
Dn Slope=0.005
Boundary for River Rch & Prof#=REPPOND BRANCH,Reach-1,6
Up Type=0
Dn Type=3
Dn Slope=0.005
Boundary for River Rch & Prof#=REPPOND BRANCH,Reach-1,7
Up Type=0
Dn Type=3
Dn Slope=0.005

--- REPPOND BRANCH.g01 (geometry) ---

Geom Title=Existing Conditions

River Reach=REPPOND BRANCH,Reach-1
Reach XY= 30
      2861989.06      7058707.43      2862088.91      7058362.08
      2862309.76      7058017.05      2862636.94      7057813.96
      2862811.35      7057792.61      2862850.99      7057608.49
      2863003.40      7057446.49      2863378.83      7057397.61
      2863481.09      7057007.99      2863825.66      7056810.71
      2863911.07      7056683.89      2863865.60      7056626.34
      2864202.80      7056425.26      2864384.70      7056455.64
      2864597.88      7056334.78      2864689.34      7056247.72
      2864670.21      7056151.96      2864978.42      7056135.39
      2865185.80      7055865.62      2865241.35      7055644.85
      2865543.94      7055597.03      2865659.18      7055531.80
      2865667.15      7055443.61      2865991.52      7055302.58
      2866329.74      7054991.24      2866299.65      7054902.86
      2866406.35      7054751.06      2866775.45      7054411.83
      2866869.99      7054468.70      2867205.59      7054390.71

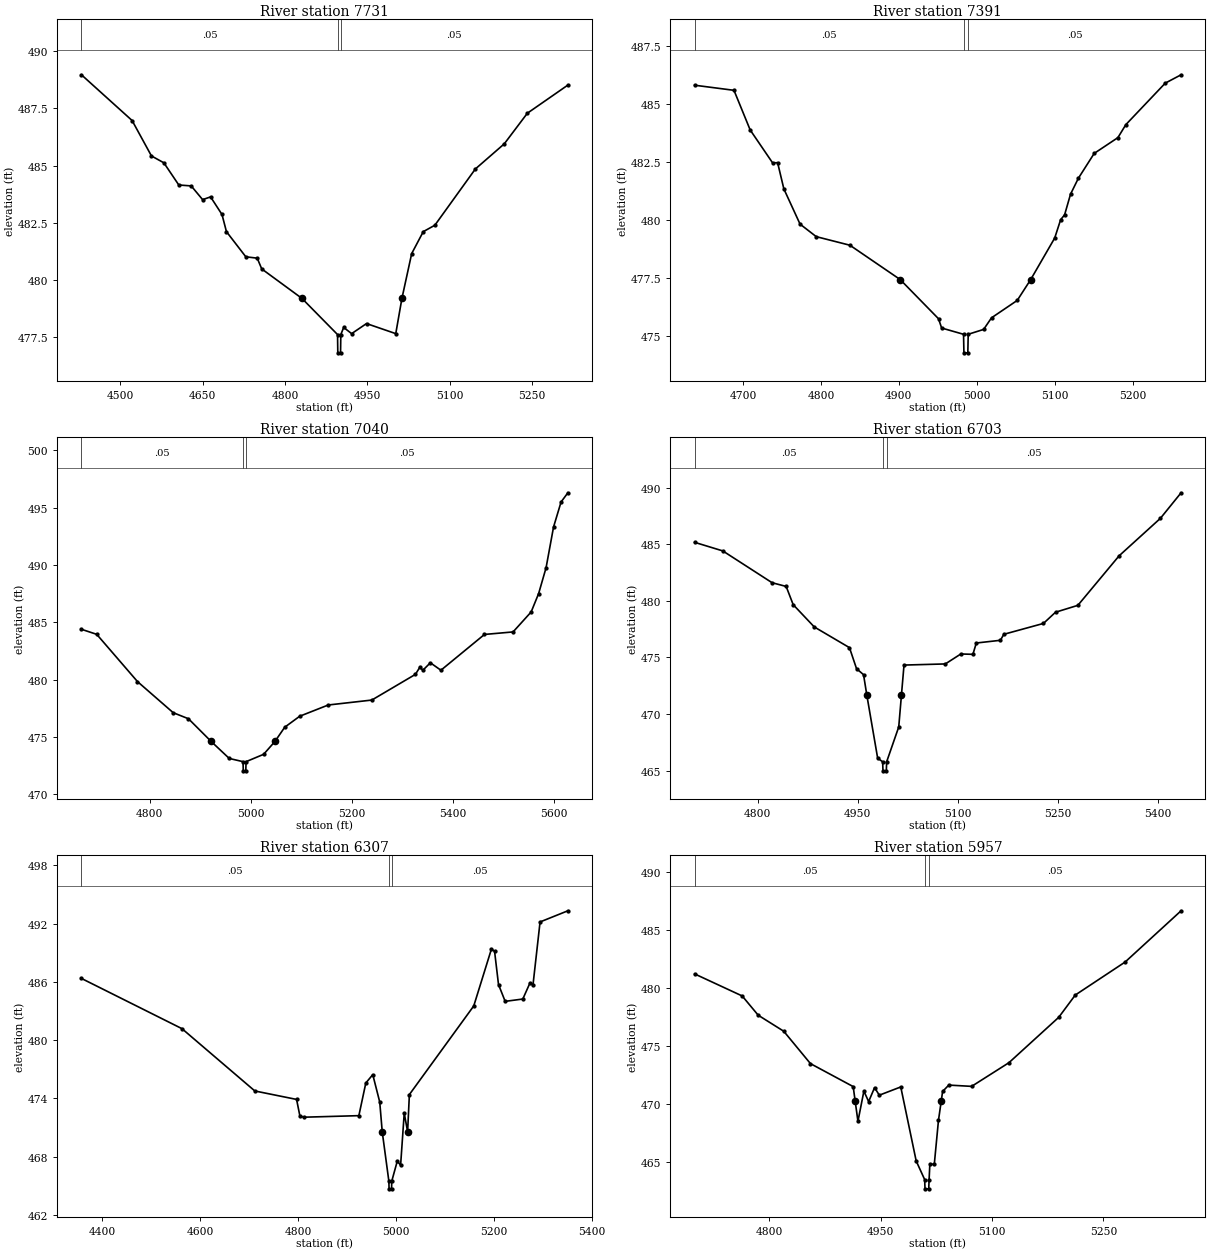
Type RM Length L Ch R = 1,7731,340,340,340
BEGIN DESCRIPTION:
REPPOND BRANCH 15.0
END DESCRIPTION:
XS GIS Cut Line= 3
      2862425.00      7058875.00      2862075.00      7058425.00
      2861775.01      7058325.00
#Sta/Elev= 30
  4429.3  488.97  4521.6  486.97  4556.9  485.42  4579.5  485.12  4606.7  484.15
  4629.3  484.11  4650.1  483.51  4664.6  483.63  4685.4  482.86  4693.5  482.11
  4728.8  481.01  4749.6  480.95  4757.8  480.48  4831.1  479.19  4895.9  477.61
  4896.4  476.81  4901.4  476.81  4901.9  477.61  4907.1  477.92  4921.6  477.65
  4948.7  478.09  5002.0  477.65  5013.2  479.19  5031.0  481.15  5052.1  482.11
  5073.2  482.39  5147.0  484.85  5199.7  485.95  5241.8  487.29  5315.6  488.52
#Mann=3,-1,0
  4429.3    0.05       0  4895.9    0.03       0  4901.9    0.05       0
Bank Sta=4831.1,5013.2
Exp/Cntr=0.3,0.1

Type RM Length L Ch R = 1,7391,351,351,351
BEGIN DESCRIPTION:
REPPOND BRANCH 14.0
END DESCRIPTION:
XS GIS Cut Line= 3
      2862525.02      7058325.02      2862275.00      7058125.00
      2861975.02      7058175.00
#Sta/Elev= 30
  4637.9  485.82  4688.4  485.60  4709.2  483.89  4738.0  482.47  4744.4  482.48
  4752.4  481.35  4773.2  479.83  4794.0  479.29  4837.2  478.92  4901.7  477.44
  4950.9  475.75  4954.9  475.35  4983.0  475.08  4983.5  474.28  4988.5  474.28
  4989.0  475.08  5008.8  475.29  5018.9  475.79  5051.9  476.54  5069.2  477.44
  5100.0  479.23  5107.6  480.02  5112.7  480.23  5120.3  481.12  5130.4  481.81
  5150.7  482.88  5181.1  483.56  5191.3  484.12  5241.9  485.91  5262.2  486.27
#Mann=3,-1,0
  4637.9    0.05       0  4983.0    0.03       0  4989.0    0.05       0
Bank Sta=4901.7,5069.2
Exp/Cntr=0.3,0.1

Type RM Length L Ch R = 1,7040,337,337,337
BEGIN DESCRIPTION:
REPPOND BRANCH 13.0
END DESCRIPTION:
XS GIS Cut Line= 3
      2862525.00      7058224.99      2862475.00      7057875.00
      2861974.98      7057524.98
#Sta/Elev= 30
  4664.5  484.39  4694.8  483.95  4775.6  479.83  4846.3  477.12  4876.6  476.59
  4921.6  474.61  4957.4  473.13  4984.7  472.85  4985.2  472.05  4990.2  472.05
  4990.7  472.85  5025.5  473.49  5047.9  474.61  5067.3  475.85  5097.0  476.81
  5153.6  477.79  5239.9  478.22  5326.3  480.46  5335.0  481.08  5341.1  480.82
  5355.9  481.47  5376.8  480.82  5463.1  483.94  5519.8  484.16  5555.6  485.90
  5570.4  487.50  5585.2  489.76  5600.0  493.31  5614.9  495.49  5628.4  496.29
#Mann=3,-1,0
  4664.5    0.05       0  4984.7    0.03       0  4990.7    0.05       0
Bank Sta=4921.6,5047.9
Exp/Cntr=0.3,0.1

Type RM Length L Ch R = 1,6703,396,396,396
BEGIN DESCRIPTION:
REPPOND BRANCH 12.0
END DESCRIPTION:
XS GIS Cut Line= 3
      2862875.01      7058075.03      2862775.00      7057775.00
      2862674.99      7057374.97
#Sta/Elev= 30
  4705.8  485.18  4748.0  484.42  4821.8  481.61  4842.9  481.28  4853.4  479.67
  4885.0  477.70  4937.7  475.87  4948.3  474.01  4958.8  473.48  4963.8  471.64
  4979.9  466.11  4987.4  465.78  4987.9  464.98  4992.9  464.98  4993.4  465.78
  5011.5  468.86  5015.5  471.64  5019.4  474.33  5081.3  474.43  5104.5  475.31
  5122.6  475.28  5127.7  476.28  5163.8  476.52  5168.9  477.05  5228.2  478.01
  5246.3  479.00  5279.8  479.61  5341.6  483.99  5403.4  487.30  5434.4  489.56
#Mann=3,-1,0
  4705.8    0.05       0  4987.4    0.03       0  4993.4    0.05       0
Bank Sta=4963.8,5015.5
Exp/Cntr=0.3,0.1

Type RM Length L Ch R = 1,6307,350,350,350
BEGIN DESCRIPTION:
REPPOND BRANCH 11.0
END DESCRIPTION:
XS GIS Cut Line= 3
      2863374.99      7057974.99      2862925.00      7057475.00
      2862675.02      7057275.02
#Sta/Elev= 30
  4358.0  486.35  4563.2  481.18  4711.9  474.77  4797.1  473.90  4803.8  472.21
  4811.3  472.07  4924.2  472.23  4938.4  475.59  4952.6  476.45  4966.8  473.63
  4971.9  470.57  4985.4  465.50  4985.9  464.70  4990.9  464.70  4991.4  465.50
  5002.6  467.55  5009.4  467.13  5016.8  472.49  5023.7  470.57  5027.3  474.40
  5158.7  483.52  5194.8  489.38  5201.2  489.13  5209.2  485.72  5222.8  483.99
  5258.8  484.23  5273.2  485.86  5279.6  485.69  5294.0  492.16  5350.8  493.31
#Mann=3,-1,0
  4358.0    0.05       0  4985.4    0.03       0  4991.4    0.05       0
Bank Sta=4971.9,5023.7
Exp/Cntr=0.3,0.1

Type RM Length L Ch R = 1,5957,312,312,312
BEGIN DESCRIPTION:
REPPOND BRANCH 10.0
END DESCRIPTION:
XS GIS Cut Line= 3
      2863475.02      7057575.01      2863225.00      7057375.00
      2862924.99      7057224.99
#Sta/Elev= 30
  4699.2  481.20  4763.3  479.30  4784.9  477.64  4819.3  476.26  4855.3  473.47
  4912.9  471.49  4915.6  470.22  4919.3  468.50  4927.3  471.10  4933.7  470.20
  4941.7  471.40  4948.1  470.75  4977.0  471.46  4997.8  465.08  5009.2  463.48
  5009.7  462.68  5014.7  462.68  5015.2  463.48  5016.2  464.80  5022.2  464.80
  5027.8  468.57  5031.5  470.22  5033.4  471.07  5041.7  471.62  5072.5  471.51
  5122.8  473.55  5189.9  477.46  5212.2  479.38  5279.3  482.22  5354.8  486.64
#Mann=3,-1,0
  4699.2    0.05       0  5009.2    0.03       0  5015.2    0.05       0
Bank Sta=4915.6,5031.5
Exp/Cntr=0.3,0.1

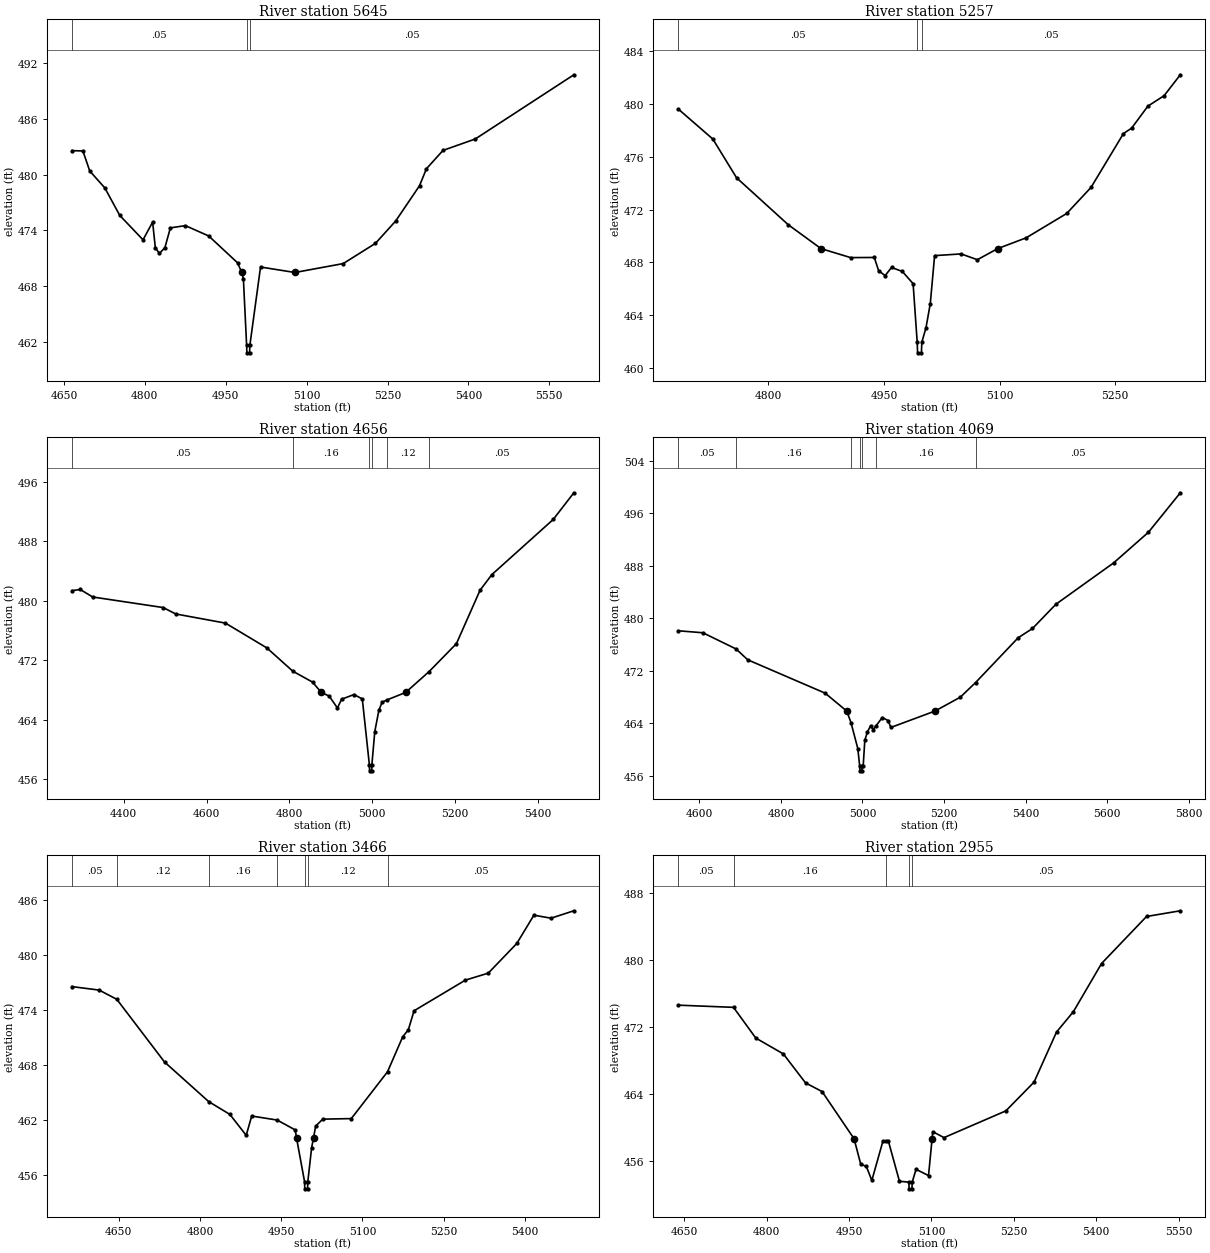
Type RM Length L Ch R = 1,5645,388,388,388
BEGIN DESCRIPTION:
REPPOND BRANCH 9.0
END DESCRIPTION:
XS GIS Cut Line= 3
      2863775.03      7057325.00      2863475.00      7057275.00
      2862924.97      7056974.98
#Sta/Elev= 30
  4664.8  482.60  4685.1  482.57  4697.8  480.41  4725.7  478.59  4753.5  475.62
  4796.6  472.99  4814.4  474.90  4819.4  472.15  4827.0  471.52  4837.2  472.15
  4847.3  474.28  4875.2  474.52  4918.3  473.41  4971.8  470.52  4979.7  469.47
  4982.7  468.80  4988.7  461.61  4989.2  460.81  4994.2  460.81  4994.7  461.61
  5014.5  470.06  5078.3  469.47  5167.8  470.43  5227.6  472.61  5265.1  475.02
  5309.3  478.82  5322.1  480.65  5352.9  482.63  5412.7  483.86  5595.5  490.78
#Mann=3,-1,0
  4664.8    0.05       0  4988.7    0.03       0  4994.7    0.05       0
Bank Sta=4979.7,5078.3
Exp/Cntr=0.3,0.1

Type RM Length L Ch R = 1,5257,601,601,601
BEGIN DESCRIPTION:
REPPOND BRANCH 8.0
END DESCRIPTION:
XS GIS Cut Line= 3
      2863725.00      7057224.99      2863575.00      7056925.00
      2863275.03      7056825.01
#Sta/Elev= 30
  4683.1  479.62  4727.8  477.35  4758.6  474.41  4825.6  470.85  4868.3  469.03
  4906.7  468.35  4937.4  468.36  4943.0  467.36  4951.4  466.98  4959.8  467.60
  4973.8  467.30  4987.8  466.37  4993.1  461.92  4993.6  461.12  4998.6  461.12
  4999.1  461.92  5004.5  463.02  5010.1  464.86  5015.7  468.50  5050.1  468.63
  5071.2  468.19  5097.5  469.03  5134.5  469.85  5187.2  471.70  5218.8  473.68
  5260.9  477.77  5271.5  478.18  5292.6  479.85  5313.6  480.64  5334.7  482.23
#Mann=3,-1,0
  4683.1    0.05       0  4993.1    0.03       0  4999.1    0.05       0
Bank Sta=4868.3,5097.5
Exp/Cntr=0.3,0.1

Type RM Length L Ch R = 1,4656,587,587,587
BEGIN DESCRIPTION:
REPPOND BRANCH 7.0
END DESCRIPTION:
XS GIS Cut Line= 3
      2863975.00      7057325.00      2863925.00      7056575.00
      2863625.02      7056225.03
#Sta/Elev= 30
  4274.8  481.33  4294.8  481.49  4324.9  480.48  4495.3  479.06  4525.4  478.20
  4645.6  476.97  4745.8  473.63  4808.5  470.50  4856.1  469.04  4877.2  467.65
  4896.2  467.16  4916.2  465.56  4926.2  466.73  4956.3  467.37  4976.3  466.77
  4993.4  457.91  4993.9  457.11  4998.9  457.11  4999.4  457.91  5006.4  462.37
  5016.4  465.27  5024.0  466.32  5035.4  466.63  5081.1  467.65  5137.6  470.45
  5203.7  474.21  5260.8  481.39  5289.3  483.49  5437.5  490.90  5487.4  494.49
#Mann=6,-1,0
  4274.8    0.05       0  4808.5    0.16       0  4993.4    0.07       0
  4999.4    0.16       0  5035.4    0.12       0  5137.6    0.05       0
Bank Sta=4877.2,5081.1
Exp/Cntr=0.3,0.1

Type RM Length L Ch R = 1,4069,603,603,603
BEGIN DESCRIPTION:
REPPOND BRANCH 6.0
END DESCRIPTION:
XS GIS Cut Line= 3
      2864425.00      7056875.03      2864425.00      7056425.00
      2863824.97      7055924.97
#Sta/Elev= 30
  4548.6  478.09  4608.6  477.79  4690.0  475.32  4718.6  473.67  4908.6  468.58
  4961.5  465.85  4971.9  464.09  4988.6  460.14  4993.1  457.54  4993.6  456.74
  4998.6  456.74  4999.1  457.54  5001.9  457.54  5005.8  461.41  5012.3  462.69
  5020.1  463.62  5026.6  463.01  5032.9  463.57  5048.7  464.87  5063.1  464.40
  5069.6  463.35  5177.8  465.85  5240.1  467.97  5277.4  470.19  5382.0  477.03
  5417.1  478.44  5474.4  482.13  5616.3  488.45  5701.6  493.12  5779.7  499.13
#Mann=7,-1,0
  4548.6    0.05       0  4690.0    0.16       0  4971.9    0.12       0
  4993.1    0.07       0  4999.1    0.12       0  5032.9    0.16       0
  5277.4    0.05       0
Bank Sta=4961.5,5177.8
Exp/Cntr=0.3,0.1

Type RM Length L Ch R = 1,3466,511,511,511
BEGIN DESCRIPTION:
REPPOND BRANCH 5.0
END DESCRIPTION:
XS GIS Cut Line= 3
      2864875.00      7056574.98      2864825.00      7056125.00
      2864675.00      7055674.99
#Sta/Elev= 30
  4563.5  476.59  4613.8  476.21  4646.4  475.20  4734.5  468.36  4816.0  464.04
  4855.3  462.63  4885.4  460.35  4895.5  462.46  4942.5  462.02  4976.0  460.94
  4978.3  460.08  4993.1  455.31  4993.6  454.51  4998.7  454.51  4999.2  455.31
  5006.2  458.99  5009.7  460.08  5013.7  461.36  5026.8  462.12  5079.5  462.18
  5146.4  467.29  5174.4  471.10  5184.9  471.88  5195.4  473.95  5290.3  477.30
  5332.5  478.06  5385.2  481.30  5416.8  484.39  5448.4  484.06  5490.6  484.87
#Mann=7,-1,0
  4563.5    0.05       0  4646.4    0.12       0  4816.0    0.16       0
  4942.5    0.12       0  4993.1    0.07       0  4999.2    0.12       0
  5146.4    0.05       0
Bank Sta=4978.3,5009.7
Exp/Cntr=0.3,0.1

Type RM Length L Ch R = 1,2955,604,604,604
BEGIN DESCRIPTION:
REPPOND BRANCH 4.0
END DESCRIPTION:
XS GIS Cut Line= 3
      2865225.00      7056224.96      2865175.00      7055775.00
      2864725.00      7055675.00
#Sta/Elev= 30
  4639.3  474.58  4739.6  474.32  4780.1  470.66  4830.4  468.76  4870.7  465.31
  4900.9  464.27  4959.1  458.64  4971.3  455.58  4981.3  455.36  4991.4  453.67
  5011.5  458.34  5017.0  458.35  5021.6  458.35  5041.7  453.57  5058.8  453.47
  5059.3  452.67  5064.4  452.67  5064.9  453.47  5071.9  455.00  5094.6  454.25
  5101.1  458.64  5102.3  459.49  5122.8  458.78  5235.4  461.97  5286.7  465.40
  5327.6  471.37  5358.4  473.81  5409.6  479.55  5491.5  485.16  5553.0  485.84
#Mann=5,-1,0
  4639.3    0.05       0  4739.6    0.16       0  5017.0    0.05       0
  5058.8    0.07       0  5064.9    0.05       0
Bank Sta=4959.1,5101.1
Exp/Cntr=0.3,0.1

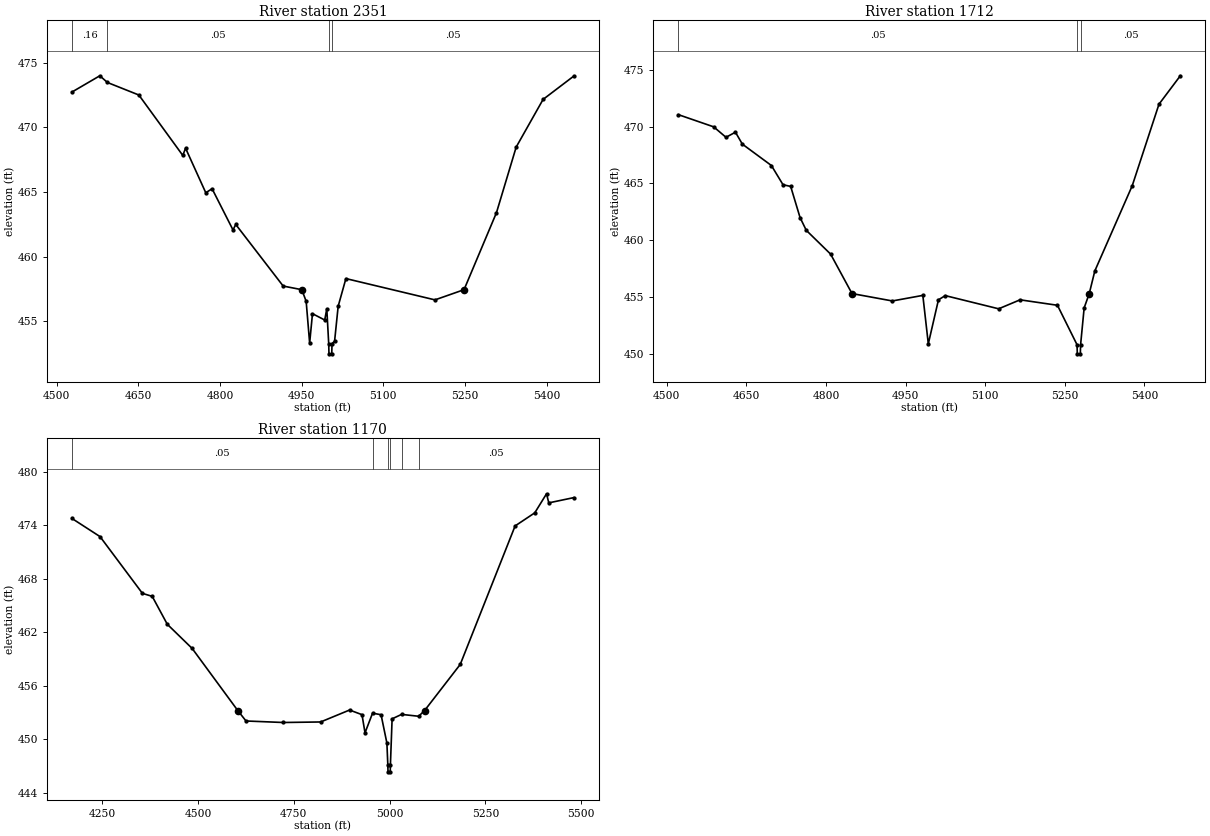
Type RM Length L Ch R = 1,2351,639,639,639
BEGIN DESCRIPTION:
REPPOND BRANCH 3.0
END DESCRIPTION:
XS GIS Cut Line= 3
      2865475.00      7056024.99      2865575.00      7055575.00
      2865275.03      7055225.03
#Sta/Elev= 30
  4528.2  472.74  4579.4  474.00  4593.4  473.48  4651.1  472.51  4731.8  467.83
  4736.9  468.39  4774.0  464.94  4785.6  465.25  4824.0  462.06  4829.1  462.48
  4916.2  457.71  4950.4  457.43  4958.4  456.53  4964.8  453.29  4970.0  455.57
  4992.5  455.08  4996.3  455.95  4999.8  453.26  5000.3  452.46  5005.4  452.46
  5005.9  453.26  5010.6  453.43  5017.2  456.15  5031.4  458.29  5195.0  456.64
  5248.4  457.43  5308.0  463.40  5344.2  468.48  5393.6  472.17  5450.1  473.98
#Mann=4,-1,0
  4528.2    0.16       0  4593.4    0.05       0  4999.8    0.03       0
  5005.9    0.05       0
Bank Sta=4950.4,5248.4
Exp/Cntr=0.3,0.1

Type RM Length L Ch R = 1,1712,542,542,542
BEGIN DESCRIPTION:
REPPOND BRANCH 2.0
END DESCRIPTION:
XS GIS Cut Line= 3
      2866225.01      7055675.02      2866025.00      7055225.00
      2865975.00      7054775.03
#Sta/Elev= 30
  4522.3  471.05  4588.7  469.98  4611.9  469.06  4629.7  469.51  4642.7  468.46
  4697.4  466.58  4719.3  464.89  4733.7  464.74  4751.4  462.00  4763.1  460.88
  4808.9  458.79  4849.2  455.32  4925.2  454.67  4982.6  455.16  4992.9  450.90
  5012.0  454.77  5024.8  455.14  5125.4  453.98  5165.7  454.77  5236.1  454.29
  5273.0  450.82  5273.5  450.02  5279.2  450.02  5279.7  450.82  5286.4  454.06
  5296.0  455.32  5306.5  457.31  5377.0  464.81  5427.3  471.97  5467.5  474.47
#Mann=3,-1,0
  4522.3    0.05       0  5273.0    0.03       0  5279.7    0.05       0
Bank Sta=4849.2,5296
Exp/Cntr=0.3,0.1

Type RM Length L Ch R = 1,1170,0,0,0
BEGIN DESCRIPTION:
REPPOND BRANCH 1.0
END DESCRIPTION:
XS GIS Cut Line= 3
      2866575.00      7055674.99      2866325.00      7054875.00
      2865925.04      7054625.02
#Sta/Elev= 30
  4171.1  474.79  4244.4  472.75  4355.0  466.38  4380.6  466.04  4419.9  462.91
  4484.9  460.19  4603.9  453.22  4625.3  452.05  4722.7  451.88  4820.1  451.94
  4895.6  453.28  4928.0  452.76  4935.9  450.72  4955.6  452.93  4977.8  452.75
  4993.0  449.57  4995.4  447.14  4995.9  446.34  5001.7  446.34  5002.2  447.14
  5006.6  452.29  5031.3  452.79  5075.9  452.58  5091.3  453.22  5184.4  458.40
  5327.6  473.95  5378.9  475.42  5409.6  477.56  5415.5  476.54  5480.9  477.13
#Mann=6,-1,0
  4171.1    0.05       0  4955.6    0.12       0  4995.4    0.07       0
  5002.2    0.12       0  5031.3    0.07       0  5075.9    0.05       0
Bank Sta=4603.9,5091.3
Exp/Cntr=0.3,0.1

Chan Stop Cuts=-1