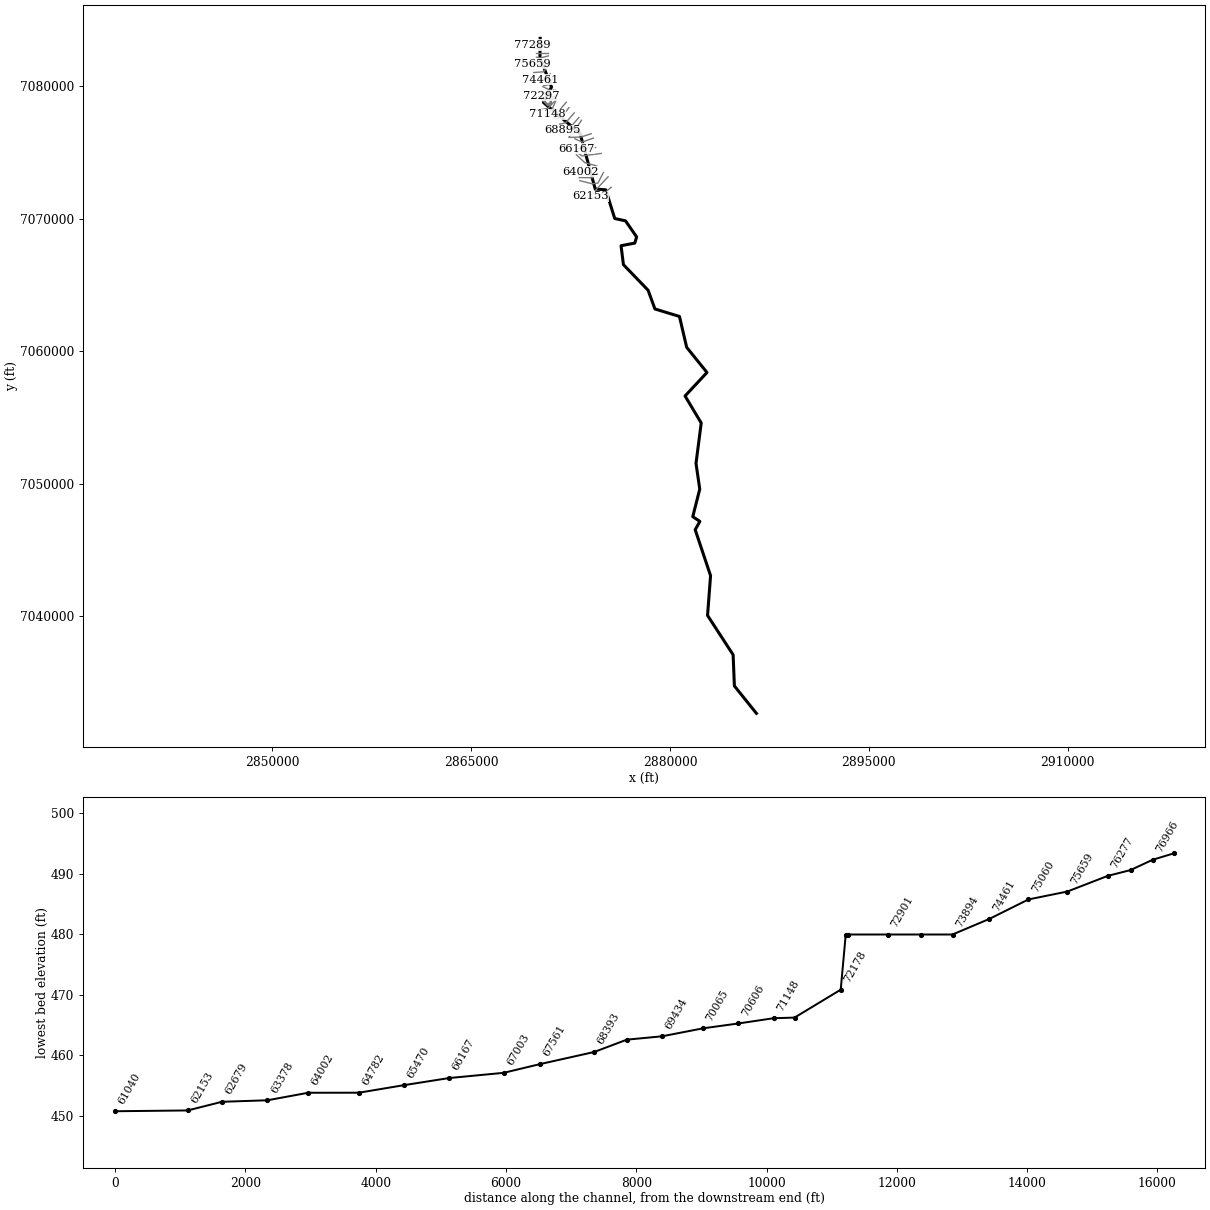
--- RUNNING CREEK.prj (project) ---

Proj Title=RUNNING CREEK Base Level Engineering
Current Plan=p01
Default Exp/Contr=0.3,0.1
English Units
Geom File=g01
Flow File=f01
Plan File=p01
BEGIN DESCRIPTION:
RUNNING CREEK
END DESCRIPTION:

--- RUNNING CREEK.p01 (plan) ---

Plan Title=Multiple Run
Short Identifier=Multiple
Geom File=g01
Flow File=f01
Subcritical Flow
K Sum by GR= 0
Std Step Tol= 0.01
Critical Tol= 0.01
Num of Std Step Trials= 20
Max Error Tol= 0.3
Flow Tol Ratio= 0.001
Split Flow NTrial= 30
Split Flow Tol= 0.02
Split Flow Ratio= 0.02
Log Output Level= 0
Friction Slope Method= 1
Unsteady Friction Slope Method= 2
Unsteady Bridges Friction Slope Method= 1
Parabolic Critical Depth
Global Vel Dist=  1 , 1 , 1
Global Log Level= 0
CheckData=True
Encroach Param= -1, 0, 0, 0
BEGIN DESCRIPTION:
Multiple Run
END DESCRIPTION:

--- RUNNING CREEK.f01 (steady flow) ---

Flow Title=Multiple
Number of Profiles=7
Profile Names=10-year,25-year,50-year,1pct_min,100-year,1pct_plu,500-year
River Rch & RM= RUNNING CREEK,Reach-1,77289
     810    1092    1323     795    1586    3165    2273
River Rch & RM= RUNNING CREEK,Reach-1,75659
    1073    1468    1794    1086    2168    4325    3157
River Rch & RM= RUNNING CREEK,Reach-1,71469
    2090    2952    3685    2273    4535    9049    6860
River Rch & RM= RUNNING CREEK,Reach-1,67561
    2779    3968    4990    3098    6181   12333    9473
River Rch & RM= RUNNING CREEK,Reach-1,64002
    2973    4241    5329    3303    6591   13150   10071
River Rch & RM= RUNNING CREEK,Reach-1,56766
    2918    4149    5202    3217    6418   12806    9761
River Rch & RM= RUNNING CREEK,Reach-1,51064
    3807    5466    6897    4289    8558   17076   13165
River Rch & RM= RUNNING CREEK,Reach-1,46269
    5490    7974   10142    6351   12673   25286   19764
River Rch & RM= RUNNING CREEK,Reach-1,39012
    5725    8325   10596    6640   13249   26436   20693
River Rch & RM= RUNNING CREEK,Reach-1,37990
    5620    8129   10310    6437   12844   25626   19912
River Rch & RM= RUNNING CREEK,Reach-1,25648
    5641    8143   10313    6431   12831   25600   19845
River Rch & RM= RUNNING CREEK,Reach-1,17382
    5777    8334   10552    6577   13123   26184   20290
River Rch & RM= RUNNING CREEK,Reach-1,11535
    5699    8187   10336    6424   12819   25576   19709
Boundary for River Rch & Prof#=RUNNING CREEK,Reach-1,1
Up Type=0
Dn Type=3
Dn Slope=0.005
Boundary for River Rch & Prof#=RUNNING CREEK,Reach-1,2
Up Type=0
Dn Type=3
Dn Slope=0.005
Boundary for River Rch & Prof#=RUNNING CREEK,Reach-1,3
Up Type=0
Dn Type=3
Dn Slope=0.005
Boundary for River Rch & Prof#=RUNNING CREEK,Reach-1,4
Up Type=0
Dn Type=3
Dn Slope=0.005
Boundary for River Rch & Prof#=RUNNING CREEK,Reach-1,5
Up Type=0
Dn Type=3
Dn Slope=0.005
Boundary for River Rch & Prof#=RUNNING CREEK,Reach-1,6
Up Type=0
Dn Type=3
Dn Slope=0.005
Boundary for River Rch & Prof#=RUNNING CREEK,Reach-1,7
Up Type=0
Dn Type=3
Dn Slope=0.005

--- RUNNING CREEK.g01 (geometry) ---

Geom Title=Existing Conditions

River Reach=RUNNING CREEK,Reach-1
Reach XY= 30
      2870205.80      7083600.63      2870188.57      7082141.87
      2871060.91      7079928.26      2870457.02      7078759.86
      2873218.18      7076417.37      2874357.71      7072236.43
      2875155.59      7072170.71      2875831.01      7070007.93
      2876645.65      7069830.52      2877482.86      7068619.42
      2877343.18      7068154.15      2876307.55      7067955.36
      2876487.11      7066526.98      2878347.95      7064598.20
      2878862.79      7063185.14      2880713.86      7062620.21
      2881257.73      7060291.39      2882789.91      7058393.06
      2881136.86      7056620.45      2882355.22      7054582.21
      2881961.80      7051538.30      2882244.71      7049592.43
      2881717.80      7047515.72      2882254.43      7047159.43
      2881899.92      7046530.85      2883060.07      7043064.28
      2882833.08      7040064.24      2884762.49      7037094.45
      2884857.07      7034745.11      2886520.40      7032675.91

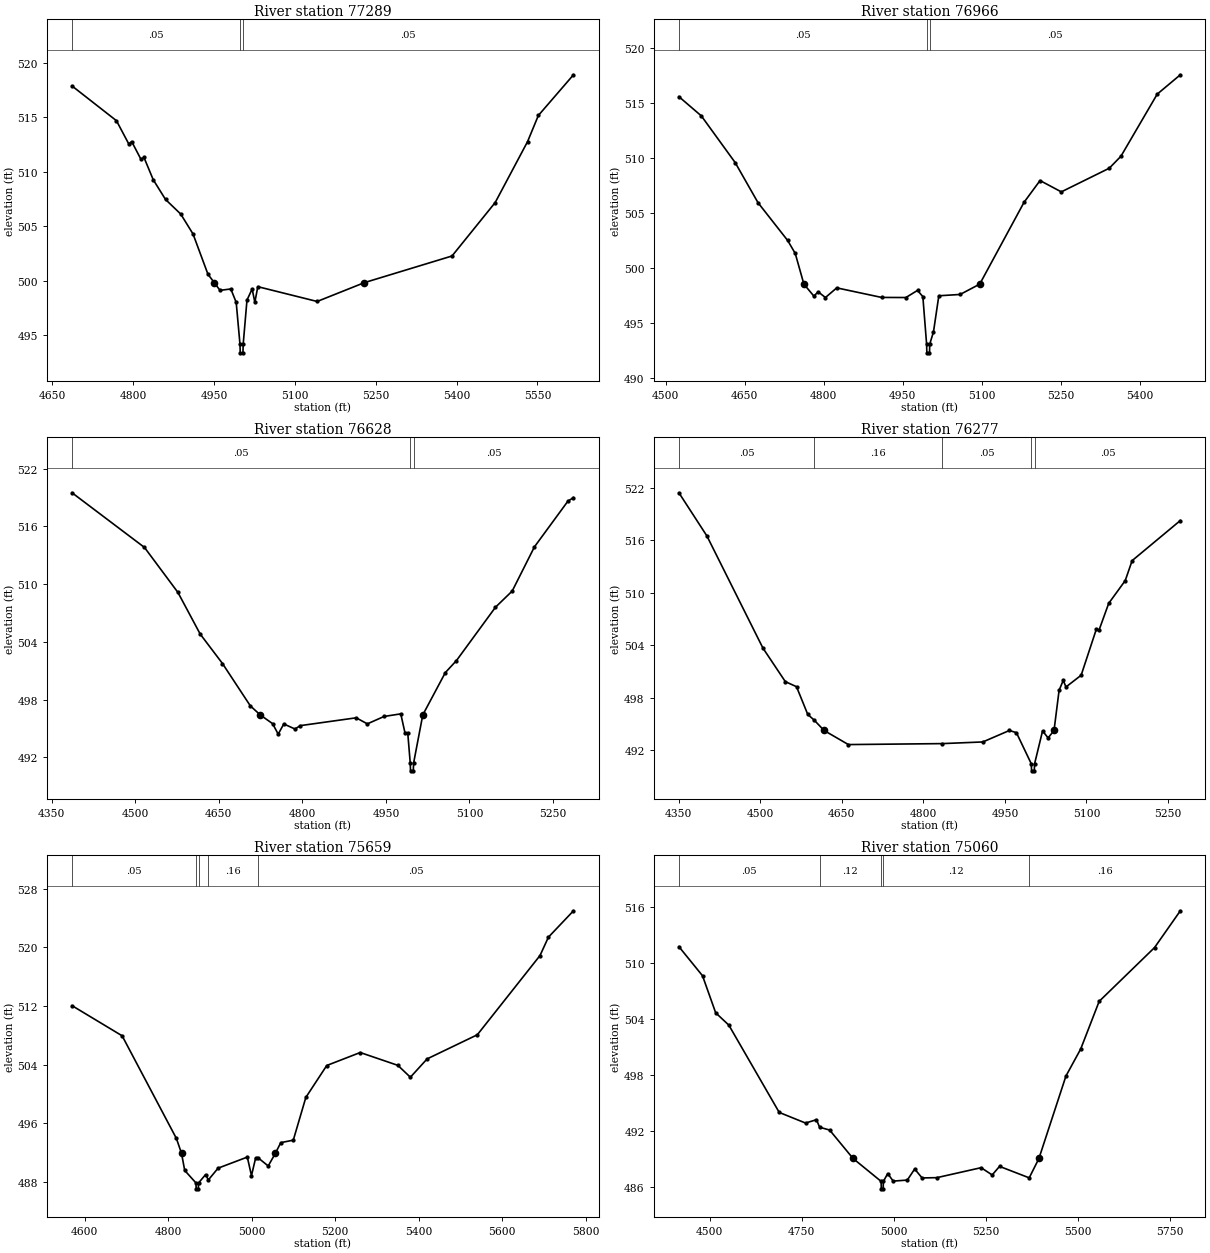
Type RM Length L Ch R = 1,77289,323,323,323
BEGIN DESCRIPTION:
RUNNING CREEK 79.0
END DESCRIPTION:
XS GIS Cut Line= 3
      2870525.02      7083175.01      2870294.10      7083065.79
      2869619.91      7083099.94
#Sta/Elev= 30
  4686.5  517.88  4768.9  514.69  4791.7  512.56  4797.2  512.77  4814.4  511.14
  4820.0  511.31  4837.2  509.26  4860.0  507.45  4888.2  506.11  4911.0  504.28
  4938.7  500.58  4950.4  499.81  4961.1  499.10  4981.1  499.23  4991.1  498.00
  4998.1  494.16  4998.6  493.36  5003.6  493.36  5004.1  494.16  5011.1  498.21
  5020.7  499.22  5025.7  498.01  5031.2  499.44  5141.3  498.08  5228.9  499.81
  5391.6  502.26  5471.7  507.17  5531.8  512.77  5551.8  515.17  5617.0  518.91
#Mann=3,-1,0
  4686.5    0.05       0  4998.1    0.03       0  5004.1    0.05       0
Bank Sta=4950.4,5228.9
Exp/Cntr=0.3,0.1

Type RM Length L Ch R = 1,76966,338,338,338
BEGIN DESCRIPTION:
RUNNING CREEK 78.0
END DESCRIPTION:
XS GIS Cut Line= 3
      2870525.01      7083025.01      2870213.60      7082783.97
      2869661.56      7082867.30
#Sta/Elev= 30
  4524.8  515.61  4567.4  513.86  4631.7  509.61  4675.1  505.96  4731.3  502.53
  4745.7  501.35  4762.1  498.56  4781.1  497.47  4789.2  497.86  4803.0  497.34
  4824.5  498.22  4909.6  497.35  4955.8  497.34  4977.9  497.99  4988.0  497.42
  4995.1  493.11  4995.6  492.31  5000.6  492.31  5001.1  493.11  5008.2  494.22
  5018.3  497.50  5058.8  497.62  5096.0  498.56  5180.1  506.00  5210.5  507.98
  5250.9  506.95  5341.9  509.10  5364.1  510.19  5433.0  515.84  5476.9  517.60
#Mann=3,-1,0
  4524.8    0.05       0  4995.1    0.03       0  5001.1    0.05       0
Bank Sta=4762.1,5096
Exp/Cntr=0.3,0.1

Type RM Length L Ch R = 1,76628,351,351,351
BEGIN DESCRIPTION:
RUNNING CREEK 77.0
END DESCRIPTION:
XS GIS Cut Line= 3
      2870775.00      7082475.00      2870175.00      7082475.00
      2869875.00      7082475.00
#Sta/Elev= 30
  4386.7  519.50  4516.7  513.82  4576.7  509.15  4616.7  504.82  4656.7  501.76
  4706.7  497.36  4724.5  496.42  4746.7  495.51  4756.7  494.42  4766.7  495.48
  4786.7  494.96  4796.7  495.31  4896.7  496.12  4916.7  495.49  4946.7  496.26
  4976.7  496.53  4984.2  494.57  4989.2  494.57  4993.7  491.41  4994.2  490.61
  4999.2  490.61  4999.7  491.41  5016.2  496.42  5056.7  500.82  5076.7  502.07
  5146.7  507.61  5176.7  509.29  5216.7  513.89  5276.7  518.63  5286.7  519.00
#Mann=3,-1,0
  4386.7    0.05       0  4993.7    0.03       0  4999.7    0.05       0
Bank Sta=4724.5,5016.2
Exp/Cntr=0.3,0.1

Type RM Length L Ch R = 1,76277,618,618,618
BEGIN DESCRIPTION:
RUNNING CREEK 76.0
END DESCRIPTION:
XS GIS Cut Line= 3
      2870824.97      7082274.99      2870225.00      7082125.00
      2869924.98      7082175.00
#Sta/Elev= 30
  4350.2  521.41  4401.7  516.48  4504.8  503.67  4546.0  499.84  4566.6  499.26
  4587.3  496.09  4599.0  495.45  4617.3  494.26  4662.0  492.65  4834.6  492.76
  4909.4  492.95  4958.3  494.26  4971.2  494.01  4998.6  490.45  4999.1  489.65
  5004.1  489.65  5004.6  490.45  5019.3  494.21  5029.5  493.41  5040.4  494.26
  5049.7  498.84  5057.3  499.98  5062.4  499.23  5090.3  500.57  5118.2  505.82
  5123.2  505.72  5141.0  508.78  5171.4  511.38  5184.1  513.66  5272.8  518.24
#Mann=5,-1,0
  4350.2    0.05       0  4599.0    0.16       0  4834.6    0.05       0
  4998.6    0.03       0  5004.6    0.05       0
Bank Sta=4617.3,5040.4
Exp/Cntr=0.3,0.1

Type RM Length L Ch R = 1,75659,599,599,599
BEGIN DESCRIPTION:
RUNNING CREEK 75.0
END DESCRIPTION:
XS GIS Cut Line= 3
      2870825.04      7081625.00      2870375.00      7081625.00
      2869625.01      7081675.00
#Sta/Elev= 30
  4569.4  512.05  4689.4  507.94  4819.4  493.95  4831.7  491.92  4839.4  489.58
  4866.4  487.87  4866.9  487.07  4872.0  487.07  4872.5  487.87  4889.4  489.01
  4896.1  488.29  4919.4  489.89  4989.4  491.40  4999.4  488.87  5009.4  491.29
  5014.6  491.33  5039.5  490.19  5056.7  491.92  5069.6  493.37  5099.6  493.71
  5129.7  499.54  5179.8  503.89  5260.0  505.66  5350.2  503.91  5380.2  502.29
  5420.3  504.79  5540.6  508.08  5690.9  518.89  5711.0  521.39  5771.1  524.99
#Mann=5,-1,0
  4569.4    0.05       0  4866.4    0.07       0  4872.5    0.05       0
  4896.1    0.16       0  5014.6    0.05       0
Bank Sta=4831.7,5056.7
Exp/Cntr=0.3,0.1

Type RM Length L Ch R = 1,75060,599,599,599
BEGIN DESCRIPTION:
RUNNING CREEK 74.0
END DESCRIPTION:
XS GIS Cut Line= 3
      2870825.02      7081575.03      2870475.00      7081075.00
      2869725.02      7081025.00
#Sta/Elev= 30
  4416.1  511.75  4480.2  508.63  4516.0  504.65  4551.7  503.33  4688.6  493.96
  4760.1  492.82  4789.7  493.18  4798.3  492.37  4825.5  492.07  4889.1  489.02
  4965.4  486.56  4965.9  485.76  4971.0  485.76  4971.5  486.56  4983.3  487.40
  4998.1  486.59  5036.5  486.70  5056.5  487.89  5076.6  486.93  5116.7  486.96
  5236.9  488.03  5267.0  487.25  5287.0  488.17  5367.6  486.94  5394.0  489.02
  5467.4  497.87  5507.5  500.77  5557.6  505.88  5708.0  511.65  5778.1  515.60
#Mann=5,-1,0
  4416.1    0.05       0  4798.3    0.12       0  4965.4    0.07       0
  4971.5    0.12       0  5367.6    0.16       0
Bank Sta=4889.1,5394
Exp/Cntr=0.3,0.1

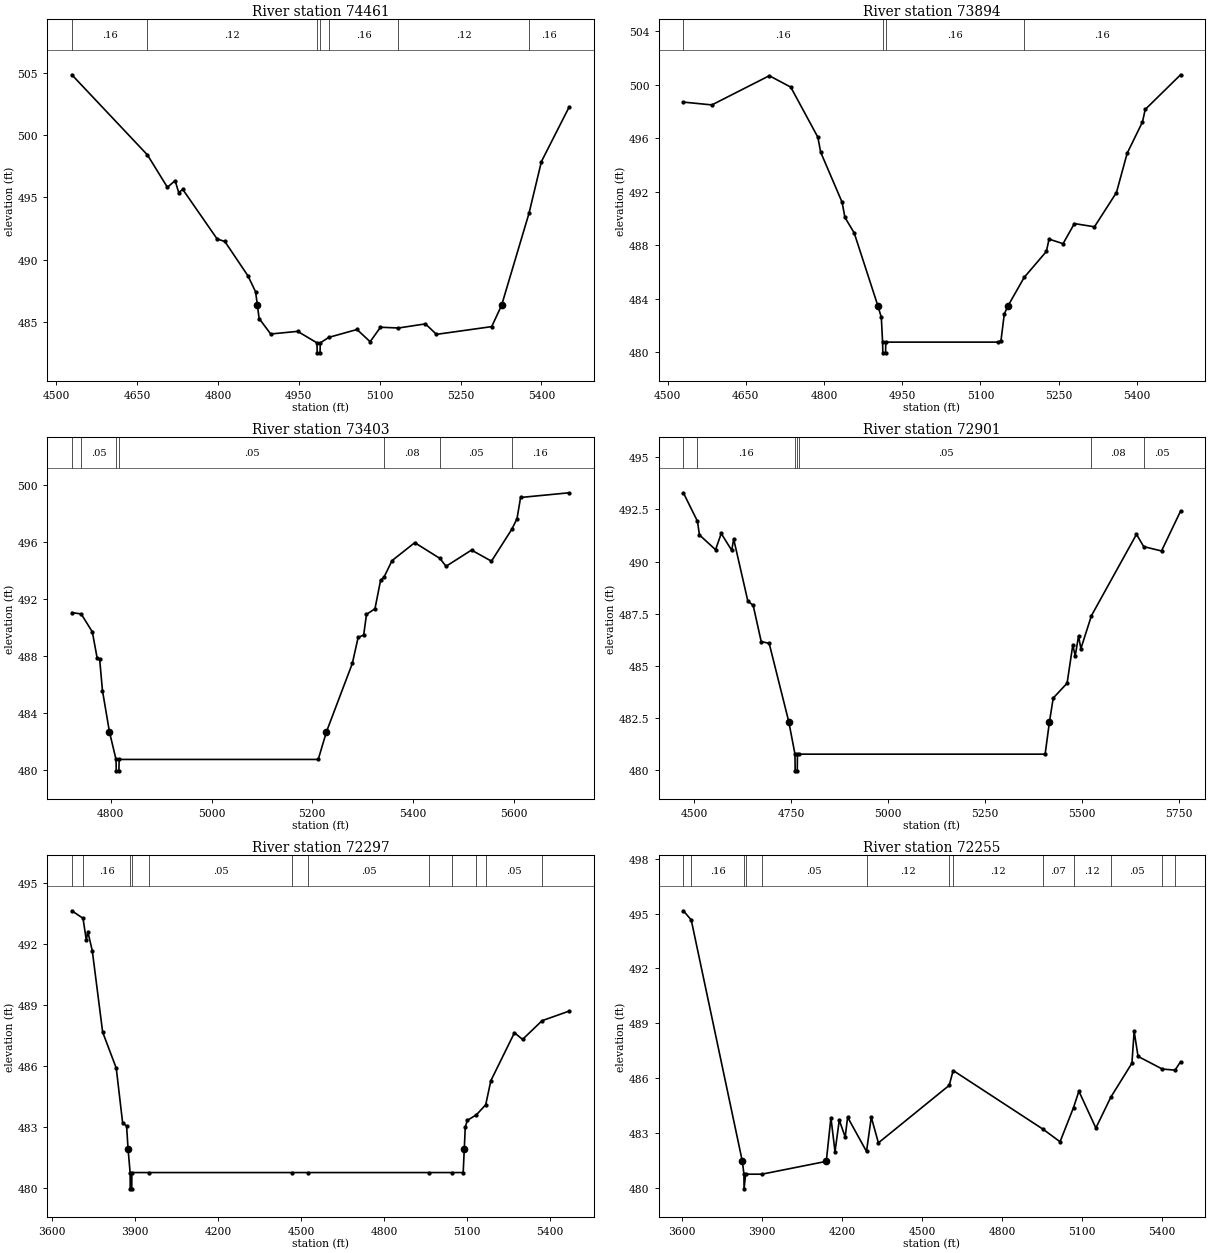
Type RM Length L Ch R = 1,74461,567,567,567
BEGIN DESCRIPTION:
RUNNING CREEK 73.0
END DESCRIPTION:
XS GIS Cut Line= 3
      2870974.97      7080924.96      2870675.00      7080575.00
      2870225.01      7080475.00
#Sta/Elev= 30
  4529.2  504.82  4669.4  498.40  4706.4  495.81  4720.7  496.34  4727.3  495.39
  4734.9  495.64  4798.6  491.67  4812.9  491.47  4855.7  488.72  4869.9  487.44
  4873.3  486.35  4876.5  485.30  4897.9  484.06  4947.9  484.27  4983.7  483.35
  4984.2  482.55  4989.4  482.55  4989.9  483.35  5005.8  483.79  5058.0  484.42
  5082.3  483.44  5101.5  484.60  5134.9  484.54  5184.8  484.87  5205.3  484.03
  5307.7  484.65  5326.0  486.35  5376.9  493.73  5399.9  497.87  5451.1  502.22
#Mann=7,-1,0
  4529.2    0.16       0  4669.4    0.12       0  4983.7    0.07       0
  4989.9    0.12       0  5005.8    0.16       0  5134.9    0.12       0
  5376.9    0.16       0
Bank Sta=4873.3,5326
Exp/Cntr=0.3,0.1

Type RM Length L Ch R = 1,73894,491,491,491
BEGIN DESCRIPTION:
RUNNING CREEK 72.0
END DESCRIPTION:
XS GIS Cut Line= 3
      2871125.01      7080575.01      2870925.00      7080125.00
      2870475.03      7080025.01
#Sta/Elev= 30
  4530.3  498.69  4585.0  498.48  4695.1  500.66  4736.2  499.81  4788.2  496.07
  4793.6  494.95  4834.7  491.21  4840.1  490.08  4857.9  488.92  4903.2  483.49
  4909.9  482.62  4912.3  480.77  4912.8  479.97  4918.0  479.97  4918.5  480.77
  5134.2  480.77  5139.3  480.87  5145.7  482.87  5153.0  483.49  5183.8  485.60
  5226.4  487.54  5231.5  488.46  5258.4  488.12  5280.1  489.62  5318.6  489.38
  5360.8  491.94  5381.3  494.87  5410.7  497.21  5415.9  498.14  5483.7  500.73
#Mann=4,-1,0
  4530.3    0.16       0  4912.3   0.033       0  4918.5    0.16       0
  5183.8    0.16       0
Bank Sta=4903.2,5153
Exp/Cntr=0.3,0.1

Type RM Length L Ch R = 1,73403,502,502,502
BEGIN DESCRIPTION:
RUNNING CREEK 71.0
END DESCRIPTION:
XS GIS Cut Line= 3
      2871335.69      7079677.09      2870938.28      7079698.27
      2870408.44      7079955.85
#Sta/Elev= 30
  4722.6  491.07  4741.1  490.98  4763.3  489.72  4772.8  487.89  4777.8  487.81
  4783.4  485.60  4797.3  482.70  4810.3  480.77  4810.8  479.97  4816.0  479.97
  4816.5  480.77  5211.8  480.77  5228.0  482.70  5279.5  487.51  5291.0  489.33
  5302.0  489.50  5307.6  490.95  5324.4  491.34  5335.7  493.36  5342.1  493.54
  5358.3  494.72  5403.4  495.98  5453.5  494.87  5465.5  494.32  5516.1  495.46
  5555.7  494.68  5596.1  496.92  5606.4  497.66  5613.5  499.15  5709.7  499.48
#Mann=7,-1,0
  4722.6    0.16       0  4741.1    0.05       0  4810.3   0.033       0
  4816.5    0.05       0  5342.1    0.08       0  5453.5    0.05       0
  5596.1    0.16       0
Bank Sta=4797.3,5228
Exp/Cntr=0.3,0.1

Type RM Length L Ch R = 1,72901,604,604,604
BEGIN DESCRIPTION:
Mapping XS 81f3d084
END DESCRIPTION:
XS GIS Cut Line= 4
      2871479.82      7079289.94      2871033.62      7079180.56
      2870837.44      7079230.91      2870332.43      7079590.15
#Sta/Elev= 30
  4471.9  493.30  4508.3  491.93  4513.3  491.28  4554.9  490.57  4569.5  491.35
  4596.5  490.54  4601.6  491.08  4638.1  488.11  4651.9  487.90  4672.5  486.17
  4693.1  486.08  4743.6  482.33  4759.6  480.77  4760.1  479.97  4765.5  479.97
  4766.0  480.77  4771.0  480.77  5404.5  480.77  5415.7  482.33  5425.4  483.46
  5461.1  484.17  5475.8  486.00  5482.0  485.48  5490.6  486.43  5496.7  485.83
  5523.9  487.41  5640.0  491.31  5658.6  490.72  5704.5  490.51  5753.6  492.42
#Mann=7,-1,0
  4471.9    0.05       0  4508.3    0.16       0  4759.6   0.033       0
  4766.0    0.16       0  4771.0    0.05       0  5523.9    0.08       0
  5658.6    0.05       0
Bank Sta=4743.6,5415.7
Exp/Cntr=0.3,0.1

Type RM Length L Ch R = 1,72297,42,42,42
BEGIN DESCRIPTION:
Mapping XS ea8a5791
END DESCRIPTION:
XS GIS Cut Line= 6
      2871394.76      7079236.13      2870946.82      7078982.65
      2870976.33      7078746.53      2870774.94      7078647.58
      2870688.14      7078704.87      2870259.65      7079265.19
#Sta/Elev= 30
  3670.7  493.63  3711.1  493.26  3722.9  492.20  3728.7  492.59  3744.6  491.67
  3782.1  487.67  3831.3  485.90  3854.3  483.22  3868.7  483.05  3873.9  481.95
  3881.4  480.77  3881.9  479.97  3887.3  479.97  3887.8  480.77  3950.1  480.77
  4467.4  480.77  4525.6  480.77  4963.4  480.77  5047.1  480.77  5085.8  480.77
  5089.8  481.95  5093.3  482.99  5100.4  483.33  5133.8  483.61  5167.2  484.10
  5185.8  485.28  5271.2  487.64  5300.4  487.31  5371.0  488.23  5468.5  488.70
#Mann=12,-1,0
  3670.7    0.05       0  3711.1    0.16       0  3881.4    0.07       0
  3887.8    0.16       0  3950.1    0.05       0  4467.4    0.12       0
  4525.6    0.05       0  4963.4    0.07       0  5047.1    0.05       0
  5133.8    0.12       0  5167.2    0.05       0  5371.0    0.08       0
Bank Sta=3873.9,5089.8
Exp/Cntr=0.3,0.1

Type RM Length L Ch R = 1,72255,77,77,77
BEGIN DESCRIPTION:
Mapping XS 7b8f46fa
END DESCRIPTION:
XS GIS Cut Line= 6
      2871413.82      7079177.08      2870983.28      7078951.40
      2871019.74      7078805.56      2870993.69      7078673.62
      2870728.07      7078604.17      2870216.92      7079231.31
#Sta/Elev= 30
  3604.5  495.15  3634.0  494.65  3825.8  481.47  3831.7  480.77  3832.2  479.97
  3838.1  480.77  3899.1  480.77  4140.7  481.47  4158.1  483.86  4173.4  482.00
  4189.5  483.72  4211.5  482.80  4220.8  483.88  4291.6  482.01  4309.5  483.88
  4336.2  482.48  4601.9  485.62  4616.6  486.43  4954.4  483.22  5017.7  482.54
  5068.3  484.41  5088.4  485.30  5152.1  483.29  5208.4  484.98  5287.4  486.83
  5295.7  488.57  5310.3  487.20  5401.4  486.51  5449.2  486.45  5469.8  486.91
#Mann=13,-1,0
  3604.5    0.05       0  3634.0    0.16       0  3831.7    0.07       0
  3838.1    0.16       0  3899.1    0.05       0  4291.6    0.12       0
  4601.9    0.05       0  4616.6    0.12       0  4954.4    0.07       0
  5068.3    0.12       0  5208.4    0.05       0  5401.4    0.12       0
  5449.2    0.05       0
Bank Sta=3825.8,4140.7
Exp/Cntr=0.3,0.1

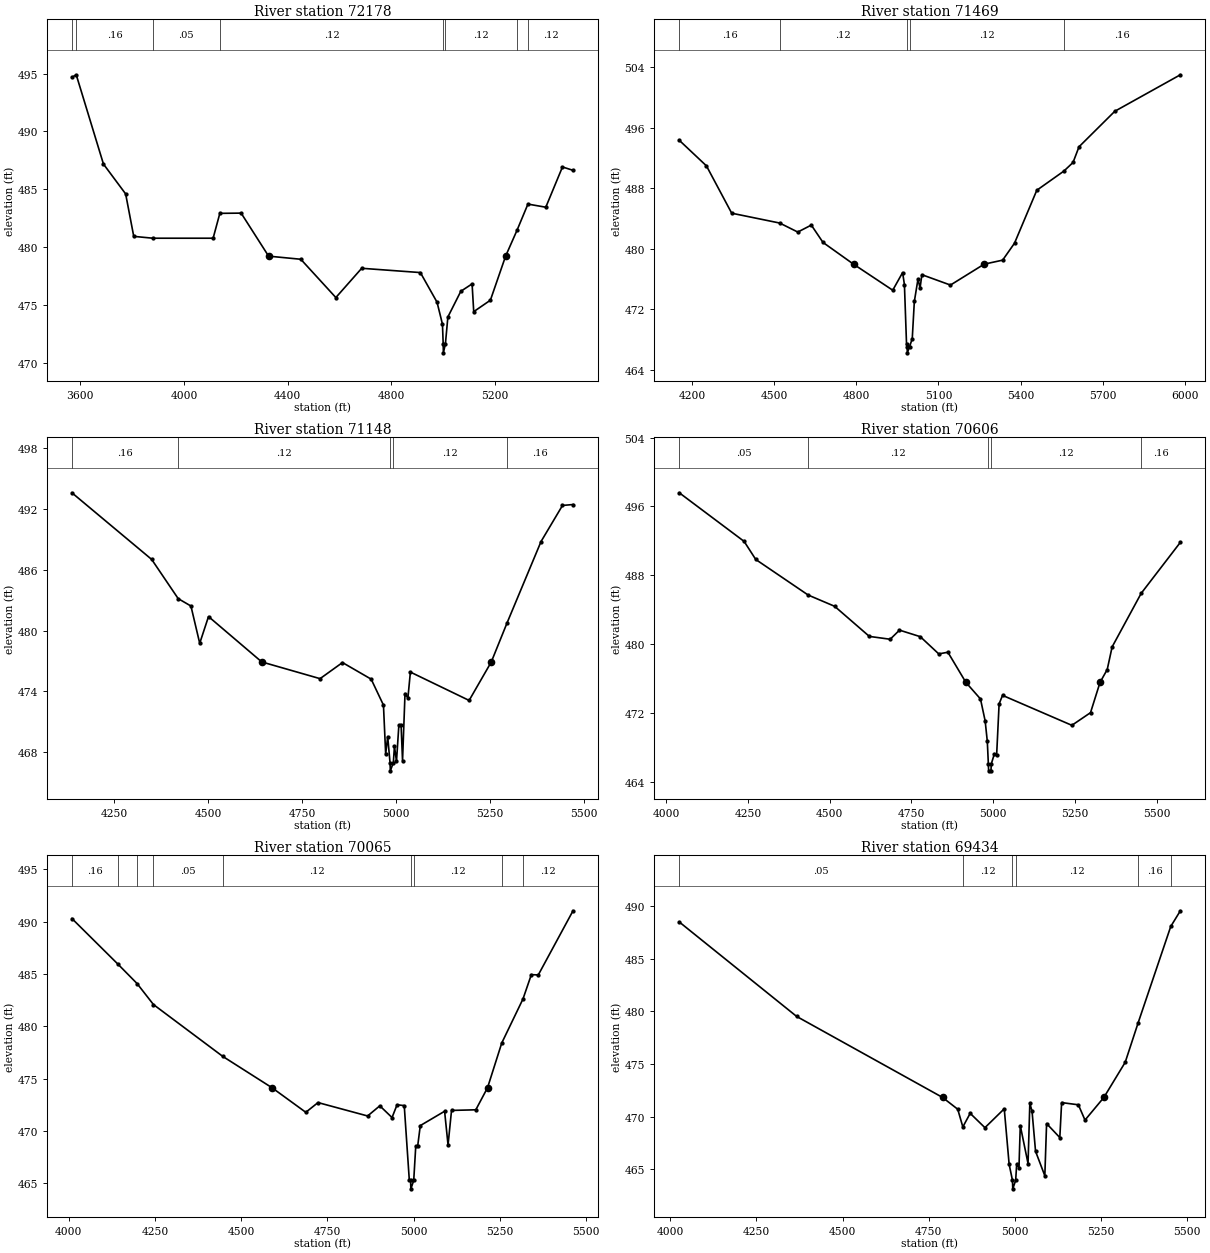
Type RM Length L Ch R = 1,72178,709,709,709
BEGIN DESCRIPTION:
RUNNING CREEK 70.0
END DESCRIPTION:
XS GIS Cut Line= 6
      2871422.48      7079133.67      2871035.58      7078902.35
      2871060.53      7078682.08      2870935.75      7078570.32
      2870762.14      7078526.92      2870154.63      7079191.57
#Sta/Elev= 30
  3567.9  494.68  3584.6  494.90  3689.6  487.18  3775.2  484.60  3806.4  480.93
  3880.2  480.77  4112.6  480.77  4138.5  482.92  4220.6  482.94  4326.6  479.22
  4450.8  478.95  4586.0  475.64  4685.7  478.17  4912.0  477.80  4976.3  475.24
  4997.2  473.34  5000.0  471.66  5000.8  470.86  5008.7  471.66  5018.1  473.96
  5068.0  476.18  5111.5  476.82  5117.8  474.42  5182.1  475.41  5240.8  479.22
  5284.7  481.45  5326.9  483.72  5395.8  483.45  5460.1  486.93  5500.8  486.64
#Mann=8,-1,0
  3567.9    0.05       0  3584.6    0.16       0  3880.2    0.05       0
  4138.5    0.12       0  5000.0    0.07       0  5008.7    0.12       0
  5284.7    0.05       0  5326.9    0.12       0
Bank Sta=4326.6,5240.8
Exp/Cntr=0.3,0.1

Type RM Length L Ch R = 1,71469,321,321,321
BEGIN DESCRIPTION:
RUNNING CREEK 69.0
END DESCRIPTION:
XS GIS Cut Line= 3
      2871425.02      7079025.02      2870823.56      7078328.13
      2869929.70      7078161.51
#Sta/Elev= 30
  4153.7  494.32  4253.0  490.94  4345.2  484.69  4520.5  483.39  4586.5  482.20
  4635.9  483.12  4678.6  480.83  4790.0  477.96  4933.2  474.52  4969.3  476.85
  4975.9  475.26  4983.6  467.41  4985.8  467.05  4986.6  466.25  4994.6  467.05
  5004.5  468.12  5012.1  473.03  5025.5  476.00  5033.0  474.79  5039.6  476.57
  5144.0  475.20  5267.0  477.96  5334.5  478.49  5377.9  480.73  5459.3  487.72
  5558.1  490.25  5591.6  491.39  5613.4  493.46  5744.1  498.15  5983.5  502.97
#Mann=5,-1,0
  4153.7    0.16       0  4520.5    0.12       0  4985.8    0.07       0
  4994.6    0.12       0  5558.1    0.16       0
Bank Sta=4790,5267
Exp/Cntr=0.3,0.1

Type RM Length L Ch R = 1,71148,542,542,542
BEGIN DESCRIPTION:
RUNNING CREEK 68.0
END DESCRIPTION:
XS GIS Cut Line= 3
      2871424.99      7078974.98      2871075.00      7078175.00
      2870724.97      7077874.98
#Sta/Elev= 30
  4137.4  493.60  4349.8  487.02  4420.4  483.15  4454.3  482.42  4477.7  478.74
  4501.1  481.38  4642.9  476.90  4798.1  475.25  4857.8  476.84  4934.2  475.20
  4966.9  472.64  4972.8  467.80  4978.2  469.53  4984.4  466.95  4985.2  466.15
  4993.2  466.95  4996.2  468.58  5001.6  467.08  5007.9  470.64  5013.9  470.64
  5017.7  467.15  5024.3  473.78  5032.0  473.34  5038.6  475.90  5195.0  473.10
  5254.0  476.90  5296.4  480.79  5386.5  488.79  5443.6  492.35  5471.6  492.44
#Mann=5,-1,0
  4137.4    0.16       0  4420.4    0.12       0  4984.4    0.07       0
  4993.2    0.12       0  5296.4    0.16       0
Bank Sta=4642.9,5254
Exp/Cntr=0.3,0.1

Type RM Length L Ch R = 1,70606,541,541,541
BEGIN DESCRIPTION:
RUNNING CREEK 67.0
END DESCRIPTION:
XS GIS Cut Line= 3
      2872174.99      7078774.99      2871525.00      7078025.00
      2871225.00      7077575.00
#Sta/Elev= 30
  4039.6  497.59  4238.1  491.94  4273.7  489.84  4433.9  485.71  4515.0  484.40
  4621.3  480.90  4685.0  480.57  4713.5  481.63  4777.1  480.87  4833.6  478.87
  4861.6  479.06  4916.6  475.56  4961.3  473.63  4975.6  471.08  4982.2  468.70
  4985.4  466.08  4986.2  465.28  4993.4  465.28  4994.3  466.08  5004.1  467.28
  5010.7  467.08  5018.3  473.06  5028.8  474.05  5240.9  470.57  5298.0  472.04
  5327.1  475.56  5349.1  477.05  5364.1  479.68  5453.1  485.91  5572.9  491.83
#Mann=5,-1,0
  4039.6    0.05       0  4433.9    0.12       0  4985.4    0.07       0
  4994.3    0.12       0  5453.1    0.16       0
Bank Sta=4916.6,5327.1
Exp/Cntr=0.3,0.1

Type RM Length L Ch R = 1,70065,631,631,631
BEGIN DESCRIPTION:
RUNNING CREEK 66.0
END DESCRIPTION:
XS GIS Cut Line= 3
      2872374.99      7078374.99      2871775.00      7077575.00
      2871324.95      7077524.99
#Sta/Elev= 30
  4009.4  490.30  4142.9  485.94  4198.3  484.09  4245.9  482.08  4446.8  477.13
  4589.4  474.14  4687.5  471.79  4722.9  472.72  4866.7  471.44  4902.1  472.41
  4937.5  471.29  4952.1  472.51  4972.9  472.43  4987.5  465.35  4991.2  465.28
  4992.1  464.48  5000.4  465.28  5006.3  468.57  5011.9  468.57  5019.4  470.52
  5089.9  471.89  5099.9  468.67  5110.0  471.97  5180.4  472.03  5214.4  474.14
  5255.6  478.41  5317.2  482.62  5341.4  484.94  5361.5  484.91  5462.2  491.04
#Mann=9,-1,0
  4009.4    0.16       0  4142.9    0.05       0  4198.3    0.16       0
  4245.9    0.05       0  4446.8    0.12       0  4991.2    0.07       0
  5000.4    0.12       0  5255.6    0.16       0  5317.2    0.12       0
Bank Sta=4589.4,5214.4
Exp/Cntr=0.3,0.1

Type RM Length L Ch R = 1,69434,539,539,539
BEGIN DESCRIPTION:
RUNNING CREEK 65.0
END DESCRIPTION:
XS GIS Cut Line= 3
      2872774.98      7077974.98      2872125.00      7077225.00
      2871675.02      7077125.00
#Sta/Elev= 30
  4026.4  488.47  4366.9  479.51  4790.0  471.83  4834.1  470.71  4848.9  469.03
  4870.2  470.32  4913.0  468.96  4969.0  470.75  4983.2  465.48  4992.9  463.96
  4993.7  463.16  5002.1  463.96  5005.1  465.51  5011.7  465.16  5015.5  469.16
  5038.0  465.56  5043.2  471.27  5049.6  470.53  5059.8  466.72  5086.7  464.40
  5091.8  469.35  5130.2  468.02  5135.4  471.34  5184.0  471.13  5203.2  469.68
  5258.0  471.83  5319.8  475.16  5357.6  478.93  5451.9  488.04  5479.8  489.53
#Mann=6,-1,0
  4026.4    0.05       0  4848.9    0.12       0  4992.9    0.07       0
  5002.1    0.12       0  5357.6    0.16       0  5451.9    0.12       0
Bank Sta=4790,5258
Exp/Cntr=0.3,0.1

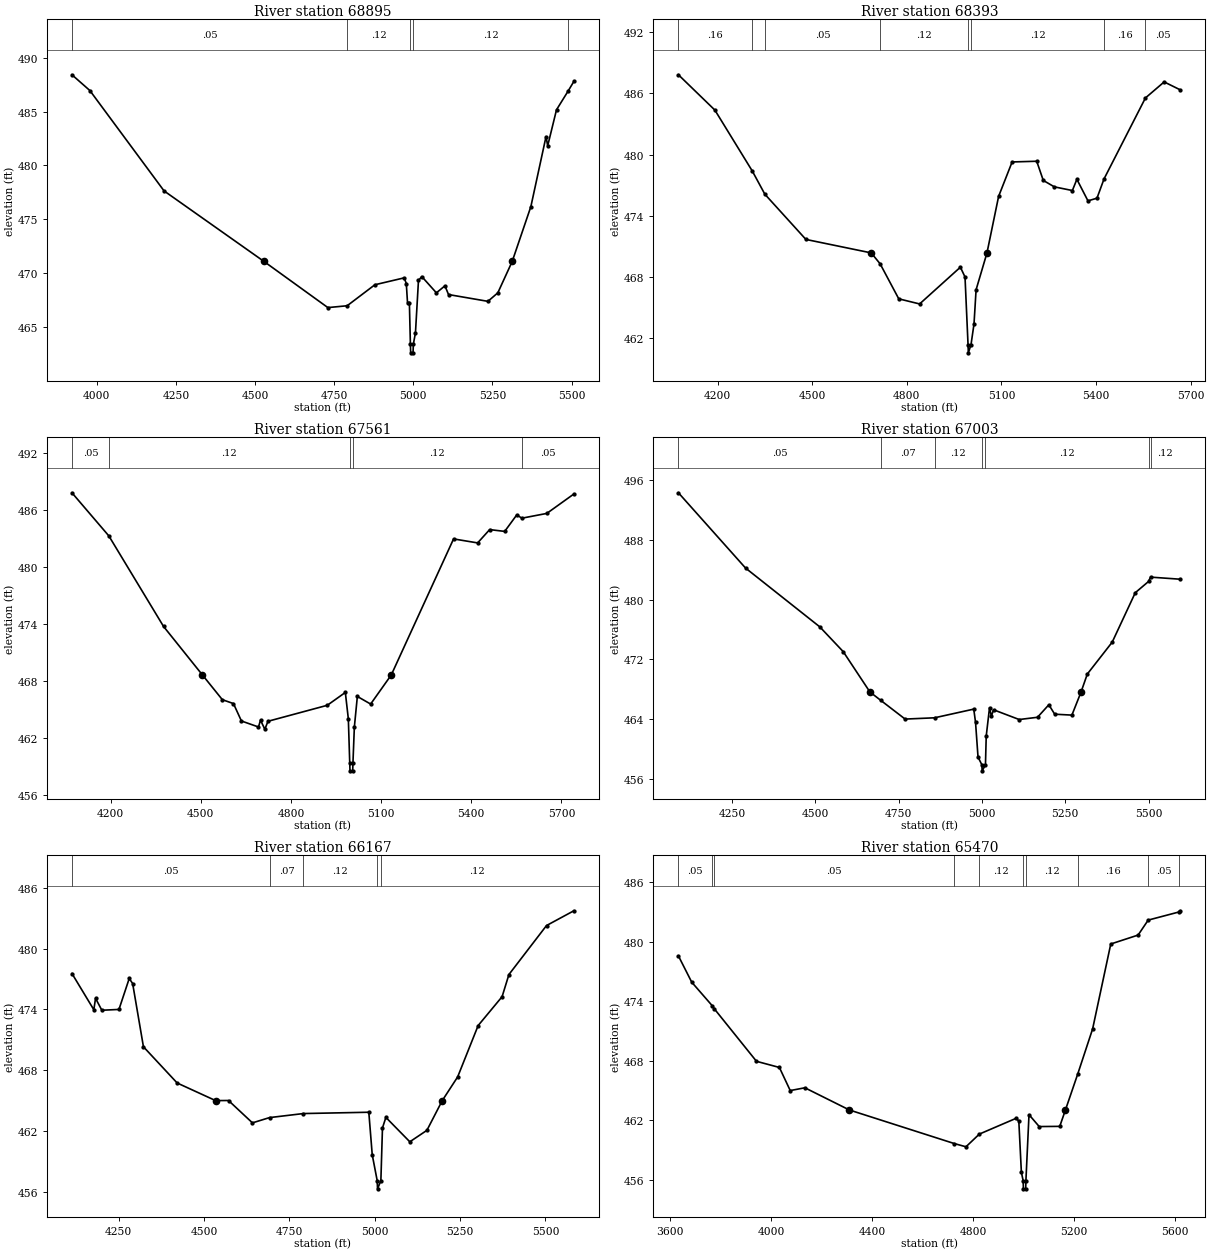
Type RM Length L Ch R = 1,68895,502,502,502
BEGIN DESCRIPTION:
RUNNING CREEK 64.0
END DESCRIPTION:
XS GIS Cut Line= 3
      2873124.99      7077624.99      2872425.00      7076825.00
      2871925.02      7076675.01
#Sta/Elev= 30
  3922.0  488.42  3978.5  486.96  4212.9  477.64  4528.1  471.10  4730.2  466.81
  4791.1  466.98  4878.7  468.93  4971.2  469.57  4977.9  469.04  4981.7  467.26
  4987.6  467.26  4990.8  463.41  4991.7  462.61  4999.2  462.61  5000.1  463.41
  5006.8  464.47  5016.3  469.33  5026.8  469.69  5072.9  468.18  5099.9  468.83
  5111.2  468.02  5235.6  467.39  5266.9  468.18  5312.4  471.10  5371.3  476.19
  5419.1  482.68  5424.4  481.83  5452.2  485.17  5488.7  486.90  5507.0  487.80
#Mann=5,-1,0
  3922.0    0.05       0  4791.1    0.12       0  4990.8    0.07       0
  5000.1    0.12       0  5488.7    0.16       0
Bank Sta=4528.1,5312.4
Exp/Cntr=0.3,0.1

Type RM Length L Ch R = 1,68393,832,832,832
BEGIN DESCRIPTION:
RUNNING CREEK 63.0
END DESCRIPTION:
XS GIS Cut Line= 3
      2873324.97      7077424.96      2872825.00      7076675.00
      2872377.40      7076150.32
#Sta/Elev= 30
  4076.1  487.81  4191.7  484.35  4310.3  478.38  4350.1  476.11  4480.2  471.68
  4687.3  470.36  4715.5  469.29  4774.6  465.86  4840.7  465.36  4969.9  468.96
  4984.6  468.00  4994.2  461.37  4995.1  460.57  5003.6  461.37  5013.1  463.40
  5019.7  466.75  5054.2  470.36  5091.1  475.90  5133.9  479.27  5211.9  479.34
  5232.7  477.46  5267.8  476.83  5324.9  476.47  5339.2  477.57  5374.3  475.46
  5402.9  475.72  5425.3  477.61  5556.5  485.54  5615.9  487.11  5667.1  486.33
#Mann=8,-1,0
  4076.1    0.16       0  4310.3    0.12       0  4350.1    0.05       0
  4715.5    0.12       0  4994.2    0.07       0  5003.6    0.12       0
  5425.3    0.16       0  5556.5    0.05       0
Bank Sta=4687.3,5054.2
Exp/Cntr=0.3,0.1

Type RM Length L Ch R = 1,67561,558,558,558
BEGIN DESCRIPTION:
RUNNING CREEK 62.0
END DESCRIPTION:
XS GIS Cut Line= 3
      2874054.48      7076407.24      2873297.51      7076157.23
      2872425.00      7076125.00
#Sta/Elev= 30
  4071.1  487.80  4193.8  483.27  4375.9  473.75  4505.3  468.65  4571.6  466.05
  4608.6  465.64  4635.1  463.81  4691.9  463.18  4698.6  463.90  4713.0  462.94
  4723.5  463.78  4920.8  465.46  4980.9  466.81  4990.9  464.04  4995.6  459.37
  4996.4  458.57  5005.4  458.57  5006.2  459.37  5010.9  463.16  5020.9  466.39
  5065.1  465.59  5133.8  468.65  5341.1  482.95  5421.2  482.53  5461.2  483.93
  5511.2  483.74  5551.3  485.47  5568.6  485.13  5651.3  485.63  5741.4  487.67
#Mann=5,-1,0
  4071.1    0.05       0  4193.8    0.12       0  4995.6    0.07       0
  5006.2    0.12       0  5568.6    0.05       0
Bank Sta=4505.3,5133.8
Exp/Cntr=0.3,0.1

Type RM Length L Ch R = 1,67003,836,836,836
BEGIN DESCRIPTION:
RUNNING CREEK 61.0
END DESCRIPTION:
XS GIS Cut Line= 3
      2874224.95      7076074.98      2873375.00      7075775.00
      2872824.99      7076025.00
#Sta/Elev= 30
  4089.8  494.25  4291.2  484.20  4513.9  476.35  4584.2  473.04  4664.2  467.66
  4696.4  466.55  4769.8  464.04  4858.0  464.21  4975.7  465.37  4981.0  463.62
  4988.5  458.97  5000.1  457.93  5000.9  457.13  5010.8  457.93  5013.1  461.77
  5023.0  465.56  5028.5  464.43  5035.1  465.28  5112.0  463.98  5166.9  464.28
  5200.9  465.95  5218.5  464.69  5270.1  464.57  5297.6  467.66  5316.3  470.05
  5391.0  474.31  5460.2  480.91  5500.0  482.41  5505.9  482.99  5595.3  482.71
#Mann=7,-1,0
  4089.8    0.05       0  4696.4    0.07       0  4858.0    0.12       0
  5000.1    0.07       0  5010.8    0.12       0  5500.0    0.05       0
  5505.9    0.12       0
Bank Sta=4664.2,5297.6
Exp/Cntr=0.3,0.1

Type RM Length L Ch R = 1,66167,697,697,697
BEGIN DESCRIPTION:
RUNNING CREEK 60.0
END DESCRIPTION:
XS GIS Cut Line= 3
      2874392.39      7075364.69      2873555.40      7075304.82
      2872925.03      7075275.00
#Sta/Elev= 30
  4113.0  477.55  4177.1  473.97  4182.1  475.10  4200.6  473.92  4250.7  474.00
  4280.8  477.06  4290.8  476.56  4322.4  470.31  4421.2  466.73  4533.8  464.99
  4571.6  465.00  4641.7  462.79  4691.7  463.31  4790.9  463.71  4982.6  463.84
  4992.6  459.64  5007.2  457.07  5008.1  456.27  5017.9  457.07  5022.6  462.29
  5032.6  463.33  5102.7  460.92  5152.7  462.05  5197.7  464.99  5242.8  467.33
  5302.9  472.41  5373.0  475.26  5393.0  477.45  5503.1  482.29  5583.2  483.75
#Mann=5,-1,0
  4113.0    0.05       0  4691.7    0.07       0  4790.9    0.12       0
  5007.2    0.07       0  5017.9    0.12       0
Bank Sta=4533.8,5197.7
Exp/Cntr=0.3,0.1

Type RM Length L Ch R = 1,65470,688,688,688
BEGIN DESCRIPTION:
RUNNING CREEK 59.0
END DESCRIPTION:
XS GIS Cut Line= 3
      2874811.47      7074916.93      2873373.99      7074729.43
      2872925.00      7075025.00
#Sta/Elev= 30
  3632.8  478.58  3685.5  475.93  3766.9  473.55  3774.4  473.26  3941.9  467.95
  4032.6  467.33  4075.5  465.00  4133.5  465.28  4309.9  463.04  4724.6  459.66
  4771.3  459.33  4824.2  460.61  4970.5  462.21  4980.6  461.91  4990.7  456.76
  4997.9  455.89  4998.7  455.09  5007.8  455.09  5008.6  455.89  5020.9  462.57
  5061.3  461.37  5142.6  461.39  5165.1  463.04  5214.1  466.69  5272.8  471.22
  5344.6  479.78  5452.8  480.68  5492.8  482.19  5614.8  483.01  5620.0  483.13
#Mann=10,-1,0
  3632.8    0.05       0  3766.9    0.16       0  3774.4    0.05       0
  4724.6    0.07       0  4824.2    0.12       0  4997.9    0.07       0
  5008.6    0.12       0  5214.1    0.16       0  5492.8    0.05       0
  5614.8    0.16       0
Bank Sta=4309.9,5165.1
Exp/Cntr=0.3,0.1

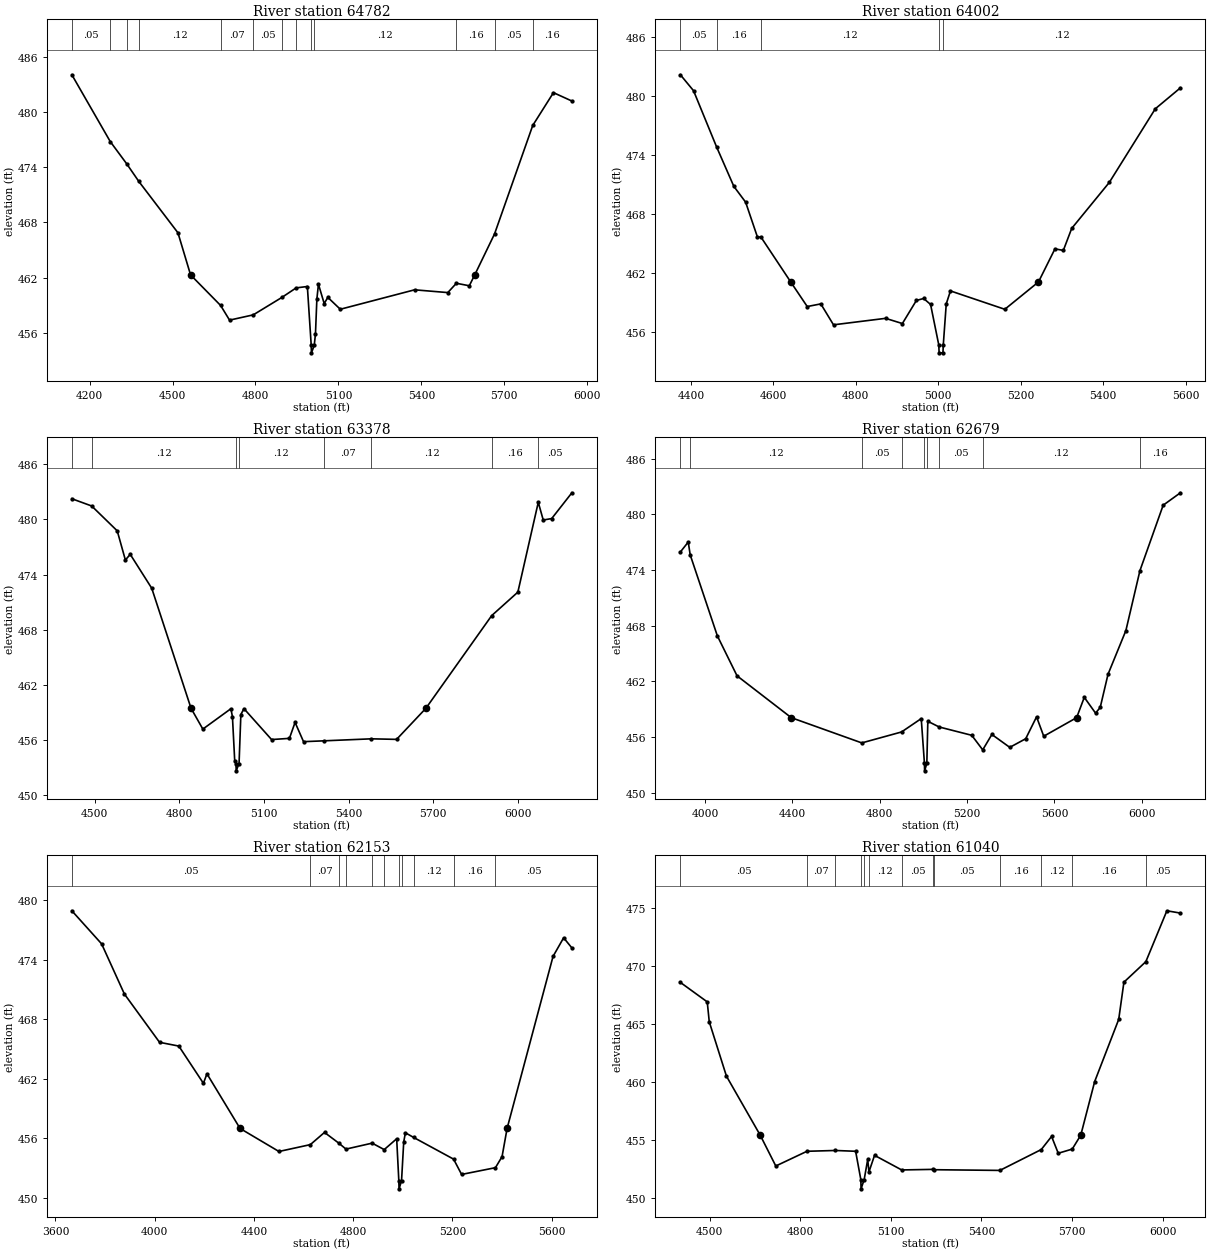
Type RM Length L Ch R = 1,64782,780,780,780
BEGIN DESCRIPTION:
RUNNING CREEK 58.0
END DESCRIPTION:
XS GIS Cut Line= 3
      2874474.97      7073975.01      2873573.06      7074223.18
      2872932.89      7074816.99
#Sta/Elev= 30
  4135.9  484.03  4274.8  476.78  4334.2  474.37  4378.2  472.45  4519.6  466.88
  4565.3  462.31  4674.0  458.99  4706.3  457.40  4791.9  457.97  4895.3  459.86
  4947.2  460.90  4987.7  461.05  5001.7  454.65  5002.5  453.85  5012.5  454.65
  5017.0  455.88  5022.1  459.68  5027.8  461.30  5048.6  459.20  5061.7  459.87
  5106.8  458.58  5375.5  460.69  5495.7  460.39  5526.7  461.40  5573.4  461.13
  5593.1  462.31  5664.8  466.76  5802.9  478.53  5877.8  482.09  5944.5  481.18
#Mann=13,-1,0
  4135.9    0.05       0  4274.8    0.12       0  4334.2    0.05       0
  4378.2    0.12       0  4674.0    0.07       0  4791.9    0.05       0
  4895.3    0.16       0  4947.2    0.12       0  5001.7    0.07       0
  5012.5    0.12       0  5526.7    0.16       0  5664.8    0.05       0
  5802.9    0.16       0
Bank Sta=4565.3,5593.1
Exp/Cntr=0.3,0.1

Type RM Length L Ch R = 1,64002,624,624,624
BEGIN DESCRIPTION:
RUNNING CREEK 57.0
END DESCRIPTION:
XS GIS Cut Line= 3
      2874425.02      7073875.01      2873875.00      7073625.00
      2873274.95      7073524.99
#Sta/Elev= 30
  4374.5  482.13  4406.4  480.51  4462.3  474.79  4504.1  470.78  4532.7  469.17
  4561.3  465.63  4570.0  465.61  4642.1  461.05  4682.1  458.55  4715.0  458.82
  4745.8  456.69  4872.1  457.35  4912.8  456.82  4946.8  459.17  4964.4  459.37
  4981.2  458.76  5001.1  454.64  5001.9  453.84  5011.2  453.84  5012.0  454.64
  5019.2  458.82  5029.4  460.14  5161.2  458.27  5242.8  461.05  5282.8  464.42
  5303.1  464.26  5323.4  466.50  5414.6  471.18  5526.1  478.67  5587.0  480.80
#Mann=5,-1,0
  4374.5    0.05       0  4462.3    0.16       0  4570.0    0.12       0
  5001.1    0.07       0  5012.0    0.12       0
Bank Sta=4642.1,5242.8
Exp/Cntr=0.3,0.1

Type RM Length L Ch R = 1,63378,699,699,699
BEGIN DESCRIPTION:
RUNNING CREEK 56.0
END DESCRIPTION:
XS GIS Cut Line= 3
      2874475.00      7073775.01      2874177.72      7073087.79
      2873153.42      7073096.47
#Sta/Elev= 30
  4418.8  482.26  4489.1  481.47  4579.7  478.76  4608.6  475.58  4625.8  476.20
  4702.1  472.50  4841.4  459.42  4883.3  457.15  4982.7  459.37  4988.2  458.51
  4996.3  453.69  5000.8  453.40  5001.5  452.60  5011.7  453.40  5018.1  458.74
  5029.0  459.38  5127.0  456.01  5190.3  456.14  5210.3  457.88  5240.3  455.78
  5311.8  455.87  5480.6  456.09  5570.3  456.03  5674.3  459.42  5907.5  469.52
  6000.3  472.08  6072.7  481.87  6090.3  479.94  6120.3  480.10  6191.9  482.91
#Mann=8,-1,0
  4418.8    0.05       0  4489.1    0.12       0  5000.8    0.07       0
  5011.7    0.12       0  5311.8    0.07       0  5480.6    0.12       0
  5907.5    0.16       0  6072.7    0.05       0
Bank Sta=4841.4,5674.3
Exp/Cntr=0.3,0.1

Type RM Length L Ch R = 1,62679,526,526,526
BEGIN DESCRIPTION:
RUNNING CREEK 55.0
END DESCRIPTION:
XS GIS Cut Line= 4
      2874975.02      7073475.04      2874559.67      7072679.80
      2874104.71      7072631.06      2873198.43      7072861.68
#Sta/Elev= 30
  3886.9  475.94  3922.9  477.01  3932.0  475.62  4056.2  466.90  4146.4  462.59
  4394.8  458.08  4717.7  455.36  4899.8  456.54  4989.9  457.98  5004.6  453.15
  5005.3  452.35  5015.5  453.15  5020.1  457.69  5071.7  457.08  5221.2  456.18
  5271.5  454.61  5313.4  456.27  5395.3  454.88  5468.3  455.81  5518.0  458.17
  5550.9  456.08  5701.5  458.08  5736.6  460.27  5788.2  458.57  5809.5  459.18
  5845.3  462.76  5927.1  467.47  5991.3  473.92  6097.8  480.98  6176.8  482.32
#Mann=9,-1,0
  3886.9    0.05       0  3932.0    0.12       0  4717.7    0.05       0
  4899.8    0.12       0  5004.6    0.07       0  5015.5    0.12       0
  5071.7    0.05       0  5271.5    0.12       0  5991.3    0.16       0
Bank Sta=4394.8,5701.5
Exp/Cntr=0.3,0.1

Type RM Length L Ch R = 1,62153,1113,1113,1113
BEGIN DESCRIPTION:
RUNNING CREEK 54.0
END DESCRIPTION:
XS GIS Cut Line= 3
      2875332.21      7073157.21      2874646.91      7072427.45
      2873969.66      7071673.17
#Sta/Elev= 30
  3666.4  478.91  3786.3  475.58  3878.1  470.53  4019.7  465.67  4097.4  465.29
  4196.5  461.54  4210.7  462.50  4344.1  457.00  4500.8  454.68  4627.3  455.37
  4684.4  456.60  4742.0  455.52  4770.9  454.92  4876.3  455.52  4925.0  454.87
  4975.2  455.96  4983.9  451.72  4984.7  450.92  4994.8  451.72  5003.6  455.64
  5010.3  456.56  5043.9  456.09  5204.5  453.91  5236.8  452.37  5373.2  453.05
  5399.8  454.16  5420.1  457.00  5605.3  474.32  5647.9  476.19  5681.2  475.17
#Mann=11,-1,0
  3666.4    0.05       0  4627.3    0.07       0  4742.0    0.12       0
  4770.9    0.16       0  4876.3    0.12       0  4925.0    0.16       0
  4983.9    0.07       0  4994.8    0.16       0  5043.9    0.12       0
  5204.5    0.16       0  5373.2    0.05       0
Bank Sta=4344.1,5420.1
Exp/Cntr=0.3,0.1

Type RM Length L Ch R = 1,61040,391,391,391
BEGIN DESCRIPTION:
RUNNING CREEK 53.0
END DESCRIPTION:
XS GIS Cut Line= 3
      2875565.65      7072369.67      2875166.36      7072020.29
      2874149.28      7071541.03
#Sta/Elev= 30
  4403.5  468.60  4492.4  466.92  4499.1  465.20  4556.0  460.51  4667.7  455.42
  4719.3  452.76  4822.4  454.03  4916.4  454.10  4983.5  454.03  5000.7  451.59
  5001.5  450.79  5011.8  451.59  5023.5  453.33  5027.6  452.25  5046.1  453.68
  5135.9  452.42  5240.3  452.47  5244.2  452.44  5460.9  452.38  5597.9  454.18
  5632.0  455.31  5654.1  453.86  5700.4  454.22  5728.6  455.42  5774.7  460.05
  5854.2  465.41  5871.4  468.62  5944.0  470.39  6013.6  474.78  6058.4  474.58
#Mann=13,-1,0
  4403.5    0.05       0  4822.4    0.07       0  4916.4    0.16       0
  5000.7    0.07       0  5011.8    0.16       0  5027.6    0.12       0
  5135.9    0.05       0  5240.3    0.16       0  5244.2    0.05       0
  5460.9    0.16       0  5597.9    0.12       0  5700.4    0.16       0
  5944.0    0.05       0
Bank Sta=4667.7,5728.6
Exp/Cntr=0.3,0.1