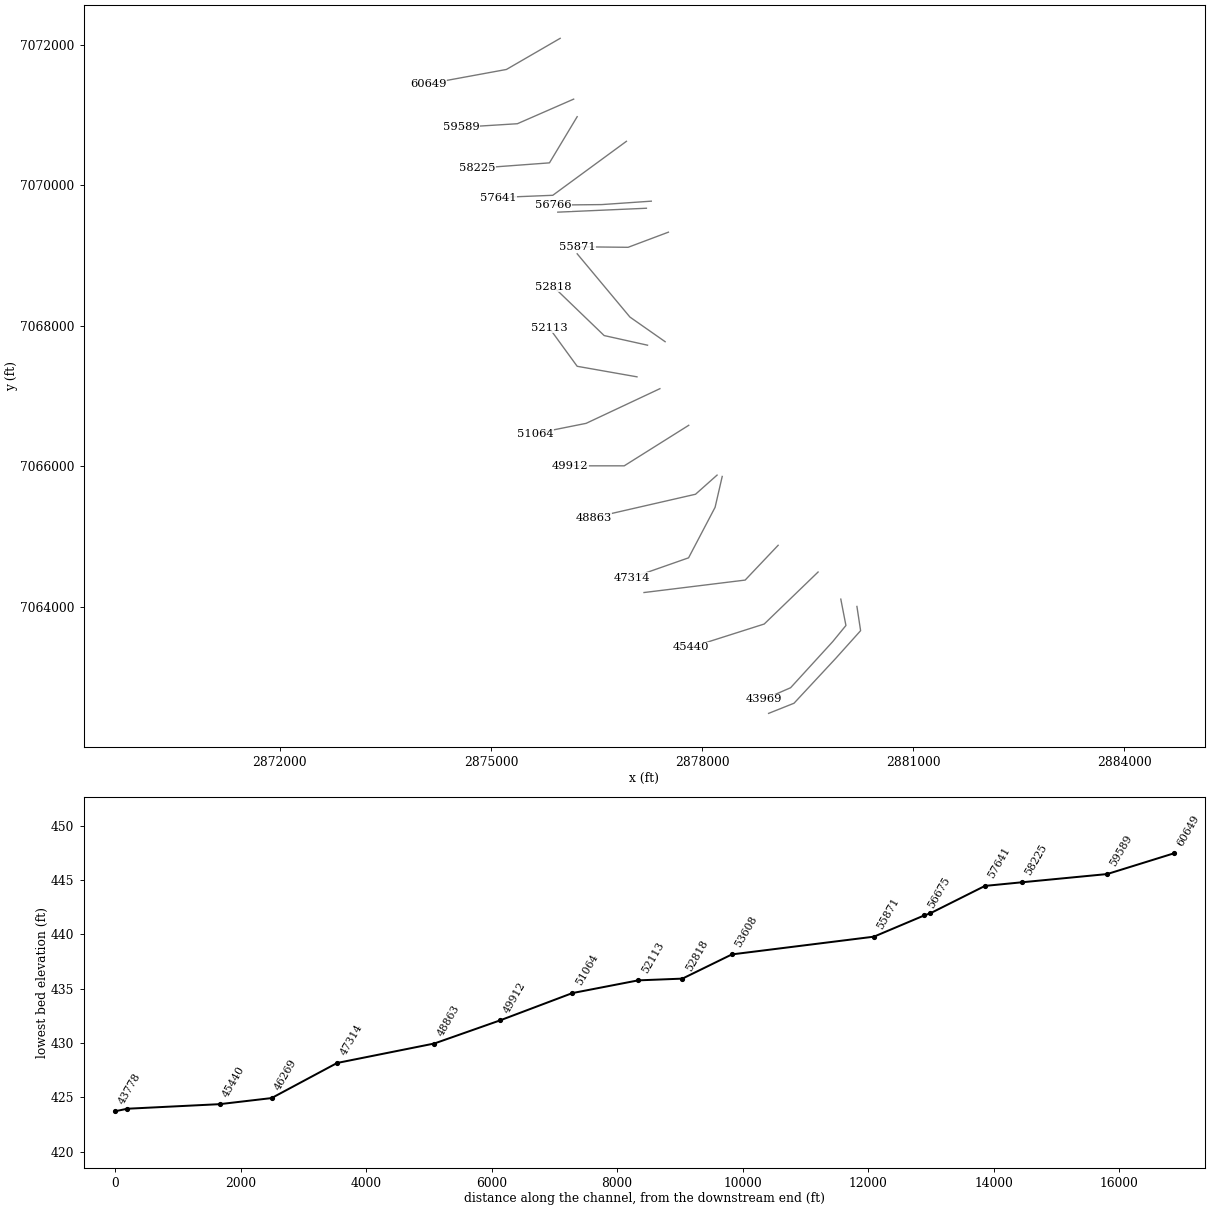
HEC-RAS study RUNNING CREEK.prj: RUNNING CREEK Base Level Engineering

--- RUNNING CREEK.g01 (geometry) --- (continued)

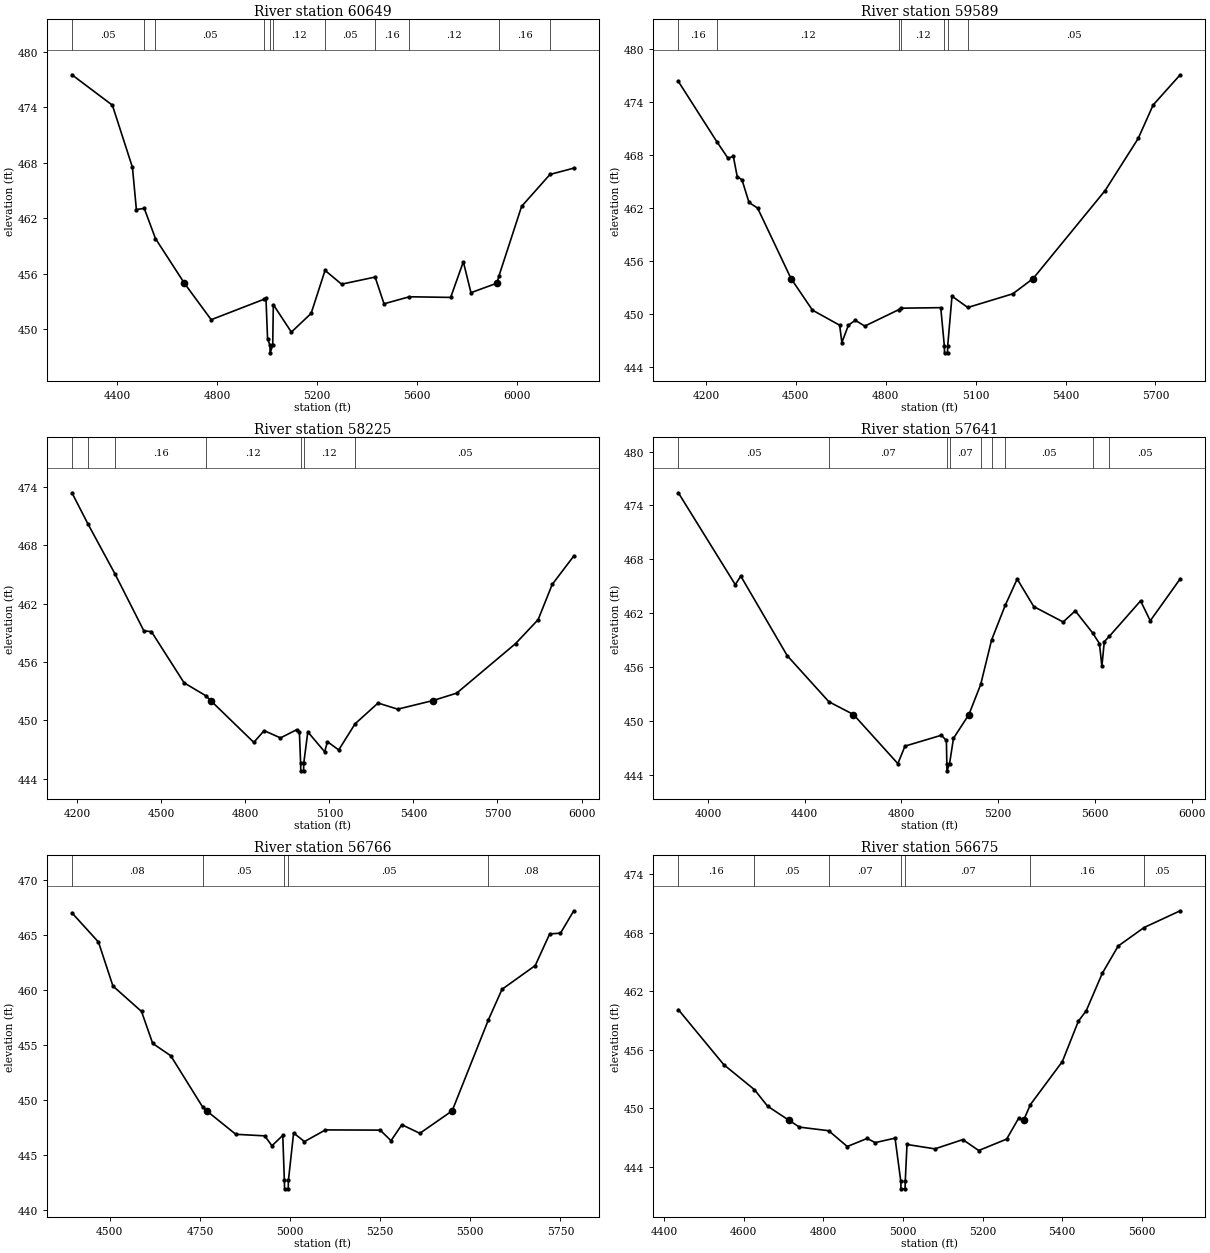
Type RM Length L Ch R = 1,60649,1060,1060,1060
BEGIN DESCRIPTION:
RUNNING CREEK 52.0
END DESCRIPTION:
XS GIS Cut Line= 3
      2875983.25      7072089.51      2875219.39      7071646.82
      2874109.71      7071443.07
#Sta/Elev= 30
  4217.9  477.50  4380.0  474.21  4460.3  467.50  4476.1  462.94  4507.7  463.06
  4552.6  459.80  4668.3  454.98  4775.9  451.03  4986.4  453.23  4995.4  453.35
  5001.8  448.99  5011.4  448.25  5012.1  447.45  5022.5  448.25  5024.9  452.66
  5097.2  449.69  5176.4  451.71  5232.2  456.36  5298.4  454.87  5432.8  455.64
  5468.5  452.75  5570.2  453.51  5735.6  453.44  5786.4  457.29  5816.9  453.95
  5921.1  454.98  5929.1  455.76  6019.9  463.28  6133.7  466.73  6229.0  467.41
#Mann=11,-1,0
  4217.9    0.05       0  4507.7    0.16       0  4552.6    0.05       0
  4986.4    0.12       0  5011.4    0.07       0  5022.5    0.12       0
  5232.2    0.05       0  5432.8    0.16       0  5570.2    0.12       0
  5929.1    0.16       0  6133.7    0.05       0
Bank Sta=4668.3,5921.1
Exp/Cntr=0.3,0.1

Type RM Length L Ch R = 1,59589,1364,1364,1364
BEGIN DESCRIPTION:
RUNNING CREEK 51.0
END DESCRIPTION:
XS GIS Cut Line= 3
      2876174.96      7071224.98      2875375.00      7070875.00
      2874575.03      7070825.00
#Sta/Elev= 30
  4107.9  476.31  4236.5  469.47  4273.5  467.61  4291.5  467.81  4304.3  465.53
  4320.3  465.16  4343.7  462.59  4372.5  461.95  4483.9  453.97  4555.4  450.39
  4646.2  448.68  4653.6  446.72  4675.4  448.68  4698.4  449.24  4730.0  448.58
  4843.3  450.44  4849.6  450.61  4983.6  450.67  4995.5  446.35  4996.2  445.55
  5006.1  445.55  5006.8  446.35  5021.1  451.97  5073.8  450.69  5224.0  452.24
  5291.9  453.97  5532.1  463.94  5642.4  469.84  5692.4  473.64  5782.6  477.06
#Mann=7,-1,0
  4107.9    0.16       0  4236.5    0.12       0  4843.3    0.07       0
  4849.6    0.12       0  4995.5    0.07       0  5006.8    0.12       0
  5073.8    0.05       0
Bank Sta=4483.9,5291.9
Exp/Cntr=0.3,0.1

Type RM Length L Ch R = 1,58225,584,584,584
BEGIN DESCRIPTION:
RUNNING CREEK 50.0
END DESCRIPTION:
XS GIS Cut Line= 3
      2876225.01      7070975.01      2875831.03      7070318.38
      2874808.10      7070242.44
#Sta/Elev= 30
  4180.9  473.42  4237.3  470.25  4334.7  465.06  4437.5  459.21  4464.7  459.12
  4581.3  453.85  4659.6  452.51  4676.0  452.03  4830.1  447.72  4867.0  448.93
  4925.3  448.18  4982.8  449.02  4992.8  448.81  4997.2  445.59  4997.8  444.79
  5007.8  444.79  5008.5  445.59  5022.9  448.80  5083.1  446.75  5093.1  447.79
  5133.2  446.94  5191.6  449.63  5273.6  451.77  5343.8  451.14  5470.1  452.03
  5554.4  452.79  5764.9  457.90  5845.2  460.36  5895.3  463.98  5972.4  466.91
#Mann=7,-1,0
  4180.9    0.16       0  4237.3    0.12       0  4334.7    0.16       0
  4659.6    0.12       0  4997.2    0.07       0  5008.5    0.12       0
  5191.6    0.05       0
Bank Sta=4676,5470.1
Exp/Cntr=0.3,0.1

Type RM Length L Ch R = 1,57641,875,875,875
BEGIN DESCRIPTION:
RUNNING CREEK 49.0
END DESCRIPTION:
XS GIS Cut Line= 3
      2876924.97      7070624.98      2875878.19      7069857.11
      2875101.35      7069825.64
#Sta/Elev= 30
  3877.0  475.41  4112.6  465.18  4135.1  466.14  4327.3  457.28  4499.6  452.15
  4601.3  450.73  4785.0  445.26  4814.3  447.21  4964.8  448.42  4985.7  447.84
  4987.5  445.26  4988.1  444.46  4998.8  445.26  5015.0  448.08  5078.9  450.73
  5127.6  454.08  5172.5  459.01  5228.8  462.87  5278.5  465.81  5347.2  462.74
  5468.7  461.03  5518.7  462.27  5590.6  459.81  5618.8  458.62  5628.8  456.09
  5638.8  458.84  5660.2  459.45  5788.9  463.38  5828.9  461.16  5952.7  465.83
#Mann=9,-1,0
  3877.0    0.05       0  4499.6    0.07       0  4987.5    0.07       0
  4998.8    0.07       0  5127.6    0.12       0  5172.5    0.16       0
  5228.8    0.05       0  5590.6    0.16       0  5660.2    0.05       0
Bank Sta=4601.3,5078.9
Exp/Cntr=0.3,0.1

Type RM Length L Ch R = 1,56766,91,91,91
BEGIN DESCRIPTION:
Mapping XS df35e63a
END DESCRIPTION:
XS GIS Cut Line= 3
      2877278.46      7069773.56      2876573.56      7069724.94
      2875888.07      7069718.02
#Sta/Elev= 30
  4395.1  466.98  4468.7  464.33  4508.8  460.34  4588.1  458.03  4619.1  455.13
  4669.2  454.01  4757.6  449.36  4768.9  449.01  4849.6  446.88  4929.8  446.74
  4949.9  445.84  4979.9  446.78  4984.3  442.73  4984.9  441.93  4995.0  441.93
  4995.7  442.73  5010.0  447.00  5040.1  446.22  5098.4  447.28  5250.2  447.26
  5280.2  446.30  5310.2  447.75  5360.2  446.97  5449.8  449.01  5550.3  457.27
  5588.1  460.04  5680.3  462.20  5720.3  465.07  5750.3  465.14  5787.2  467.17
#Mann=5,-1,0
  4395.1    0.08       0  4757.6    0.05       0  4984.3    0.04       0
  4995.7    0.05       0  5550.3    0.08       0
Bank Sta=4768.9,5449.8
Exp/Cntr=0.3,0.1

Type RM Length L Ch R = 1,56675,804,804,804
BEGIN DESCRIPTION:
RUNNING CREEK 48.0
END DESCRIPTION:
XS GIS Cut Line= 2
      2877208.98      7069672.86      2875949.30      7069617.34
#Sta/Elev= 30
  4435.6  460.13  4549.7  454.49  4626.9  451.92  4659.8  450.23  4713.2  448.79
  4739.9  448.08  4813.4  447.71  4860.0  446.09  4910.0  446.92  4930.1  446.49
  4980.1  446.95  4994.4  442.55  4995.1  441.75  5005.2  441.75  5005.8  442.55
  5010.1  446.30  5080.2  445.85  5150.3  446.80  5190.3  445.68  5260.4  446.85
  5290.4  448.97  5303.1  448.79  5320.3  450.40  5400.5  454.81  5440.6  458.94
  5460.6  460.03  5500.6  463.84  5540.6  466.65  5605.7  468.55  5696.5  470.27
#Mann=7,-1,0
  4435.6    0.16       0  4626.9    0.05       0  4813.4    0.07       0
  4994.4    0.07       0  5005.8    0.07       0  5320.3    0.16       0
  5605.7    0.05       0
Bank Sta=4713.2,5303.1
Exp/Cntr=0.3,0.1

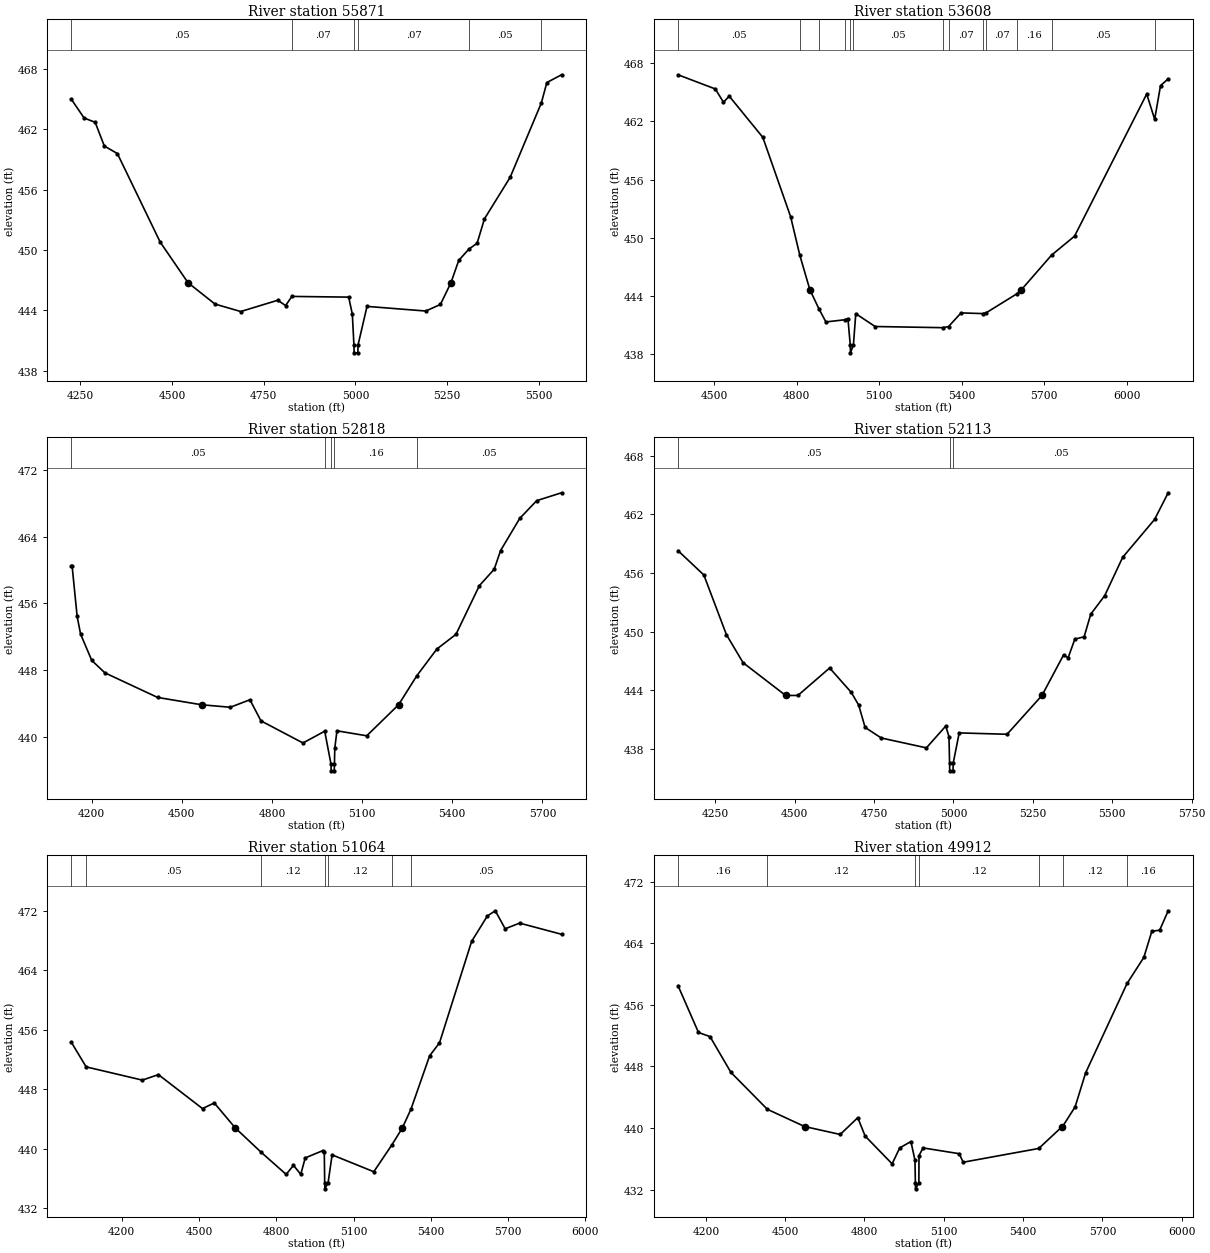
Type RM Length L Ch R = 1,55871,2263,2263,2263
BEGIN DESCRIPTION:
RUNNING CREEK 47.0
END DESCRIPTION:
XS GIS Cut Line= 3
      2877521.45      7069332.57      2876948.56      7069117.30
      2876225.00      7069125.00
#Sta/Elev= 30
  4226.1  464.96  4260.8  463.10  4291.0  462.67  4315.9  460.32  4351.5  459.57
  4468.0  450.79  4544.0  446.75  4617.6  444.63  4687.6  443.89  4788.5  445.01
  4809.9  444.48  4826.9  445.39  4981.7  445.32  4991.7  443.64  4996.0  440.59
  4996.6  439.79  5006.7  439.79  5007.4  440.59  5031.7  444.40  5191.7  443.94
  5231.7  444.59  5260.4  446.75  5281.7  448.97  5309.2  450.08  5331.7  450.67
  5351.7  453.09  5421.7  457.21  5506.8  464.60  5521.7  466.62  5561.7  467.39
#Mann=6,-1,0
  4226.1    0.05       0  4826.9    0.07       0  4996.0    0.07       0
  5007.4    0.07       0  5309.2    0.05       0  5506.8    0.16       0
Bank Sta=4544,5260.4
Exp/Cntr=0.3,0.1

Type RM Length L Ch R = 1,53608,790,790,790
BEGIN DESCRIPTION:
RUNNING CREEK 46.0
END DESCRIPTION:
XS GIS Cut Line= 3
      2877474.98      7067775.01      2876975.00      7068125.00
      2876225.03      7069024.96
#Sta/Elev= 30
  4368.4  466.78  4504.0  465.32  4533.6  463.95  4554.5  464.58  4676.6  460.34
  4777.7  452.17  4811.2  448.19  4847.7  444.65  4881.1  442.66  4905.9  441.34
  4976.3  441.57  4985.9  441.69  4994.5  438.96  4995.1  438.16  5005.9  438.96
  5014.5  442.19  5084.8  440.87  5329.8  440.75  5351.6  440.86  5397.2  442.27
  5476.5  442.20  5489.0  442.29  5601.4  444.26  5616.4  444.65  5726.3  448.22
  5809.8  450.17  6072.1  464.80  6101.0  462.20  6122.3  465.66  6150.2  466.36
#Mann=13,-1,0
  4368.4    0.05       0  4811.2    0.07       0  4881.1    0.12       0
  4976.3    0.05       0  4994.5    0.07       0  5005.9    0.05       0
  5329.8    0.05       0  5351.6    0.07       0  5476.5    0.05       0
  5489.0    0.07       0  5601.4    0.16       0  5726.3    0.05       0
  6101.0    0.16       0
Bank Sta=4847.7,5616.4
Exp/Cntr=0.3,0.1

Type RM Length L Ch R = 1,52818,705,705,705
BEGIN DESCRIPTION:
RUNNING CREEK 45.0
END DESCRIPTION:
XS GIS Cut Line= 3
      2877224.99      7067725.00      2876608.28      7067862.09
      2875888.90      7068555.47
#Sta/Elev= 30
  4132.7  460.48  4135.2  460.48  4151.9  454.45  4163.4  452.32  4200.5  449.17
  4244.1  447.68  4419.5  444.73  4565.9  443.85  4661.5  443.55  4726.8  444.45
  4763.6  441.92  4903.3  439.27  4975.7  440.68  4996.6  436.73  4997.2  435.93
  5007.4  435.93  5008.0  436.73  5009.2  438.65  5016.4  440.73  5115.5  440.13
  5221.4  443.85  5282.0  447.32  5348.8  450.53  5412.4  452.29  5490.3  458.13
  5539.7  460.10  5560.8  462.33  5624.6  466.19  5681.2  468.32  5763.6  469.26
#Mann=5,-1,0
  4132.7    0.05       0  4975.7    0.16       0  4996.6    0.07       0
  5008.0    0.16       0  5282.0    0.05       0
Bank Sta=4565.9,5221.4
Exp/Cntr=0.3,0.1

Type RM Length L Ch R = 1,52113,1049,1049,1049
BEGIN DESCRIPTION:
RUNNING CREEK 44.0
END DESCRIPTION:
XS GIS Cut Line= 3
      2877075.03      7067275.00      2876225.00      7067425.00
      2875825.02      7067974.97
#Sta/Elev= 30
  4132.9  458.29  4214.2  455.80  4285.2  449.70  4337.7  446.83  4471.7  443.48
  4510.3  443.48  4610.2  446.29  4677.9  443.81  4701.6  442.50  4721.9  440.21
  4772.7  439.13  4914.8  438.12  4975.8  440.35  4985.9  439.27  4987.8  436.57
  4988.4  435.77  4998.6  435.77  4999.3  436.57  5018.1  439.65  5168.8  439.51
  5278.7  443.48  5346.5  447.61  5361.2  447.34  5382.1  449.24  5411.4  449.48
  5432.3  451.79  5476.4  453.70  5532.8  457.61  5633.2  461.48  5676.1  464.21
#Mann=3,-1,0
  4132.9    0.05       0  4987.8    0.03       0  4999.3    0.05       0
Bank Sta=4471.7,5278.7
Exp/Cntr=0.3,0.1

Type RM Length L Ch R = 1,51064,1152,1152,1152
BEGIN DESCRIPTION:
RUNNING CREEK 43.0
END DESCRIPTION:
XS GIS Cut Line= 3
      2877400.71      7067106.51      2876352.10      7066613.46
      2875622.98      7066467.63
#Sta/Elev= 30
  4005.0  454.30  4062.4  451.00  4280.4  449.22  4342.8  449.96  4514.0  445.39
  4559.6  446.15  4641.2  442.79  4742.4  439.49  4838.7  436.54  4867.0  437.76
  4895.3  436.55  4912.6  438.76  4981.0  439.74  4986.6  439.56  4988.2  435.40
  4988.8  434.60  5001.3  435.40  5016.9  439.17  5178.7  436.90  5249.1  440.52
  5289.6  442.79  5323.4  445.35  5395.3  452.48  5433.7  454.23  5558.5  467.88
  5619.7  471.30  5650.3  471.99  5688.6  469.57  5744.7  470.33  5907.3  468.83
#Mann=7,-1,0
  4005.0    0.16       0  4062.4    0.05       0  4742.4    0.12       0
  4988.2    0.07       0  5001.3    0.12       0  5249.1    0.16       0
  5323.4    0.05       0
Bank Sta=4641.2,5289.6
Exp/Cntr=0.3,0.1

Type RM Length L Ch R = 1,49912,1049,1049,1049
BEGIN DESCRIPTION:
RUNNING CREEK 42.0
END DESCRIPTION:
XS GIS Cut Line= 3
      2877810.47      7066585.70      2876893.77      7066009.29
      2876122.93      7066009.29
#Sta/Elev= 30
  4094.9  458.50  4172.2  452.42  4215.9  451.88  4294.9  447.23  4432.7  442.43
  4573.7  440.19  4708.2  439.16  4774.7  441.34  4802.5  438.95  4904.6  435.34
  4933.2  437.41  4975.6  438.24  4990.9  435.82  4992.5  432.89  4993.1  432.09
  5005.7  432.89  5006.2  436.41  5021.5  437.41  5158.1  436.66  5173.4  435.55
  5459.1  437.34  5548.1  440.19  5550.8  440.28  5596.5  442.74  5636.5  447.18
  5793.1  458.79  5856.5  462.18  5886.5  465.55  5916.5  465.73  5948.6  468.24
#Mann=7,-1,0
  4094.9    0.16       0  4432.7    0.12       0  4992.5    0.07       0
  5005.7    0.12       0  5459.1    0.16       0  5550.8    0.12       0
  5793.1    0.16       0
Bank Sta=4573.7,5548.1
Exp/Cntr=0.3,0.1

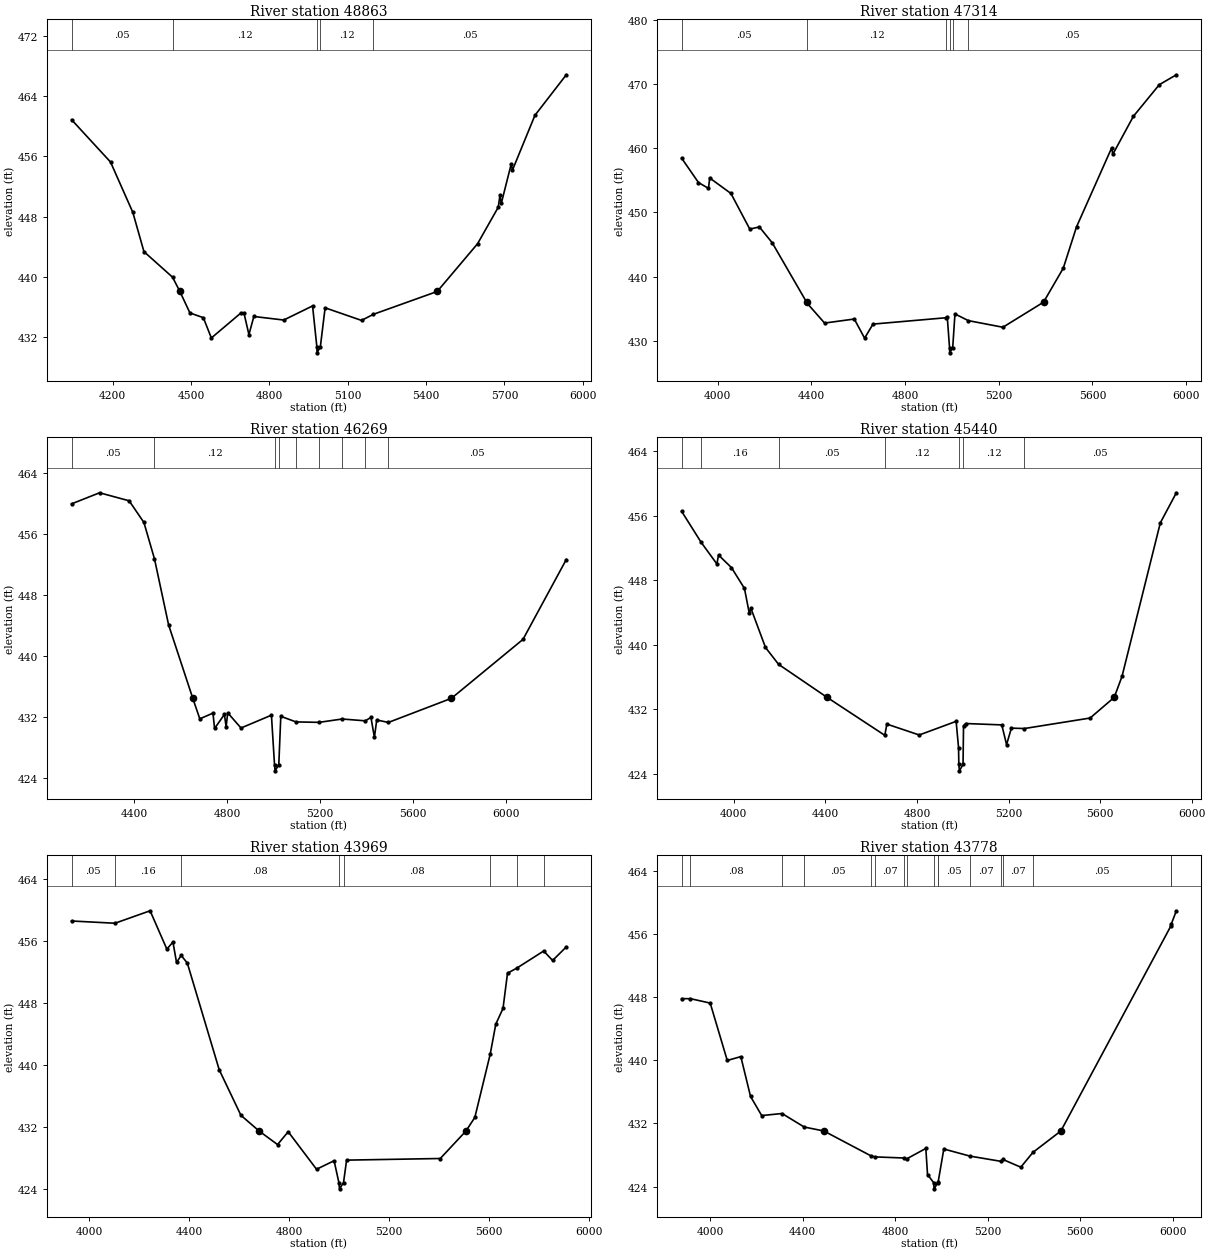
Type RM Length L Ch R = 1,48863,1549,1549,1549
BEGIN DESCRIPTION:
RUNNING CREEK 41.0
END DESCRIPTION:
XS GIS Cut Line= 3
      2878213.20      7065877.33      2877907.25      7065605.13
      2876461.07      7065273.60
#Sta/Elev= 30
  4043.4  460.87  4192.4  455.26  4277.7  448.59  4320.3  443.38  4429.8  439.99
  4457.8  438.10  4496.3  435.25  4547.6  434.62  4578.3  431.93  4691.2  435.24
  4703.1  435.23  4722.0  432.38  4740.9  434.78  4855.3  434.31  4965.6  436.18
  4982.0  430.76  4982.7  429.96  4995.4  430.76  5013.6  435.93  5152.9  434.26
  5198.5  435.07  5442.7  438.10  5596.9  444.42  5676.1  449.26  5682.7  450.85
  5687.8  449.77  5725.6  454.97  5730.7  454.20  5816.5  461.45  5936.6  466.83
#Mann=5,-1,0
  4043.4    0.05       0  4429.8    0.12       0  4982.0    0.07       0
  4995.4    0.12       0  5198.5    0.05       0
Bank Sta=4457.8,5442.7
Exp/Cntr=0.3,0.1

Type RM Length L Ch R = 1,47314,1045,1045,1045
BEGIN DESCRIPTION:
RUNNING CREEK 40.0
END DESCRIPTION:
XS GIS Cut Line= 4
      2878286.54      7065858.33      2878185.17      7065419.07
      2877808.43      7064700.94      2877006.33      7064419.52
#Sta/Elev= 30
  3846.5  458.45  3918.3  454.66  3961.1  453.75  3966.2  455.37  4056.9  452.96
  4137.3  447.42  4178.3  447.75  4233.1  445.29  4379.9  436.05  4382.0  435.89
  4456.7  432.80  4583.4  433.43  4627.5  430.45  4663.3  432.64  4975.4  433.63
  4980.4  433.74  4990.1  428.97  4990.8  428.17  5003.6  428.97  5013.2  434.22
  5070.4  433.18  5217.9  432.15  5391.3  436.05  5475.5  441.33  5532.2  447.77
  5681.9  460.03  5687.2  459.06  5774.9  464.96  5885.5  469.88  5958.3  471.42
#Mann=6,-1,0
  3846.5    0.05       0  4382.0    0.12       0  4975.4    0.16       0
  4990.1    0.07       0  5003.6    0.16       0  5070.4    0.05       0
Bank Sta=4379.9,5391.3
Exp/Cntr=0.3,0.1

Type RM Length L Ch R = 1,46269,829,829,829
BEGIN DESCRIPTION:
Mapping XS 47307ede
END DESCRIPTION:
XS GIS Cut Line= 3
      2879081.25      7064879.06      2878612.52      7064384.29
      2877175.04      7064207.21
#Sta/Elev= 30
  4130.8  459.91  4251.2  461.36  4378.6  460.31  4442.2  457.47  4487.7  452.70
  4548.5  444.05  4652.6  434.44  4682.8  431.75  4739.5  432.50  4746.4  430.49
  4788.8  432.33  4796.1  430.69  4803.0  432.54  4860.2  430.55  4991.2  432.23
  5004.5  425.74  5007.0  424.94  5022.9  425.74  5031.5  432.08  5096.7  431.35
  5196.3  431.29  5295.8  431.73  5395.3  431.49  5419.7  431.94  5434.5  429.32
  5444.6  431.60  5494.8  431.28  5766.2  434.44  6074.3  442.16  6260.7  452.62
#Mann=9,-1,0
  4130.8    0.05       0  4487.7    0.12       0  5004.5    0.07       0
  5022.9    0.12       0  5096.7    0.05       0  5196.3    0.07       0
  5295.8    0.12       0  5395.3    0.07       0  5494.8    0.05       0
Bank Sta=4652.6,5766.2
Exp/Cntr=0.3,0.1

Type RM Length L Ch R = 1,45440,1471,1471,1471
BEGIN DESCRIPTION:
RUNNING CREEK 39.0
END DESCRIPTION:
XS GIS Cut Line= 3
      2879648.98      7064498.88      2878883.35      7063759.29
      2877838.26      7063426.52
#Sta/Elev= 30
  3771.9  456.52  3857.1  452.68  3926.0  450.00  3933.0  451.11  3989.6  449.55
  4046.2  446.98  4067.5  443.89  4074.5  444.51  4138.2  439.66  4195.4  437.57
  4407.2  433.48  4659.5  428.78  4668.4  430.17  4809.9  428.82  4971.1  430.51
  4981.6  427.27  4982.9  425.18  4985.4  424.38  5001.3  425.18  5003.4  429.96
  5013.1  430.24  5170.5  430.07  5191.4  427.63  5212.5  429.67  5269.1  429.62
  5556.4  430.92  5661.8  433.48  5695.8  436.08  5863.2  455.10  5933.2  458.82
#Mann=7,-1,0
  3771.9    0.05       0  3857.1    0.16       0  4195.4    0.05       0
  4659.5    0.12       0  4982.9    0.07       0  5001.3    0.12       0
  5269.1    0.05       0
Bank Sta=4407.2,5661.8
Exp/Cntr=0.3,0.1

Type RM Length L Ch R = 1,43969,191,191,191
BEGIN DESCRIPTION:
RUNNING CREEK 38.0
END DESCRIPTION:
XS GIS Cut Line= 5
      2879971.89      7064113.47      2880044.81      7063738.46
      2879857.31      7063509.29      2879258.35      7062853.04
      2878879.31      7062688.36
#Sta/Elev= 30
  3930.1  458.57  4103.7  458.28  4244.3  459.89  4311.3  454.94  4335.8  455.84
  4350.1  453.21  4368.6  454.12  4393.2  453.14  4521.0  439.34  4607.8  433.46
  4681.1  431.42  4754.4  429.68  4797.0  431.34  4910.4  426.49  4980.7  427.59
  4999.9  424.76  5002.4  423.96  5018.4  424.76  5030.7  427.67  5405.7  427.88
  5508.1  431.42  5544.0  433.19  5605.5  441.36  5627.8  445.24  5656.7  447.27
  5674.7  451.82  5712.4  452.49  5819.4  454.69  5855.2  453.47  5910.0  455.22
#Mann=8,-1,0
  3930.1    0.05       0  4103.7    0.16       0  4368.6    0.08       0
  4999.9    0.07       0  5018.4    0.08       0  5605.5    0.16       0
  5712.4    0.08       0  5819.4    0.05       0
Bank Sta=4681.1,5508.1
Exp/Cntr=0.3,0.1

Type RM Length L Ch R = 1,43778,1170,1170,1170
BEGIN DESCRIPTION:
RUNNING CREEK 37.0
END DESCRIPTION:
XS GIS Cut Line= 5
      2880201.06      7064009.32      2880253.42      7063664.76
      2879898.98      7063269.71      2879306.76      7062632.50
      2878945.83      7062488.44
#Sta/Elev= 30
  3877.7  447.79  3915.9  447.79  4001.1  447.23  4074.8  439.97  4133.4  440.46
  4175.4  435.42  4223.6  433.00  4311.5  433.26  4407.4  431.55  4492.2  431.05
  4696.6  427.89  4714.2  427.77  4839.7  427.63  4850.0  427.52  4932.9  428.84
  4940.2  425.54  4966.2  424.53  4968.7  423.73  4984.7  424.53  4986.5  424.65
  5010.6  428.77  5123.6  427.87  5259.5  427.20  5265.5  427.45  5343.3  426.47
  5396.0  428.35  5516.5  431.05  5991.9  456.99  5993.8  457.24  6015.5  458.91
#Mann=17,-1,0
  3877.7    0.16       0  3915.9    0.08       0  4311.5    0.07       0
  4407.4    0.05       0  4696.6    0.08       0  4714.2    0.07       0
  4839.7    0.08       0  4850.0    0.16       0  4966.2    0.03       0
  4984.7    0.16       0  4986.5    0.05       0  5123.6    0.07       0
  5259.5    0.05       0  5265.5    0.07       0  5396.0    0.05       0
  5991.9    0.08       0  5993.8    0.05       0
Bank Sta=4492.2,5516.5
Exp/Cntr=0.3,0.1