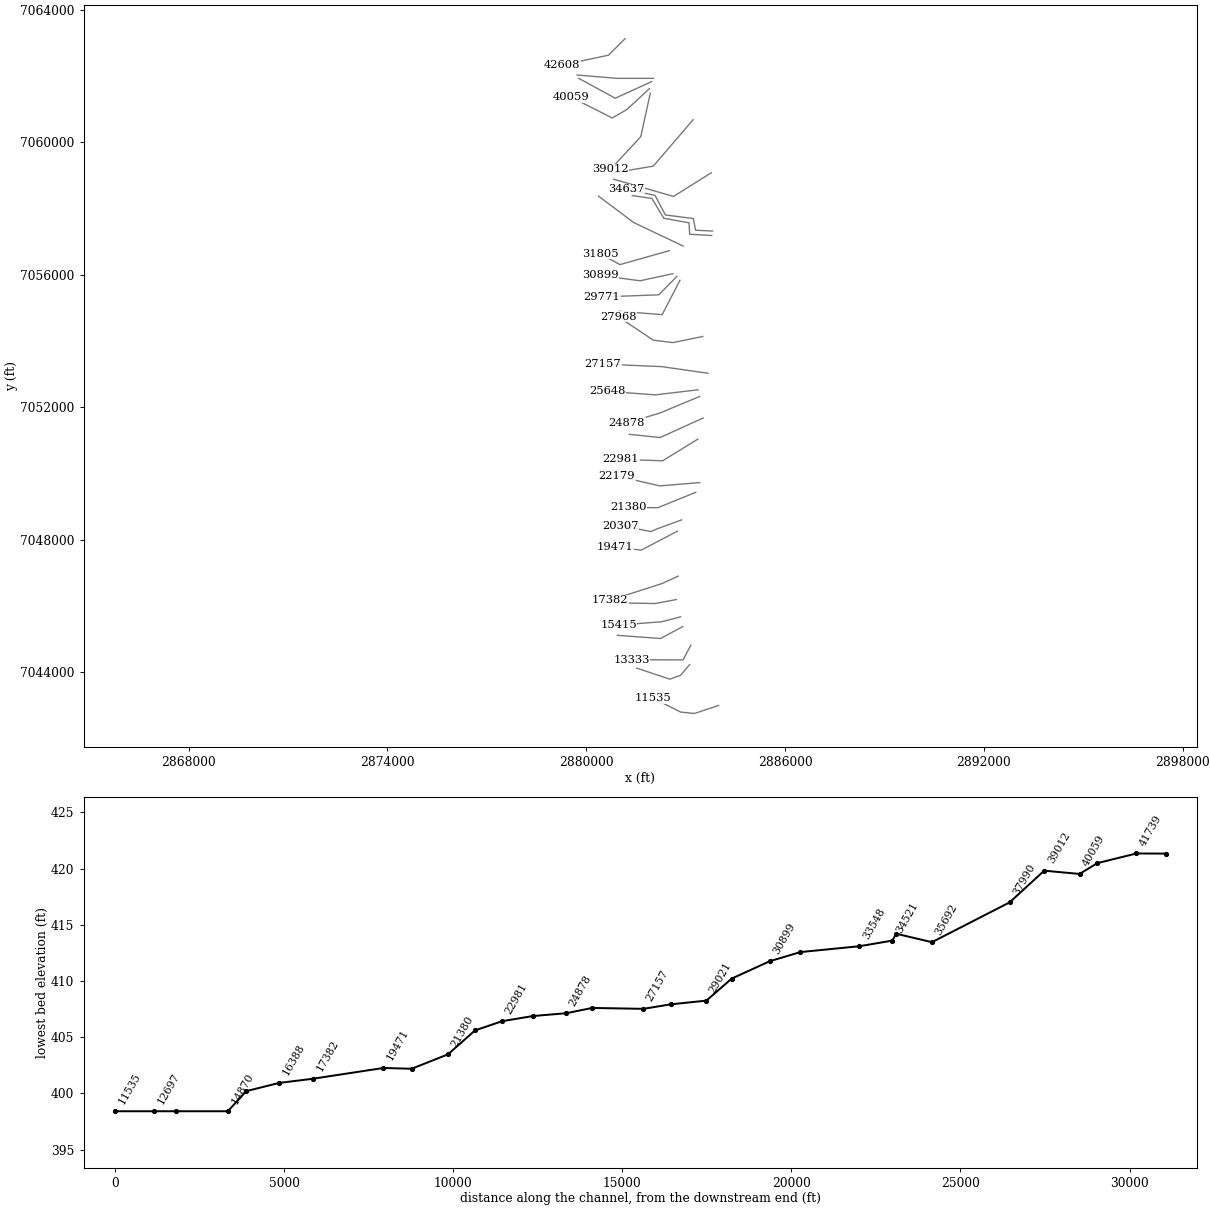
HEC-RAS study RUNNING CREEK.prj: RUNNING CREEK Base Level Engineering

--- RUNNING CREEK.g01 (geometry) --- (continued)

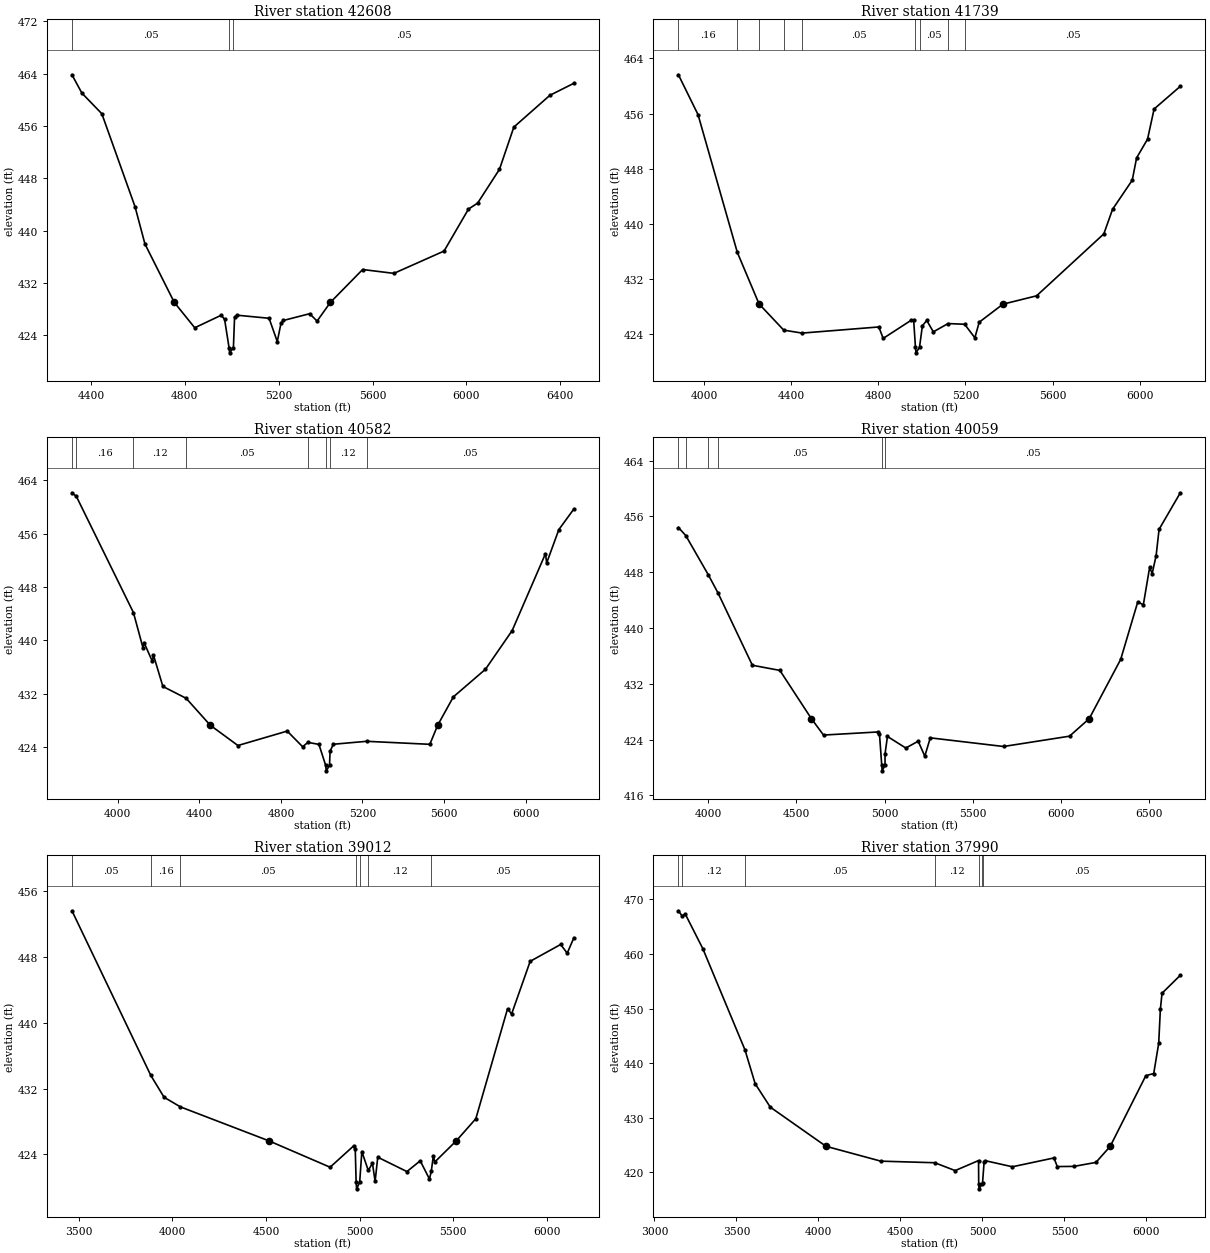
Type RM Length L Ch R = 1,42608,869,869,869
BEGIN DESCRIPTION:
RUNNING CREEK 36.0
END DESCRIPTION:
XS GIS Cut Line= 3
      2881175.01      7063125.01      2880675.00      7062625.00
      2879275.01      7062325.00
#Sta/Elev= 30
  4318.9  463.81  4361.3  461.01  4446.2  457.86  4587.6  443.67  4630.0  437.96
  4755.0  429.04  4842.2  425.16  4955.3  427.08  4969.5  426.43  4988.4  422.13
  4990.9  421.33  5007.0  422.13  5011.9  426.79  5022.5  427.08  5159.0  426.61
  5193.9  423.05  5210.1  425.91  5220.3  426.28  5332.0  427.31  5363.5  426.18
  5420.3  429.04  5557.8  434.06  5690.8  433.47  5904.7  436.88  6008.7  443.29
  6047.9  444.21  6140.8  449.37  6202.1  455.82  6355.5  460.67  6457.8  462.51
#Mann=3,-1,0
  4318.9    0.05       0  4988.4    0.03       0  5007.0    0.05       0
Bank Sta=4755,5420.3
Exp/Cntr=0.3,0.1

Type RM Length L Ch R = 1,41739,1157,1157,1157
BEGIN DESCRIPTION:
RUNNING CREEK 35.0
END DESCRIPTION:
XS GIS Cut Line= 3
      2882024.96      7061925.00      2880925.00      7061925.00
      2879725.02      7062025.00
#Sta/Elev= 30
  3882.1  461.62  3972.1  455.85  4152.4  435.90  4251.4  428.49  4253.3  428.39
  4365.6  424.63  4449.5  424.20  4802.1  425.09  4822.1  423.43  4952.1  426.09
  4962.1  426.03  4970.3  422.14  4972.8  421.34  4988.9  422.14  5002.1  425.26
  5022.2  426.03  5052.3  424.38  5120.1  425.58  5196.1  425.48  5243.0  423.52
  5263.0  425.78  5372.0  428.39  5526.4  429.60  5835.0  438.57  5875.1  442.13
  5965.5  446.35  5985.5  449.58  6035.7  452.29  6065.8  456.66  6186.2  459.95
#Mann=9,-1,0
  3882.1    0.16       0  4152.4    0.12       0  4251.4    0.05       0
  4365.6    0.12       0  4449.5    0.05       0  4970.3    0.03       0
  4988.9    0.05       0  5120.1    0.12       0  5196.1    0.05       0
Bank Sta=4253.3,5372
Exp/Cntr=0.3,0.1

Type RM Length L Ch R = 1,40582,523,523,523
BEGIN DESCRIPTION:
RUNNING CREEK 34.0
END DESCRIPTION:
XS GIS Cut Line= 3
      2881974.98      7061824.99      2880875.00      7061325.00
      2879774.98      7061925.01
#Sta/Elev= 30
  3775.3  462.10  3796.9  461.56  4076.8  444.17  4123.5  438.91  4129.0  439.67
  4169.6  436.86  4175.1  437.80  4221.3  433.11  4335.2  431.34  4453.5  427.31
  4589.2  424.27  4830.9  426.43  4906.7  424.08  4932.2  424.74  4986.4  424.44
  5019.8  421.28  5022.3  420.48  5038.4  421.28  5041.0  423.41  5057.1  424.46
  5220.4  424.90  5530.3  424.45  5568.9  427.31  5645.7  431.55  5803.3  435.69
  5934.2  441.48  6097.5  452.99  6103.2  451.59  6163.0  456.59  6236.6  459.67
#Mann=8,-1,0
  3775.3    0.05       0  3796.9    0.16       0  4076.8    0.12       0
  4335.2    0.05       0  4932.2    0.12       0  5019.8    0.07       0
  5038.4    0.12       0  5220.4    0.05       0
Bank Sta=4453.5,5568.9
Exp/Cntr=0.3,0.1

Type RM Length L Ch R = 1,40059,1047,1047,1047
BEGIN DESCRIPTION:
RUNNING CREEK 33.0
END DESCRIPTION:
XS GIS Cut Line= 4
      2881907.69      7061614.61      2881224.73      7060982.31
      2880787.87      7060729.17      2879529.56      7061362.66
#Sta/Elev= 30
  3831.2  454.41  3872.8  453.26  4000.8  447.62  4056.1  445.00  4250.3  434.66
  4406.2  433.92  4585.1  426.99  4653.5  424.65  4964.9  425.10  4970.7  424.78
  4983.5  420.32  4986.0  419.52  5002.1  420.32  5002.2  421.96  5015.9  424.45
  5119.8  422.79  5190.2  423.77  5227.5  421.62  5258.6  424.25  5673.8  423.01
  6047.6  424.49  6159.0  426.99  6337.7  435.50  6434.4  443.74  6466.0  443.33
  6501.6  448.68  6516.2  447.81  6538.5  450.39  6555.2  454.15  6675.6  459.39
#Mann=6,-1,0
  3831.2    0.16       0  3872.8    0.05       0  4000.8    0.16       0
  4056.1    0.05       0  4983.5    0.03       0  5002.1    0.05       0
Bank Sta=4585.1,6159
Exp/Cntr=0.3,0.1

Type RM Length L Ch R = 1,39012,1022,1022,1022
BEGIN DESCRIPTION:
RUNNING CREEK 32.0
END DESCRIPTION:
XS GIS Cut Line= 3
      2881933.71      7061475.73      2881647.24      7060164.93
      2880735.81      7059184.06
#Sta/Elev= 30
  3463.1  453.64  3884.0  433.62  3955.2  430.95  4042.5  429.78  4514.0  425.66
  4841.9  422.44  4968.9  425.06  4976.2  424.65  4981.0  420.61  4983.5  419.81
  4999.9  420.61  5011.4  424.34  5045.8  422.05  5068.1  422.92  5082.3  420.71
  5096.4  423.66  5252.3  421.91  5323.2  423.22  5372.5  421.01  5382.2  421.92
  5393.5  423.86  5400.8  423.07  5516.2  425.66  5620.2  428.34  5789.7  441.72
  5811.3  441.08  5910.5  447.49  6073.2  449.54  6108.3  448.48  6143.8  450.35
#Mann=7,-1,0
  3463.1    0.05       0  3884.0    0.16       0  4042.5    0.05       0
  4981.0    0.03       0  4999.9    0.05       0  5045.8    0.12       0
  5382.2    0.05       0
Bank Sta=4514,5516.2
Exp/Cntr=0.3,0.1

Type RM Length L Ch R = 1,37990,2298,2298,2298
BEGIN DESCRIPTION:
RUNNING CREEK 31.0
END DESCRIPTION:
XS GIS Cut Line= 3
      2883225.01      7060675.01      2882025.00      7059275.00
      2880824.97      7059075.00
#Sta/Elev= 30
  3146.5  467.91  3168.8  466.97  3188.8  467.28  3295.2  460.98  3552.3  442.44
  3614.6  436.23  3706.8  431.95  4046.5  424.78  4380.7  422.06  4709.8  421.77
  4834.0  420.33  4976.7  422.17  4977.6  417.79  4980.1  416.99  4996.6  417.79
  5001.1  418.11  5010.7  421.98  5018.3  422.14  5183.0  421.03  5436.5  422.65
  5456.8  421.07  5558.1  421.10  5692.5  421.83  5779.6  424.78  5996.6  437.71
  6044.8  438.11  6075.2  443.64  6085.3  449.86  6095.5  452.81  6207.0  456.10
#Mann=7,-1,0
  3146.5    0.16       0  3168.8    0.12       0  3552.3    0.05       0
  4709.8    0.12       0  4977.6    0.07       0  4996.6    0.12       0
  5001.1    0.05       0
Bank Sta=4046.5,5779.6
Exp/Cntr=0.3,0.1

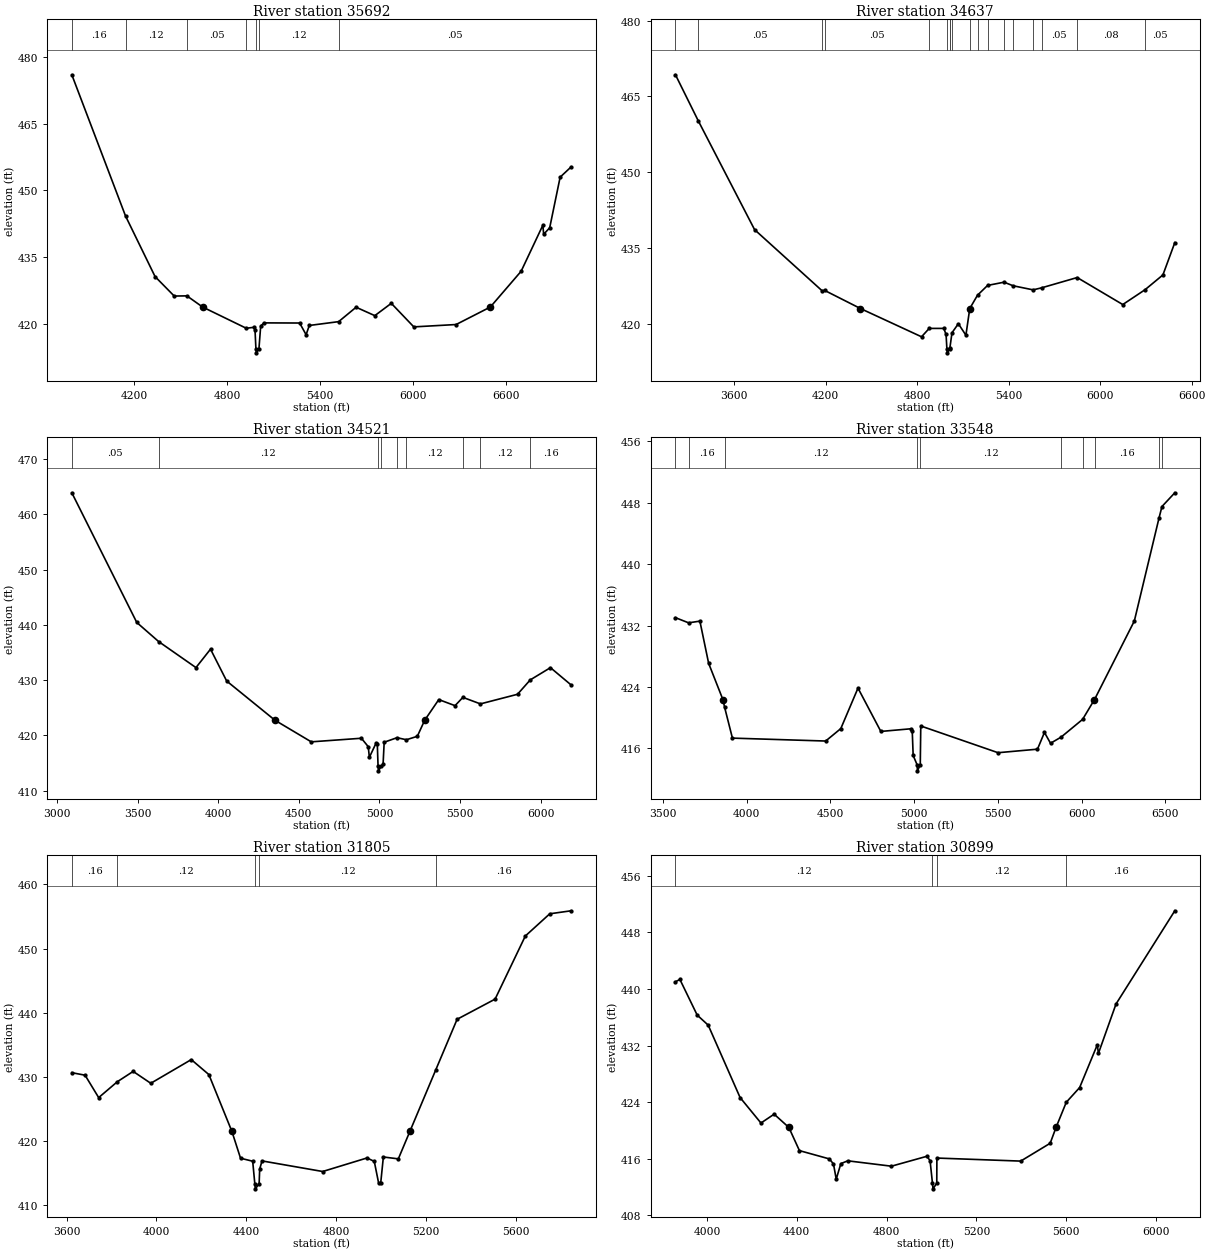
Type RM Length L Ch R = 1,35692,1055,1055,1055
BEGIN DESCRIPTION:
RUNNING CREEK 30.0
END DESCRIPTION:
XS GIS Cut Line= 3
      2883774.96      7059074.97      2882634.43      7058361.39
      2880831.61      7058879.64
#Sta/Elev= 30
  3799.5  476.02  4146.0  444.24  4336.5  430.61  4460.0  426.23  4541.8  426.27
  4643.2  423.76  4925.0  418.98  4975.5  419.20  4981.4  418.50  4987.2  414.25
  4989.7  413.45  5006.3  414.25  5017.9  419.47  5039.1  420.19  5269.1  420.16
  5310.8  417.53  5331.6  419.61  5520.7  420.47  5633.3  423.71  5754.1  421.82
  5860.4  424.59  6005.6  419.29  6278.4  419.82  6499.4  423.76  6698.0  431.81
  6838.1  442.17  6843.3  440.13  6882.2  441.59  6949.6  452.98  7020.7  455.30
#Mann=7,-1,0
  3799.5    0.16       0  4146.0    0.12       0  4541.8    0.05       0
  4925.0    0.12       0  4987.2    0.07       0  5006.3    0.12       0
  5520.7    0.05       0
Bank Sta=4643.2,6499.4
Exp/Cntr=0.3,0.1

Type RM Length L Ch R = 1,34637,116,116,116
BEGIN DESCRIPTION:
Mapping XS 47aac5d2
END DESCRIPTION:
XS GIS Cut Line= 6
      2883813.00      7057316.26      2883300.89      7057342.30
      2883231.45      7057693.87      2882389.43      7057802.37
      2882076.93      7058392.65      2881218.74      7058574.57
#Sta/Elev= 30
  3213.9  469.30  3363.1  460.20  3732.9  438.61  4176.8  426.47  4191.8  426.58
  4427.4  422.98  4828.1  417.38  4878.3  419.04  4974.1  419.04  4989.0  417.84
  4994.4  415.00  4996.9  414.20  5013.5  415.00  5013.9  415.14  5027.9  418.18
  5069.6  419.97  5119.2  417.69  5144.4  422.98  5144.7  422.99  5195.2  425.62
  5261.4  427.56  5369.4  428.20  5428.9  427.49  5560.1  426.68  5615.4  427.08
  5849.1  429.12  6148.1  423.77  6294.4  426.71  6411.5  429.64  6489.5  436.04
#Mann=18,-1,0
  3213.9    0.08       0  3363.1    0.05       0  4176.8    0.12       0
  4191.8    0.05       0  4878.3    0.08       0  4994.4    0.07       0
  5013.5    0.08       0  5013.9    0.12       0  5027.9    0.05       0
  5144.7    0.12       0  5195.2    0.08       0  5261.4    0.05       0
  5369.4     0.1       0  5428.9    0.05       0  5560.1    0.12       0
  5615.4    0.05       0  5849.1    0.08       0  6294.4    0.05       0
Bank Sta=4427.4,5144.4
Exp/Cntr=0.3,0.1

Type RM Length L Ch R = 1,34521,973,973,973
BEGIN DESCRIPTION:
RUNNING CREEK 29.0
END DESCRIPTION:
XS GIS Cut Line= 6
      2883786.98      7057181.71      2883122.94      7057220.78
      2883100.58      7057564.84      2882341.69      7057702.55
      2881981.45      7058301.51      2881388.05      7058387.08
#Sta/Elev= 30
  3092.7  463.93  3495.4  440.45  3631.1  436.99  3862.3  432.28  3952.5  435.62
  4052.7  429.85  4352.0  422.75  4577.0  418.84  4887.9  419.49  4930.4  417.96
  4937.2  416.03  4979.8  418.67  4986.5  418.41  4991.2  414.39  4993.7  413.59
  5010.3  414.39  5022.3  414.82  5029.1  418.77  5108.6  419.59  5166.8  419.22
  5234.5  419.84  5280.2  422.75  5367.6  426.49  5468.3  425.39  5517.0  426.89
  5625.7  425.71  5855.6  427.45  5934.4  430.05  6059.9  432.27  6188.2  429.13
#Mann=9,-1,0
  3092.7    0.05       0  3631.1    0.12       0  4991.2    0.07       0
  5010.3    0.12       0  5108.6    0.08       0  5166.8    0.12       0
  5517.0    0.05       0  5625.7    0.12       0  5934.4    0.16       0
Bank Sta=4352,5280.2
Exp/Cntr=0.3,0.1

Type RM Length L Ch R = 1,33548,1743,1743,1743
BEGIN DESCRIPTION:
RUNNING CREEK 28.0
END DESCRIPTION:
XS GIS Cut Line= 3
      2882926.73      7056864.02      2881433.70      7057572.34
      2880371.83      7058370.47
#Sta/Elev= 30
  3575.5  433.03  3653.9  432.36  3721.3  432.58  3773.6  427.08  3859.7  422.31
  3868.6  421.39  3915.5  417.35  4472.2  416.97  4562.5  418.59  4665.1  423.86
  4801.5  418.22  4983.1  418.57  4988.9  418.31  4994.5  415.09  5017.8  413.89
  5020.3  413.09  5036.9  413.89  5039.9  418.93  5501.2  415.45  5736.6  415.91
  5778.2  418.09  5814.4  416.68  5877.0  417.47  6006.0  419.79  6075.2  422.31
  6077.8  422.40  6314.8  432.60  6462.9  446.07  6479.7  447.50  6556.4  449.29
#Mann=10,-1,0
  3575.5    0.12       0  3653.9    0.16       0  3868.6    0.12       0
  5017.8    0.07       0  5036.9    0.12       0  5877.0    0.16       0
  6006.0    0.12       0  6077.8    0.16       0  6462.9    0.12       0
  6479.7    0.16       0
Bank Sta=3859.7,6075.2
Exp/Cntr=0.3,0.1

Type RM Length L Ch R = 1,31805,906,906,906
BEGIN DESCRIPTION:
RUNNING CREEK 27.0
END DESCRIPTION:
XS GIS Cut Line= 3
      2882510.07      7056725.11      2881015.90      7056302.96
      2880428.39      7056626.99
#Sta/Elev= 30
  3623.1  430.66  3682.1  430.27  3742.7  426.78  3826.0  429.26  3896.3  430.86
  3974.7  429.01  4155.0  432.70  4233.3  430.37  4336.0  421.51  4374.4  417.34
  4428.5  416.87  4438.0  413.37  4440.5  412.57  4457.2  413.37  4459.7  415.65
  4470.1  416.92  4740.2  415.27  4937.7  417.38  4970.0  416.84  4989.6  413.42
  4998.8  413.54  5010.4  417.53  5077.1  417.24  5128.4  421.51  5243.9  431.11
  5338.8  438.98  5508.0  442.12  5642.6  451.95  5751.4  455.41  5846.7  455.88
#Mann=5,-1,0
  3623.1    0.16       0  3826.0    0.12       0  4438.0    0.07       0
  4457.2    0.12       0  5243.9    0.16       0
Bank Sta=4336,5128.4
Exp/Cntr=0.3,0.1

Type RM Length L Ch R = 1,30899,1128,1128,1128
BEGIN DESCRIPTION:
RUNNING CREEK 26.0
END DESCRIPTION:
XS GIS Cut Line= 3
      2882614.23      7056030.67      2881628.15      7055815.39
      2880425.00      7055975.00
#Sta/Elev= 30
  3860.1  441.02  3879.8  441.35  3956.8  436.31  4005.8  434.89  4147.8  424.66
  4240.7  421.06  4299.4  422.31  4364.8  420.44  4412.0  417.16  4545.1  415.99
  4563.5  415.28  4575.8  413.13  4596.3  415.32  4627.0  415.72  4821.5  414.96
  4979.5  416.36  4993.6  415.74  5004.2  412.56  5006.7  411.76  5023.4  412.56
  5023.9  416.11  5397.1  415.68  5528.3  418.20  5554.4  420.44  5599.9  423.99
  5659.4  426.07  5738.0  432.11  5743.0  430.90  5821.4  437.88  6083.1  451.05
#Mann=4,-1,0
  3860.1    0.12       0  5004.2    0.07       0  5023.4    0.12       0
  5599.9    0.16       0
Bank Sta=4364.8,5554.4
Exp/Cntr=0.3,0.1

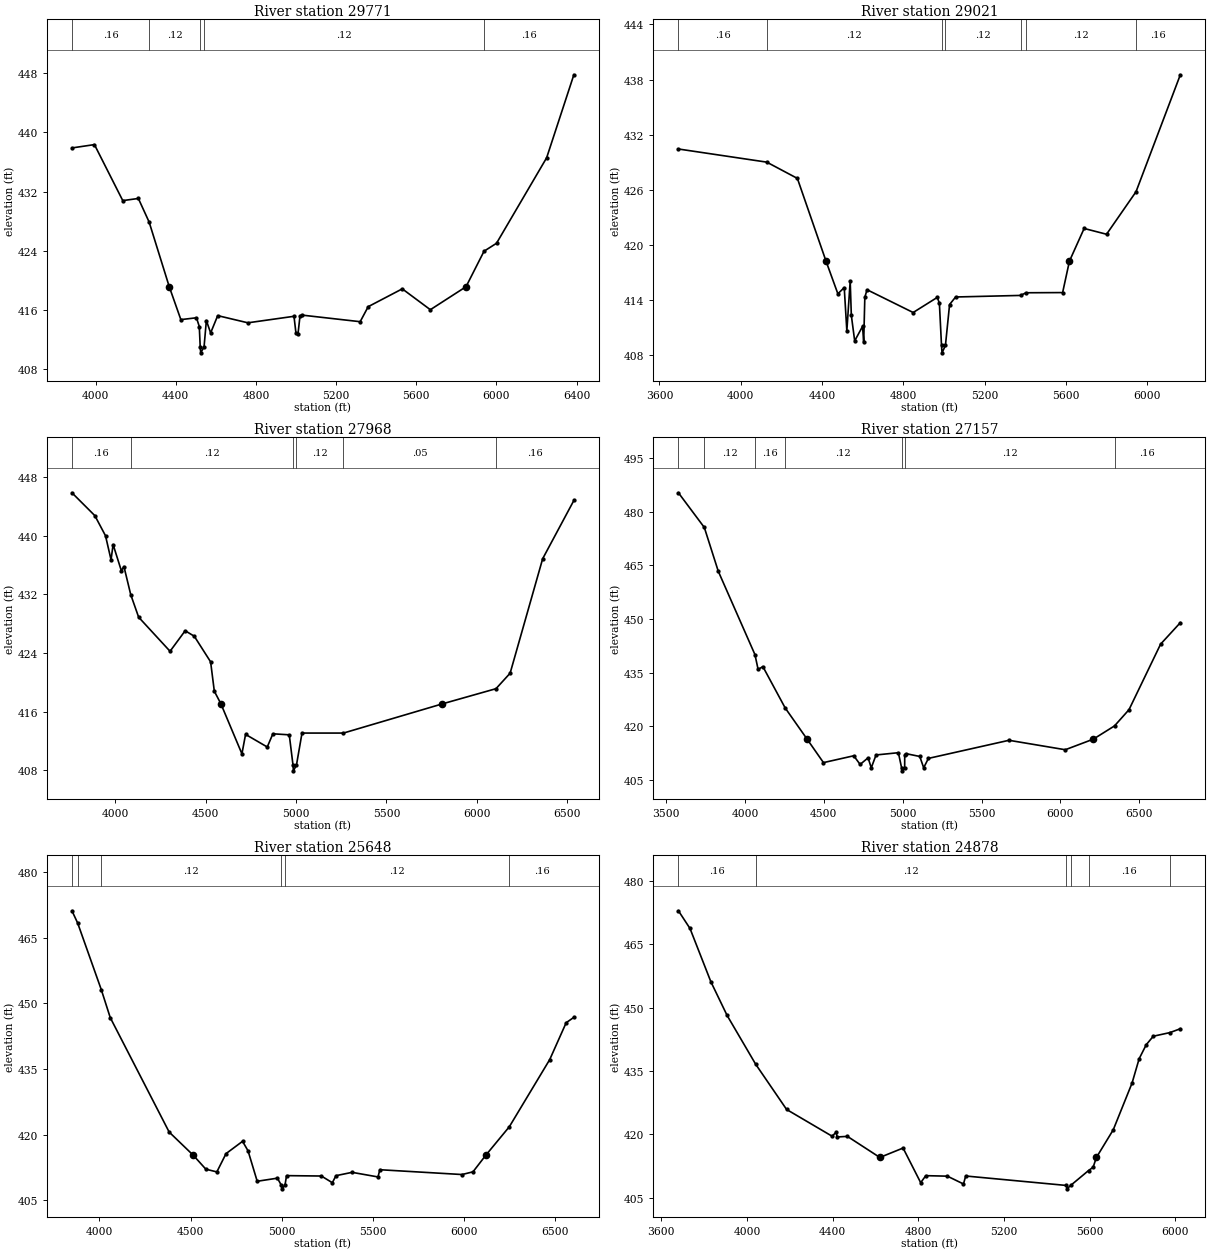
Type RM Length L Ch R = 1,29771,750,750,750
BEGIN DESCRIPTION:
RUNNING CREEK 25.0
END DESCRIPTION:
XS GIS Cut Line= 3
      2882738.49      7055950.16      2882190.65      7055391.78
      2880469.29      7055327.80
#Sta/Elev= 30
  3881.7  437.91  3993.9  438.36  4135.3  430.79  4213.1  431.08  4266.9  427.89
  4367.3  419.15  4425.2  414.70  4503.1  414.95  4517.2  413.77  4521.8  411.01
  4524.3  410.21  4541.0  411.01  4552.5  414.58  4573.8  412.90  4609.1  415.24
  4759.7  414.27  4989.8  415.15  4999.8  412.84  5009.8  412.76  5019.8  415.19
  5029.9  415.31  5320.1  414.42  5360.1  416.45  5530.2  418.86  5670.3  416.04
  5848.4  419.15  5938.3  423.95  6000.5  425.02  6250.7  436.58  6386.5  447.80
#Mann=5,-1,0
  3881.7    0.16       0  4266.9    0.12       0  4521.8    0.07       0
  4541.0    0.12       0  5938.3    0.16       0
Bank Sta=4367.3,5848.4
Exp/Cntr=0.3,0.1

Type RM Length L Ch R = 1,29021,1053,1053,1053
BEGIN DESCRIPTION:
RUNNING CREEK 24.0
END DESCRIPTION:
XS GIS Cut Line= 3
      2882829.55      7055829.31      2882293.06      7054794.44
      2880993.06      7054894.44
#Sta/Elev= 30
  3693.4  430.44  4128.1  429.01  4278.7  427.24  4419.7  418.23  4477.9  414.68
  4509.3  415.35  4522.1  410.64  4538.6  416.07  4544.2  412.33  4560.7  409.55
  4599.4  411.13  4605.0  409.40  4610.6  414.30  4621.5  415.12  4848.4  412.64
  4967.4  414.29  4977.5  413.63  4987.9  409.05  4990.4  408.25  5007.2  409.05
  5027.6  413.51  5057.3  414.33  5376.6  414.50  5403.7  414.79  5583.8  414.81
  5617.3  418.23  5689.6  421.79  5799.9  421.16  5945.0  425.79  6162.9  438.52
#Mann=7,-1,0
  3693.4    0.16       0  4128.1    0.12       0  4987.9    0.07       0
  5007.2    0.12       0  5376.6    0.16       0  5403.7    0.12       0
  5945.0    0.16       0
Bank Sta=4419.7,5617.3
Exp/Cntr=0.3,0.1

Type RM Length L Ch R = 1,27968,811,811,811
BEGIN DESCRIPTION:
RUNNING CREEK 23.0
END DESCRIPTION:
XS GIS Cut Line= 4
      2883517.01      7054134.83      2882611.88      7053949.92
      2882023.98      7054023.73      2880975.03      7054724.98
#Sta/Elev= 30
  3759.0  445.83  3885.8  442.71  3944.8  439.97  3975.4  436.69  3986.8  438.77
  4032.2  435.22  4046.8  435.77  4084.4  431.94  4128.1  428.87  4302.0  424.22
  4385.7  427.02  4436.2  426.27  4526.5  422.78  4547.0  418.78  4583.6  417.05
  4699.8  410.24  4720.0  412.89  4840.0  411.17  4871.2  412.97  4961.9  412.83
  4982.5  408.72  4985.0  407.92  5001.8  408.72  5032.4  413.07  5261.7  413.07
  5809.0  417.05  6106.1  419.12  6184.3  421.23  6364.5  436.84  6537.1  444.78
#Mann=6,-1,0
  3759.0    0.16       0  4084.4    0.12       0  4982.5    0.07       0
  5001.8    0.12       0  5261.7    0.05       0  6106.1    0.16       0
Bank Sta=4583.6,5809
Exp/Cntr=0.3,0.1

Type RM Length L Ch R = 1,27157,1509,1509,1509
BEGIN DESCRIPTION:
RUNNING CREEK 22.0
END DESCRIPTION:
XS GIS Cut Line= 3
      2883674.96      7053025.01      2882275.00      7053225.00
      2880510.13      7053301.50
#Sta/Elev= 30
  3578.8  485.26  3743.0  475.56  3831.3  463.33  4063.7  440.03  4083.8  435.89
  4114.1  436.66  4255.1  425.12  4394.3  416.38  4498.0  409.82  4689.9  411.73
  4730.3  409.31  4780.8  411.16  4801.0  408.36  4831.3  411.96  4972.8  412.59
  4993.3  408.32  4995.8  407.52  5012.6  408.32  5013.0  411.95  5023.0  412.31
  5108.3  411.54  5133.1  408.38  5163.1  411.00  5673.6  416.06  6030.5  413.42
  6208.2  416.38  6342.4  420.08  6434.3  424.62  6634.5  442.94  6759.5  448.94
#Mann=7,-1,0
  3578.8    0.16       0  3743.0    0.12       0  4063.7    0.16       0
  4255.1    0.12       0  4993.3    0.07       0  5012.6    0.12       0
  6342.4    0.16       0
Bank Sta=4394.3,6208.2
Exp/Cntr=0.3,0.1

Type RM Length L Ch R = 1,25648,770,770,770
BEGIN DESCRIPTION:
RUNNING CREEK 21.0
END DESCRIPTION:
XS GIS Cut Line= 3
      2883374.98      7052525.00      2882077.83      7052372.46
      2880632.97      7052480.67
#Sta/Elev= 30
  3849.0  471.16  3880.4  468.35  4010.2  453.11  4059.2  446.74  4382.6  420.58
  4514.9  415.28  4584.0  412.09  4644.4  411.47  4694.8  415.65  4785.4  418.46
  4815.6  416.29  4865.9  409.33  4976.7  410.04  4998.7  408.40  5001.2  407.60
  5018.2  408.40  5027.0  410.62  5218.1  410.53  5278.3  409.00  5298.3  410.61
  5386.7  411.37  5529.0  410.32  5539.0  411.97  5990.3  410.87  6050.4  411.49
  6120.6  415.28  6249.9  421.80  6471.6  437.15  6561.8  445.57  6604.0  446.80
#Mann=6,-1,0
  3849.0    0.12       0  3880.4    0.16       0  4010.2    0.12       0
  4998.7    0.07       0  5018.2    0.12       0  6249.9    0.16       0
Bank Sta=4514.9,6120.6
Exp/Cntr=0.3,0.1

Type RM Length L Ch R = 1,24878,985,985,985
BEGIN DESCRIPTION:
RUNNING CREEK 20.0
END DESCRIPTION:
XS GIS Cut Line= 3
      2883424.96      7052324.98      2882225.00      7051825.00
      2881224.98      7051525.00
#Sta/Elev= 30
  3680.1  472.96  3734.2  468.77  3831.7  456.15  3907.6  448.17  4040.8  436.64
  4185.4  425.92  4397.8  419.59  4416.2  420.52  4421.6  419.41  4469.3  419.55
  4620.8  414.56  4729.3  416.79  4811.6  408.59  4835.4  410.25  4936.2  410.13
  5011.4  408.28  5021.8  410.17  5492.3  407.93  5494.8  407.13  5511.8  407.93
  5595.5  411.46  5616.9  412.25  5632.2  414.56  5710.9  421.11  5798.7  432.17
  5831.8  437.93  5864.9  441.25  5897.9  443.26  5975.4  444.12  6024.1  445.03
#Mann=6,-1,0
  3680.1    0.16       0  4040.8    0.12       0  5492.3    0.07       0
  5511.8    0.12       0  5595.5    0.16       0  5975.4     0.1       0
Bank Sta=4620.8,5632.2
Exp/Cntr=0.3,0.1

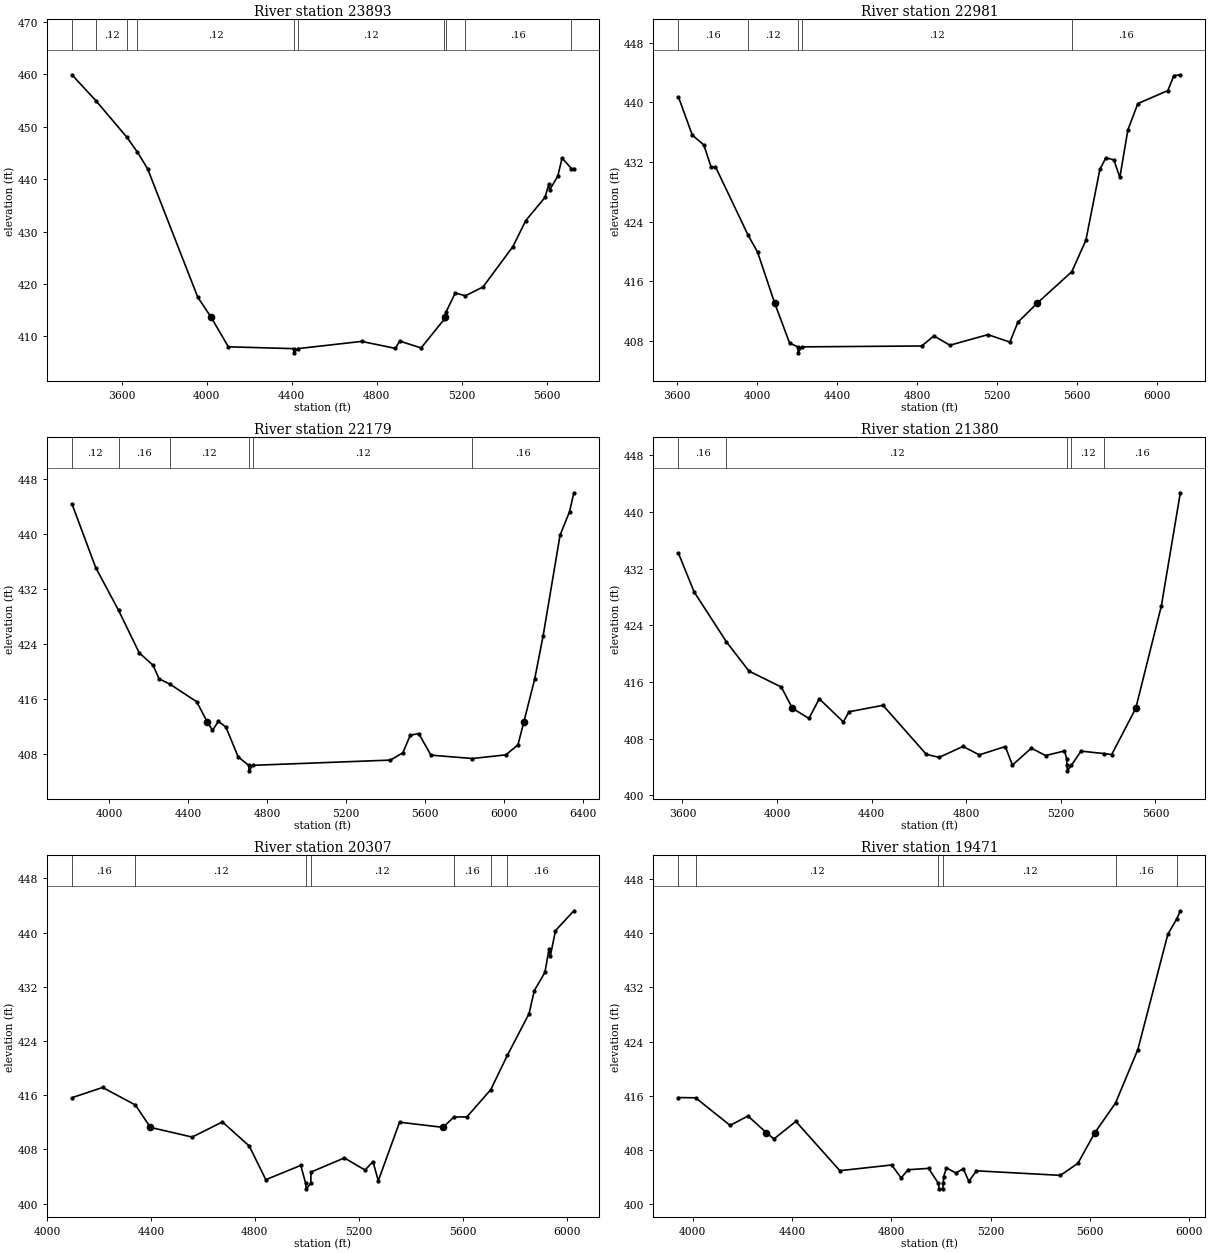
Type RM Length L Ch R = 1,23893,912,912,912
BEGIN DESCRIPTION:
RUNNING CREEK 19.0
END DESCRIPTION:
XS GIS Cut Line= 3
      2883528.85      7051675.12      2882230.23      7051084.84
      2881299.87      7051182.04
#Sta/Elev= 30
  3366.5  459.89  3480.3  454.90  3624.4  448.01  3674.9  445.13  3722.5  441.97
  3958.6  417.49  4020.8  413.70  4102.5  408.03  4409.1  407.68  4411.6  406.88
  4428.7  407.68  4729.7  409.06  4888.7  407.73  4908.8  409.12  5009.4  407.81
  5118.2  413.27  5122.0  413.70  5126.7  414.64  5170.2  418.30  5217.9  417.76
  5301.0  419.44  5441.7  427.15  5502.0  432.09  5592.5  436.51  5610.1  439.00
  5615.1  437.98  5652.9  440.57  5673.0  444.02  5717.0  442.00  5728.4  441.99
#Mann=10,-1,0
  3366.5    0.16       0  3480.3    0.12       0  3624.4    0.16       0
  3674.9    0.12       0  4409.1    0.07       0  4428.7    0.12       0
  5118.2    0.16       0  5126.7    0.12       0  5217.9    0.16       0
  5717.0     0.1       0
Bank Sta=4020.8,5122
Exp/Cntr=0.3,0.1

Type RM Length L Ch R = 1,22981,802,802,802
BEGIN DESCRIPTION:
RUNNING CREEK 18.0
END DESCRIPTION:
XS GIS Cut Line= 3
      2883369.01      7051036.41      2882306.47      7050383.61
      2881042.61      7050425.27
#Sta/Elev= 30
  3606.0  440.74  3675.4  435.62  3733.4  434.28  3770.1  431.29  3791.4  431.37
  3954.5  422.21  4002.1  419.93  4087.7  413.09  4162.3  407.74  4203.0  407.22
  4205.5  406.42  4222.6  407.22  4823.6  407.34  4884.5  408.69  4964.6  407.44
  5154.7  408.86  5264.7  407.86  5304.8  410.53  5401.9  413.09  5574.6  417.30
  5645.0  421.51  5715.0  431.01  5745.0  432.57  5785.0  432.29  5815.0  429.94
  5855.1  436.31  5905.1  439.84  6055.2  441.58  6085.2  443.58  6117.6  443.70
#Mann=5,-1,0
  3606.0    0.16       0  3954.5    0.12       0  4203.0    0.07       0
  4222.6    0.12       0  5574.6    0.16       0
Bank Sta=4087.7,5401.9
Exp/Cntr=0.3,0.1

Type RM Length L Ch R = 1,22179,799,799,799
BEGIN DESCRIPTION:
RUNNING CREEK 17.0
END DESCRIPTION:
XS GIS Cut Line= 3
      2883424.96      7049725.00      2882225.00      7049625.00
      2880918.83      7049924.99
#Sta/Elev= 30
  3811.3  444.36  3931.7  435.11  4047.4  428.91  4152.4  422.73  4222.7  420.92
  4252.8  418.97  4307.1  418.20  4443.4  415.64  4497.7  412.69  4523.7  411.48
  4553.8  412.79  4591.5  411.96  4654.2  407.62  4707.1  406.40  4709.6  405.60
  4726.7  406.40  5425.8  407.16  5488.5  408.21  5526.2  410.76  5569.1  411.02
  5631.0  407.88  5841.7  407.39  6010.7  407.92  6072.2  409.37  6102.0  412.69
  6157.0  418.92  6199.9  425.22  6285.6  439.81  6333.6  443.22  6355.6  445.97
#Mann=6,-1,0
  3811.3    0.12       0  4047.4    0.16       0  4307.1    0.12       0
  4707.1    0.07       0  4726.7    0.12       0  5841.7    0.16       0
Bank Sta=4497.7,6102
Exp/Cntr=0.3,0.1

Type RM Length L Ch R = 1,21380,1073,1073,1073
BEGIN DESCRIPTION:
RUNNING CREEK 16.0
END DESCRIPTION:
XS GIS Cut Line= 3
      2883306.45      7049432.21      2882160.64      7048966.94
      2881274.95      7048975.00
#Sta/Elev= 30
  3582.8  434.16  3649.1  428.71  3786.0  421.65  3881.1  417.54  4017.7  415.29
  4065.1  412.28  4134.8  410.86  4178.4  413.63  4280.1  410.37  4304.2  411.80
  4447.8  412.71  4631.3  405.79  4685.3  405.37  4786.3  406.91  4855.1  405.72
  4965.1  406.90  4995.1  404.28  5075.1  406.67  5135.1  405.63  5215.1  406.27
  5225.1  405.18  5225.3  404.27  5227.8  403.47  5244.9  404.27  5285.1  406.25
  5381.1  405.91  5415.1  405.77  5516.7  412.28  5625.1  426.75  5705.2  442.68
#Mann=5,-1,0
  3582.8    0.16       0  3786.0    0.12       0  5225.3    0.07       0
  5244.9    0.12       0  5381.1    0.16       0
Bank Sta=4065.1,5516.7
Exp/Cntr=0.3,0.1

Type RM Length L Ch R = 1,20307,836,836,836
BEGIN DESCRIPTION:
RUNNING CREEK 15.0
END DESCRIPTION:
XS GIS Cut Line= 4
      2882875.88      7048598.87      2882140.16      7048328.91
      2881957.87      7048248.18      2881025.58      7048427.87
#Sta/Elev= 30
  4095.7  415.64  4213.8  417.15  4340.1  414.56  4397.7  411.26  4558.4  409.83
  4675.1  412.06  4778.4  408.51  4842.1  403.54  4976.7  405.65  4995.7  402.99
  4998.2  402.19  5015.3  402.99  5016.3  404.67  5144.5  406.75  5224.3  404.96
  5254.8  406.21  5275.2  403.38  5357.1  412.02  5524.4  411.26  5566.5  412.79
  5616.5  412.81  5708.0  416.81  5771.9  421.87  5855.7  428.04  5875.9  431.44
  5916.8  434.13  5932.9  437.65  5938.0  436.61  5957.5  440.29  6028.2  443.22
#Mann=7,-1,0
  4095.7    0.16       0  4340.1    0.12       0  4995.7    0.07       0
  5015.3    0.12       0  5566.5    0.16       0  5708.0     0.1       0
  5771.9    0.16       0
Bank Sta=4397.7,5524.4
Exp/Cntr=0.3,0.1

Type RM Length L Ch R = 1,19471,2089,2089,2089
BEGIN DESCRIPTION:
RUNNING CREEK 14.0
END DESCRIPTION:
XS GIS Cut Line= 3
      2882750.93      7048258.62      2881662.00      7047687.56
      2880875.03      7047775.00
#Sta/Elev= 30
  3942.8  415.73  4012.1  415.69  4151.1  411.62  4222.9  413.01  4297.4  410.53
  4327.6  409.62  4415.8  412.21  4593.1  404.94  4801.6  405.78  4840.0  403.87
  4867.7  405.08  4950.3  405.28  4990.2  403.06  4992.7  402.26  5007.4  402.26
  5009.9  403.06  5010.8  404.04  5022.2  405.35  5060.6  404.59  5090.0  405.23
  5112.5  403.37  5143.2  404.92  5481.3  404.25  5551.7  406.02  5619.8  410.53
  5703.4  414.93  5793.2  422.82  5913.9  439.82  5949.2  442.04  5964.2  443.29
#Mann=6,-1,0
  3942.8    0.16       0  4012.1    0.12       0  4990.2    0.07       0
  5009.9    0.12       0  5703.4    0.16       0  5949.2    0.05       0
Bank Sta=4297.4,5619.8
Exp/Cntr=0.3,0.1

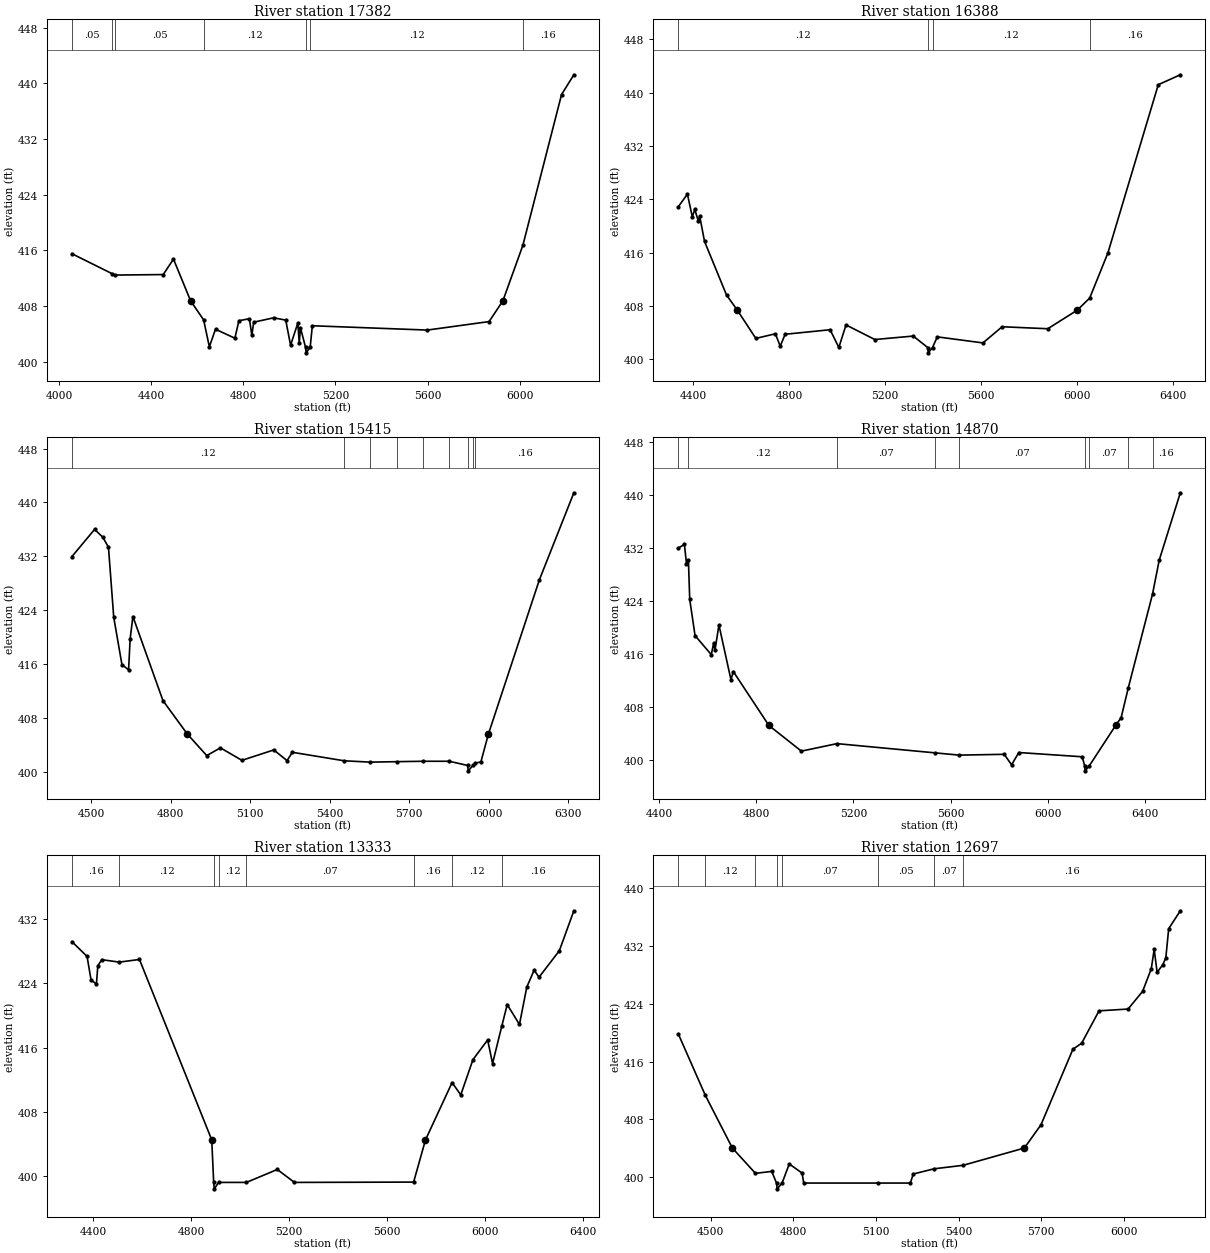
Type RM Length L Ch R = 1,17382,994,994,994
BEGIN DESCRIPTION:
RUNNING CREEK 13.0
END DESCRIPTION:
XS GIS Cut Line= 3
      2882775.26      7046900.99      2882286.91      7046678.05
      2880724.95      7046174.98
#Sta/Elev= 30
  4056.6  415.53  4232.5  412.64  4245.2  412.47  4452.6  412.54  4497.2  414.76
  4571.4  408.77  4628.0  406.03  4652.8  402.17  4679.5  404.69  4763.5  403.40
  4781.0  405.91  4826.6  406.20  4837.1  403.80  4845.2  405.70  4931.6  406.33
  4984.2  406.00  5005.2  402.40  5036.7  405.57  5042.8  402.72  5048.1  404.90
  5070.1  402.10  5072.6  401.30  5090.3  402.10  5099.7  405.19  5598.5  404.57
  5866.6  405.79  5926.5  408.77  6013.1  416.73  6181.0  438.39  6234.4  441.23
#Mann=7,-1,0
  4056.6    0.05       0  4232.5    0.16       0  4245.2    0.05       0
  4628.0    0.12       0  5070.1    0.07       0  5090.3    0.12       0
  6013.1    0.16       0
Bank Sta=4571.4,5926.5
Exp/Cntr=0.3,0.1

Type RM Length L Ch R = 1,16388,973,973,973
BEGIN DESCRIPTION:
RUNNING CREEK 12.0
END DESCRIPTION:
XS GIS Cut Line= 3
      2882721.88      7046195.30      2882075.00      7046075.00
      2880643.23      7046102.36
#Sta/Elev= 30
  4339.6  422.90  4377.1  424.77  4397.5  421.35  4407.6  422.48  4423.1  420.67
  4428.2  421.47  4448.3  417.67  4539.9  409.62  4584.7  407.35  4661.9  403.10
  4743.3  403.79  4763.6  401.93  4784.0  403.72  4971.2  404.40  5007.6  401.74
  5037.6  405.12  5157.6  402.93  5317.6  403.45  5377.5  401.73  5380.0  400.93
  5397.7  401.73  5417.6  403.33  5607.7  402.42  5687.7  404.85  5877.7  404.55
  6000.8  407.35  6052.2  409.16  6127.8  415.91  6337.8  441.21  6429.6  442.70
#Mann=4,-1,0
  4339.6    0.12       0  5377.5    0.07       0  5397.7    0.12       0
  6052.2    0.16       0
Bank Sta=4584.7,6000.8
Exp/Cntr=0.3,0.1

Type RM Length L Ch R = 1,15415,545,545,545
BEGIN DESCRIPTION:
RUNNING CREEK 11.0
END DESCRIPTION:
XS GIS Cut Line= 3
      2882847.80      7045673.50      2882275.00      7045525.00
      2880974.97      7045425.00
#Sta/Elev= 30
  4426.4  431.98  4511.9  436.01  4542.9  434.85  4564.3  433.37  4584.2  422.98
  4615.2  415.96  4640.3  415.18  4646.2  419.78  4656.6  423.09  4770.2  410.61
  4861.9  405.67  4935.5  402.46  4987.1  403.61  5068.3  401.76  5188.6  403.30
  5238.8  401.72  5258.8  402.95  5454.7  401.69  5553.9  401.49  5653.0  401.56
  5752.2  401.62  5851.4  401.62  5920.7  401.00  5923.2  400.20  5940.9  401.00
  5950.5  401.35  5970.9  401.52  5999.4  405.67  6191.6  428.51  6322.0  441.44
#Mann=9,-1,0
  4426.4    0.12       0  5454.7    0.16       0  5553.9    0.05       0
  5653.0    0.16       0  5752.2    0.12       0  5851.4    0.07       0
  5920.7    0.07       0  5940.9    0.07       0  5950.5    0.16       0
Bank Sta=4861.9,5999.4
Exp/Cntr=0.3,0.1

Type RM Length L Ch R = 1,14870,1537,1537,1537
BEGIN DESCRIPTION:
RUNNING CREEK 10.0
END DESCRIPTION:
XS GIS Cut Line= 3
      2882914.27      7045380.29      2882240.64      7045019.16
      2880942.00      7045116.39
#Sta/Elev= 30
  4479.6  431.99  4504.3  432.52  4512.8  429.62  4520.7  430.22  4526.2  424.23
  4548.1  418.79  4614.9  415.92  4624.5  417.61  4630.2  416.61  4646.4  420.39
  4695.9  412.14  4705.7  413.37  4852.1  405.25  4985.9  401.38  5132.5  402.51
  5536.1  401.12  5635.6  400.78  5821.2  400.90  5851.3  399.32  5881.3  401.17
  6142.1  400.53  6152.0  399.21  6154.5  398.41  6172.2  399.21  6279.8  405.25
  6302.5  406.42  6332.2  410.95  6431.7  425.03  6459.3  430.16  6546.2  440.31
#Mann=9,-1,0
  4479.6    0.16       0  4520.7    0.12       0  5132.5    0.07       0
  5536.1    0.12       0  5635.6    0.07       0  6152.0    0.07       0
  6172.2    0.07       0  6332.2     0.1       0  6431.7    0.16       0
Bank Sta=4852.1,6279.8
Exp/Cntr=0.3,0.1

Type RM Length L Ch R = 1,13333,636,636,636
BEGIN DESCRIPTION:
RUNNING CREEK 9.0
END DESCRIPTION:
XS GIS Cut Line= 3
      2883157.32      7044817.81      2882921.19      7044373.33
      2881372.61      7044380.27
#Sta/Elev= 30
  4312.0  429.17  4373.8  427.34  4390.2  424.39  4412.1  423.91  4417.8  426.18
  4434.1  426.93  4505.7  426.63  4588.0  426.96  4883.5  404.50  4891.4  399.21
  4893.9  398.41  4911.6  399.21  5025.4  399.21  5151.5  400.82  5221.5  399.21
  5708.8  399.25  5757.3  404.50  5866.1  411.64  5901.5  410.10  5951.5  414.50
  6011.5  416.94  6031.5  414.01  6069.0  418.63  6091.5  421.35  6141.5  418.87
  6171.5  423.52  6201.5  425.63  6221.5  424.75  6304.6  428.05  6363.9  433.02
#Mann=8,-1,0
  4312.0    0.16       0  4505.7    0.12       0  4891.4    0.07       0
  4911.6    0.12       0  5025.4    0.07       0  5708.8    0.16       0
  5866.1    0.12       0  6069.0    0.16       0
Bank Sta=4883.5,5757.3
Exp/Cntr=0.3,0.1

Type RM Length L Ch R = 1,12697,1162,1162,1162
BEGIN DESCRIPTION:
RUNNING CREEK 8.0
END DESCRIPTION:
XS GIS Cut Line= 4
      2883122.57      7044234.43      2882848.58      7043910.94
      2882523.74      7043792.09      2881525.00      7044125.00
#Sta/Elev= 30
  4382.4  419.78  4480.3  411.32  4578.3  404.05  4662.2  400.55  4721.3  400.82
  4738.6  399.21  4741.1  398.41  4758.8  399.21  4785.0  401.85  4831.4  400.59
  4837.5  399.21  5108.8  399.21  5224.7  399.21  5235.2  400.46  5310.8  401.18
  5416.0  401.66  5638.6  404.05  5699.0  407.26  5815.0  417.71  5846.6  418.53
  5909.8  423.01  6015.3  423.26  6068.0  425.70  6099.6  428.83  6110.1  431.52
  6120.7  428.33  6141.7  429.41  6152.3  430.32  6162.8  434.37  6205.0  436.84
#Mann=8,-1,0
  4382.4    0.16       0  4480.3    0.12       0  4662.2    0.07       0
  4738.6    0.07       0  4758.8    0.07       0  5108.8    0.05       0
  5310.8    0.07       0  5416.0    0.16       0
Bank Sta=4578.3,5638.6
Exp/Cntr=0.3,0.1

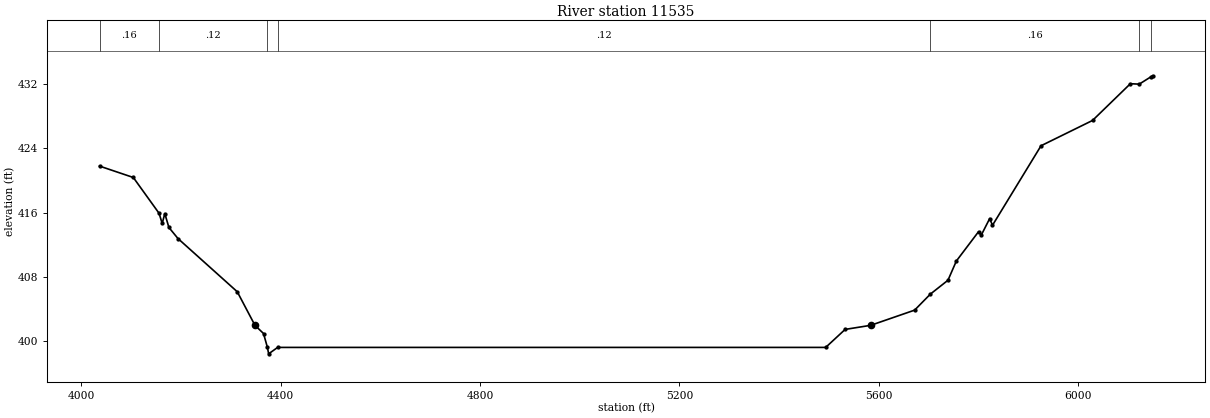
Type RM Length L Ch R = 1,11535,0,0,0
BEGIN DESCRIPTION:
RUNNING CREEK 7.0
END DESCRIPTION:
XS GIS Cut Line= 4
      2883997.10      7043000.48      2883267.98      7042757.44
      2882851.31      7042799.11      2882024.92      7043215.78
#Sta/Elev= 30
  4036.7  421.78  4104.5  420.36  4156.2  415.90  4162.4  414.64  4167.7  415.86
  4175.9  414.14  4194.1  412.76  4313.0  406.14  4348.5  401.96  4365.7  400.94
  4373.5  399.21  4376.0  398.41  4394.0  399.21  5493.4  399.21  5532.4  401.45
  5583.7  401.96  5671.8  403.85  5703.5  405.85  5738.7  407.57  5755.5  409.96
  5800.1  413.62  5805.7  413.21  5822.4  415.25  5828.0  414.41  5925.4  424.31
  6028.7  427.46  6104.6  432.03  6122.4  431.98  6145.0  432.86  6149.5  433.02
#Mann=7,-1,0
  4036.7    0.16       0  4156.2    0.12       0  4373.5   0.033       0
  4394.0    0.12       0  5703.5    0.16       0  6122.4    0.12       0
  6145.0    0.16       0
Bank Sta=4348.5,5583.7
Exp/Cntr=0.3,0.1

Chan Stop Cuts=-1