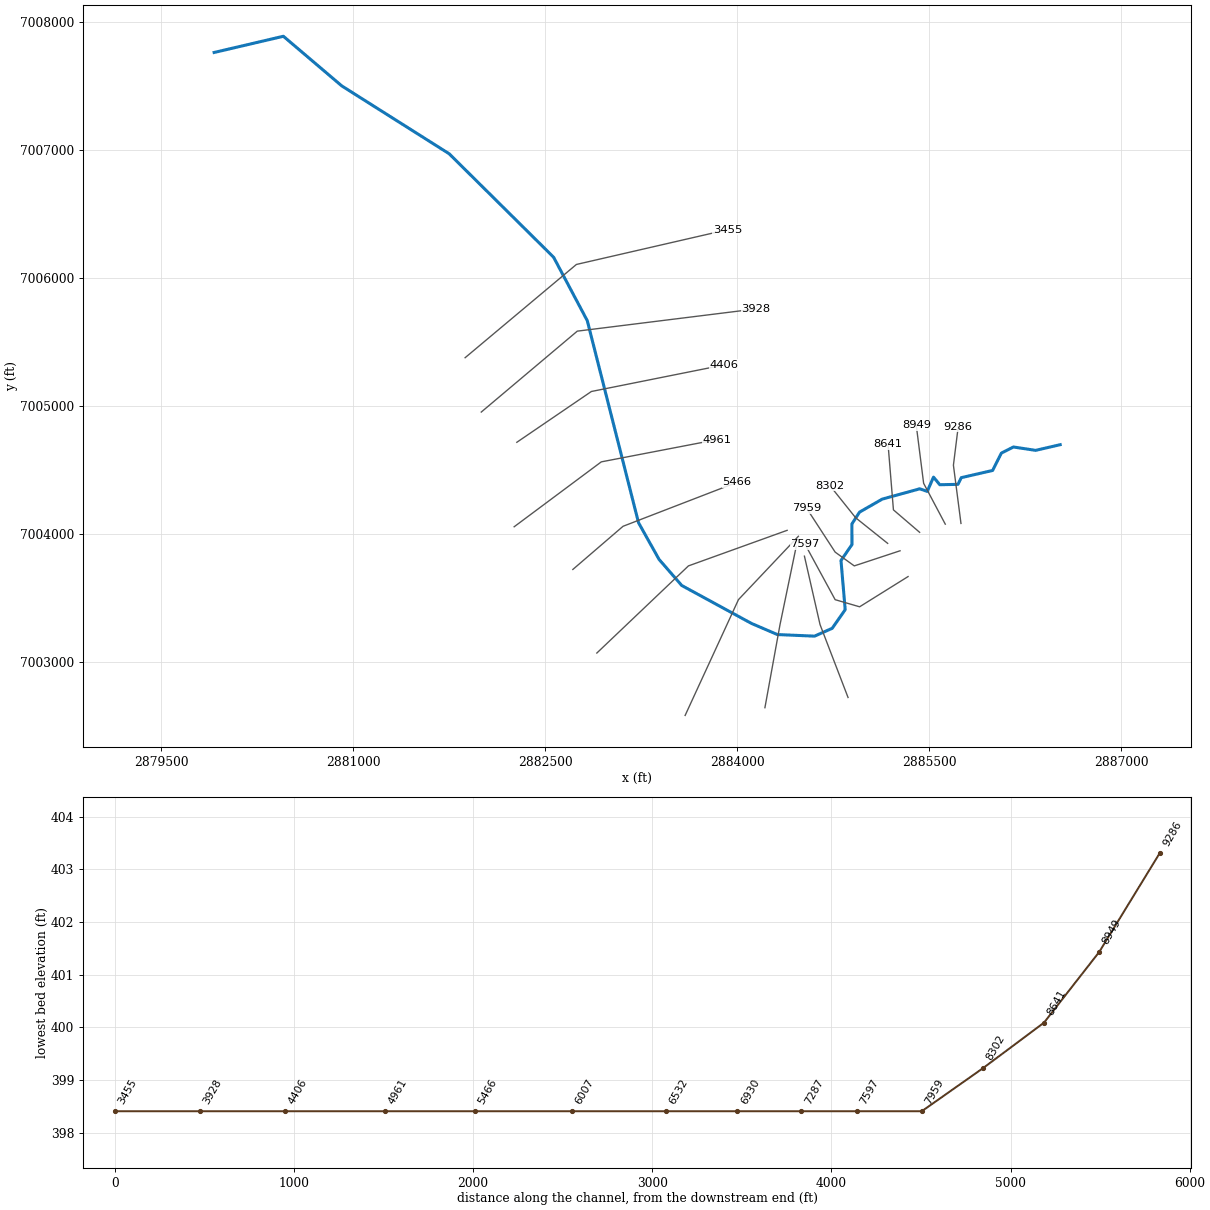
--- SEARCY BRANCH.prj (project) ---

Proj Title=SEARCY BRANCH Base Level Engineering
Current Plan=p01
Default Exp/Contr=0.3,0.1
English Units
Geom File=g01
Flow File=f01
Plan File=p01
BEGIN DESCRIPTION:
SEARCY BRANCH
END DESCRIPTION:

--- SEARCY BRANCH.p01 (plan) ---

Plan Title=Multiple Run
Short Identifier=Multiple
Geom File=g01
Flow File=f01
Subcritical Flow
K Sum by GR= 0
Std Step Tol= 0.01
Critical Tol= 0.01
Num of Std Step Trials= 20
Max Error Tol= 0.3
Flow Tol Ratio= 0.001
Split Flow NTrial= 30
Split Flow Tol= 0.02
Split Flow Ratio= 0.02
Log Output Level= 0
Friction Slope Method= 1
Unsteady Friction Slope Method= 2
Unsteady Bridges Friction Slope Method= 1
Parabolic Critical Depth
Global Vel Dist=  1 , 1 , 1
Global Log Level= 0
CheckData=True
Encroach Param= -1, 0, 0, 0
BEGIN DESCRIPTION:
Multiple Run
END DESCRIPTION:

--- SEARCY BRANCH.f01 (steady flow) ---

Flow Title=Multiple
Number of Profiles=7
Profile Names=10-year,25-year,50-year,1pct_min,100-year,1pct_plu,500-year
River Rch & RM= SEARCY BRANCH,Reach-1,9286
     464     616     740     442     883    1761    1256
River Rch & RM= SEARCY BRANCH,Reach-1,7287
     658     892    1086     657    1311    2615    1913
River Rch & RM= SEARCY BRANCH,Reach-1,6007
     748    1013    1231     743    1482    2958    2154
Boundary for River Rch & Prof#=SEARCY BRANCH,Reach-1,1
Up Type=0
Dn Type=3
Dn Slope=0.005
Boundary for River Rch & Prof#=SEARCY BRANCH,Reach-1,2
Up Type=0
Dn Type=3
Dn Slope=0.005
Boundary for River Rch & Prof#=SEARCY BRANCH,Reach-1,3
Up Type=0
Dn Type=3
Dn Slope=0.005
Boundary for River Rch & Prof#=SEARCY BRANCH,Reach-1,4
Up Type=0
Dn Type=3
Dn Slope=0.005
Boundary for River Rch & Prof#=SEARCY BRANCH,Reach-1,5
Up Type=0
Dn Type=3
Dn Slope=0.005
Boundary for River Rch & Prof#=SEARCY BRANCH,Reach-1,6
Up Type=0
Dn Type=3
Dn Slope=0.005
Boundary for River Rch & Prof#=SEARCY BRANCH,Reach-1,7
Up Type=0
Dn Type=3
Dn Slope=0.005

--- SEARCY BRANCH.g01 (geometry) ---

Geom Title=Existing Conditions

River Reach=SEARCY BRANCH,Reach-1
Reach XY= 30
      2886522.38      7004695.67      2886330.51      7004651.40
      2886156.97      7004677.78      2886063.13      7004629.97
      2885994.50      7004494.34      2885749.77      7004438.13
      2885724.22      7004386.01      2885582.16      7004382.95
      2885533.11      7004442.22      2885484.06      7004330.82
      2885425.80      7004351.26      2885132.50      7004270.53
      2884955.70      7004169.35      2884895.58      7004076.69
      2884896.07      7003915.51      2884810.58      7003791.22
      2884843.28      7003406.96      2884742.10      7003261.84
      2884604.14      7003200.52      2884313.90      7003212.79
      2884111.55      7003299.66      2883566.84      7003596.03
      2883389.43      7003800.30      2883229.33      7004086.18
      2882829.10      7005664.26      2882566.08      7006159.79
      2881750.36      7006967.88      2880911.77      7007497.72
      2880455.71      7007885.37      2879914.94      7007758.78

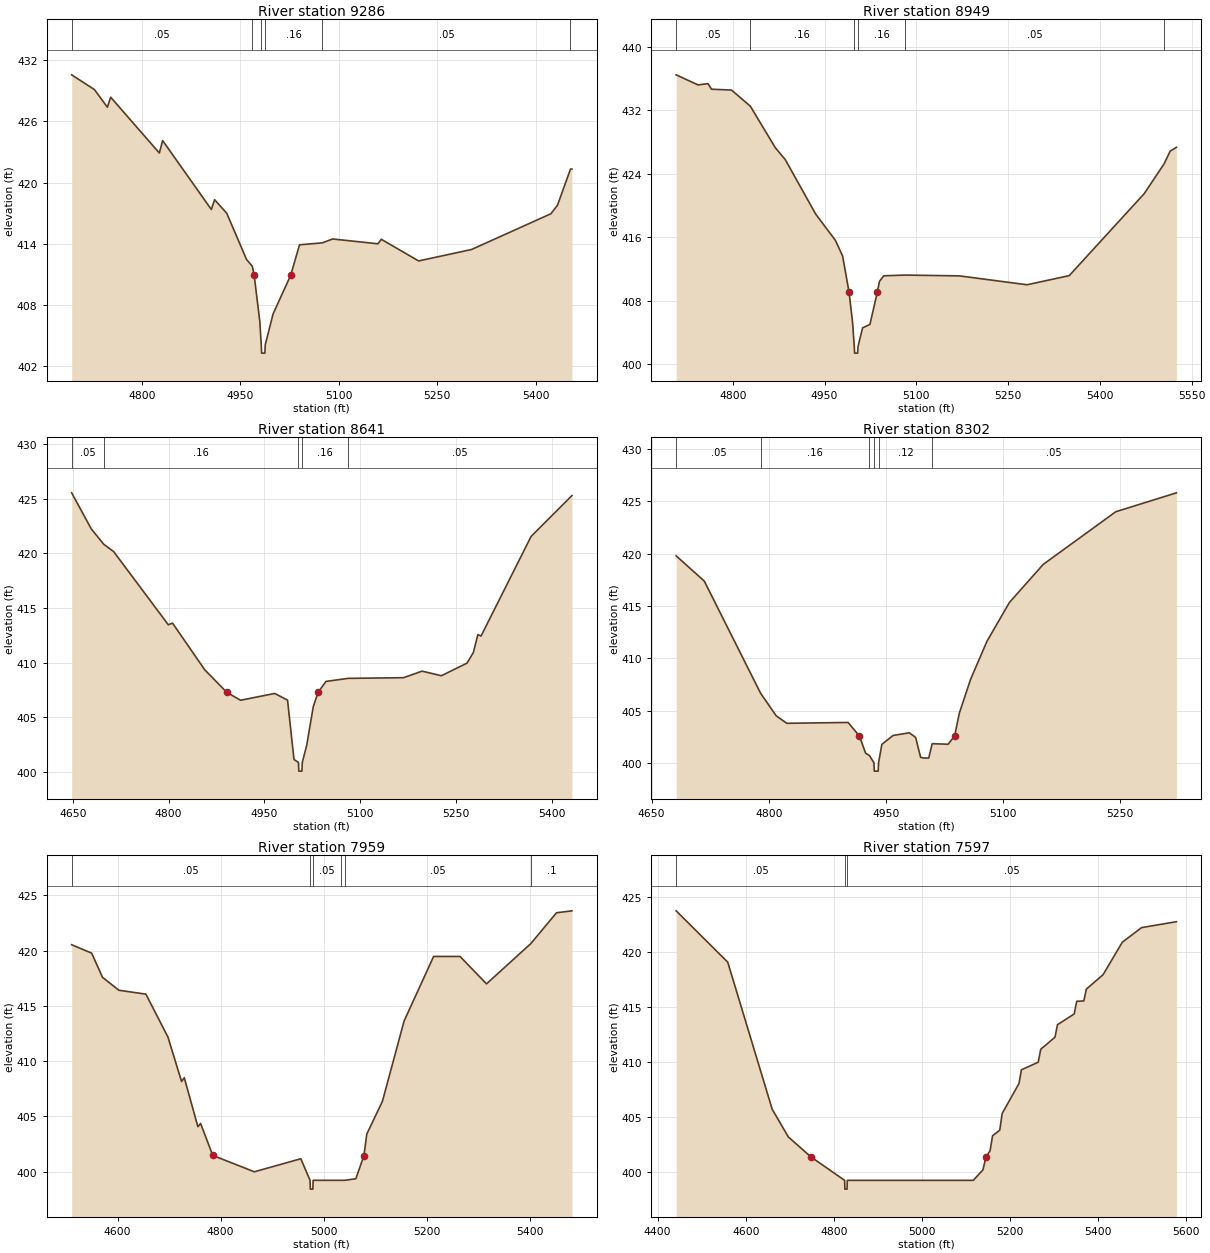
Type RM Length L Ch R = 1,9286,337,337,337
BEGIN DESCRIPTION:
SEARCY BRANCH 15.0
END DESCRIPTION:
XS GIS Cut Line= 3
      2885747.60      7004080.67      2885688.57      7004535.56
      2885726.12      7004836.82
#Sta/Elev= 30
  4693.1  430.56  4727.7  429.12  4747.5  427.39  4752.5  428.37  4826.7  422.90
  4831.7  424.12  4905.9  417.37  4910.9  418.33  4929.4  417.00  4959.6  412.47
  4968.3  411.82  4971.2  410.92  4979.8  406.39  4982.0  404.10  4982.5  403.30
  4987.5  403.30  4988.0  404.10  5000.0  407.14  5026.8  410.92  5040.3  413.91
  5075.0  414.10  5090.7  414.48  5159.8  414.01  5164.9  414.45  5221.8  412.33
  5302.4  413.45  5423.3  416.95  5433.4  417.79  5453.2  421.33  5455.4  421.33
#Mann=6,-1,0
  4693.1    0.05       0  4968.3    0.16       0  4982.0    0.07       0
  4988.0    0.16       0  5075.0    0.05       0  5453.2    0.08       0
Bank Sta=4971.2,5026.8
Exp/Cntr=0.3,0.1

Type RM Length L Ch R = 1,8949,308,308,308
BEGIN DESCRIPTION:
SEARCY BRANCH 14.0
END DESCRIPTION:
XS GIS Cut Line= 3
      2885624.98      7004075.04      2885455.93      7004394.07
      2885398.34      7004847.17
#Sta/Elev= 30
  4707.3  436.48  4743.1  435.21  4759.4  435.37  4765.1  434.67  4797.8  434.56
  4828.6  432.53  4869.4  427.30  4885.7  425.80  4935.4  418.94  4967.6  415.64
  4979.4  413.67  4990.0  409.09  4995.7  405.30  4998.5  402.23  4999.0  401.43
  5004.0  401.43  5004.5  402.23  5012.1  404.61  5024.1  405.05  5036.1  409.09
  5039.7  410.47  5046.8  411.17  5081.8  411.26  5170.1  411.16  5281.0  410.04
  5349.9  411.19  5472.5  421.52  5504.9  425.26  5514.9  426.87  5525.1  427.35
#Mann=6,-1,0
  4707.3    0.05       0  4828.6    0.16       0  4998.5    0.07       0
  5004.5    0.16       0  5081.8    0.05       0  5504.9    0.08       0
Bank Sta=4990,5036.1
Exp/Cntr=0.3,0.1

Type RM Length L Ch R = 1,8641,339,339,339
BEGIN DESCRIPTION:
SEARCY BRANCH 13.0
END DESCRIPTION:
XS GIS Cut Line= 3
      2885424.64      7004011.28      2885220.04      7004186.71
      2885178.15      7004698.79
#Sta/Elev= 30
  4648.3  425.53  4678.9  422.24  4698.5  420.83  4714.0  420.16  4799.6  413.47
  4806.2  413.62  4856.7  409.35  4891.2  407.29  4912.7  406.57  4966.3  407.19
  4986.3  406.58  4996.4  401.15  5003.4  400.89  5003.9  400.09  5008.9  400.09
  5009.4  400.89  5016.4  402.48  5026.5  405.96  5034.1  407.29  5046.5  408.29
  5081.2  408.57  5167.8  408.63  5197.0  409.23  5227.1  408.81  5267.3  409.96
  5277.3  410.94  5284.3  412.57  5289.3  412.44  5367.6  421.54  5431.6  425.28
#Mann=5,-1,0
  4648.3    0.05       0  4698.5    0.16       0  5003.4    0.07       0
  5009.4    0.16       0  5081.2    0.05       0
Bank Sta=4891.2,5034.1
Exp/Cntr=0.3,0.1

Type RM Length L Ch R = 1,8302,343,343,343
BEGIN DESCRIPTION:
SEARCY BRANCH 12.0
END DESCRIPTION:
XS GIS Cut Line= 3
      2885174.97      7003925.02      2884925.00      7004125.00
      2884724.99      7004375.02
#Sta/Elev= 30
  4681.5  419.80  4717.5  417.39  4789.6  406.67  4809.5  404.52  4823.1  403.80
  4901.6  403.88  4916.1  402.58  4924.0  400.94  4928.9  400.72  4934.6  400.03
  4935.1  399.23  4940.1  399.23  4940.6  400.03  4944.8  401.79  4959.2  402.64
  4980.0  402.89  4988.0  402.45  4994.4  400.55  4998.4  400.48  5004.8  400.48
  5009.2  401.85  5029.6  401.80  5037.9  402.58  5044.0  404.78  5058.4  408.01
  5079.3  411.63  5108.1  415.35  5151.3  418.98  5244.1  424.01  5321.8  425.82
#Mann=6,-1,0
  4681.5    0.05       0  4789.6    0.16       0  4928.9    0.12       0
  4934.6    0.07       0  4940.6    0.12       0  5009.2    0.05       0
Bank Sta=4916.1,5037.9
Exp/Cntr=0.3,0.1

Type RM Length L Ch R = 1,7959,362,362,362
BEGIN DESCRIPTION:
SEARCY BRANCH 11.0
END DESCRIPTION:
XS GIS Cut Line= 4
      2885271.86      7003867.14      2884914.26      7003749.10
      2884764.95      7003856.74      2884540.89      7004201.13
#Sta/Elev= 30
  4510.9  420.53  4549.7  419.77  4570.8  417.58  4602.6  416.41  4655.0  416.06
  4697.8  412.18  4724.3  408.15  4729.6  408.49  4756.0  404.06  4761.3  404.35
  4784.9  401.46  4865.6  399.98  4955.9  401.16  4973.8  399.21  4974.3  398.41
  4979.3  398.41  4979.8  399.21  5033.5  399.21  5041.5  399.21  5062.7  399.35
  5078.5  401.45  5084.0  403.39  5114.3  406.35  5156.5  413.63  5213.8  419.47
  5265.1  419.47  5316.5  416.99  5402.7  420.64  5452.3  423.42  5482.4  423.60
#Mann=6,-1,0
  4510.9    0.05       0  4973.8   0.033       0  4979.8    0.05       0
  5033.5    0.12       0  5041.5    0.05       0  5402.7     0.1       0
Bank Sta=4784.9,5078.5
Exp/Cntr=0.3,0.1

Type RM Length L Ch R = 1,7597,310,310,310
BEGIN DESCRIPTION:
SEARCY BRANCH 10.0
END DESCRIPTION:
XS GIS Cut Line= 4
      2885334.36      7003665.74      2884955.93      7003429.66
      2884764.95      7003485.21      2884530.59      7003916.41
#Sta/Elev= 30
  4442.1  423.78  4559.2  419.10  4660.1  405.70  4696.7  403.17  4748.0  401.35
  4824.6  399.21  4825.1  398.41  4830.1  398.41  4830.6  399.21  5116.8  399.21
  5138.6  400.17  5145.6  401.35  5154.8  401.91  5160.5  403.28  5176.7  403.78
  5182.3  405.31  5220.4  408.04  5226.0  409.29  5264.1  409.98  5269.8  411.16
  5302.1  412.26  5307.8  413.40  5345.8  414.38  5351.5  415.53  5367.6  415.57
  5373.3  416.64  5411.3  417.96  5455.0  420.92  5498.7  422.25  5577.8  422.79
#Mann=3,-1,0
  4442.1    0.05       0  4824.6   0.033       0  4830.6    0.05       0
Bank Sta=4748,5145.6
Exp/Cntr=0.3,0.1

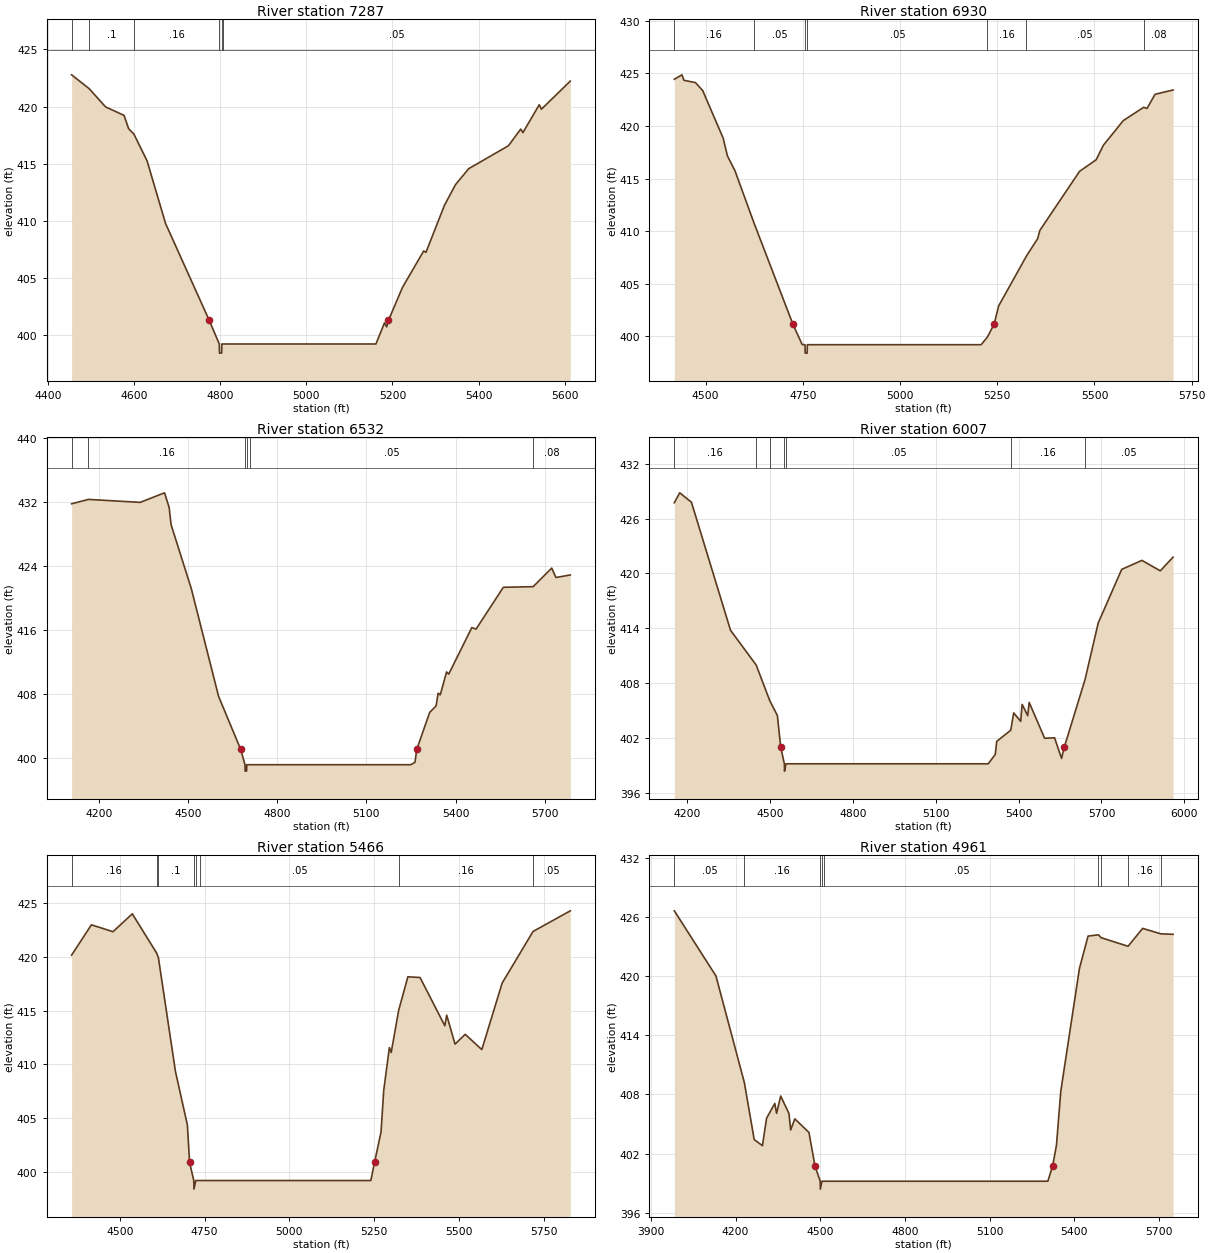
Type RM Length L Ch R = 1,7287,357,357,357
BEGIN DESCRIPTION:
SEARCY BRANCH 9.0
END DESCRIPTION:
XS GIS Cut Line= 3
      2884865.64      7002721.35      2884646.90      7003290.77
      2884525.01      7003824.95
#Sta/Elev= 30
  4455.2  422.78  4496.0  421.57  4534.1  419.97  4576.9  419.23  4587.7  418.06
  4599.9  417.59  4630.5  415.24  4673.4  409.76  4774.9  401.27  4798.1  399.21
  4798.6  398.41  4803.6  398.41  4804.1  399.21  4807.7  399.21  5161.8  399.21
  5181.7  401.06  5186.8  400.71  5190.8  401.27  5223.4  404.16  5272.8  407.36
  5277.9  407.23  5320.9  411.35  5346.5  413.16  5377.2  414.56  5469.5  416.57
  5498.0  418.03  5503.1  417.72  5541.0  420.16  5546.1  419.77  5613.1  422.23
#Mann=6,-1,0
  4455.2    0.05       0  4496.0     0.1       0  4599.9    0.16       0
  4798.1   0.033       0  4804.1    0.16       0  4807.7    0.05       0
Bank Sta=4774.9,5190.8
Exp/Cntr=0.3,0.1

Type RM Length L Ch R = 1,6930,398,398,398
BEGIN DESCRIPTION:
SEARCY BRANCH 8.0
END DESCRIPTION:
XS GIS Cut Line= 3
      2884216.35      7002641.48      2884334.40      7003290.77
      2884460.79      7003900.37
#Sta/Elev= 30
  4419.6  424.43  4439.2  424.85  4444.3  424.33  4474.0  424.11  4492.6  423.35
  4545.1  418.84  4556.1  417.15  4575.6  415.73  4624.8  410.74  4724.3  401.18
  4748.4  399.22  4755.6  399.21  4756.1  398.41  4761.1  398.41  4761.6  399.21
  5208.6  399.21  5224.8  399.94  5242.2  401.18  5253.6  402.89  5325.2  407.64
  5353.9  409.28  5359.6  410.07  5461.7  415.68  5504.4  416.78  5523.0  418.16
  5574.1  420.50  5626.4  421.76  5635.3  421.66  5655.8  423.00  5702.1  423.41
#Mann=7,-1,0
  4419.6    0.16       0  4624.8    0.05       0  4755.6   0.033       0
  4761.6    0.05       0  5224.8    0.16       0  5325.2    0.05       0
  5626.4    0.08       0
Bank Sta=4724.3,5242.2
Exp/Cntr=0.3,0.1

Type RM Length L Ch R = 1,6532,525,525,525
BEGIN DESCRIPTION:
SEARCY BRANCH 7.0
END DESCRIPTION:
XS GIS Cut Line= 3
      2883593.23      7002581.18      2884009.76      7003485.54
      2884477.70      7003980.34
#Sta/Elev= 30
  4109.0  431.77  4165.8  432.32  4339.6  431.95  4421.5  433.14  4437.0  431.31
  4443.5  429.17  4511.4  421.19  4603.2  407.74  4677.6  401.11  4692.0  399.21
  4692.5  398.41  4697.5  398.41  4698.0  399.21  4710.3  399.21  5249.5  399.21
  5263.7  399.52  5269.4  401.11  5313.0  405.74  5334.5  406.55  5341.3  408.13
  5348.6  407.93  5369.7  410.79  5376.9  410.51  5454.6  416.32  5468.8  416.13
  5560.6  421.35  5660.9  421.43  5723.3  423.75  5737.4  422.57  5785.7  422.89
#Mann=6,-1,0
  4109.0    0.05       0  4165.8    0.16       0  4692.0   0.033       0
  4698.0    0.16       0  4710.3    0.05       0  5660.9    0.08       0
Bank Sta=4677.6,5269.4
Exp/Cntr=0.3,0.1

Type RM Length L Ch R = 1,6007,541,541,541
BEGIN DESCRIPTION:
SEARCY BRANCH 6.0
END DESCRIPTION:
XS GIS Cut Line= 3
      2882903.85      7003068.56      2883619.12      7003749.10
      2884389.91      7004026.86
#Sta/Elev= 30
  4152.7  427.73  4172.1  428.81  4214.6  427.79  4356.2  413.80  4449.4  409.99
  4498.4  406.11  4526.0  404.48  4538.1  401.02  4551.3  399.21  4551.8  398.41
  4557.3  399.21  5289.9  399.21  5315.3  400.24  5320.6  401.66  5371.5  402.88
  5382.0  404.77  5407.4  403.85  5412.7  405.70  5432.8  404.47  5438.1  405.92
  5494.2  402.00  5530.2  402.05  5555.5  399.80  5565.3  401.02  5640.5  408.41
  5688.3  414.60  5773.4  420.45  5846.5  421.43  5913.2  420.29  5959.3  421.78
#Mann=7,-1,0
  4152.7    0.16       0  4449.4     0.1       0  4498.4    0.05       0
  4551.3   0.033       0  4557.3    0.05       0  5371.5    0.16       0
  5640.5    0.05       0
Bank Sta=4538.1,5565.3
Exp/Cntr=0.3,0.1

Type RM Length L Ch R = 1,5466,505,505,505
BEGIN DESCRIPTION:
SEARCY BRANCH 5.0
END DESCRIPTION:
XS GIS Cut Line= 3
      2882716.34      7003721.33      2883108.42      7004058.42
      2883998.46      7004401.94
#Sta/Elev= 30
  4357.9  420.16  4416.3  422.98  4480.0  422.34  4537.0  424.00  4608.7  420.36
  4614.0  419.92  4664.3  409.34  4699.5  404.37  4706.0  400.89  4718.3  399.21
  4718.8  398.41  4724.4  399.21  4736.7  399.21  5240.7  399.21  5251.5  400.89
  5270.7  403.72  5278.6  407.57  5295.3  411.57  5300.7  411.11  5322.7  415.02
  5349.9  418.15  5385.8  418.08  5459.0  413.59  5464.4  414.58  5489.0  411.89
  5519.0  412.80  5568.0  411.38  5628.1  417.57  5719.1  422.36  5829.0  424.28
#Mann=8,-1,0
  4357.9    0.16       0  4608.7    0.05       0  4614.0     0.1       0
  4718.3   0.033       0  4724.4     0.1       0  4736.7    0.05       0
  5322.7    0.16       0  5719.1    0.05       0
Bank Sta=4706,5251.5
Exp/Cntr=0.3,0.1

Type RM Length L Ch R = 1,4961,555,555,555
BEGIN DESCRIPTION:
SEARCY BRANCH 4.0
END DESCRIPTION:
XS GIS Cut Line= 3
      2882258.03      7004054.68      2882938.57      7004561.60
      2883840.65      7004735.08
#Sta/Elev= 30
  3982.9  426.60  4130.4  420.00  4231.0  409.20  4265.9  403.43  4295.1  402.81
  4309.7  405.59  4338.9  407.09  4345.2  406.08  4359.8  407.84  4389.0  406.07
  4395.2  404.40  4409.8  405.53  4459.9  404.15  4481.4  400.75  4499.8  399.21
  4500.3  398.41  4505.9  399.21  4514.4  399.21  5306.5  399.21  5323.4  400.75
  5337.0  402.86  5352.4  408.33  5418.5  420.77  5449.0  424.04  5485.9  424.17
  5495.0  423.88  5590.8  423.01  5642.5  424.82  5707.0  424.27  5750.1  424.22
#Mann=9,-1,0
  3982.9    0.05       0  4231.0    0.16       0  4499.8   0.033       0
  4505.9    0.16       0  4514.4    0.05       0  5485.9    0.16       0
  5495.0    0.05       0  5590.8    0.16       0  5707.0    0.05       0
Bank Sta=4481.4,5323.4
Exp/Cntr=0.3,0.1

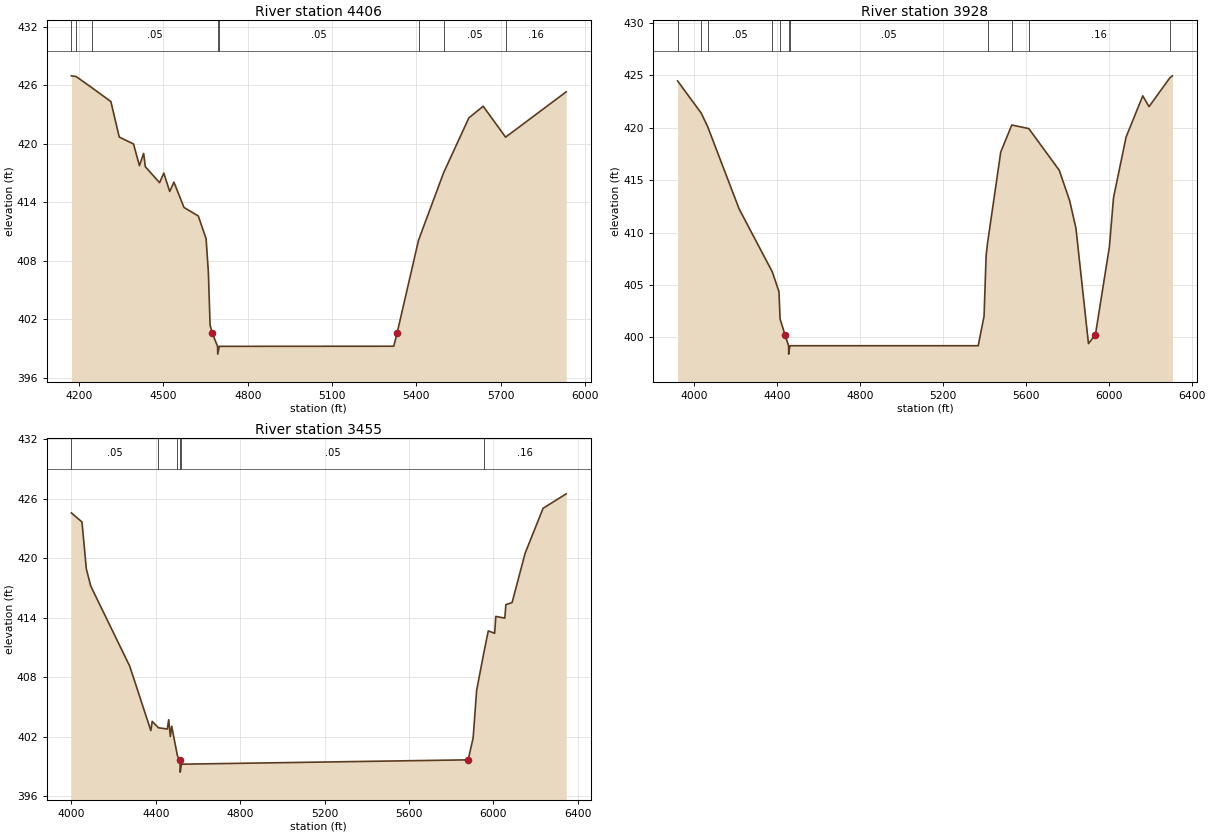
Type RM Length L Ch R = 1,4406,478,478,478
BEGIN DESCRIPTION:
SEARCY BRANCH 3.0
END DESCRIPTION:
XS GIS Cut Line= 3
      2882278.88      7004714.40      2882861.19      7005111.19
      2883896.89      7005318.54
#Sta/Elev= 30
  4172.5  426.95  4189.3  426.88  4245.5  425.73  4313.0  424.31  4342.8  420.67
  4393.6  419.96  4414.6  417.73  4429.5  419.00  4435.6  417.63  4486.4  415.99
  4501.3  416.98  4522.3  415.09  4537.3  416.05  4573.2  413.45  4624.0  412.58
  4651.8  410.25  4659.9  406.84  4666.0  401.39  4674.0  400.55  4692.7  399.21
  4693.2  398.41  4698.9  399.21  5319.6  399.22  5331.4  400.55  5407.8  410.09
  5497.4  417.03  5587.0  422.64  5638.0  423.83  5717.7  420.66  5933.4  425.31
#Mann=8,-1,0
  4172.5    0.08       0  4189.3     0.1       0  4245.5    0.05       0
  4692.7   0.033       0  4698.9    0.05       0  5407.8    0.16       0
  5497.4    0.05       0  5717.7    0.16       0
Bank Sta=4674,5331.4
Exp/Cntr=0.3,0.1

Type RM Length L Ch R = 1,3928,473,473,473
BEGIN DESCRIPTION:
SEARCY BRANCH 2.0
END DESCRIPTION:
XS GIS Cut Line= 3
      2882001.08      7004950.50      2882751.07      7005582.44
      2884146.89      7005756.05
#Sta/Elev= 30
  3919.9  424.46  4033.2  421.41  4064.6  420.12  4216.6  412.26  4376.9  406.25
  4408.9  404.37  4414.3  401.76  4437.6  400.28  4455.3  399.21  4455.8  398.41
  4461.6  399.21  5370.1  399.21  5398.4  402.02  5408.4  407.81  5415.2  409.00
  5479.0  417.69  5532.2  420.26  5614.2  419.92  5761.1  415.95  5811.5  413.04
  5841.8  410.41  5902.2  399.41  5935.9  400.28  6003.0  408.63  6023.1  413.34
  6083.6  419.11  6164.2  423.04  6194.4  422.01  6295.1  424.77  6307.2  424.95
#Mann=11,-1,0
  3919.9    0.05       0  4033.2    0.08       0  4064.6    0.05       0
  4376.9    0.08       0  4414.3    0.05       0  4455.3   0.033       0
  4461.6    0.05       0  5415.2    0.16       0  5532.2    0.05       0
  5614.2    0.16       0  6295.1    0.05       0
Bank Sta=4437.6,5935.9
Exp/Cntr=0.3,0.1

Type RM Length L Ch R = 1,3455,0,0,0
BEGIN DESCRIPTION:
SEARCY BRANCH 1.0
END DESCRIPTION:
XS GIS Cut Line= 3
      2881875.02      7005375.01      2882744.12      7006103.27
      2883924.98      7006374.99
#Sta/Elev= 30
  3999.8  424.56  4049.9  423.65  4070.7  418.90  4091.5  417.18  4276.3  409.10
  4376.4  402.60  4382.9  403.53  4412.1  402.89  4454.5  402.76  4461.0  403.70
  4468.8  402.00  4475.3  403.04  4502.3  400.07  4512.6  399.65  4515.1  399.21
  4515.6  398.41  4521.4  399.21  5880.5  399.65  5904.2  401.86  5920.7  406.65
  5954.4  410.40  5976.0  412.66  6006.3  412.42  6011.5  414.12  6054.3  413.95
  6059.4  415.31  6088.9  415.52  6150.5  420.49  6235.8  425.03  6345.4  426.49
#Mann=6,-1,0
  3999.8    0.05       0  4412.1     0.1       0  4502.3    0.05       0
  4515.1   0.033       0  4521.4    0.05       0  5954.4    0.16       0
Bank Sta=4512.6,5880.5
Exp/Cntr=0.3,0.1

Chan Stop Cuts=-1