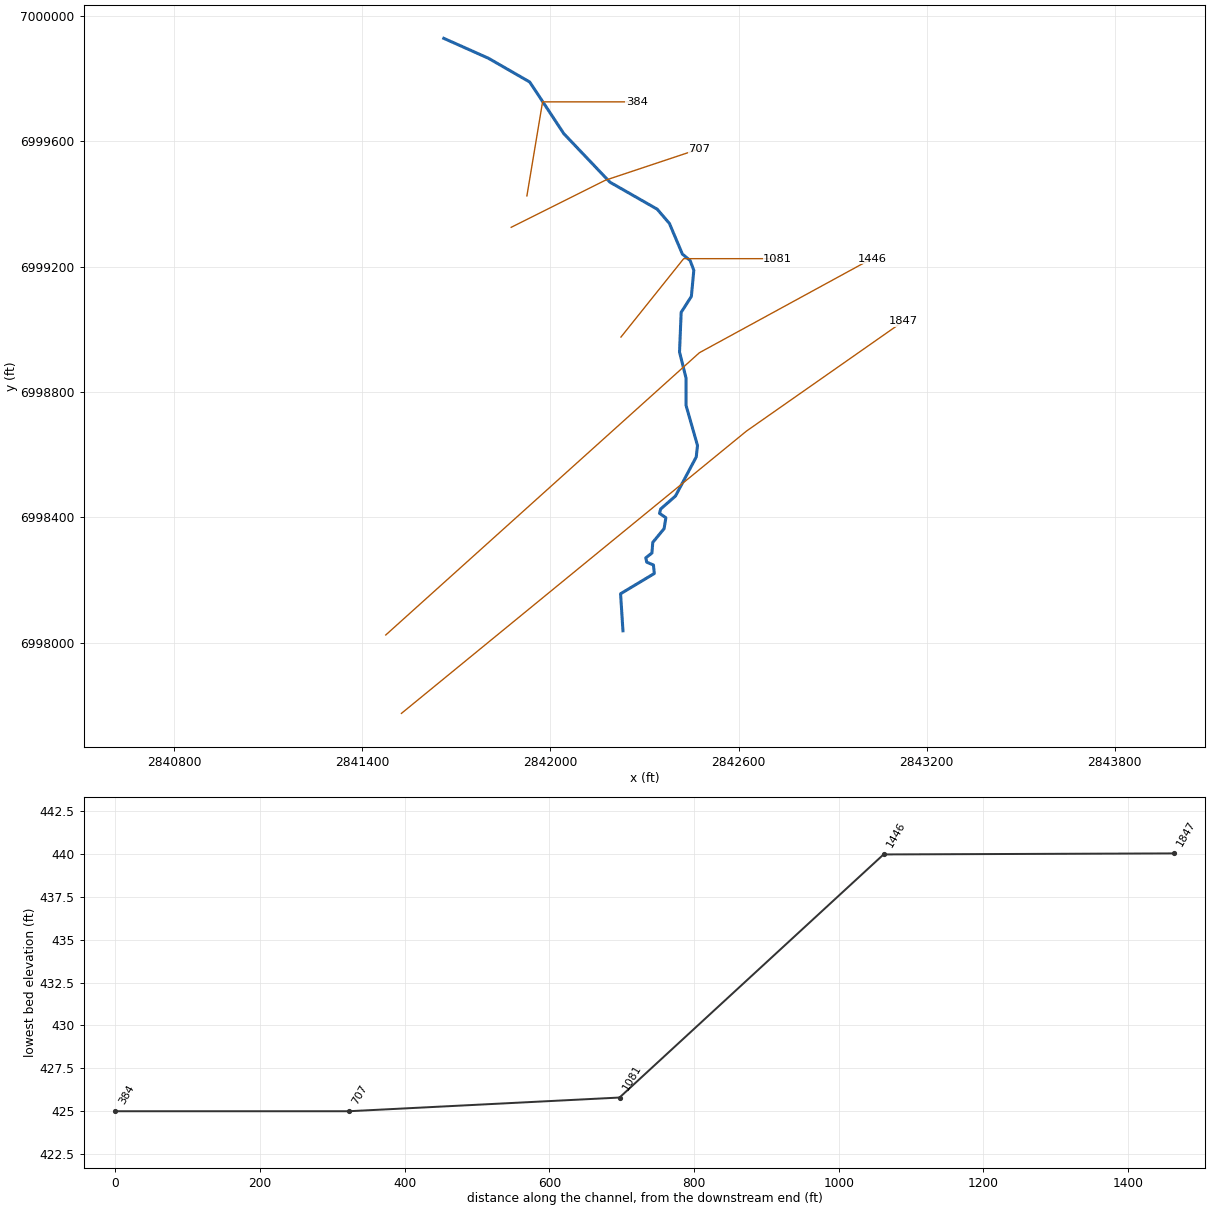
--- UNT 001 in Running Cr Watershed.prj (project) ---

Proj Title=UNT 001 in Running Cr Watershed Base Level Engineering
Current Plan=p01
Default Exp/Contr=0.3,0.1
English Units
Geom File=g01
Flow File=f01
Plan File=p01
BEGIN DESCRIPTION:
UNT 001 in Running Cr Watershed
END DESCRIPTION:

--- UNT 001 in Running Cr Watershed.p01 (plan) ---

Plan Title=Multiple Run
Short Identifier=Multiple
Geom File=g01
Flow File=f01
Subcritical Flow
K Sum by GR= 0
Std Step Tol= 0.01
Critical Tol= 0.01
Num of Std Step Trials= 20
Max Error Tol= 0.3
Flow Tol Ratio= 0.001
Split Flow NTrial= 30
Split Flow Tol= 0.02
Split Flow Ratio= 0.02
Log Output Level= 0
Friction Slope Method= 1
Unsteady Friction Slope Method= 2
Unsteady Bridges Friction Slope Method= 1
Parabolic Critical Depth
Global Vel Dist=  1 , 1 , 1
Global Log Level= 0
CheckData=True
Encroach Param= -1, 0, 0, 0
BEGIN DESCRIPTION:
Multiple Run
END DESCRIPTION:

--- UNT 001 in Running Cr Watershed.f01 (steady flow) ---

Flow Title=Multiple
Number of Profiles=7
Profile Names=10-year,25-year,50-year,1pct_min,100-year,1pct_plu,500-year
River Rch & RM= UNT 001 in Runni,Reach-1,1847
     112     134     149      83     167     332     206
Boundary for River Rch & Prof#=UNT 001 in Runni,Reach-1,1
Up Type=0
Dn Type=3
Dn Slope=0.005
Boundary for River Rch & Prof#=UNT 001 in Runni,Reach-1,2
Up Type=0
Dn Type=3
Dn Slope=0.005
Boundary for River Rch & Prof#=UNT 001 in Runni,Reach-1,3
Up Type=0
Dn Type=3
Dn Slope=0.005
Boundary for River Rch & Prof#=UNT 001 in Runni,Reach-1,4
Up Type=0
Dn Type=3
Dn Slope=0.005
Boundary for River Rch & Prof#=UNT 001 in Runni,Reach-1,5
Up Type=0
Dn Type=3
Dn Slope=0.005
Boundary for River Rch & Prof#=UNT 001 in Runni,Reach-1,6
Up Type=0
Dn Type=3
Dn Slope=0.005
Boundary for River Rch & Prof#=UNT 001 in Runni,Reach-1,7
Up Type=0
Dn Type=3
Dn Slope=0.005

--- UNT 001 in Running Cr Watershed.g01 (geometry) ---

Geom Title=Existing Conditions

River Reach=UNT 001 in Runni,Reach-1
Reach XY= 30
      2842231.35      6998038.41      2842223.71      6998156.46
      2842331.35      6998221.05      2842328.57      6998248.13
      2842307.04      6998257.16      2842304.26      6998271.05
      2842323.71      6998286.32      2842326.48      6998320.35
      2842362.60      6998364.10      2842368.15      6998398.82
      2842348.01      6998412.71      2842351.48      6998426.60
      2842398.71      6998467.83      2842465.11      6998592.83
      2842469.02      6998629.29      2842432.56      6998756.90
      2842432.56      6998844.14      2842411.73      6998927.47
      2842416.94      6999053.77      2842449.49      6999104.55
      2842457.30      6999187.89      2842445.58      6999219.14
      2842420.84      6999239.54      2842379.61      6999337.19
      2842340.55      6999382.76      2842189.89      6999468.88
      2842042.97      6999623.37      2841933.91      6999788.47
      2841802.14      6999864.20      2841659.97      6999927.60

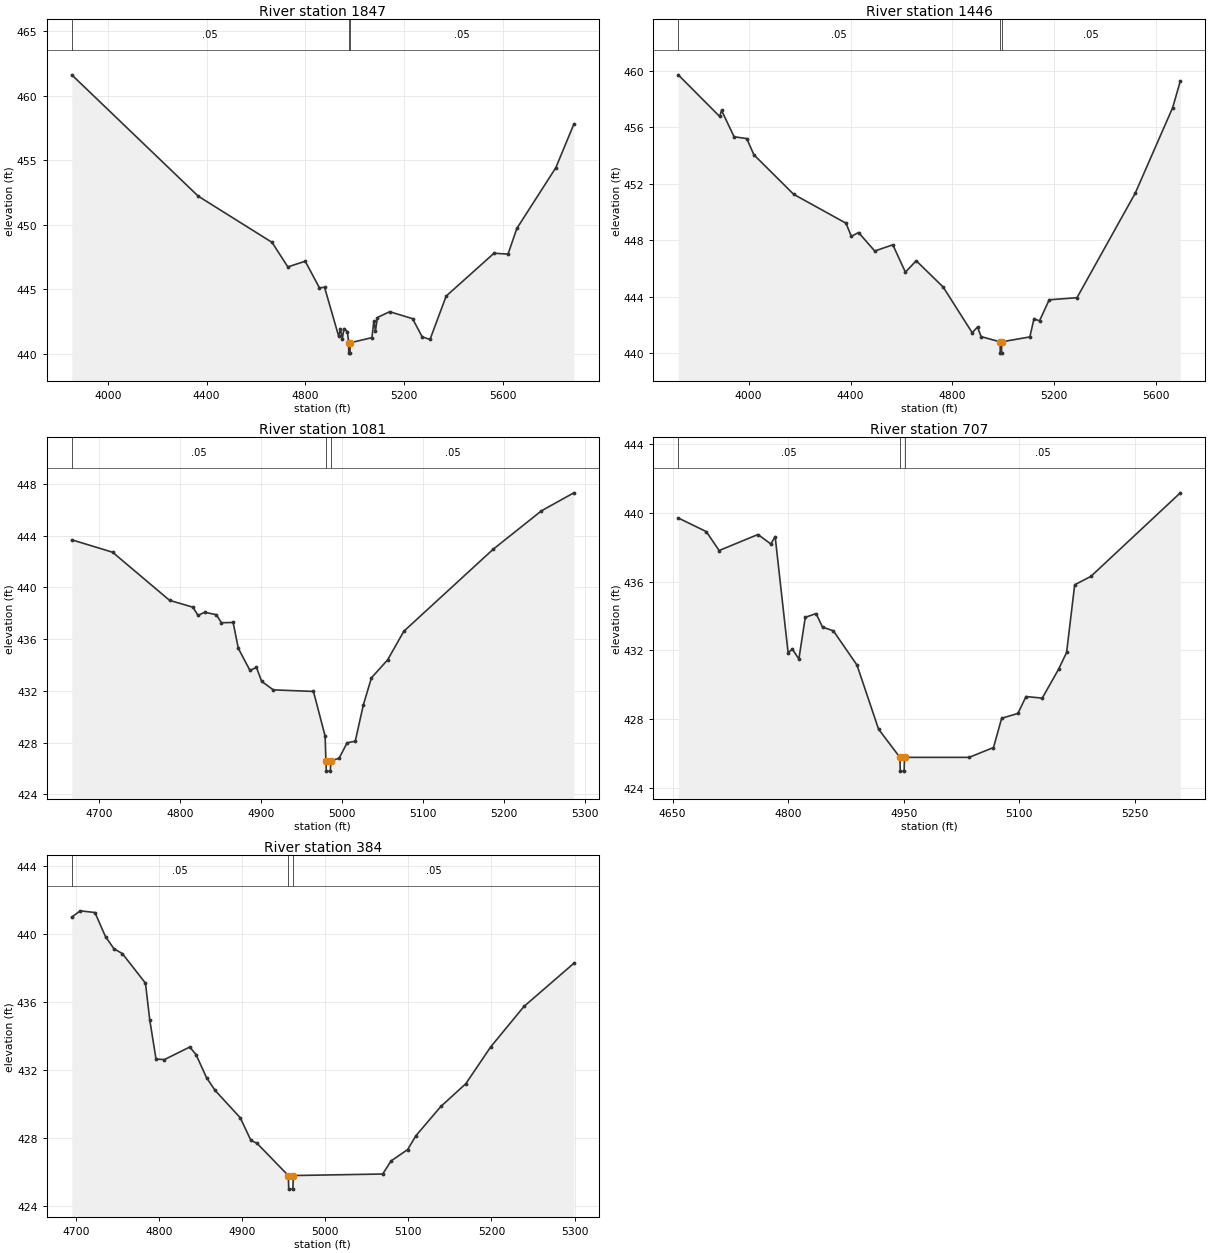
Type RM Length L Ch R = 1,1847,401,401,401
BEGIN DESCRIPTION:
UNT 001 in Running Cr Watershed 5.0
END DESCRIPTION:
XS GIS Cut Line= 3
      2841524.99      6997774.99      2842625.00      6998675.00
      2843124.99      6999024.99
#Sta/Elev= 30
  3854.4  461.61  4366.2  452.21  4664.8  448.63  4728.7  446.73  4799.1  447.17
  4856.5  445.11  4877.3  445.15  4934.7  441.34  4941.2  441.95  4949.1  441.16
  4955.5  441.95  4969.9  441.72  4974.8  440.85  4975.3  440.05  4980.3  440.05
  4980.8  440.85  5069.0  441.25  5076.8  442.55  5083.3  441.78  5091.2  442.81
  5140.7  443.26  5233.3  442.72  5272.5  441.31  5304.0  441.11  5369.4  444.47
  5563.0  447.79  5619.6  447.72  5655.4  449.71  5813.2  454.42  5886.0  457.79
#Mann=3,-1,0
  3854.4    0.05       0  4974.8    0.03       0  4980.8    0.05       0
Bank Sta=4974.8,4980.8
Exp/Cntr=0.3,0.1

Type RM Length L Ch R = 1,1446,365,365,365
BEGIN DESCRIPTION:
UNT 001 in Running Cr Watershed 4.0
END DESCRIPTION:
XS GIS Cut Line= 3
      2841474.96      6998024.97      2842475.00      6998925.00
      2843024.99      6999225.00
#Sta/Elev= 30
  3723.4  459.72  3886.0  456.77  3893.5  457.20  3942.8  455.33  3992.5  455.20
  4020.6  454.05  4176.8  451.25  4382.3  449.20  4403.2  448.27  4431.6  448.54
  4495.2  447.23  4566.2  447.67  4615.5  445.73  4658.1  446.54  4764.2  444.67
  4877.8  441.44  4898.8  441.84  4913.0  441.16  4987.7  440.79  4988.2  439.99
  4993.2  439.99  4993.7  440.79  5104.4  441.14  5120.5  442.42  5142.4  442.28
  5180.3  443.77  5289.5  443.92  5518.3  451.33  5665.4  457.40  5695.3  459.28
#Mann=3,-1,0
  3723.4    0.05       0  4987.7    0.03       0  4993.7    0.05       0
Bank Sta=4987.7,4993.7
Exp/Cntr=0.3,0.1

Type RM Length L Ch R = 1,1081,374,374,374
BEGIN DESCRIPTION:
UNT 001 in Running Cr Watershed 3.0
END DESCRIPTION:
XS GIS Cut Line= 3
      2842225.02      6998975.02      2842425.00      6999225.00
      2842724.97      6999225.00
#Sta/Elev= 30
  4666.4  443.67  4716.8  442.71  4787.2  438.99  4816.0  438.46  4822.4  437.82
  4830.5  438.07  4844.9  437.88  4851.3  437.26  4865.7  437.28  4872.1  435.28
  4886.5  433.57  4894.5  433.81  4900.9  432.73  4915.3  432.07  4964.9  431.95
  4979.3  428.50  4980.3  426.59  4980.8  425.79  4985.8  425.79  4986.3  426.59
  4996.5  426.78  5006.5  427.98  5016.5  428.10  5026.5  430.90  5036.5  433.00
  5056.5  434.39  5076.5  436.60  5186.5  442.92  5246.5  445.91  5286.5  447.30
#Mann=3,-1,0
  4666.4    0.05       0  4980.3    0.03       0  4986.3    0.05       0
Bank Sta=4980.3,4986.3
Exp/Cntr=0.3,0.1

Type RM Length L Ch R = 1,707,323,323,323
BEGIN DESCRIPTION:
UNT 001 in Running Cr Watershed 2.0
END DESCRIPTION:
XS GIS Cut Line= 3
      2841874.97      6999324.99      2842175.00      6999475.00
      2842475.03      6999575.01
#Sta/Elev= 30
  4657.3  439.69  4693.7  438.90  4710.4  437.80  4760.8  438.73  4777.5  438.18
  4783.1  438.61  4799.9  431.87  4805.5  432.07  4813.9  431.50  4822.2  433.92
  4836.2  434.14  4844.6  433.35  4858.6  433.14  4889.3  431.15  4917.3  427.43
  4945.0  425.79  4945.5  424.99  4950.5  424.99  4951.0  425.79  5034.9  425.79
  5066.5  426.36  5077.1  428.06  5098.2  428.34  5108.7  429.32  5129.8  429.23
  5150.9  430.90  5161.4  431.88  5171.9  435.81  5193.0  436.30  5309.0  441.15
#Mann=3,-1,0
  4657.3    0.05       0  4945.0    0.03       0  4951.0    0.05       0
Bank Sta=4945,4951
Exp/Cntr=0.3,0.1

Type RM Length L Ch R = 1,384,0,0,0
BEGIN DESCRIPTION:
UNT 001 in Running Cr Watershed 1.0
END DESCRIPTION:
XS GIS Cut Line= 3
      2841925.00      6999424.98      2841975.00      6999725.00
      2842275.04      6999725.00
#Sta/Elev= 30
  4695.0  441.01  4705.2  441.38  4722.9  441.28  4735.6  439.86  4745.7  439.15
  4755.9  438.86  4783.7  437.12  4788.8  434.97  4796.4  432.65  4806.5  432.62
  4837.0  433.36  4844.6  432.91  4857.2  431.55  4867.4  430.81  4897.8  429.19
  4910.5  427.87  4918.1  427.68  4955.6  425.79  4956.1  424.99  4961.1  424.99
  4961.6  425.79  5069.2  425.88  5079.2  426.65  5099.2  427.32  5109.2  428.14
  5139.2  429.86  5169.2  431.20  5199.2  433.37  5239.2  435.75  5299.2  438.29
#Mann=3,-1,0
  4695.0    0.05       0  4955.6    0.03       0  4961.6    0.05       0
Bank Sta=4955.6,4961.6
Exp/Cntr=0.3,0.1

Chan Stop Cuts=-1