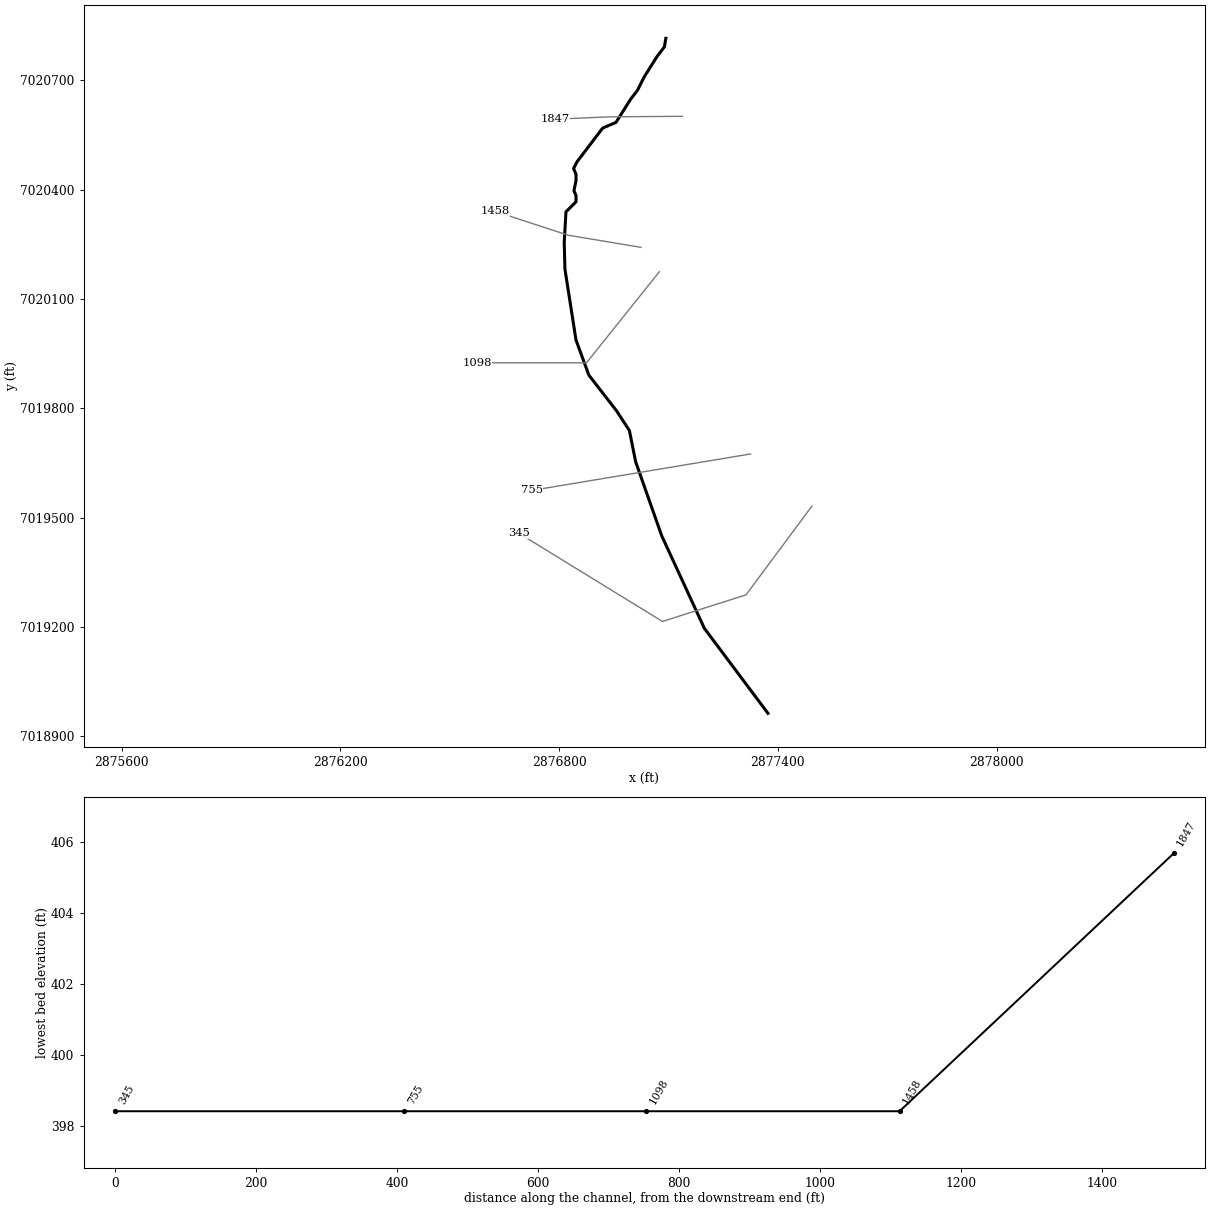
--- UNT 003 in Running Cr Watershed.prj (project) ---

Proj Title=UNT 003 in Running Cr Watershed Base Level Engineering
Current Plan=p01
Default Exp/Contr=0.3,0.1
English Units
Geom File=g01
Flow File=f01
Plan File=p01
BEGIN DESCRIPTION:
UNT 003 in Running Cr Watershed
END DESCRIPTION:

--- UNT 003 in Running Cr Watershed.p01 (plan) ---

Plan Title=Multiple Run
Short Identifier=Multiple
Geom File=g01
Flow File=f01
Subcritical Flow
K Sum by GR= 0
Std Step Tol= 0.01
Critical Tol= 0.01
Num of Std Step Trials= 20
Max Error Tol= 0.3
Flow Tol Ratio= 0.001
Split Flow NTrial= 30
Split Flow Tol= 0.02
Split Flow Ratio= 0.02
Log Output Level= 0
Friction Slope Method= 1
Unsteady Friction Slope Method= 2
Unsteady Bridges Friction Slope Method= 1
Parabolic Critical Depth
Global Vel Dist=  1 , 1 , 1
Global Log Level= 0
CheckData=True
Encroach Param= -1, 0, 0, 0
BEGIN DESCRIPTION:
Multiple Run
END DESCRIPTION:

--- UNT 003 in Running Cr Watershed.f01 (steady flow) ---

Flow Title=Multiple
Number of Profiles=7
Profile Names=10-year,25-year,50-year,1pct_min,100-year,1pct_plu,500-year
River Rch & RM= UNT 003 in Runni,Reach-1,1847
     147     179     202     114     228     454     288
Boundary for River Rch & Prof#=UNT 003 in Runni,Reach-1,1
Up Type=0
Dn Type=3
Dn Slope=0.005
Boundary for River Rch & Prof#=UNT 003 in Runni,Reach-1,2
Up Type=0
Dn Type=3
Dn Slope=0.005
Boundary for River Rch & Prof#=UNT 003 in Runni,Reach-1,3
Up Type=0
Dn Type=3
Dn Slope=0.005
Boundary for River Rch & Prof#=UNT 003 in Runni,Reach-1,4
Up Type=0
Dn Type=3
Dn Slope=0.005
Boundary for River Rch & Prof#=UNT 003 in Runni,Reach-1,5
Up Type=0
Dn Type=3
Dn Slope=0.005
Boundary for River Rch & Prof#=UNT 003 in Runni,Reach-1,6
Up Type=0
Dn Type=3
Dn Slope=0.005
Boundary for River Rch & Prof#=UNT 003 in Runni,Reach-1,7
Up Type=0
Dn Type=3
Dn Slope=0.005

--- UNT 003 in Running Cr Watershed.g01 (geometry) ---

Geom Title=Existing Conditions

River Reach=UNT 003 in Runni,Reach-1
Reach XY= 26
      2877092.68      7020815.08      2877088.77      7020791.64
      2877067.94      7020764.30      2877032.78      7020708.31
      2877014.55      7020671.85      2876996.32      7020648.41
      2876955.93      7020584.48      2876919.50      7020568.99
      2876849.19      7020476.54      2876839.68      7020458.13
      2876846.33      7020441.96      2876846.33      7020424.84
      2876840.63      7020397.26      2876846.33      7020383.94
      2876846.33      7020366.82      2876818.75      7020339.23
      2876813.99      7020255.52      2876815.89      7020182.28
      2876846.33      7019987.28      2876881.53      7019891.21
      2876957.63      7019793.23      2876992.82      7019739.01
      2877009.94      7019653.40      2877081.29      7019450.79
      2877198.29      7019196.81      2877372.88      7018963.43

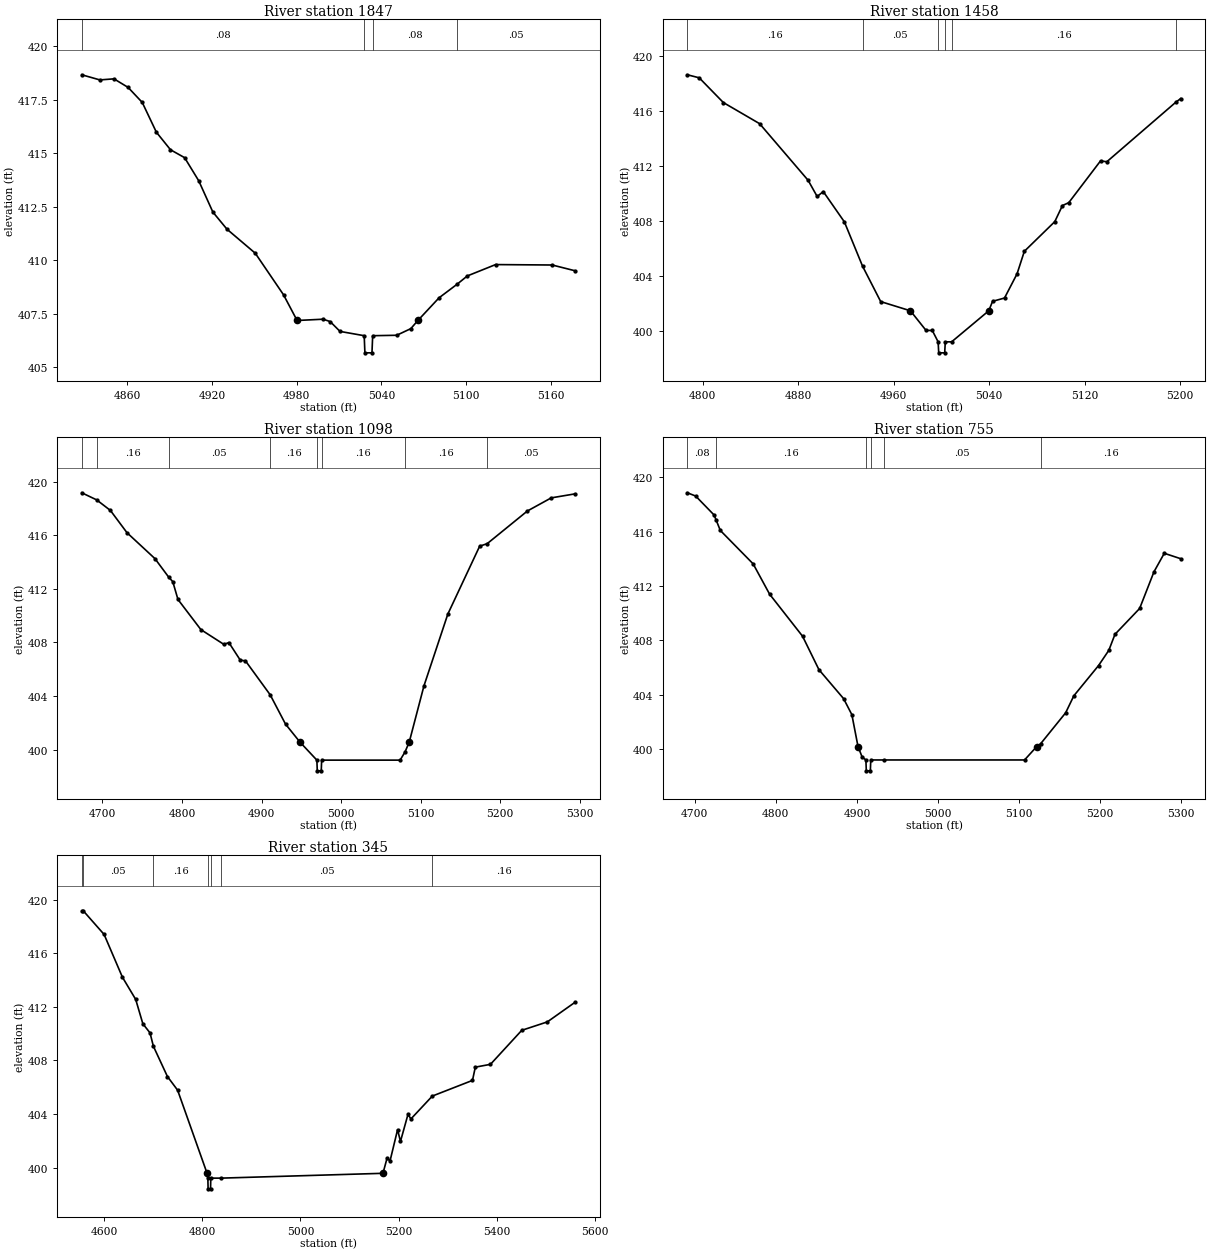
Type RM Length L Ch R = 1,1847,389,389,389
BEGIN DESCRIPTION:
UNT 003 in Running Cr Watershed 5.0
END DESCRIPTION:
XS GIS Cut Line= 3
      2877137.84      7020601.16      2876942.53      7020599.86
      2876788.78      7020593.40
#Sta/Elev= 30
  4827.9  418.66  4840.7  418.42  4850.7  418.47  4860.7  418.07  4870.7  417.37
  4880.7  415.98  4890.7  415.16  4900.7  414.79  4910.7  413.71  4920.7  412.25
  4930.7  411.45  4950.7  410.33  4970.7  408.39  4980.3  407.19  4998.7  407.25
  5003.7  407.14  5010.7  406.68  5027.8  406.48  5028.3  405.68  5033.3  405.68
  5033.8  406.48  5050.8  406.50  5060.8  406.81  5065.8  407.19  5080.8  408.25
  5093.5  408.88  5100.8  409.27  5120.8  409.80  5160.9  409.78  5177.1  409.51
#Mann=4,-1,0
  4827.9    0.08       0  5027.8    0.07       0  5033.8    0.08       0
  5093.5    0.05       0
Bank Sta=4980.3,5065.8
Exp/Cntr=0.3,0.1

Type RM Length L Ch R = 1,1458,360,360,360
BEGIN DESCRIPTION:
UNT 003 in Running Cr Watershed 4.0
END DESCRIPTION:
XS GIS Cut Line= 3
      2877024.72      7020241.71      2876825.00      7020275.00
      2876624.67      7020340.37
#Sta/Elev= 30
  4787.3  418.65  4797.2  418.43  4817.4  416.63  4847.8  415.09  4888.4  410.97
  4896.0  409.79  4901.1  410.15  4918.8  407.94  4934.0  404.72  4949.2  402.14
  4974.1  401.47  4987.2  400.04  4992.4  400.04  4997.3  399.21  4997.8  398.41
  5002.8  398.41  5003.3  399.21  5008.6  399.21  5039.7  401.47  5042.9  402.16
  5052.9  402.40  5063.4  404.16  5069.5  405.80  5095.0  407.96  5101.4  409.13
  5106.7  409.34  5133.3  412.38  5138.6  412.32  5196.6  416.67  5200.5  416.92
#Mann=6,-1,0
  4787.3    0.16       0  4934.0    0.05       0  4997.3   0.035       0
  5003.3    0.05       0  5008.6    0.16       0  5196.6    0.05       0
Bank Sta=4974.1,5039.7
Exp/Cntr=0.3,0.1

Type RM Length L Ch R = 1,1098,343,343,343
BEGIN DESCRIPTION:
UNT 003 in Running Cr Watershed 3.0
END DESCRIPTION:
XS GIS Cut Line= 3
      2877075.00      7020174.99      2876875.00      7019925.00
      2876575.05      7019925.00
#Sta/Elev= 30
  4674.0  419.18  4692.7  418.65  4710.0  417.86  4730.8  416.20  4766.0  414.26
  4783.1  412.89  4788.4  412.54  4794.9  411.21  4823.7  408.96  4852.5  407.86
  4858.9  407.99  4873.3  406.67  4879.7  406.63  4910.8  404.09  4930.1  401.90
  4948.2  400.56  4969.5  399.21  4970.0  398.41  4975.0  398.41  4975.5  399.21
  5074.1  399.21  5080.3  399.82  5085.6  400.56  5104.1  404.76  5134.1  410.12
  5174.1  415.19  5183.6  415.38  5234.1  417.82  5264.1  418.80  5294.1  419.10
#Mann=8,-1,0
  4674.0    0.05       0  4692.7    0.16       0  4783.1    0.05       0
  4910.8    0.16       0  4969.5   0.033       0  4975.5    0.16       0
  5080.3    0.16       0  5183.6    0.05       0
Bank Sta=4948.2,5085.6
Exp/Cntr=0.3,0.1

Type RM Length L Ch R = 1,755,410,410,410
BEGIN DESCRIPTION:
UNT 003 in Running Cr Watershed 2.0
END DESCRIPTION:
XS GIS Cut Line= 3
      2877325.02      7019675.00      2877025.00      7019625.00
      2876725.00      7019575.00
#Sta/Elev= 30
  4691.0  418.86  4701.2  418.62  4724.0  417.22  4726.4  416.86  4731.6  416.09
  4772.1  413.63  4792.4  411.40  4833.0  408.31  4853.2  405.85  4883.6  403.72
  4893.8  402.54  4901.4  400.19  4906.5  399.42  4911.1  399.21  4911.6  398.41
  4916.6  398.41  4917.1  399.21  4933.2  399.21  5106.7  399.21  5121.5  400.18
  5126.5  400.40  5157.4  402.68  5167.5  403.93  5197.9  406.15  5210.6  407.27
  5218.2  408.45  5248.6  410.35  5266.3  413.05  5279.0  414.41  5299.3  414.01
#Mann=6,-1,0
  4691.0    0.08       0  4726.4    0.16       0  4911.1   0.033       0
  4917.1    0.16       0  4933.2    0.05       0  5126.5    0.16       0
Bank Sta=4901.4,5121.5
Exp/Cntr=0.3,0.1

Type RM Length L Ch R = 1,345,0,0,0
BEGIN DESCRIPTION:
UNT 003 in Running Cr Watershed 1.0
END DESCRIPTION:
XS GIS Cut Line= 4
      2877493.18      7019531.59      2877312.61      7019288.51
      2877083.44      7019215.60      2876688.79      7019457.93
#Sta/Elev= 30
  4553.9  419.18  4556.9  419.18  4599.5  417.41  4636.8  414.22  4663.9  412.56
  4678.5  410.74  4693.1  410.06  4700.0  409.06  4728.6  406.80  4749.4  405.78
  4809.5  399.57  4811.1  399.21  4811.6  398.41  4816.6  398.41  4817.1  399.21
  4838.4  399.21  5168.3  399.57  5176.8  400.72  5182.7  400.49  5198.1  402.83
  5204.0  401.95  5219.4  403.98  5225.3  403.63  5269.0  405.34  5350.9  406.51
  5356.7  407.50  5387.6  407.71  5451.4  410.25  5503.6  410.88  5560.3  412.35
#Mann=7,-1,0
  4553.9    0.08       0  4556.9    0.05       0  4700.0    0.16       0
  4811.1   0.033       0  4817.1    0.16       0  4838.4    0.05       0
  5269.0    0.16       0
Bank Sta=4809.5,5168.3
Exp/Cntr=0.3,0.1

Chan Stop Cuts=-1