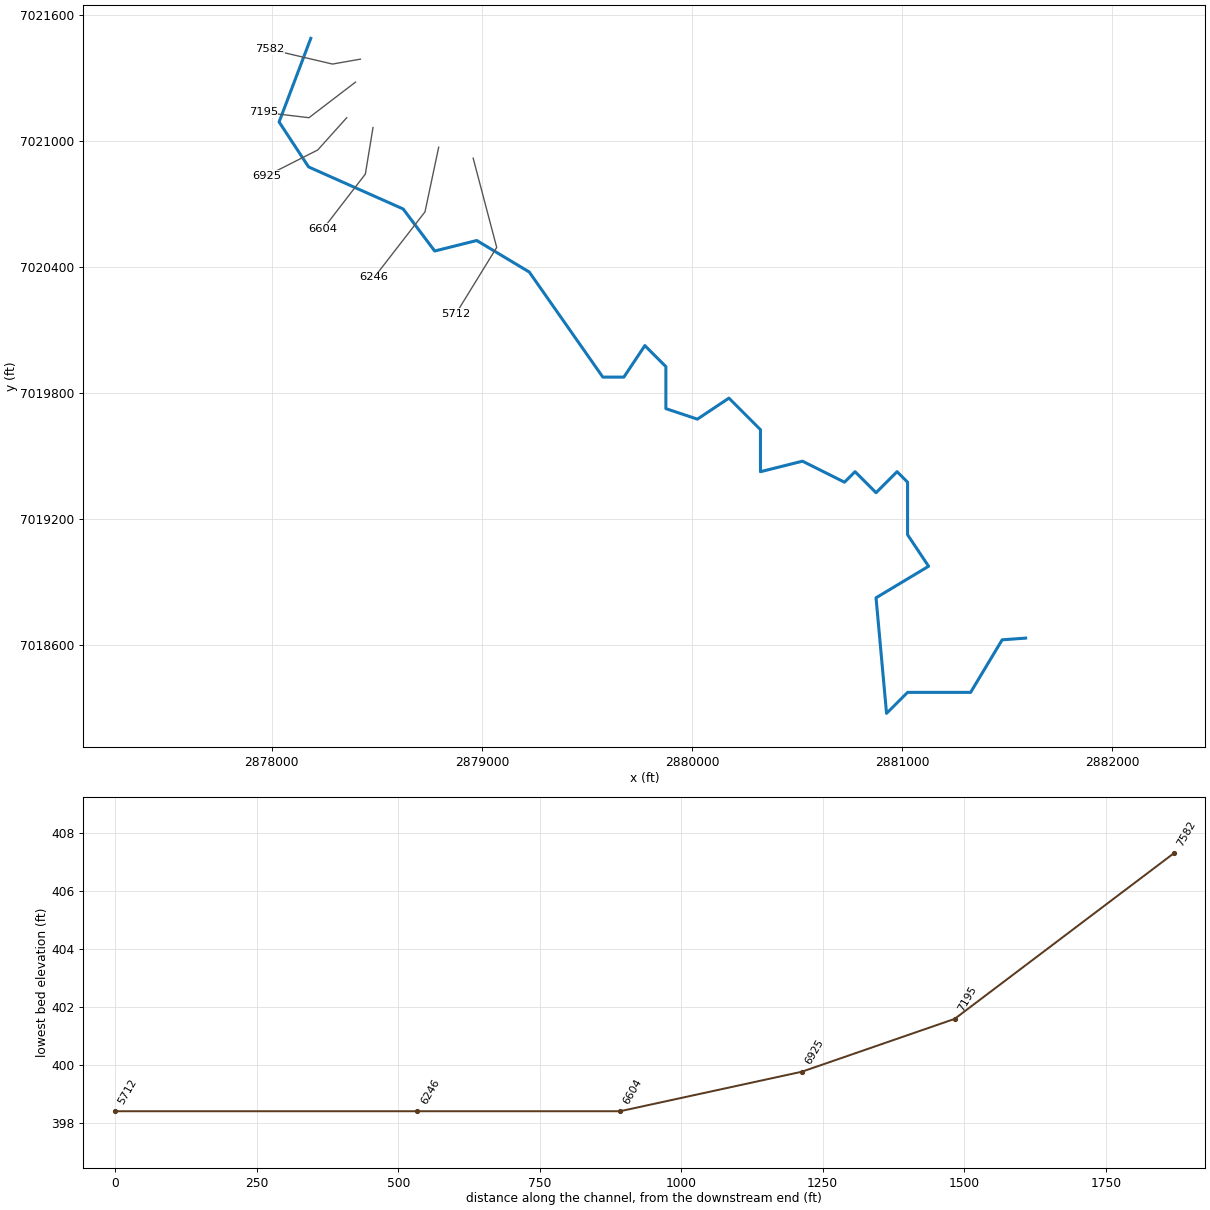
--- UNT 004 in Running Cr Watershed.prj (project) ---

Proj Title=UNT 004 in Running Cr Watershed Base Level Engineering
Current Plan=p01
Default Exp/Contr=0.3,0.1
English Units
Geom File=g01
Flow File=f01
Plan File=p01
BEGIN DESCRIPTION:
UNT 004 in Running Cr Watershed
END DESCRIPTION:

--- UNT 004 in Running Cr Watershed.p01 (plan) ---

Plan Title=Multiple Run
Short Identifier=Multiple
Geom File=g01
Flow File=f01
Subcritical Flow
K Sum by GR= 0
Std Step Tol= 0.01
Critical Tol= 0.01
Num of Std Step Trials= 20
Max Error Tol= 0.3
Flow Tol Ratio= 0.001
Split Flow NTrial= 30
Split Flow Tol= 0.02
Split Flow Ratio= 0.02
Log Output Level= 0
Friction Slope Method= 1
Unsteady Friction Slope Method= 2
Unsteady Bridges Friction Slope Method= 1
Parabolic Critical Depth
Global Vel Dist=  1 , 1 , 1
Global Log Level= 0
CheckData=True
Encroach Param= -1, 0, 0, 0
BEGIN DESCRIPTION:
Multiple Run
END DESCRIPTION:

--- UNT 004 in Running Cr Watershed.f01 (steady flow) ---

Flow Title=Multiple
Number of Profiles=7
Profile Names=10-year,25-year,50-year,1pct_min,100-year,1pct_plu,500-year
River Rch & RM= UNT 004 in Runni,Reach-1,7582
     109     127     140      77     154     307     185
Boundary for River Rch & Prof#=UNT 004 in Runni,Reach-1,1
Up Type=0
Dn Type=3
Dn Slope=0.005
Boundary for River Rch & Prof#=UNT 004 in Runni,Reach-1,2
Up Type=0
Dn Type=3
Dn Slope=0.005
Boundary for River Rch & Prof#=UNT 004 in Runni,Reach-1,3
Up Type=0
Dn Type=3
Dn Slope=0.005
Boundary for River Rch & Prof#=UNT 004 in Runni,Reach-1,4
Up Type=0
Dn Type=3
Dn Slope=0.005
Boundary for River Rch & Prof#=UNT 004 in Runni,Reach-1,5
Up Type=0
Dn Type=3
Dn Slope=0.005
Boundary for River Rch & Prof#=UNT 004 in Runni,Reach-1,6
Up Type=0
Dn Type=3
Dn Slope=0.005
Boundary for River Rch & Prof#=UNT 004 in Runni,Reach-1,7
Up Type=0
Dn Type=3
Dn Slope=0.005

--- UNT 004 in Running Cr Watershed.g01 (geometry) ---

Geom Title=Existing Conditions

River Reach=UNT 004 in Runni,Reach-1
Reach XY= 30
      2878185.38      7021486.92      2878034.68      7021089.01
      2878175.00      7020875.00      2878625.00      7020675.00
      2878775.00      7020475.00      2878975.00      7020525.00
      2879225.00      7020375.00      2879575.00      7019875.00
      2879675.00      7019875.00      2879775.00      7020025.00
      2879875.00      7019925.00      2879875.00      7019725.00
      2880025.00      7019675.00      2880175.00      7019775.00
      2880325.00      7019625.00      2880325.00      7019425.00
      2880525.00      7019475.00      2880725.00      7019375.00
      2880775.00      7019425.00      2880875.00      7019325.00
      2880975.00      7019425.00      2881025.00      7019375.00
      2881025.00      7019125.00      2881125.00      7018975.00
      2880875.00      7018825.00      2880925.00      7018275.00
      2881025.00      7018375.00      2881325.00      7018375.00
      2881475.00      7018625.00      2881586.69      7018633.12

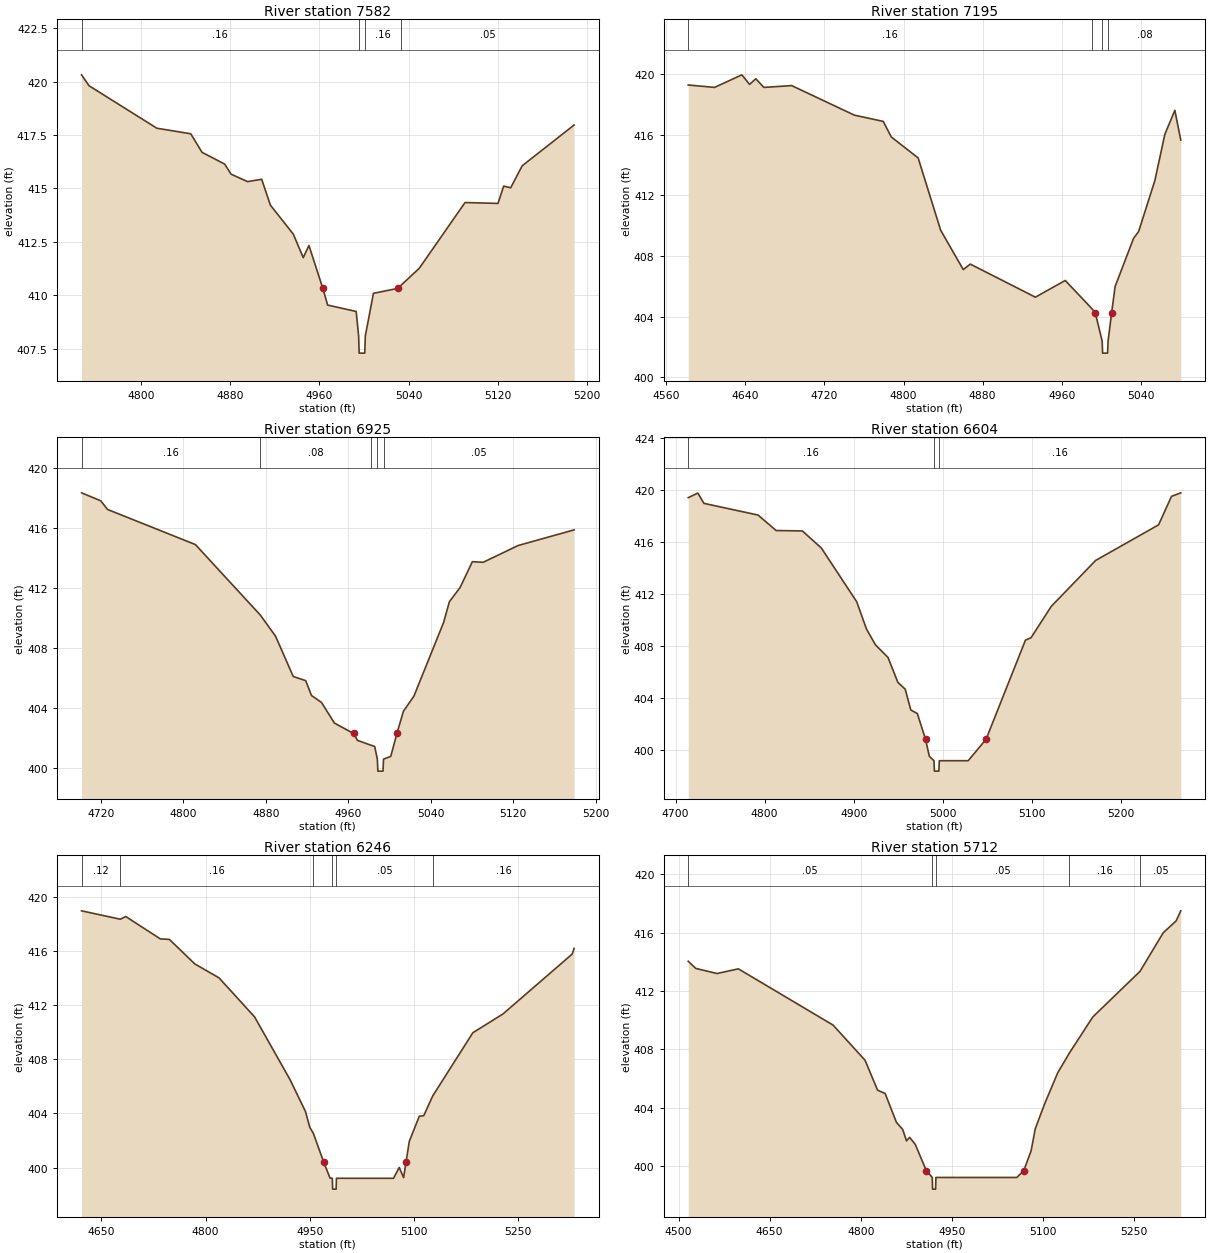
Type RM Length L Ch R = 1,7582,387,387,387
BEGIN DESCRIPTION:
UNT 004 in Running Cr Watershed 3.0
END DESCRIPTION:
XS GIS Cut Line= 3
      2878421.56      7021387.92      2878288.76      7021364.49
      2877989.64      7021434.71
#Sta/Elev= 30
  4746.5  420.32  4753.2  419.81  4814.1  417.82  4844.5  417.56  4854.7  416.69
  4875.0  416.14  4880.7  415.67  4895.5  415.32  4908.2  415.43  4916.0  414.22
  4936.6  412.86  4945.5  411.76  4950.6  412.33  4963.1  410.32  4967.4  409.54
  4993.0  409.24  4995.2  408.09  4995.7  407.29  5000.7  407.29  5001.2  408.09
  5008.5  410.09  5030.4  410.32  5032.9  410.45  5049.6  411.26  5090.7  414.34
  5120.3  414.30  5125.4  415.11  5131.7  415.03  5142.0  416.06  5188.6  417.97
#Mann=4,-1,0
  4746.5    0.16       0  4995.2    0.07       0  5001.2    0.16       0
  5032.9    0.05       0
Bank Sta=4963.1,5030.4
Exp/Cntr=0.3,0.1

Type RM Length L Ch R = 1,7195,270,270,270
BEGIN DESCRIPTION:
Mapping XS 65af14ea
END DESCRIPTION:
XS GIS Cut Line= 3
      2878398.09      7021278.52      2878176.78      7021109.28
      2877959.03      7021135.20
#Sta/Elev= 30
  4582.4  419.27  4609.0  419.11  4636.6  419.94  4644.4  419.31  4650.7  419.68
  4658.9  419.11  4687.0  419.23  4750.4  417.28  4779.5  416.87  4787.7  415.84
  4814.8  414.46  4837.6  409.69  4860.4  407.10  4867.5  407.46  4933.3  405.28
  4963.5  406.38  4990.2  404.54  4993.9  404.24  5000.8  402.39  5001.3  401.59
  5006.3  401.59  5006.8  402.39  5010.4  404.24  5013.9  405.98  5032.6  409.16
  5037.7  409.61  5054.1  412.97  5064.2  416.02  5074.3  417.60  5080.3  415.64
#Mann=4,-1,0
  4582.4    0.16       0  4990.2    0.08       0  5000.8    0.07       0
  5006.8    0.08       0
Bank Sta=4993.9,5010.4
Exp/Cntr=0.3,0.1

Type RM Length L Ch R = 1,6925,321,321,321
BEGIN DESCRIPTION:
Mapping XS e6167e87
END DESCRIPTION:
XS GIS Cut Line= 3
      2878356.48      7021109.29      2878218.44      7020955.63
      2877976.27      7020833.24
#Sta/Elev= 30
  4701.1  418.32  4719.7  417.79  4726.4  417.21  4811.6  414.87  4874.6  410.17
  4889.3  408.77  4906.5  406.08  4918.6  405.80  4924.2  404.81  4933.9  404.35
  4946.5  402.97  4965.0  402.28  4968.8  401.82  4981.8  401.50  4985.5  401.42
  4988.1  400.57  4988.6  399.77  4993.6  399.77  4994.1  400.57  5001.1  400.75
  5007.1  402.28  5013.4  403.76  5023.6  404.77  5052.4  409.68  5058.0  411.06
  5068.4  412.01  5080.3  413.73  5090.8  413.69  5124.8  414.81  5179.0  415.85
#Mann=5,-1,0
  4701.1    0.16       0  4874.6    0.08       0  4981.8    0.05       0
  4988.1    0.04       0  4994.1    0.05       0
Bank Sta=4965,5007.1
Exp/Cntr=0.3,0.1

Type RM Length L Ch R = 1,6604,358,358,358
BEGIN DESCRIPTION:
Mapping XS ebbd68fd
END DESCRIPTION:
XS GIS Cut Line= 3
      2878481.47      7021062.40      2878445.01      7020841.05
      2878244.49      7020580.64
#Sta/Elev= 30
  4714.3  419.44  4725.1  419.79  4731.9  419.00  4792.7  418.10  4813.0  416.91
  4842.4  416.88  4863.7  415.57  4903.5  411.43  4914.4  409.34  4924.5  408.12
  4938.6  407.15  4949.7  405.23  4957.9  404.71  4964.2  403.11  4971.5  402.84
  4980.7  400.86  4985.0  399.55  4990.2  399.21  4990.7  398.41  4995.7  398.41
  4996.2  399.21  5028.6  399.21  5048.7  400.86  5092.9  408.48  5099.2  408.67
  5121.9  411.08  5171.7  414.61  5242.4  417.35  5256.9  419.54  5267.3  419.81
#Mann=3,-1,0
  4714.3    0.16       0  4990.2    0.07       0  4996.2    0.16       0
Bank Sta=4980.7,5048.7
Exp/Cntr=0.3,0.1

Type RM Length L Ch R = 1,6246,534,534,534
BEGIN DESCRIPTION:
UNT 004 in Running Cr Watershed 2.0
END DESCRIPTION:
XS GIS Cut Line= 3
      2878793.96      7020968.63      2878728.86      7020661.36
      2878487.14      7020349.46
#Sta/Elev= 30
  4621.6  418.95  4677.4  418.33  4685.2  418.53  4734.9  416.88  4748.0  416.84
  4784.6  415.03  4819.5  414.00  4870.6  411.12  4921.8  406.47  4943.7  404.15
  4950.1  402.96  4955.2  402.52  4970.0  400.41  4979.1  399.23  4982.4  399.21
  4982.9  398.41  4987.9  398.41  4988.4  399.21  5070.5  399.21  5078.7  400.01
  5085.0  399.26  5088.5  400.41  5093.2  401.94  5107.6  403.79  5114.0  403.83
  5126.8  405.28  5184.6  409.95  5228.0  411.34  5327.6  415.76  5330.3  416.18
#Mann=6,-1,0
  4621.6    0.12       0  4677.4    0.16       0  4955.2    0.05       0
  4982.4   0.033       0  4988.4    0.05       0  5126.8    0.16       0
Bank Sta=4970,5088.5
Exp/Cntr=0.3,0.1

Type RM Length L Ch R = 1,5712,0,0,0
BEGIN DESCRIPTION:
UNT 004 in Running Cr Watershed 1.0
END DESCRIPTION:
XS GIS Cut Line= 3
      2878958.04      7020916.53      2879070.01      7020492.09
      2878875.01      7020175.01
#Sta/Elev= 30
  4515.9  414.04  4528.3  413.55  4563.4  413.20  4598.5  413.52  4754.5  409.66
  4807.1  407.25  4827.7  405.20  4840.2  404.97  4858.8  402.99  4869.1  402.50
  4875.4  401.72  4880.5  401.96  4889.8  401.48  4908.0  399.68  4917.8  399.21
  4918.3  398.41  4923.3  398.41  4923.8  399.21  5057.1  399.21  5068.5  399.68
  5080.6  401.04  5087.5  402.56  5102.9  404.26  5124.2  406.37  5143.4  407.73
  5182.2  410.22  5260.0  413.35  5298.1  415.99  5319.4  416.81  5327.1  417.50
#Mann=5,-1,0
  4515.9    0.05       0  4917.8   0.033       0  4923.8    0.05       0
  5143.4    0.16       0  5260.0    0.05       0
Bank Sta=4908,5068.5
Exp/Cntr=0.3,0.1

Chan Stop Cuts=-1