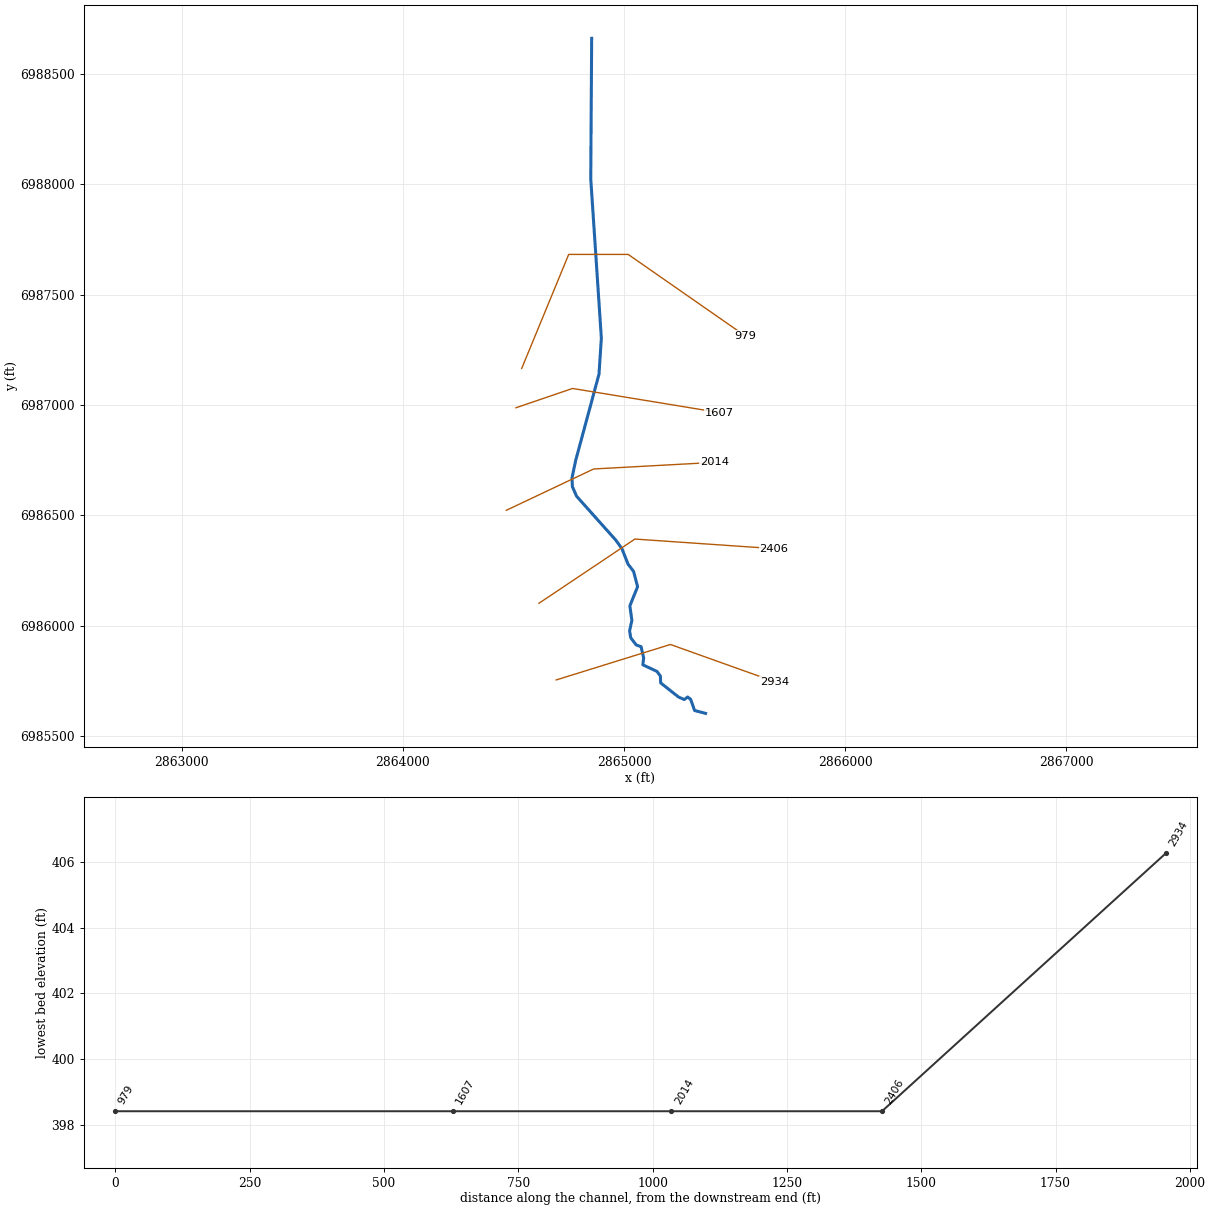
--- UNT 005 in Running Cr Watershed.prj (project) ---

Proj Title=UNT 005 in Running Cr Watershed Base Level Engineering
Current Plan=p01
Default Exp/Contr=0.3,0.1
English Units
Geom File=g01
Flow File=f01
Plan File=p01
BEGIN DESCRIPTION:
UNT 005 in Running Cr Watershed
END DESCRIPTION:

--- UNT 005 in Running Cr Watershed.p01 (plan) ---

Plan Title=Multiple Run
Short Identifier=Multiple
Geom File=g01
Flow File=f01
Subcritical Flow
K Sum by GR= 0
Std Step Tol= 0.01
Critical Tol= 0.01
Num of Std Step Trials= 20
Max Error Tol= 0.3
Flow Tol Ratio= 0.001
Split Flow NTrial= 30
Split Flow Tol= 0.02
Split Flow Ratio= 0.02
Log Output Level= 0
Friction Slope Method= 1
Unsteady Friction Slope Method= 2
Unsteady Bridges Friction Slope Method= 1
Parabolic Critical Depth
Global Vel Dist=  1 , 1 , 1
Global Log Level= 0
CheckData=True
Encroach Param= -1, 0, 0, 0
BEGIN DESCRIPTION:
Multiple Run
END DESCRIPTION:

--- UNT 005 in Running Cr Watershed.f01 (steady flow) ---

Flow Title=Multiple
Number of Profiles=7
Profile Names=10-year,25-year,50-year,1pct_min,100-year,1pct_plu,500-year
River Rch & RM= UNT 005 in Runni,Reach-1,2934
     197     247     285     164     327     653     432
Boundary for River Rch & Prof#=UNT 005 in Runni,Reach-1,1
Up Type=0
Dn Type=3
Dn Slope=0.005
Boundary for River Rch & Prof#=UNT 005 in Runni,Reach-1,2
Up Type=0
Dn Type=3
Dn Slope=0.005
Boundary for River Rch & Prof#=UNT 005 in Runni,Reach-1,3
Up Type=0
Dn Type=3
Dn Slope=0.005
Boundary for River Rch & Prof#=UNT 005 in Runni,Reach-1,4
Up Type=0
Dn Type=3
Dn Slope=0.005
Boundary for River Rch & Prof#=UNT 005 in Runni,Reach-1,5
Up Type=0
Dn Type=3
Dn Slope=0.005
Boundary for River Rch & Prof#=UNT 005 in Runni,Reach-1,6
Up Type=0
Dn Type=3
Dn Slope=0.005
Boundary for River Rch & Prof#=UNT 005 in Runni,Reach-1,7
Up Type=0
Dn Type=3
Dn Slope=0.005

--- UNT 005 in Running Cr Watershed.g01 (geometry) ---

Geom Title=Existing Conditions

River Reach=UNT 005 in Runni,Reach-1
Reach XY= 30
      2865369.04      6985603.54      2865319.56      6985616.56
      2865301.33      6985667.34      2865288.31      6985677.75
      2865272.68      6985666.04      2865246.64      6985677.75
      2865165.91      6985741.56      2865164.61      6985772.81
      2865148.98      6985793.64      2865085.18      6985823.59
      2865089.09      6985854.84      2865077.37      6985905.62
      2865055.23      6985913.43      2865030.49      6985945.98
      2865025.29      6985977.23      2865035.70      6986024.11
      2865026.59      6986090.51      2865061.58      6986177.16
      2865043.42      6986246.48      2865018.03      6986279.81
      2864991.05      6986348.85      2864963.28      6986387.73
      2864785.52      6986586.91      2864766.48      6986630.55
      2864764.89      6986670.23      2864781.56      6986749.58
      2864886.93      6987139.70      2864897.59      6987302.27
      2864849.61      6988024.52      2864853.76      6988660.65

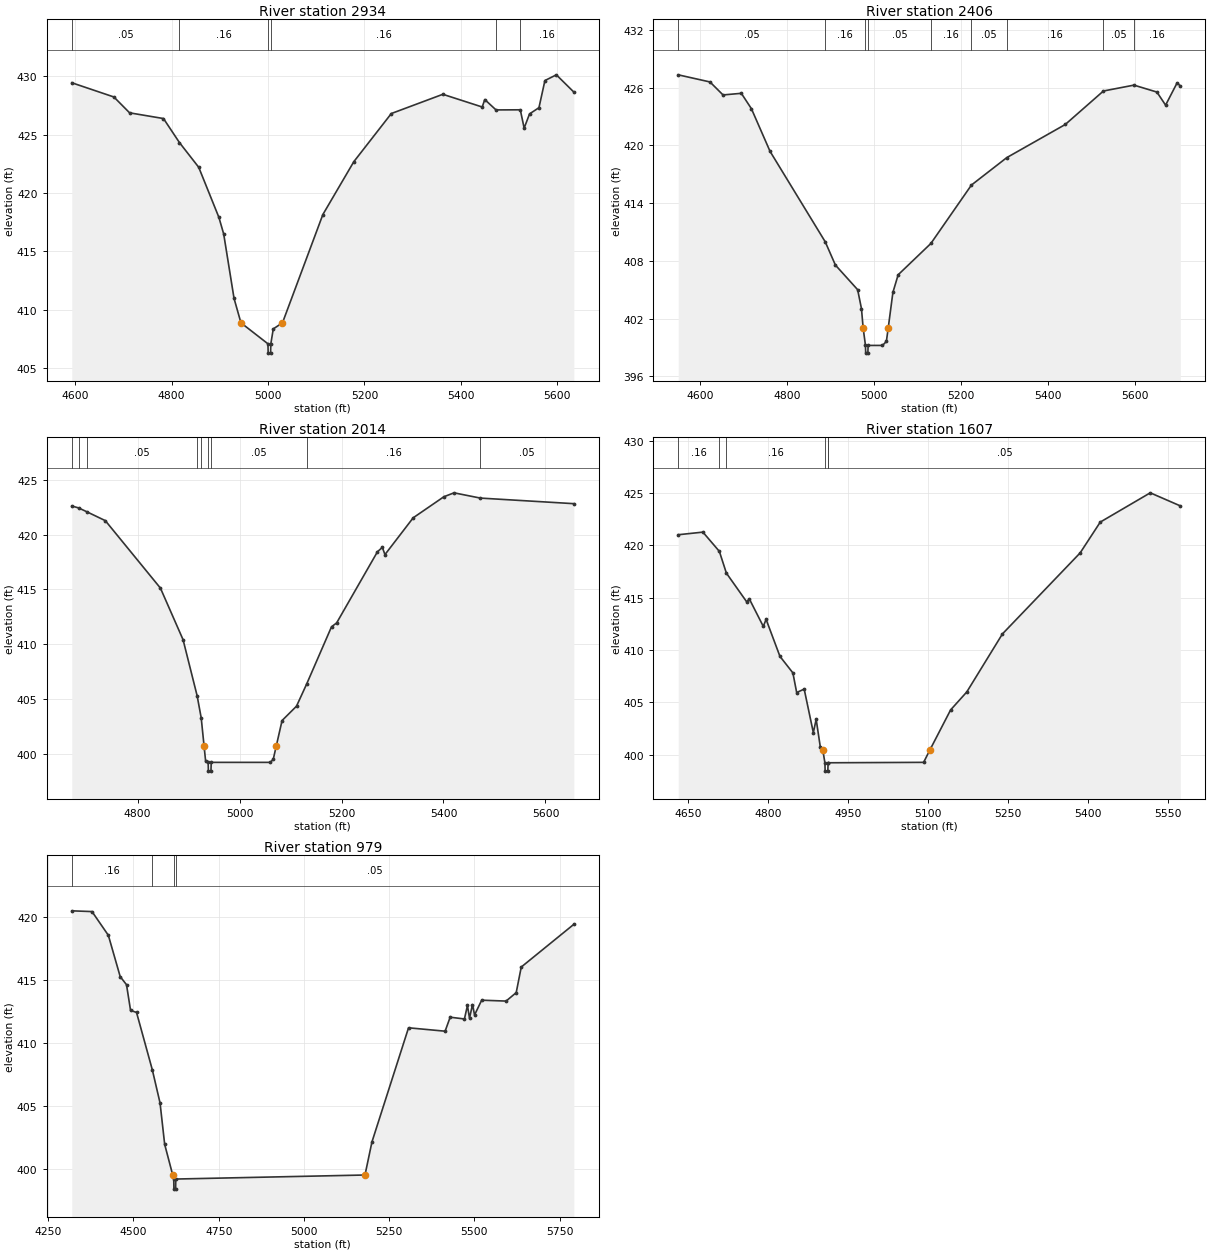
Type RM Length L Ch R = 1,2934,528,528,528
BEGIN DESCRIPTION:
UNT 005 in Running Cr Watershed 5.0
END DESCRIPTION:
XS GIS Cut Line= 3
      2864693.50      6985754.99      2865209.94      6985915.57
      2865681.53      6985746.84
#Sta/Elev= 30
  4592.7  429.45  4680.1  428.23  4712.7  426.87  4783.0  426.38  4816.1  424.32
  4856.1  422.20  4898.0  417.90  4907.9  416.48  4929.4  410.95  4943.7  408.86
  4999.7  407.06  5000.2  406.26  5005.2  406.26  5005.7  407.06  5010.8  408.34
  5029.9  408.86  5113.7  418.15  5177.9  422.68  5255.7  426.81  5362.6  428.46
  5444.3  427.37  5449.6  428.01  5472.9  427.12  5523.3  427.13  5531.3  425.56
  5542.5  426.78  5562.0  427.31  5574.4  429.64  5598.1  430.13  5634.4  428.65
#Mann=6,-1,0
  4592.7    0.05       0  4816.1    0.16       0  4999.7    0.07       0
  5005.7    0.16       0  5472.9    0.08       0  5523.3    0.16       0
Bank Sta=4943.7,5029.9
Exp/Cntr=0.3,0.1

Type RM Length L Ch R = 1,2406,392,392,392
BEGIN DESCRIPTION:
UNT 005 in Running Cr Watershed 4.0
END DESCRIPTION:
XS GIS Cut Line= 3
      2864615.32      6986102.20      2865049.35      6986393.00
      2865678.72      6986349.60
#Sta/Elev= 30
  4550.7  427.32  4623.6  426.58  4653.6  425.23  4695.6  425.40  4718.8  423.80
  4761.6  419.37  4888.4  409.97  4911.7  407.56  4962.8  405.00  4971.6  403.03
  4975.5  401.00  4980.8  399.21  4981.3  398.41  4986.3  398.41  4986.8  399.21
  5019.8  399.21  5028.8  399.62  5033.0  401.00  5043.8  404.72  5055.9  406.55
  5131.0  409.80  5224.2  415.87  5305.4  418.72  5439.7  422.16  5527.4  425.64
  5597.5  426.25  5650.2  425.53  5670.2  424.17  5696.7  426.49  5704.0  426.16
#Mann=9,-1,0
  4550.7    0.05       0  4888.4    0.16       0  4980.8    0.03       0
  4986.8    0.05       0  5131.0    0.16       0  5224.2    0.05       0
  5305.4    0.16       0  5527.4    0.05       0  5597.5    0.16       0
Bank Sta=4975.5,5033
Exp/Cntr=0.3,0.1

Type RM Length L Ch R = 1,2014,407,407,407
BEGIN DESCRIPTION:
UNT 005 in Running Cr Watershed 3.0
END DESCRIPTION:
XS GIS Cut Line= 3
      2864467.72      6986523.20      2864862.81      6986710.37
      2865409.62      6986740.22
#Sta/Elev= 30
  4670.9  422.62  4684.4  422.44  4700.0  422.10  4736.7  421.28  4844.8  415.12
  4889.2  410.41  4916.8  405.29  4924.8  403.27  4930.5  400.66  4933.5  399.30
  4938.4  399.21  4938.9  398.41  4943.9  398.41  4944.4  399.21  5060.6  399.21
  5066.2  399.51  5071.8  400.66  5083.4  403.03  5111.7  404.34  5131.4  406.34
  5180.4  411.59  5190.4  411.94  5270.5  418.44  5280.1  418.84  5285.2  418.18
  5340.6  421.54  5400.7  423.46  5420.7  423.82  5472.3  423.34  5655.7  422.83
#Mann=9,-1,0
  4670.9    0.05       0  4684.4    0.16       0  4700.0    0.05       0
  4916.8    0.16       0  4924.8    0.05       0  4938.4   0.033       0
  4944.4    0.05       0  5131.4    0.16       0  5472.3    0.05       0
Bank Sta=4930.5,5071.8
Exp/Cntr=0.3,0.1

Type RM Length L Ch R = 1,1607,628,628,628
BEGIN DESCRIPTION:
UNT 005 in Running Cr Watershed 2.0
END DESCRIPTION:
XS GIS Cut Line= 3
      2864511.20      6986987.63      2864767.23      6987075.00
      2865430.61      6986966.03
#Sta/Elev= 30
  4631.2  421.03  4677.5  421.28  4708.4  419.44  4721.6  417.36  4759.6  414.62
  4764.8  414.88  4790.9  412.26  4796.2  412.93  4822.2  409.39  4846.5  407.81
  4853.6  405.93  4867.7  406.26  4884.9  402.09  4890.2  403.37  4897.9  400.75
  4902.8  400.40  4906.6  399.21  4907.1  398.41  4912.1  398.41  4912.6  399.21
  4913.3  399.21  5092.0  399.25  5103.4  400.40  5142.7  404.27  5173.1  405.99
  5240.0  411.54  5385.9  419.29  5423.7  422.24  5517.6  425.04  5574.0  423.79
#Mann=6,-1,0
  4631.2    0.16       0  4708.4    0.12       0  4721.6    0.16       0
  4906.6   0.033       0  4912.6    0.16       0  4913.3    0.05       0
Bank Sta=4902.8,5103.4
Exp/Cntr=0.3,0.1

Type RM Length L Ch R = 1,979,0,0,0
BEGIN DESCRIPTION:
UNT 005 in Running Cr Watershed 1.0
END DESCRIPTION:
XS GIS Cut Line= 4
      2864537.18      6987165.53      2864749.87      6987682.06
      2865018.97      6987682.06      2865548.51      6987313.12
#Sta/Elev= 30
  4318.9  420.49  4378.3  420.43  4426.2  418.55  4461.0  415.27  4479.5  414.63
  4491.4  412.59  4508.9  412.43  4555.3  407.87  4577.9  405.25  4591.5  401.96
  4615.1  399.53  4618.1  399.21  4618.6  398.41  4623.6  398.41  4624.1  399.21
  5179.2  399.53  5199.7  402.16  5307.0  411.21  5414.3  410.94  5429.1  412.05
  5471.0  411.91  5479.8  412.98  5485.9  411.97  5494.6  413.05  5500.7  412.23
  5521.6  413.40  5593.2  413.33  5622.9  414.00  5637.7  416.03  5792.0  419.42
#Mann=4,-1,0
  4318.9    0.16       0  4555.3    0.05       0  4618.1   0.033       0
  4624.1    0.05       0
Bank Sta=4615.1,5179.2
Exp/Cntr=0.3,0.1

Chan Stop Cuts=-1