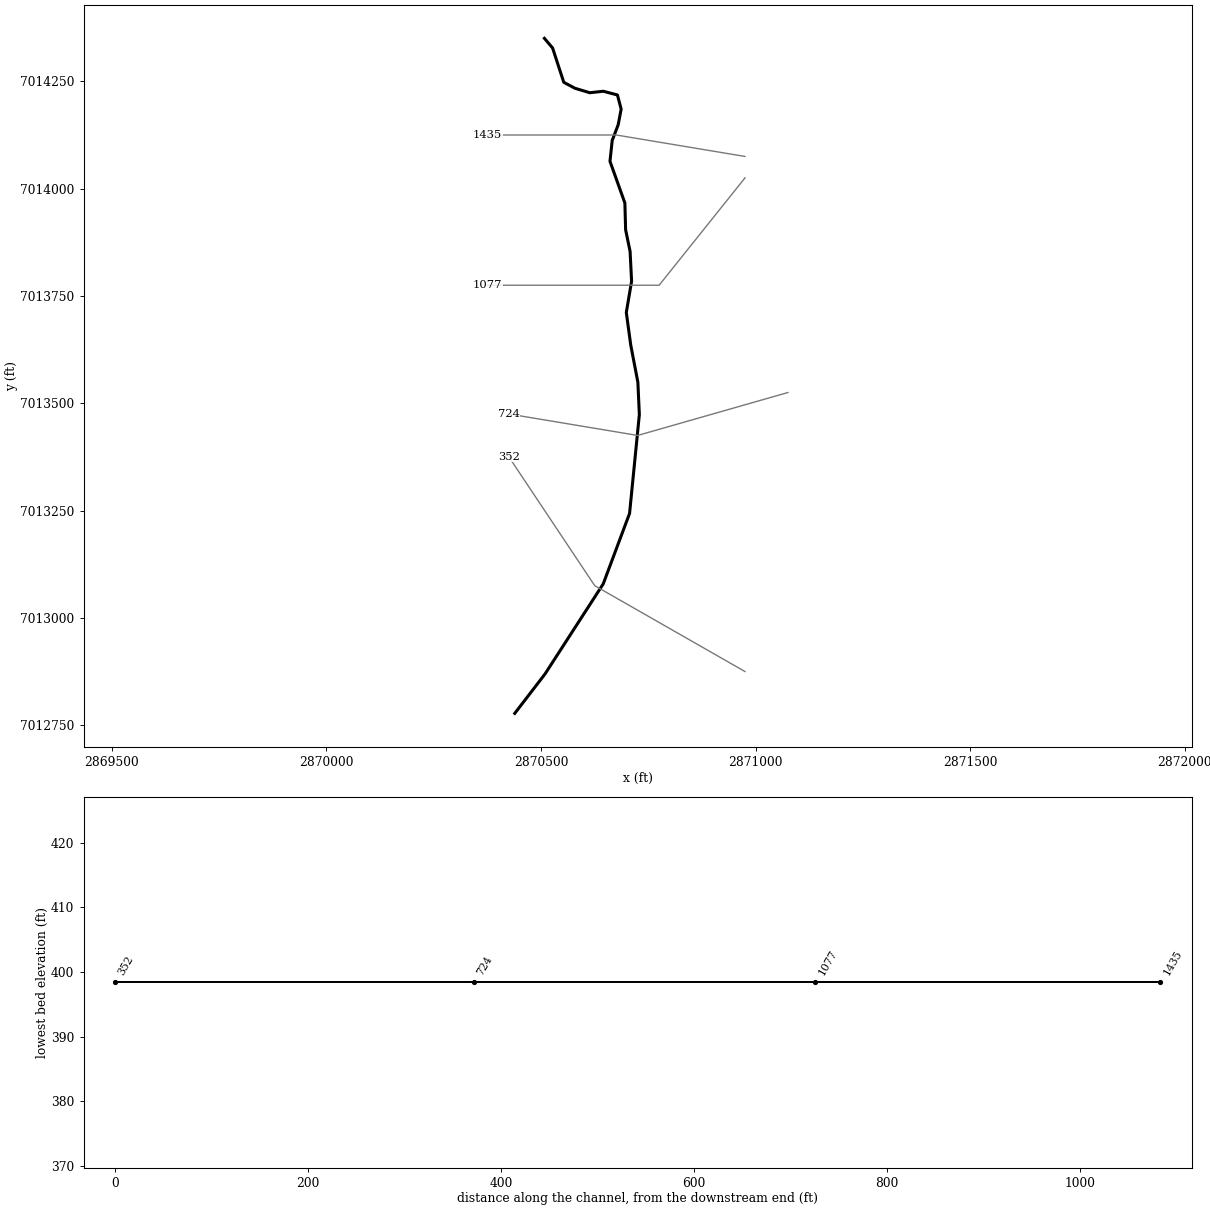
--- UNT 006 in Running Cr Watershed.prj (project) ---

Proj Title=UNT 006 in Running Cr Watershed Base Level Engineering
Current Plan=p01
Default Exp/Contr=0.3,0.1
English Units
Geom File=g01
Flow File=f01
Plan File=p01
BEGIN DESCRIPTION:
UNT 006 in Running Cr Watershed
END DESCRIPTION:

--- UNT 006 in Running Cr Watershed.p01 (plan) ---

Plan Title=Multiple Run
Short Identifier=Multiple
Geom File=g01
Flow File=f01
Subcritical Flow
K Sum by GR= 0
Std Step Tol= 0.01
Critical Tol= 0.01
Num of Std Step Trials= 20
Max Error Tol= 0.3
Flow Tol Ratio= 0.001
Split Flow NTrial= 30
Split Flow Tol= 0.02
Split Flow Ratio= 0.02
Log Output Level= 0
Friction Slope Method= 1
Unsteady Friction Slope Method= 2
Unsteady Bridges Friction Slope Method= 1
Parabolic Critical Depth
Global Vel Dist=  1 , 1 , 1
Global Log Level= 0
CheckData=True
Encroach Param= -1, 0, 0, 0
BEGIN DESCRIPTION:
Multiple Run
END DESCRIPTION:

--- UNT 006 in Running Cr Watershed.f01 (steady flow) ---

Flow Title=Multiple
Number of Profiles=7
Profile Names=10-year,25-year,50-year,1pct_min,100-year,1pct_plu,500-year
River Rch & RM= UNT 006 in Runni,Reach-1,1435
     142     172     195     110     220     439     279
Boundary for River Rch & Prof#=UNT 006 in Runni,Reach-1,1
Up Type=0
Dn Type=3
Dn Slope=0.005
Boundary for River Rch & Prof#=UNT 006 in Runni,Reach-1,2
Up Type=0
Dn Type=3
Dn Slope=0.005
Boundary for River Rch & Prof#=UNT 006 in Runni,Reach-1,3
Up Type=0
Dn Type=3
Dn Slope=0.005
Boundary for River Rch & Prof#=UNT 006 in Runni,Reach-1,4
Up Type=0
Dn Type=3
Dn Slope=0.005
Boundary for River Rch & Prof#=UNT 006 in Runni,Reach-1,5
Up Type=0
Dn Type=3
Dn Slope=0.005
Boundary for River Rch & Prof#=UNT 006 in Runni,Reach-1,6
Up Type=0
Dn Type=3
Dn Slope=0.005
Boundary for River Rch & Prof#=UNT 006 in Runni,Reach-1,7
Up Type=0
Dn Type=3
Dn Slope=0.005

--- UNT 006 in Running Cr Watershed.g01 (geometry) ---

Geom Title=Existing Conditions

River Reach=UNT 006 in Runni,Reach-1
Reach XY= 23
      2870507.73      7014350.18      2870526.83      7014327.61
      2870552.87      7014247.75      2870578.91      7014233.86
      2870613.63      7014223.44      2870644.88      7014226.91
      2870677.87      7014218.23      2870686.55      7014185.25
      2870679.61      7014148.79      2870665.72      7014112.33
      2870660.51      7014063.72      2870695.23      7013966.50
      2870696.97      7013904.00      2870707.38      7013853.65
      2870710.86      7013784.20      2870698.53      7013711.52
      2870708.90      7013635.48      2870725.48      7013549.08
      2870728.94      7013473.73      2870706.13      7013243.28
      2870644.71      7013079.03      2870509.03      7012869.08
      2870438.64      7012777.49

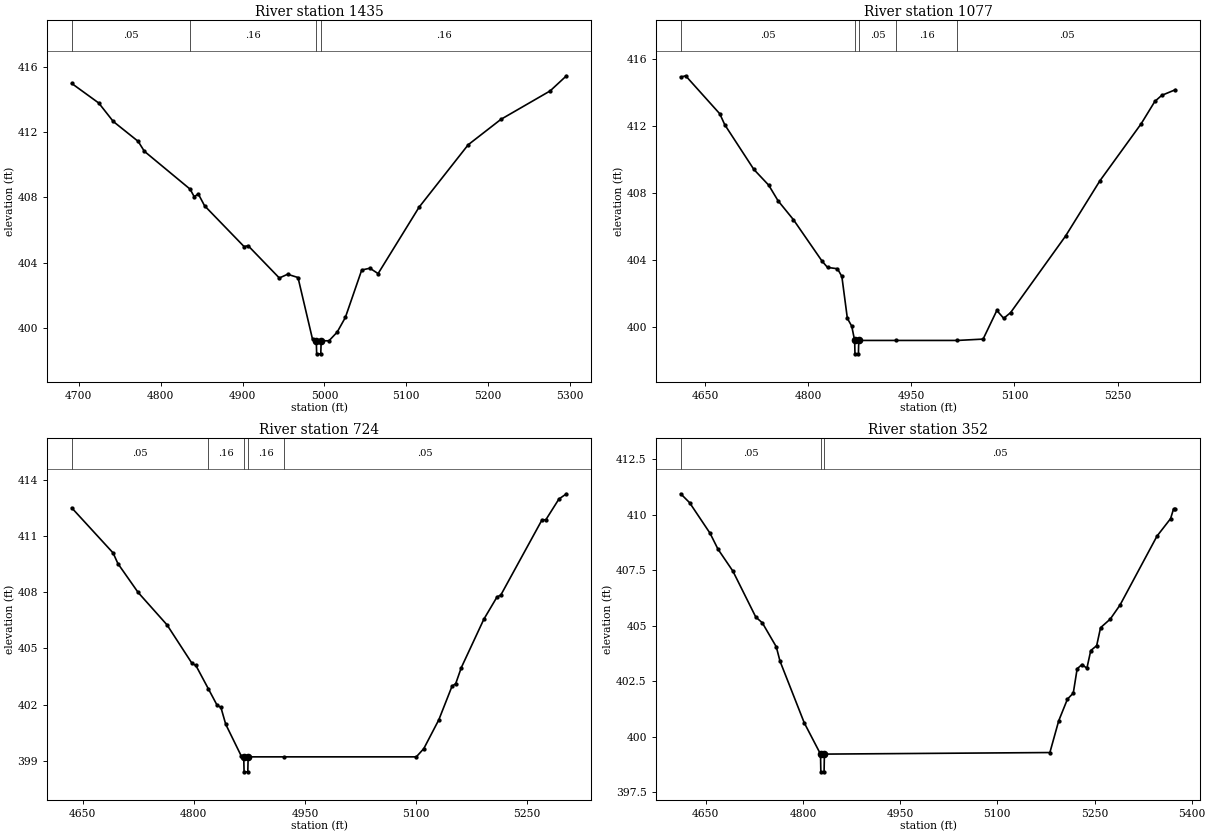
Type RM Length L Ch R = 1,1435,358,358,358
BEGIN DESCRIPTION:
UNT 006 in Running Cr Watershed 4.0
END DESCRIPTION:
XS GIS Cut Line= 3
      2870975.01      7014075.00      2870675.00      7014125.00
      2870375.04      7014125.00
#Sta/Elev= 30
  4691.4  414.99  4724.4  413.79  4742.1  412.66  4772.5  411.44  4780.1  410.83
  4835.9  408.51  4840.9  408.05  4846.0  408.21  4853.6  407.49  4901.8  404.99
  4906.8  405.04  4944.9  403.06  4955.0  403.29  4967.7  403.09  4985.4  399.31
  4990.0  399.21  4990.5  398.41  4995.5  398.41  4996.0  399.21  5005.5  399.21
  5015.5  399.74  5025.5  400.64  5045.5  403.55  5055.5  403.66  5065.5  403.33
  5115.5  407.40  5175.5  411.23  5215.5  412.79  5275.5  414.53  5295.5  415.46
#Mann=4,-1,0
  4691.4    0.05       0  4835.9    0.16       0  4990.0    0.07       0
  4996.0    0.16       0
Bank Sta=4990,4996
Exp/Cntr=0.3,0.1

Type RM Length L Ch R = 1,1077,353,353,353
BEGIN DESCRIPTION:
UNT 006 in Running Cr Watershed 3.0
END DESCRIPTION:
XS GIS Cut Line= 3
      2870975.02      7014025.03      2870775.00      7013775.00
      2870374.99      7013775.00
#Sta/Elev= 30
  4614.1  414.93  4621.3  415.01  4671.0  412.74  4678.2  412.09  4720.6  409.42
  4742.2  408.48  4755.8  407.55  4778.2  406.42  4819.8  403.95  4827.8  403.57
  4842.3  403.49  4848.7  403.03  4856.7  400.53  4863.1  400.06  4867.3  399.21
  4867.8  398.41  4872.8  398.41  4873.3  399.21  4927.8  399.21  5016.9  399.21
  5054.3  399.29  5074.3  401.00  5084.3  400.53  5094.3  400.87  5174.3  405.44
  5224.3  408.74  5284.3  412.14  5304.3  413.48  5314.3  413.84  5334.3  414.18
#Mann=5,-1,0
  4614.1    0.05       0  4867.3    0.07       0  4873.3    0.05       0
  4927.8    0.16       0  5016.9    0.05       0
Bank Sta=4867.3,4873.3
Exp/Cntr=0.3,0.1

Type RM Length L Ch R = 1,724,372,372,372
BEGIN DESCRIPTION:
UNT 006 in Running Cr Watershed 2.0
END DESCRIPTION:
XS GIS Cut Line= 3
      2871075.01      7013525.00      2870725.00      7013425.00
      2870424.96      7013475.01
#Sta/Elev= 30
  4635.1  412.51  4691.0  410.10  4697.5  409.53  4724.8  407.99  4763.8  406.26
  4797.6  404.20  4802.8  404.09  4819.7  402.84  4831.4  401.97  4836.6  401.85
  4843.1  400.95  4863.9  399.27  4867.4  399.21  4867.9  398.41  4872.9  398.41
  4873.4  399.21  4922.0  399.21  5100.5  399.21  5110.6  399.65  5130.9  401.19
  5148.7  402.98  5153.7  403.12  5161.3  403.98  5191.7  406.56  5209.5  407.75
  5214.6  407.85  5270.3  411.87  5275.4  411.87  5293.1  412.98  5303.3  413.26
#Mann=5,-1,0
  4635.1    0.05       0  4819.7    0.16       0  4867.4   0.033       0
  4873.4    0.16       0  4922.0    0.05       0
Bank Sta=4867.4,4873.4
Exp/Cntr=0.3,0.1

Type RM Length L Ch R = 1,352,0,0,0
BEGIN DESCRIPTION:
UNT 006 in Running Cr Watershed 1.0
END DESCRIPTION:
XS GIS Cut Line= 3
      2870974.98      7012875.01      2870625.00      7013075.00
      2870425.03      7013374.96
#Sta/Elev= 30
  4611.3  410.95  4625.0  410.55  4656.6  409.17  4668.9  408.45  4691.9  407.46
  4727.2  405.39  4737.3  405.13  4758.8  404.05  4764.6  403.40  4802.0  400.62
  4827.1  399.21  4827.6  398.41  4832.6  398.41  4833.1  399.21  5181.1  399.28
  5194.7  400.71  5208.2  401.69  5217.2  401.96  5223.2  403.06  5230.7  403.25
  5238.2  403.08  5244.2  403.88  5253.3  404.10  5259.3  404.91  5274.3  405.30
  5289.3  405.93  5346.4  409.04  5367.4  409.83  5371.9  410.26  5374.9  410.26
#Mann=3,-1,0
  4611.3    0.05       0  4827.1   0.033       0  4833.1    0.05       0
Bank Sta=4827.1,4833.1
Exp/Cntr=0.3,0.1

Chan Stop Cuts=-1