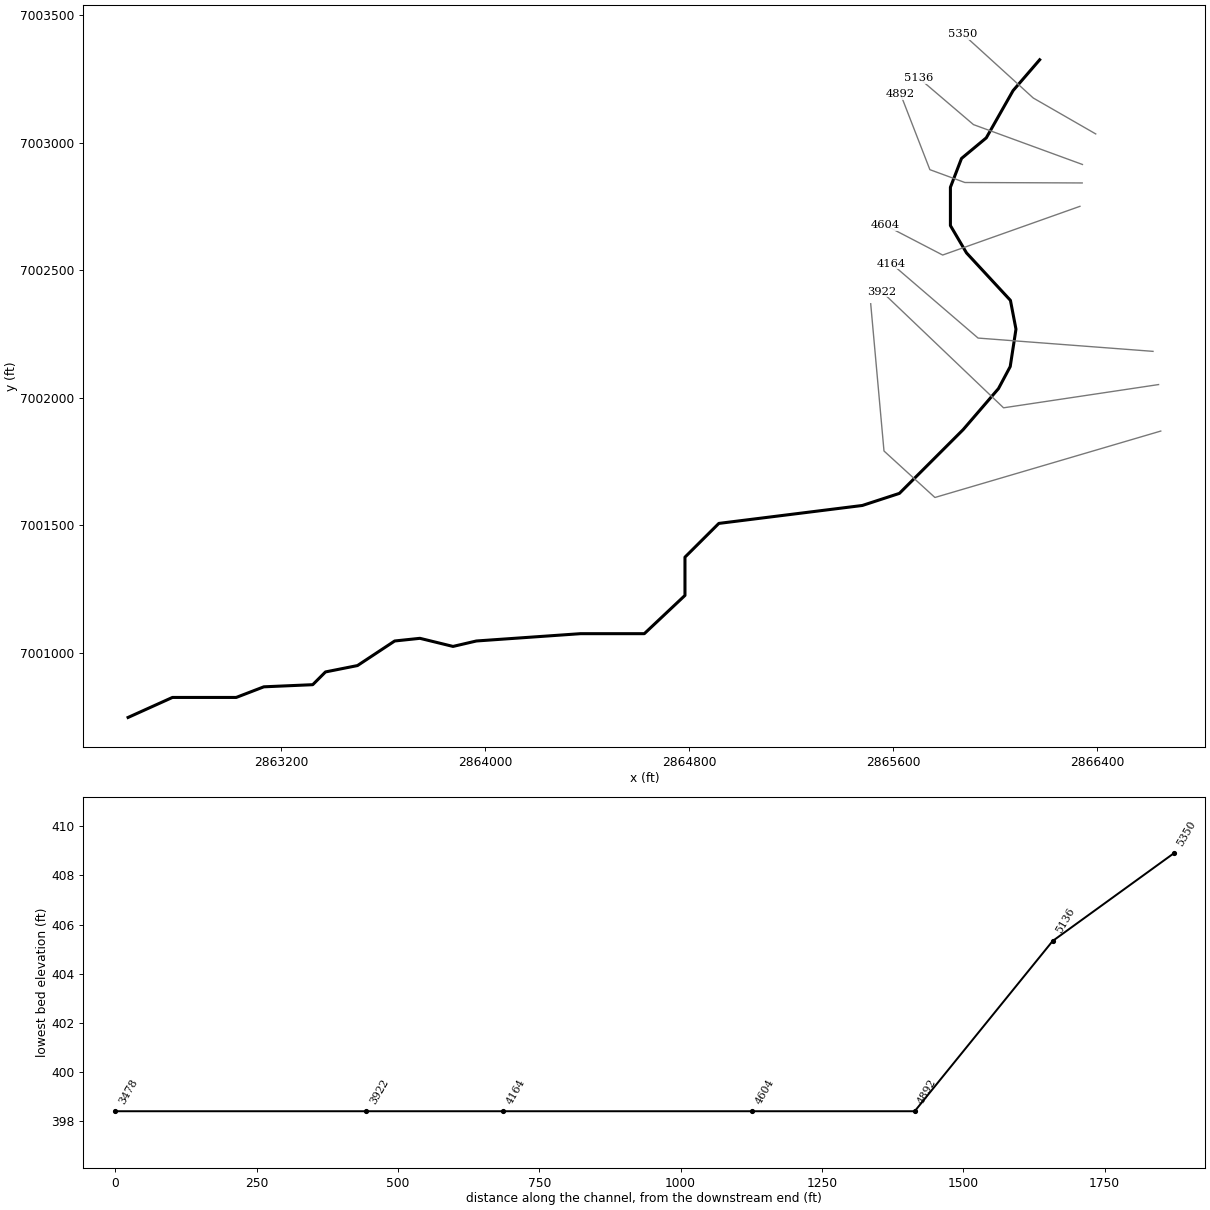
--- UNT 007 in Running Cr Watershed.prj (project) ---

Proj Title=UNT 007 in Running Cr Watershed Base Level Engineering
Current Plan=p01
Default Exp/Contr=0.3,0.1
English Units
Geom File=g01
Flow File=f01
Plan File=p01
BEGIN DESCRIPTION:
UNT 007 in Running Cr Watershed
END DESCRIPTION:

--- UNT 007 in Running Cr Watershed.p01 (plan) ---

Plan Title=Multiple Run
Short Identifier=Multiple
Geom File=g01
Flow File=f01
Subcritical Flow
K Sum by GR= 0
Std Step Tol= 0.01
Critical Tol= 0.01
Num of Std Step Trials= 20
Max Error Tol= 0.3
Flow Tol Ratio= 0.001
Split Flow NTrial= 30
Split Flow Tol= 0.02
Split Flow Ratio= 0.02
Log Output Level= 0
Friction Slope Method= 1
Unsteady Friction Slope Method= 2
Unsteady Bridges Friction Slope Method= 1
Parabolic Critical Depth
Global Vel Dist=  1 , 1 , 1
Global Log Level= 0
CheckData=True
Encroach Param= -1, 0, 0, 0
BEGIN DESCRIPTION:
Multiple Run
END DESCRIPTION:

--- UNT 007 in Running Cr Watershed.f01 (steady flow) ---

Flow Title=Multiple
Number of Profiles=7
Profile Names=10-year,25-year,50-year,1pct_min,100-year,1pct_plu,500-year
River Rch & RM= UNT 007 in Runni,Reach-1,5350
     160     196     222     126     251     501     321
Boundary for River Rch & Prof#=UNT 007 in Runni,Reach-1,1
Up Type=0
Dn Type=3
Dn Slope=0.005
Boundary for River Rch & Prof#=UNT 007 in Runni,Reach-1,2
Up Type=0
Dn Type=3
Dn Slope=0.005
Boundary for River Rch & Prof#=UNT 007 in Runni,Reach-1,3
Up Type=0
Dn Type=3
Dn Slope=0.005
Boundary for River Rch & Prof#=UNT 007 in Runni,Reach-1,4
Up Type=0
Dn Type=3
Dn Slope=0.005
Boundary for River Rch & Prof#=UNT 007 in Runni,Reach-1,5
Up Type=0
Dn Type=3
Dn Slope=0.005
Boundary for River Rch & Prof#=UNT 007 in Runni,Reach-1,6
Up Type=0
Dn Type=3
Dn Slope=0.005
Boundary for River Rch & Prof#=UNT 007 in Runni,Reach-1,7
Up Type=0
Dn Type=3
Dn Slope=0.005

--- UNT 007 in Running Cr Watershed.g01 (geometry) ---

Geom Title=Existing Conditions

River Reach=UNT 007 in Runni,Reach-1
Reach XY= 30
      2866175.00      7003325.00      2866070.69      7003204.08
      2865965.65      7003018.84      2865868.50      7002938.09
      2865825.00      7002825.00      2865825.00      7002675.00
      2865888.12      7002567.78      2866060.34      7002381.67
      2866082.04      7002268.82      2866059.47      7002122.12
      2866013.51      7002035.92      2865875.00      7001875.00
      2865625.00      7001625.00      2865479.65      7001577.59
      2864917.15      7001507.28      2864784.34      7001374.99
      2864784.34      7001224.99      2864625.00      7001075.00
      2864375.00      7001075.00      2863966.63      7001046.34
      2863875.00      7001025.00      2863745.28      7001056.76
      2863646.32      7001046.34      2863500.49      7000949.99
      2863375.00      7000925.00      2863325.00      7000875.00
      2863133.30      7000866.65      2863025.00      7000825.00
      2862775.00      7000825.00      2862601.03      7000746.52

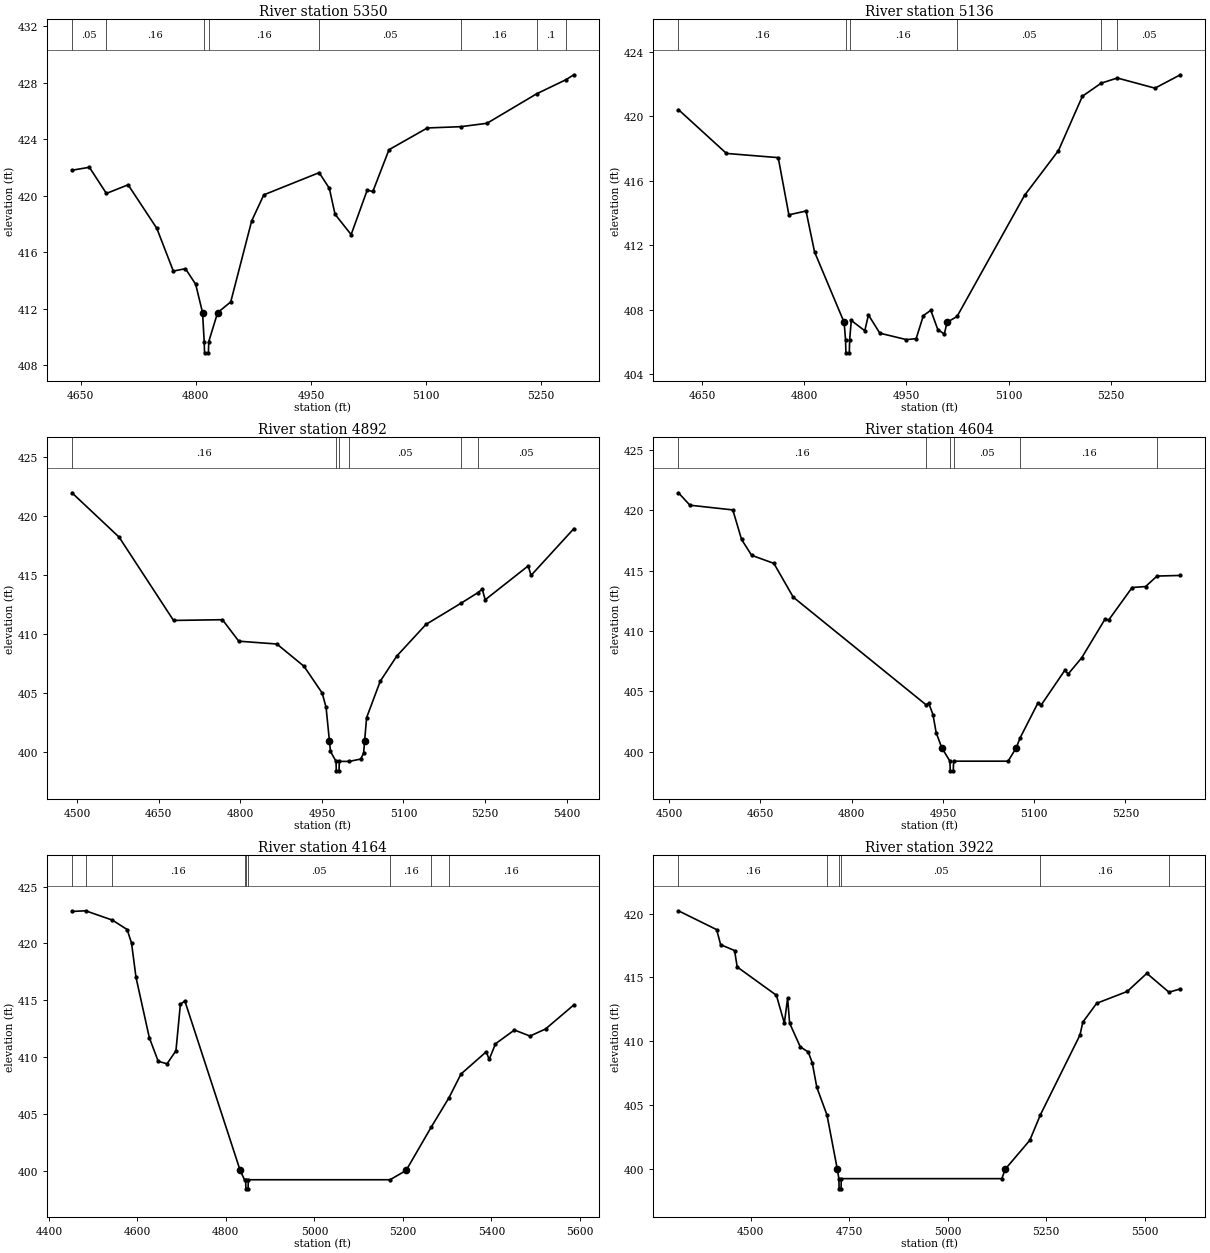
Type RM Length L Ch R = 1,5350,214,214,214
BEGIN DESCRIPTION:
UNT 007 in Running Cr Watershed 5.0
END DESCRIPTION:
XS GIS Cut Line= 3
      2866394.71      7003034.24      2866149.89      7003175.00
      2865874.98      7003425.02
#Sta/Elev= 30
  4638.6  421.80  4661.3  422.01  4683.5  420.16  4711.8  420.77  4749.2  417.69
  4770.7  414.67  4786.5  414.84  4799.8  413.74  4808.8  411.73  4810.9  409.69
  4811.4  408.89  4816.4  408.89  4816.9  409.69  4828.4  411.73  4845.5  412.49
  4872.8  418.22  4888.6  420.06  4960.7  421.63  4974.0  420.52  4981.4  418.69
  5002.4  417.25  5023.3  420.39  5030.7  420.30  5051.7  423.25  5101.7  424.79
  5145.2  424.88  5179.4  425.12  5244.3  427.21  5281.9  428.19  5292.6  428.55
#Mann=8,-1,0
  4638.6    0.05       0  4683.5    0.16       0  4810.9    0.03       0
  4816.9    0.16       0  4960.7    0.05       0  5145.2    0.16       0
  5244.3     0.1       0  5281.9    0.05       0
Bank Sta=4808.8,4828.4
Exp/Cntr=0.3,0.1

Type RM Length L Ch R = 1,5136,244,244,244
BEGIN DESCRIPTION:
UNT 007 in Running Cr Watershed 4.0
END DESCRIPTION:
XS GIS Cut Line= 3
      2866342.63      7002914.46      2865915.52      7003070.72
      2865701.08      7003253.55
#Sta/Elev= 30
  4615.5  420.42  4686.0  417.70  4762.0  417.44  4777.6  413.89  4802.8  414.13
  4815.3  411.59  4858.7  407.22  4860.8  406.13  4861.3  405.33  4866.3  405.33
  4866.8  406.13  4869.2  407.34  4889.0  406.70  4894.4  407.68  4911.1  406.55
  4950.1  406.15  4964.4  406.21  4975.0  407.64  4985.9  407.97  4996.3  406.76
  5005.8  406.50  5009.7  407.22  5024.5  407.59  5123.5  415.10  5173.3  417.88
  5208.4  421.25  5236.0  422.06  5259.6  422.38  5314.9  421.75  5352.1  422.58
#Mann=6,-1,0
  4615.5    0.16       0  4860.8    0.07       0  4866.8    0.16       0
  5024.5    0.05       0  5236.0    0.16       0  5259.6    0.05       0
Bank Sta=4858.7,5009.7
Exp/Cntr=0.3,0.1

Type RM Length L Ch R = 1,4892,288,288,288
BEGIN DESCRIPTION:
Mapping XS 3733bea6
END DESCRIPTION:
XS GIS Cut Line= 4
      2866341.73      7002842.07      2865881.67      7002843.81
      2865744.51      7002894.15      2865629.95      7003189.23
#Sta/Elev= 30
  4490.5  421.98  4577.2  418.22  4677.2  411.16  4767.2  411.22  4797.2  409.40
  4867.2  409.16  4917.2  407.27  4950.6  405.00  4957.7  403.78  4963.9  400.92
  4965.8  400.06  4976.0  399.21  4976.5  398.41  4981.5  398.41  4982.0  399.21
  5000.2  399.21  5021.4  399.41  5026.7  399.91  5028.5  400.92  5032.2  402.92
  5057.2  406.00  5087.7  408.14  5141.3  410.82  5206.2  412.63  5236.3  413.50
  5244.8  413.81  5250.2  412.91  5329.2  415.78  5334.6  414.98  5413.2  418.94
#Mann=6,-1,0
  4490.5    0.16       0  4976.0    0.07       0  4982.0    0.16       0
  5000.2    0.05       0  5206.2    0.16       0  5236.3    0.05       0
Bank Sta=4963.9,5028.5
Exp/Cntr=0.3,0.1

Type RM Length L Ch R = 1,4604,440,440,440
BEGIN DESCRIPTION:
UNT 007 in Running Cr Watershed 3.0
END DESCRIPTION:
XS GIS Cut Line= 3
      2866332.83      7002750.40      2865794.64      7002559.43
      2865569.45      7002676.36
#Sta/Elev= 30
  4515.3  421.45  4534.2  420.42  4604.7  420.03  4619.1  417.58  4635.6  416.27
  4672.2  415.60  4704.0  412.80  4921.8  403.90  4926.8  403.99  4933.6  403.07
  4938.9  401.57  4948.0  400.33  4961.5  399.21  4962.0  398.41  4967.0  398.41
  4967.5  399.21  5057.1  399.21  5070.6  400.33  5076.7  401.13  5106.1  404.03
  5111.7  403.88  5150.3  406.74  5155.9  406.44  5178.1  407.78  5216.7  411.01
  5222.3  410.90  5260.9  413.60  5283.0  413.68  5301.8  414.55  5340.1  414.60
#Mann=6,-1,0
  4515.3    0.16       0  4921.8    0.05       0  4961.5   0.033       0
  4967.5    0.05       0  5076.7    0.16       0  5301.8    0.08       0
Bank Sta=4948,5070.6
Exp/Cntr=0.3,0.1

Type RM Length L Ch R = 1,4164,242,242,242
BEGIN DESCRIPTION:
UNT 007 in Running Cr Watershed 2.0
END DESCRIPTION:
XS GIS Cut Line= 3
      2866619.33      7002181.82      2865933.53      7002233.91
      2865594.96      7002524.73
#Sta/Elev= 30
  4452.2  422.81  4483.0  422.87  4543.5  422.05  4576.9  421.22  4586.9  420.02
  4596.9  417.02  4627.0  411.71  4647.1  409.63  4667.1  409.41  4687.2  410.56
  4697.2  414.64  4707.3  414.94  4832.3  400.03  4842.1  399.21  4844.7  399.21
  4845.2  398.41  4850.2  398.41  4850.7  399.21  5171.0  399.21  5207.3  400.03
  5263.7  403.82  5304.2  406.43  5331.3  408.51  5388.4  410.47  5395.0  409.79
  5409.2  411.17  5452.0  412.38  5487.2  411.85  5522.3  412.47  5586.3  414.59
#Mann=9,-1,0
  4452.2    0.16       0  4483.0     0.1       0  4543.5    0.16       0
  4842.1    0.05       0  4844.7   0.033       0  4850.7    0.05       0
  5171.0    0.16       0  5263.7    0.05       0  5304.2    0.16       0
Bank Sta=4832.3,5207.3
Exp/Cntr=0.3,0.1

Type RM Length L Ch R = 1,3922,444,444,444
BEGIN DESCRIPTION:
Mapping XS 326dbcaf
END DESCRIPTION:
XS GIS Cut Line= 3
      2866641.04      7002051.62      2866033.36      7001960.47
      2865555.93      7002416.20
#Sta/Elev= 30
  4316.2  420.23  4413.3  418.75  4423.4  417.57  4458.8  417.11  4465.5  415.82
  4565.0  413.60  4585.2  411.41  4593.5  413.36  4598.6  411.41  4625.7  409.55
  4645.9  409.15  4656.0  408.31  4667.7  406.37  4693.5  404.20  4719.8  399.93
  4723.7  399.21  4724.2  398.41  4729.2  398.41  4729.7  399.21  5137.7  399.21
  5145.5  399.93  5208.5  402.22  5235.4  404.22  5335.9  410.48  5343.1  411.49
  5378.3  412.97  5456.0  413.90  5505.7  415.32  5561.9  413.84  5590.7  414.10
#Mann=6,-1,0
  4316.2    0.16       0  4693.5    0.05       0  4723.7   0.033       0
  4729.7    0.05       0  5235.4    0.16       0  5561.9    0.05       0
Bank Sta=4719.8,5145.5
Exp/Cntr=0.3,0.1

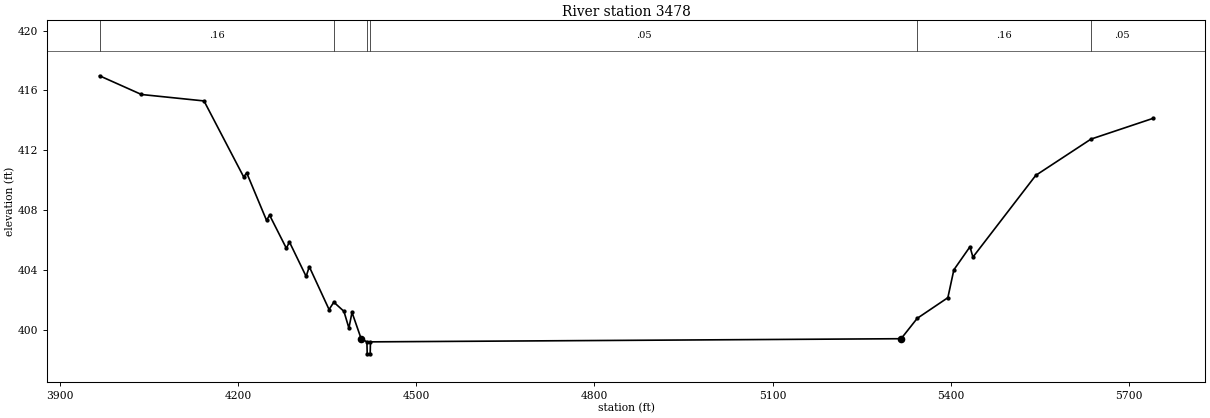
Type RM Length L Ch R = 1,3478,0,0,0
BEGIN DESCRIPTION:
Mapping XS f638667b
END DESCRIPTION:
XS GIS Cut Line= 4
      2866649.69      7001869.33      2865764.26      7001608.91
      2865564.61      7001791.20      2865512.52      7002368.47
#Sta/Elev= 30
  3967.1  416.98  4037.7  415.73  4143.0  415.30  4209.7  410.23  4214.9  410.49
  4248.2  407.33  4253.4  407.67  4281.6  405.46  4286.8  405.88  4314.9  403.58
  4320.2  404.23  4353.5  401.37  4361.5  401.86  4378.5  401.25  4386.9  400.13
  4392.1  401.18  4407.5  399.42  4417.2  399.21  4417.7  398.41  4422.7  398.41
  4423.2  399.21  5316.4  399.42  5343.5  400.78  5395.1  402.16  5405.2  404.02
  5432.3  405.56  5437.3  404.87  5543.1  410.33  5636.0  412.75  5740.0  414.13
#Mann=6,-1,0
  3967.1    0.16       0  4361.5    0.05       0  4417.2   0.033       0
  4423.2    0.05       0  5343.5    0.16       0  5636.0    0.05       0
Bank Sta=4407.5,5316.4
Exp/Cntr=0.3,0.1

Chan Stop Cuts=-1