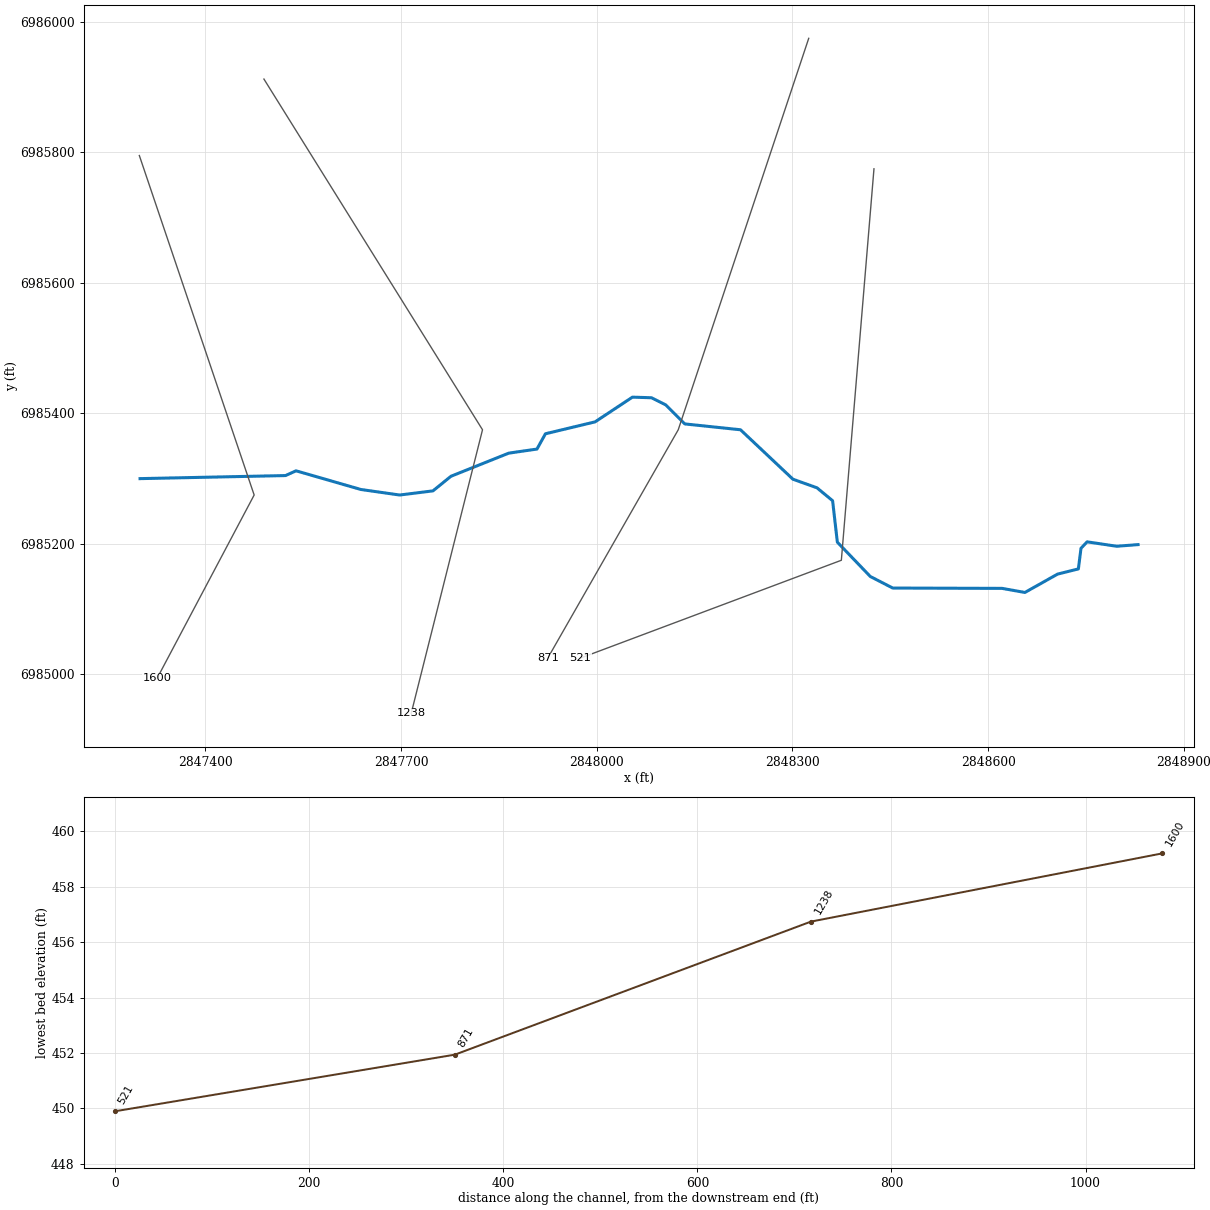
--- UNT 008 in Running Cr Watershed.prj (project) ---

Proj Title=UNT 008 in Running Cr Watershed Base Level Engineering
Current Plan=p01
Default Exp/Contr=0.3,0.1
English Units
Geom File=g01
Flow File=f01
Plan File=p01
BEGIN DESCRIPTION:
UNT 008 in Running Cr Watershed
END DESCRIPTION:

--- UNT 008 in Running Cr Watershed.p01 (plan) ---

Plan Title=Multiple Run
Short Identifier=Multiple
Geom File=g01
Flow File=f01
Subcritical Flow
K Sum by GR= 0
Std Step Tol= 0.01
Critical Tol= 0.01
Num of Std Step Trials= 20
Max Error Tol= 0.3
Flow Tol Ratio= 0.001
Split Flow NTrial= 30
Split Flow Tol= 0.02
Split Flow Ratio= 0.02
Log Output Level= 0
Friction Slope Method= 1
Unsteady Friction Slope Method= 2
Unsteady Bridges Friction Slope Method= 1
Parabolic Critical Depth
Global Vel Dist=  1 , 1 , 1
Global Log Level= 0
CheckData=True
Encroach Param= -1, 0, 0, 0
BEGIN DESCRIPTION:
Multiple Run
END DESCRIPTION:

--- UNT 008 in Running Cr Watershed.f01 (steady flow) ---

Flow Title=Multiple
Number of Profiles=7
Profile Names=10-year,25-year,50-year,1pct_min,100-year,1pct_plu,500-year
River Rch & RM= UNT 008 in Runni,Reach-1,1600
      89     105     116      65     129     258     159
Boundary for River Rch & Prof#=UNT 008 in Runni,Reach-1,1
Up Type=0
Dn Type=3
Dn Slope=0.005
Boundary for River Rch & Prof#=UNT 008 in Runni,Reach-1,2
Up Type=0
Dn Type=3
Dn Slope=0.005
Boundary for River Rch & Prof#=UNT 008 in Runni,Reach-1,3
Up Type=0
Dn Type=3
Dn Slope=0.005
Boundary for River Rch & Prof#=UNT 008 in Runni,Reach-1,4
Up Type=0
Dn Type=3
Dn Slope=0.005
Boundary for River Rch & Prof#=UNT 008 in Runni,Reach-1,5
Up Type=0
Dn Type=3
Dn Slope=0.005
Boundary for River Rch & Prof#=UNT 008 in Runni,Reach-1,6
Up Type=0
Dn Type=3
Dn Slope=0.005
Boundary for River Rch & Prof#=UNT 008 in Runni,Reach-1,7
Up Type=0
Dn Type=3
Dn Slope=0.005

--- UNT 008 in Running Cr Watershed.g01 (geometry) ---

Geom Title=Existing Conditions

River Reach=UNT 008 in Runni,Reach-1
Reach XY= 30
      2847300.12      6985300.12      2847523.04      6985304.81
      2847539.18      6985312.10      2847638.66      6985283.45
      2847698.04      6985275.00      2847749.08      6985281.37
      2847776.68      6985303.76      2847865.22      6985339.18
      2847908.45      6985345.43      2847921.47      6985368.87
      2847997.52      6985387.10      2848054.81      6985425.00
      2848083.97      6985424.08      2848105.85      6985413.14
      2848135.02      6985383.97      2848220.43      6985375.00
      2848300.78      6985299.22      2848337.62      6985286.06
      2848361.58      6985266.26      2848368.87      6985202.72
      2848419.39      6985150.12      2848453.77      6985132.41
      2848621.47      6985131.89      2848656.37      6985125.64
      2848706.37      6985153.76      2848738.28      6985161.72
      2848742.31      6985193.35      2848751.68      6985203.24
      2848797.00      6985196.47      2848829.77      6985198.98

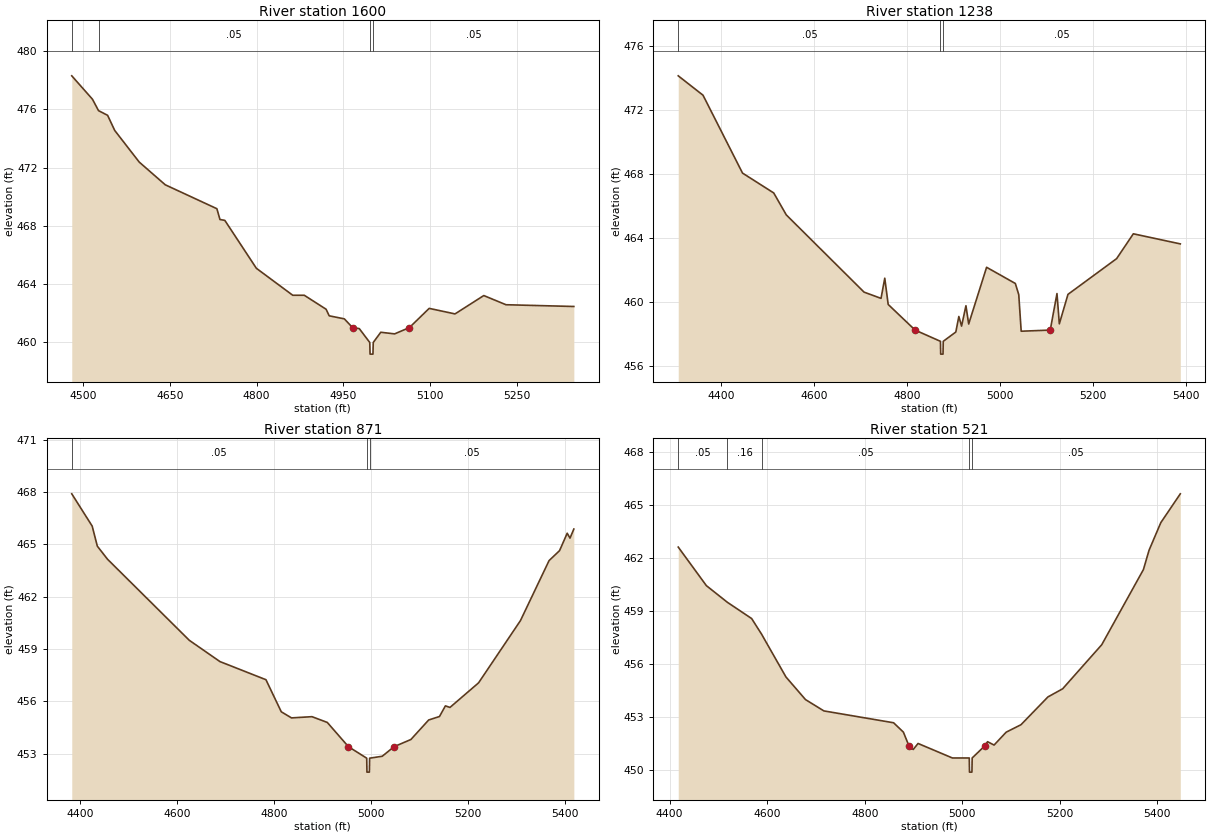
Type RM Length L Ch R = 1,1600,362,362,362
BEGIN DESCRIPTION:
UNT 008 in Running Cr Watershed 4.0
END DESCRIPTION:
XS GIS Cut Line= 3
      2847299.02      6985795.33      2847475.00      6985275.00
      2847326.34      6984994.21
#Sta/Elev= 30
  4480.9  478.30  4516.7  476.69  4527.1  475.91  4542.8  475.59  4555.1  474.55
  4597.4  472.38  4642.4  470.82  4731.5  469.18  4736.8  468.44  4745.2  468.38
  4799.7  465.09  4862.5  463.24  4882.4  463.24  4920.1  462.28  4925.4  461.83
  4951.6  461.62  4965.8  461.02  4977.4  460.95  4995.5  460.00  4996.0  459.20
  5001.0  459.20  5001.5  460.00  5014.5  460.70  5038.4  460.59  5063.9  461.02
  5098.1  462.34  5142.7  461.96  5192.4  463.22  5230.7  462.59  5347.9  462.47
#Mann=4,-1,0
  4480.9    0.16       0  4527.1    0.05       0  4995.5    0.03       0
  5001.5    0.05       0
Bank Sta=4965.8,5063.9
Exp/Cntr=0.3,0.1

Type RM Length L Ch R = 1,1238,367,367,367
BEGIN DESCRIPTION:
UNT 008 in Running Cr Watershed 3.0
END DESCRIPTION:
XS GIS Cut Line= 3
      2847489.98      6985912.54      2847825.00      6985375.00
      2847715.70      6984940.32
#Sta/Elev= 30
  4307.1  474.11  4360.5  472.90  4445.6  468.04  4512.8  466.80  4539.9  465.43
  4707.4  460.61  4744.0  460.22  4752.0  461.48  4759.4  459.84  4817.4  458.24
  4872.0  457.54  4872.5  456.74  4877.5  456.74  4878.0  457.54  4905.1  458.12
  4911.6  459.09  4917.5  458.49  4926.9  459.76  4932.8  458.62  4971.4  462.16
  5033.3  461.15  5040.7  460.45  5045.9  458.17  5108.5  458.24  5123.0  460.52
  5128.1  458.63  5146.7  460.47  5251.5  462.70  5287.5  464.25  5388.7  463.62
#Mann=3,-1,0
  4307.1    0.05       0  4872.0    0.03       0  4878.0    0.05       0
Bank Sta=4817.4,5108.5
Exp/Cntr=0.3,0.1

Type RM Length L Ch R = 1,871,350,350,350
BEGIN DESCRIPTION:
UNT 008 in Running Cr Watershed 2.0
END DESCRIPTION:
XS GIS Cut Line= 3
      2848324.99      6985974.96      2848125.00      6985375.00
      2847925.01      6985025.02
#Sta/Elev= 30
  4382.6  467.90  4424.7  466.05  4435.3  464.90  4456.3  464.15  4625.0  459.50
  4688.2  458.28  4783.1  457.24  4814.7  455.40  4835.8  455.05  4878.0  455.12
  4909.6  454.79  4953.2  453.40  4990.9  452.74  4991.4  451.94  4996.4  451.94
  4996.9  452.74  5022.9  452.85  5047.4  453.40  5082.0  453.81  5118.7  454.93
  5141.0  455.13  5153.2  455.74  5162.6  455.65  5221.6  457.06  5308.0  460.63
  5367.0  464.07  5388.6  464.64  5404.4  465.64  5410.2  465.36  5418.1  465.88
#Mann=3,-1,0
  4382.6    0.05       0  4990.9    0.03       0  4996.9    0.05       0
Bank Sta=4953.2,5047.4
Exp/Cntr=0.3,0.1

Type RM Length L Ch R = 1,521,0,0,0
BEGIN DESCRIPTION:
UNT 008 in Running Cr Watershed 1.0
END DESCRIPTION:
XS GIS Cut Line= 3
      2848425.00      6985775.02      2848375.00      6985175.00
      2847975.00      6985025.00
#Sta/Elev= 30
  4417.6  462.62  4475.3  460.44  4518.3  459.50  4568.1  458.58  4588.4  457.70
  4638.4  455.28  4678.5  454.00  4716.2  453.36  4859.1  452.69  4879.2  452.16
  4890.8  451.37  4899.3  451.18  4909.3  451.52  4979.6  450.70  5014.2  450.70
  5014.7  449.90  5019.7  449.90  5020.2  450.70  5045.5  451.37  5051.7  451.62
  5065.1  451.43  5090.0  452.16  5120.3  452.58  5175.5  454.15  5205.7  454.61
  5285.8  457.10  5371.3  461.35  5382.8  462.44  5406.9  464.00  5446.9  465.63
#Mann=5,-1,0
  4417.6    0.05       0  4518.3    0.16       0  4588.4    0.05       0
  5014.2    0.03       0  5020.2    0.05       0
Bank Sta=4890.8,5045.5
Exp/Cntr=0.3,0.1

Chan Stop Cuts=-1