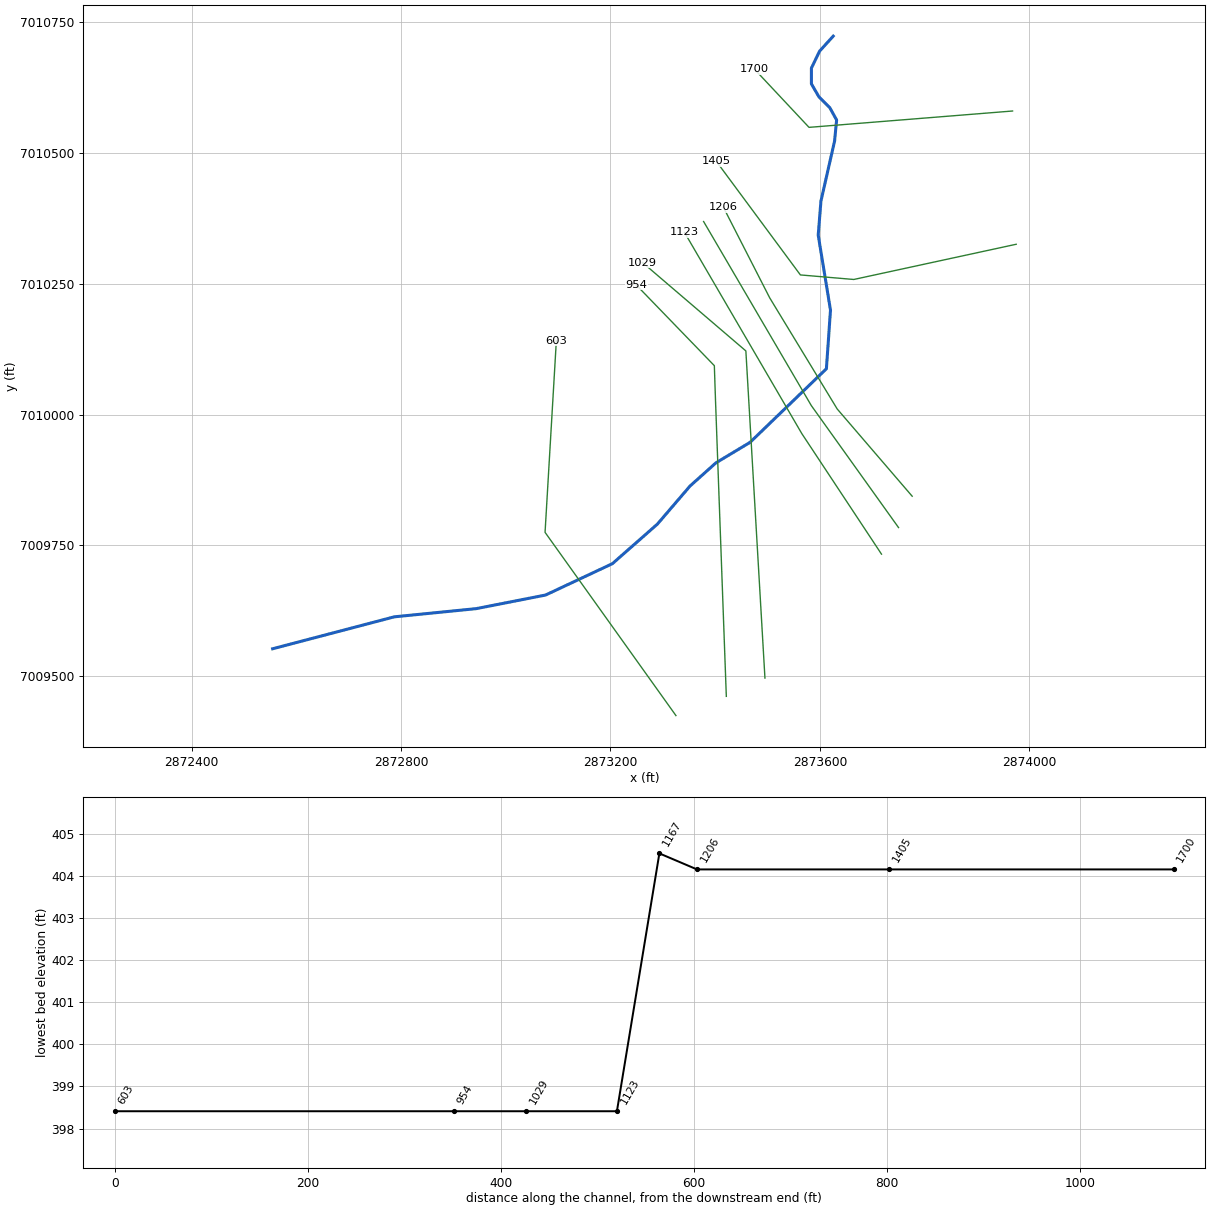
--- UNT 009 in Running Cr Watershed.prj (project) ---

Proj Title=UNT 009 in Running Cr Watershed Base Level Engineering
Current Plan=p01
Default Exp/Contr=0.3,0.1
English Units
Geom File=g01
Flow File=f01
Plan File=p01
BEGIN DESCRIPTION:
UNT 009 in Running Cr Watershed
END DESCRIPTION:

--- UNT 009 in Running Cr Watershed.p01 (plan) ---

Plan Title=Multiple Run
Short Identifier=Multiple
Geom File=g01
Flow File=f01
Subcritical Flow
K Sum by GR= 0
Std Step Tol= 0.01
Critical Tol= 0.01
Num of Std Step Trials= 20
Max Error Tol= 0.3
Flow Tol Ratio= 0.001
Split Flow NTrial= 30
Split Flow Tol= 0.02
Split Flow Ratio= 0.02
Log Output Level= 0
Friction Slope Method= 1
Unsteady Friction Slope Method= 2
Unsteady Bridges Friction Slope Method= 1
Parabolic Critical Depth
Global Vel Dist=  1 , 1 , 1
Global Log Level= 0
CheckData=True
Encroach Param= -1, 0, 0, 0
BEGIN DESCRIPTION:
Multiple Run
END DESCRIPTION:

--- UNT 009 in Running Cr Watershed.f01 (steady flow) ---

Flow Title=Multiple
Number of Profiles=7
Profile Names=10-year,25-year,50-year,1pct_min,100-year,1pct_plu,500-year
River Rch & RM= UNT 009 in Runni,Reach-1,1700
      81      94     102      56     111     221     130
Boundary for River Rch & Prof#=UNT 009 in Runni,Reach-1,1
Up Type=0
Dn Type=3
Dn Slope=0.005
Boundary for River Rch & Prof#=UNT 009 in Runni,Reach-1,2
Up Type=0
Dn Type=3
Dn Slope=0.005
Boundary for River Rch & Prof#=UNT 009 in Runni,Reach-1,3
Up Type=0
Dn Type=3
Dn Slope=0.005
Boundary for River Rch & Prof#=UNT 009 in Runni,Reach-1,4
Up Type=0
Dn Type=3
Dn Slope=0.005
Boundary for River Rch & Prof#=UNT 009 in Runni,Reach-1,5
Up Type=0
Dn Type=3
Dn Slope=0.005
Boundary for River Rch & Prof#=UNT 009 in Runni,Reach-1,6
Up Type=0
Dn Type=3
Dn Slope=0.005
Boundary for River Rch & Prof#=UNT 009 in Runni,Reach-1,7
Up Type=0
Dn Type=3
Dn Slope=0.005

--- UNT 009 in Running Cr Watershed.g01 (geometry) ---

Geom Title=Existing Conditions

River Reach=UNT 009 in Runni,Reach-1
Reach XY= 21
      2873625.50      7010722.96      2873599.46      7010694.31
      2873583.83      7010661.76      2873583.83      7010631.81
      2873598.15      7010607.07      2873618.99      7010586.24
      2873632.01      7010562.80      2873628.10      7010522.44
      2873602.06      7010407.85      2873596.85      7010342.75
      2873620.29      7010199.52      2873612.48      7010087.54
      2873466.64      7009946.92      2873401.54      7009907.85
      2873352.06      7009863.58      2873289.56      7009790.67
      2873203.62      7009715.14      2873076.02      7009655.25
      2872943.21      7009629.21      2872786.96      7009613.58
      2872554.50      7009552.56

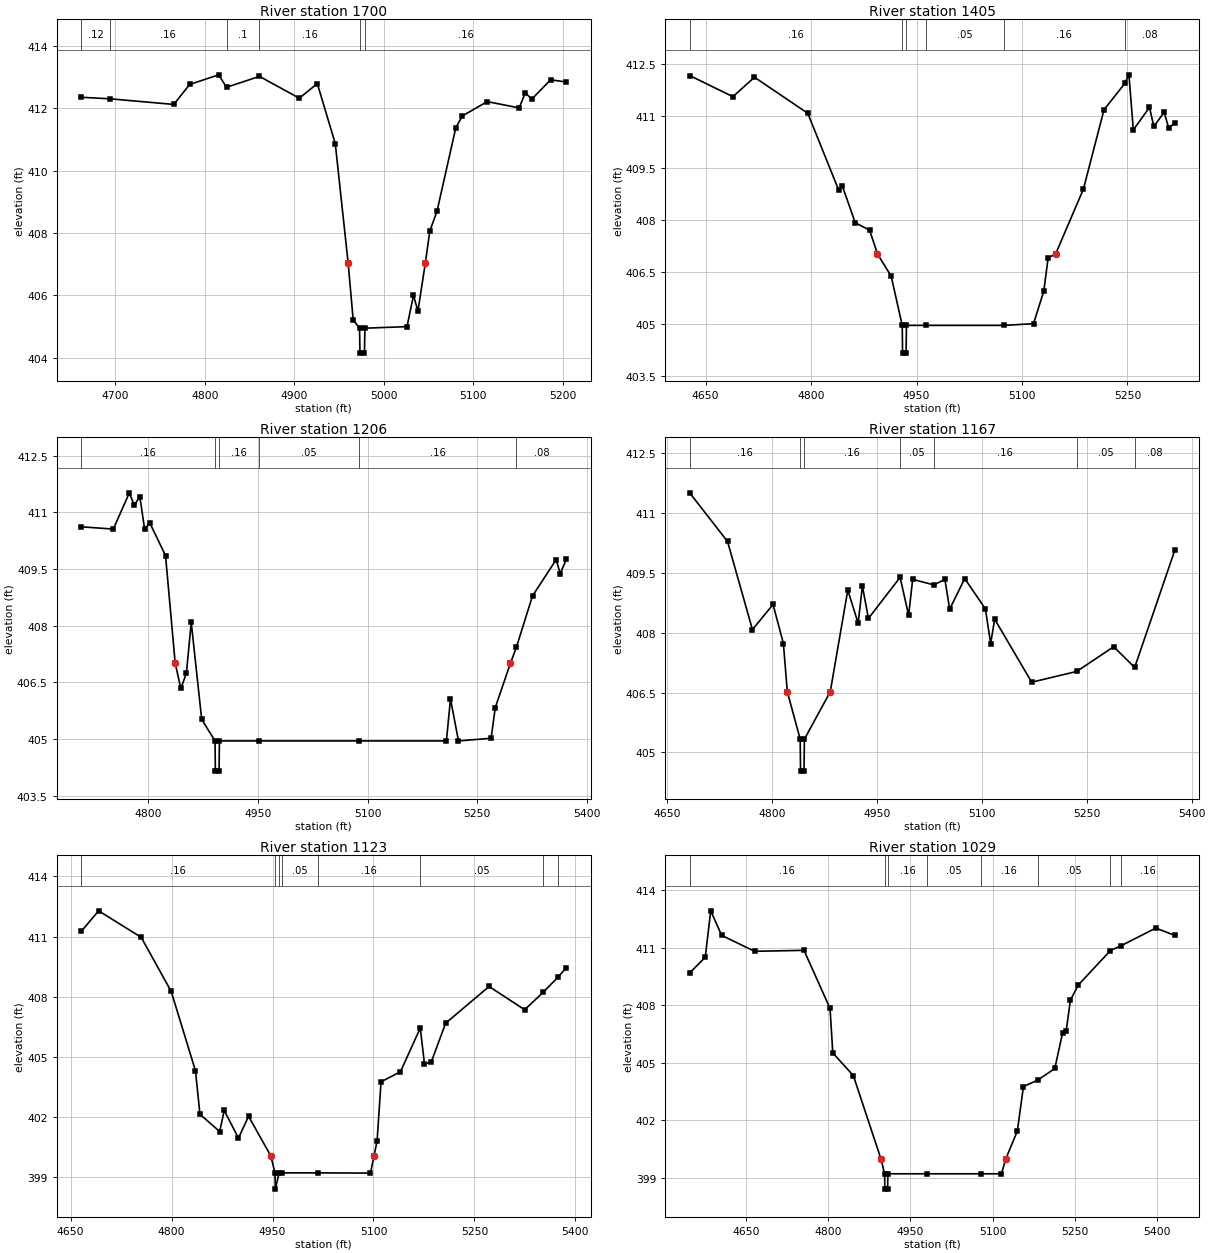
Type RM Length L Ch R = 1,1700,295,295,295
BEGIN DESCRIPTION:
UNT 009 in Running Cr Watershed 2.0
END DESCRIPTION:
XS GIS Cut Line= 3
      2873968.16      7010579.93      2873579.28      7010548.68
      2873475.14      7010659.77
#Sta/Elev= 30
  4661.8  412.36  4694.2  412.31  4765.3  412.13  4783.1  412.77  4815.5  413.08
  4824.3  412.68  4861.1  413.03  4905.7  412.33  4925.8  412.80  4945.9  410.87
  4960.3  407.03  4965.9  405.22  4973.0  404.95  4973.5  404.15  4978.5  404.15
  4979.0  404.95  5026.1  405.00  5033.3  406.00  5038.3  405.50  5046.5  407.03
  5051.6  408.07  5059.6  408.70  5080.6  411.38  5087.9  411.76  5115.8  412.22
  5151.5  412.02  5158.3  412.50  5165.6  412.30  5186.6  412.92  5204.2  412.85
#Mann=6,-1,0
  4661.8    0.12       0  4694.2    0.16       0  4824.3     0.1       0
  4861.1    0.16       0  4973.0    0.07       0  4979.0    0.16       0
Bank Sta=4960.3,5046.5
Exp/Cntr=0.3,0.1

Type RM Length L Ch R = 1,1405,199,199,199
BEGIN DESCRIPTION:
Mapping XS b04b7c8b
END DESCRIPTION:
XS GIS Cut Line= 4
      2873975.13      7010325.38      2873664.78      7010258.10
      2873562.78      7010266.78      2873402.19      7010483.80
#Sta/Elev= 30
  4627.4  412.16  4688.9  411.55  4719.6  412.11  4795.4  411.07  4839.4  408.85
  4844.6  408.97  4862.9  407.91  4883.3  407.70  4894.5  407.01  4914.0  406.37
  4929.7  404.95  4930.2  404.15  4935.2  404.15  4935.7  404.95  4963.3  404.95
  5074.2  404.95  5116.4  405.00  5131.0  405.94  5137.2  406.90  5147.8  407.01
  5187.3  408.88  5216.6  411.17  5246.1  411.93  5252.1  412.18  5258.3  410.59
  5281.3  411.24  5287.5  410.69  5302.2  411.10  5308.4  410.66  5317.3  410.78
#Mann=6,-1,0
  4627.4    0.16       0  4929.7   0.033       0  4935.7    0.16       0
  4963.3    0.05       0  5074.2    0.16       0  5246.1    0.08       0
Bank Sta=4894.5,5147.8
Exp/Cntr=0.3,0.1

Type RM Length L Ch R = 1,1206,39,39,39
BEGIN DESCRIPTION:
Mapping XS 079221cd
END DESCRIPTION:
XS GIS Cut Line= 4
      2873776.31      7009844.05      2873633.10      7010010.71
      2873504.19      7010222.94      2873415.63      7010396.16
#Sta/Elev= 30
  4708.9  410.62  4752.8  410.56  4774.7  411.52  4781.3  411.19  4789.0  411.42
  4795.6  410.55  4802.4  410.73  4824.1  409.86  4837.3  407.01  4845.0  406.34
  4852.6  406.74  4859.2  408.09  4873.5  405.52  4891.7  404.95  4892.2  404.15
  4897.2  404.15  4897.7  404.95  4952.1  404.95  5088.5  404.95  5207.7  404.95
  5213.3  406.06  5224.2  404.95  5268.8  405.02  5274.4  405.83  5295.2  407.01
  5303.3  407.43  5325.3  408.79  5357.6  409.75  5363.2  409.38  5371.5  409.76
#Mann=6,-1,0
  4708.9    0.16       0  4891.7   0.033       0  4897.7    0.16       0
  4952.1    0.05       0  5088.5    0.16       0  5303.3    0.08       0
Bank Sta=4837.3,5295.2
Exp/Cntr=0.3,0.1

Type RM Length L Ch R = 1,1167,44,44,44
BEGIN DESCRIPTION:
Mapping XS c502e4b0
END DESCRIPTION:
XS GIS Cut Line= 3
      2873750.28      7009784.15      2873583.62      7010017.22
      2873377.87      7010368.82
#Sta/Elev= 30
  4682.0  411.51  4736.2  410.29  4771.8  408.08  4801.3  408.71  4816.1  407.73
  4821.7  406.52  4840.1  405.33  4840.6  404.53  4845.6  404.53  4846.1  405.33
  4883.1  406.52  4908.2  409.07  4923.0  408.24  4929.1  409.17  4937.7  408.36
  4983.0  409.39  4995.2  408.44  5001.0  409.34  5031.4  409.20  5047.1  409.34
  5053.9  408.59  5075.4  409.36  5105.0  408.60  5112.5  407.73  5118.3  408.34
  5171.2  406.76  5235.6  407.03  5288.5  407.65  5318.5  407.13  5375.9  410.07
#Mann=7,-1,0
  4682.0    0.16       0  4840.1   0.033       0  4846.1    0.16       0
  4983.0    0.05       0  5031.4    0.16       0  5235.6    0.05       0
  5318.5    0.08       0
Bank Sta=4821.7,4883.1
Exp/Cntr=0.3,0.1

Type RM Length L Ch R = 1,1123,94,94,94
BEGIN DESCRIPTION:
Mapping XS f23901bf
END DESCRIPTION:
XS GIS Cut Line= 3
      2873717.74      7009733.35      2873565.39      7009963.83
      2873341.44      7010347.93
#Sta/Elev= 30
  4665.7  411.25  4691.6  412.28  4754.9  410.96  4799.5  408.26  4835.5  404.31
  4842.2  402.14  4871.5  401.28  4878.3  402.33  4899.4  400.95  4914.4  402.04
  4947.6  400.06  4953.7  399.21  4954.2  398.41  4959.7  399.21  4964.7  399.22
  5017.0  399.22  5095.6  399.21  5100.8  400.06  5105.4  400.81  5111.3  403.76
  5140.1  404.26  5169.6  406.44  5175.8  404.65  5185.8  404.74  5207.3  406.68
  5271.8  408.51  5324.7  407.35  5352.2  408.22  5374.4  408.98  5386.6  409.45
#Mann=8,-1,0
  4665.7    0.16       0  4953.7   0.033       0  4959.7    0.16       0
  4964.7    0.05       0  5017.0    0.16       0  5169.6    0.05       0
  5352.2    0.08       0  5374.4    0.16       0
Bank Sta=4947.6,5100.8
Exp/Cntr=0.3,0.1

Type RM Length L Ch R = 1,1029,75,75,75
BEGIN DESCRIPTION:
Mapping XS 23fd3394
END DESCRIPTION:
XS GIS Cut Line= 3
      2873495.08      7009496.56      2873458.62      7010121.60
      2873261.18      7010290.46
#Sta/Elev= 30
  4546.9  409.68  4575.4  410.50  4585.4  412.92  4605.4  411.64  4665.5  410.81
  4755.7  410.86  4803.3  407.83  4808.3  405.51  4845.8  404.33  4896.4  399.97
  4902.9  399.21  4903.4  398.41  4908.4  398.41  4908.9  399.21  4980.5  399.21
  5078.4  399.21  5116.3  399.21  5123.9  399.97  5145.3  401.44  5156.4  403.76
  5182.3  404.09  5213.7  404.70  5227.9  406.56  5234.5  406.67  5242.2  408.26
  5256.5  409.05  5315.3  410.85  5335.4  411.11  5398.1  412.02  5432.8  411.64
#Mann=8,-1,0
  4546.9    0.16       0  4902.9   0.033       0  4908.9    0.16       0
  4980.5    0.05       0  5078.4    0.16       0  5182.3    0.05       0
  5315.3     0.1       0  5335.4    0.16       0
Bank Sta=4896.4,5123.9
Exp/Cntr=0.3,0.1

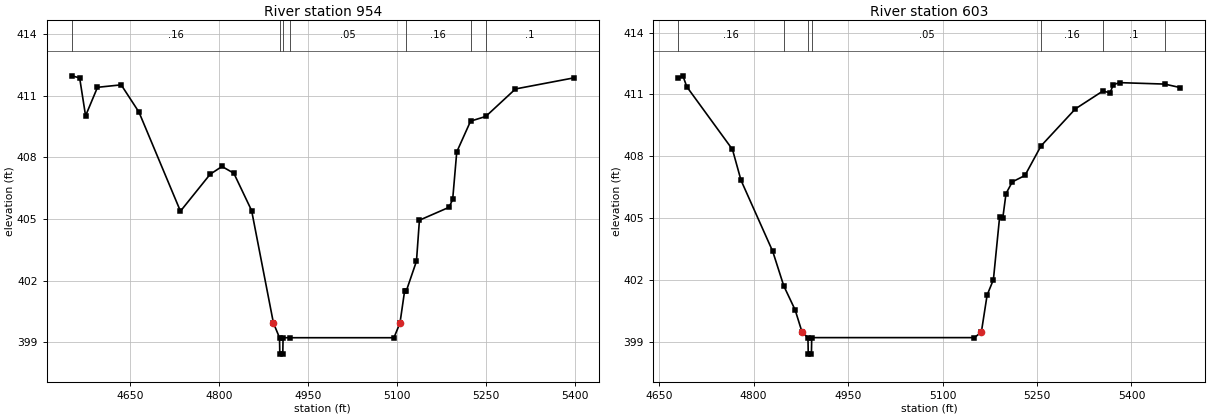
Type RM Length L Ch R = 1,954,351,351,351
BEGIN DESCRIPTION:
Mapping XS 3ec376d0
END DESCRIPTION:
XS GIS Cut Line= 4
      2873421.29      7009461.68      2873400.67      7010025.90
      2873398.40      7010093.42      2873248.81      7010248.04
#Sta/Elev= 30
  4551.5  411.98  4564.8  411.88  4574.8  410.03  4594.9  411.42  4634.9  411.54
  4664.9  410.21  4734.9  405.38  4785.0  407.18  4805.0  407.56  4825.0  407.23
  4855.0  405.41  4891.8  399.93  4902.1  399.21  4902.6  398.41  4907.6  398.41
  4908.1  399.21  4920.2  399.21  5095.2  399.21  5105.4  399.93  5113.1  401.47
  5115.8  401.47  5133.2  402.94  5138.2  404.94  5188.2  405.57  5194.3  405.95
  5201.2  408.27  5224.5  409.77  5250.2  410.00  5300.3  411.34  5398.8  411.88
#Mann=7,-1,0
  4551.5    0.16       0  4902.1   0.033       0  4908.1    0.16       0
  4920.2    0.05       0  5115.8    0.16       0  5224.5    0.05       0
  5250.2     0.1       0
Bank Sta=4891.8,5105.4
Exp/Cntr=0.3,0.1

Type RM Length L Ch R = 1,603,0,0,0
BEGIN DESCRIPTION:
UNT 009 in Running Cr Watershed 1.0
END DESCRIPTION:
XS GIS Cut Line= 3
      2873325.02      7009424.97      2873075.00      7009775.00
      2873096.57      7010141.21
#Sta/Elev= 30
  4680.5  411.78  4687.9  411.90  4694.1  411.37  4766.6  408.33  4780.1  406.84
  4830.5  403.39  4848.0  401.72  4866.1  400.55  4877.0  399.48  4886.4  399.21
  4886.9  398.41  4891.9  398.41  4892.4  399.21  5150.7  399.21  5161.7  399.48
  5170.8  401.27  5180.8  402.02  5190.7  405.07  5195.8  405.03  5200.8  406.19
  5210.8  406.76  5230.9  407.07  5256.3  408.50  5311.0  410.30  5354.4  411.16
  5366.0  411.08  5371.1  411.47  5381.1  411.57  5452.6  411.50  5477.5  411.33
#Mann=7,-1,0
  4680.5    0.16       0  4848.0    0.05       0  4886.4   0.033       0
  4892.4    0.05       0  5256.3    0.16       0  5354.4     0.1       0
  5452.6    0.16       0
Bank Sta=4877,5161.7
Exp/Cntr=0.3,0.1

Chan Stop Cuts=-1