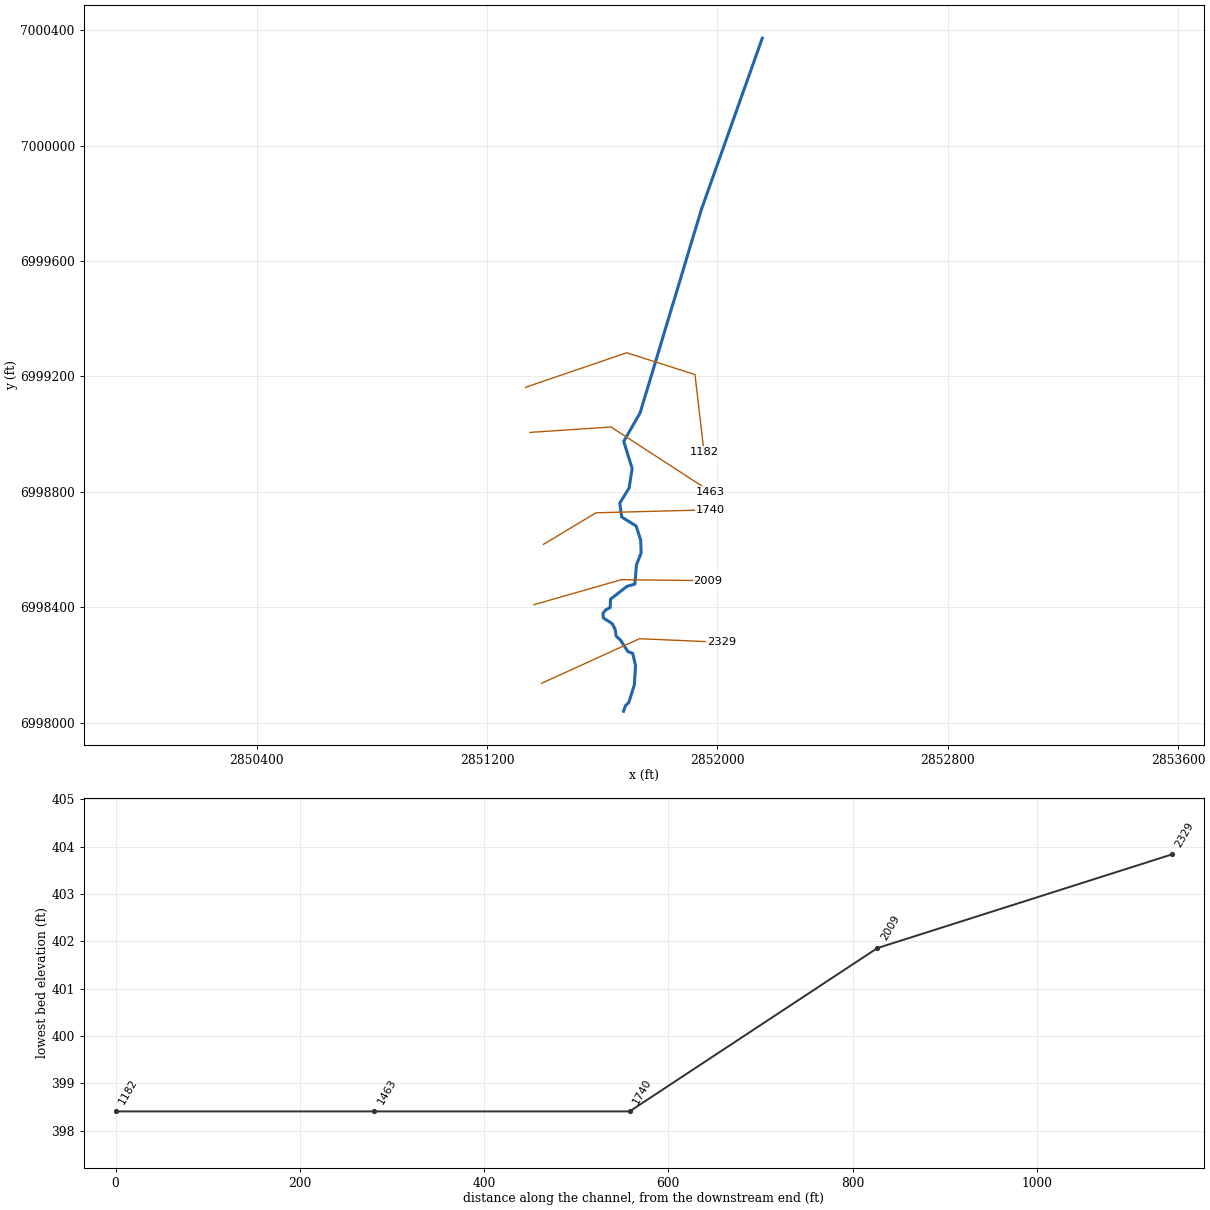
--- UNT 010 in Running Cr Watershed.prj (project) ---

Proj Title=UNT 010 in Running Cr Watershed Base Level Engineering
Current Plan=p01
Default Exp/Contr=0.3,0.1
English Units
Geom File=g01
Flow File=f01
Plan File=p01
BEGIN DESCRIPTION:
UNT 010 in Running Cr Watershed
END DESCRIPTION:

--- UNT 010 in Running Cr Watershed.p01 (plan) ---

Plan Title=Multiple Run
Short Identifier=Multiple
Geom File=g01
Flow File=f01
Subcritical Flow
K Sum by GR= 0
Std Step Tol= 0.01
Critical Tol= 0.01
Num of Std Step Trials= 20
Max Error Tol= 0.3
Flow Tol Ratio= 0.001
Split Flow NTrial= 30
Split Flow Tol= 0.02
Split Flow Ratio= 0.02
Log Output Level= 0
Friction Slope Method= 1
Unsteady Friction Slope Method= 2
Unsteady Bridges Friction Slope Method= 1
Parabolic Critical Depth
Global Vel Dist=  1 , 1 , 1
Global Log Level= 0
CheckData=True
Encroach Param= -1, 0, 0, 0
BEGIN DESCRIPTION:
Multiple Run
END DESCRIPTION:

--- UNT 010 in Running Cr Watershed.f01 (steady flow) ---

Flow Title=Multiple
Number of Profiles=7
Profile Names=10-year,25-year,50-year,1pct_min,100-year,1pct_plu,500-year
River Rch & RM= UNT 010 in Runni,Reach-1,2329
     184     229     263     151     302     603     397
Boundary for River Rch & Prof#=UNT 010 in Runni,Reach-1,1
Up Type=0
Dn Type=3
Dn Slope=0.005
Boundary for River Rch & Prof#=UNT 010 in Runni,Reach-1,2
Up Type=0
Dn Type=3
Dn Slope=0.005
Boundary for River Rch & Prof#=UNT 010 in Runni,Reach-1,3
Up Type=0
Dn Type=3
Dn Slope=0.005
Boundary for River Rch & Prof#=UNT 010 in Runni,Reach-1,4
Up Type=0
Dn Type=3
Dn Slope=0.005
Boundary for River Rch & Prof#=UNT 010 in Runni,Reach-1,5
Up Type=0
Dn Type=3
Dn Slope=0.005
Boundary for River Rch & Prof#=UNT 010 in Runni,Reach-1,6
Up Type=0
Dn Type=3
Dn Slope=0.005
Boundary for River Rch & Prof#=UNT 010 in Runni,Reach-1,7
Up Type=0
Dn Type=3
Dn Slope=0.005

--- UNT 010 in Running Cr Watershed.g01 (geometry) ---

Geom Title=Existing Conditions

River Reach=UNT 010 in Runni,Reach-1
Reach XY= 30
      2851674.28      6998039.77      2851681.05      6998059.04
      2851692.51      6998069.97      2851711.78      6998130.91
      2851715.95      6998197.58      2851706.05      6998240.81
      2851689.86      6998246.02      2851663.82      6998286.16
      2851648.63      6998300.27      2851645.38      6998323.06
      2851634.52      6998343.67      2851604.14      6998363.20
      2851603.06      6998379.48      2851612.82      6998391.42
      2851628.01      6998399.01      2851629.10      6998428.31
      2851686.61      6998472.80      2851713.73      6998480.39
      2851719.16      6998547.67      2851735.44      6998588.03
      2851733.70      6998633.17      2851718.07      6998681.78
      2851667.73      6998713.03      2851661.21      6998761.21
      2851693.77      6998813.72      2851704.19      6998881.43
      2851675.00      6998975.00      2851731.95      6999074.29
      2851944.10      6999777.33      2852155.99      7000372.44

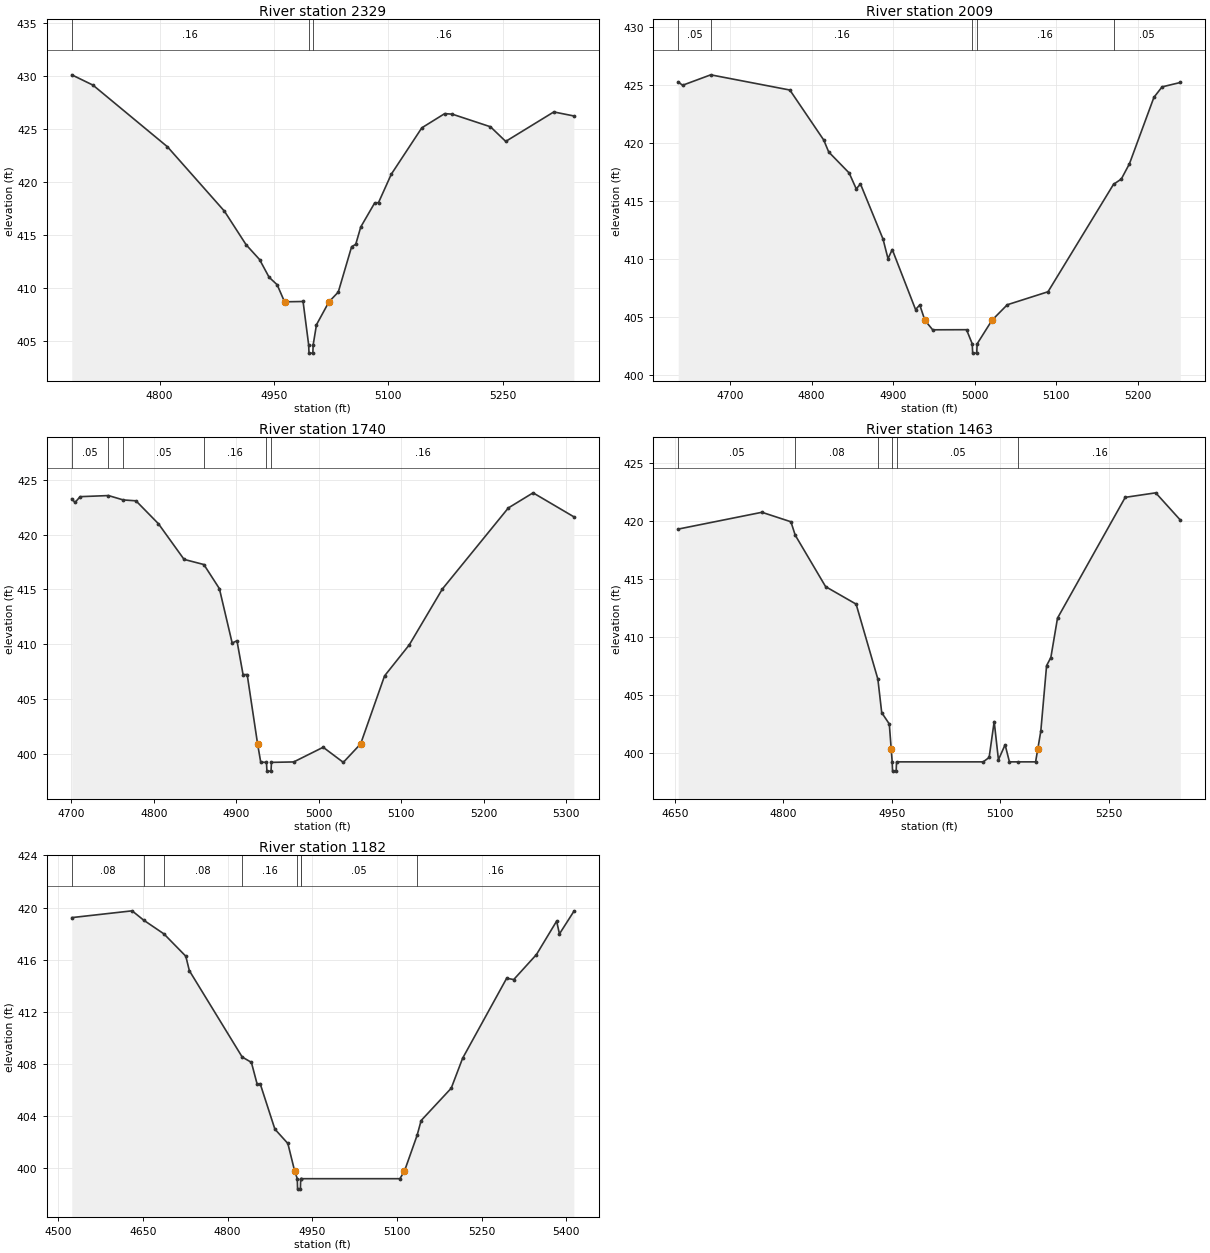
Type RM Length L Ch R = 1,2329,320,320,320
BEGIN DESCRIPTION:
UNT 010 in Running Cr Watershed 5.0
END DESCRIPTION:
XS GIS Cut Line= 3
      2851389.30      6998136.40      2851729.79      6998291.16
      2852014.31      6998278.77
#Sta/Elev= 30
  4684.7  430.09  4712.5  429.12  4810.3  423.30  4885.0  417.23  4913.5  414.06
  4931.1  412.67  4943.6  411.00  4954.2  410.29  4963.9  408.68  4988.2  408.71
  4995.5  404.64  4996.0  403.84  5001.0  403.84  5001.5  404.64  5005.8  406.52
  5022.2  408.68  5034.4  409.60  5051.9  413.88  5057.3  414.10  5063.9  415.74
  5082.2  418.01  5087.2  418.04  5104.0  420.72  5144.0  425.09  5174.0  426.43
  5184.0  426.38  5234.1  425.19  5254.1  423.81  5317.2  426.59  5343.5  426.21
#Mann=3,-1,0
  4684.7    0.16       0  4995.5    0.07       0  5001.5    0.16       0
Bank Sta=4963.9,5022.2
Exp/Cntr=0.3,0.1

Type RM Length L Ch R = 1,2009,269,269,269
BEGIN DESCRIPTION:
Mapping XS 7429fdb2
END DESCRIPTION:
XS GIS Cut Line= 3
      2851363.29      6998408.98      2851667.10      6998495.79
      2851967.41      6998492.32
#Sta/Elev= 30
  4636.2  425.24  4641.5  424.95  4676.1  425.85  4773.2  424.54  4814.8  420.23
  4820.9  419.20  4846.0  417.39  4854.7  416.02  4859.9  416.44  4887.6  411.69
  4893.7  410.00  4898.9  410.79  4927.5  405.62  4932.7  406.01  4938.9  404.70
  4948.5  403.87  4990.1  403.88  4997.1  402.66  4997.6  401.86  5002.6  401.86
  5003.1  402.66  5021.4  404.70  5040.1  406.03  5090.1  407.15  5170.5  416.41
  5180.1  416.87  5190.1  418.19  5220.1  423.91  5230.1  424.81  5252.5  425.19
#Mann=5,-1,0
  4636.2    0.05       0  4676.1    0.16       0  4997.1    0.07       0
  5003.1    0.16       0  5170.5    0.05       0
Bank Sta=4938.9,5021.4
Exp/Cntr=0.3,0.1

Type RM Length L Ch R = 1,1740,277,277,277
BEGIN DESCRIPTION:
UNT 010 in Running Cr Watershed 4.0
END DESCRIPTION:
XS GIS Cut Line= 3
      2851396.28      6998618.19      2851578.56      6998727.56
      2851974.35      6998737.97
#Sta/Elev= 30
  4700.5  423.28  4704.4  422.95  4710.7  423.48  4745.0  423.58  4762.9  423.18
  4778.3  423.10  4805.5  421.01  4836.6  417.75  4860.6  417.28  4879.4  415.08
  4894.9  410.11  4900.7  410.32  4908.1  407.23  4913.1  407.23  4925.7  400.90
  4929.5  399.23  4936.5  399.21  4937.0  398.41  4942.0  398.41  4942.5  399.21
  4969.5  399.25  5005.2  400.59  5029.6  399.21  5050.6  400.90  5079.6  407.11
  5109.6  409.95  5149.6  415.04  5229.6  422.45  5259.6  423.83  5309.0  421.64
#Mann=6,-1,0
  4700.5    0.05       0  4745.0    0.16       0  4762.9    0.05       0
  4860.6    0.16       0  4936.5    0.07       0  4942.5    0.16       0
Bank Sta=4925.7,5050.6
Exp/Cntr=0.3,0.1

Type RM Length L Ch R = 1,1463,281,281,281
BEGIN DESCRIPTION:
UNT 010 in Running Cr Watershed 3.0
END DESCRIPTION:
XS GIS Cut Line= 3
      2851349.42      6999006.21      2851630.65      6999025.00
      2851976.99      6998800.48
#Sta/Elev= 30
  4654.7  419.31  4770.5  420.76  4810.6  419.94  4816.5  418.79  4858.6  414.34
  4900.8  412.83  4930.9  406.35  4936.2  403.46  4946.7  402.48  4949.3  400.35
  4950.7  399.21  4951.2  398.41  4956.2  398.41  4956.7  399.21  5076.6  399.21
  5084.8  399.59  5091.8  402.69  5097.7  399.39  5106.9  400.69  5112.9  399.21
  5125.4  399.21  5149.1  399.21  5152.2  400.35  5156.3  401.86  5164.3  407.52
  5170.2  408.22  5179.4  411.62  5273.1  422.05  5315.3  422.44  5349.3  420.09
#Mann=6,-1,0
  4654.7    0.05       0  4816.5    0.08       0  4930.9    0.05       0
  4950.7   0.033       0  4956.7    0.05       0  5125.4    0.16       0
Bank Sta=4949.3,5152.2
Exp/Cntr=0.3,0.1

Type RM Length L Ch R = 1,1182,0,0,0
BEGIN DESCRIPTION:
Mapping XS 6f498a5f
END DESCRIPTION:
XS GIS Cut Line= 4
      2851333.80      6999162.46      2851685.33      6999282.25
      2851922.31      6999206.72      2851953.48      6998939.24
#Sta/Elev= 30
  4523.9  419.23  4630.8  419.75  4651.1  419.04  4687.2  417.98  4725.9  416.27
  4732.2  415.16  4825.8  408.54  4842.1  408.13  4852.4  406.44  4857.6  406.50
  4883.7  403.01  4906.7  401.91  4918.7  399.80  4923.4  399.21  4923.9  398.41
  4928.9  398.41  4929.4  399.21  4929.9  399.21  5105.2  399.21  5113.3  399.80
  5135.6  402.53  5142.8  403.67  5196.1  406.15  5216.2  408.44  5294.3  414.58
  5306.8  414.48  5347.1  416.40  5382.8  418.96  5387.8  417.98  5413.3  419.71
#Mann=8,-1,0
  4523.9    0.08       0  4651.1    0.05       0  4687.2    0.08       0
  4825.8    0.16       0  4923.4   0.033       0  4929.4    0.16       0
  4929.9    0.05       0  5135.6    0.16       0
Bank Sta=4918.7,5113.3
Exp/Cntr=0.3,0.1

Chan Stop Cuts=-1