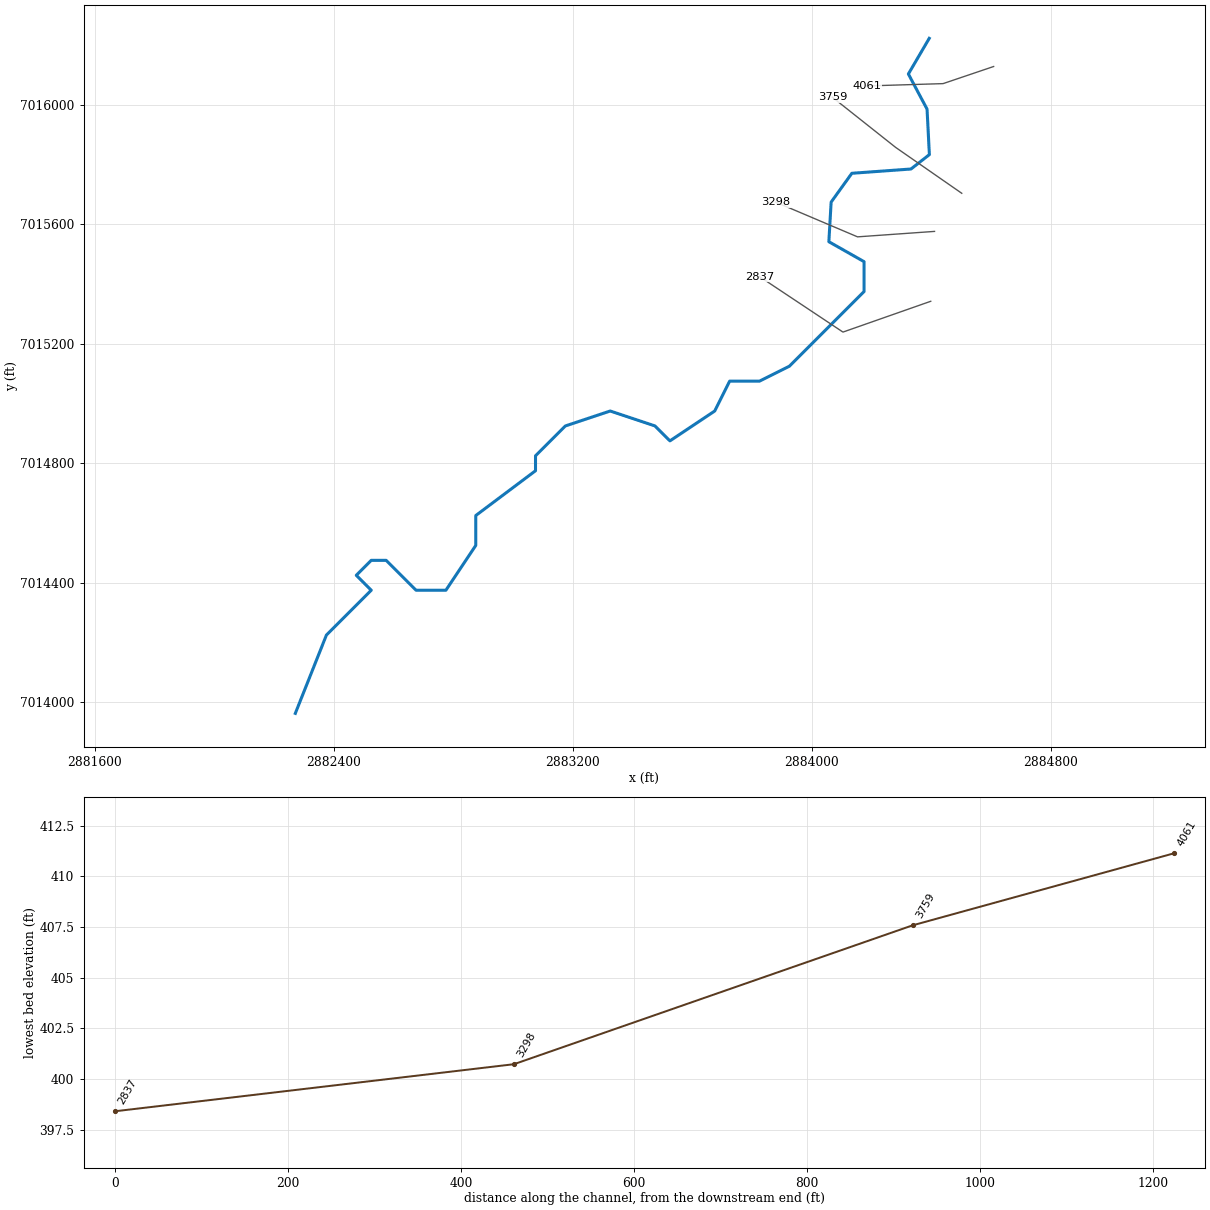
--- UNT 011 in Running Cr Watershed.prj (project) ---

Proj Title=UNT 011 in Running Cr Watershed Base Level Engineering
Current Plan=p01
Default Exp/Contr=0.3,0.1
English Units
Geom File=g01
Flow File=f01
Plan File=p01
BEGIN DESCRIPTION:
UNT 011 in Running Cr Watershed
END DESCRIPTION:

--- UNT 011 in Running Cr Watershed.p01 (plan) ---

Plan Title=Multiple Run
Short Identifier=Multiple
Geom File=g01
Flow File=f01
Subcritical Flow
K Sum by GR= 0
Std Step Tol= 0.01
Critical Tol= 0.01
Num of Std Step Trials= 20
Max Error Tol= 0.3
Flow Tol Ratio= 0.001
Split Flow NTrial= 30
Split Flow Tol= 0.02
Split Flow Ratio= 0.02
Log Output Level= 0
Friction Slope Method= 1
Unsteady Friction Slope Method= 2
Unsteady Bridges Friction Slope Method= 1
Parabolic Critical Depth
Global Vel Dist=  1 , 1 , 1
Global Log Level= 0
CheckData=True
Encroach Param= -1, 0, 0, 0
BEGIN DESCRIPTION:
Multiple Run
END DESCRIPTION:

--- UNT 011 in Running Cr Watershed.f01 (steady flow) ---

Flow Title=Multiple
Number of Profiles=7
Profile Names=10-year,25-year,50-year,1pct_min,100-year,1pct_plu,500-year
River Rch & RM= UNT 011 in Runni,Reach-1,4061
     114     136     152      85     169     337     209
Boundary for River Rch & Prof#=UNT 011 in Runni,Reach-1,1
Up Type=0
Dn Type=3
Dn Slope=0.005
Boundary for River Rch & Prof#=UNT 011 in Runni,Reach-1,2
Up Type=0
Dn Type=3
Dn Slope=0.005
Boundary for River Rch & Prof#=UNT 011 in Runni,Reach-1,3
Up Type=0
Dn Type=3
Dn Slope=0.005
Boundary for River Rch & Prof#=UNT 011 in Runni,Reach-1,4
Up Type=0
Dn Type=3
Dn Slope=0.005
Boundary for River Rch & Prof#=UNT 011 in Runni,Reach-1,5
Up Type=0
Dn Type=3
Dn Slope=0.005
Boundary for River Rch & Prof#=UNT 011 in Runni,Reach-1,6
Up Type=0
Dn Type=3
Dn Slope=0.005
Boundary for River Rch & Prof#=UNT 011 in Runni,Reach-1,7
Up Type=0
Dn Type=3
Dn Slope=0.005

--- UNT 011 in Running Cr Watershed.g01 (geometry) ---

Geom Title=Existing Conditions

River Reach=UNT 011 in Runni,Reach-1
Reach XY= 30
      2884393.24      7016222.72      2884323.36      7016103.36
      2884385.86      7015985.74      2884393.68      7015833.40
      2884332.04      7015785.22      2884134.13      7015770.90
      2884064.77      7015674.46      2884057.13      7015541.82
      2884175.00      7015475.00      2884175.00      7015375.00
      2883925.00      7015125.00      2883825.00      7015075.00
      2883725.00      7015075.00      2883675.00      7014975.00
      2883525.00      7014875.00      2883475.00      7014925.00
      2883325.00      7014975.00      2883175.00      7014925.00
      2883075.00      7014825.00      2883075.00      7014775.00
      2882875.00      7014625.00      2882875.00      7014525.00
      2882775.00      7014375.00      2882675.00      7014375.00
      2882575.00      7014475.00      2882525.00      7014475.00
      2882475.00      7014425.00      2882525.00      7014375.00
      2882375.00      7014225.00      2882270.83      7013962.69

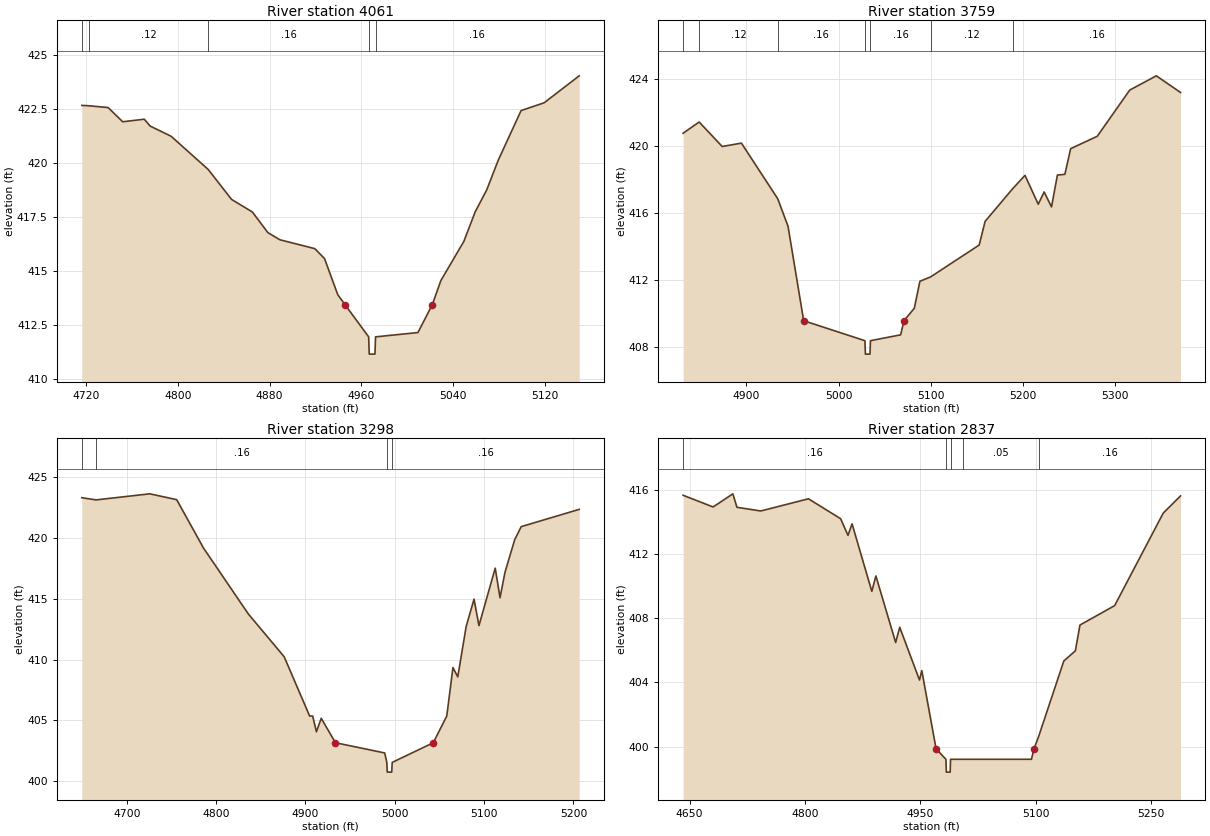
Type RM Length L Ch R = 1,4061,302,302,302
BEGIN DESCRIPTION:
UNT 011 in Running Cr Watershed 1.0
END DESCRIPTION:
XS GIS Cut Line= 3
      2884608.82      7016128.40      2884439.58      7016071.12
      2884184.37      7016063.31
#Sta/Elev= 30
  4716.1  422.66  4722.6  422.64  4739.1  422.56  4751.8  421.90  4770.6  422.02
  4775.8  421.70  4794.0  421.23  4826.4  419.69  4846.8  418.30  4864.9  417.72
  4878.5  416.76  4889.0  416.43  4919.4  416.02  4927.9  415.56  4939.4  413.89
  4945.8  413.42  4966.4  411.93  4966.9  411.13  4971.9  411.13  4972.4  411.93
  5009.4  412.13  5021.9  413.42  5029.4  414.54  5049.4  416.35  5059.4  417.73
  5069.4  418.74  5079.4  420.11  5099.4  422.42  5119.5  422.78  5150.1  424.03
#Mann=5,-1,0
  4716.1    0.16       0  4722.6    0.12       0  4826.4    0.16       0
  4966.4    0.07       0  4972.4    0.16       0
Bank Sta=4945.8,5021.9
Exp/Cntr=0.3,0.1

Type RM Length L Ch R = 1,3759,461,461,461
BEGIN DESCRIPTION:
Mapping XS 8c2c724f
END DESCRIPTION:
XS GIS Cut Line= 3
      2884502.06      7015703.95      2884280.72      7015857.58
      2884068.61      7016025.72
#Sta/Elev= 30
  4831.2  420.74  4848.6  421.41  4873.6  419.95  4894.5  420.15  4933.9  416.84
  4945.1  415.20  4962.1  409.57  5028.6  408.38  5029.1  407.58  5034.1  407.58
  5034.6  408.38  5067.4  408.73  5071.0  409.57  5082.2  410.31  5088.3  411.92
  5099.9  412.18  5152.7  414.08  5159.1  415.49  5189.1  417.44  5202.4  418.23
  5216.8  416.51  5223.2  417.24  5231.2  416.35  5237.6  418.25  5245.7  418.29
  5252.0  419.82  5280.9  420.56  5316.1  423.31  5345.0  424.16  5371.3  423.17
#Mann=7,-1,0
  4831.2    0.05       0  4848.6    0.12       0  4933.9    0.16       0
  5028.6    0.07       0  5034.6    0.16       0  5099.9    0.12       0
  5189.1    0.16       0
Bank Sta=4962.1,5071
Exp/Cntr=0.3,0.1

Type RM Length L Ch R = 1,3298,461,461,461
BEGIN DESCRIPTION:
Mapping XS 7da4165e
END DESCRIPTION:
XS GIS Cut Line= 3
      2884410.91      7015576.33      2884153.12      7015558.10
      2883878.57      7015674.66
#Sta/Elev= 30
  4649.7  423.32  4665.7  423.14  4725.8  423.64  4755.9  423.16  4785.9  419.18
  4836.1  413.75  4876.2  410.23  4904.7  405.35  4908.1  405.35  4912.3  404.05
  4917.7  405.16  4933.6  403.15  4988.7  402.31  4991.1  401.53  4991.6  400.73
  4996.6  400.73  4997.1  401.53  5043.1  403.15  5058.2  405.35  5065.1  409.34
  5070.5  408.57  5079.9  412.72  5088.7  414.97  5094.2  412.79  5112.4  417.52
  5117.8  415.09  5123.4  417.20  5134.2  419.86  5141.5  420.94  5206.4  422.36
#Mann=4,-1,0
  4649.7    0.12       0  4665.7    0.16       0  4991.1    0.07       0
  4997.1    0.16       0
Bank Sta=4933.6,5043.1
Exp/Cntr=0.3,0.1

Type RM Length L Ch R = 1,2837,0,0,0
BEGIN DESCRIPTION:
UNT 011 in Running Cr Watershed 2.0
END DESCRIPTION:
XS GIS Cut Line= 3
      2884398.24      7015342.38      2884104.35      7015239.27
      2883825.01      7015424.99
#Sta/Elev= 30
  4641.6  415.67  4680.6  414.94  4706.3  415.76  4711.6  414.92  4742.6  414.69
  4804.6  415.45  4846.4  414.21  4856.0  413.17  4861.3  413.89  4887.0  409.68
  4892.3  410.64  4918.0  406.49  4923.3  407.44  4949.0  404.15  4952.0  404.74
  4970.6  399.86  4983.4  399.21  4983.9  398.41  4988.9  398.41  4989.4  399.21
  5006.1  399.21  5094.6  399.21  5097.9  399.86  5104.1  400.65  5136.7  405.34
  5151.7  405.97  5157.7  407.58  5202.8  408.79  5266.0  414.56  5288.5  415.63
#Mann=5,-1,0
  4641.6    0.16       0  4983.4    0.07       0  4989.4    0.16       0
  5006.1    0.05       0  5104.1    0.16       0
Bank Sta=4970.6,5097.9
Exp/Cntr=0.3,0.1

Chan Stop Cuts=-1