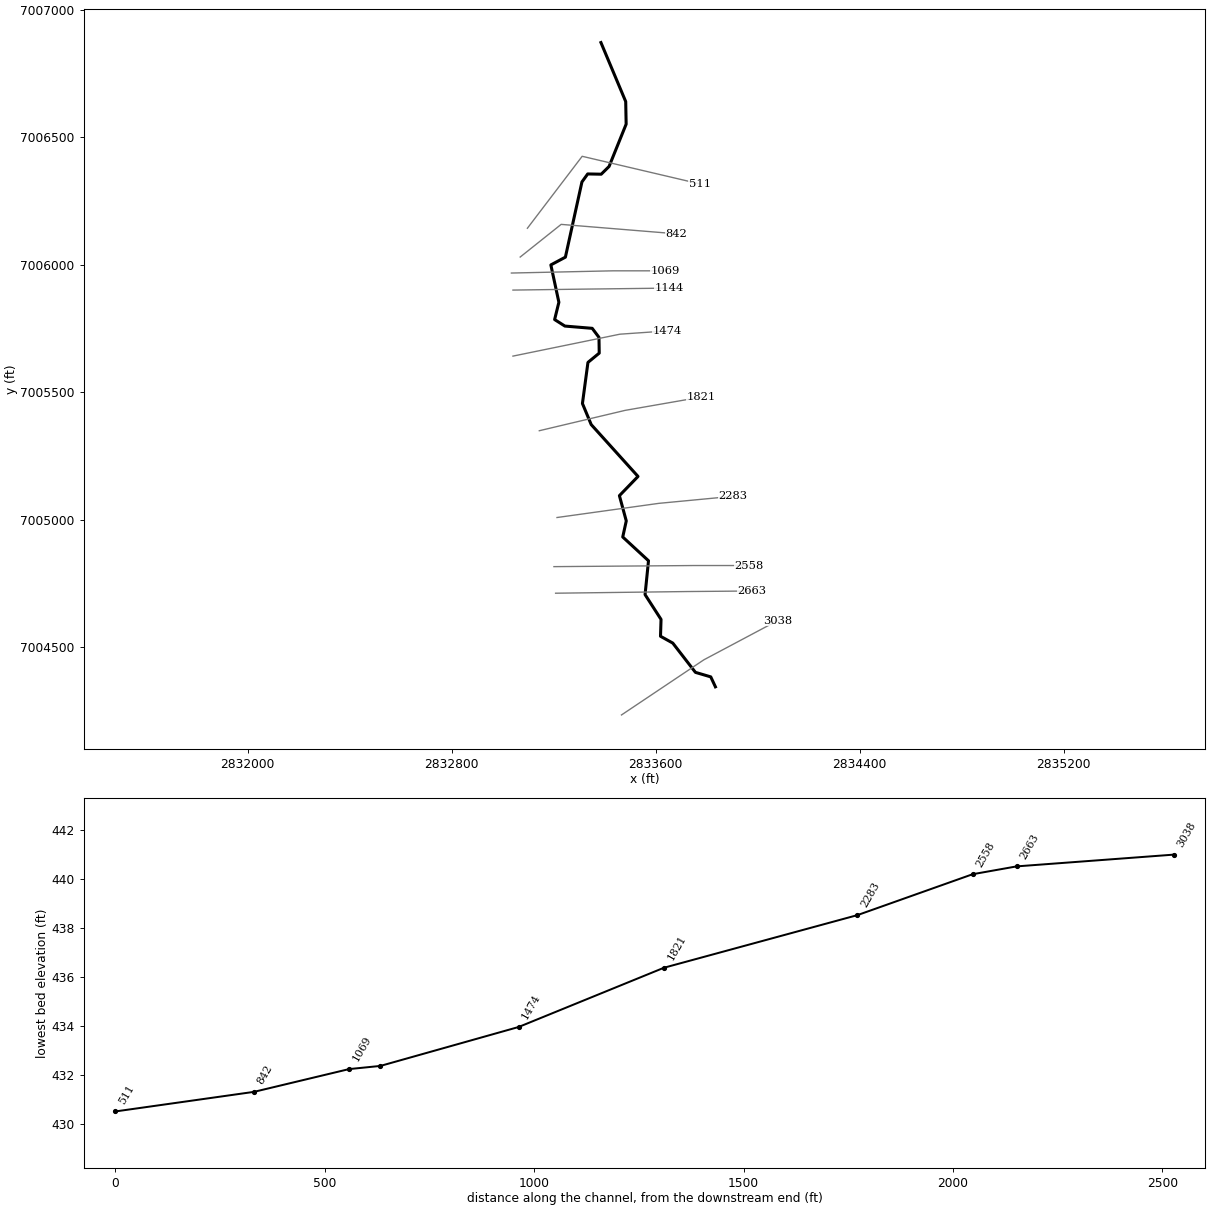
--- UNT 012 in Running Cr Watershed.prj (project) ---

Proj Title=UNT 012 in Running Cr Watershed Base Level Engineering
Current Plan=p01
Default Exp/Contr=0.3,0.1
English Units
Geom File=g01
Flow File=f01
Plan File=p01
BEGIN DESCRIPTION:
UNT 012 in Running Cr Watershed
END DESCRIPTION:

--- UNT 012 in Running Cr Watershed.p01 (plan) ---

Plan Title=Multiple Run
Short Identifier=Multiple
Geom File=g01
Flow File=f01
Subcritical Flow
K Sum by GR= 0
Std Step Tol= 0.01
Critical Tol= 0.01
Num of Std Step Trials= 20
Max Error Tol= 0.3
Flow Tol Ratio= 0.001
Split Flow NTrial= 30
Split Flow Tol= 0.02
Split Flow Ratio= 0.02
Log Output Level= 0
Friction Slope Method= 1
Unsteady Friction Slope Method= 2
Unsteady Bridges Friction Slope Method= 1
Parabolic Critical Depth
Global Vel Dist=  1 , 1 , 1
Global Log Level= 0
CheckData=True
Encroach Param= -1, 0, 0, 0
BEGIN DESCRIPTION:
Multiple Run
END DESCRIPTION:

--- UNT 012 in Running Cr Watershed.f01 (steady flow) ---

Flow Title=Multiple
Number of Profiles=7
Profile Names=10-year,25-year,50-year,1pct_min,100-year,1pct_plu,500-year
River Rch & RM= UNT 012 in Runni,Reach-1,3038
     280     357     416     241     481     960     646
Boundary for River Rch & Prof#=UNT 012 in Runni,Reach-1,1
Up Type=0
Dn Type=3
Dn Slope=0.005
Boundary for River Rch & Prof#=UNT 012 in Runni,Reach-1,2
Up Type=0
Dn Type=3
Dn Slope=0.005
Boundary for River Rch & Prof#=UNT 012 in Runni,Reach-1,3
Up Type=0
Dn Type=3
Dn Slope=0.005
Boundary for River Rch & Prof#=UNT 012 in Runni,Reach-1,4
Up Type=0
Dn Type=3
Dn Slope=0.005
Boundary for River Rch & Prof#=UNT 012 in Runni,Reach-1,5
Up Type=0
Dn Type=3
Dn Slope=0.005
Boundary for River Rch & Prof#=UNT 012 in Runni,Reach-1,6
Up Type=0
Dn Type=3
Dn Slope=0.005
Boundary for River Rch & Prof#=UNT 012 in Runni,Reach-1,7
Up Type=0
Dn Type=3
Dn Slope=0.005

--- UNT 012 in Running Cr Watershed.g01 (geometry) ---

Geom Title=Existing Conditions

River Reach=UNT 012 in Runni,Reach-1
Reach XY= 30
      2833834.48      7004344.84      2833816.19      7004383.86
      2833756.13      7004401.56      2833667.28      7004516.34
      2833619.15      7004543.12      2833621.23      7004609.23
      2833558.61      7004706.38      2833572.07      7004839.11
      2833471.05      7004932.28      2833484.91      7004995.28
      2833458.00      7005094.35      2833530.97      7005169.67
      2833347.41      7005373.03      2833313.02      7005455.57
      2833334.64      7005616.72      2833378.86      7005653.07
      2833377.87      7005714.98      2833351.34      7005750.35
      2833244.24      7005759.19      2833203.96      7005784.74
      2833220.66      7005852.54      2833189.22      7005998.94
      2833246.21      7006029.40      2833311.06      7006324.18
      2833333.66      7006355.62      2833386.72      7006354.64
      2833417.47      7006384.94      2833484.42      7006550.79
      2833482.69      7006639.45      2833385.59      7006870.71

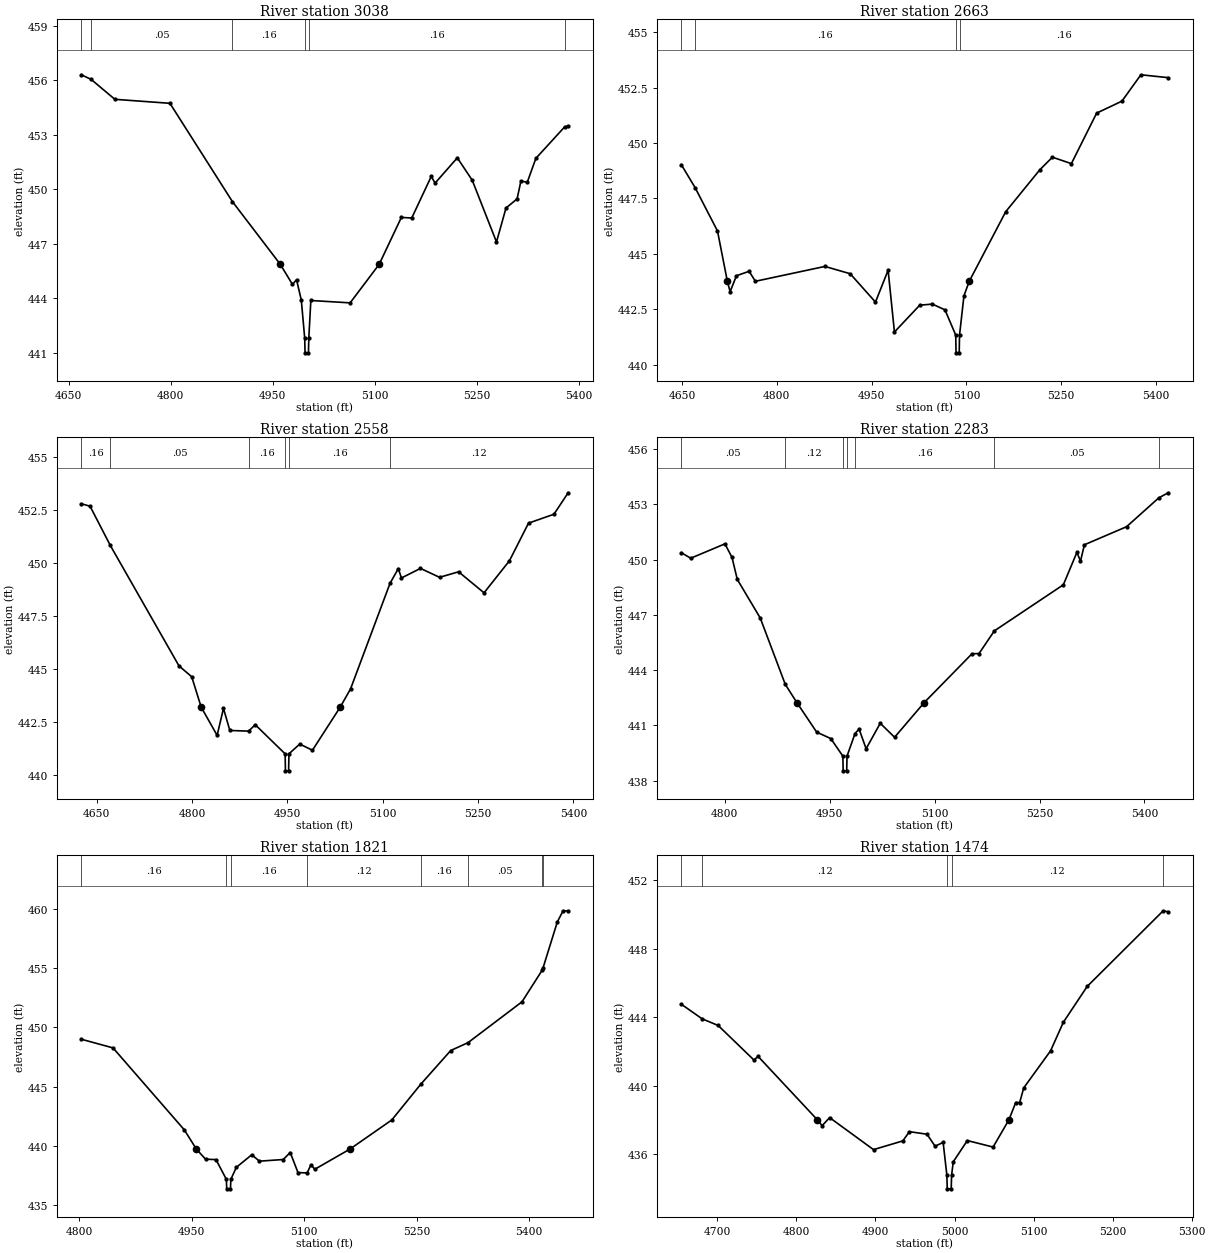
Type RM Length L Ch R = 1,3038,375,375,375
BEGIN DESCRIPTION:
UNT 012 in Running Cr Watershed 6.0
END DESCRIPTION:
XS GIS Cut Line= 3
      2833466.14      7004234.56      2833789.04      7004450.69
      2834078.09      7004604.33
#Sta/Elev= 30
  4668.8  456.31  4683.1  456.06  4718.1  454.96  4799.1  454.74  4891.0  449.33
  4961.4  445.88  4979.2  444.78  4985.3  445.03  4992.3  443.91  4997.3  441.81
  4997.8  441.01  5002.8  441.01  5003.3  441.81  5006.3  443.89  5064.1  443.76
  5106.8  445.88  5139.4  448.46  5154.7  448.43  5183.4  450.72  5189.0  450.35
  5221.7  451.74  5243.6  450.51  5279.3  447.11  5293.3  448.98  5309.6  449.48
  5315.2  450.46  5324.6  450.40  5337.2  451.71  5379.7  453.45  5384.7  453.48
#Mann=6,-1,0
  4668.8    0.16       0  4683.1    0.05       0  4891.0    0.16       0
  4997.3    0.07       0  5003.3    0.16       0  5379.7    0.05       0
Bank Sta=4961.4,5106.8
Exp/Cntr=0.3,0.1

Type RM Length L Ch R = 1,2663,105,105,105
BEGIN DESCRIPTION:
Mapping XS 88944dfc
END DESCRIPTION:
XS GIS Cut Line= 3
      2833207.83      7004711.89      2833722.12      7004718.40
      2833978.18      7004720.57
#Sta/Elev= 30
  4648.9  449.02  4670.6  447.99  4706.1  446.03  4721.7  443.76  4726.1  443.29
  4736.1  444.01  4756.1  444.21  4766.1  443.76  4876.1  444.43  4916.1  444.10
  4956.1  442.82  4976.1  444.26  4986.1  441.47  5026.1  442.68  5046.1  442.73
  5066.1  442.47  5083.1  441.33  5083.6  440.53  5088.6  440.53  5089.1  441.33
  5096.1  443.10  5104.5  443.76  5162.2  446.90  5216.1  448.79  5236.1  449.36
  5266.1  449.07  5306.1  451.35  5346.1  451.89  5376.1  453.08  5419.3  452.95
#Mann=4,-1,0
  4648.9    0.05       0  4670.6    0.16       0  5083.1    0.07       0
  5089.1    0.16       0
Bank Sta=4721.7,5104.5
Exp/Cntr=0.3,0.1

Type RM Length L Ch R = 1,2558,275,275,275
BEGIN DESCRIPTION:
Mapping XS 3cad48e3
END DESCRIPTION:
XS GIS Cut Line= 3
      2833201.28      7004816.06      2833750.33      7004820.40
      2833967.36      7004820.40
#Sta/Elev= 30
  4625.6  452.78  4639.3  452.67  4671.2  450.82  4779.3  445.15  4799.3  444.64
  4814.2  443.21  4839.3  441.88  4849.3  443.15  4859.3  442.11  4888.8  442.08
  4899.3  442.38  4946.3  441.01  4946.8  440.21  4951.8  440.21  4952.3  441.01
  4969.3  441.47  4989.3  441.18  5033.0  443.21  5049.3  444.07  5111.4  449.04
  5124.4  449.73  5129.4  449.29  5159.3  449.74  5189.3  449.32  5219.3  449.58
  5259.3  448.59  5299.3  450.10  5329.3  451.87  5369.3  452.29  5391.7  453.30
#Mann=6,-1,0
  4625.6    0.16       0  4671.2    0.05       0  4888.8    0.16       0
  4946.3    0.07       0  4952.3    0.16       0  5111.4    0.12       0
Bank Sta=4814.2,5033
Exp/Cntr=0.3,0.1

Type RM Length L Ch R = 1,2283,462,462,462
BEGIN DESCRIPTION:
UNT 012 in Running Cr Watershed 5.0
END DESCRIPTION:
XS GIS Cut Line= 3
      2833213.31      7005008.62      2833612.60      7005064.18
      2833904.25      7005091.95
#Sta/Elev= 30
  4737.8  450.37  4751.2  450.07  4800.1  450.85  4810.2  450.12  4817.8  448.92
  4850.6  446.83  4886.4  443.23  4903.0  442.24  4931.3  440.64  4951.5  440.29
  4968.7  439.34  4969.2  438.54  4974.2  438.54  4974.7  439.34  4986.1  440.56
  4991.9  440.81  5002.0  439.74  5022.2  441.12  5042.7  440.36  5085.0  442.24
  5153.4  444.89  5163.4  444.90  5185.3  446.13  5284.0  448.63  5303.4  450.39
  5308.5  449.91  5314.1  450.80  5374.4  451.78  5420.3  453.34  5433.9  453.62
#Mann=7,-1,0
  4737.8    0.05       0  4886.4    0.12       0  4968.7    0.07       0
  4974.7    0.12       0  4986.1    0.16       0  5185.3    0.05       0
  5420.3    0.16       0
Bank Sta=4903,5085
Exp/Cntr=0.3,0.1

Type RM Length L Ch R = 1,1821,347,347,347
BEGIN DESCRIPTION:
UNT 012 in Running Cr Watershed 4.0
END DESCRIPTION:
XS GIS Cut Line= 3
      2833143.88      7005348.91      2833480.65      7005428.76
      2833779.23      7005480.84
#Sta/Elev= 30
  4802.8  448.99  4845.1  448.26  4940.1  441.36  4956.3  439.73  4968.4  438.89
  4982.4  438.85  4996.2  437.19  4996.7  436.39  5001.7  436.39  5002.2  437.19
  5009.5  438.20  5030.1  439.26  5040.3  438.72  5072.0  438.86  5081.4  439.45
  5091.7  437.76  5103.9  437.73  5109.0  438.41  5114.2  438.04  5160.8  439.73
  5216.8  442.19  5255.3  445.19  5295.4  448.04  5318.4  448.70  5390.4  452.14
  5417.2  454.79  5418.5  455.00  5437.6  458.88  5444.9  459.77  5452.0  459.81
#Mann=8,-1,0
  4802.8    0.16       0  4996.2    0.07       0  5002.2    0.16       0
  5103.9    0.12       0  5255.3    0.16       0  5318.4    0.05       0
  5417.2    0.16       0  5418.5    0.05       0
Bank Sta=4956.3,5160.8
Exp/Cntr=0.3,0.1

Type RM Length L Ch R = 1,1474,330,330,330
BEGIN DESCRIPTION:
UNT 012 in Running Cr Watershed 3.0
END DESCRIPTION:
XS GIS Cut Line= 3
      2833040.56      7005641.43      2833459.82      7005727.37
      2833647.29      7005740.39
#Sta/Elev= 30
  4654.4  444.75  4680.7  443.90  4701.0  443.51  4746.3  441.49  4751.4  441.71
  4826.5  438.00  4832.5  437.66  4842.0  438.13  4897.5  436.26  4934.6  436.77
  4942.9  437.31  4965.2  437.16  4975.4  436.46  4985.6  436.68  4990.3  434.77
  4990.8  433.97  4995.8  433.97  4996.3  434.77  4998.4  435.55  5016.2  436.79
  5048.8  436.41  5068.8  438.00  5077.4  439.01  5082.4  439.01  5087.6  439.87
  5121.5  442.03  5137.7  443.70  5167.8  445.79  5264.0  450.21  5270.3  450.15
#Mann=5,-1,0
  4654.4    0.16       0  4680.7    0.12       0  4990.3    0.07       0
  4996.3    0.12       0  5264.0    0.16       0
Bank Sta=4826.5,5068.8
Exp/Cntr=0.3,0.1

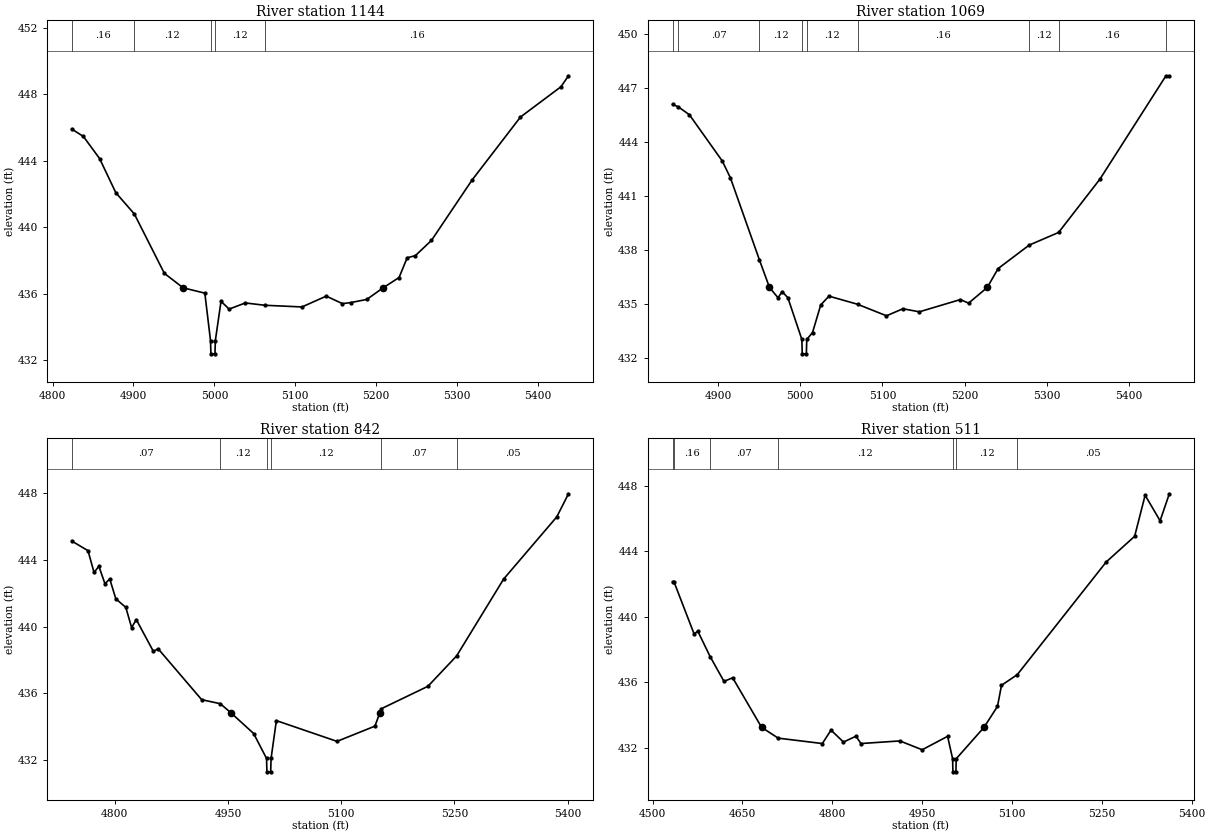
Type RM Length L Ch R = 1,1144,75,75,75
BEGIN DESCRIPTION:
Mapping XS 113bb7f2
END DESCRIPTION:
XS GIS Cut Line= 3
      2833040.52      7005900.29      2833294.02      7005903.76
      2833654.27      7005908.10
#Sta/Elev= 30
  4823.7  445.90  4838.2  445.45  4858.2  444.12  4878.2  442.07  4901.1  440.79
  4938.2  437.22  4961.4  436.35  4988.2  436.03  4995.2  433.18  4995.7  432.38
  5000.7  432.38  5001.2  433.18  5008.2  435.54  5018.2  435.07  5038.2  435.44
  5062.5  435.30  5108.2  435.20  5138.2  435.85  5158.2  435.40  5168.2  435.46
  5188.2  435.65  5208.5  436.35  5228.2  436.97  5238.2  438.16  5248.2  438.28
  5268.2  439.20  5318.2  442.82  5378.2  446.62  5428.2  448.44  5437.5  449.10
#Mann=5,-1,0
  4823.7    0.16       0  4901.1    0.12       0  4995.2    0.07       0
  5001.2    0.12       0  5062.5    0.16       0
Bank Sta=4961.4,5208.5
Exp/Cntr=0.3,0.1

Type RM Length L Ch R = 1,1069,227,227,227
BEGIN DESCRIPTION:
Mapping XS d096fa03
END DESCRIPTION:
XS GIS Cut Line= 3
      2833034.51      7005967.13      2833432.04      7005975.81
      2833639.52      7005975.81
#Sta/Elev= 30
  4844.3  446.08  4851.2  445.95  4864.8  445.51  4904.8  442.95  4914.8  442.01
  4950.2  437.45  4962.4  435.93  4972.8  435.36  4977.8  435.70  4984.8  435.36
  5001.8  433.05  5002.3  432.25  5007.3  432.25  5007.8  433.05  5014.8  433.43
  5024.8  434.96  5034.8  435.45  5069.6  435.00  5104.9  434.36  5124.9  434.75
  5144.9  434.58  5194.9  435.26  5204.9  435.06  5227.6  435.93  5240.9  436.98
  5278.7  438.28  5314.5  438.98  5364.9  441.94  5445.3  447.67  5449.4  447.67
#Mann=9,-1,0
  4844.3    0.12       0  4851.2    0.07       0  4950.2    0.12       0
  5001.8    0.07       0  5007.8    0.12       0  5069.6    0.16       0
  5278.7    0.12       0  5314.5    0.16       0  5445.3    0.05       0
Bank Sta=4962.4,5227.6
Exp/Cntr=0.3,0.1

Type RM Length L Ch R = 1,842,331,331,331
BEGIN DESCRIPTION:
UNT 012 in Running Cr Watershed 2.0
END DESCRIPTION:
XS GIS Cut Line= 3
      2833068.98      7006029.84      2833229.57      7006157.88
      2833680.48      7006121.03
#Sta/Elev= 30
  4743.2  445.11  4764.8  444.53  4772.8  443.23  4779.2  443.60  4787.2  442.56
  4793.6  442.84  4801.6  441.66  4814.9  441.14  4822.5  439.94  4828.8  440.41
  4851.3  438.52  4857.7  438.67  4915.3  435.63  4940.0  435.39  4954.7  434.82
  4984.1  433.61  5001.2  432.12  5001.7  431.32  5006.7  431.32  5007.2  432.12
  5014.2  434.38  5094.5  433.14  5144.7  434.05  5151.0  434.82  5153.2  435.09
  5214.9  436.43  5252.8  438.24  5315.2  442.84  5385.5  446.55  5401.0  447.93
#Mann=6,-1,0
  4743.2    0.07       0  4940.0    0.12       0  5001.2    0.07       0
  5007.2    0.12       0  5153.2    0.07       0  5252.8    0.05       0
Bank Sta=4954.7,5151
Exp/Cntr=0.3,0.1

Type RM Length L Ch R = 1,511,0,0,0
BEGIN DESCRIPTION:
UNT 012 in Running Cr Watershed 1.0
END DESCRIPTION:
XS GIS Cut Line= 3
      2833097.20      7006142.71      2833312.03      7006424.81
      2833774.28      7006316.30
#Sta/Elev= 30
  4533.2  442.15  4535.5  442.15  4569.2  438.95  4575.4  439.12  4595.9  437.57
  4619.1  436.05  4633.6  436.27  4681.9  433.24  4709.6  432.58  4783.3  432.25
  4797.8  433.07  4818.6  432.34  4839.5  432.70  4847.7  432.25  4912.7  432.41
  4950.0  431.87  4992.4  432.69  5000.8  431.32  5001.3  430.52  5006.3  430.52
  5006.8  431.32  5053.2  433.24  5075.7  434.52  5082.4  435.81  5108.7  436.46
  5257.2  443.35  5304.7  444.92  5322.2  447.43  5347.2  445.87  5362.6  447.52
#Mann=7,-1,0
  4533.2    0.07       0  4535.5    0.16       0  4595.9    0.07       0
  4709.6    0.12       0  5000.8    0.07       0  5006.8    0.12       0
  5108.7    0.05       0
Bank Sta=4681.9,5053.2
Exp/Cntr=0.3,0.1

Chan Stop Cuts=-1