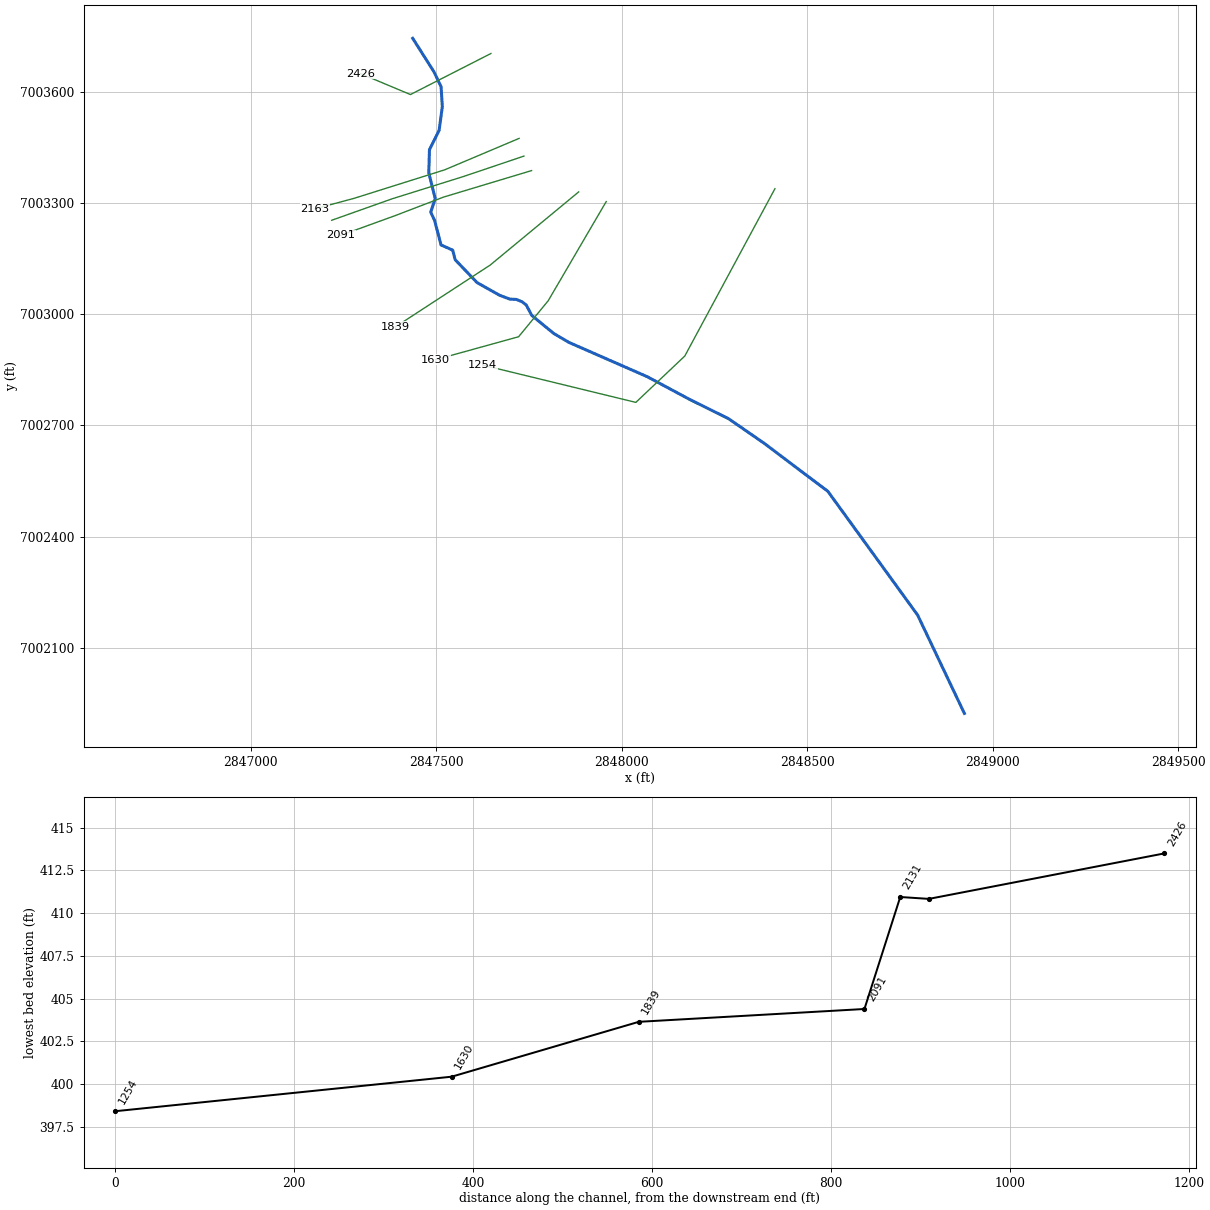
--- UNT 013 in Running Cr Watershed.prj (project) ---

Proj Title=UNT 013 in Running Cr Watershed Base Level Engineering
Current Plan=p01
Default Exp/Contr=0.3,0.1
English Units
Geom File=g01
Flow File=f01
Plan File=p01
BEGIN DESCRIPTION:
UNT 013 in Running Cr Watershed
END DESCRIPTION:

--- UNT 013 in Running Cr Watershed.p01 (plan) ---

Plan Title=Multiple Run
Short Identifier=Multiple
Geom File=g01
Flow File=f01
Subcritical Flow
K Sum by GR= 0
Std Step Tol= 0.01
Critical Tol= 0.01
Num of Std Step Trials= 20
Max Error Tol= 0.3
Flow Tol Ratio= 0.001
Split Flow NTrial= 30
Split Flow Tol= 0.02
Split Flow Ratio= 0.02
Log Output Level= 0
Friction Slope Method= 1
Unsteady Friction Slope Method= 2
Unsteady Bridges Friction Slope Method= 1
Parabolic Critical Depth
Global Vel Dist=  1 , 1 , 1
Global Log Level= 0
CheckData=True
Encroach Param= -1, 0, 0, 0
BEGIN DESCRIPTION:
Multiple Run
END DESCRIPTION:

--- UNT 013 in Running Cr Watershed.f01 (steady flow) ---

Flow Title=Multiple
Number of Profiles=7
Profile Names=10-year,25-year,50-year,1pct_min,100-year,1pct_plu,500-year
River Rch & RM= UNT 013 in Runni,Reach-1,2426
     156     192     218     124     248     495     319
Boundary for River Rch & Prof#=UNT 013 in Runni,Reach-1,1
Up Type=0
Dn Type=3
Dn Slope=0.005
Boundary for River Rch & Prof#=UNT 013 in Runni,Reach-1,2
Up Type=0
Dn Type=3
Dn Slope=0.005
Boundary for River Rch & Prof#=UNT 013 in Runni,Reach-1,3
Up Type=0
Dn Type=3
Dn Slope=0.005
Boundary for River Rch & Prof#=UNT 013 in Runni,Reach-1,4
Up Type=0
Dn Type=3
Dn Slope=0.005
Boundary for River Rch & Prof#=UNT 013 in Runni,Reach-1,5
Up Type=0
Dn Type=3
Dn Slope=0.005
Boundary for River Rch & Prof#=UNT 013 in Runni,Reach-1,6
Up Type=0
Dn Type=3
Dn Slope=0.005
Boundary for River Rch & Prof#=UNT 013 in Runni,Reach-1,7
Up Type=0
Dn Type=3
Dn Slope=0.005

--- UNT 013 in Running Cr Watershed.g01 (geometry) ---

Geom Title=Existing Conditions

River Reach=UNT 013 in Runni,Reach-1
Reach XY= 29
      2847436.91      7003743.78      2847494.20      7003653.50
      2847513.30      7003613.57      2847516.77      7003559.75
      2847508.09      7003495.51      2847482.05      7003443.43
      2847480.31      7003380.93      2847497.67      7003311.49
      2847485.52      7003275.03      2847495.94      7003252.46
      2847513.30      7003186.49      2847544.55      7003172.60
      2847551.49      7003146.56      2847610.29      7003085.04
      2847670.62      7003051.08      2847698.31      7003040.53
      2847716.44      7003039.54      2847731.61      7003033.28
      2847742.82      7003024.71      2847758.00      7002996.25
      2847817.40      7002947.54      2847857.79      7002923.78
      2848069.23      7002831.12      2848184.46      7002769.35
      2848287.81      7002718.27      2848384.03      7002651.75
      2848556.03      7002522.03      2848798.04      7002188.22
      2848924.04      7001923.10

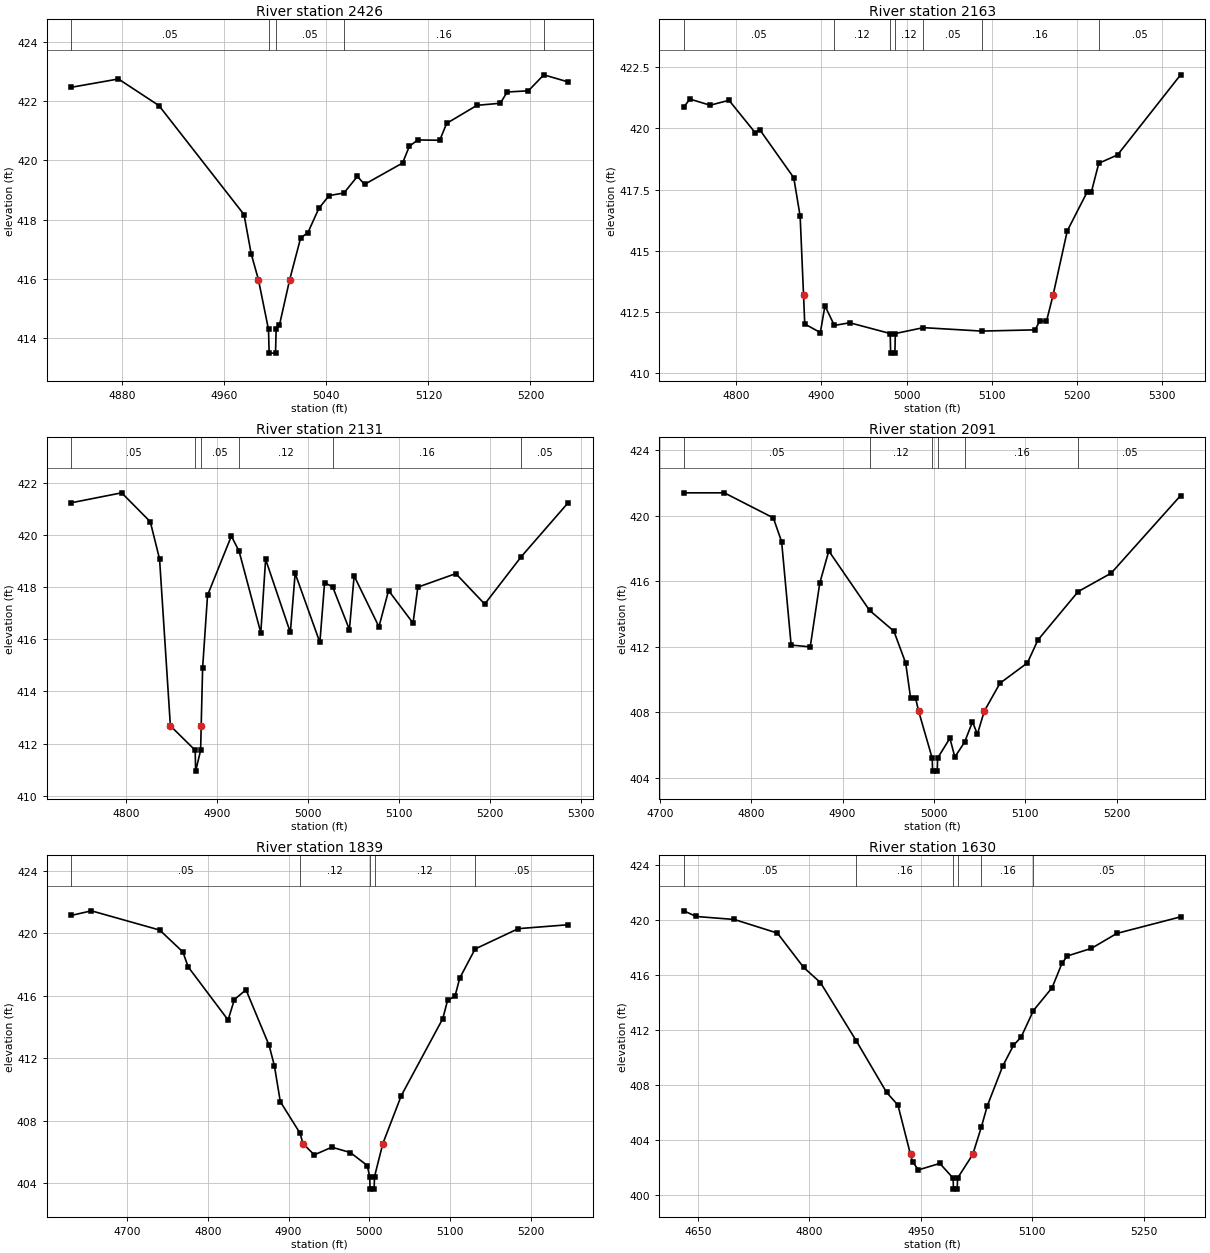
Type RM Length L Ch R = 1,2426,263,263,263
BEGIN DESCRIPTION:
UNT 013 in Running Cr Watershed 3.0
END DESCRIPTION:
XS GIS Cut Line= 3
      2847647.78      7003702.86      2847430.75      7003592.17
      2847296.23      7003648.58
#Sta/Elev= 30
  4840.1  422.47  4876.9  422.75  4908.7  421.85  4975.4  418.17  4981.0  416.85
  4986.7  415.97  4994.6  414.29  4995.1  413.49  5000.1  413.49  5000.6  414.29
  5003.2  414.44  5011.2  415.97  5019.8  417.38  5025.5  417.56  5034.1  418.38
  5042.1  418.81  5053.8  418.90  5064.3  419.46  5069.9  419.19  5099.7  419.91
  5105.1  420.48  5111.7  420.69  5128.9  420.68  5134.3  421.25  5158.1  421.86
  5176.4  421.93  5181.8  422.31  5198.4  422.35  5210.5  422.89  5229.6  422.65
#Mann=5,-1,0
  4840.1    0.05       0  4994.6    0.03       0  5000.6    0.05       0
  5053.8    0.16       0  5210.5    0.05       0
Bank Sta=4986.7,5011.2
Exp/Cntr=0.3,0.1

Type RM Length L Ch R = 1,2163,32,32,32
BEGIN DESCRIPTION:
Mapping XS 073911c0
END DESCRIPTION:
XS GIS Cut Line= 4
      2847723.74      7003473.91      2847523.39      7003389.21
      2847278.84      7003312.22      2847173.56      7003284.00
#Sta/Elev= 30
  4738.6  420.88  4745.6  421.20  4769.3  420.95  4791.5  421.15  4822.2  419.83
  4827.6  419.95  4867.5  417.99  4875.0  416.42  4879.0  413.19  4880.4  412.02
  4898.7  411.67  4904.1  412.76  4915.2  411.96  4933.2  412.07  4980.7  411.63
  4981.2  410.83  4986.2  410.83  4986.7  411.63  5019.6  411.87  5088.0  411.73
  5150.8  411.78  5156.1  412.14  5164.1  412.13  5171.8  413.19  5188.5  415.82
  5211.9  417.41  5216.8  417.41  5225.5  418.58  5247.5  418.92  5321.5  422.19
#Mann=7,-1,0
  4738.6    0.05       0  4915.2    0.12       0  4980.7    0.07       0
  4986.7    0.12       0  5019.6    0.05       0  5088.0    0.16       0
  5225.5    0.05       0
Bank Sta=4879,5171.8
Exp/Cntr=0.3,0.1

Type RM Length L Ch R = 1,2131,40,40,40
BEGIN DESCRIPTION:
Mapping XS 968d25ec
END DESCRIPTION:
XS GIS Cut Line= 4
      2847736.79      7003426.17      2847572.90      7003370.82
      2847381.93      7003311.14      2847218.50      7003253.08
#Sta/Elev= 30
  4739.5  421.24  4794.7  421.62  4826.2  420.51  4836.4  419.08  4848.3  412.68
  4875.6  411.74  4876.1  410.94  4881.6  411.74  4882.2  412.68  4883.8  414.91
  4889.2  417.69  4915.4  419.96  4923.9  419.38  4947.8  416.25  4953.1  419.07
  4980.3  416.26  4985.6  418.53  5012.8  415.88  5018.0  418.17  5026.9  418.01
  5045.3  416.37  5050.5  418.43  5077.8  416.48  5088.4  417.87  5115.3  416.62
  5120.6  418.00  5162.4  418.52  5194.2  417.35  5234.4  419.17  5286.0  421.24
#Mann=6,-1,0
  4739.5    0.05       0  4875.6    0.07       0  4881.6    0.05       0
  4923.9    0.12       0  5026.9    0.16       0  5234.4    0.05       0
Bank Sta=4848.3,4882.2
Exp/Cntr=0.3,0.1

Type RM Length L Ch R = 1,2091,252,252,252
BEGIN DESCRIPTION:
Mapping XS a2aee0b9
END DESCRIPTION:
XS GIS Cut Line= 4
      2847757.32      7003387.08      2847519.73      7003315.48
      2847389.52      7003265.56      2847243.07      7003212.41
#Sta/Elev= 30
  4726.4  421.39  4770.6  421.39  4824.2  419.86  4833.3  418.40  4843.7  412.09
  4864.6  411.98  4875.0  415.87  4884.9  417.84  4929.5  414.21  4956.1  412.94
  4969.0  411.00  4974.4  408.86  4979.8  408.86  4983.2  408.05  4998.0  405.19
  4998.5  404.39  5003.5  404.39  5004.0  405.19  5017.4  406.40  5022.8  405.25
  5033.5  406.16  5042.1  407.40  5047.5  406.65  5055.0  408.05  5072.2  409.76
  5102.2  411.00  5113.7  412.40  5157.8  415.36  5193.8  416.48  5269.8  421.22
#Mann=6,-1,0
  4726.4    0.05       0  4929.5    0.12       0  4998.0    0.07       0
  5004.0    0.12       0  5033.5    0.16       0  5157.8    0.05       0
Bank Sta=4983.2,5055
Exp/Cntr=0.3,0.1

Type RM Length L Ch R = 1,1839,209,209,209
BEGIN DESCRIPTION:
UNT 013 in Running Cr Watershed 2.0
END DESCRIPTION:
XS GIS Cut Line= 3
      2847884.34      7003329.61      2847645.60      7003132.10
      2847389.80      7002965.18
#Sta/Elev= 30
  4631.1  421.14  4655.8  421.43  4740.4  420.20  4769.1  418.80  4775.6  417.85
  4825.1  414.45  4832.9  415.76  4847.3  416.38  4875.9  412.83  4882.4  411.54
  4889.8  409.23  4914.3  407.21  4917.8  406.55  4931.9  405.83  4953.6  406.32
  4976.5  405.98  4997.5  405.15  5000.5  404.44  5001.0  403.64  5006.0  403.64
  5006.5  404.44  5016.8  406.55  5039.7  409.62  5091.1  414.54  5097.0  415.71
  5106.2  415.97  5112.1  417.13  5131.1  418.99  5184.6  420.29  5246.4  420.54
#Mann=5,-1,0
  4631.1    0.05       0  4914.3    0.12       0  5000.5    0.07       0
  5006.5    0.12       0  5131.1    0.05       0
Bank Sta=4917.8,5016.8
Exp/Cntr=0.3,0.1

Type RM Length L Ch R = 1,1630,376,376,376
BEGIN DESCRIPTION:
Mapping XS e51abb65
END DESCRIPTION:
XS GIS Cut Line= 4
      2847958.52      7003303.52      2847802.28      7003036.18
      2847722.42      7002938.96      2847498.41      7002876.92
#Sta/Elev= 30
  4631.4  420.67  4647.7  420.26  4699.2  420.04  4757.1  419.05  4792.3  416.56
  4815.0  415.45  4863.0  411.23  4903.9  407.47  4919.2  406.54  4936.1  402.95
  4938.8  402.42  4946.8  401.83  4975.5  402.30  4993.4  401.23  4993.9  400.43
  4998.9  400.43  4999.4  401.23  5019.8  402.95  5031.4  404.95  5039.4  406.49
  5060.2  409.39  5074.6  410.89  5084.9  411.49  5101.4  413.42  5126.4  415.07
  5140.0  416.88  5147.2  417.39  5179.4  417.94  5213.7  419.03  5299.3  420.23
#Mann=6,-1,0
  4631.4    0.05       0  4863.0    0.16       0  4993.4    0.07       0
  4999.4    0.16       0  5031.4    0.16       0  5101.4    0.05       0
Bank Sta=4936.1,5019.8
Exp/Cntr=0.3,0.1

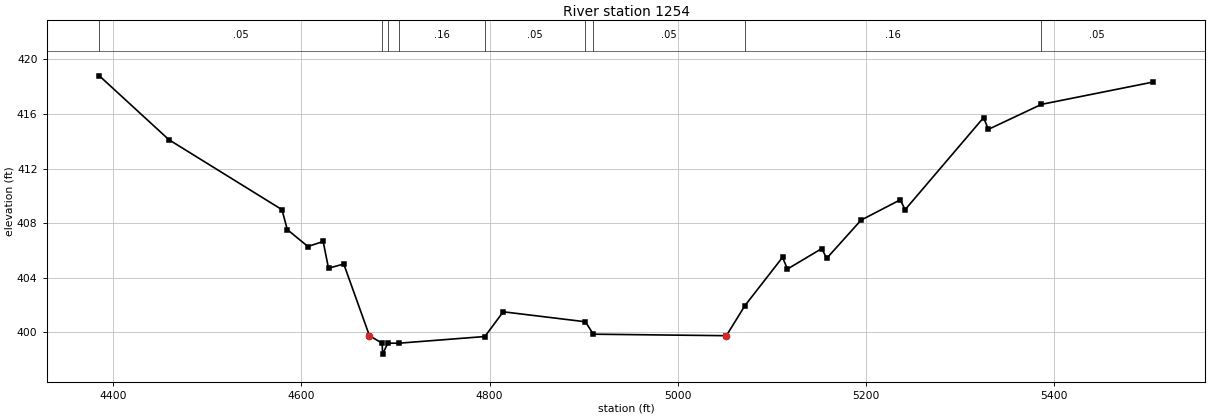
Type RM Length L Ch R = 1,1254,0,0,0
BEGIN DESCRIPTION:
Mapping XS 4fb102c2
END DESCRIPTION:
XS GIS Cut Line= 4
      2848413.41      7003338.30      2848170.34      7002886.88
      2848038.39      7002761.88      2847625.24      7002862.56
#Sta/Elev= 30
  4385.2  418.79  4459.2  414.11  4579.3  408.99  4585.0  407.53  4606.9  406.29
  4623.1  406.66  4628.8  404.70  4645.0  405.01  4672.3  399.76  4685.8  399.21
  4686.3  398.41  4691.8  399.21  4703.5  399.21  4795.0  399.70  4814.5  401.51
  4901.8  400.78  4910.3  399.87  5051.7  399.76  5071.4  401.96  5111.4  405.50
  5116.6  404.64  5153.1  406.14  5158.3  405.42  5194.8  408.22  5236.5  409.71
  5241.7  408.99  5325.1  415.73  5330.2  414.87  5386.6  416.70  5504.9  418.33
#Mann=9,-1,0
  4385.2    0.05       0  4685.8   0.033       0  4691.8    0.05       0
  4703.5    0.16       0  4795.0    0.05       0  4901.8    0.16       0
  4910.3    0.05       0  5071.4    0.16       0  5386.6    0.05       0
Bank Sta=4672.3,5051.7
Exp/Cntr=0.3,0.1

Chan Stop Cuts=-1