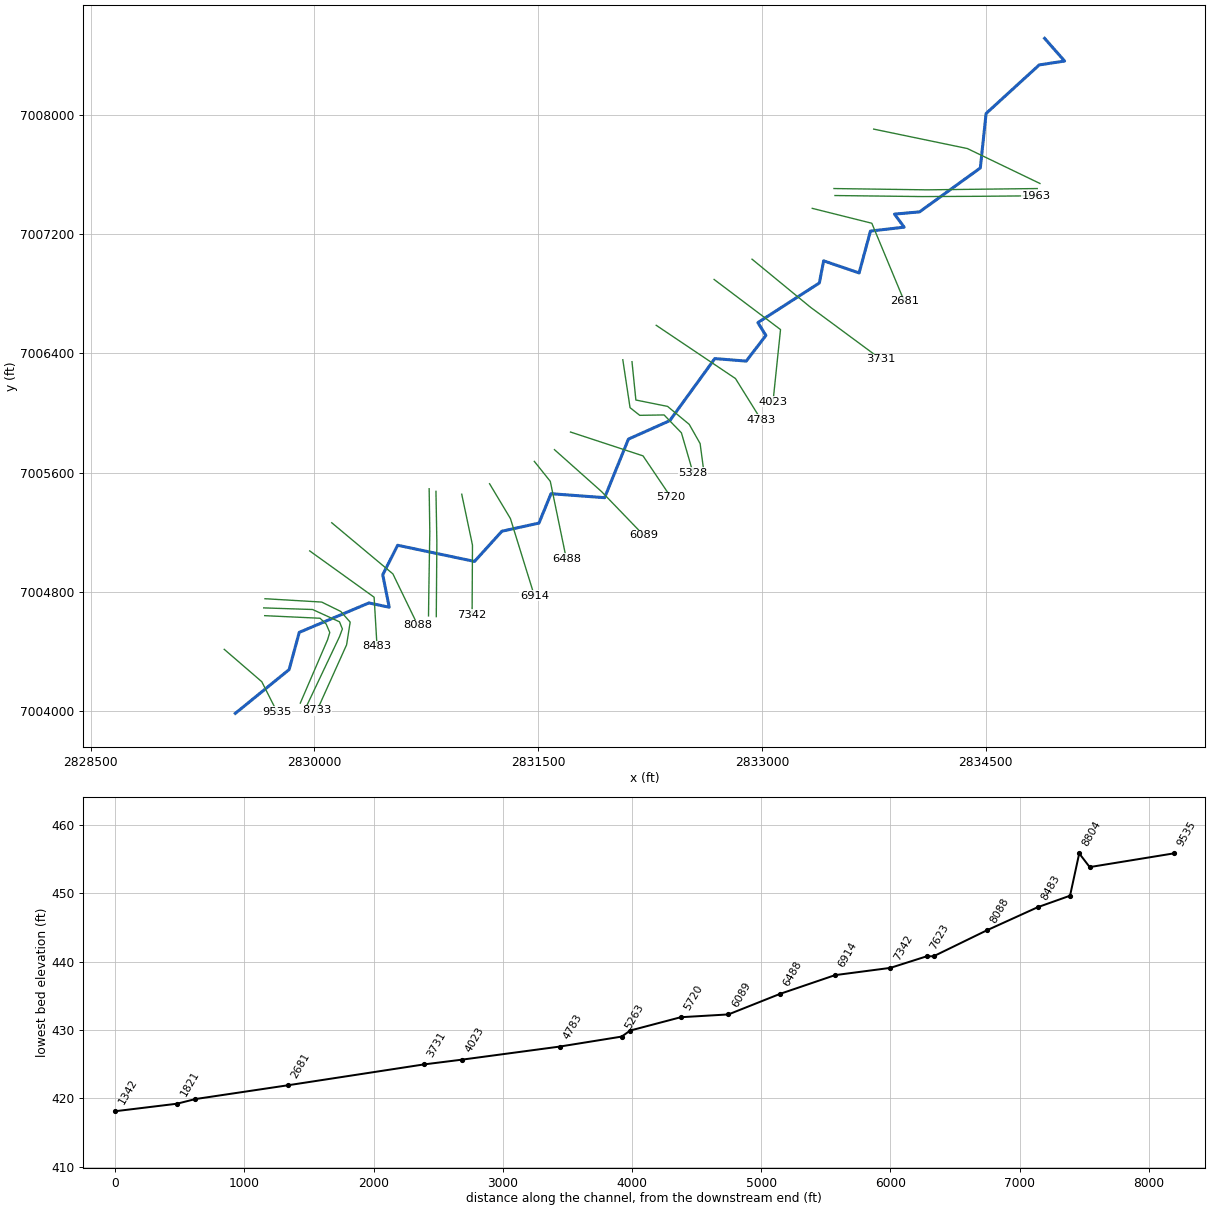
--- UNT 014 in Running Cr Watershed.prj (project) ---

Proj Title=UNT 014 in Running Cr Watershed Base Level Engineering
Current Plan=p01
Default Exp/Contr=0.3,0.1
English Units
Geom File=g01
Flow File=f01
Plan File=p01
BEGIN DESCRIPTION:
UNT 014 in Running Cr Watershed
END DESCRIPTION:

--- UNT 014 in Running Cr Watershed.p01 (plan) ---

Plan Title=Multiple Run
Short Identifier=Multiple
Geom File=g01
Flow File=f01
Subcritical Flow
K Sum by GR= 0
Std Step Tol= 0.01
Critical Tol= 0.01
Num of Std Step Trials= 20
Max Error Tol= 0.3
Flow Tol Ratio= 0.001
Split Flow NTrial= 30
Split Flow Tol= 0.02
Split Flow Ratio= 0.02
Log Output Level= 0
Friction Slope Method= 1
Unsteady Friction Slope Method= 2
Unsteady Bridges Friction Slope Method= 1
Parabolic Critical Depth
Global Vel Dist=  1 , 1 , 1
Global Log Level= 0
CheckData=True
Encroach Param= -1, 0, 0, 0
BEGIN DESCRIPTION:
Multiple Run
END DESCRIPTION:

--- UNT 014 in Running Cr Watershed.f01 (steady flow) ---

Flow Title=Multiple
Number of Profiles=7
Profile Names=10-year,25-year,50-year,1pct_min,100-year,1pct_plu,500-year
River Rch & RM= UNT 014 in Runni,Reach-1,9535
     370     479     566     332     663    1323     911
River Rch & RM= UNT 014 in Runni,Reach-1,5328
     704     945    1140     683    1363    2720    1951
River Rch & RM= UNT 014 in Runni,Reach-1,2681
     872    1182    1435     865    1725    3442    2498
Boundary for River Rch & Prof#=UNT 014 in Runni,Reach-1,1
Up Type=0
Dn Type=3
Dn Slope=0.005
Boundary for River Rch & Prof#=UNT 014 in Runni,Reach-1,2
Up Type=0
Dn Type=3
Dn Slope=0.005
Boundary for River Rch & Prof#=UNT 014 in Runni,Reach-1,3
Up Type=0
Dn Type=3
Dn Slope=0.005
Boundary for River Rch & Prof#=UNT 014 in Runni,Reach-1,4
Up Type=0
Dn Type=3
Dn Slope=0.005
Boundary for River Rch & Prof#=UNT 014 in Runni,Reach-1,5
Up Type=0
Dn Type=3
Dn Slope=0.005
Boundary for River Rch & Prof#=UNT 014 in Runni,Reach-1,6
Up Type=0
Dn Type=3
Dn Slope=0.005
Boundary for River Rch & Prof#=UNT 014 in Runni,Reach-1,7
Up Type=0
Dn Type=3
Dn Slope=0.005

--- UNT 014 in Running Cr Watershed.g01 (geometry) ---

Geom Title=Existing Conditions

River Reach=UNT 014 in Runni,Reach-1
Reach XY= 30
      2829470.59      7003985.71      2829831.37      7004279.19
      2829899.34      7004528.72      2830366.33      7004726.02
      2830502.39      7004697.12      2830458.86      7004914.96
      2830558.96      7005112.62      2831074.20      7005004.25
      2831257.67      7005206.75      2831506.16      7005261.17
      2831586.78      7005458.21      2831946.14      7005431.58
      2832105.80      7005824.09      2832383.03      7005947.97
      2832684.64      7006363.84      2832895.70      7006347.24
      2833027.28      7006519.09      2832973.55      7006605.16
      2833385.59      7006870.71      2833414.47      7007019.12
      2833652.19      7006938.08      2833728.20      7007218.66
      2833953.90      7007244.86      2833889.53      7007332.38
      2834057.22      7007347.41      2834464.75      7007641.81
      2834503.39      7008006.96      2834859.54      7008332.57
      2835029.65      7008358.38      2834895.59      7008510.71

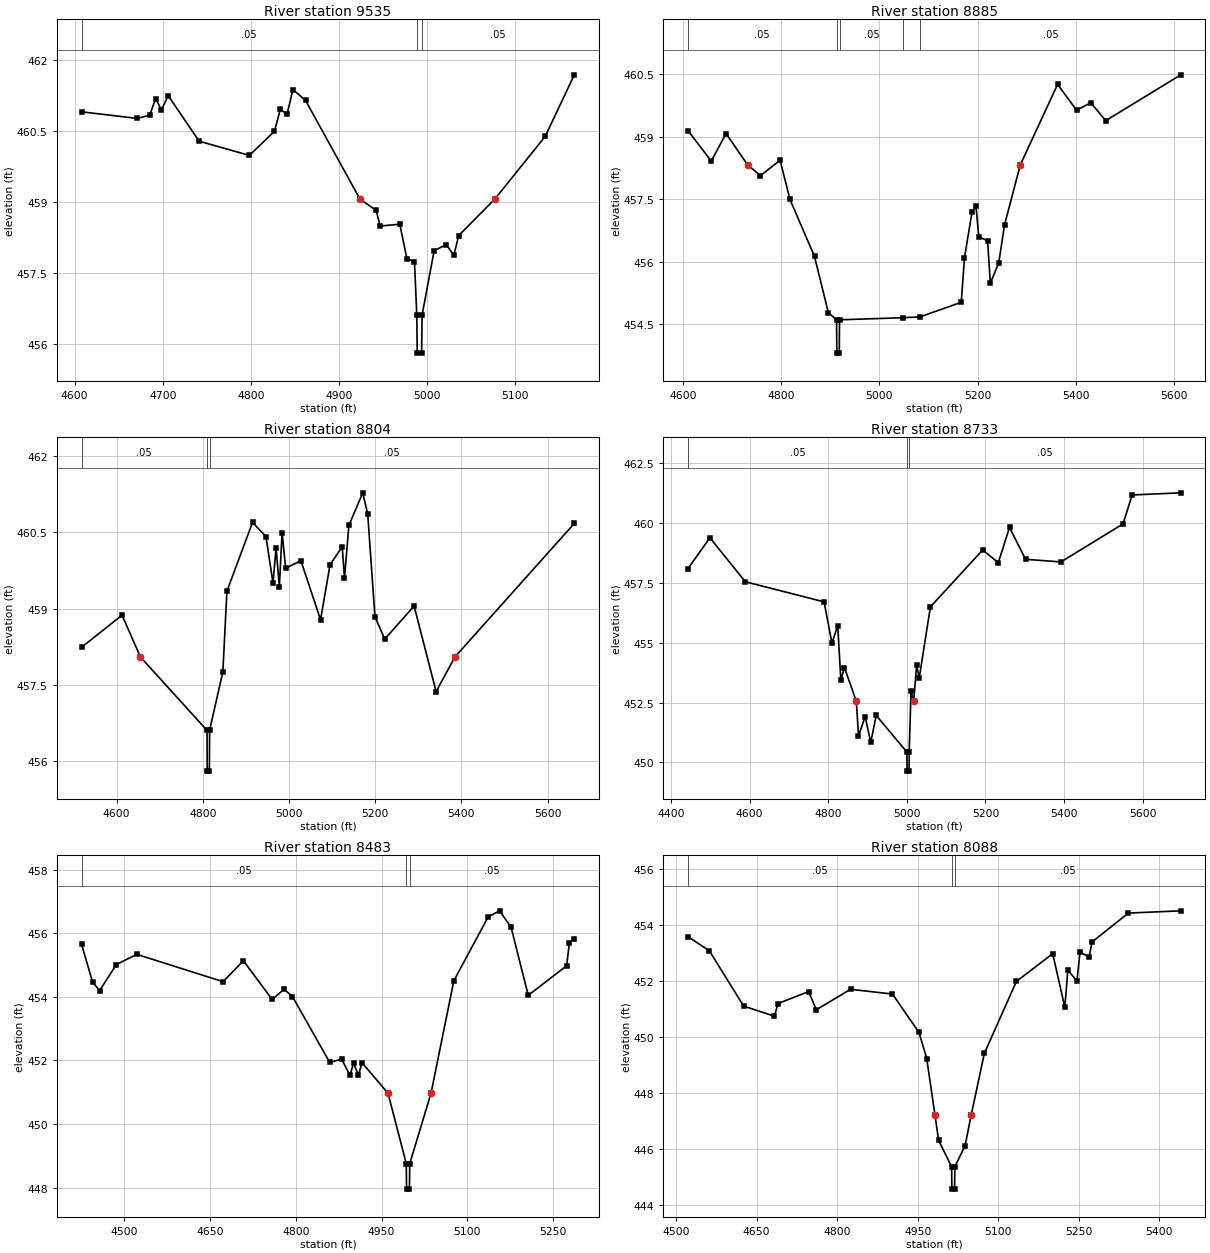
Type RM Length L Ch R = 1,9535,650,650,650
BEGIN DESCRIPTION:
UNT 014 in Running Cr Watershed 16.0
END DESCRIPTION:
XS GIS Cut Line= 3
      2829396.39      7004415.01      2829648.11      7004198.00
      2829750.49      7003995.45
#Sta/Elev= 30
  4607.9  460.90  4671.2  460.76  4685.3  460.83  4692.0  461.18  4698.6  460.94
  4706.3  461.24  4741.4  460.28  4798.4  459.98  4826.9  460.49  4833.5  460.95
  4841.2  460.85  4847.8  461.37  4862.1  461.14  4923.9  459.06  4942.3  458.82
  4946.8  458.49  4969.1  458.53  4977.2  457.80  4985.8  457.74  4988.4  456.61
  4988.9  455.81  4993.9  455.81  4994.4  456.61  5008.1  457.97  5022.0  458.10
  5030.4  457.87  5036.0  458.29  5077.0  459.06  5134.1  460.38  5167.2  461.68
#Mann=3,-1,0
  4607.9    0.05       0  4988.4    0.03       0  4994.4    0.05       0
Bank Sta=4923.9,5077
Exp/Cntr=0.3,0.1

Type RM Length L Ch R = 1,8885,81,81,81
BEGIN DESCRIPTION:
Mapping XS 23a7ffb2
END DESCRIPTION:
XS GIS Cut Line= 6
      2829667.68      7004640.71      2830038.74      7004623.35
      2830079.97      7004584.29      2830103.84      7004527.86
      2830088.65      7004477.95      2829906.34      7004054.73
#Sta/Elev= 30
  4610.7  459.15  4658.0  458.42  4688.1  459.08  4731.9  458.33  4758.1  458.07
  4798.1  458.44  4818.1  457.50  4868.1  456.13  4896.3  454.78  4913.0  454.61
  4913.5  453.81  4918.5  453.81  4919.0  454.61  5049.1  454.66  5082.8  454.68
  5166.7  455.03  5173.3  456.10  5188.5  457.19  5196.8  457.33  5202.3  456.60
  5220.3  456.51  5225.8  455.49  5242.9  455.97  5254.8  456.89  5286.9  458.33
  5362.7  460.26  5401.4  459.64  5430.3  459.82  5460.7  459.39  5613.4  460.49
#Mann=5,-1,0
  4610.7    0.05       0  4913.0    0.03       0  4919.0    0.05       0
  5049.1    0.07       0  5082.8    0.05       0
Bank Sta=4731.9,5286.9
Exp/Cntr=0.3,0.1

Type RM Length L Ch R = 1,8804,71,71,71
BEGIN DESCRIPTION:
Mapping XS 2c8ea721
END DESCRIPTION:
XS GIS Cut Line= 6
      2829661.09      7004692.79      2829988.83      7004681.94
      2830168.95      7004599.48      2830188.48      7004551.73
      2830168.95      7004499.65      2829951.94      7004041.77
#Sta/Elev= 30
  4518.7  458.24  4612.7  458.87  4655.2  458.05  4809.8  456.61  4810.3  455.81
  4815.3  455.81  4815.8  456.61  4846.6  457.76  4856.0  459.34  4915.4  460.69
  4946.6  460.41  4963.0  459.50  4970.0  460.19  4977.7  459.43  4984.0  460.49
  4992.3  459.79  5027.6  459.94  5073.3  458.78  5095.3  459.86  5123.5  460.21
  5128.8  459.60  5139.0  460.63  5171.2  461.27  5182.7  460.85  5199.5  458.84
  5222.2  458.40  5290.4  459.05  5341.4  457.37  5385.1  458.05  5662.1  460.67
#Mann=3,-1,0
  4518.7    0.05       0  4809.8    0.03       0  4815.8    0.05       0
Bank Sta=4655.2,5385.1
Exp/Cntr=0.3,0.1

Type RM Length L Ch R = 1,8733,250,250,250
BEGIN DESCRIPTION:
UNT 014 in Running Cr Watershed 15.0
END DESCRIPTION:
XS GIS Cut Line= 6
      2829669.50      7004754.28      2830049.59      7004731.86
      2830177.63      7004668.92      2830240.56      7004597.31
      2830216.69      7004445.40      2830019.22      7004007.06
#Sta/Elev= 30
  4443.5  458.10  4499.1  459.39  4589.3  457.55  4789.6  456.71  4809.6  454.98
  4824.3  455.72  4832.2  453.44  4841.4  453.96  4871.6  452.55  4877.1  451.10
  4894.0  451.91  4908.3  450.83  4922.1  451.96  5000.1  450.43  5000.6  449.63
  5005.6  449.63  5006.1  450.43  5010.7  452.98  5017.4  452.55  5024.9  454.05
  5031.6  453.53  5060.0  456.50  5192.9  458.88  5232.6  458.35  5261.2  459.82
  5302.0  458.49  5392.0  458.38  5549.9  459.97  5573.1  461.18  5696.8  461.27
#Mann=3,-1,0
  4443.5    0.05       0  5000.1    0.03       0  5006.1    0.05       0
Bank Sta=4871.6,5017.4
Exp/Cntr=0.3,0.1

Type RM Length L Ch R = 1,8483,395,395,395
BEGIN DESCRIPTION:
UNT 014 in Running Cr Watershed 14.0
END DESCRIPTION:
XS GIS Cut Line= 3
      2829969.31      7005074.72      2830401.15      7004764.41
      2830420.68      7004434.56
#Sta/Elev= 30
  4425.1  455.66  4444.3  454.47  4456.7  454.20  4486.1  455.02  4521.7  455.34
  4672.7  454.48  4708.3  455.14  4758.6  453.92  4779.5  454.24  4794.2  454.01
  4859.3  451.94  4880.2  452.04  4894.9  451.53  4901.0  451.92  4909.6  451.53
  4915.8  451.93  4961.3  450.97  4993.3  448.75  4993.8  447.95  4998.8  447.95
  4999.3  448.75  5036.6  450.97  5076.5  454.51  5136.6  456.52  5156.6  456.71
  5176.7  456.19  5206.7  454.05  5273.8  454.98  5278.8  455.71  5287.3  455.83
#Mann=3,-1,0
  4425.1    0.05       0  4993.3    0.03       0  4999.3    0.05       0
Bank Sta=4961.3,5036.6
Exp/Cntr=0.3,0.1

Type RM Length L Ch R = 1,8088,411,411,411
BEGIN DESCRIPTION:
UNT 014 in Running Cr Watershed 13.0
END DESCRIPTION:
XS GIS Cut Line= 3
      2830116.86      7005263.54      2830527.02      7004920.66
      2830694.13      7004575.59
#Sta/Elev= 30
  4522.1  453.57  4562.0  453.06  4625.8  451.09  4683.1  450.73  4689.6  451.18
  4746.8  451.61  4761.1  450.96  4824.9  451.69  4903.0  451.52  4952.4  450.15
  4966.8  449.22  4982.2  447.20  4988.9  446.30  5013.2  445.36  5013.7  444.56
  5018.7  444.56  5019.2  445.36  5038.3  446.11  5049.6  447.20  5074.1  449.40
  5133.8  451.97  5201.5  452.96  5224.1  451.05  5229.7  452.38  5246.7  451.98
  5252.3  453.02  5269.3  452.84  5274.8  453.38  5342.6  454.41  5440.1  454.49
#Mann=3,-1,0
  4522.1    0.05       0  5013.2    0.03       0  5019.2    0.05       0
Bank Sta=4982.2,5049.6
Exp/Cntr=0.3,0.1

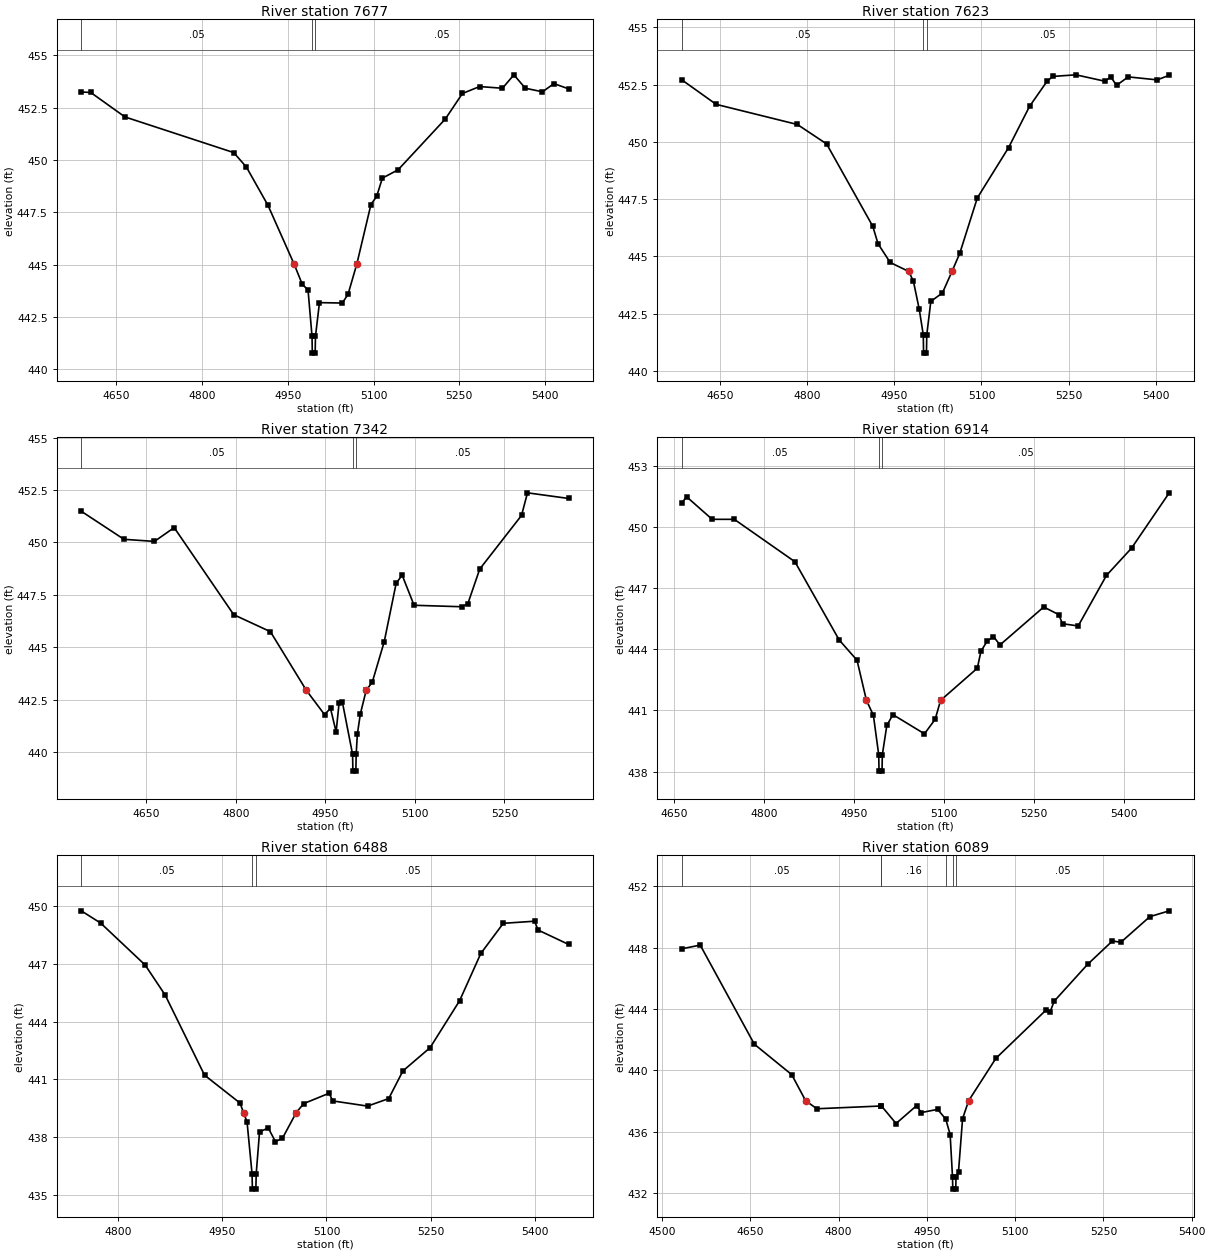
Type RM Length L Ch R = 1,7677,54,54,54
BEGIN DESCRIPTION:
Mapping XS 0be74bad
END DESCRIPTION:
XS GIS Cut Line= 4
      2830770.08      7005491.43      2830774.42      7005202.78
      2830767.91      7004807.81      2830765.75      7004639.23
#Sta/Elev= 30
  4589.0  453.24  4605.4  453.22  4665.4  452.05  4855.5  450.35  4877.7  449.66
  4915.5  447.83  4961.0  445.04  4975.5  444.06  4985.5  443.80  4992.5  441.58
  4993.0  440.78  4998.0  440.78  4998.5  441.58  5005.5  443.19  5045.5  443.17
  5055.5  443.59  5070.9  445.04  5095.5  447.87  5105.5  448.26  5115.5  449.13
  5143.1  449.53  5225.5  451.95  5255.5  453.17  5285.5  453.50  5325.5  453.42
  5345.5  454.06  5365.5  453.42  5395.5  453.25  5415.5  453.64  5441.3  453.39
#Mann=3,-1,0
  4589.0    0.05       0  4992.5    0.03       0  4998.5    0.05       0
Bank Sta=4961,5070.9
Exp/Cntr=0.3,0.1

Type RM Length L Ch R = 1,7623,281,281,281
BEGIN DESCRIPTION:
UNT 014 in Running Cr Watershed 12.0
END DESCRIPTION:
XS GIS Cut Line= 3
      2830815.65      7005474.09      2830821.73      7005132.03
      2830817.82      7004634.16
#Sta/Elev= 30
  4583.6  452.71  4642.7  451.64  4782.7  450.76  4833.1  449.91  4912.7  446.31
  4921.7  445.55  4942.7  444.73  4974.6  444.34  4982.7  443.91  4992.7  442.69
  4999.7  441.57  5000.2  440.77  5005.2  440.77  5005.7  441.57  5012.7  443.03
  5032.7  443.40  5049.2  444.34  5062.7  445.14  5092.8  447.55  5146.7  449.75
  5182.8  451.55  5212.8  452.64  5222.8  452.86  5262.8  452.93  5312.8  452.65
  5322.8  452.84  5332.8  452.47  5352.8  452.84  5402.8  452.71  5423.6  452.91
#Mann=3,-1,0
  4583.6    0.05       0  4999.7    0.03       0  5005.7    0.05       0
Bank Sta=4974.6,5049.2
Exp/Cntr=0.3,0.1

Type RM Length L Ch R = 1,7342,428,428,428
BEGIN DESCRIPTION:
UNT 014 in Running Cr Watershed 11.0
END DESCRIPTION:
XS GIS Cut Line= 3
      2830988.40      7005454.93      2831060.46      7005113.74
      2831057.84      7004645.96
#Sta/Elev= 30
  4541.1  451.49  4612.6  450.15  4663.7  450.05  4696.7  450.71  4796.5  446.55
  4857.9  445.74  4918.1  442.94  4948.6  441.78  4958.6  442.08  4968.0  440.95
  4973.0  442.34  4978.6  442.36  4995.6  439.88  4996.1  439.08  5001.1  439.08
  5001.6  439.88  5003.6  440.85  5008.6  441.81  5018.4  442.94  5028.6  443.33
  5048.6  445.26  5068.6  448.05  5078.6  448.44  5098.6  447.00  5178.6  446.93
  5188.6  447.07  5208.6  448.73  5278.6  451.29  5288.6  452.37  5357.6  452.10
#Mann=3,-1,0
  4541.1    0.05       0  4995.6    0.03       0  5001.6    0.05       0
Bank Sta=4918.1,5018.4
Exp/Cntr=0.3,0.1

Type RM Length L Ch R = 1,6914,426,426,426
BEGIN DESCRIPTION:
UNT 014 in Running Cr Watershed 10.0
END DESCRIPTION:
XS GIS Cut Line= 3
      2831174.98      7005525.03      2831314.78      7005291.75
      2831475.00      7004774.99
#Sta/Elev= 30
  4662.4  451.17  4670.2  451.48  4713.0  450.37  4749.9  450.37  4851.0  448.29
  4924.9  444.45  4954.6  443.46  4970.3  441.49  4981.9  440.76  4990.8  438.82
  4991.3  438.02  4996.3  438.02  4996.8  438.82  5004.3  440.26  5014.5  440.79
  5067.1  439.85  5084.9  440.56  5094.0  441.49  5155.3  443.07  5161.3  443.90
  5171.8  444.40  5182.2  444.62  5193.1  444.21  5266.0  446.07  5290.9  445.70
  5297.4  445.25  5323.5  445.14  5370.7  447.62  5412.6  448.96  5475.4  451.67
#Mann=3,-1,0
  4662.4    0.05       0  4990.8    0.03       0  4996.8    0.05       0
Bank Sta=4970.3,5094
Exp/Cntr=0.3,0.1

Type RM Length L Ch R = 1,6488,399,399,399
BEGIN DESCRIPTION:
UNT 014 in Running Cr Watershed 9.0
END DESCRIPTION:
XS GIS Cut Line= 3
      2831474.99      7005675.02      2831582.15      7005541.06
      2831689.78      7005020.93
#Sta/Elev= 30
  4746.5  449.76  4774.5  449.12  4838.6  446.94  4867.4  445.38  4924.2  441.21
  4975.3  439.76  4980.5  439.26  4985.5  438.77  4992.7  436.08  4993.2  435.28
  4998.2  435.28  4998.7  436.08  5003.5  438.26  5016.1  438.46  5026.4  437.75
  5036.6  437.93  5056.4  439.26  5067.2  439.73  5103.9  440.27  5109.0  439.87
  5159.2  439.60  5189.7  439.99  5210.2  441.43  5249.4  442.64  5291.9  445.08
  5322.5  447.54  5354.9  449.11  5400.0  449.22  5405.1  448.76  5449.2  448.01
#Mann=3,-1,0
  4746.5    0.05       0  4992.7    0.03       0  4998.7    0.05       0
Bank Sta=4980.5,5056.4
Exp/Cntr=0.3,0.1

Type RM Length L Ch R = 1,6089,369,369,369
BEGIN DESCRIPTION:
Mapping XS 1e825168
END DESCRIPTION:
XS GIS Cut Line= 3
      2831609.88      7005753.59      2831925.89      7005472.31
      2832207.11      7005180.67
#Sta/Elev= 30
  4533.7  447.92  4564.9  448.16  4656.9  441.71  4720.4  439.73  4744.1  438.03
  4763.1  437.51  4872.4  437.69  4872.9  437.69  4897.7  436.55  4932.8  437.72
  4940.3  437.26  4968.3  437.47  4982.1  436.84  4989.6  435.83  4993.6  433.08
  4994.1  432.28  4999.1  432.28  4999.6  433.08  5003.8  433.41  5010.7  436.86
  5021.0  438.03  5067.3  440.79  5152.2  443.92  5159.4  443.81  5166.4  444.51
  5223.0  446.90  5265.4  448.43  5279.6  448.34  5328.9  450.01  5361.9  450.39
#Mann=6,-1,0
  4533.7    0.05       0  4872.4    0.12       0  4872.9    0.16       0
  4982.1    0.05       0  4993.6    0.03       0  4999.6    0.05       0
Bank Sta=4744.1,5021
Exp/Cntr=0.3,0.1

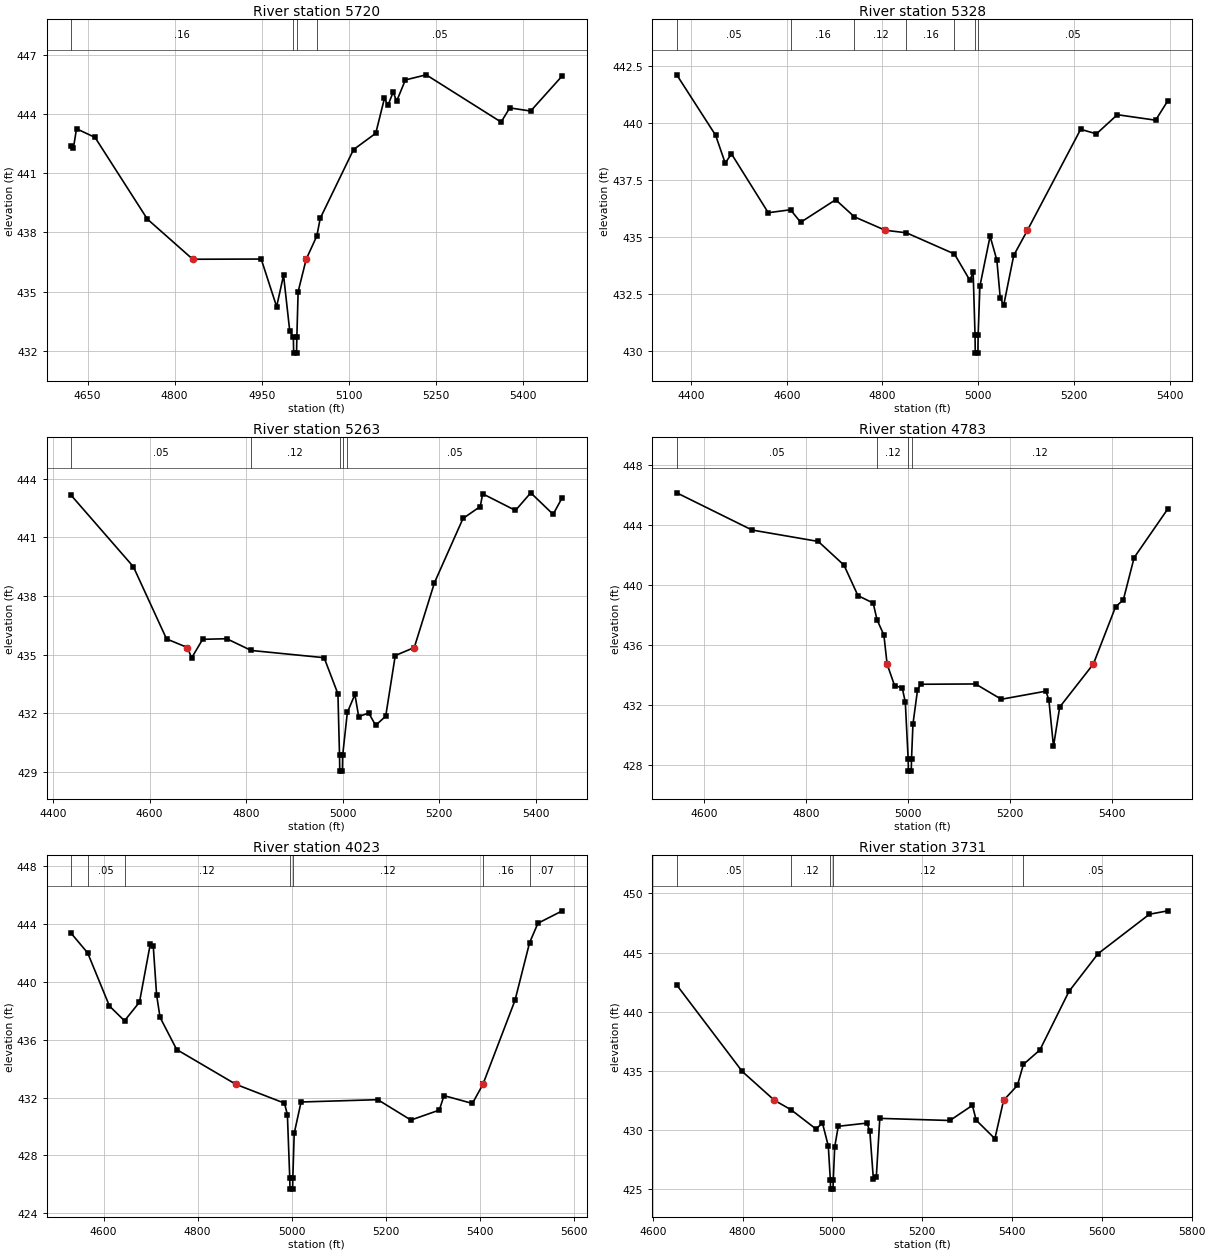
Type RM Length L Ch R = 1,5720,392,392,392
BEGIN DESCRIPTION:
UNT 014 in Running Cr Watershed 8.0
END DESCRIPTION:
XS GIS Cut Line= 3
      2831717.54      7005871.62      2832203.67      7005711.89
      2832390.59      7005434.97
#Sta/Elev= 30
  4621.9  442.37  4625.8  442.31  4631.0  443.27  4662.9  442.83  4753.0  438.68
  4831.2  436.64  4949.1  436.65  4975.7  434.23  4987.6  435.83  4998.2  433.01
  5004.5  432.67  5005.0  431.87  5010.0  431.87  5010.5  432.67  5012.7  434.99
  5026.6  436.64  5044.9  437.82  5050.8  438.72  5108.1  442.21  5146.4  443.04
  5161.4  444.82  5167.4  444.46  5176.4  445.13  5182.4  444.67  5197.4  445.75
  5233.3  446.01  5362.3  443.61  5377.2  444.33  5413.2  444.17  5467.7  445.96
#Mann=4,-1,0
  4621.9    0.16       0  5004.5    0.07       0  5010.5    0.16       0
  5044.9    0.05       0
Bank Sta=4831.2,5026.6
Exp/Cntr=0.3,0.1

Type RM Length L Ch R = 1,5328,65,65,65
BEGIN DESCRIPTION:
Mapping XS 3ef7daaa
END DESCRIPTION:
XS GIS Cut Line= 6
      2832068.12      7006356.20      2832116.73      7006034.98
      2832181.54      7005983.59      2832344.73      7005986.20
      2832461.05      7005866.40      2832538.58      7005599.58
#Sta/Elev= 30
  4370.2  442.13  4451.4  439.48  4471.4  438.26  4484.6  438.66  4561.4  436.08
  4607.9  436.21  4629.1  435.66  4702.2  436.65  4741.4  435.90  4805.8  435.31
  4850.0  435.20  4950.4  434.27  4982.5  433.12  4989.5  433.46  4993.4  430.72
  4993.9  429.92  4999.4  429.92  4999.9  430.72  5003.6  432.86  5024.9  435.05
  5039.0  434.00  5046.0  432.36  5053.2  432.01  5074.3  434.21  5102.9  435.31
  5214.1  439.74  5247.1  439.54  5290.7  440.38  5370.7  440.14  5396.2  440.99
#Mann=7,-1,0
  4370.2    0.05       0  4607.9    0.16       0  4741.4    0.12       0
  4850.0    0.16       0  4950.4    0.05       0  4993.4    0.03       0
  4999.9    0.05       0
Bank Sta=4805.8,5102.9
Exp/Cntr=0.3,0.1

Type RM Length L Ch R = 1,5263,480,480,480
BEGIN DESCRIPTION:
UNT 014 in Running Cr Watershed 7.0
END DESCRIPTION:
XS GIS Cut Line= 6
      2832129.75      7006343.18      2832155.80      7006086.20
      2832368.17      7006043.49      2832513.44      7005923.00
      2832586.35      7005794.53      2832612.39      7005600.13
#Sta/Elev= 30
  4437.7  443.14  4566.5  439.49  4635.2  435.80  4678.5  435.36  4687.2  434.83
  4710.0  435.78  4759.9  435.81  4810.6  435.21  4961.7  434.84  4990.3  432.99
  4993.6  429.84  4994.1  429.04  4999.6  429.04  5000.1  429.84  5009.8  432.04
  5025.5  432.96  5033.3  431.83  5054.1  432.01  5068.5  431.38  5089.3  431.85
  5109.1  434.95  5148.5  435.36  5190.4  438.68  5249.5  441.96  5285.2  442.57
  5290.2  443.22  5358.2  442.37  5389.8  443.27  5436.2  442.17  5455.2  443.03
#Mann=5,-1,0
  4437.7    0.05       0  4810.6    0.12       0  4993.6    0.07       0
  5000.1    0.12       0  5009.8    0.05       0
Bank Sta=4678.5,5148.5
Exp/Cntr=0.3,0.1

Type RM Length L Ch R = 1,4783,760,760,760
BEGIN DESCRIPTION:
UNT 014 in Running Cr Watershed 6.0
END DESCRIPTION:
XS GIS Cut Line= 3
      2832292.10      7006587.05      2832823.33      7006230.29
      2832995.22      7005954.23
#Sta/Elev= 30
  4545.5  446.13  4693.5  443.65  4823.6  442.89  4874.2  441.31  4901.6  439.28
  4931.6  438.78  4939.1  437.67  4952.6  436.65  4958.9  434.72  4973.7  433.27
  4988.6  433.14  4994.7  432.17  5000.3  428.38  5000.8  427.58  5006.4  427.58
  5006.9  428.38  5009.7  430.71  5018.6  432.96  5024.6  433.37  5132.7  433.39
  5183.4  432.37  5271.0  432.91  5276.8  432.33  5285.9  429.23  5298.1  431.85
  5364.3  434.72  5407.9  438.53  5423.2  439.00  5444.4  441.81  5510.6  445.06
#Mann=4,-1,0
  4545.5    0.05       0  4939.1    0.12       0  5000.3    0.07       0
  5006.9    0.12       0
Bank Sta=4958.9,5364.3
Exp/Cntr=0.3,0.1

Type RM Length L Ch R = 1,4023,292,292,292
BEGIN DESCRIPTION:
UNT 014 in Running Cr Watershed 5.0
END DESCRIPTION:
XS GIS Cut Line= 3
      2832680.10      7006894.36      2833125.42      7006558.42
      2833075.00      7006074.96
#Sta/Elev= 30
  4531.3  443.36  4566.2  442.01  4612.6  438.33  4644.6  437.31  4676.4  438.60
  4699.3  442.61  4705.6  442.52  4712.8  439.10  4720.1  437.55  4755.5  435.32
  4881.5  432.91  4984.5  431.61  4990.8  430.82  4995.8  426.46  4996.3  425.66
  5001.9  425.66  5002.4  426.46  5005.3  429.52  5019.9  431.69  5183.0  431.85
  5253.4  430.44  5313.7  431.13  5323.8  432.13  5384.1  431.59  5406.4  432.91
  5407.0  432.96  5474.6  438.72  5505.6  442.71  5523.4  444.06  5575.2  444.92
#Mann=7,-1,0
  4531.3    0.12       0  4566.2    0.05       0  4644.6    0.12       0
  4995.8    0.07       0  5002.4    0.12       0  5407.0    0.16       0
  5505.6    0.07       0
Bank Sta=4881.5,5406.4
Exp/Cntr=0.3,0.1

Type RM Length L Ch R = 1,3731,1050,1050,1050
BEGIN DESCRIPTION:
UNT 014 in Running Cr Watershed 4.0
END DESCRIPTION:
XS GIS Cut Line= 3
      2832934.42      7007030.28      2833325.05      7006709.10
      2833797.95      7006359.85
#Sta/Elev= 30
  4653.3  442.25  4799.2  434.93  4870.8  432.49  4907.8  431.69  4963.5  430.06
  4977.7  430.57  4990.8  428.63  4995.3  425.77  4995.8  424.97  5001.4  424.97
  5001.9  425.77  5005.1  428.55  5013.0  430.29  5076.8  430.56  5083.3  429.88
  5091.2  425.81  5097.7  425.98  5105.5  430.96  5261.6  430.78  5311.7  432.06
  5320.1  430.81  5361.8  429.24  5381.2  432.49  5411.9  433.75  5425.3  435.53
  5462.0  436.75  5526.8  441.71  5591.5  444.90  5705.9  448.24  5746.9  448.53
#Mann=5,-1,0
  4653.3    0.05       0  4907.8    0.12       0  4995.3    0.07       0
  5001.9    0.12       0  5425.3    0.05       0
Bank Sta=4870.8,5381.2
Exp/Cntr=0.3,0.1

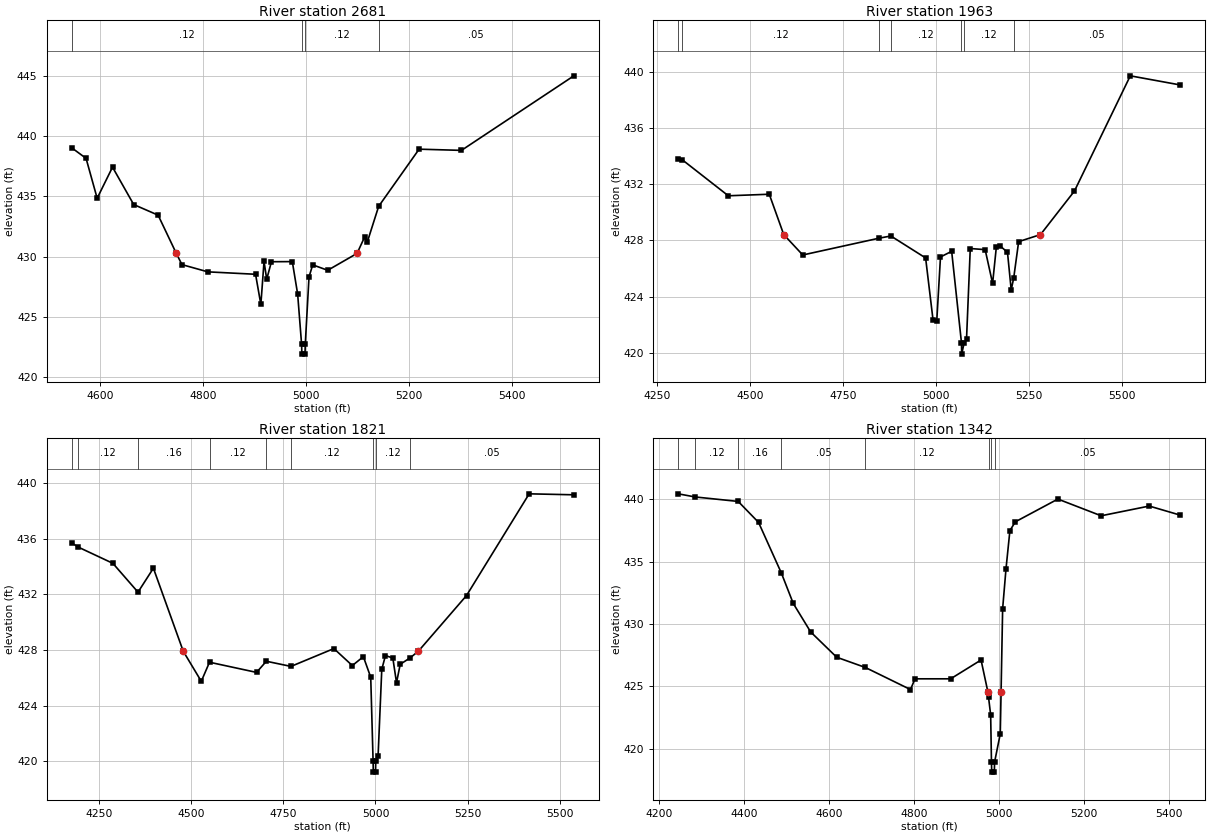
Type RM Length L Ch R = 1,2681,718,718,718
BEGIN DESCRIPTION:
UNT 014 in Running Cr Watershed 3.0
END DESCRIPTION:
XS GIS Cut Line= 3
      2833338.06      7007370.99      2833737.38      7007271.16
      2833954.53      7006749.24
#Sta/Elev= 30
  4544.2  439.03  4572.0  438.16  4593.6  434.85  4623.5  437.43  4664.7  434.33
  4712.2  433.45  4747.6  430.28  4758.6  429.35  4809.0  428.75  4901.8  428.55
  4912.1  426.05  4918.3  429.61  4923.5  428.14  4932.7  429.59  4973.3  429.60
  4983.7  426.91  4991.4  422.73  4991.9  421.93  4998.0  421.93  4998.5  422.73
  5005.8  428.33  5013.0  429.33  5042.2  428.88  5099.3  430.28  5113.8  431.62
  5119.2  431.22  5141.3  434.18  5220.0  438.92  5302.4  438.82  5521.1  445.00
#Mann=4,-1,0
  4544.2    0.12       0  4991.4    0.07       0  4998.5    0.12       0
  5141.3    0.05       0
Bank Sta=4747.6,5099.3
Exp/Cntr=0.3,0.1

Type RM Length L Ch R = 1,1963,142,142,142
BEGIN DESCRIPTION:
Mapping XS 4d9da433
END DESCRIPTION:
XS GIS Cut Line= 4
      2833490.38      7007456.93      2834075.49      7007449.98
      2834448.75      7007451.72      2834839.42      7007455.19
#Sta/Elev= 30
  4307.7  433.79  4319.0  433.72  4442.3  431.17  4552.3  431.28  4591.2  428.41
  4642.3  426.96  4848.3  428.16  4879.1  428.31  4972.4  426.75  4992.4  422.33
  5002.4  422.29  5012.4  426.82  5042.4  427.22  5068.8  420.71  5069.3  419.91
  5076.0  420.71  5082.4  421.01  5092.4  427.42  5132.4  427.34  5152.4  424.94
  5162.4  427.51  5172.4  427.61  5192.4  427.15  5202.4  424.48  5209.1  425.32
  5222.4  427.91  5281.1  428.41  5372.4  431.51  5522.4  439.70  5656.8  439.05
#Mann=7,-1,0
  4307.7    0.16       0  4319.0    0.12       0  4848.3    0.07       0
  4879.1    0.12       0  5068.8    0.07       0  5076.0    0.12       0
  5209.1    0.05       0
Bank Sta=4591.2,5281.1
Exp/Cntr=0.3,0.1

Type RM Length L Ch R = 1,1821,479,479,479
BEGIN DESCRIPTION:
UNT 014 in Running Cr Watershed 2.0
END DESCRIPTION:
XS GIS Cut Line= 3
      2833483.44      7007503.80      2834106.74      7007495.12
      2834846.33      7007503.80
#Sta/Elev= 30
  4175.6  435.69  4192.8  435.39  4287.2  434.22  4355.4  432.15  4397.2  433.87
  4478.2  427.91  4527.2  425.75  4549.5  427.12  4677.2  426.39  4703.8  427.19
  4770.7  426.82  4887.2  428.10  4937.2  426.88  4967.2  427.52  4987.2  426.04
  4993.6  420.03  4994.2  419.23  5000.3  419.23  5000.8  420.03  5007.2  420.40
  5017.2  426.61  5027.2  427.60  5047.2  427.42  5057.2  425.65  5067.2  426.97
  5095.0  427.45  5116.8  427.92  5247.3  431.91  5417.3  439.21  5538.6  439.14
#Mann=9,-1,0
  4175.6    0.16       0  4192.8    0.12       0  4355.4    0.16       0
  4549.5    0.12       0  4703.8    0.07       0  4770.7    0.12       0
  4993.6    0.07       0  5000.8    0.12       0  5095.0    0.05       0
Bank Sta=4478.2,5116.8
Exp/Cntr=0.3,0.1

Type RM Length L Ch R = 1,1342,0,0,0
BEGIN DESCRIPTION:
UNT 014 in Running Cr Watershed 1.0
END DESCRIPTION:
XS GIS Cut Line= 3
      2833749.92      7007902.25      2834377.57      7007772.03
      2834864.59      7007537.64
#Sta/Elev= 30
  4244.5  440.44  4284.0  440.19  4385.6  439.83  4433.5  438.15  4487.3  434.08
  4515.2  431.65  4556.1  429.37  4617.4  427.34  4684.8  426.52  4791.0  424.75
  4801.7  425.61  4885.5  425.61  4957.1  427.12  4973.3  424.54  4974.7  424.14
  4979.7  422.72  4981.6  418.93  4982.2  418.13  4988.4  418.13  4988.9  418.93
  5002.3  421.20  5004.2  424.54  5007.9  431.23  5015.8  434.43  5025.0  437.50
  5038.0  438.20  5137.9  440.02  5239.7  438.68  5352.9  439.46  5426.0  438.73
#Mann=8,-1,0
  4244.5    0.05       0  4284.0    0.12       0  4385.6    0.16       0
  4487.3    0.05       0  4684.8    0.12       0  4974.7    0.05       0
  4981.6    0.03       0  4988.9    0.05       0
Bank Sta=4973.3,5004.2
Exp/Cntr=0.3,0.1

Chan Stop Cuts=-1