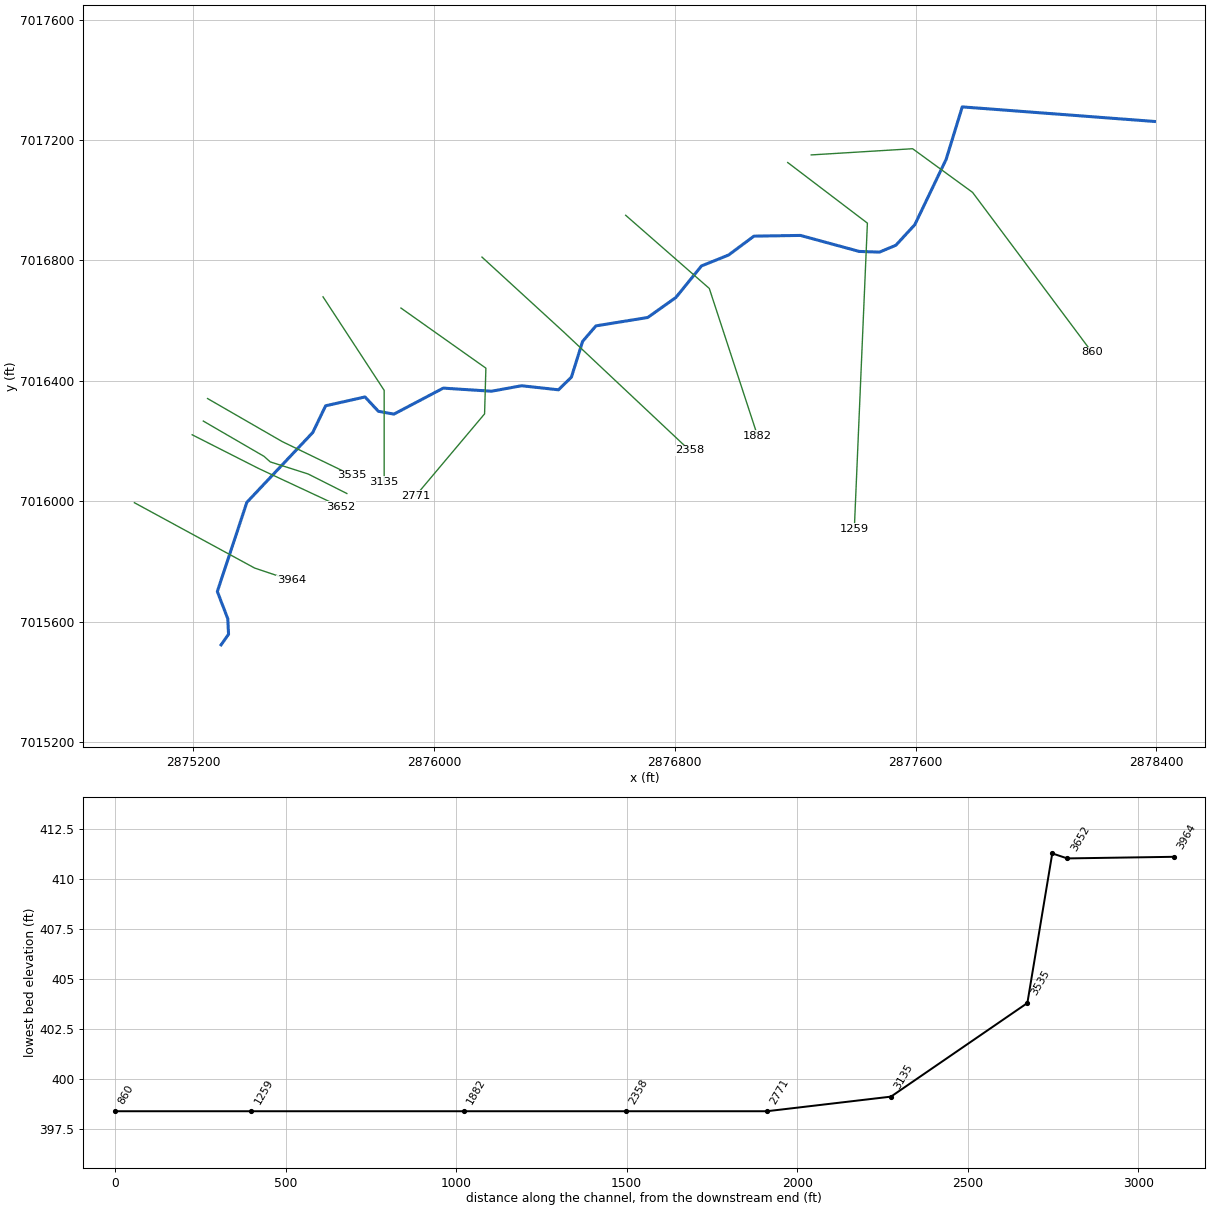
--- UNT 015 in Running Cr Watershed.prj (project) ---

Proj Title=UNT 015 in Running Cr Watershed Base Level Engineering
Current Plan=p01
Default Exp/Contr=0.3,0.1
English Units
Geom File=g01
Flow File=f01
Plan File=p01
BEGIN DESCRIPTION:
UNT 015 in Running Cr Watershed
END DESCRIPTION:

--- UNT 015 in Running Cr Watershed.p01 (plan) ---

Plan Title=Multiple Run
Short Identifier=Multiple
Geom File=g01
Flow File=f01
Subcritical Flow
K Sum by GR= 0
Std Step Tol= 0.01
Critical Tol= 0.01
Num of Std Step Trials= 20
Max Error Tol= 0.3
Flow Tol Ratio= 0.001
Split Flow NTrial= 30
Split Flow Tol= 0.02
Split Flow Ratio= 0.02
Log Output Level= 0
Friction Slope Method= 1
Unsteady Friction Slope Method= 2
Unsteady Bridges Friction Slope Method= 1
Parabolic Critical Depth
Global Vel Dist=  1 , 1 , 1
Global Log Level= 0
CheckData=True
Encroach Param= -1, 0, 0, 0
BEGIN DESCRIPTION:
Multiple Run
END DESCRIPTION:

--- UNT 015 in Running Cr Watershed.f01 (steady flow) ---

Flow Title=Multiple
Number of Profiles=7
Profile Names=10-year,25-year,50-year,1pct_min,100-year,1pct_plu,500-year
River Rch & RM= UNT 015 in Runni,Reach-1,3964
     229     287     330     190     379     756     498
Boundary for River Rch & Prof#=UNT 015 in Runni,Reach-1,1
Up Type=0
Dn Type=3
Dn Slope=0.005
Boundary for River Rch & Prof#=UNT 015 in Runni,Reach-1,2
Up Type=0
Dn Type=3
Dn Slope=0.005
Boundary for River Rch & Prof#=UNT 015 in Runni,Reach-1,3
Up Type=0
Dn Type=3
Dn Slope=0.005
Boundary for River Rch & Prof#=UNT 015 in Runni,Reach-1,4
Up Type=0
Dn Type=3
Dn Slope=0.005
Boundary for River Rch & Prof#=UNT 015 in Runni,Reach-1,5
Up Type=0
Dn Type=3
Dn Slope=0.005
Boundary for River Rch & Prof#=UNT 015 in Runni,Reach-1,6
Up Type=0
Dn Type=3
Dn Slope=0.005
Boundary for River Rch & Prof#=UNT 015 in Runni,Reach-1,7
Up Type=0
Dn Type=3
Dn Slope=0.005

--- UNT 015 in Running Cr Watershed.g01 (geometry) ---

Geom Title=Existing Conditions

River Reach=UNT 015 in Runni,Reach-1
Reach XY= 30
      2875292.76      7015522.80      2875317.50      7015557.96
      2875314.89      7015609.60      2875280.17      7015699.88
      2875378.26      7015996.11      2875597.20      7016228.12
      2875640.00      7016316.89      2875770.78      7016346.22
      2875815.17      7016298.66      2875866.69      7016289.15
      2876030.77      7016375.55      2876190.88      7016365.24
      2876290.75      7016383.47      2876413.61      7016370.00
      2876456.41      7016412.01      2876493.66      7016530.90
      2876538.05      7016582.42      2876710.05      7016610.17
      2876803.58      7016676.75      2876888.39      7016781.37
      2876978.75      7016817.84      2877062.77      7016880.45
      2877217.34      7016882.83      2877412.32      7016829.72
      2877479.70      7016827.35      2877534.31      7016850.19
      2877597.18      7016918.45      2877701.36      7017135.79
      2877754.80      7017309.82      2878393.18      7017261.40

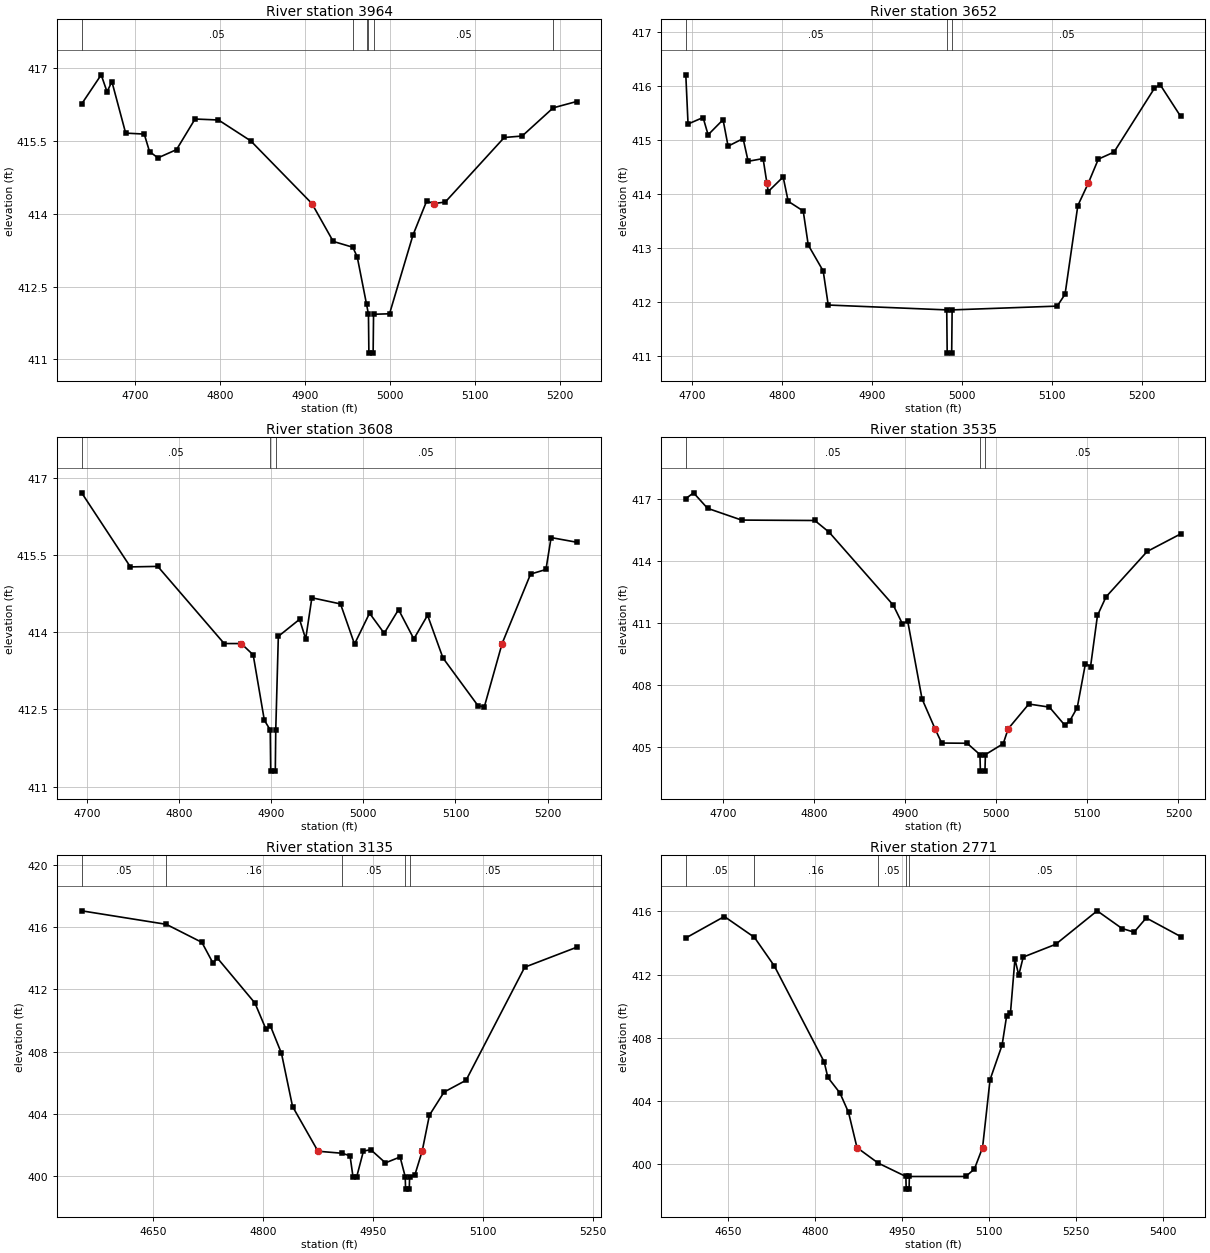
Type RM Length L Ch R = 1,3964,312,312,312
BEGIN DESCRIPTION:
UNT 015 in Running Cr Watershed 6.0
END DESCRIPTION:
XS GIS Cut Line= 3
      2875004.76      7015994.88      2875404.10      7015777.85
      2875525.63      7015737.05
#Sta/Elev= 30
  4637.0  416.26  4660.0  416.86  4666.9  416.51  4672.6  416.72  4688.8  415.66
  4710.7  415.64  4716.9  415.28  4726.8  415.15  4748.7  415.32  4770.5  415.95
  4798.1  415.93  4836.1  415.50  4908.1  414.21  4933.2  413.43  4956.3  413.31
  4961.5  413.11  4972.4  412.14  4974.7  411.93  4975.2  411.13  4980.2  411.13
  4980.7  411.93  4999.5  411.94  5027.1  413.56  5043.2  414.26  5051.7  414.21
  5065.1  414.24  5134.6  415.57  5155.7  415.60  5192.2  416.18  5219.7  416.31
#Mann=6,-1,0
  4637.0    0.05       0  4956.3    0.08       0  4972.4    0.05       0
  4974.7    0.04       0  4980.7    0.05       0  5192.2    0.08       0
Bank Sta=4908.1,5051.7
Exp/Cntr=0.3,0.1

Type RM Length L Ch R = 1,3652,44,44,44
BEGIN DESCRIPTION:
Mapping XS fef295fe
END DESCRIPTION:
XS GIS Cut Line= 3
      2875196.64      7016220.56      2875416.91      7016108.80
      2875691.48      7015980.66
#Sta/Elev= 30
  4692.8  416.20  4695.3  415.29  4712.0  415.41  4717.6  415.09  4734.2  415.37
  4739.8  414.88  4756.5  415.02  4762.1  414.60  4778.7  414.65  4783.0  414.19
  4784.4  414.04  4801.0  414.31  4806.6  413.86  4823.3  413.68  4828.9  413.05
  4845.5  412.57  4851.1  411.94  4982.8  411.85  4983.3  411.05  4988.3  411.05
  4988.8  411.85  5105.6  411.92  5114.3  412.14  5128.5  413.78  5140.0  414.19
  5151.3  414.64  5168.7  414.77  5213.6  415.95  5219.9  416.02  5242.8  415.43
#Mann=3,-1,0
  4692.8    0.05       0  4982.8    0.03       0  4988.8    0.05       0
Bank Sta=4783,5140
Exp/Cntr=0.3,0.1

Type RM Length L Ch R = 1,3608,73,73,73
BEGIN DESCRIPTION:
Mapping XS 03e1e516
END DESCRIPTION:
XS GIS Cut Line= 5
      2875233.54      7016266.12      2875435.35      7016148.94
      2875455.97      7016130.50      2875581.84      7016090.35
      2875710.47      7016025.49
#Sta/Elev= 30
  4694.2  416.71  4747.1  415.27  4776.8  415.28  4848.9  413.78  4867.4  413.78
  4880.4  413.56  4892.5  412.29  4898.9  412.10  4899.4  411.30  4904.4  411.30
  4904.9  412.10  4907.7  413.92  4930.7  414.25  4937.4  413.87  4944.1  414.67
  4975.2  414.55  4990.4  413.77  5006.7  414.37  5022.6  413.98  5038.2  414.44
  5054.8  413.87  5069.7  414.33  5086.4  413.50  5124.5  412.57  5131.3  412.55
  5150.6  413.78  5181.5  415.13  5198.2  415.22  5203.8  415.84  5231.4  415.75
#Mann=3,-1,0
  4694.2    0.05       0  4898.9    0.03       0  4904.9    0.05       0
Bank Sta=4867.4,5150.6
Exp/Cntr=0.3,0.1

Type RM Length L Ch R = 1,3535,400,400,400
BEGIN DESCRIPTION:
Mapping XS 2a978ee9
END DESCRIPTION:
XS GIS Cut Line= 3
      2875247.61      7016341.01      2875496.12      7016197.77
      2875727.28      7016085.99
#Sta/Elev= 30
  4658.9  417.02  4667.4  417.30  4682.8  416.55  4720.2  415.98  4800.6  415.96
  4816.4  415.39  4886.8  411.86  4896.9  410.95  4902.6  411.10  4918.4  407.32
  4932.7  405.87  4940.0  405.18  4967.9  405.17  4982.0  404.62  4982.5  403.82
  4987.5  403.82  4988.0  404.62  5007.6  405.15  5013.0  405.87  5035.7  407.07
  5058.3  406.92  5075.3  406.04  5080.9  406.27  5088.9  406.90  5097.9  409.03
  5103.5  408.88  5111.1  411.36  5120.5  412.26  5165.7  414.46  5202.5  415.31
#Mann=3,-1,0
  4658.9    0.05       0  4982.0    0.03       0  4988.0    0.05       0
Bank Sta=4932.7,5013
Exp/Cntr=0.3,0.1

Type RM Length L Ch R = 1,3135,364,364,364
BEGIN DESCRIPTION:
Mapping XS fe8de014
END DESCRIPTION:
XS GIS Cut Line= 3
      2875631.31      7016678.90      2875834.44      7016368.13
      2875834.44      7016064.29
#Sta/Elev= 30
  4552.2  417.06  4667.7  416.19  4716.2  415.03  4731.3  413.70  4737.3  414.02
  4788.6  411.12  4803.7  409.43  4809.7  409.65  4824.8  407.88  4839.9  404.46
  4874.6  401.58  4907.2  401.45  4918.3  401.29  4922.3  399.95  4927.5  399.95
  4936.6  401.59  4946.6  401.68  4966.6  400.83  4986.6  401.21  4993.6  399.94
  4994.1  399.14  4999.1  399.14  4999.6  399.94  5006.6  400.03  5016.7  401.58
  5026.6  403.90  5046.6  405.39  5076.6  406.15  5156.6  413.43  5227.3  414.71
#Mann=5,-1,0
  4552.2    0.05       0  4667.7    0.16       0  4907.2    0.05       0
  4993.6    0.03       0  4999.6    0.05       0
Bank Sta=4874.6,5016.7
Exp/Cntr=0.3,0.1

Type RM Length L Ch R = 1,2771,413,413,413
BEGIN DESCRIPTION:
UNT 015 in Running Cr Watershed 5.0
END DESCRIPTION:
XS GIS Cut Line= 4
      2875890.23      7016641.55      2876172.33      7016441.91
      2876167.99      7016290.00      2875938.99      7016017.79
#Sta/Elev= 30
  4577.7  414.32  4644.2  415.68  4696.0  414.36  4730.3  412.55  4816.3  406.47
  4822.6  405.49  4843.5  404.50  4858.3  403.27  4872.9  401.04  4909.4  400.06
  4957.2  399.21  4957.7  398.41  4962.7  398.41  4963.2  399.21  5060.3  399.21
  5075.3  399.68  5089.4  401.04  5102.3  405.34  5123.1  407.54  5130.9  409.38
  5137.5  409.56  5145.2  412.98  5151.8  411.96  5159.5  413.11  5215.5  413.92
  5287.0  416.04  5329.9  414.92  5350.7  414.69  5371.6  415.59  5431.0  414.41
#Mann=5,-1,0
  4577.7    0.05       0  4696.0    0.16       0  4909.4    0.05       0
  4957.2   0.033       0  4963.2    0.05       0
Bank Sta=4872.9,5089.4
Exp/Cntr=0.3,0.1

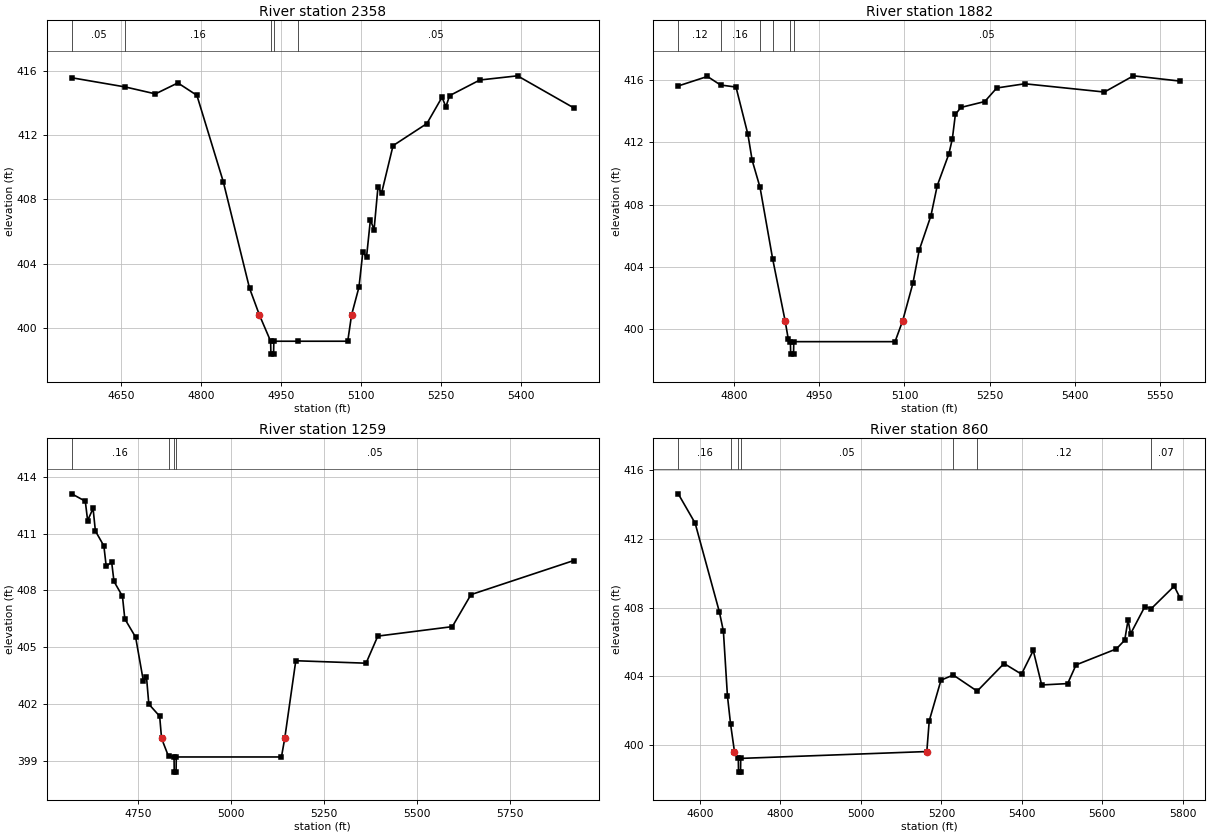
Type RM Length L Ch R = 1,2358,476,476,476
BEGIN DESCRIPTION:
UNT 015 in Running Cr Watershed 4.0
END DESCRIPTION:
XS GIS Cut Line= 3
      2876159.34      7016810.81      2876432.04      7016560.92
      2876848.63      7016169.21
#Sta/Elev= 30
  4558.1  415.55  4658.4  414.98  4715.0  414.55  4757.1  415.23  4792.8  414.46
  4842.2  409.11  4891.5  402.50  4910.0  400.84  4931.1  399.21  4931.6  398.41
  4936.6  398.41  4937.1  399.21  4982.7  399.21  5075.7  399.21  5082.9  400.84
  5096.8  402.57  5104.1  404.76  5110.9  404.41  5118.2  406.74  5125.1  406.13
  5132.4  408.77  5139.2  408.40  5160.7  411.34  5224.2  412.71  5252.5  414.34
  5259.8  413.75  5266.7  414.44  5323.4  415.41  5394.2  415.67  5499.8  413.68
#Mann=5,-1,0
  4558.1    0.05       0  4658.4    0.16       0  4931.1   0.033       0
  4937.1    0.16       0  4982.7    0.05       0
Bank Sta=4910,5082.9
Exp/Cntr=0.3,0.1

Type RM Length L Ch R = 1,1882,623,623,623
BEGIN DESCRIPTION:
UNT 015 in Running Cr Watershed 3.0
END DESCRIPTION:
XS GIS Cut Line= 3
      2876636.75      7016949.72      2876914.52      7016706.67
      2877074.50      7016218.08
#Sta/Elev= 30
  4702.0  415.62  4753.3  416.23  4776.5  415.68  4803.6  415.55  4824.5  412.52
  4832.1  410.84  4845.9  409.11  4868.0  404.54  4890.0  400.55  4895.7  399.35
  4899.3  399.21  4899.8  398.41  4904.8  398.41  4905.3  399.21  5083.4  399.21
  5096.8  400.55  5114.9  402.97  5125.8  405.07  5146.5  407.29  5157.6  409.22
  5178.1  411.26  5184.2  412.23  5189.5  413.79  5199.1  414.24  5241.2  414.62
  5262.3  415.49  5311.6  415.76  5451.7  415.23  5502.7  416.27  5585.2  415.93
#Mann=6,-1,0
  4702.0    0.12       0  4776.5    0.16       0  4845.9    0.12       0
  4868.0    0.05       0  4899.3   0.033       0  4905.3    0.05       0
Bank Sta=4890,5096.8
Exp/Cntr=0.3,0.1

Type RM Length L Ch R = 1,1259,399,399,399
BEGIN DESCRIPTION:
UNT 015 in Running Cr Watershed 2.0
END DESCRIPTION:
XS GIS Cut Line= 3
      2877175.02      7017124.99      2877439.69      7016923.68
      2877396.33      7015909.04
#Sta/Elev= 30
  4572.6  413.10  4608.9  412.71  4615.2  411.69  4629.8  412.33  4636.0  411.14
  4658.8  410.35  4665.1  409.27  4679.7  409.50  4685.9  408.48  4708.7  407.69
  4715.0  406.50  4744.1  405.53  4764.9  403.21  4773.2  403.44  4779.5  402.00
  4808.6  401.36  4813.7  400.19  4832.4  399.24  4847.2  399.21  4847.7  398.41
  4852.7  398.41  4853.2  399.21  5135.6  399.21  5144.4  400.19  5174.1  404.29
  5362.8  404.16  5394.3  405.59  5594.4  406.09  5644.5  407.78  5920.7  409.58
#Mann=4,-1,0
  4572.6    0.16       0  4832.4    0.05       0  4847.2   0.033       0
  4853.2    0.05       0
Bank Sta=4813.7,5144.4
Exp/Cntr=0.3,0.1

Type RM Length L Ch R = 1,860,0,0,0
BEGIN DESCRIPTION:
UNT 015 in Running Cr Watershed 1.0
END DESCRIPTION:
XS GIS Cut Line= 4
      2877253.03      7017150.24      2877589.93      7017170.83
      2877789.14      7017025.81      2878186.20      7016494.02
#Sta/Elev= 30
  4546.1  414.63  4588.1  412.92  4648.3  407.75  4658.3  406.63  4668.3  402.87
  4676.1  401.22  4685.8  399.61  4695.4  399.21  4695.9  398.41  4700.9  398.41
  4701.4  399.21  5163.8  399.61  5169.8  401.40  5199.0  403.77  5229.5  404.07
  5288.9  403.13  5355.7  404.74  5399.1  404.12  5428.3  405.50  5449.2  403.49
  5513.8  403.57  5534.6  404.66  5634.7  405.59  5655.5  406.10  5663.9  407.28
  5670.1  406.47  5705.6  408.06  5721.2  407.93  5778.5  409.25  5793.7  408.53
#Mann=7,-1,0
  4546.1    0.16       0  4676.1    0.05       0  4695.4   0.033       0
  4701.4    0.05       0  5229.5    0.16       0  5288.9    0.12       0
  5721.2    0.07       0
Bank Sta=4685.8,5163.8
Exp/Cntr=0.3,0.1

Chan Stop Cuts=-1