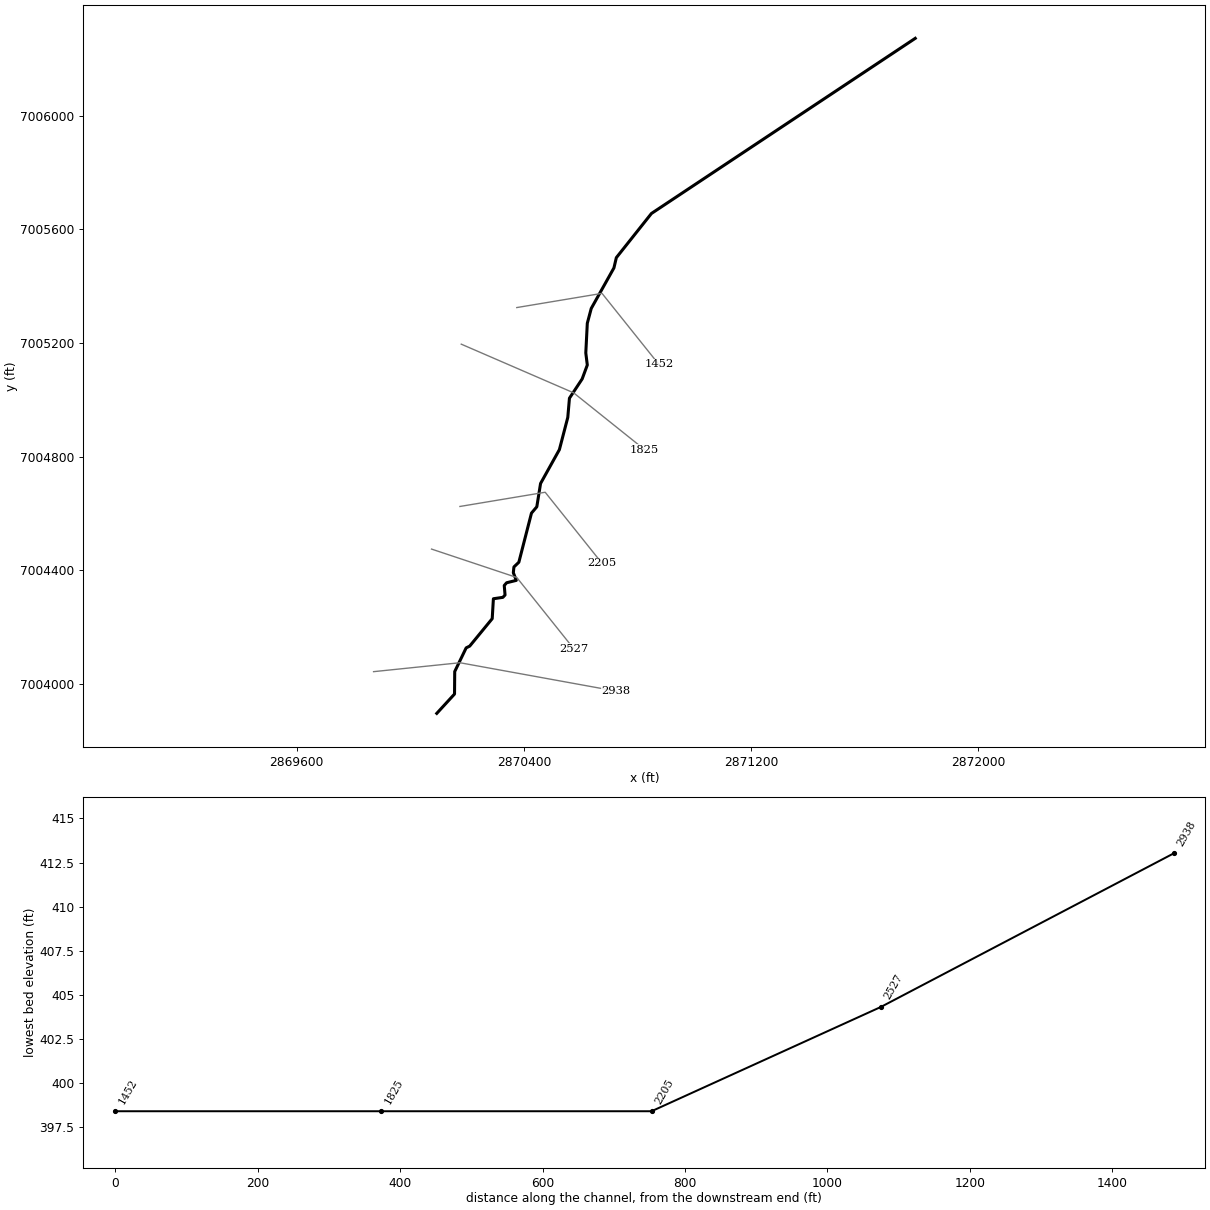
--- UNT 016 in Running Cr Watershed.prj (project) ---

Proj Title=UNT 016 in Running Cr Watershed Base Level Engineering
Current Plan=p01
Default Exp/Contr=0.3,0.1
English Units
Geom File=g01
Flow File=f01
Plan File=p01
BEGIN DESCRIPTION:
UNT 016 in Running Cr Watershed
END DESCRIPTION:

--- UNT 016 in Running Cr Watershed.p01 (plan) ---

Plan Title=Multiple Run
Short Identifier=Multiple
Geom File=g01
Flow File=f01
Subcritical Flow
K Sum by GR= 0
Std Step Tol= 0.01
Critical Tol= 0.01
Num of Std Step Trials= 20
Max Error Tol= 0.3
Flow Tol Ratio= 0.001
Split Flow NTrial= 30
Split Flow Tol= 0.02
Split Flow Ratio= 0.02
Log Output Level= 0
Friction Slope Method= 1
Unsteady Friction Slope Method= 2
Unsteady Bridges Friction Slope Method= 1
Parabolic Critical Depth
Global Vel Dist=  1 , 1 , 1
Global Log Level= 0
CheckData=True
Encroach Param= -1, 0, 0, 0
BEGIN DESCRIPTION:
Multiple Run
END DESCRIPTION:

--- UNT 016 in Running Cr Watershed.f01 (steady flow) ---

Flow Title=Multiple
Number of Profiles=7
Profile Names=10-year,25-year,50-year,1pct_min,100-year,1pct_plu,500-year
River Rch & RM= UNT 016 in Runni,Reach-1,2938
     164     201     229     130     259     516     331
Boundary for River Rch & Prof#=UNT 016 in Runni,Reach-1,1
Up Type=0
Dn Type=3
Dn Slope=0.005
Boundary for River Rch & Prof#=UNT 016 in Runni,Reach-1,2
Up Type=0
Dn Type=3
Dn Slope=0.005
Boundary for River Rch & Prof#=UNT 016 in Runni,Reach-1,3
Up Type=0
Dn Type=3
Dn Slope=0.005
Boundary for River Rch & Prof#=UNT 016 in Runni,Reach-1,4
Up Type=0
Dn Type=3
Dn Slope=0.005
Boundary for River Rch & Prof#=UNT 016 in Runni,Reach-1,5
Up Type=0
Dn Type=3
Dn Slope=0.005
Boundary for River Rch & Prof#=UNT 016 in Runni,Reach-1,6
Up Type=0
Dn Type=3
Dn Slope=0.005
Boundary for River Rch & Prof#=UNT 016 in Runni,Reach-1,7
Up Type=0
Dn Type=3
Dn Slope=0.005

--- UNT 016 in Running Cr Watershed.g01 (geometry) ---

Geom Title=Existing Conditions

River Reach=UNT 016 in Runni,Reach-1
Reach XY= 30
      2870093.44      7003896.76      2870155.94      7003964.82
      2870156.63      7004043.98      2870196.91      7004127.32
      2870209.41      7004133.57      2870288.58      7004230.09
      2870292.74      7004300.23      2870326.08      7004305.09
      2870333.72      7004313.43      2870330.94      7004346.76
      2870339.27      7004356.48      2870373.30      7004364.82
      2870362.88      7004391.90      2870364.97      7004412.04
      2870382.33      7004428.70      2870426.77      7004601.62
      2870445.52      7004623.84      2870458.72      7004705.79
      2870525.00      7004825.00      2870554.55      7004938.43
      2870560.40      7005006.03      2870605.14      7005073.79
      2870623.24      7005122.76      2870617.92      7005165.35
      2870623.24      7005269.67      2870637.08      7005321.84
      2870716.92      7005464.49      2870725.44      7005500.68
      2870848.93      7005656.11      2871777.47      7006272.56

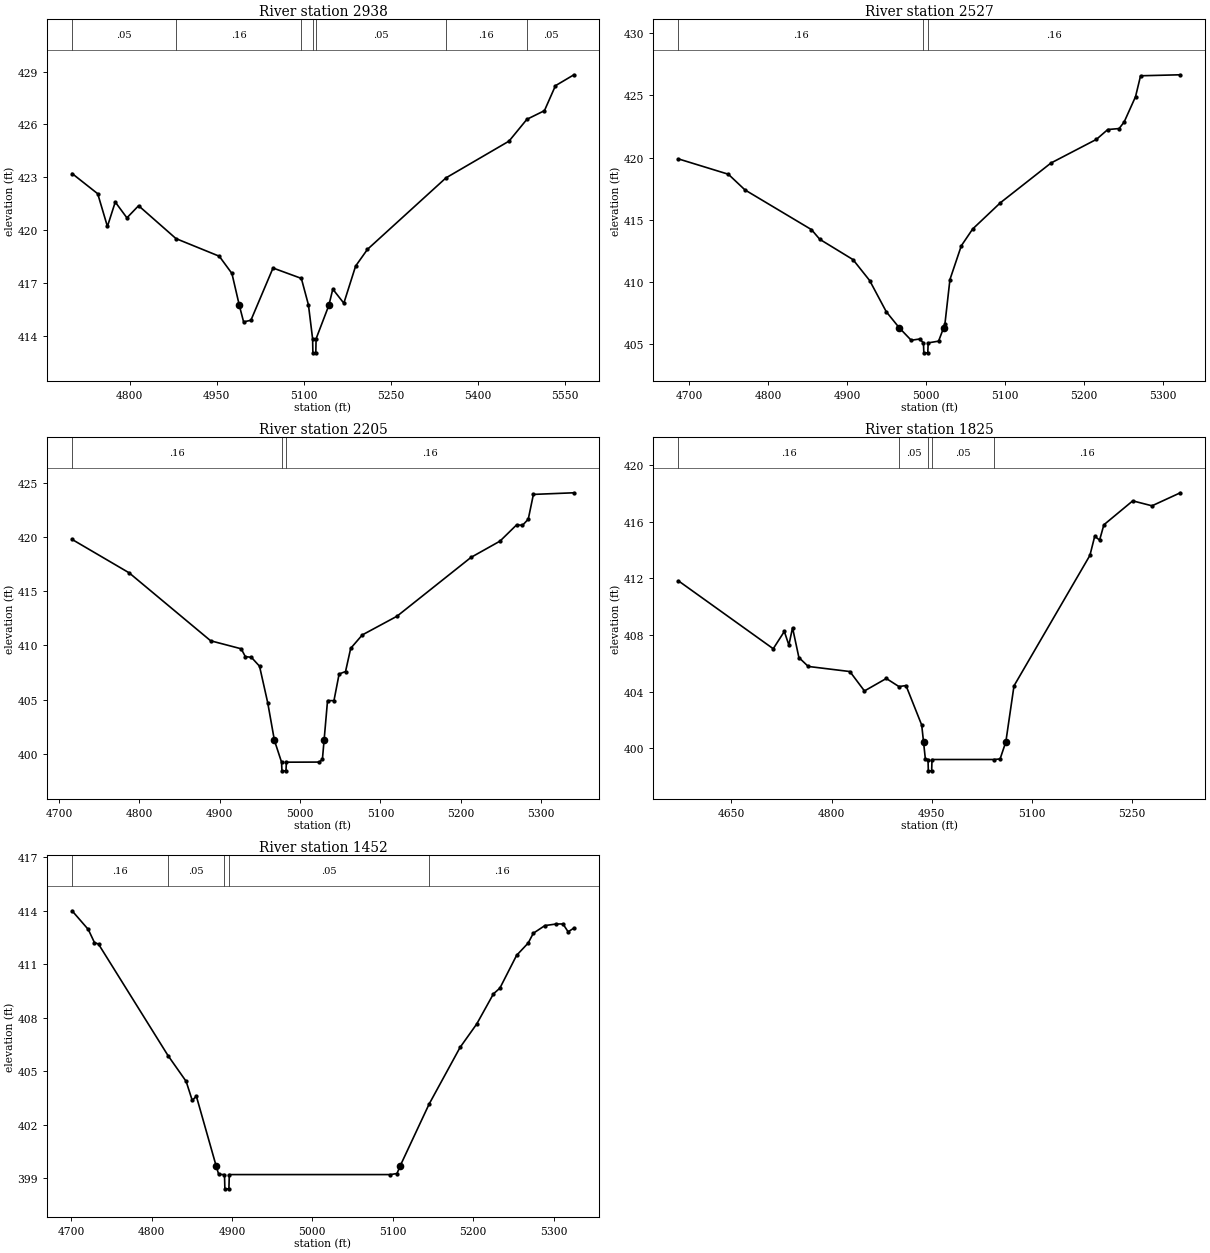
Type RM Length L Ch R = 1,2938,411,411,411
BEGIN DESCRIPTION:
UNT 016 in Running Cr Watershed 5.0
END DESCRIPTION:
XS GIS Cut Line= 3
      2869871.03      7004043.58      2870175.00      7004075.00
      2870724.99      7003975.00
#Sta/Elev= 30
  4700.6  423.21  4744.8  422.06  4761.5  420.20  4775.0  421.59  4795.1  420.69
  4815.2  421.38  4879.7  419.51  4954.2  418.51  4976.0  417.53  4988.8  415.71
  4996.1  414.78  5008.7  414.87  5046.8  417.84  5095.6  417.25  5107.8  415.75
  5115.0  413.82  5115.5  413.02  5120.5  413.02  5121.0  413.82  5142.9  415.71
  5149.8  416.64  5168.8  415.84  5189.1  417.95  5209.5  418.90  5344.7  422.96
  5453.4  425.05  5484.2  426.29  5514.4  426.78  5533.4  428.20  5565.2  428.82
#Mann=7,-1,0
  4700.6    0.05       0  4879.7    0.16       0  5095.6    0.05       0
  5115.0    0.07       0  5121.0    0.05       0  5344.7    0.16       0
  5484.2    0.05       0
Bank Sta=4988.8,5142.9
Exp/Cntr=0.3,0.1

Type RM Length L Ch R = 1,2527,322,322,322
BEGIN DESCRIPTION:
UNT 016 in Running Cr Watershed 4.0
END DESCRIPTION:
XS GIS Cut Line= 3
      2870075.03      7004474.99      2870375.00      7004375.00
      2870574.97      7004125.04
#Sta/Elev= 30
  4686.1  419.90  4749.3  418.67  4770.4  417.41  4854.7  414.22  4865.3  413.44
  4907.4  411.81  4928.5  410.13  4949.6  407.62  4966.2  406.32  4981.2  405.33
  4991.8  405.43  4996.7  405.12  4997.2  404.32  5002.2  404.32  5002.7  405.12
  5015.9  405.26  5022.2  406.32  5023.9  406.62  5030.3  410.21  5044.7  412.92
  5059.1  414.27  5094.3  416.38  5158.4  419.57  5216.0  421.47  5230.4  422.26
  5244.8  422.34  5251.2  422.87  5265.6  424.90  5272.0  426.58  5322.4  426.66
#Mann=3,-1,0
  4686.1    0.16       0  4996.7    0.07       0  5002.7    0.16       0
Bank Sta=4966.2,5022.2
Exp/Cntr=0.3,0.1

Type RM Length L Ch R = 1,2205,380,380,380
BEGIN DESCRIPTION:
UNT 016 in Running Cr Watershed 3.0
END DESCRIPTION:
XS GIS Cut Line= 3
      2870174.95      7004624.99      2870475.00      7004675.00
      2870674.97      7004425.03
#Sta/Elev= 30
  4716.4  419.80  4787.4  416.71  4888.8  410.43  4926.8  409.69  4931.9  408.97
  4939.5  408.90  4949.6  408.08  4959.8  404.70  4968.1  401.23  4977.0  399.21
  4977.5  398.41  4982.5  398.41  4983.0  399.21  5023.8  399.22  5027.8  399.46
  5029.9  401.23  5034.2  404.90  5042.2  404.90  5048.6  407.36  5056.6  407.59
  5063.0  409.73  5077.4  410.97  5120.6  412.70  5212.7  418.14  5248.7  419.64
  5269.5  421.15  5276.7  421.10  5283.9  421.67  5290.3  423.96  5340.7  424.11
#Mann=3,-1,0
  4716.4    0.16       0  4977.0    0.07       0  4983.0    0.16       0
Bank Sta=4968.1,5029.9
Exp/Cntr=0.3,0.1

Type RM Length L Ch R = 1,1825,373,373,373
BEGIN DESCRIPTION:
UNT 016 in Running Cr Watershed 2.0
END DESCRIPTION:
XS GIS Cut Line= 3
      2870179.62      7005196.20      2870575.00      7005025.00
      2870824.99      7004825.01
#Sta/Elev= 30
  4570.9  411.82  4712.7  407.03  4729.3  408.25  4736.1  407.29  4741.6  408.51
  4751.1  406.41  4765.1  405.78  4827.4  405.42  4849.2  404.05  4881.9  404.93
  4900.8  404.36  4911.4  404.43  4934.9  401.64  4937.6  400.46  4940.3  399.27
  4944.3  399.21  4944.8  398.41  4949.8  398.41  4950.3  399.21  5042.9  399.21
  5052.2  399.25  5060.8  400.46  5073.0  404.41  5186.6  413.62  5193.8  414.97
  5201.1  414.70  5207.5  415.78  5250.7  417.47  5279.5  417.12  5321.9  418.04
#Mann=5,-1,0
  4570.9    0.16       0  4900.8    0.05       0  4944.3   0.033       0
  4950.3    0.05       0  5042.9    0.16       0
Bank Sta=4937.6,5060.8
Exp/Cntr=0.3,0.1

Type RM Length L Ch R = 1,1452,0,0,0
BEGIN DESCRIPTION:
UNT 016 in Running Cr Watershed 1.0
END DESCRIPTION:
XS GIS Cut Line= 3
      2870375.04      7005325.01      2870675.00      7005375.00
      2870875.03      7005124.97
#Sta/Elev= 30
  4701.1  414.01  4721.3  412.96  4728.9  412.23  4734.0  412.14  4820.4  405.89
  4843.0  404.44  4850.6  403.37  4855.7  403.61  4880.3  399.70  4883.5  399.22
  4890.7  399.21  4891.2  398.41  4896.2  398.41  4896.7  399.21  5097.2  399.21
  5105.3  399.27  5109.3  399.70  5145.2  403.16  5183.7  406.34  5204.5  407.66
  5225.3  409.35  5233.3  409.67  5254.1  411.51  5268.5  412.20  5274.9  412.75
  5289.3  413.18  5303.7  413.27  5311.8  413.27  5318.2  412.83  5325.4  413.04
#Mann=5,-1,0
  4701.1    0.16       0  4820.4    0.05       0  4890.7   0.033       0
  4896.7    0.05       0  5145.2    0.16       0
Bank Sta=4880.3,5109.3
Exp/Cntr=0.3,0.1

Chan Stop Cuts=-1