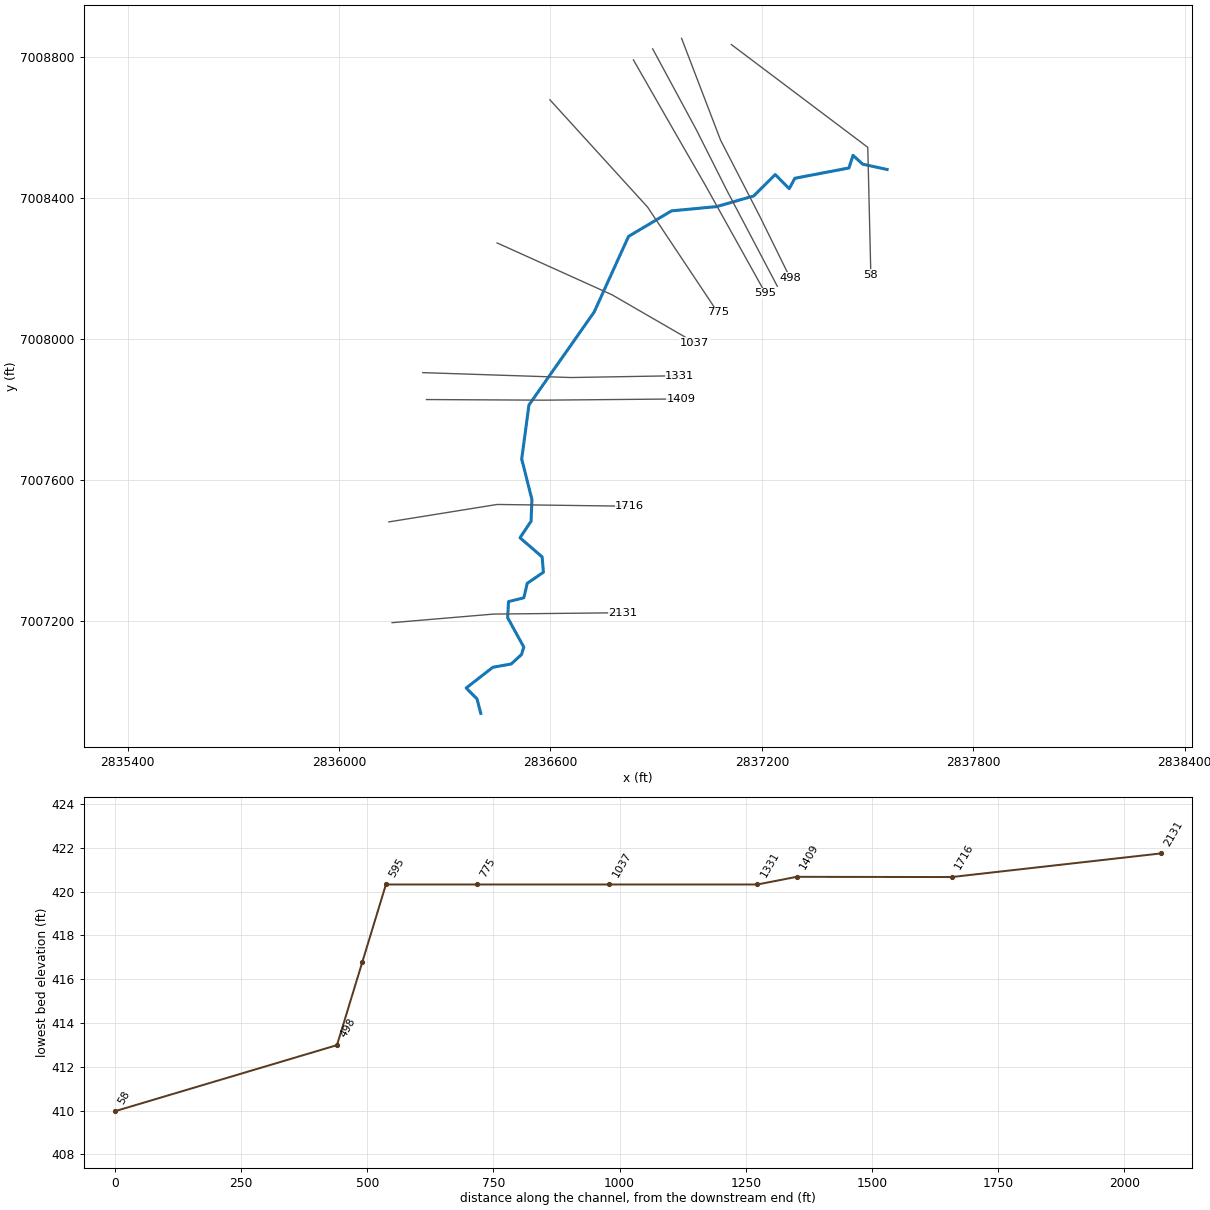
--- UNT 017 in Running Cr Watershed.prj (project) ---

Proj Title=UNT 017 in Running Cr Watershed Base Level Engineering
Current Plan=p01
Default Exp/Contr=0.3,0.1
English Units
Geom File=g01
Flow File=f01
Plan File=p01
BEGIN DESCRIPTION:
UNT 017 in Running Cr Watershed
END DESCRIPTION:

--- UNT 017 in Running Cr Watershed.p01 (plan) ---

Plan Title=Multiple Run
Short Identifier=Multiple
Geom File=g01
Flow File=f01
Subcritical Flow
K Sum by GR= 0
Std Step Tol= 0.01
Critical Tol= 0.01
Num of Std Step Trials= 20
Max Error Tol= 0.3
Flow Tol Ratio= 0.001
Split Flow NTrial= 30
Split Flow Tol= 0.02
Split Flow Ratio= 0.02
Log Output Level= 0
Friction Slope Method= 1
Unsteady Friction Slope Method= 2
Unsteady Bridges Friction Slope Method= 1
Parabolic Critical Depth
Global Vel Dist=  1 , 1 , 1
Global Log Level= 0
CheckData=True
Encroach Param= -1, 0, 0, 0
BEGIN DESCRIPTION:
Multiple Run
END DESCRIPTION:

--- UNT 017 in Running Cr Watershed.f01 (steady flow) ---

Flow Title=Multiple
Number of Profiles=7
Profile Names=10-year,25-year,50-year,1pct_min,100-year,1pct_plu,500-year
River Rch & RM= UNT 017 in Runni,Reach-1,2131
     288     368     430     250     499     996     673
Boundary for River Rch & Prof#=UNT 017 in Runni,Reach-1,1
Up Type=0
Dn Type=3
Dn Slope=0.005
Boundary for River Rch & Prof#=UNT 017 in Runni,Reach-1,2
Up Type=0
Dn Type=3
Dn Slope=0.005
Boundary for River Rch & Prof#=UNT 017 in Runni,Reach-1,3
Up Type=0
Dn Type=3
Dn Slope=0.005
Boundary for River Rch & Prof#=UNT 017 in Runni,Reach-1,4
Up Type=0
Dn Type=3
Dn Slope=0.005
Boundary for River Rch & Prof#=UNT 017 in Runni,Reach-1,5
Up Type=0
Dn Type=3
Dn Slope=0.005
Boundary for River Rch & Prof#=UNT 017 in Runni,Reach-1,6
Up Type=0
Dn Type=3
Dn Slope=0.005
Boundary for River Rch & Prof#=UNT 017 in Runni,Reach-1,7
Up Type=0
Dn Type=3
Dn Slope=0.005

--- UNT 017 in Running Cr Watershed.g01 (geometry) ---

Geom Title=Existing Conditions

River Reach=UNT 017 in Runni,Reach-1
Reach XY= 30
      2836402.45      7006937.11      2836391.59      7006978.33
      2836360.98      7007009.08      2836436.67      7007068.01
      2836488.71      7007077.24      2836517.95      7007104.09
      2836524.46      7007125.28      2836478.67      7007208.39
      2836481.08      7007254.29      2836524.57      7007265.17
      2836534.24      7007306.24      2836580.14      7007337.65
      2836576.52      7007381.14      2836513.70      7007435.50
      2836545.11      7007482.61      2836547.53      7007544.23
      2836518.53      7007658.99      2836539.07      7007812.41
      2836723.90      7008075.77      2836821.75      7008290.80
      2836943.76      7008363.28      2837071.82      7008375.36
      2837176.92      7008405.56      2837238.05      7008466.27
      2837277.75      7008426.31      2837293.75      7008455.80
      2837447.21      7008484.99      2837458.84      7008520.91
      2837486.27      7008495.80      2837555.59      7008480.71

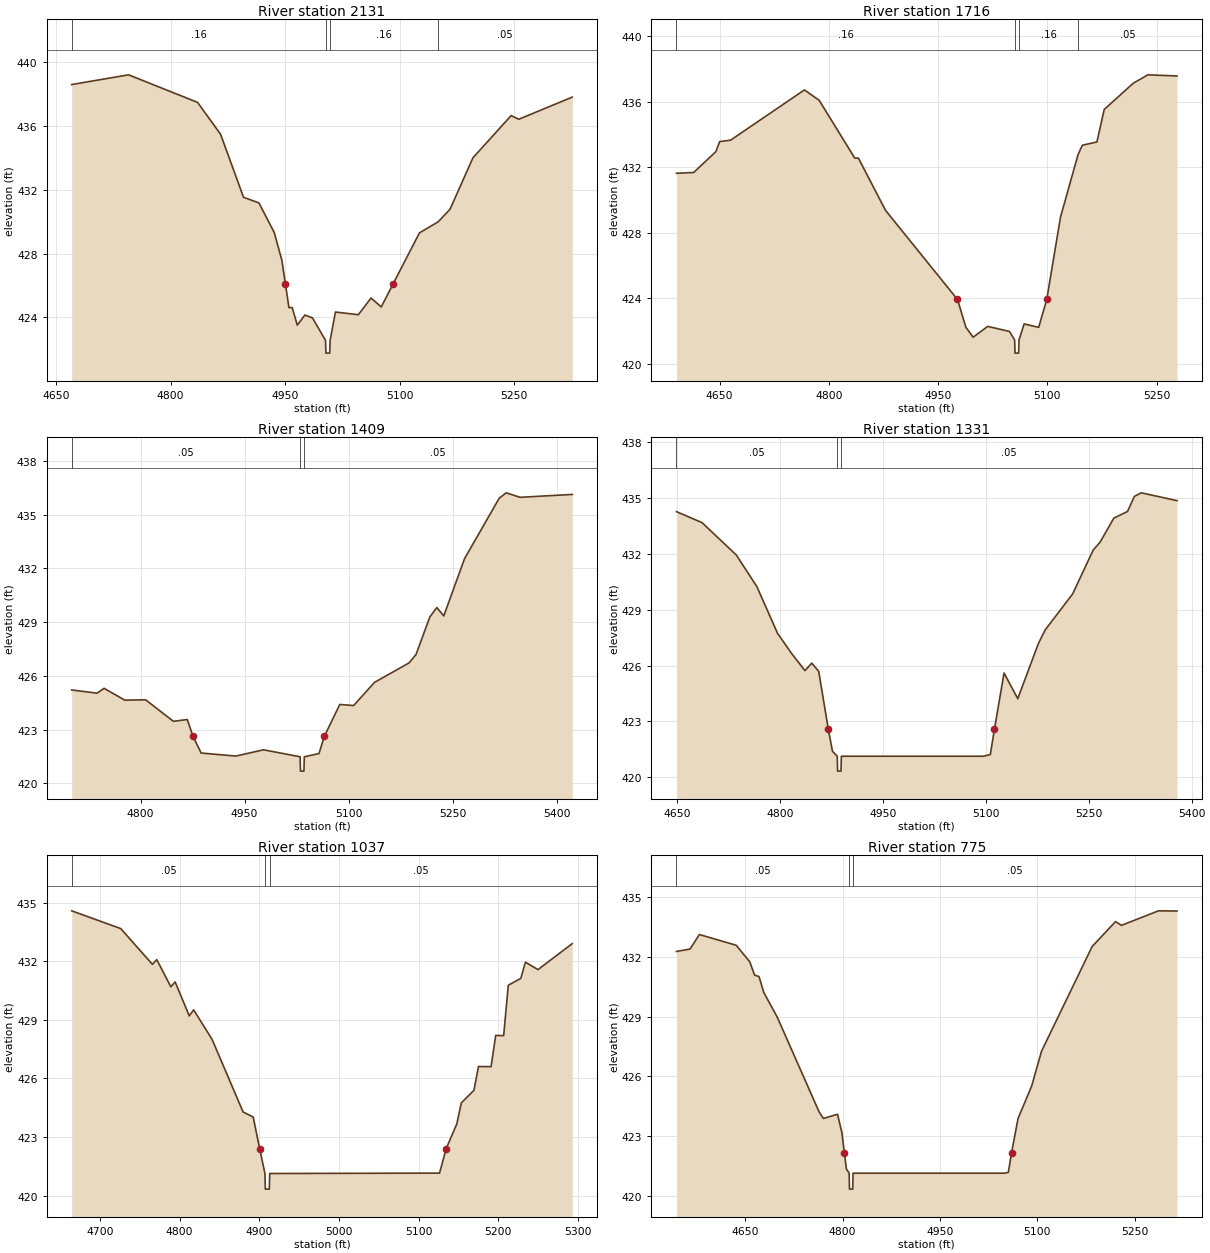
Type RM Length L Ch R = 1,2131,415,415,415
BEGIN DESCRIPTION:
UNT 017 in Running Cr Watershed 6.0
END DESCRIPTION:
XS GIS Cut Line= 3
      2836150.77      7007194.53      2836438.40      7007218.90
      2836805.02      7007222.74
#Sta/Elev= 30
  4670.5  438.61  4745.0  439.22  4835.3  437.49  4865.4  435.49  4895.5  431.53
  4915.6  431.18  4935.7  429.32  4945.7  427.57  4950.4  426.07  4954.9  424.61
  4959.2  424.61  4965.8  423.51  4975.8  424.14  4985.8  423.96  5002.8  422.55
  5003.3  421.75  5008.3  421.75  5008.8  422.55  5015.8  424.33  5045.8  424.16
  5062.4  425.21  5075.8  424.65  5091.0  426.07  5125.8  429.30  5150.2  429.99
  5165.8  430.78  5195.8  434.01  5245.8  436.66  5255.8  436.43  5325.8  437.82
#Mann=4,-1,0
  4670.5    0.16       0  5002.8    0.07       0  5008.8    0.16       0
  5150.2    0.05       0
Bank Sta=4950.4,5091
Exp/Cntr=0.3,0.1

Type RM Length L Ch R = 1,1716,307,307,307
BEGIN DESCRIPTION:
UNT 017 in Running Cr Watershed 5.0
END DESCRIPTION:
XS GIS Cut Line= 3
      2836141.58      7007480.56      2836448.83      7007530.03
      2836824.99      7007525.00
#Sta/Elev= 30
  4590.7  431.63  4614.4  431.68  4644.8  432.95  4650.0  433.56  4665.1  433.65
  4766.4  436.71  4786.6  436.08  4835.5  432.56  4840.6  432.55  4877.8  429.37
  4976.6  423.94  4988.1  422.25  4998.1  421.64  5018.1  422.30  5048.1  421.99
  5055.1  421.47  5055.6  420.67  5060.6  420.67  5061.1  421.47  5068.1  422.45
  5088.1  422.24  5099.2  423.94  5118.1  428.96  5142.2  432.77  5148.1  433.34
  5168.1  433.54  5178.1  435.52  5218.1  437.12  5238.1  437.63  5278.1  437.56
#Mann=4,-1,0
  4590.7    0.16       0  5055.1    0.07       0  5061.1    0.16       0
  5142.2    0.05       0
Bank Sta=4976.6,5099.2
Exp/Cntr=0.3,0.1

Type RM Length L Ch R = 1,1409,78,78,78
BEGIN DESCRIPTION:
Mapping XS 751aa486
END DESCRIPTION:
XS GIS Cut Line= 3
      2836248.28      7007827.78      2836581.64      7007826.04
      2836970.26      7007829.51
#Sta/Elev= 30
  4700.7  425.21  4737.4  425.03  4747.4  425.30  4777.4  424.64  4807.4  424.66
  4847.4  423.46  4867.4  423.56  4875.7  422.62  4887.4  421.69  4937.4  421.52
  4977.4  421.87  5030.2  421.48  5030.7  420.68  5035.7  420.68  5036.2  421.48
  5057.4  421.66  5065.1  422.62  5087.4  424.40  5107.4  424.34  5137.4  425.63
  5187.4  426.72  5197.4  427.19  5217.4  429.29  5227.4  429.81  5237.4  429.34
  5267.4  432.54  5317.4  435.91  5327.4  436.21  5347.4  435.96  5422.7  436.12
#Mann=3,-1,0
  4700.7    0.05       0  5030.2    0.03       0  5036.2    0.05       0
Bank Sta=4875.7,5065.1
Exp/Cntr=0.3,0.1

Type RM Length L Ch R = 1,1331,294,294,294
BEGIN DESCRIPTION:
UNT 017 in Running Cr Watershed 4.0
END DESCRIPTION:
XS GIS Cut Line= 3
      2836237.86      7007904.17      2836658.03      7007890.28
      2836967.09      7007895.48
#Sta/Elev= 30
  4649.2  434.27  4686.4  433.68  4736.4  431.94  4766.4  430.24  4796.4  427.74
  4816.4  426.68  4836.4  425.73  4846.4  426.13  4856.5  425.69  4870.5  422.58
  4876.5  421.40  4883.5  421.13  4884.0  420.33  4889.0  420.33  4889.5  421.13
  5096.6  421.13  5106.6  421.22  5112.6  422.58  5126.6  425.60  5146.6  424.22
  5176.6  427.18  5186.6  427.92  5226.6  429.85  5256.6  432.21  5266.6  432.63
  5286.6  433.92  5306.6  434.28  5316.6  435.09  5326.6  435.28  5378.7  434.86
#Mann=3,-1,0
  4649.2    0.05       0  4883.5    0.03       0  4889.5    0.05       0
Bank Sta=4870.5,5112.6
Exp/Cntr=0.3,0.1

Type RM Length L Ch R = 1,1037,262,262,262
BEGIN DESCRIPTION:
UNT 017 in Running Cr Watershed 3.0
END DESCRIPTION:
XS GIS Cut Line= 3
      2836448.83      7008272.22      2836775.00      7008125.00
      2837009.22      7007989.59
#Sta/Elev= 30
  4664.5  434.58  4726.1  433.67  4765.8  431.84  4771.3  432.08  4789.0  430.69
  4794.4  430.94  4812.1  429.20  4817.6  429.51  4840.7  428.00  4879.7  424.28
  4892.4  424.02  4900.4  422.41  4907.1  421.13  4907.6  420.33  4912.6  420.33
  4913.1  421.13  5126.3  421.15  5134.7  422.41  5147.9  423.66  5153.7  424.75
  5169.5  425.39  5175.2  426.61  5191.0  426.60  5196.8  428.20  5206.8  428.19
  5212.6  430.77  5228.3  431.12  5234.1  431.95  5249.9  431.57  5292.9  432.90
#Mann=3,-1,0
  4664.5    0.05       0  4907.1   0.033       0  4913.1    0.05       0
Bank Sta=4900.4,5134.7
Exp/Cntr=0.3,0.1

Type RM Length L Ch R = 1,775,180,180,180
BEGIN DESCRIPTION:
UNT 017 in Running Cr Watershed 2.0
END DESCRIPTION:
XS GIS Cut Line= 3
      2836598.54      7008678.51      2836875.91      7008373.78
      2837075.00      7008075.00
#Sta/Elev= 30
  4544.2  432.27  4565.2  432.39  4579.4  433.12  4636.2  432.58  4657.1  431.75
  4664.5  431.08  4671.3  431.01  4678.7  430.21  4699.7  428.95  4763.9  424.21
  4770.6  423.88  4792.3  424.09  4799.0  423.17  4802.9  422.15  4805.9  421.35
  4810.2  421.13  4810.7  420.33  4815.7  420.33  4816.2  421.13  5049.4  421.13
  5055.4  421.17  5060.4  422.15  5070.4  423.88  5091.4  425.51  5106.5  427.25
  5184.6  432.52  5220.6  433.77  5229.7  433.58  5286.7  434.31  5315.3  434.30
#Mann=3,-1,0
  4544.2    0.05       0  4810.2   0.033       0  4816.2    0.05       0
Bank Sta=4802.9,5060.4
Exp/Cntr=0.3,0.1

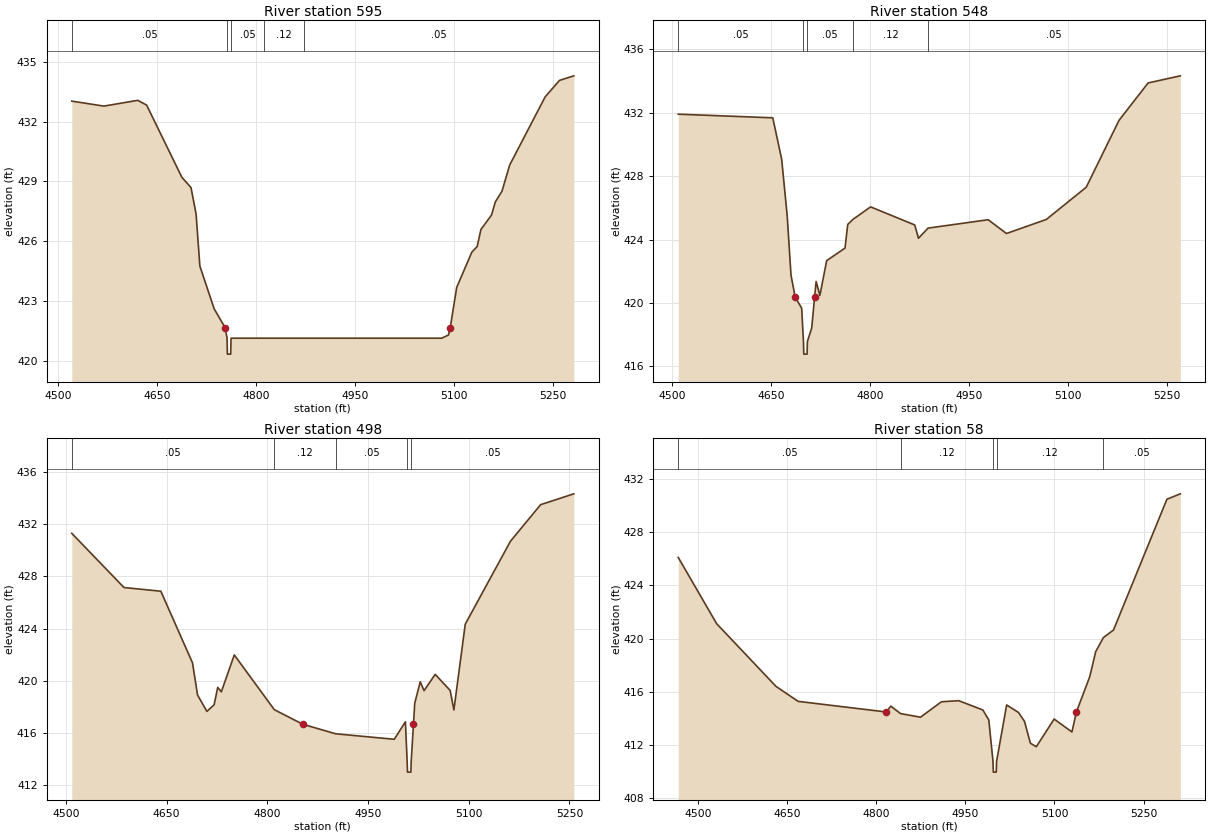
Type RM Length L Ch R = 1,595,47,47,47
BEGIN DESCRIPTION:
Mapping XS f655909a
END DESCRIPTION:
XS GIS Cut Line= 4
      2836835.55      7008791.75      2836948.83      7008593.83
      2837037.37      7008440.19      2837210.01      7008129.96
#Sta/Elev= 30
  4520.9  433.03  4569.6  432.78  4620.9  433.07  4634.3  432.83  4687.6  429.21
  4701.5  428.69  4709.2  427.36  4714.9  424.75  4736.5  422.61  4753.1  421.66
  4756.1  421.13  4756.6  420.33  4761.6  420.33  4762.1  421.13  4812.7  421.13
  4872.3  421.13  5081.2  421.13  5091.5  421.29  5094.1  421.66  5103.9  423.68
  5126.8  425.45  5134.9  425.73  5140.6  426.59  5156.6  427.31  5162.4  427.97
  5172.5  428.51  5184.1  429.82  5237.8  433.24  5259.5  434.07  5281.3  434.30
#Mann=5,-1,0
  4520.9    0.05       0  4756.1    0.03       0  4762.1    0.05       0
  4812.7    0.12       0  4872.3    0.05       0
Bank Sta=4753.1,5094.1
Exp/Cntr=0.3,0.1

Type RM Length L Ch R = 1,548,50,50,50
BEGIN DESCRIPTION:
Mapping XS 8df9e7f2
END DESCRIPTION:
XS GIS Cut Line= 4
      2836890.24      7008822.99      2837013.94      7008593.83
      2837101.17      7008420.66      2837244.01      7008149.27
#Sta/Elev= 30
  4509.5  431.91  4652.8  431.68  4666.3  429.06  4674.7  425.48  4680.4  421.76
  4686.8  420.36  4696.6  419.67  4699.3  417.57  4699.8  416.77  4704.8  416.77
  4705.3  417.57  4711.8  418.41  4716.2  420.36  4718.5  421.35  4724.2  420.48
  4734.5  422.67  4762.3  423.46  4766.4  424.95  4774.5  425.28  4801.1  426.06
  4868.0  424.92  4873.6  424.08  4888.1  424.72  4979.3  425.25  5007.0  424.38
  5067.5  425.27  5127.9  427.30  5177.6  431.52  5221.7  433.88  5270.5  434.33
#Mann=5,-1,0
  4509.5    0.05       0  4699.3    0.03       0  4705.3    0.05       0
  4774.5    0.12       0  4888.1    0.05       0
Bank Sta=4686.8,4716.2
Exp/Cntr=0.3,0.1

Type RM Length L Ch R = 1,498,440,440,440
BEGIN DESCRIPTION:
Mapping XS fa1e008e
END DESCRIPTION:
XS GIS Cut Line= 4
      2836972.27      7008852.94      2837082.95      7008563.89
      2837194.92      7008346.44      2837280.42      7008172.85
#Sta/Elev= 30
  4508.9  431.31  4586.7  427.15  4641.5  426.87  4688.7  421.37  4696.2  418.91
  4710.1  417.65  4720.9  418.16  4726.2  419.49  4731.6  419.15  4750.9  421.98
  4810.5  417.78  4853.0  416.66  4902.0  415.93  4989.1  415.51  5005.7  416.85
  5008.3  413.79  5008.8  412.99  5013.8  412.99  5014.3  413.79  5017.7  416.66
  5019.6  418.28  5027.8  419.92  5033.5  419.24  5050.0  420.49  5072.3  419.26
  5077.9  417.76  5094.8  424.34  5162.2  430.71  5207.1  433.51  5256.5  434.34
#Mann=5,-1,0
  4508.9    0.05       0  4810.5    0.12       0  4902.0    0.05       0
  5008.3    0.03       0  5014.3    0.05       0
Bank Sta=4853,5017.7
Exp/Cntr=0.3,0.1

Type RM Length L Ch R = 1,58,0,0,0
BEGIN DESCRIPTION:
UNT 017 in Running Cr Watershed 1.0
END DESCRIPTION:
XS GIS Cut Line= 3
      2837113.53      7008835.27      2837500.70      7008543.60
      2837509.38      7008182.44
#Sta/Elev= 30
  4466.0  426.11  4530.7  421.13  4630.6  416.42  4668.0  415.29  4816.8  414.49
  4824.2  414.93  4840.6  414.37  4874.2  414.10  4909.6  415.26  4938.7  415.34
  4979.3  414.64  4989.3  413.89  4996.4  410.77  4996.9  409.97  5001.9  409.97
  5002.4  410.77  5019.4  415.02  5039.4  414.45  5049.4  413.79  5059.4  412.14
  5069.4  411.88  5099.4  413.96  5129.4  412.99  5136.9  414.49  5159.4  417.14
  5169.4  419.02  5182.3  420.08  5199.4  420.65  5289.4  430.48  5312.0  430.89
#Mann=5,-1,0
  4466.0    0.05       0  4840.6    0.12       0  4996.4    0.07       0
  5002.4    0.12       0  5182.3    0.05       0
Bank Sta=4816.8,5136.9
Exp/Cntr=0.3,0.1

Chan Stop Cuts=-1