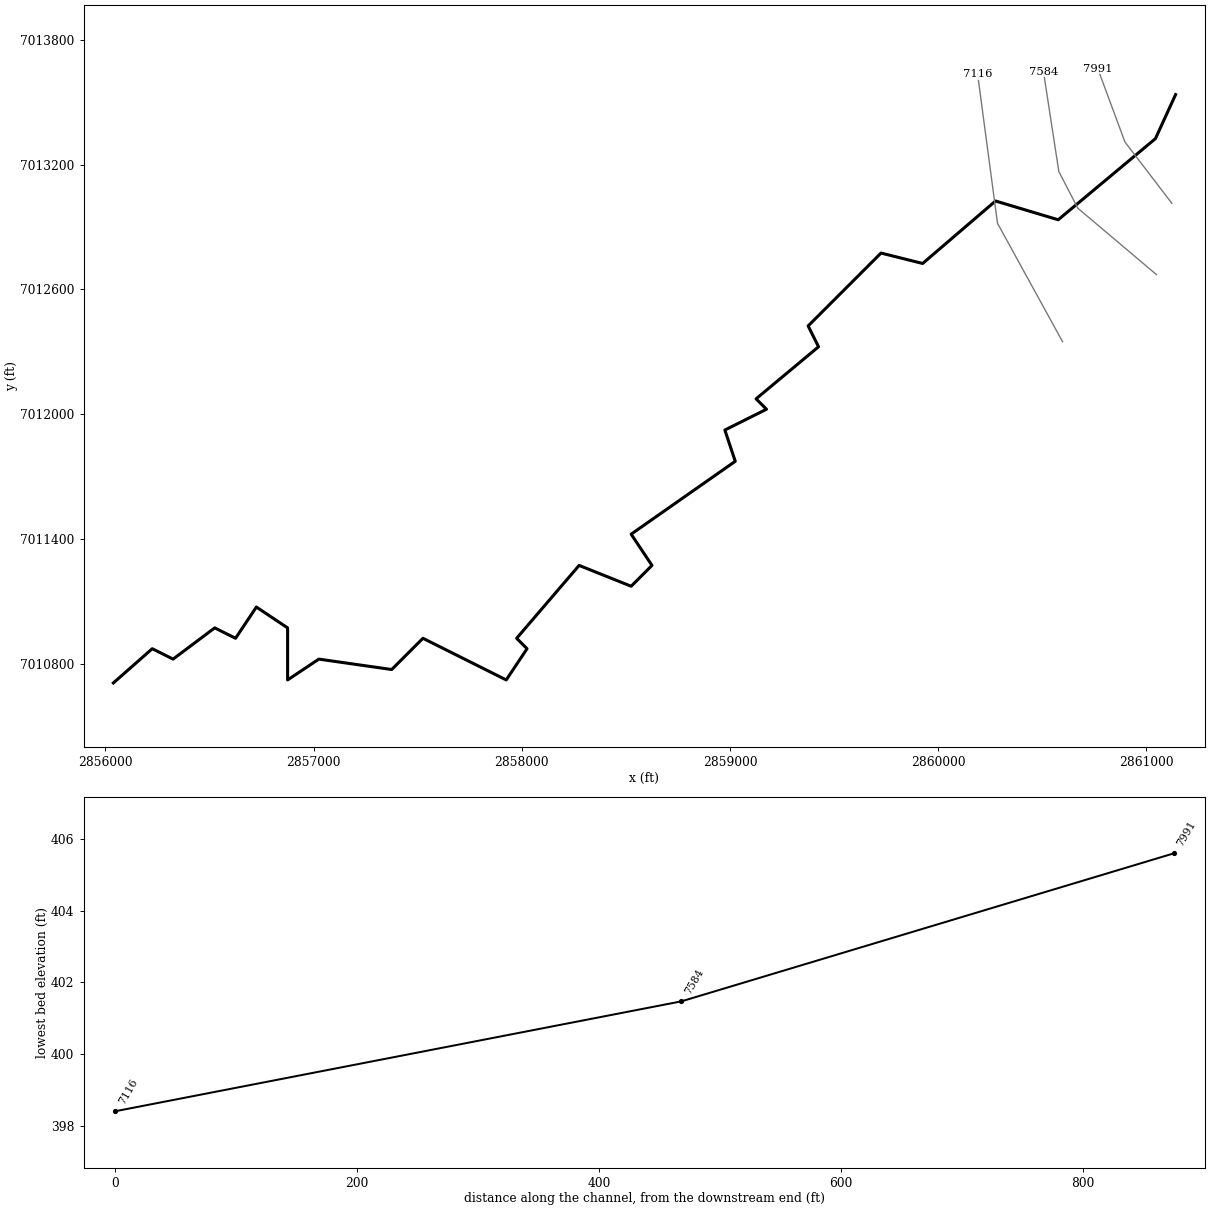
--- UNT 018 in Running Cr Watershed.prj (project) ---

Proj Title=UNT 018 in Running Cr Watershed Base Level Engineering
Current Plan=p01
Default Exp/Contr=0.3,0.1
English Units
Geom File=g01
Flow File=f01
Plan File=p01
BEGIN DESCRIPTION:
UNT 018 in Running Cr Watershed
END DESCRIPTION:

--- UNT 018 in Running Cr Watershed.p01 (plan) ---

Plan Title=Multiple Run
Short Identifier=Multiple
Geom File=g01
Flow File=f01
Subcritical Flow
K Sum by GR= 0
Std Step Tol= 0.01
Critical Tol= 0.01
Num of Std Step Trials= 20
Max Error Tol= 0.3
Flow Tol Ratio= 0.001
Split Flow NTrial= 30
Split Flow Tol= 0.02
Split Flow Ratio= 0.02
Log Output Level= 0
Friction Slope Method= 1
Unsteady Friction Slope Method= 2
Unsteady Bridges Friction Slope Method= 1
Parabolic Critical Depth
Global Vel Dist=  1 , 1 , 1
Global Log Level= 0
CheckData=True
Encroach Param= -1, 0, 0, 0
BEGIN DESCRIPTION:
Multiple Run
END DESCRIPTION:

--- UNT 018 in Running Cr Watershed.f01 (steady flow) ---

Flow Title=Multiple
Number of Profiles=7
Profile Names=10-year,25-year,50-year,1pct_min,100-year,1pct_plu,500-year
River Rch & RM= UNT 018 in Runni,Reach-1,7991
     264     334     388     225     449     896     600
Boundary for River Rch & Prof#=UNT 018 in Runni,Reach-1,1
Up Type=0
Dn Type=3
Dn Slope=0.005
Boundary for River Rch & Prof#=UNT 018 in Runni,Reach-1,2
Up Type=0
Dn Type=3
Dn Slope=0.005
Boundary for River Rch & Prof#=UNT 018 in Runni,Reach-1,3
Up Type=0
Dn Type=3
Dn Slope=0.005
Boundary for River Rch & Prof#=UNT 018 in Runni,Reach-1,4
Up Type=0
Dn Type=3
Dn Slope=0.005
Boundary for River Rch & Prof#=UNT 018 in Runni,Reach-1,5
Up Type=0
Dn Type=3
Dn Slope=0.005
Boundary for River Rch & Prof#=UNT 018 in Runni,Reach-1,6
Up Type=0
Dn Type=3
Dn Slope=0.005
Boundary for River Rch & Prof#=UNT 018 in Runni,Reach-1,7
Up Type=0
Dn Type=3
Dn Slope=0.005

--- UNT 018 in Running Cr Watershed.g01 (geometry) ---

Geom Title=Existing Conditions

River Reach=UNT 018 in Runni,Reach-1
Reach XY= 30
      2861139.88      7013536.10      2861043.00      7013324.46
      2860575.99      7012934.88      2860275.00      7013025.00
      2859925.00      7012725.00      2859725.00      7012775.00
      2859375.00      7012425.00      2859425.00      7012325.00
      2859125.00      7012075.00      2859175.00      7012025.00
      2858975.00      7011925.00      2859025.00      7011775.00
      2858525.00      7011425.00      2858625.00      7011275.00
      2858525.00      7011175.00      2858275.00      7011275.00
      2857975.00      7010925.00      2858025.00      7010875.00
      2857925.00      7010725.00      2857525.00      7010925.00
      2857375.00      7010775.00      2857025.00      7010825.00
      2856875.00      7010725.00      2856875.00      7010975.00
      2856725.00      7011075.00      2856625.00      7010925.00
      2856525.00      7010975.00      2856325.00      7010825.00
      2856225.00      7010875.00      2856038.12      7010710.53

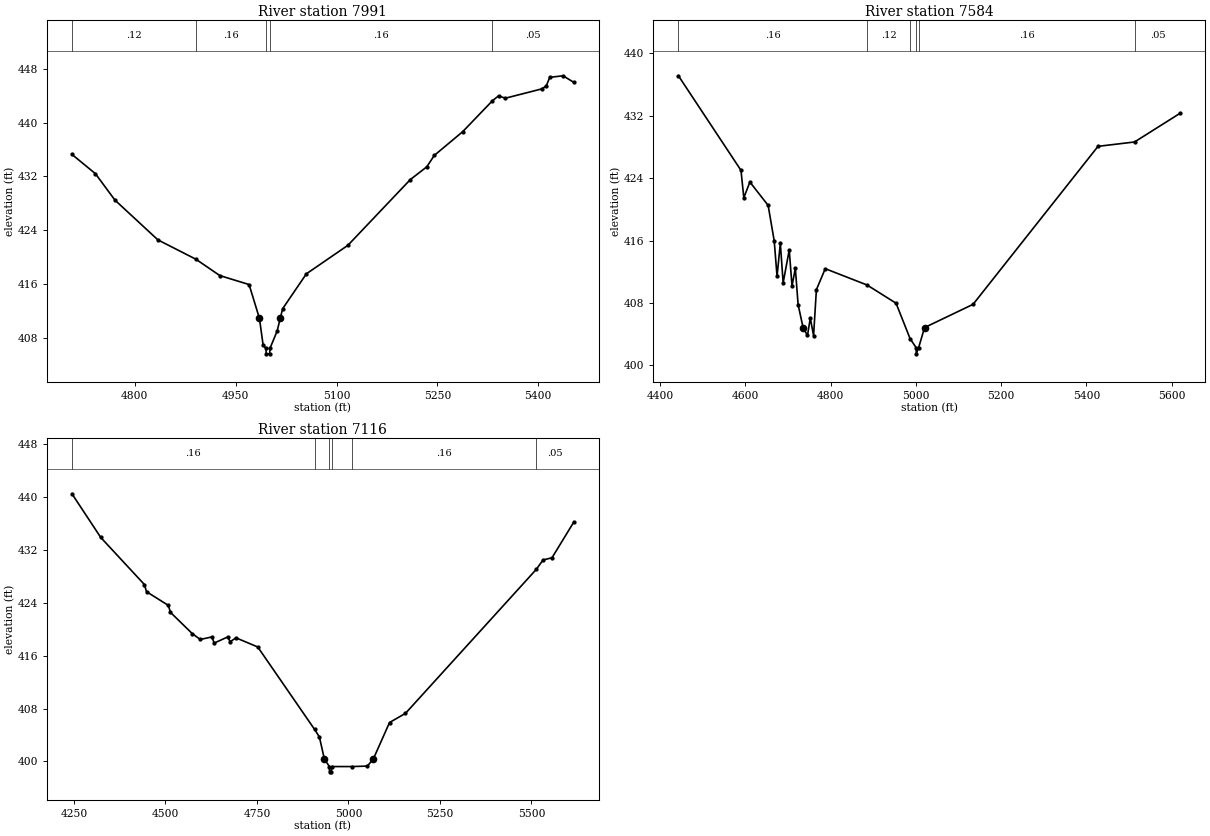
Type RM Length L Ch R = 1,7991,407,407,407
BEGIN DESCRIPTION:
UNT 018 in Running Cr Watershed 11.0
END DESCRIPTION:
XS GIS Cut Line= 3
      2861122.11      7013013.49      2860896.43      7013308.61
      2860766.27      7013660.05
#Sta/Elev= 30
  4706.6  435.27  4741.5  432.40  4770.5  428.47  4834.4  422.55  4890.9  419.67
  4926.4  417.24  4970.0  415.90  4985.4  410.86  4990.8  406.94  4995.0  406.39
  4995.5  405.59  5000.5  405.59  5001.0  406.39  5011.7  408.98  5016.3  410.86
  5019.9  412.31  5055.2  417.50  5116.9  421.74  5209.7  431.52  5234.2  433.42
  5245.4  435.12  5287.6  438.65  5331.8  443.25  5340.9  443.98  5351.0  443.63
  5404.9  445.01  5411.8  445.45  5417.1  446.74  5436.8  446.97  5452.9  445.99
#Mann=5,-1,0
  4706.6    0.12       0  4890.9    0.16       0  4995.0    0.07       0
  5001.0    0.16       0  5331.8    0.05       0
Bank Sta=4985.4,5016.3
Exp/Cntr=0.3,0.1

Type RM Length L Ch R = 1,7584,468,468,468
BEGIN DESCRIPTION:
Mapping XS c71083ca
END DESCRIPTION:
XS GIS Cut Line= 4
      2861047.77      7012671.54      2860670.19      7012990.54
      2860579.04      7013166.32      2860505.26      7013645.87
#Sta/Elev= 30
  4442.7  437.13  4589.5  425.00  4596.1  421.49  4610.4  423.50  4653.2  420.51
  4667.5  415.93  4674.1  411.40  4681.8  415.65  4688.4  410.58  4702.7  414.79
  4709.2  410.17  4717.0  412.44  4723.5  407.79  4735.1  404.84  4745.5  403.83
  4752.1  406.04  4759.8  403.81  4766.4  409.70  4787.2  412.39  4885.2  410.30
  4953.3  407.96  4986.2  403.42  5000.3  402.27  5000.8  401.47  5006.3  402.27
  5020.2  404.84  5134.0  407.82  5427.1  428.08  5512.8  428.64  5620.2  432.34
#Mann=6,-1,0
  4442.7    0.16       0  4885.2    0.12       0  4986.2    0.16       0
  5000.3    0.07       0  5006.3    0.16       0  5512.8    0.05       0
Bank Sta=4735.1,5020.2
Exp/Cntr=0.3,0.1

Type RM Length L Ch R = 1,7116,0,0,0
BEGIN DESCRIPTION:
UNT 018 in Running Cr Watershed 10.0
END DESCRIPTION:
XS GIS Cut Line= 3
      2860596.96      7012349.40      2860284.45      7012917.99
      2860188.96      7013634.14
#Sta/Elev= 30
  4244.6  440.53  4323.2  433.92  4442.6  426.78  4448.3  425.70  4508.0  423.62
  4513.7  422.57  4573.3  419.35  4595.1  418.46  4627.3  418.85  4633.0  417.91
  4670.9  418.86  4676.6  418.10  4692.7  418.71  4752.3  417.32  4907.6  404.83
  4920.7  403.69  4934.1  400.38  4947.9  399.21  4948.4  398.41  4953.4  398.41
  4953.9  399.21  5009.1  399.21  5051.8  399.28  5068.2  400.38  5112.3  405.88
  5155.9  407.27  5513.1  429.07  5531.7  430.50  5556.2  430.84  5615.9  436.26
#Mann=6,-1,0
  4244.6    0.16       0  4907.6    0.05       0  4947.9   0.033       0
  4953.9    0.05       0  5009.1    0.16       0  5513.1    0.05       0
Bank Sta=4934.1,5068.2
Exp/Cntr=0.3,0.1

Chan Stop Cuts=-1