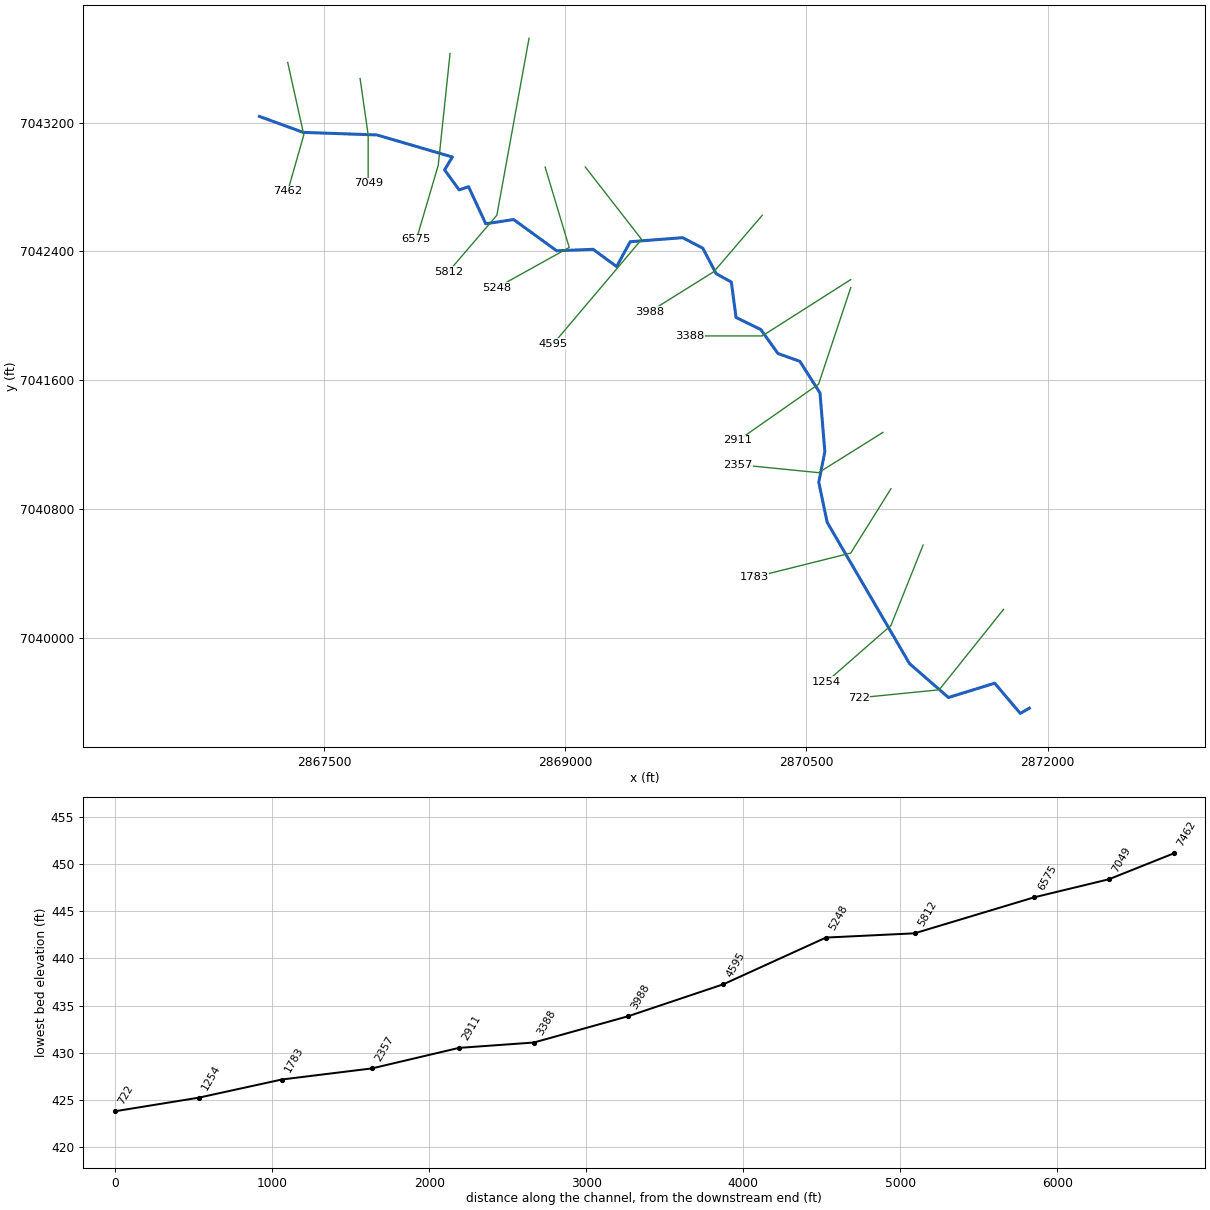
--- UNT 019 in Running Cr Watershed.prj (project) ---

Proj Title=UNT 019 in Running Cr Watershed Base Level Engineering
Current Plan=p01
Default Exp/Contr=0.3,0.1
English Units
Geom File=g01
Flow File=f01
Plan File=p01
BEGIN DESCRIPTION:
UNT 019 in Running Cr Watershed
END DESCRIPTION:

--- UNT 019 in Running Cr Watershed.p01 (plan) ---

Plan Title=Multiple Run
Short Identifier=Multiple
Geom File=g01
Flow File=f01
Subcritical Flow
K Sum by GR= 0
Std Step Tol= 0.01
Critical Tol= 0.01
Num of Std Step Trials= 20
Max Error Tol= 0.3
Flow Tol Ratio= 0.001
Split Flow NTrial= 30
Split Flow Tol= 0.02
Split Flow Ratio= 0.02
Log Output Level= 0
Friction Slope Method= 1
Unsteady Friction Slope Method= 2
Unsteady Bridges Friction Slope Method= 1
Parabolic Critical Depth
Global Vel Dist=  1 , 1 , 1
Global Log Level= 0
CheckData=True
Encroach Param= -1, 0, 0, 0
BEGIN DESCRIPTION:
Multiple Run
END DESCRIPTION:

--- UNT 019 in Running Cr Watershed.f01 (steady flow) ---

Flow Title=Multiple
Number of Profiles=7
Profile Names=10-year,25-year,50-year,1pct_min,100-year,1pct_plu,500-year
River Rch & RM= UNT 019 in Runni,Reach-1,7462
     564     752     905     542    1081    2156    1542
River Rch & RM= UNT 019 in Runni,Reach-1,6575
     773    1047    1271     766    1529    3051    2217
Boundary for River Rch & Prof#=UNT 019 in Runni,Reach-1,1
Up Type=0
Dn Type=3
Dn Slope=0.005
Boundary for River Rch & Prof#=UNT 019 in Runni,Reach-1,2
Up Type=0
Dn Type=3
Dn Slope=0.005
Boundary for River Rch & Prof#=UNT 019 in Runni,Reach-1,3
Up Type=0
Dn Type=3
Dn Slope=0.005
Boundary for River Rch & Prof#=UNT 019 in Runni,Reach-1,4
Up Type=0
Dn Type=3
Dn Slope=0.005
Boundary for River Rch & Prof#=UNT 019 in Runni,Reach-1,5
Up Type=0
Dn Type=3
Dn Slope=0.005
Boundary for River Rch & Prof#=UNT 019 in Runni,Reach-1,6
Up Type=0
Dn Type=3
Dn Slope=0.005
Boundary for River Rch & Prof#=UNT 019 in Runni,Reach-1,7
Up Type=0
Dn Type=3
Dn Slope=0.005

--- UNT 019 in Running Cr Watershed.g01 (geometry) ---

Geom Title=Existing Conditions

River Reach=UNT 019 in Runni,Reach-1
Reach XY= 30
      2867099.28      7043239.58      2867371.29      7043140.34
      2867829.53      7043124.41      2868298.80      7042987.18
      2868249.79      7042907.54      2868340.30      7042783.22
      2868399.26      7042802.37      2868505.96      7042572.21
      2868679.62      7042598.51      2868947.00      7042404.13
      2869173.48      7042413.37      2869319.48      7042306.30
      2869404.30      7042460.64      2869730.59      7042485.71
      2869855.64      7042420.13      2869938.22      7042262.25
      2870032.91      7042209.72      2870061.97      7041989.90
      2870216.36      7041914.38      2870322.79      7041765.45
      2870458.74      7041717.08      2870584.01      7041520.00
      2870614.17      7041155.65      2870576.26      7040965.81
      2870628.31      7040716.74      2871140.46      7039837.90
      2871382.53      7039627.16      2871670.05      7039716.09
      2871829.22      7039528.46      2871885.59      7039560.71

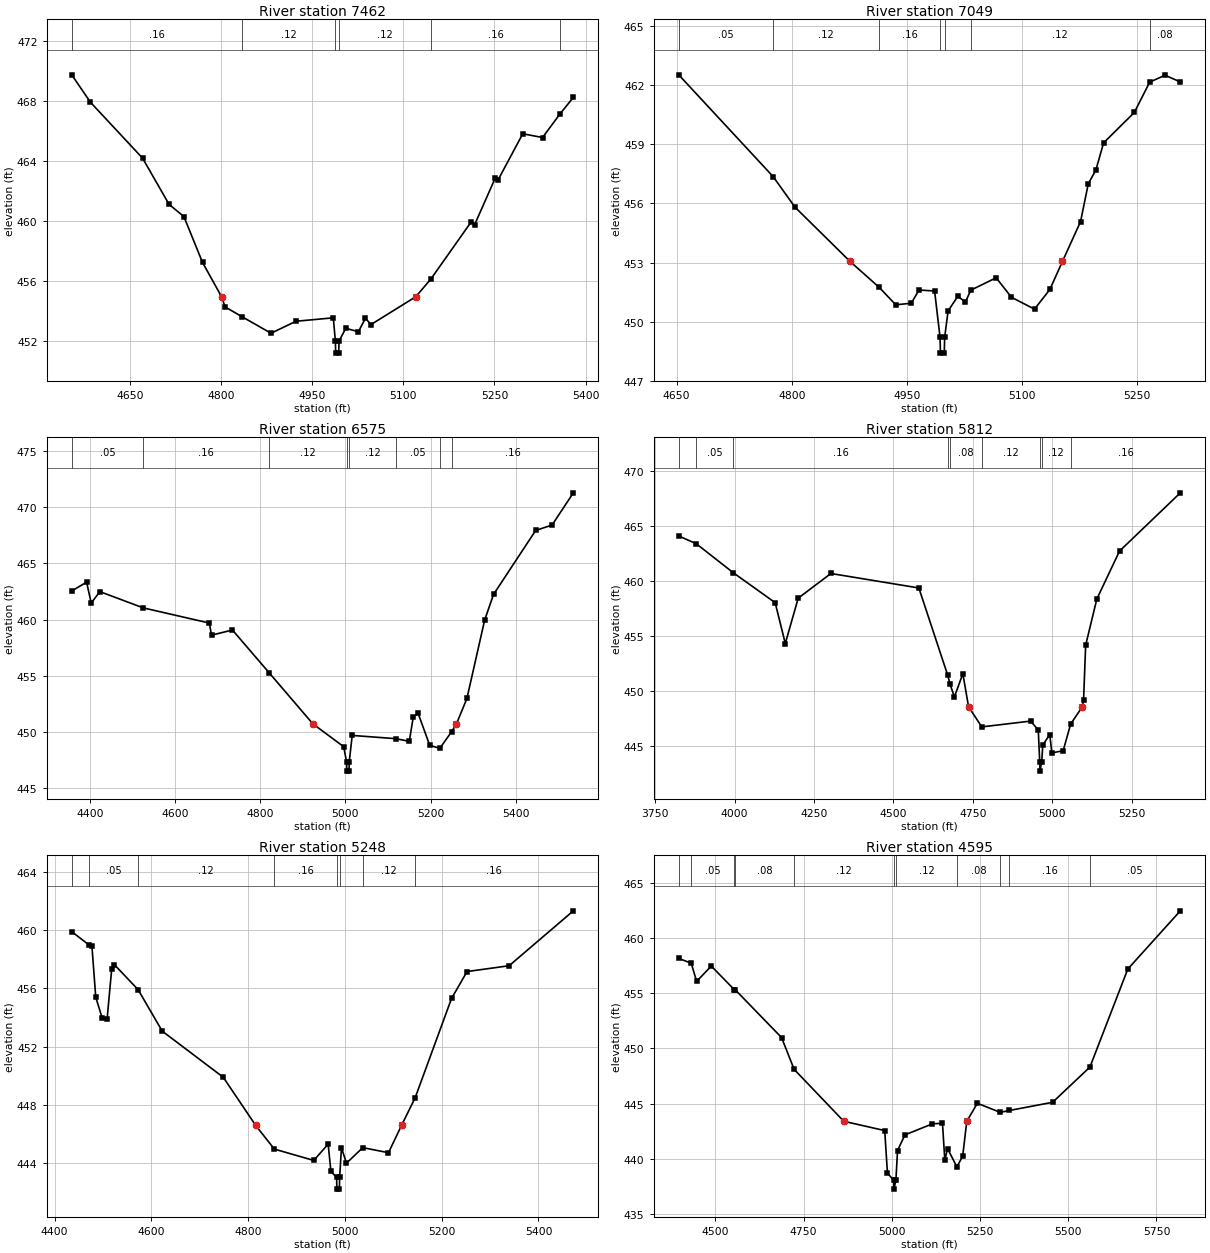
Type RM Length L Ch R = 1,7462,413,413,413
BEGIN DESCRIPTION:
UNT 019 in Running Cr Watershed 13.0
END DESCRIPTION:
XS GIS Cut Line= 3
      2867275.00      7043574.99      2867375.00      7043125.00
      2867274.99      7042774.97
#Sta/Elev= 30
  4554.7  469.76  4585.4  467.93  4671.2  464.19  4714.8  461.10  4739.1  460.29
  4769.8  457.22  4801.1  454.93  4806.9  454.25  4834.9  453.59  4882.5  452.49
  4923.5  453.29  4984.9  453.52  4988.3  451.96  4988.8  451.16  4993.8  451.16
  4994.3  451.96  5005.4  452.82  5026.1  452.59  5037.8  453.49  5046.9  453.07
  5120.6  454.93  5145.7  456.13  5212.0  459.95  5217.2  459.73  5251.0  462.84
  5256.2  462.76  5296.5  465.82  5329.0  465.57  5358.0  467.16  5379.7  468.25
#Mann=6,-1,0
  4554.7    0.16       0  4834.9    0.12       0  4988.3    0.07       0
  4994.3    0.12       0  5145.7    0.16       0  5358.0    0.05       0
Bank Sta=4801.1,5120.6
Exp/Cntr=0.3,0.1

Type RM Length L Ch R = 1,7049,474,474,474
BEGIN DESCRIPTION:
UNT 019 in Running Cr Watershed 12.0
END DESCRIPTION:
XS GIS Cut Line= 3
      2867725.00      7043475.00      2867775.00      7043125.00
      2867775.00      7042824.95
#Sta/Elev= 30
  4652.7  462.52  4775.7  457.36  4804.2  455.81  4875.9  453.06  4914.0  451.74
  4935.5  450.86  4955.7  450.94  4965.8  451.61  4986.1  451.56  4993.2  449.21
  4993.7  448.41  4998.7  448.41  4999.2  449.21  5003.7  450.55  5016.3  451.29
  5026.3  451.00  5033.2  451.60  5066.3  452.23  5086.3  451.24  5116.3  450.64
  5136.3  451.64  5152.7  453.06  5176.3  455.08  5186.3  456.99  5196.3  457.70
  5206.3  459.07  5246.3  460.61  5266.4  462.15  5286.3  462.50  5306.3  462.16
#Mann=7,-1,0
  4652.7    0.05       0  4775.7    0.12       0  4914.0    0.16       0
  4993.2    0.07       0  4999.2    0.16       0  5033.2    0.12       0
  5266.4    0.08       0
Bank Sta=4875.9,5152.7
Exp/Cntr=0.3,0.1

Type RM Length L Ch R = 1,6575,763,763,763
BEGIN DESCRIPTION:
UNT 019 in Running Cr Watershed 11.0
END DESCRIPTION:
XS GIS Cut Line= 3
      2868284.11      7043630.59      2868210.68      7042935.90
      2868075.01      7042475.02
#Sta/Elev= 30
  4356.7  462.55  4391.6  463.33  4402.5  461.47  4422.7  462.49  4524.9  461.04
  4680.1  459.69  4685.2  458.61  4734.4  459.07  4820.7  455.26  4923.5  450.71
  4995.8  448.68  5002.8  447.30  5003.3  446.50  5008.4  446.50  5008.9  447.30
  5015.9  449.68  5119.1  449.39  5150.0  449.15  5159.6  451.35  5170.9  451.64
  5198.1  448.80  5221.8  448.53  5249.5  450.01  5261.0  450.71  5285.5  452.97
  5327.2  459.95  5348.1  462.24  5447.2  467.94  5485.7  468.42  5535.7  471.29
#Mann=8,-1,0
  4356.7    0.05       0  4524.9    0.16       0  4820.7    0.12       0
  5002.8    0.07       0  5008.9    0.12       0  5119.1    0.05       0
  5221.8    0.12       0  5249.5    0.16       0
Bank Sta=4923.5,5261
Exp/Cntr=0.3,0.1

Type RM Length L Ch R = 1,5812,564,564,564
BEGIN DESCRIPTION:
UNT 019 in Running Cr Watershed 10.0
END DESCRIPTION:
XS GIS Cut Line= 3
      2868775.00      7043725.00      2868575.00      7042625.00
      2868275.01      7042275.01
#Sta/Elev= 30
  3824.1  464.10  3879.3  463.39  3996.2  460.74  4127.7  458.02  4159.5  454.30
  4200.2  458.43  4303.1  460.68  4580.0  459.36  4670.8  451.41  4678.2  450.59
  4691.8  449.43  4718.5  451.55  4736.4  448.54  4778.1  446.70  4932.0  447.23
  4955.9  446.41  4960.5  443.47  4961.0  442.67  4966.6  443.47  4970.1  445.05
  4992.1  446.00  4998.7  444.33  5034.3  444.53  5057.7  446.95  5094.6  448.54
  5098.5  449.16  5105.1  454.15  5140.2  458.35  5211.6  462.72  5403.1  468.03
#Mann=9,-1,0
  3824.1    0.16       0  3879.3    0.05       0  3996.2    0.16       0
  4670.8    0.12       0  4678.2    0.08       0  4778.1    0.12       0
  4960.5    0.07       0  4966.6    0.12       0  5057.7    0.16       0
Bank Sta=4736.4,5094.6
Exp/Cntr=0.3,0.1

Type RM Length L Ch R = 1,5248,653,653,653
BEGIN DESCRIPTION:
UNT 019 in Running Cr Watershed 9.0
END DESCRIPTION:
XS GIS Cut Line= 3
      2868875.01      7042924.98      2869025.00      7042425.00
      2868574.98      7042174.99
#Sta/Elev= 30
  4435.3  459.90  4470.9  458.99  4477.0  458.92  4484.9  455.40  4497.9  454.00
  4508.4  453.90  4517.9  457.34  4523.2  457.64  4572.4  455.92  4622.3  453.07
  4748.5  449.90  4815.6  446.59  4854.0  444.97  4935.5  444.19  4965.3  445.31
  4971.0  443.44  4982.8  443.02  4983.3  442.22  4988.5  442.22  4989.0  443.02
  4992.8  445.06  5003.1  444.00  5036.9  445.07  5090.0  444.72  5116.9  446.59
  5145.2  448.50  5220.4  455.32  5252.4  457.16  5339.4  457.56  5472.1  461.33
#Mann=8,-1,0
  4435.3    0.16       0  4470.9    0.05       0  4572.4    0.12       0
  4854.0    0.16       0  4982.8    0.07       0  4989.0    0.16       0
  5036.9    0.12       0  5145.2    0.16       0
Bank Sta=4815.6,5116.9
Exp/Cntr=0.3,0.1

Type RM Length L Ch R = 1,4595,607,607,607
BEGIN DESCRIPTION:
UNT 019 in Running Cr Watershed 8.0
END DESCRIPTION:
XS GIS Cut Line= 3
      2869124.99      7042925.02      2869475.00      7042475.00
      2868924.99      7041824.98
#Sta/Elev= 30
  4396.0  458.14  4431.5  457.71  4446.7  456.06  4488.3  457.45  4553.3  455.32
  4556.8  455.28  4687.4  450.98  4723.1  448.10  4863.8  443.40  4979.8  442.56
  4987.5  438.71  5005.3  438.06  5005.8  437.26  5011.5  438.06  5016.1  440.75
  5037.0  442.17  5115.0  443.17  5143.5  443.22  5150.1  439.86  5157.8  440.93
  5184.2  439.28  5200.7  440.23  5212.3  443.40  5242.4  445.03  5307.1  444.21
  5333.4  444.38  5455.6  445.12  5561.4  448.31  5668.7  457.18  5817.6  462.45
#Mann=11,-1,0
  4396.0    0.08       0  4431.5    0.05       0  4553.3    0.12       0
  4556.8    0.08       0  4723.1    0.12       0  5005.3    0.07       0
  5011.5    0.12       0  5184.2    0.08       0  5307.1    0.05       0
  5333.4    0.16       0  5561.4    0.05       0
Bank Sta=4863.8,5212.3
Exp/Cntr=0.3,0.1

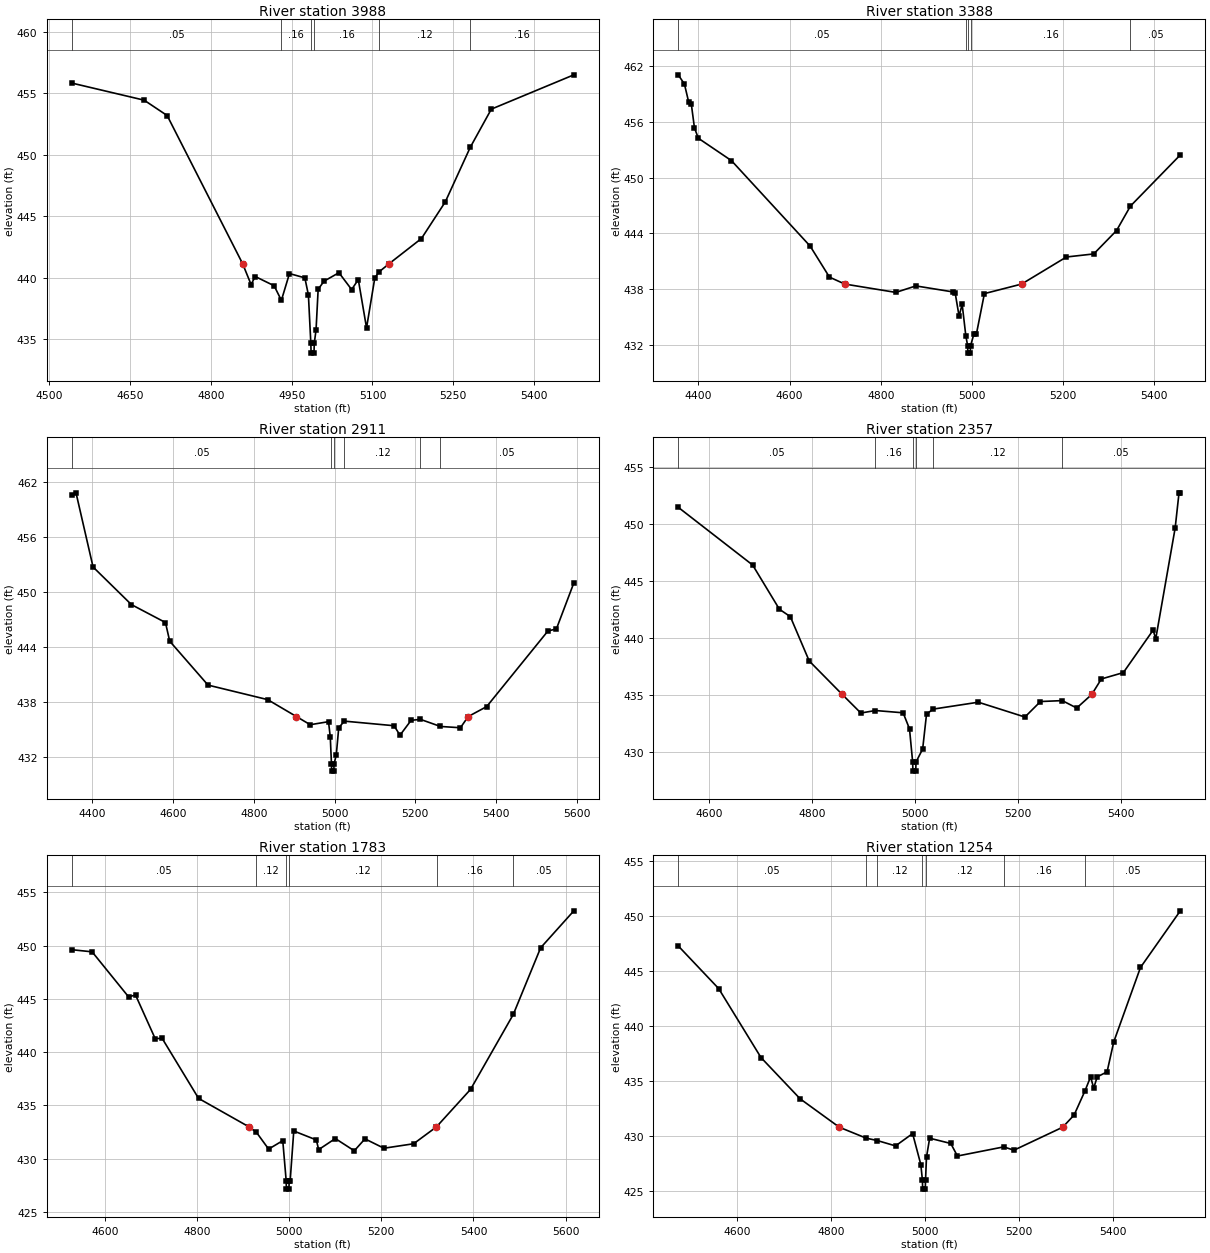
Type RM Length L Ch R = 1,3988,600,600,600
BEGIN DESCRIPTION:
UNT 019 in Running Cr Watershed 7.0
END DESCRIPTION:
XS GIS Cut Line= 3
      2870225.00      7042624.99      2869925.00      7042275.00
      2869524.97      7042024.98
#Sta/Elev= 30
  4541.4  455.82  4675.8  454.43  4718.6  453.18  4858.7  441.14  4874.5  439.44
  4882.2  440.09  4917.3  439.34  4930.8  438.15  4945.8  440.33  4974.4  439.98
  4981.0  438.59  4985.5  434.66  4986.0  433.86  4991.4  433.86  4991.9  434.66
  4995.2  435.75  4999.1  439.05  5010.0  439.71  5037.7  440.40  5061.3  439.03
  5073.7  439.84  5089.0  435.91  5104.4  439.99  5112.6  440.48  5131.2  441.14
  5191.0  443.18  5235.3  446.16  5281.6  450.59  5320.8  453.70  5474.1  456.49
#Mann=6,-1,0
  4541.4    0.05       0  4930.8    0.16       0  4985.5    0.07       0
  4991.9    0.16       0  5112.6    0.12       0  5281.6    0.16       0
Bank Sta=4858.7,5131.2
Exp/Cntr=0.3,0.1

Type RM Length L Ch R = 1,3388,477,477,477
BEGIN DESCRIPTION:
UNT 019 in Running Cr Watershed 6.0
END DESCRIPTION:
XS GIS Cut Line= 3
      2870775.04      7042225.02      2870225.00      7041875.00
      2869774.97      7041875.00
#Sta/Elev= 30
  4355.6  461.09  4369.2  460.09  4378.5  458.16  4384.4  457.90  4391.2  455.37
  4399.7  454.25  4472.5  451.83  4645.2  442.61  4687.5  439.27  4721.2  438.52
  4833.2  437.62  4877.2  438.32  4957.6  437.68  4963.5  437.54  4972.0  435.07
  4978.8  436.33  4986.8  432.95  4990.8  431.87  4991.3  431.07  4996.7  431.07
  4997.2  431.87  5004.6  433.14  5010.1  433.14  5027.6  437.49  5109.3  438.52
  5207.6  441.44  5267.6  441.77  5317.6  444.29  5348.1  446.93  5457.6  452.45
#Mann=5,-1,0
  4355.6    0.05       0  4986.8    0.16       0  4990.8    0.07       0
  4997.2    0.16       0  5348.1    0.05       0
Bank Sta=4721.2,5109.3
Exp/Cntr=0.3,0.1

Type RM Length L Ch R = 1,2911,554,554,554
BEGIN DESCRIPTION:
UNT 019 in Running Cr Watershed 5.0
END DESCRIPTION:
XS GIS Cut Line= 3
      2870774.99      7042174.98      2870575.00      7041575.00
      2870074.97      7041224.98
#Sta/Elev= 30
  4349.6  460.52  4360.1  460.78  4402.3  452.71  4497.2  448.62  4581.5  446.67
  4592.0  444.64  4686.9  439.86  4834.5  438.28  4905.6  436.44  4939.9  435.55
  4985.1  435.88  4989.5  434.22  4992.4  431.30  4992.9  430.50  4998.3  430.50
  4998.8  431.30  5004.3  432.24  5010.4  435.21  5024.2  435.94  5147.3  435.44
  5162.1  434.41  5189.6  436.03  5212.8  436.13  5262.2  435.36  5311.6  435.22
  5331.0  436.44  5376.6  437.52  5528.3  445.75  5549.2  445.97  5592.4  450.98
#Mann=6,-1,0
  4349.6    0.05       0  4992.4    0.03       0  4998.8    0.05       0
  5024.2    0.12       0  5212.8    0.16       0  5262.2    0.05       0
Bank Sta=4905.6,5331
Exp/Cntr=0.3,0.1

Type RM Length L Ch R = 1,2357,574,574,574
BEGIN DESCRIPTION:
UNT 019 in Running Cr Watershed 4.0
END DESCRIPTION:
XS GIS Cut Line= 3
      2870974.96      7041274.97      2870575.00      7041025.00
      2870075.04      7041075.00
#Sta/Elev= 30
  4540.6  451.48  4685.0  446.41  4736.9  442.53  4758.1  441.88  4794.7  437.99
  4858.8  435.05  4894.9  433.42  4923.1  433.64  4976.9  433.44  4989.3  432.03
  4995.4  429.12  4995.9  428.32  5001.4  428.32  5001.9  429.12  5014.8  430.26
  5022.3  433.31  5034.7  433.76  5122.8  434.37  5213.2  433.07  5243.4  434.43
  5285.7  434.51  5313.7  433.86  5342.9  435.05  5361.5  436.41  5404.2  436.97
  5462.0  440.70  5467.0  439.93  5504.7  449.66  5512.2  452.75  5514.7  452.75
#Mann=6,-1,0
  4540.6    0.05       0  4923.1    0.16       0  4995.4    0.07       0
  5001.9    0.16       0  5034.7    0.12       0  5285.7    0.05       0
Bank Sta=4858.8,5342.9
Exp/Cntr=0.3,0.1

Type RM Length L Ch R = 1,1783,529,529,529
BEGIN DESCRIPTION:
UNT 019 in Running Cr Watershed 3.0
END DESCRIPTION:
XS GIS Cut Line= 3
      2871024.98      7040924.97      2870775.00      7040525.00
      2870175.02      7040375.01
#Sta/Elev= 30
  4527.8  449.62  4572.0  449.42  4651.0  445.20  4666.3  445.36  4708.8  441.28
  4724.1  441.29  4803.1  435.66  4912.9  432.98  4928.8  432.47  4955.2  430.90
  4985.9  431.69  4993.3  427.94  4993.8  427.14  4999.3  427.14  4999.8  427.94
  5002.0  427.94  5009.8  432.60  5058.7  431.76  5063.9  430.85  5100.0  431.89
  5141.2  430.74  5164.4  431.86  5205.6  430.98  5270.0  431.40  5319.5  432.98
  5319.7  432.99  5393.7  436.51  5486.4  443.54  5545.8  449.80  5617.9  453.27
#Mann=6,-1,0
  4527.8    0.05       0  4928.8    0.12       0  4993.3    0.07       0
  4999.8    0.12       0  5319.7    0.16       0  5486.4    0.05       0
Bank Sta=4912.9,5319.5
Exp/Cntr=0.3,0.1

Type RM Length L Ch R = 1,1254,532,532,532
BEGIN DESCRIPTION:
UNT 019 in Running Cr Watershed 2.0
END DESCRIPTION:
XS GIS Cut Line= 3
      2871225.01      7040575.01      2871025.00      7040075.00
      2870625.03      7039725.02
#Sta/Elev= 30
  4474.1  447.32  4560.3  443.44  4650.5  437.17  4733.9  433.42  4817.3  430.84
  4874.9  429.84  4898.0  429.63  4937.2  429.14  4973.6  430.26  4991.1  427.44
  4994.5  426.01  4995.0  425.21  5000.6  425.21  5001.1  426.01  5003.2  428.13
  5009.9  429.84  5054.9  429.36  5069.1  428.22  5167.8  429.05  5189.6  428.75
  5293.5  430.84  5317.8  431.95  5340.9  434.14  5352.9  435.42  5359.5  434.40
  5367.1  435.42  5388.0  435.87  5402.2  438.59  5459.2  445.36  5544.1  450.51
#Mann=7,-1,0
  4474.1    0.05       0  4874.9    0.16       0  4898.0    0.12       0
  4994.5    0.07       0  5001.1    0.12       0  5167.8    0.16       0
  5340.9    0.05       0
Bank Sta=4817.3,5293.5
Exp/Cntr=0.3,0.1

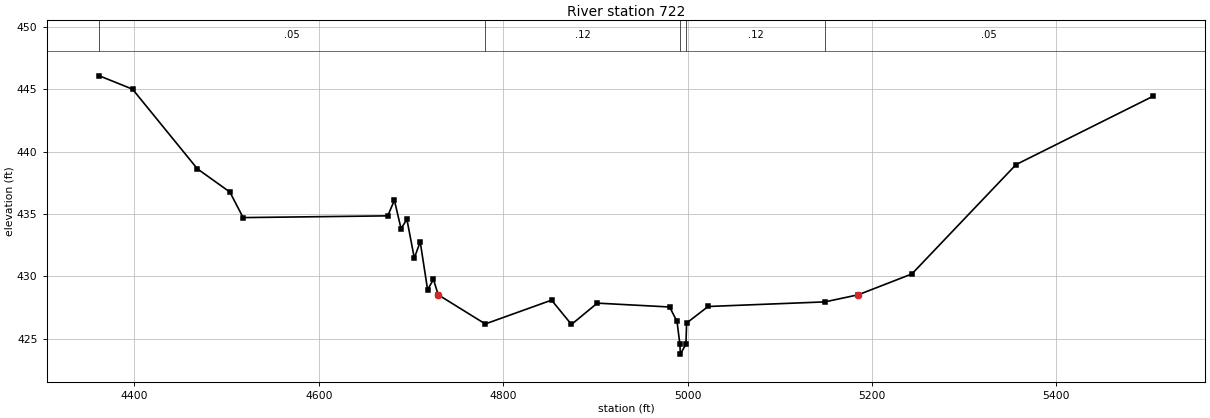
Type RM Length L Ch R = 1,722,0,0,0
BEGIN DESCRIPTION:
UNT 019 in Running Cr Watershed 1.0
END DESCRIPTION:
XS GIS Cut Line= 3
      2871724.98      7040174.98      2871325.00      7039675.00
      2870824.98      7039625.00
#Sta/Elev= 30
  4361.9  446.09  4397.9  445.02  4468.3  438.63  4503.5  436.77  4517.9  434.72
  4674.8  434.86  4682.0  436.11  4689.2  433.84  4695.6  434.57  4703.6  431.47
  4710.0  432.78  4718.0  428.94  4724.4  429.76  4729.5  428.53  4780.6  426.19
  4852.5  428.10  4874.1  426.15  4902.1  427.86  4980.6  427.55  4988.6  426.39
  4991.7  424.57  4992.2  423.77  4998.3  424.57  4999.0  426.26  5022.3  427.59
  5149.1  427.96  5185.2  428.53  5243.4  430.20  5356.4  438.97  5504.7  444.44
#Mann=5,-1,0
  4361.9    0.05       0  4780.6    0.12       0  4991.7    0.07       0
  4998.3    0.12       0  5149.1    0.05       0
Bank Sta=4729.5,5185.2
Exp/Cntr=0.3,0.1

Chan Stop Cuts=-1