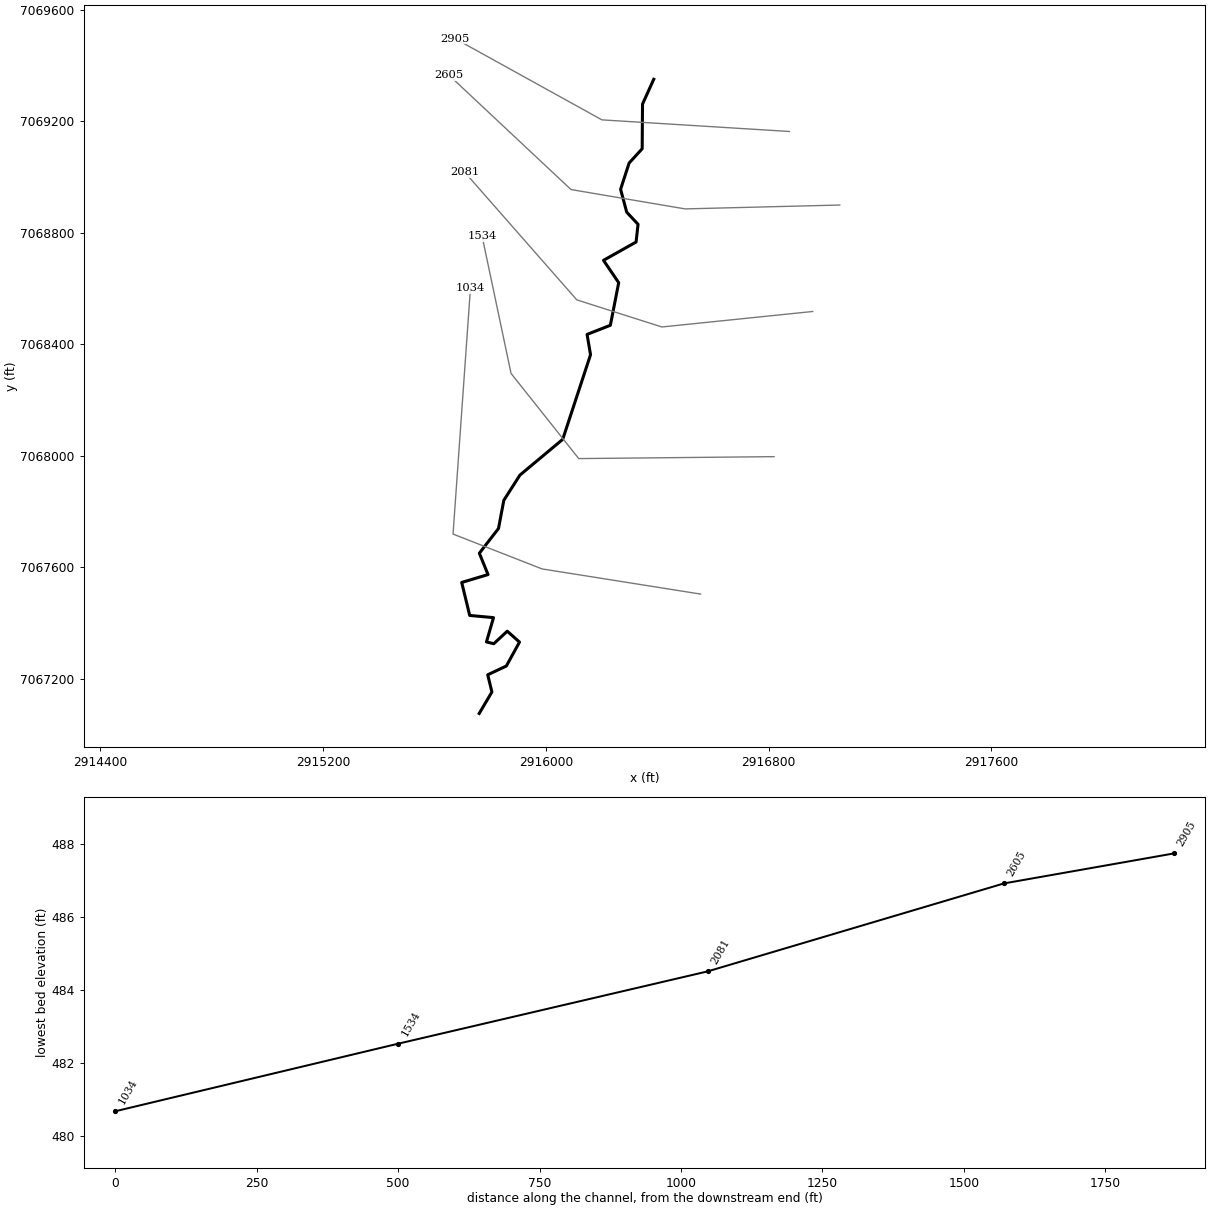
--- UNT 020 in Running Cr Watershed.prj (project) ---

Proj Title=UNT 020 in Running Cr Watershed Base Level Engineering
Current Plan=p01
Default Exp/Contr=0.3,0.1
English Units
Geom File=g01
Flow File=f01
Plan File=p01
BEGIN DESCRIPTION:
UNT 020 in Running Cr Watershed
END DESCRIPTION:

--- UNT 020 in Running Cr Watershed.p01 (plan) ---

Plan Title=Multiple Run
Short Identifier=Multiple
Geom File=g01
Flow File=f01
Subcritical Flow
K Sum by GR= 0
Std Step Tol= 0.01
Critical Tol= 0.01
Num of Std Step Trials= 20
Max Error Tol= 0.3
Flow Tol Ratio= 0.001
Split Flow NTrial= 30
Split Flow Tol= 0.02
Split Flow Ratio= 0.02
Log Output Level= 0
Friction Slope Method= 1
Unsteady Friction Slope Method= 2
Unsteady Bridges Friction Slope Method= 1
Parabolic Critical Depth
Global Vel Dist=  1 , 1 , 1
Global Log Level= 0
CheckData=True
Encroach Param= -1, 0, 0, 0
BEGIN DESCRIPTION:
Multiple Run
END DESCRIPTION:

--- UNT 020 in Running Cr Watershed.f01 (steady flow) ---

Flow Title=Multiple
Number of Profiles=7
Profile Names=10-year,25-year,50-year,1pct_min,100-year,1pct_plu,500-year
River Rch & RM= UNT 020 in Runni,Reach-1,2905
     735     984    1186     709    1414    2822    2007
River Rch & RM= UNT 020 in Runni,Reach-1,2605
     864    1167    1413     848    1692    3376    2420
Boundary for River Rch & Prof#=UNT 020 in Runni,Reach-1,1
Up Type=0
Dn Type=3
Dn Slope=0.005
Boundary for River Rch & Prof#=UNT 020 in Runni,Reach-1,2
Up Type=0
Dn Type=3
Dn Slope=0.005
Boundary for River Rch & Prof#=UNT 020 in Runni,Reach-1,3
Up Type=0
Dn Type=3
Dn Slope=0.005
Boundary for River Rch & Prof#=UNT 020 in Runni,Reach-1,4
Up Type=0
Dn Type=3
Dn Slope=0.005
Boundary for River Rch & Prof#=UNT 020 in Runni,Reach-1,5
Up Type=0
Dn Type=3
Dn Slope=0.005
Boundary for River Rch & Prof#=UNT 020 in Runni,Reach-1,6
Up Type=0
Dn Type=3
Dn Slope=0.005
Boundary for River Rch & Prof#=UNT 020 in Runni,Reach-1,7
Up Type=0
Dn Type=3
Dn Slope=0.005

--- UNT 020 in Running Cr Watershed.g01 (geometry) ---

Geom Title=Existing Conditions

River Reach=UNT 020 in Runni,Reach-1
Reach XY= 30
      2916387.15      7069350.06      2916346.82      7069260.84
      2916345.59      7069100.71      2916298.66      7069049.41
      2916268.11      7068955.27      2916290.02      7068873.11
      2916330.76      7068829.60      2916323.66      7068765.99
      2916206.68      7068700.38      2916261.26      7068620.19
      2916231.30      7068467.31      2916147.68      7068434.60
      2916160.11      7068361.77      2916060.25      7068058.08
      2915906.44      7067929.76      2915848.70      7067839.36
      2915829.55      7067738.26      2915760.78      7067649.54
      2915791.96      7067572.94      2915697.43      7067544.59
      2915726.19      7067426.25      2915811.61      7067418.43
      2915786.29      7067331.15      2915812.66      7067324.84
      2915861.04      7067369.78      2915905.00      7067330.67
      2915857.73      7067244.84      2915790.85      7067213.33
      2915805.89      7067151.70      2915760.24      7067074.57

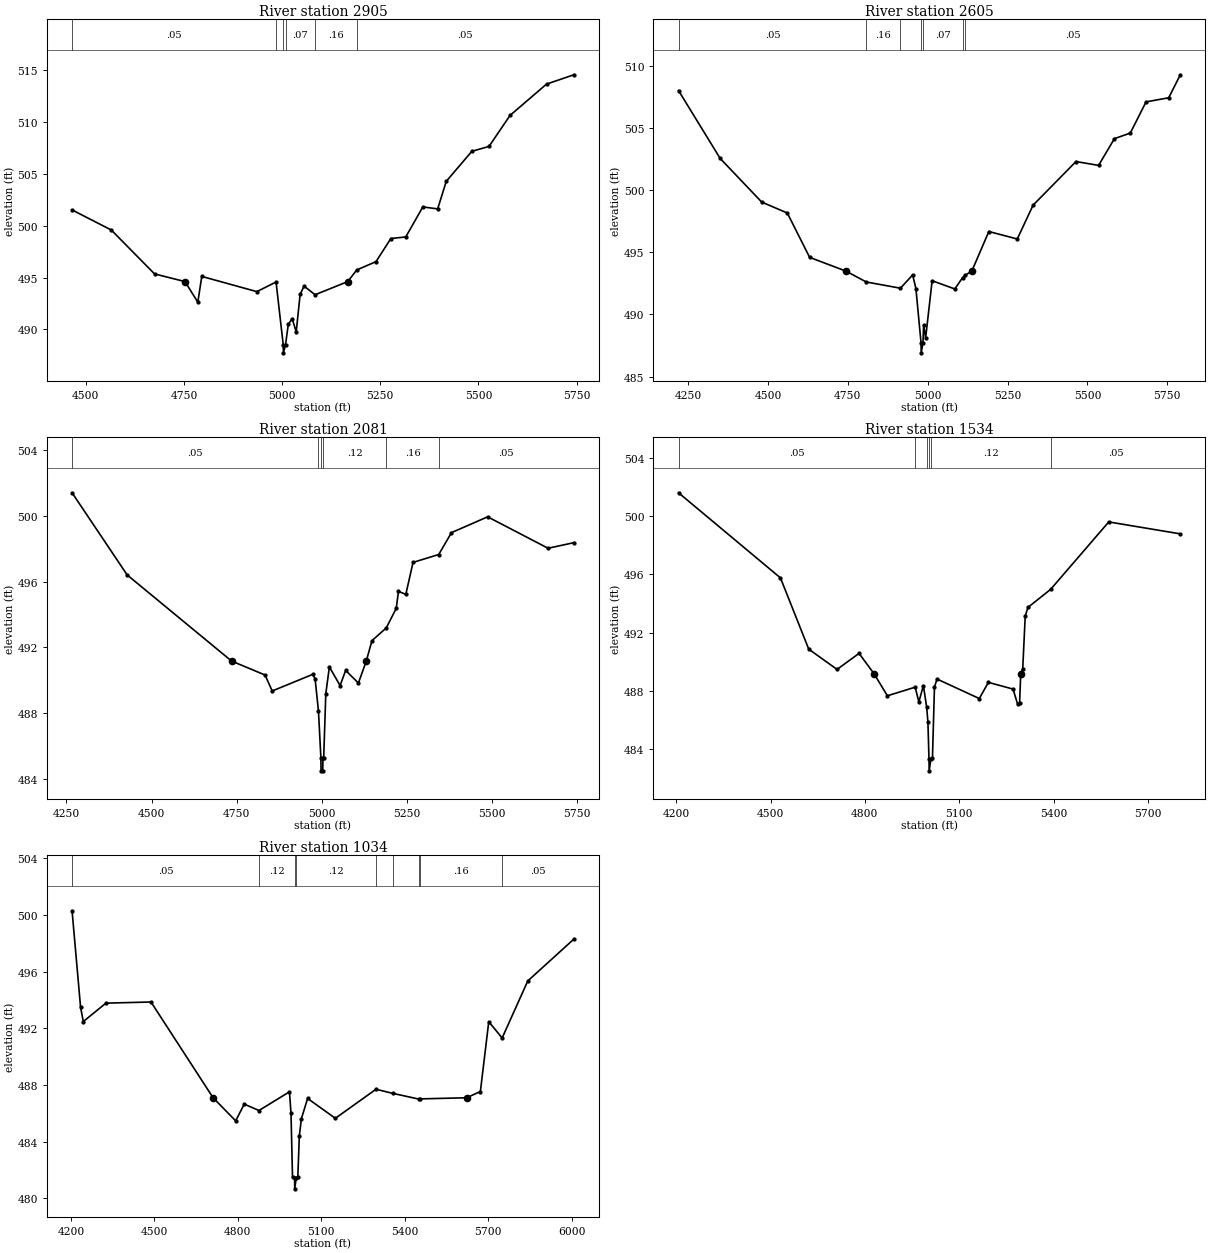
Type RM Length L Ch R = 1,2905,300,300,300
BEGIN DESCRIPTION:
UNT 020 in Running Cr Watershed 2.0
END DESCRIPTION:
XS GIS Cut Line= 3
      2916874.67      7069162.66      2916201.05      7069204.33
      2915673.28      7069495.99
#Sta/Elev= 30
  4465.2  501.53  4565.1  499.59  4675.3  495.35  4752.8  494.61  4785.5  492.62
  4795.5  495.11  4935.8  493.64  4984.7  494.57  5002.9  488.53  5003.4  487.73
  5008.9  488.53  5015.9  490.50  5025.9  491.02  5036.0  489.74  5046.0  493.38
  5056.0  494.17  5084.1  493.34  5167.3  494.61  5190.1  495.73  5239.3  496.54
  5277.1  498.77  5315.0  498.92  5358.5  501.82  5396.3  501.63  5418.1  504.29
  5483.3  507.19  5526.9  507.66  5580.7  510.66  5673.5  513.68  5743.1  514.58
#Mann=6,-1,0
  4465.2    0.05       0  4984.7    0.07       0  5002.9    0.07       0
  5008.9    0.07       0  5084.1    0.16       0  5190.1    0.05       0
Bank Sta=4752.8,5167.3
Exp/Cntr=0.3,0.1

Type RM Length L Ch R = 1,2605,524,524,524
BEGIN DESCRIPTION:
Mapping XS c0a5b731
END DESCRIPTION:
XS GIS Cut Line= 4
      2917055.25      7068898.77      2916499.66      7068884.88
      2916089.94      7068954.33      2915652.46      7069364.03
#Sta/Elev= 30
  4220.2  508.01  4350.5  502.55  4480.5  499.04  4560.6  498.16  4630.6  494.59
  4744.8  493.48  4807.8  492.61  4914.8  492.11  4953.1  493.18  4963.3  492.07
  4979.3  487.71  4979.8  486.91  4985.3  487.71  4987.4  489.17  4993.7  488.12
  5014.0  492.71  5085.0  492.05  5109.4  492.96  5116.5  493.14  5138.2  493.48
  5191.5  496.67  5280.5  496.07  5330.0  498.79  5464.3  502.30  5535.1  501.99
  5584.5  504.14  5634.3  504.59  5683.6  507.10  5754.5  507.43  5790.9  509.28
#Mann=7,-1,0
  4220.2    0.05       0  4807.8    0.16       0  4914.8    0.07       0
  4979.3    0.07       0  4985.3    0.07       0  5109.4    0.16       0
  5116.5    0.05       0
Bank Sta=4744.8,5138.2
Exp/Cntr=0.3,0.1

Type RM Length L Ch R = 1,2081,547,547,547
BEGIN DESCRIPTION:
Mapping XS a017fe4c
END DESCRIPTION:
XS GIS Cut Line= 4
      2916957.95      7068516.82      2916416.32      7068461.27
      2916110.77      7068558.50      2915708.97      7069015.72
#Sta/Elev= 30
  4266.7  501.39  4428.5  496.40  4735.1  491.17  4833.5  490.32  4854.5  489.35
  4973.5  490.36  4980.5  490.09  4990.4  488.13  4997.5  485.30  4998.0  484.50
  5003.0  484.50  5003.5  485.30  5005.8  485.31  5011.9  489.18  5022.4  490.81
  5053.9  489.68  5070.2  490.60  5107.7  489.83  5130.8  491.17  5147.6  492.41
  5189.5  493.18  5218.8  494.37  5225.4  495.40  5247.0  495.22  5268.1  497.16
  5343.6  497.64  5381.1  498.97  5487.3  499.93  5664.8  498.02  5740.5  498.36
#Mann=6,-1,0
  4266.7    0.05       0  4990.4    0.12       0  4997.5    0.07       0
  5003.5    0.12       0  5189.5    0.16       0  5343.6    0.05       0
Bank Sta=4735.1,5130.8
Exp/Cntr=0.3,0.1

Type RM Length L Ch R = 1,1534,500,500,500
BEGIN DESCRIPTION:
Mapping XS 752e05ad
END DESCRIPTION:
XS GIS Cut Line= 4
      2916819.12      7067996.00      2916117.71      7067989.05
      2915874.66      7068294.61      2915770.49      7068787.65
#Sta/Elev= 30
  4207.5  501.60  4531.6  495.76  4621.6  490.87  4711.6  489.48  4781.6  490.58
  4830.0  489.16  4871.7  487.67  4960.0  488.26  4971.8  487.25  4986.2  488.37
  4996.7  486.88  5000.6  485.87  5004.0  483.32  5004.5  482.52  5010.1  483.32
  5015.0  483.37  5021.4  488.26  5029.5  488.82  5164.0  487.48  5192.8  488.59
  5271.3  488.13  5285.8  487.10  5292.1  487.15  5295.7  489.16  5302.1  489.52
  5310.0  493.13  5318.5  493.73  5390.7  494.97  5575.7  499.60  5803.3  498.78
#Mann=6,-1,0
  4207.5    0.05       0  4960.0    0.07       0  4996.7    0.12       0
  5004.0    0.07       0  5010.1    0.12       0  5390.7    0.05       0
Bank Sta=4830,5295.7
Exp/Cntr=0.3,0.1

Type RM Length L Ch R = 1,1034,0,0,0
BEGIN DESCRIPTION:
UNT 020 in Running Cr Watershed 1.0
END DESCRIPTION:
XS GIS Cut Line= 4
      2916555.22      7067502.94      2915985.77      7067593.22
      2915666.32      7067718.22      2915728.82      7068600.12
#Sta/Elev= 30
  4204.2  500.30  4234.8  493.48  4244.6  492.48  4325.9  493.78  4487.9  493.86
  4711.1  487.10  4792.3  485.47  4823.0  486.65  4876.0  486.20  4985.6  487.52
  4991.2  485.99  4996.6  481.49  5004.0  481.47  5004.5  480.67  5010.1  481.47
  5015.7  481.50  5021.1  484.41  5028.6  485.63  5050.9  487.05  5150.6  485.65
  5296.7  487.70  5357.2  487.41  5449.9  487.01  5455.4  487.02  5622.4  487.10
  5671.9  487.54  5702.0  492.47  5750.1  491.32  5842.4  495.35  6007.9  498.30
#Mann=9,-1,0
  4204.2    0.05       0  4876.0    0.12       0  5004.0    0.07       0
  5010.1    0.12       0  5296.7    0.16       0  5357.2    0.05       0
  5449.9    0.12       0  5455.4    0.16       0  5750.1    0.05       0
Bank Sta=4711.1,5622.4
Exp/Cntr=0.3,0.1

Chan Stop Cuts=-1