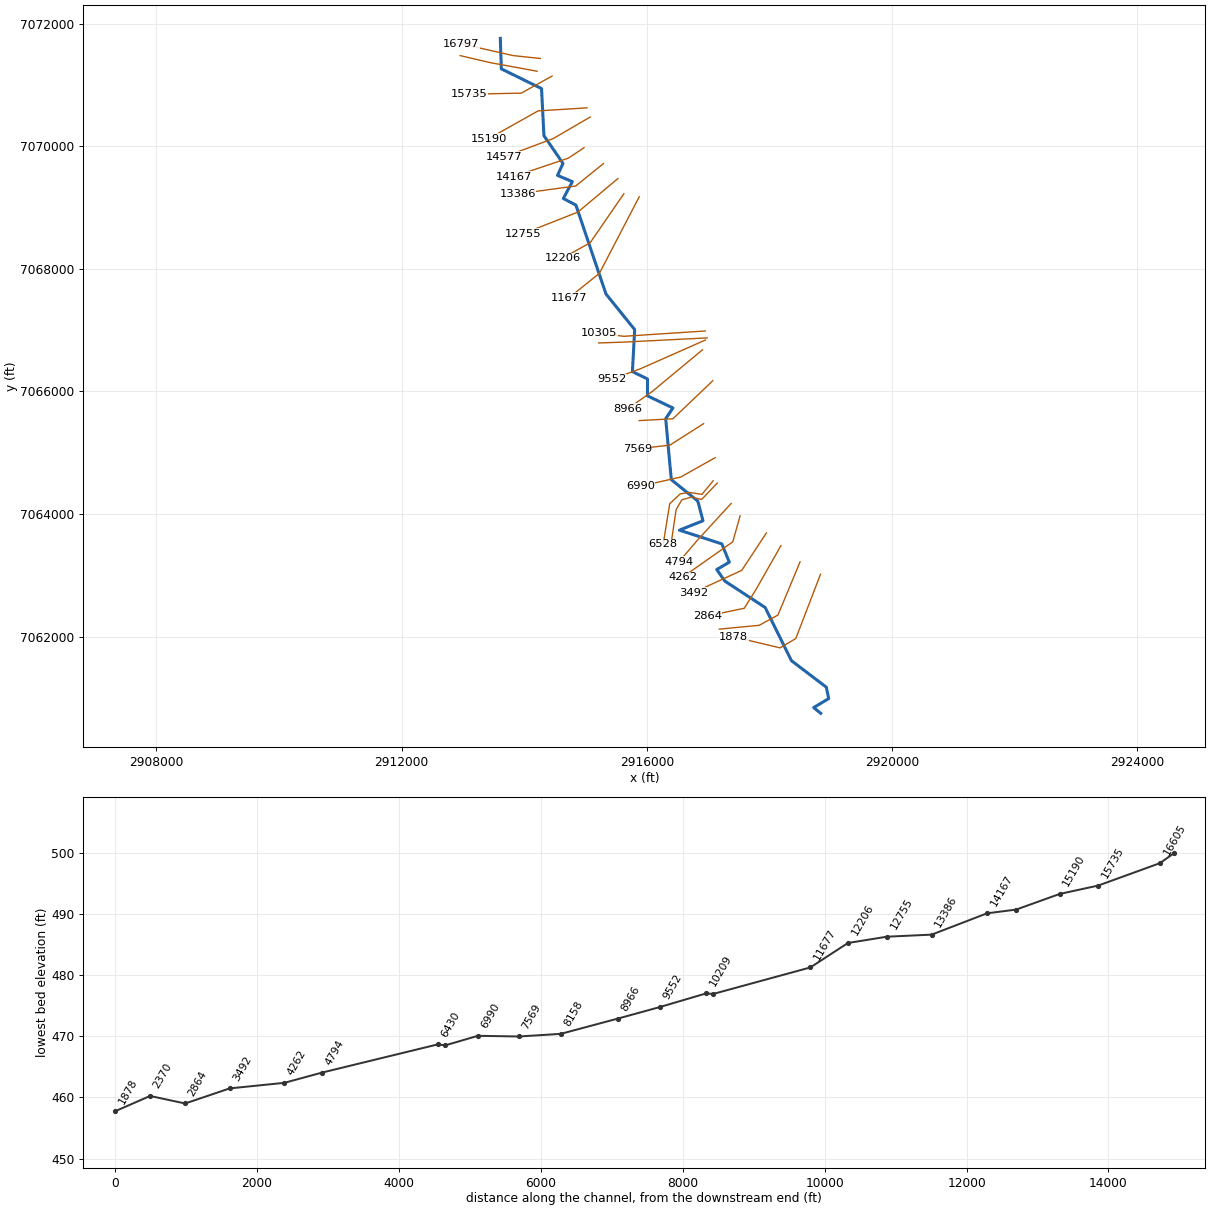
--- UNT 021 in Running Cr Watershed.prj (project) ---

Proj Title=UNT 021 in Running Cr Watershed Base Level Engineering
Current Plan=p01
Default Exp/Contr=0.3,0.1
English Units
Geom File=g01
Flow File=f01
Plan File=p01
BEGIN DESCRIPTION:
UNT 021 in Running Cr Watershed
END DESCRIPTION:

--- UNT 021 in Running Cr Watershed.p01 (plan) ---

Plan Title=Multiple Run
Short Identifier=Multiple
Geom File=g01
Flow File=f01
Subcritical Flow
K Sum by GR= 0
Std Step Tol= 0.01
Critical Tol= 0.01
Num of Std Step Trials= 20
Max Error Tol= 0.3
Flow Tol Ratio= 0.001
Split Flow NTrial= 30
Split Flow Tol= 0.02
Split Flow Ratio= 0.02
Log Output Level= 0
Friction Slope Method= 1
Unsteady Friction Slope Method= 2
Unsteady Bridges Friction Slope Method= 1
Parabolic Critical Depth
Global Vel Dist=  1 , 1 , 1
Global Log Level= 0
CheckData=True
Encroach Param= -1, 0, 0, 0
BEGIN DESCRIPTION:
Multiple Run
END DESCRIPTION:

--- UNT 021 in Running Cr Watershed.f01 (steady flow) ---

Flow Title=Multiple
Number of Profiles=7
Profile Names=10-year,25-year,50-year,1pct_min,100-year,1pct_plu,500-year
River Rch & RM= UNT 021 in Runni,Reach-1,16797
    1170    1612    1978    1203    2400    4788    3524
River Rch & RM= UNT 021 in Runni,Reach-1,10305
    1823    2558    3178    1952    3894    7769    5838
Boundary for River Rch & Prof#=UNT 021 in Runni,Reach-1,1
Up Type=0
Dn Type=3
Dn Slope=0.005
Boundary for River Rch & Prof#=UNT 021 in Runni,Reach-1,2
Up Type=0
Dn Type=3
Dn Slope=0.005
Boundary for River Rch & Prof#=UNT 021 in Runni,Reach-1,3
Up Type=0
Dn Type=3
Dn Slope=0.005
Boundary for River Rch & Prof#=UNT 021 in Runni,Reach-1,4
Up Type=0
Dn Type=3
Dn Slope=0.005
Boundary for River Rch & Prof#=UNT 021 in Runni,Reach-1,5
Up Type=0
Dn Type=3
Dn Slope=0.005
Boundary for River Rch & Prof#=UNT 021 in Runni,Reach-1,6
Up Type=0
Dn Type=3
Dn Slope=0.005
Boundary for River Rch & Prof#=UNT 021 in Runni,Reach-1,7
Up Type=0
Dn Type=3
Dn Slope=0.005

--- UNT 021 in Running Cr Watershed.g01 (geometry) ---

Geom Title=Existing Conditions

River Reach=UNT 021 in Runni,Reach-1
Reach XY= 30
      2913609.74      7071758.34      2913626.41      7071260.45
      2914282.18      7070938.95      2914320.90      7070172.05
      2914631.82      7069719.00      2914543.26      7069523.73
      2914784.55      7069421.52      2914637.49      7069146.70
      2914842.25      7069039.25      2915332.44      7067590.00
      2915800.85      7067009.04      2915763.93      7066323.22
      2916010.32      7066203.34      2916009.62      7065928.69
      2916424.64      7065730.77      2916306.18      7065555.92
      2916398.27      7064561.92      2916830.60      7064212.29
      2916914.52      7063891.44      2916530.61      7063738.71
      2917222.11      7063514.08      2917343.98      7063216.17
      2917139.40      7063095.85      2917271.22      7062907.75
      2917928.88      7062477.36      2918356.52      7061610.32
      2918925.65      7061178.02      2918964.94      7060991.62
      2918719.88      7060845.34      2918835.59      7060750.71

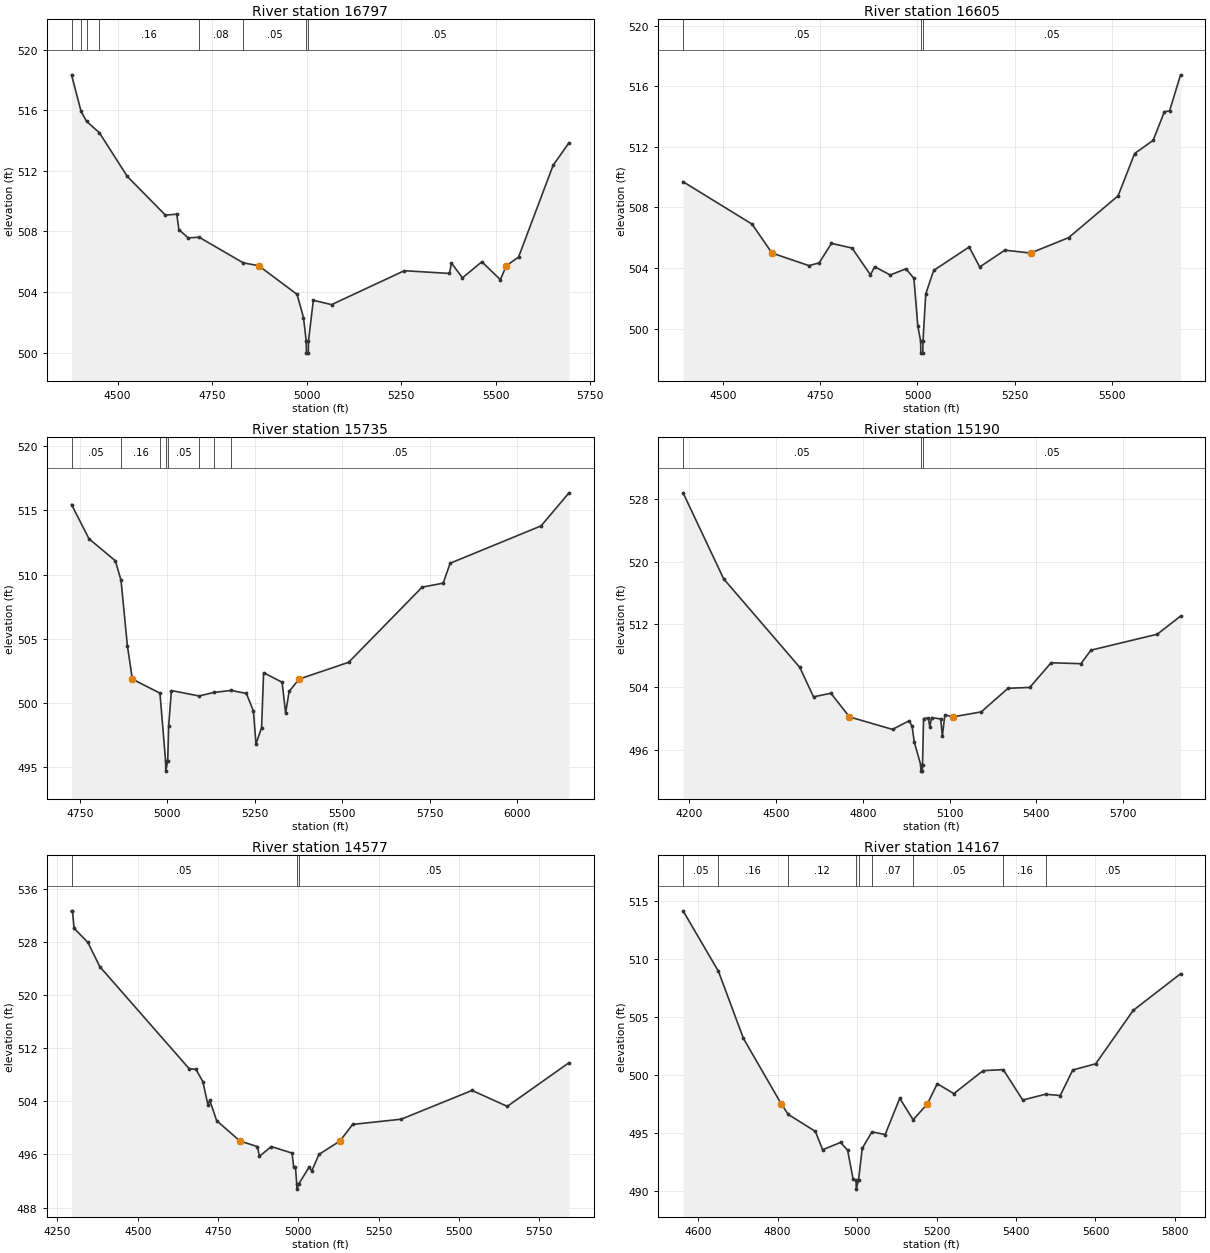
Type RM Length L Ch R = 1,16797,192,192,192
BEGIN DESCRIPTION:
UNT 021 in Running Cr Watershed 22.0
END DESCRIPTION:
XS GIS Cut Line= 3
      2914261.80      7071430.02      2913819.10      7071476.90
      2912970.17      7071669.60
#Sta/Elev= 30
  4378.0  518.34  4403.2  515.93  4417.7  515.27  4451.6  514.52  4525.6  511.63
  4626.2  509.08  4656.3  509.14  4662.0  508.12  4686.5  507.58  4715.5  507.62
  4832.1  505.93  4873.1  505.74  4974.4  503.85  4991.5  502.32  4998.7  500.77
  4999.2  499.97  5004.2  499.97  5004.7  500.77  5017.5  503.46  5065.7  503.17
  5258.1  505.41  5377.6  505.23  5382.8  505.92  5411.9  504.94  5463.2  506.00
  5512.1  504.82  5528.1  505.74  5560.3  506.31  5651.6  512.36  5693.7  513.86
#Mann=8,-1,0
  4378.0    0.05       0  4403.2    0.08       0  4417.7    0.05       0
  4451.6    0.16       0  4715.5    0.08       0  4832.1    0.05       0
  4998.7    0.03       0  5004.7    0.05       0
Bank Sta=4873.1,5528.1
Exp/Cntr=0.3,0.1

Type RM Length L Ch R = 1,16605,870,870,870
BEGIN DESCRIPTION:
UNT 021 in Running Cr Watershed 21.0
END DESCRIPTION:
XS GIS Cut Line= 3
      2914209.70      7071221.70      2913444.10      7071362.32
      2912954.53      7071476.90
#Sta/Elev= 30
  4396.3  509.70  4573.9  506.90  4625.3  504.99  4720.2  504.16  4746.8  504.34
  4778.4  505.63  4831.5  505.32  4878.9  503.55  4889.6  504.09  4929.8  503.54
  4970.4  503.95  4990.8  503.32  5000.9  500.16  5008.1  499.18  5008.6  498.38
  5013.7  498.38  5014.2  499.18  5021.3  502.29  5041.6  503.84  5133.1  505.39
  5160.2  504.07  5225.1  505.18  5291.4  504.99  5389.5  506.01  5516.7  508.77
  5559.2  511.56  5606.8  512.43  5635.9  514.32  5649.3  514.38  5677.5  516.76
#Mann=3,-1,0
  4396.3    0.05       0  5008.1    0.03       0  5014.2    0.05       0
Bank Sta=4625.3,5291.4
Exp/Cntr=0.3,0.1

Type RM Length L Ch R = 1,15735,545,545,545
BEGIN DESCRIPTION:
UNT 021 in Running Cr Watershed 20.0
END DESCRIPTION:
XS GIS Cut Line= 3
      2914454.50      7071143.55      2913952.52      7070865.09
      2913105.56      7070846.69
#Sta/Elev= 30
  4726.4  515.46  4776.1  512.80  4851.6  511.08  4867.8  509.56  4885.9  504.48
  4900.2  501.87  4979.0  500.78  4995.1  495.51  4995.6  494.71  5001.2  495.51
  5003.9  498.24  5011.7  500.98  5090.8  500.56  5132.4  500.83  5181.7  500.99
  5225.9  500.76  5246.1  499.38  5253.3  496.83  5269.4  498.10  5275.1  502.37
  5328.0  501.63  5338.0  499.23  5348.0  500.91  5376.2  501.87  5518.0  503.18
  5728.1  509.03  5788.1  509.34  5808.1  510.89  6068.1  513.80  6147.6  516.37
#Mann=8,-1,0
  4726.4    0.05       0  4867.8    0.16       0  4979.0    0.05       0
  4995.1    0.03       0  5001.2    0.05       0  5090.8    0.07       0
  5132.4    0.16       0  5181.7    0.05       0
Bank Sta=4900.2,5376.2
Exp/Cntr=0.3,0.1

Type RM Length L Ch R = 1,15190,613,613,613
BEGIN DESCRIPTION:
UNT 021 in Running Cr Watershed 19.0
END DESCRIPTION:
XS GIS Cut Line= 3
      2915025.02      7070625.00      2914225.00      7070575.00
      2913424.96      7070124.98
#Sta/Elev= 30
  4179.1  528.74  4319.4  517.79  4582.4  506.54  4630.0  502.78  4690.1  503.24
  4754.2  500.23  4903.0  498.64  4960.6  499.74  4970.7  499.02  4978.2  497.04
  5000.5  494.13  5001.0  493.33  5006.2  493.33  5006.7  494.13  5010.3  500.01
  5026.3  500.11  5032.0  498.99  5038.0  500.14  5069.6  499.97  5075.3  497.80
  5083.9  500.50  5111.1  500.23  5209.8  500.87  5302.3  503.87  5377.5  503.98
  5451.1  507.12  5554.4  507.00  5588.8  508.72  5818.2  510.75  5898.6  513.05
#Mann=3,-1,0
  4179.1    0.05       0  5000.5    0.03       0  5006.7    0.05       0
Bank Sta=4754.2,5111.1
Exp/Cntr=0.3,0.1

Type RM Length L Ch R = 1,14577,410,410,410
BEGIN DESCRIPTION:
UNT 021 in Running Cr Watershed 18.0
END DESCRIPTION:
XS GIS Cut Line= 3
      2915075.03      7070475.02      2914475.00      7070125.00
      2913674.96      7069824.99
#Sta/Elev= 30
  4294.0  532.67  4296.9  532.67  4301.9  530.05  4344.9  527.91  4382.1  524.26
  4660.0  508.92  4681.5  508.80  4703.0  506.95  4718.7  503.47  4724.5  504.14
  4746.0  501.07  4818.4  498.02  4872.9  497.17  4879.1  495.72  4916.3  497.18
  4980.8  496.19  4985.8  494.06  4991.3  494.06  4995.3  491.57  4995.8  490.77
  5001.6  491.57  5034.0  494.09  5042.1  493.50  5064.3  495.99  5129.9  498.02
  5169.3  500.51  5320.6  501.30  5541.3  505.63  5650.8  503.23  5843.1  509.80
#Mann=3,-1,0
  4294.0    0.05       0  4995.3    0.03       0  5001.6    0.05       0
Bank Sta=4818.4,5129.9
Exp/Cntr=0.3,0.1

Type RM Length L Ch R = 1,14167,781,781,781
BEGIN DESCRIPTION:
UNT 021 in Running Cr Watershed 17.0
END DESCRIPTION:
XS GIS Cut Line= 3
      2914975.03      7069975.02      2914720.14      7069805.02
      2913824.28      7069502.93
#Sta/Elev= 30
  4562.3  514.12  4651.3  508.91  4714.1  503.14  4809.3  497.50  4827.0  496.59
  4895.2  495.13  4913.4  493.55  4958.5  494.18  4976.3  493.52  4990.2  491.01
  4997.6  490.96  4998.1  490.16  5003.9  490.96  5013.1  493.67  5037.5  495.09
  5070.8  494.86  5107.5  497.98  5141.2  496.13  5177.1  497.50  5201.9  499.24
  5243.5  498.38  5317.3  500.36  5368.0  500.45  5417.0  497.83  5474.4  498.33
  5511.4  498.22  5542.9  500.42  5600.6  500.95  5695.0  505.55  5814.1  508.70
#Mann=9,-1,0
  4562.3    0.05       0  4651.3    0.16       0  4827.0    0.12       0
  4997.6    0.07       0  5003.9    0.12       0  5037.5    0.07       0
  5141.2    0.05       0  5368.0    0.16       0  5474.4    0.05       0
Bank Sta=4809.3,5177.1
Exp/Cntr=0.3,0.1

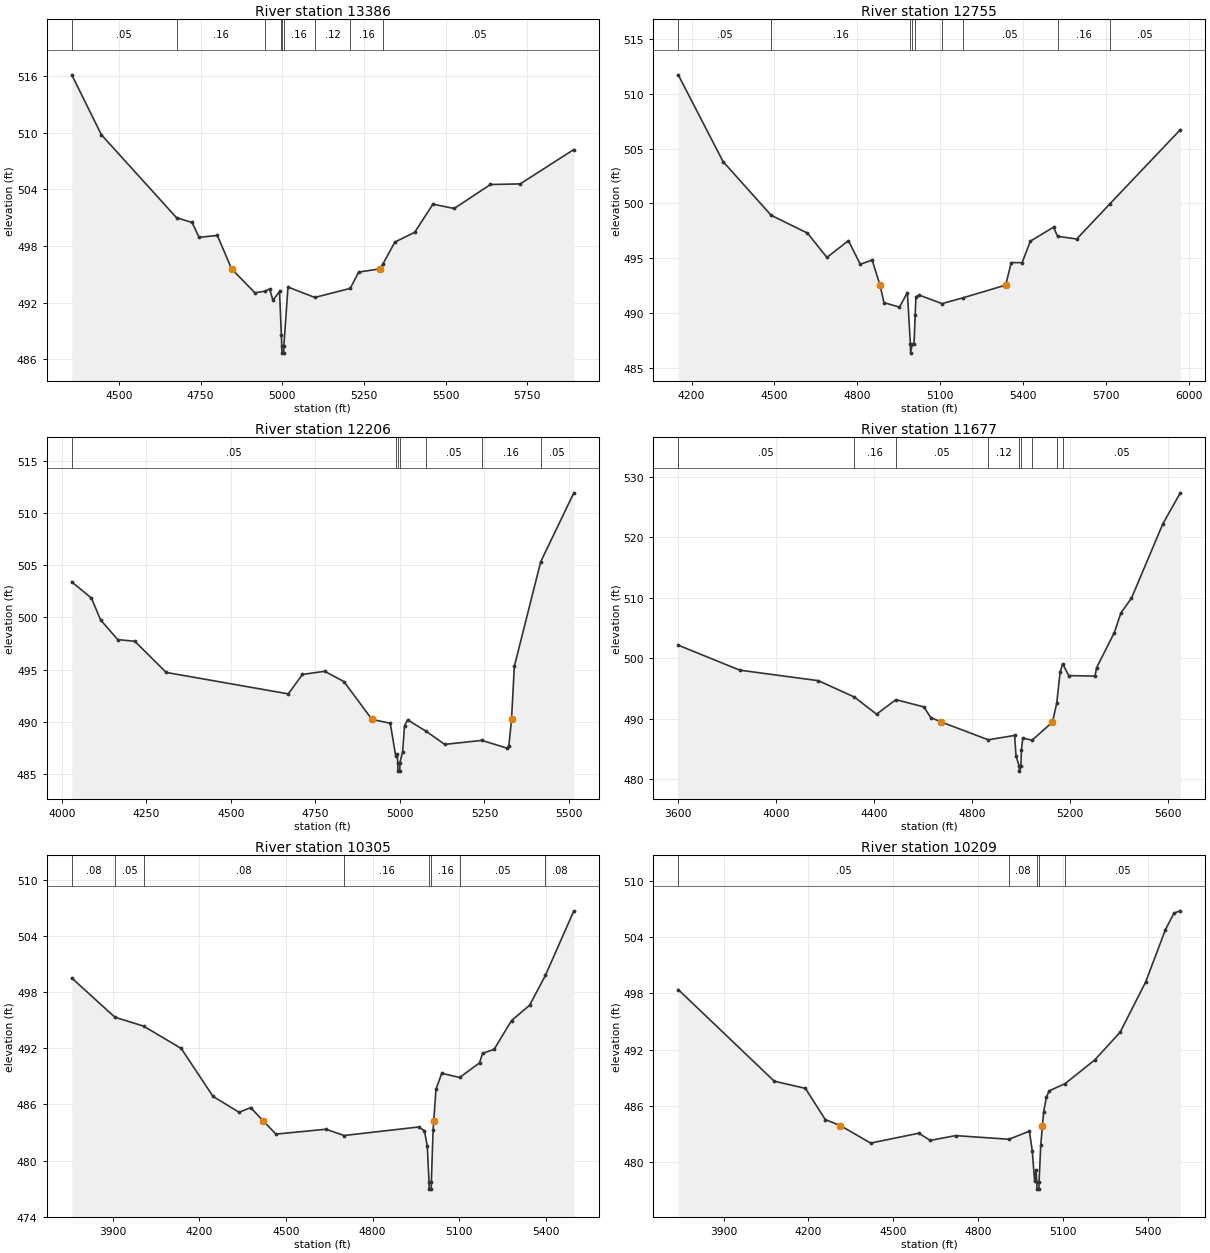
Type RM Length L Ch R = 1,13386,631,631,631
BEGIN DESCRIPTION:
UNT 021 in Running Cr Watershed 16.0
END DESCRIPTION:
XS GIS Cut Line= 3
      2915291.64      7069716.09      2914839.84      7069351.06
      2913892.06      7069221.70
#Sta/Elev= 30
  4355.4  516.11  4446.1  509.77  4676.1  501.00  4723.9  500.49  4745.1  498.92
  4801.1  499.12  4844.9  495.58  4916.2  493.05  4948.0  493.23  4961.3  493.46
  4971.4  492.26  4991.6  493.19  4997.1  488.63  4998.5  487.47  4999.0  486.67
  5004.4  486.67  5004.9  487.47  5017.4  493.66  5099.5  492.56  5208.3  493.52
  5233.8  495.24  5298.1  495.58  5307.9  496.09  5344.8  498.42  5405.4  499.45
  5461.3  502.43  5526.5  501.97  5637.5  504.51  5728.4  504.57  5892.8  508.21
#Mann=9,-1,0
  4355.4    0.05       0  4676.1    0.16       0  4948.0    0.12       0
  4997.1    0.16       0  4998.5    0.07       0  5004.9    0.16       0
  5099.5    0.12       0  5208.3    0.16       0  5307.9    0.05       0
Bank Sta=4844.9,5298.1
Exp/Cntr=0.3,0.1

Type RM Length L Ch R = 1,12755,549,549,549
BEGIN DESCRIPTION:
UNT 021 in Running Cr Watershed 15.0
END DESCRIPTION:
XS GIS Cut Line= 3
      2915527.43      7069471.69      2914875.00      7068925.00
      2913975.37      7068570.65
#Sta/Elev= 30
  4151.7  511.74  4314.0  503.82  4488.4  498.91  4619.7  497.29  4690.0  495.07
  4768.1  496.60  4811.0  494.44  4853.9  494.83  4882.3  492.54  4896.8  490.94
  4952.8  490.53  4981.4  491.86  4992.5  487.13  4993.0  486.33  4998.9  487.13
  5005.6  487.20  5009.7  489.78  5012.4  491.48  5024.4  491.63  5106.8  490.85
  5182.7  491.38  5337.4  492.54  5357.6  494.60  5396.9  494.59  5426.6  496.55
  5510.6  497.83  5525.2  497.00  5594.5  496.75  5715.5  499.98  5969.8  506.73
#Mann=9,-1,0
  4151.7    0.05       0  4488.4    0.16       0  4992.5    0.07       0
  4998.9    0.16       0  5009.7    0.12       0  5106.8    0.16       0
  5182.7    0.05       0  5525.2    0.16       0  5715.5    0.05       0
Bank Sta=4882.3,5337.4
Exp/Cntr=0.3,0.1

Type RM Length L Ch R = 1,12206,529,529,529
BEGIN DESCRIPTION:
UNT 021 in Running Cr Watershed 14.0
END DESCRIPTION:
XS GIS Cut Line= 3
      2915625.01      7069225.02      2915075.00      7068425.00
      2914625.02      7068175.01
#Sta/Elev= 30
  4029.1  503.40  4087.3  501.85  4114.3  499.77  4165.1  497.88  4215.8  497.72
  4308.5  494.74  4669.8  492.69  4711.7  494.55  4777.4  494.85  4834.2  493.87
  4917.6  490.24  4971.5  489.88  4987.9  486.70  4992.5  486.93  4993.7  486.10
  4994.2  485.30  4999.6  485.30  5000.1  486.10  5008.0  487.14  5013.7  489.64
  5022.8  490.20  5077.7  489.11  5132.6  487.86  5242.7  488.24  5316.8  487.50
  5322.5  487.74  5330.3  490.24  5338.6  495.32  5416.7  505.33  5514.7  511.92
#Mann=7,-1,0
  4029.1    0.05       0  4987.9    0.16       0  4993.7    0.07       0
  5000.1    0.16       0  5077.7    0.05       0  5242.7    0.16       0
  5416.7    0.05       0
Bank Sta=4917.6,5330.3
Exp/Cntr=0.3,0.1

Type RM Length L Ch R = 1,11677,1372,1372,1372
BEGIN DESCRIPTION:
UNT 021 in Running Cr Watershed 13.0
END DESCRIPTION:
XS GIS Cut Line= 3
      2915875.00      7069175.00      2915225.00      7067925.00
      2914725.01      7067525.01
#Sta/Elev= 30
  3600.9  502.16  3852.3  498.02  4172.7  496.28  4319.5  493.58  4410.3  490.73
  4489.3  493.14  4603.6  491.93  4631.3  490.18  4674.9  489.43  4866.1  486.49
  4973.8  487.21  4979.5  483.86  4992.6  482.10  4993.1  481.30  4999.2  482.10
  5001.6  484.76  5007.0  486.78  5045.2  486.42  5128.4  489.43  5145.7  492.56
  5159.5  497.67  5169.8  499.10  5194.7  497.12  5301.9  497.04  5308.3  498.42
  5380.4  504.21  5407.6  507.49  5450.8  509.95  5578.9  522.26  5650.1  527.39
#Mann=9,-1,0
  3600.9    0.05       0  4319.5    0.16       0  4489.3    0.05       0
  4866.1    0.12       0  4992.6    0.07       0  4999.2    0.12       0
  5045.2    0.16       0  5145.7    0.07       0  5169.8    0.05       0
Bank Sta=4674.9,5128.4
Exp/Cntr=0.3,0.1

Type RM Length L Ch R = 1,10305,96,96,96
BEGIN DESCRIPTION:
UNT 021 in Running Cr Watershed 11.0
END DESCRIPTION:
XS GIS Cut Line= 3
      2916953.09      7066986.25      2915624.93      7066899.45
      2915220.85      7066948.96
#Sta/Elev= 30
  3758.6  499.51  3908.3  495.31  4007.4  494.37  4137.5  491.98  4247.7  486.86
  4337.9  485.16  4378.0  485.66  4421.3  484.24  4465.5  482.83  4638.6  483.35
  4701.3  482.68  4959.3  483.59  4979.3  483.19  4989.3  481.58  4995.3  477.75
  4996.0  476.95  5002.7  476.95  5003.4  477.75  5009.4  483.23  5011.7  484.24
  5019.4  487.61  5039.4  489.33  5101.4  488.88  5170.1  490.44  5180.8  491.47
  5220.5  491.88  5280.9  494.96  5343.6  496.60  5398.1  499.78  5496.7  506.69
#Mann=8,-1,0
  3758.6    0.08       0  3908.3    0.05       0  4007.4    0.08       0
  4701.3    0.16       0  4995.3    0.07       0  5003.4    0.16       0
  5101.4    0.05       0  5398.1    0.08       0
Bank Sta=4421.3,5011.7
Exp/Cntr=0.3,0.1

Type RM Length L Ch R = 1,10209,657,657,657
BEGIN DESCRIPTION:
UNT 021 in Running Cr Watershed 10.0
END DESCRIPTION:
XS GIS Cut Line= 3
      2916983.42      7066873.40      2915603.23      7066803.96
      2915212.59      7066790.94
#Sta/Elev= 30
  3740.1  498.42  4079.0  488.61  4189.1  487.84  4259.2  484.50  4312.2  483.86
  4419.4  481.98  4589.6  483.04  4629.6  482.27  4719.8  482.78  4908.1  482.39
  4980.1  483.26  4990.1  481.15  4998.5  477.92  5003.5  479.11  5006.1  477.85
  5006.8  477.05  5013.5  477.05  5014.2  477.85  5020.1  481.75  5026.1  483.86
  5030.2  485.28  5040.2  486.92  5050.2  487.58  5106.3  488.35  5210.3  490.87
  5300.4  493.85  5390.4  499.22  5460.5  504.84  5490.5  506.61  5512.9  506.85
#Mann=5,-1,0
  3740.1    0.05       0  4908.1    0.08       0  5006.1    0.07       0
  5014.2    0.08       0  5106.3    0.05       0
Bank Sta=4312.2,5026.1
Exp/Cntr=0.3,0.1

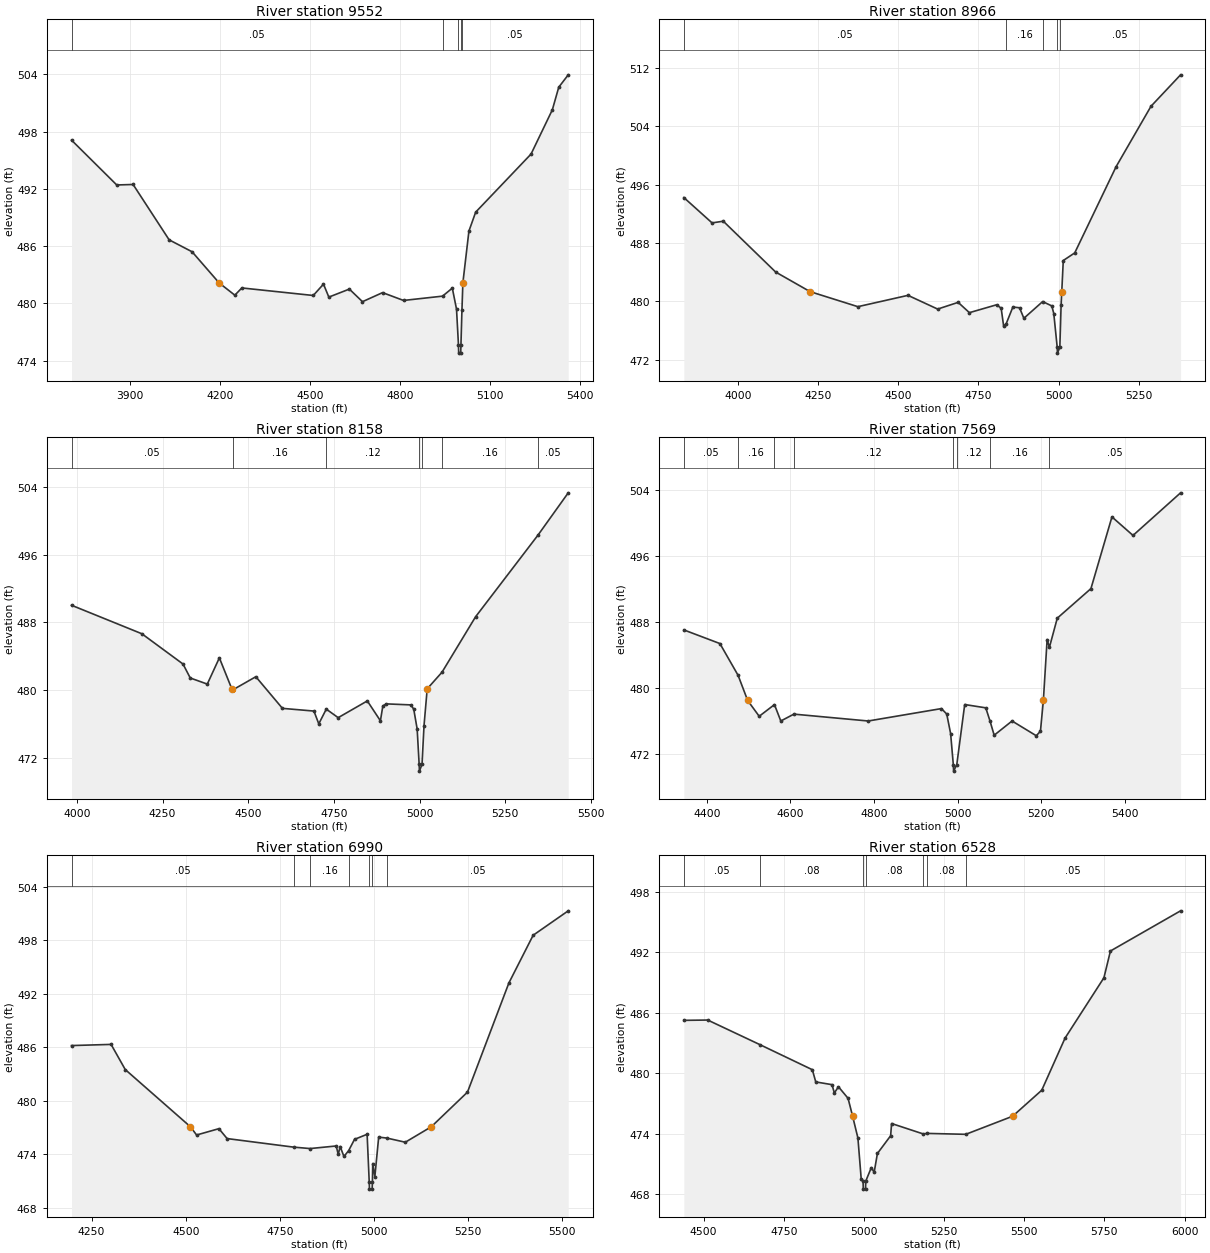
Type RM Length L Ch R = 1,9552,586,586,586
BEGIN DESCRIPTION:
UNT 021 in Running Cr Watershed 9.0
END DESCRIPTION:
XS GIS Cut Line= 3
      2916953.05      7066838.68      2915894.02      7066369.93
      2915425.27      7066196.32
#Sta/Elev= 30
  3704.1  497.12  3855.1  492.42  3909.7  492.47  4030.0  486.67  4106.6  485.42
  4196.8  482.16  4249.3  480.87  4272.6  481.63  4511.0  480.84  4545.2  482.03
  4563.0  480.67  4631.5  481.51  4675.3  480.19  4742.4  481.14  4812.3  480.32
  4942.5  480.77  4975.2  481.61  4989.2  479.41  4995.8  475.60  4996.4  474.80
  5003.2  474.80  5003.9  475.60  5007.3  479.29  5010.4  482.16  5030.6  487.59
  5053.1  489.57  5238.0  495.66  5309.1  500.30  5330.4  502.66  5362.1  503.96
#Mann=5,-1,0
  3704.1    0.05       0  4942.5    0.16       0  4995.8    0.07       0
  5003.9    0.16       0  5007.3    0.05       0
Bank Sta=4196.8,5010.4
Exp/Cntr=0.3,0.1

Type RM Length L Ch R = 1,8966,808,808,808
BEGIN DESCRIPTION:
UNT 021 in Running Cr Watershed 8.0
END DESCRIPTION:
XS GIS Cut Line= 3
      2916905.28      7066678.07      2916089.34      7066001.01
      2915690.83      7065719.46
#Sta/Elev= 30
  3831.7  494.23  3919.6  490.76  3954.7  490.99  4117.9  484.03  4225.1  481.35
  4374.1  479.29  4530.3  480.84  4622.8  478.96  4686.6  479.88  4721.7  478.47
  4806.6  479.55  4820.7  479.08  4828.5  476.61  4836.5  476.97  4857.2  479.24
  4878.0  479.14  4891.5  477.70  4950.1  479.99  4978.6  479.39  4984.7  478.35
  4995.4  473.73  4996.1  472.93  5003.6  473.73  5007.5  479.47  5009.6  481.35
  5014.3  485.61  5050.0  486.65  5178.9  498.45  5287.6  506.72  5379.9  511.03
#Mann=5,-1,0
  3831.7    0.05       0  4836.5    0.16       0  4950.1    0.05       0
  4995.4    0.03       0  5003.6    0.05       0
Bank Sta=4225.1,5009.6
Exp/Cntr=0.3,0.1

Type RM Length L Ch R = 1,8158,589,589,589
BEGIN DESCRIPTION:
UNT 021 in Running Cr Watershed 7.0
END DESCRIPTION:
XS GIS Cut Line= 3
      2917074.96      7066174.97      2916424.01      7065554.72
      2915874.95      7065525.00
#Sta/Elev= 30
  3984.4  490.03  4189.6  486.66  4309.7  483.08  4330.8  481.43  4380.5  480.71
  4415.7  483.81  4452.0  480.15  4454.2  480.01  4522.1  481.58  4599.7  477.84
  4691.6  477.52  4705.7  476.01  4727.6  477.75  4762.3  476.74  4847.3  478.72
  4885.5  476.37  4892.6  478.12  4902.6  478.37  4974.2  478.25  4982.7  477.75
  4992.7  475.40  4998.5  471.22  4999.3  470.42  5006.9  471.22  5012.7  475.80
  5022.0  480.15  5065.3  482.12  5163.0  488.66  5345.5  498.34  5433.4  503.32
#Mann=7,-1,0
  3984.4    0.05       0  4454.2    0.16       0  4727.6    0.12       0
  4998.5    0.07       0  5006.9    0.12       0  5065.3    0.16       0
  5345.5    0.05       0
Bank Sta=4452,5022
Exp/Cntr=0.3,0.1

Type RM Length L Ch R = 1,7569,579,579,579
BEGIN DESCRIPTION:
UNT 021 in Running Cr Watershed 6.0
END DESCRIPTION:
XS GIS Cut Line= 3
      2916924.98      7065474.98      2916375.00      7065125.00
      2915841.93      7065063.51
#Sta/Elev= 30
  4345.0  487.06  4431.3  485.41  4474.8  481.57  4497.7  478.53  4525.3  476.62
  4561.8  478.03  4577.0  476.05  4608.3  476.88  4786.1  476.05  4961.3  477.55
  4974.0  476.89  4983.3  474.53  4989.7  470.79  4990.5  469.99  4998.1  470.79
  5017.0  478.04  5067.4  477.64  5077.6  476.04  5087.5  474.33  5130.3  476.05
  5188.2  474.27  5198.2  474.81  5205.2  478.53  5214.2  485.90  5219.7  484.96
  5238.5  488.48  5319.0  492.05  5369.3  500.72  5419.7  498.48  5533.5  503.63
#Mann=8,-1,0
  4345.0    0.05       0  4474.8    0.16       0  4561.8    0.05       0
  4608.3    0.12       0  4989.7    0.07       0  4998.1    0.12       0
  5077.6    0.16       0  5219.7    0.05       0
Bank Sta=4497.7,5205.2
Exp/Cntr=0.3,0.1

Type RM Length L Ch R = 1,6990,462,462,462
BEGIN DESCRIPTION:
UNT 021 in Running Cr Watershed 5.0
END DESCRIPTION:
XS GIS Cut Line= 3
      2917113.66      7064920.29      2916549.41      7064603.44
      2915894.04      7064455.87
#Sta/Elev= 30
  4196.7  486.20  4301.8  486.33  4339.4  483.51  4512.6  477.09  4528.8  476.17
  4588.1  476.88  4609.8  475.77  4786.4  474.81  4830.2  474.65  4899.6  474.94
  4904.9  473.99  4910.0  474.88  4920.1  473.76  4932.6  474.42  4948.1  475.68
  4981.6  476.25  4987.2  470.90  4987.9  470.10  4994.9  470.10  4995.6  470.90
  4996.5  472.97  5002.1  471.49  5012.3  475.93  5033.6  475.83  5083.0  475.36
  5151.9  477.09  5248.1  480.98  5358.0  493.22  5422.4  498.57  5515.6  501.31
#Mann=7,-1,0
  4196.7    0.05       0  4786.4    0.12       0  4830.2    0.16       0
  4932.6    0.12       0  4987.2    0.07       0  4995.6    0.12       0
  5033.6    0.05       0
Bank Sta=4512.6,5151.9
Exp/Cntr=0.3,0.1

Type RM Length L Ch R = 1,6528,98,98,98
BEGIN DESCRIPTION:
Mapping XS cd2ce60f
END DESCRIPTION:
XS GIS Cut Line= 6
      2917080.63      7064543.52      2916898.36      7064322.19
      2916692.64      7064353.44      2916544.20      7064330.00
      2916372.32      7064168.54      2916265.77      7063508.56
#Sta/Elev= 30
  4438.2  485.25  4512.7  485.28  4675.1  482.85  4839.0  480.36  4849.7  479.15
  4900.3  478.88  4907.7  478.06  4920.5  478.67  4950.4  477.53  4964.7  475.75
  4981.2  473.59  4991.4  469.56  4997.2  469.33  4998.0  468.53  5005.0  468.53
  5005.7  469.33  5023.0  470.66  5031.9  470.20  5042.0  472.06  5083.3  473.82
  5086.2  475.03  5184.7  474.00  5197.3  474.05  5317.7  473.96  5463.7  475.75
  5554.7  478.33  5627.3  483.49  5748.6  489.47  5768.9  492.12  5987.7  496.10
#Mann=7,-1,0
  4438.2    0.05       0  4675.1    0.08       0  4997.2    0.07       0
  5005.7    0.08       0  5184.7    0.05       0  5197.3    0.08       0
  5317.7    0.05       0
Bank Sta=4964.7,5463.7
Exp/Cntr=0.3,0.1

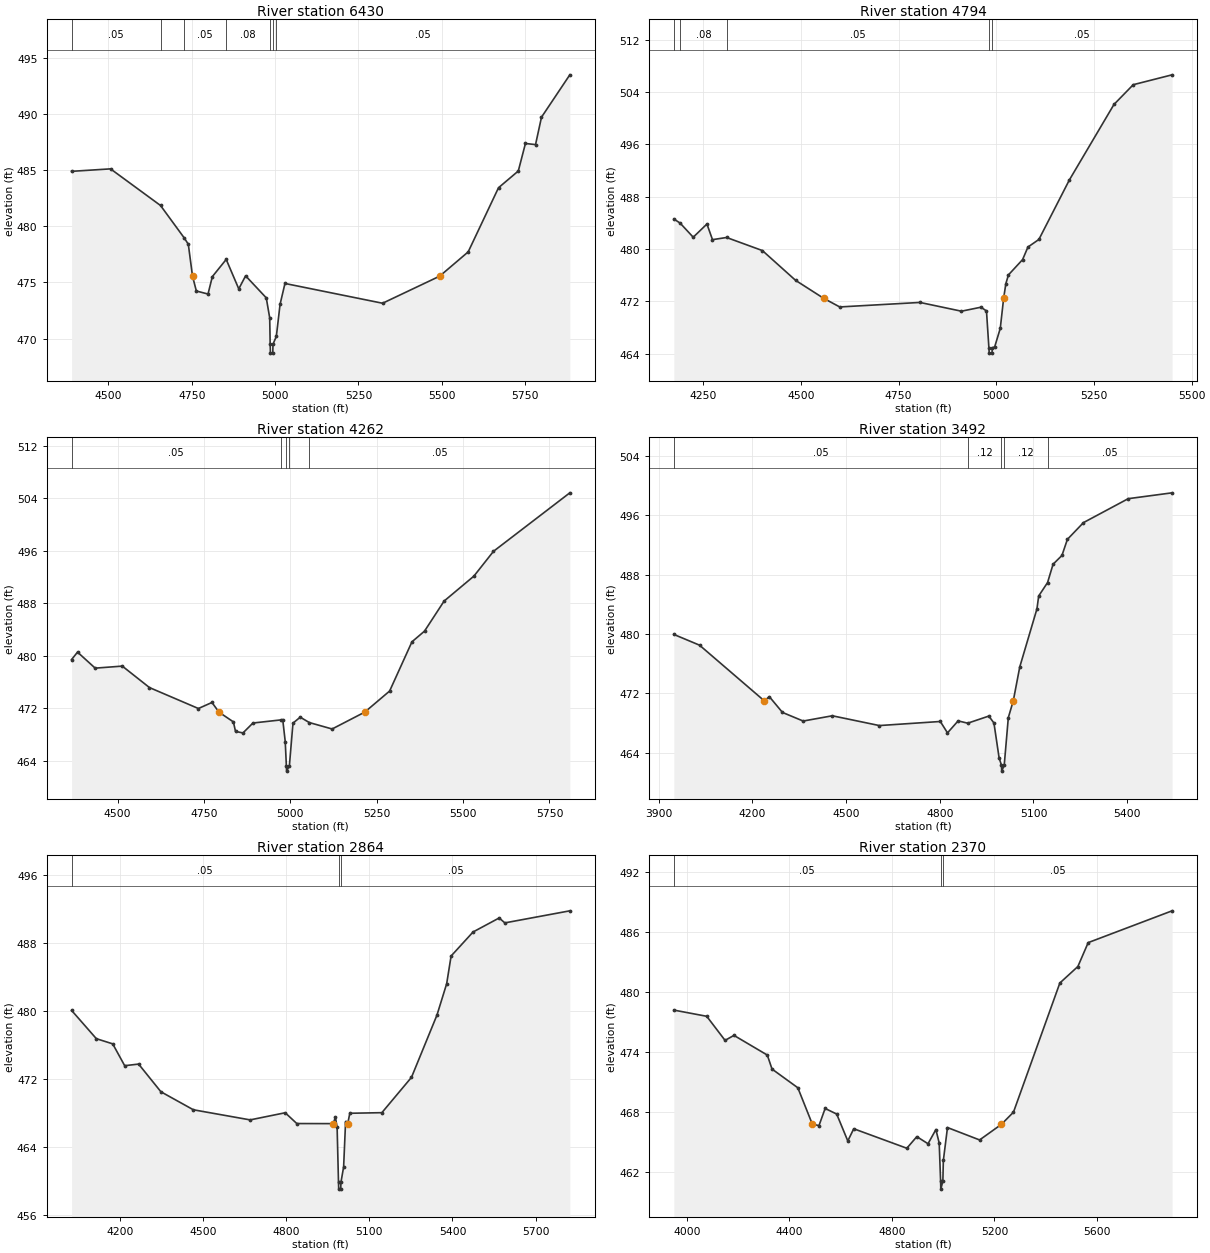
Type RM Length L Ch R = 1,6430,1636,1636,1636
BEGIN DESCRIPTION:
UNT 021 in Running Cr Watershed 4.0
END DESCRIPTION:
XS GIS Cut Line= 6
      2917148.34      7064507.06      2916893.16      7064238.86
      2916730.23      7064276.29      2916570.24      7064233.65
      2916476.49      7064072.19      2916387.95      7063473.25
#Sta/Elev= 30
  4389.3  484.89  4506.2  485.11  4656.2  481.85  4726.9  478.98  4739.6  478.40
  4752.2  475.56  4763.7  474.24  4798.7  473.97  4811.7  475.52  4853.3  477.05
  4891.0  474.43  4911.5  475.59  4973.5  473.63  4983.8  471.85  4985.2  469.51
  4986.0  468.71  4993.0  468.71  4993.7  469.51  5003.7  470.19  5014.9  473.05
  5029.6  474.91  5322.5  473.15  5493.8  475.56  5579.4  477.72  5670.4  483.43
  5729.8  484.92  5751.2  487.37  5781.5  487.27  5799.4  489.71  5884.4  493.48
#Mann=7,-1,0
  4389.3    0.05       0  4656.2    0.08       0  4726.9    0.05       0
  4853.3    0.08       0  4985.2    0.07       0  4993.7    0.08       0
  5003.7    0.05       0
Bank Sta=4752.2,5493.8
Exp/Cntr=0.3,0.1

Type RM Length L Ch R = 1,4794,532,532,532
BEGIN DESCRIPTION:
UNT 021 in Running Cr Watershed 3.0
END DESCRIPTION:
XS GIS Cut Line= 3
      2917374.97      7064174.97      2916825.00      7063575.00
      2916524.98      7063224.98
#Sta/Elev= 30
  4175.0  484.59  4191.1  483.96  4224.6  481.80  4259.7  483.82  4273.9  481.43
  4310.0  481.76  4401.6  479.76  4486.7  475.20  4558.1  472.47  4599.5  471.14
  4804.8  471.83  4910.9  470.49  4960.8  471.10  4975.0  470.53  4981.2  464.88
  4982.0  464.08  4989.1  464.08  4989.8  464.88  4996.0  465.04  5010.3  467.87
  5018.9  472.47  5024.6  474.71  5031.2  476.04  5067.4  478.38  5081.1  480.30
  5109.1  481.46  5187.0  490.55  5301.2  502.10  5350.5  505.12  5449.9  506.63
#Mann=5,-1,0
  4175.0    0.16       0  4191.1    0.08       0  4310.0    0.05       0
  4981.2    0.03       0  4989.8    0.05       0
Bank Sta=4558.1,5018.9
Exp/Cntr=0.3,0.1

Type RM Length L Ch R = 1,4262,770,770,770
BEGIN DESCRIPTION:
UNT 021 in Running Cr Watershed 2.0
END DESCRIPTION:
XS GIS Cut Line= 3
      2917519.61      7063971.54      2917400.79      7063547.88
      2916581.32      7062971.47
#Sta/Elev= 30
  4367.0  479.40  4384.2  480.53  4435.3  478.09  4513.8  478.40  4592.4  475.13
  4734.0  471.94  4773.3  472.86  4793.5  471.39  4835.3  469.90  4841.4  468.45
  4863.0  468.22  4891.9  469.73  4972.2  470.20  4978.1  470.24  4985.3  466.91
  4988.6  463.20  4989.3  462.40  4997.3  463.20  5007.7  469.71  5028.7  470.62
  5055.0  469.80  5121.0  468.82  5215.4  471.39  5287.4  474.60  5352.0  482.10
  5388.4  483.73  5445.1  488.31  5531.3  492.11  5588.0  495.89  5808.9  504.80
#Mann=5,-1,0
  4367.0    0.05       0  4972.2    0.16       0  4988.6    0.07       0
  4997.3    0.16       0  5055.0    0.05       0
Bank Sta=4793.5,5215.4
Exp/Cntr=0.3,0.1

Type RM Length L Ch R = 1,3492,628,628,628
BEGIN DESCRIPTION:
Mapping XS 5852026b
END DESCRIPTION:
XS GIS Cut Line= 3
      2917949.42      7063693.74      2917546.63      7063082.61
      2916761.87      7062721.48
#Sta/Elev= 30
  3948.1  479.94  4030.4  478.49  4237.8  470.98  4254.0  471.54  4296.1  469.41
  4362.4  468.25  4455.7  468.96  4606.3  467.64  4801.6  468.19  4824.6  466.65
  4858.6  468.27  4889.4  467.96  4957.0  468.92  4973.4  467.98  4990.0  463.25
  4997.5  462.29  4998.3  461.49  5006.3  462.29  5019.4  468.71  5035.3  470.98
  5056.1  475.56  5111.1  483.39  5116.7  485.13  5145.1  486.94  5162.7  489.41
  5191.2  490.60  5208.6  492.77  5260.1  495.03  5403.4  498.26  5543.9  499.05
#Mann=5,-1,0
  3948.1    0.05       0  4889.4    0.12       0  4997.5    0.07       0
  5006.3    0.12       0  5145.1    0.05       0
Bank Sta=4237.8,5035.3
Exp/Cntr=0.3,0.1

Type RM Length L Ch R = 1,2864,494,494,494
BEGIN DESCRIPTION:
Mapping XS e2621ce3
END DESCRIPTION:
XS GIS Cut Line= 4
      2918185.51      7063485.37      2917782.74      7062777.05
      2917588.29      7062464.55      2916985.25      7062339.78
#Sta/Elev= 30
  4025.0  480.06  4114.4  476.73  4173.5  476.12  4216.7  473.55  4267.0  473.74
  4347.5  470.48  4464.7  468.36  4669.6  467.17  4796.2  468.01  4838.1  466.74
  4968.8  466.73  4977.6  467.46  4983.6  466.29  4988.6  459.82  4989.4  459.02
  4996.6  459.02  4997.4  459.82  5007.1  461.63  5014.2  466.98  5021.9  466.73
  5029.5  467.95  5145.2  468.02  5252.1  472.18  5344.0  479.50  5379.1  483.20
  5395.1  486.46  5474.4  489.29  5568.7  490.94  5589.1  490.36  5823.7  491.78
#Mann=3,-1,0
  4025.0    0.05       0  4988.6    0.03       0  4997.4    0.05       0
Bank Sta=4968.8,5021.9
Exp/Cntr=0.3,0.1

Type RM Length L Ch R = 1,2370,492,492,492
BEGIN DESCRIPTION:
Mapping XS 835c31f9
END DESCRIPTION:
XS GIS Cut Line= 4
      2918498.02      7063221.49      2918136.91      7062353.44
      2917831.35      7062186.77      2917179.26      7062124.34
#Sta/Elev= 30
  3949.5  478.16  4077.8  477.54  4149.3  475.13  4184.0  475.63  4314.1  473.66
  4332.5  472.26  4433.1  470.39  4490.0  466.73  4515.7  466.61  4539.6  468.32
  4584.7  467.76  4628.0  465.07  4651.2  466.29  4858.2  464.34  4897.2  465.50
  4940.9  464.79  4971.6  466.21  4984.5  464.86  4990.0  461.05  4990.8  460.25
  4998.8  461.05  5000.7  463.12  5016.8  466.41  5142.1  465.17  5227.1  466.73
  5274.2  467.95  5455.1  480.87  5525.4  482.52  5565.6  484.91  5892.8  488.09
#Mann=3,-1,0
  3949.5    0.05       0  4990.0    0.03       0  4998.8    0.05       0
Bank Sta=4490,5227.1
Exp/Cntr=0.3,0.1

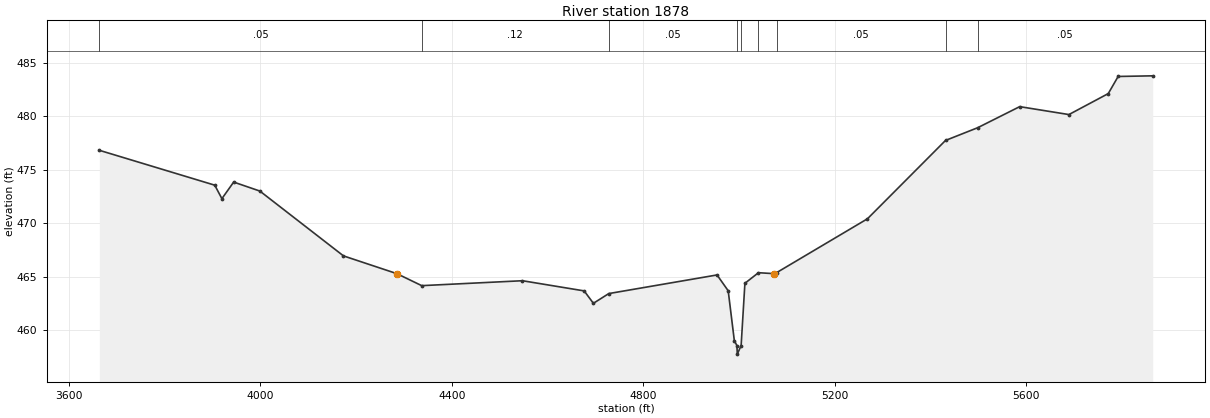
Type RM Length L Ch R = 1,1878,0,0,0
BEGIN DESCRIPTION:
UNT 021 in Running Cr Watershed 1.0
END DESCRIPTION:
XS GIS Cut Line= 4
      2918831.34      7063020.07      2918428.57      7061971.50
      2918171.63      7061818.72      2917414.67      7061999.28
#Sta/Elev= 30
  3663.6  476.80  3904.7  473.54  3919.6  472.28  3944.2  473.83  3998.9  472.99
  4173.6  466.93  4285.2  465.27  4337.0  464.15  4547.4  464.61  4676.3  463.66
  4695.6  462.50  4727.8  463.41  4953.9  465.15  4977.2  463.67  4990.0  459.01
  4995.4  458.55  4996.2  457.75  5004.2  458.55  5012.1  464.37  5040.4  465.36
  5073.0  465.27  5078.5  465.37  5268.1  470.40  5431.1  477.72  5498.3  478.91
  5586.1  480.88  5688.9  480.14  5771.1  482.10  5791.7  483.70  5864.0  483.76
#Mann=9,-1,0
  3663.6    0.05       0  4337.0    0.12       0  4727.8    0.05       0
  4995.4    0.03       0  5004.2    0.05       0  5040.4    0.12       0
  5078.5    0.05       0  5431.1    0.16       0  5498.3    0.05       0
Bank Sta=4285.2,5073
Exp/Cntr=0.3,0.1

Chan Stop Cuts=-1