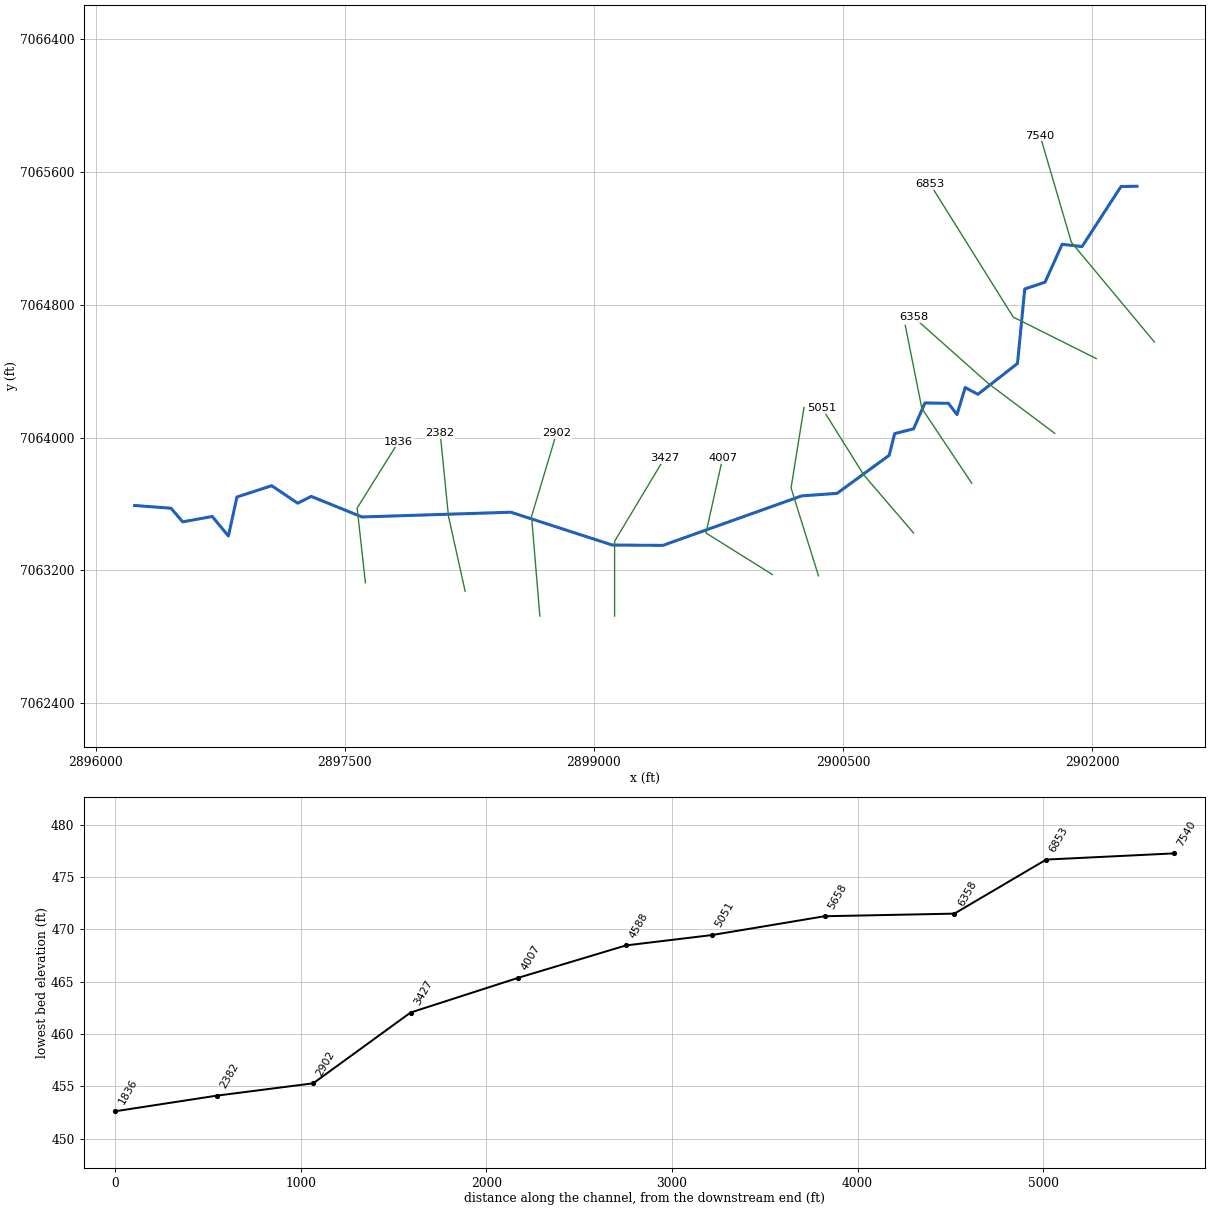
--- UNT 022 in Running Cr Watershed.prj (project) ---

Proj Title=UNT 022 in Running Cr Watershed Base Level Engineering
Current Plan=p01
Default Exp/Contr=0.3,0.1
English Units
Geom File=g01
Flow File=f01
Plan File=p01
BEGIN DESCRIPTION:
UNT 022 in Running Cr Watershed
END DESCRIPTION:

--- UNT 022 in Running Cr Watershed.p01 (plan) ---

Plan Title=Multiple Run
Short Identifier=Multiple
Geom File=g01
Flow File=f01
Subcritical Flow
K Sum by GR= 0
Std Step Tol= 0.01
Critical Tol= 0.01
Num of Std Step Trials= 20
Max Error Tol= 0.3
Flow Tol Ratio= 0.001
Split Flow NTrial= 30
Split Flow Tol= 0.02
Split Flow Ratio= 0.02
Log Output Level= 0
Friction Slope Method= 1
Unsteady Friction Slope Method= 2
Unsteady Bridges Friction Slope Method= 1
Parabolic Critical Depth
Global Vel Dist=  1 , 1 , 1
Global Log Level= 0
CheckData=True
Encroach Param= -1, 0, 0, 0
BEGIN DESCRIPTION:
Multiple Run
END DESCRIPTION:

--- UNT 022 in Running Cr Watershed.f01 (steady flow) ---

Flow Title=Multiple
Number of Profiles=7
Profile Names=10-year,25-year,50-year,1pct_min,100-year,1pct_plu,500-year
River Rch & RM= UNT 022 in Runni,Reach-1,7540
     814    1102    1337     805    1606    3204    2310
River Rch & RM= UNT 022 in Runni,Reach-1,6853
    1169    1610    1976    1201    2396    4782    3519
Boundary for River Rch & Prof#=UNT 022 in Runni,Reach-1,1
Up Type=0
Dn Type=3
Dn Slope=0.005
Boundary for River Rch & Prof#=UNT 022 in Runni,Reach-1,2
Up Type=0
Dn Type=3
Dn Slope=0.005
Boundary for River Rch & Prof#=UNT 022 in Runni,Reach-1,3
Up Type=0
Dn Type=3
Dn Slope=0.005
Boundary for River Rch & Prof#=UNT 022 in Runni,Reach-1,4
Up Type=0
Dn Type=3
Dn Slope=0.005
Boundary for River Rch & Prof#=UNT 022 in Runni,Reach-1,5
Up Type=0
Dn Type=3
Dn Slope=0.005
Boundary for River Rch & Prof#=UNT 022 in Runni,Reach-1,6
Up Type=0
Dn Type=3
Dn Slope=0.005
Boundary for River Rch & Prof#=UNT 022 in Runni,Reach-1,7
Up Type=0
Dn Type=3
Dn Slope=0.005

--- UNT 022 in Running Cr Watershed.g01 (geometry) ---

Geom Title=Existing Conditions

River Reach=UNT 022 in Runni,Reach-1
Reach XY= 30
      2902269.91      7065512.82      2902173.46      7065510.78
      2901939.17      7065149.36      2901819.25      7065163.22
      2901716.45      7064934.99      2901594.21      7064893.95
      2901550.59      7064445.61      2901312.08      7064259.95
      2901235.78      7064300.78      2901186.45      7064138.21
      2901134.85      7064205.76      2900993.47      7064207.98
      2900925.03      7064052.31      2900811.08      7064023.31
      2900778.26      7063893.04      2900464.37      7063663.66
      2900251.31      7063648.54      2899415.67      7063350.52
      2899111.40      7063352.68      2898500.59      7063550.14
      2897604.13      7063521.56      2897298.60      7063645.50
      2897217.12      7063604.56      2897060.69      7063709.75
      2896851.53      7063641.85      2896799.89      7063406.99
      2896702.93      7063524.40      2896524.51      7063492.16
      2896454.64      7063574.18      2896235.59      7063590.71

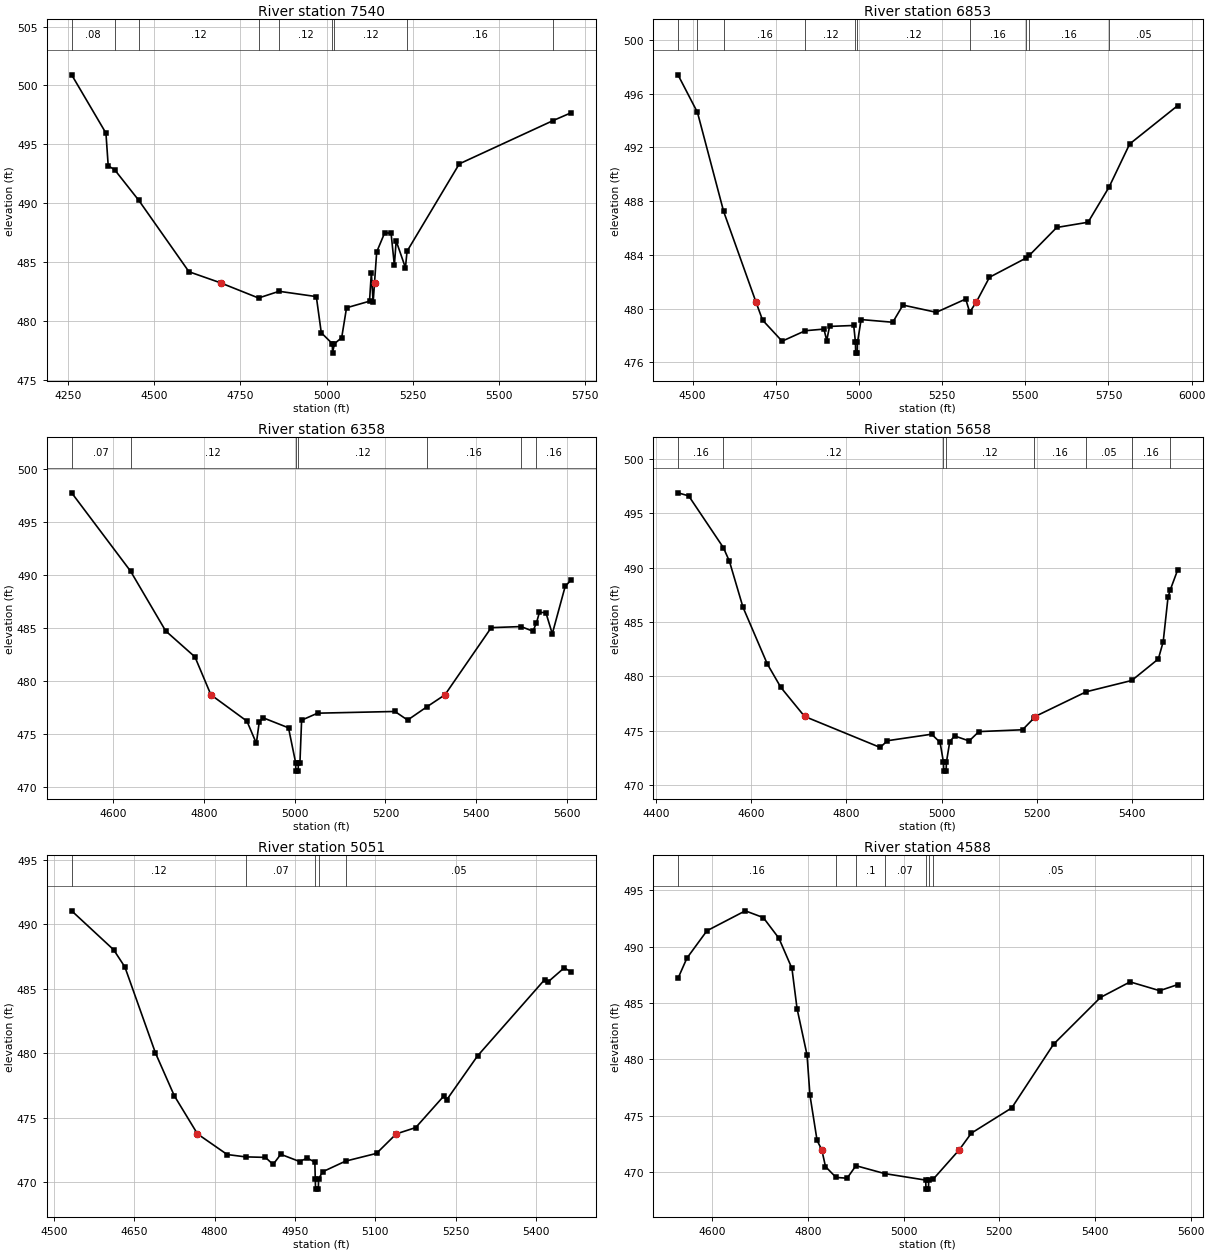
Type RM Length L Ch R = 1,7540,687,687,687
BEGIN DESCRIPTION:
UNT 022 in Running Cr Watershed 11.0
END DESCRIPTION:
XS GIS Cut Line= 3
      2902374.98      7064575.03      2901875.00      7065175.00
      2901686.73      7065817.29
#Sta/Elev= 30
  4260.3  500.90  4359.8  495.95  4366.4  493.17  4384.8  492.85  4455.4  490.23
  4600.7  484.18  4692.3  483.24  4802.6  481.95  4862.3  482.52  4970.3  482.07
  4984.7  479.00  5016.8  478.07  5017.3  477.27  5022.8  478.07  5043.9  478.58
  5058.0  481.12  5124.7  481.68  5130.0  484.09  5135.2  481.57  5139.2  483.24
  5145.5  485.86  5168.6  487.48  5187.2  487.46  5196.8  484.72  5202.0  486.80
  5228.9  484.52  5233.6  485.92  5385.2  493.34  5657.8  497.02  5710.6  497.69
#Mann=9,-1,0
  4260.3    0.08       0  4384.8    0.16       0  4455.4    0.12       0
  4802.6    0.16       0  4862.3    0.12       0  5016.8    0.07       0
  5022.8    0.12       0  5233.6    0.16       0  5657.8    0.08       0
Bank Sta=4692.3,5139.2
Exp/Cntr=0.3,0.1

Type RM Length L Ch R = 1,6853,495,495,495
BEGIN DESCRIPTION:
UNT 022 in Running Cr Watershed 10.0
END DESCRIPTION:
XS GIS Cut Line= 3
      2902024.99      7064475.01      2901525.00      7064725.00
      2901025.00      7065525.00
#Sta/Elev= 30
  4455.9  497.41  4514.5  494.61  4593.2  487.23  4690.3  480.49  4710.2  479.14
  4768.9  477.57  4838.7  478.35  4894.7  478.47  4903.1  477.62  4911.5  478.67
  4984.2  478.74  4989.5  477.48  4990.0  476.68  4995.0  476.68  4995.5  477.48
  5006.5  479.18  5101.6  478.98  5132.2  480.26  5232.5  479.72  5320.9  480.71
  5332.9  479.73  5352.9  480.49  5392.3  482.33  5500.7  483.74  5512.0  483.96
  5594.5  486.04  5688.8  486.43  5751.9  489.05  5813.8  492.26  5958.3  495.12
#Mann=10,-1,0
  4455.9    0.16       0  4514.5    0.12       0  4593.2    0.16       0
  4838.7    0.12       0  4989.5    0.07       0  4995.5    0.12       0
  5332.9    0.16       0  5500.7    0.12       0  5512.0    0.16       0
  5751.9    0.05       0
Bank Sta=4690.3,5352.9
Exp/Cntr=0.3,0.1

Type RM Length L Ch R = 1,6358,700,700,700
BEGIN DESCRIPTION:
UNT 022 in Running Cr Watershed 9.0
END DESCRIPTION:
XS GIS Cut Line= 3
      2901775.03      7064024.98      2901375.00      7064325.00
      2900925.01      7064724.99
#Sta/Elev= 30
  4508.1  497.73  4638.0  490.35  4715.4  484.72  4780.0  482.27  4815.2  478.70
  4894.6  476.22  4915.4  474.13  4921.7  476.12  4930.0  476.54  4986.3  475.59
  5002.0  472.31  5002.5  471.51  5007.6  471.51  5008.1  472.31  5011.5  472.31
  5015.2  476.31  5050.4  476.97  5221.0  477.13  5249.0  476.32  5290.8  477.55
  5331.3  478.70  5433.4  485.03  5499.2  485.13  5525.3  484.69  5533.1  485.48
  5539.6  486.46  5553.8  486.45  5568.0  484.45  5596.4  488.91  5610.2  489.56
#Mann=7,-1,0
  4508.1    0.07       0  4638.0    0.12       0  5002.0    0.07       0
  5008.1    0.12       0  5290.8    0.16       0  5499.2    0.12       0
  5533.1    0.16       0
Bank Sta=4815.2,5331.3
Exp/Cntr=0.3,0.1

Type RM Length L Ch R = 1,5658,607,607,607
BEGIN DESCRIPTION:
UNT 022 in Running Cr Watershed 8.0
END DESCRIPTION:
XS GIS Cut Line= 3
      2901275.00      7063725.00      2900975.00      7064175.00
      2900875.01      7064674.97
#Sta/Elev= 30
  4445.8  496.89  4468.3  496.61  4541.3  491.84  4554.0  490.58  4582.5  486.35
  4633.6  481.13  4662.1  478.97  4711.9  476.30  4871.0  473.44  4886.0  474.06
  4979.1  474.66  4996.8  473.91  5004.0  472.06  5004.5  471.26  5009.6  471.26
  5010.1  472.06  5017.2  473.98  5027.4  474.50  5058.0  474.04  5078.4  474.90
  5170.2  475.07  5194.8  476.17  5196.6  476.29  5304.2  478.57  5399.9  479.61
  5455.7  481.59  5465.9  483.17  5476.1  487.29  5480.7  487.94  5496.5  489.81
#Mann=8,-1,0
  4445.8    0.16       0  4541.3    0.12       0  5004.0    0.07       0
  5010.1    0.12       0  5194.8    0.16       0  5304.2    0.05       0
  5399.9    0.16       0  5480.7    0.05       0
Bank Sta=4711.9,5196.6
Exp/Cntr=0.3,0.1

Type RM Length L Ch R = 1,5051,463,463,463
BEGIN DESCRIPTION:
UNT 022 in Running Cr Watershed 7.0
END DESCRIPTION:
XS GIS Cut Line= 3
      2900924.98      7063425.02      2900625.00      7063775.00
      2900375.03      7064174.96
#Sta/Elev= 30
  4533.3  491.03  4611.7  488.01  4632.6  486.68  4689.7  480.01  4724.8  476.70
  4768.1  473.74  4823.6  472.14  4858.0  471.96  4894.9  471.92  4909.2  471.37
  4923.5  472.16  4958.6  471.60  4972.8  471.86  4987.1  471.56  4987.9  470.26
  4988.4  469.46  4993.6  469.46  4994.1  470.26  5001.9  470.81  5044.4  471.63
  5102.2  472.23  5139.0  473.74  5175.3  474.23  5227.2  476.65  5233.0  476.37
  5290.8  479.79  5415.8  485.69  5421.7  485.50  5452.4  486.61  5465.9  486.28
#Mann=5,-1,0
  4533.3    0.12       0  4858.0    0.07       0  4987.9    0.07       0
  4994.1    0.07       0  5044.4    0.05       0
Bank Sta=4768.1,5139
Exp/Cntr=0.3,0.1

Type RM Length L Ch R = 1,4588,581,581,581
BEGIN DESCRIPTION:
UNT 022 in Running Cr Watershed 6.0
END DESCRIPTION:
XS GIS Cut Line= 3
      2900352.36      7063167.18      2900187.44      7063696.66
      2900265.34      7064181.37
#Sta/Elev= 30
  4527.8  487.18  4546.5  488.98  4588.4  491.41  4668.6  493.18  4706.3  492.58
  4738.9  490.75  4766.2  488.07  4776.9  484.50  4797.8  480.38  4803.9  476.81
  4818.8  472.79  4828.6  471.97  4836.4  470.47  4858.5  469.51  4881.6  469.44
  4900.1  470.55  4960.2  469.85  5046.1  469.27  5046.6  468.47  5051.8  468.47
  5052.3  469.27  5061.9  469.36  5116.4  471.97  5141.5  473.44  5226.0  475.68
  5313.6  481.34  5411.7  485.49  5473.6  486.87  5535.5  486.09  5573.3  486.63
#Mann=7,-1,0
  4527.8    0.16       0  4858.5    0.07       0  4900.1     0.1       0
  4960.2    0.07       0  5046.1    0.07       0  5052.3    0.07       0
  5061.9    0.05       0
Bank Sta=4828.6,5116.4
Exp/Cntr=0.3,0.1

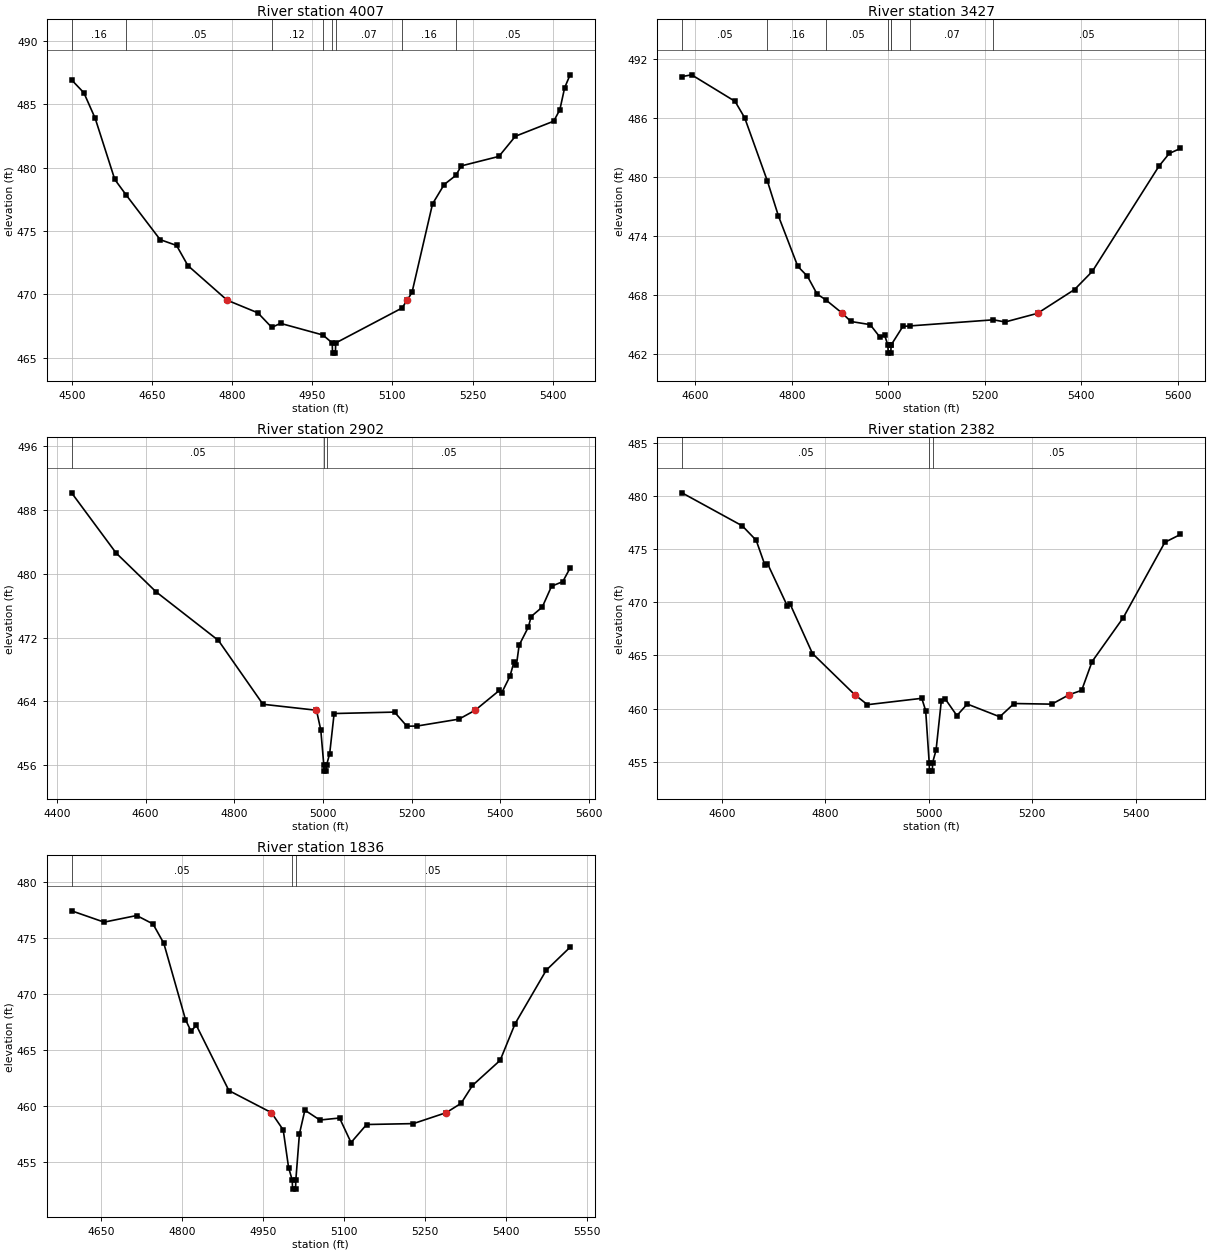
Type RM Length L Ch R = 1,4007,580,580,580
BEGIN DESCRIPTION:
UNT 022 in Running Cr Watershed 5.0
END DESCRIPTION:
XS GIS Cut Line= 3
      2900075.02      7063174.99      2899675.00      7063425.00
      2899775.00      7063875.01
#Sta/Elev= 30
  4499.7  486.94  4522.7  485.92  4543.9  483.90  4580.5  479.08  4601.7  477.86
  4665.4  474.33  4696.1  473.87  4717.3  472.28  4790.7  469.55  4848.2  468.55
  4874.2  467.40  4890.6  467.72  4970.0  466.80  4987.4  466.17  4987.9  465.37
  4993.3  465.37  4993.8  466.17  5117.9  468.93  5127.5  469.55  5136.6  470.16
  5175.0  477.15  5196.8  478.68  5218.6  479.40  5228.8  480.15  5299.2  480.90
  5330.0  482.49  5401.7  483.68  5413.2  484.58  5422.2  486.32  5432.4  487.34
#Mann=8,-1,0
  4499.7    0.16       0  4601.7    0.05       0  4874.2    0.12       0
  4970.0    0.07       0  4987.4    0.07       0  4993.8    0.07       0
  5117.9    0.16       0  5218.6    0.05       0
Bank Sta=4790.7,5127.5
Exp/Cntr=0.3,0.1

Type RM Length L Ch R = 1,3427,525,525,525
BEGIN DESCRIPTION:
UNT 022 in Running Cr Watershed 4.0
END DESCRIPTION:
XS GIS Cut Line= 3
      2899125.00      7062924.98      2899125.00      7063375.00
      2899424.99      7063874.99
#Sta/Elev= 30
  4572.4  490.19  4592.4  490.37  4682.4  487.67  4702.4  485.99  4749.4  479.56
  4772.4  475.99  4812.4  470.88  4832.4  469.87  4852.4  468.06  4870.2  467.48
  4904.8  466.10  4922.4  465.27  4962.4  464.95  4982.4  463.69  4992.4  463.86
  4999.2  462.85  4999.7  462.05  5005.2  462.05  5005.7  462.85  5006.1  462.90
  5030.2  464.77  5045.3  464.82  5217.8  465.44  5242.1  465.22  5309.2  466.10
  5385.9  468.52  5422.8  470.37  5560.8  481.07  5582.2  482.37  5605.5  482.88
#Mann=8,-1,0
  4572.4    0.05       0  4749.4    0.16       0  4870.2    0.05       0
  4999.2    0.03       0  5005.7    0.05       0  5006.1     0.1       0
  5045.3    0.07       0  5217.8    0.05       0
Bank Sta=4904.8,5309.2
Exp/Cntr=0.3,0.1

Type RM Length L Ch R = 1,2902,520,520,520
BEGIN DESCRIPTION:
UNT 022 in Running Cr Watershed 3.0
END DESCRIPTION:
XS GIS Cut Line= 3
      2898675.00      7062925.02      2898625.00      7063525.00
      2898775.01      7064025.02
#Sta/Elev= 30
  4433.0  490.12  4533.3  482.59  4623.6  477.72  4764.1  471.64  4864.5  463.65
  4985.2  462.90  4994.9  460.44  5001.7  456.08  5002.2  455.28  5007.7  455.28
  5008.2  456.08  5015.0  457.48  5025.0  462.49  5161.2  462.67  5189.1  460.90
  5212.5  460.93  5306.5  461.79  5343.0  462.90  5397.9  465.40  5403.1  465.10
  5421.4  467.15  5430.9  469.00  5436.1  468.56  5442.2  471.05  5463.1  473.33
  5469.2  474.63  5494.4  475.82  5515.3  478.43  5540.5  479.00  5557.1  480.70
#Mann=3,-1,0
  4433.0    0.05       0  5001.7    0.03       0  5008.2    0.05       0
Bank Sta=4985.2,5343
Exp/Cntr=0.3,0.1

Type RM Length L Ch R = 1,2382,546,546,546
BEGIN DESCRIPTION:
UNT 022 in Running Cr Watershed 2.0
END DESCRIPTION:
XS GIS Cut Line= 3
      2898225.00      7063075.01      2898125.00      7063525.00
      2898075.00      7064025.04
#Sta/Elev= 30
  4523.2  480.32  4639.7  477.21  4666.6  475.85  4683.2  473.55  4688.4  473.66
  4726.8  469.66  4731.9  469.87  4775.4  465.18  4856.9  461.31  4881.7  460.36
  4986.7  460.96  4994.2  459.79  5001.0  454.90  5001.5  454.10  5007.1  454.10
  5007.6  454.90  5014.3  456.09  5024.4  460.70  5031.9  460.91  5054.5  459.33
  5074.6  460.42  5137.4  459.22  5165.1  460.47  5237.9  460.41  5272.0  461.31
  5295.7  461.71  5315.8  464.42  5376.1  468.56  5456.5  475.66  5486.7  476.40
#Mann=3,-1,0
  4523.2    0.05       0  5001.0    0.03       0  5007.6    0.05       0
Bank Sta=4856.9,5272
Exp/Cntr=0.3,0.1

Type RM Length L Ch R = 1,1836,0,0,0
BEGIN DESCRIPTION:
UNT 022 in Running Cr Watershed 1.0
END DESCRIPTION:
XS GIS Cut Line= 3
      2897625.00      7063125.04      2897575.00      7063575.00
      2897824.99      7063974.98
#Sta/Elev= 30
  4594.9  477.46  4655.2  476.45  4715.6  477.04  4745.8  476.29  4765.9  474.56
  4806.1  467.75  4816.2  466.72  4826.3  467.23  4886.6  461.41  4965.4  459.44
  4987.3  457.90  4997.3  454.53  5004.1  453.41  5004.6  452.61  5010.2  452.61
  5010.7  453.41  5017.4  457.55  5027.5  459.66  5055.3  458.78  5091.8  458.96
  5113.1  456.77  5142.0  458.38  5228.6  458.46  5289.7  459.44  5317.1  460.27
  5338.3  461.87  5389.6  464.11  5417.3  467.38  5475.1  472.16  5519.3  474.21
#Mann=3,-1,0
  4594.9    0.05       0  5004.1    0.03       0  5010.7    0.05       0
Bank Sta=4965.4,5289.7
Exp/Cntr=0.3,0.1

Chan Stop Cuts=-1