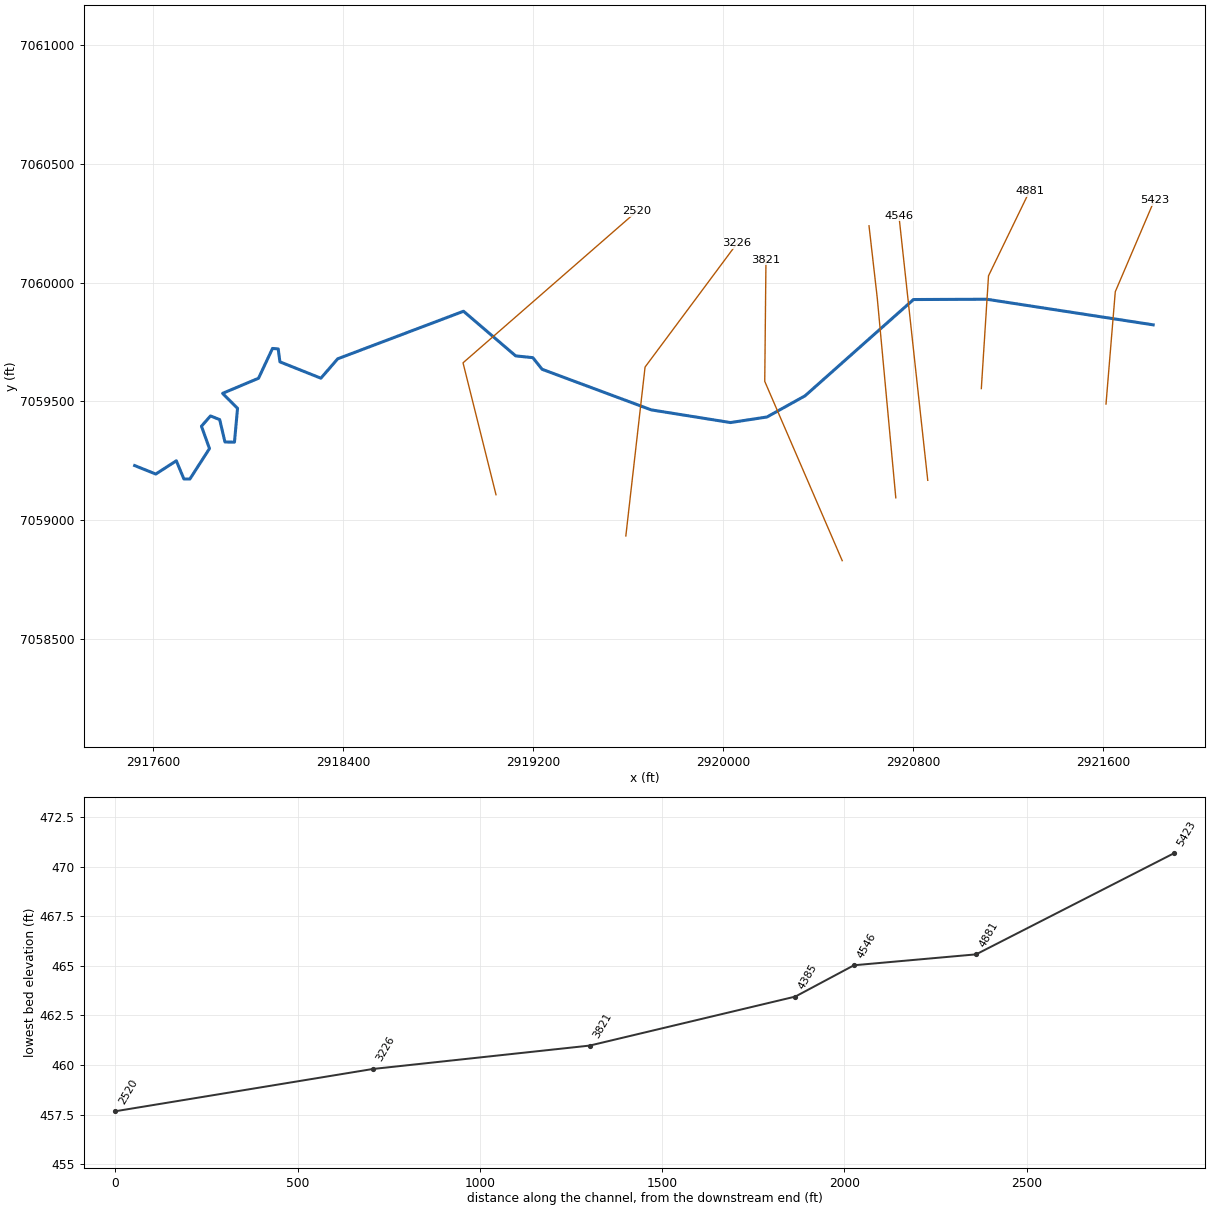
--- UNT 023 in Running Cr Watershed.prj (project) ---

Proj Title=UNT 023 in Running Cr Watershed Base Level Engineering
Current Plan=p01
Default Exp/Contr=0.3,0.1
English Units
Geom File=g01
Flow File=f01
Plan File=p01
BEGIN DESCRIPTION:
UNT 023 in Running Cr Watershed
END DESCRIPTION:

--- UNT 023 in Running Cr Watershed.p01 (plan) ---

Plan Title=Multiple Run
Short Identifier=Multiple
Geom File=g01
Flow File=f01
Subcritical Flow
K Sum by GR= 0
Std Step Tol= 0.01
Critical Tol= 0.01
Num of Std Step Trials= 20
Max Error Tol= 0.3
Flow Tol Ratio= 0.001
Split Flow NTrial= 30
Split Flow Tol= 0.02
Split Flow Ratio= 0.02
Log Output Level= 0
Friction Slope Method= 1
Unsteady Friction Slope Method= 2
Unsteady Bridges Friction Slope Method= 1
Parabolic Critical Depth
Global Vel Dist=  1 , 1 , 1
Global Log Level= 0
CheckData=True
Encroach Param= -1, 0, 0, 0
BEGIN DESCRIPTION:
Multiple Run
END DESCRIPTION:

--- UNT 023 in Running Cr Watershed.f01 (steady flow) ---

Flow Title=Multiple
Number of Profiles=7
Profile Names=10-year,25-year,50-year,1pct_min,100-year,1pct_plu,500-year
River Rch & RM= UNT 023 in Runni,Reach-1,5423
     620     836    1013     611    1219    2432    1765
River Rch & RM= UNT 023 in Runni,Reach-1,3821
     712     965    1173     709    1415    2823    2060
Boundary for River Rch & Prof#=UNT 023 in Runni,Reach-1,1
Up Type=0
Dn Type=3
Dn Slope=0.005
Boundary for River Rch & Prof#=UNT 023 in Runni,Reach-1,2
Up Type=0
Dn Type=3
Dn Slope=0.005
Boundary for River Rch & Prof#=UNT 023 in Runni,Reach-1,3
Up Type=0
Dn Type=3
Dn Slope=0.005
Boundary for River Rch & Prof#=UNT 023 in Runni,Reach-1,4
Up Type=0
Dn Type=3
Dn Slope=0.005
Boundary for River Rch & Prof#=UNT 023 in Runni,Reach-1,5
Up Type=0
Dn Type=3
Dn Slope=0.005
Boundary for River Rch & Prof#=UNT 023 in Runni,Reach-1,6
Up Type=0
Dn Type=3
Dn Slope=0.005
Boundary for River Rch & Prof#=UNT 023 in Runni,Reach-1,7
Up Type=0
Dn Type=3
Dn Slope=0.005

--- UNT 023 in Running Cr Watershed.g01 (geometry) ---

Geom Title=Existing Conditions

River Reach=UNT 023 in Runni,Reach-1
Reach XY= 30
      2921811.15      7059822.06      2921110.24      7059929.86
      2920801.44      7059928.65      2920344.64      7059523.00
      2920184.29      7059433.84      2920030.61      7059410.45
      2919696.89      7059463.86      2919237.28      7059634.79
      2919197.93      7059683.84      2919125.89      7059691.25
      2918906.19      7059879.29      2918376.15      7059678.95
      2918305.41      7059597.27      2918132.71      7059666.20
      2918125.59      7059720.71      2918101.60      7059722.67
      2918042.69      7059597.07      2917891.32      7059533.43
      2917954.29      7059470.43      2917941.30      7059327.95
      2917901.24      7059328.57      2917879.11      7059422.86
      2917840.34      7059438.34      2917802.28      7059395.06
      2917836.06      7059300.80      2917753.66      7059172.81
      2917728.31      7059172.64      2917696.37      7059249.41
      2917609.94      7059193.55      2917520.90      7059229.29

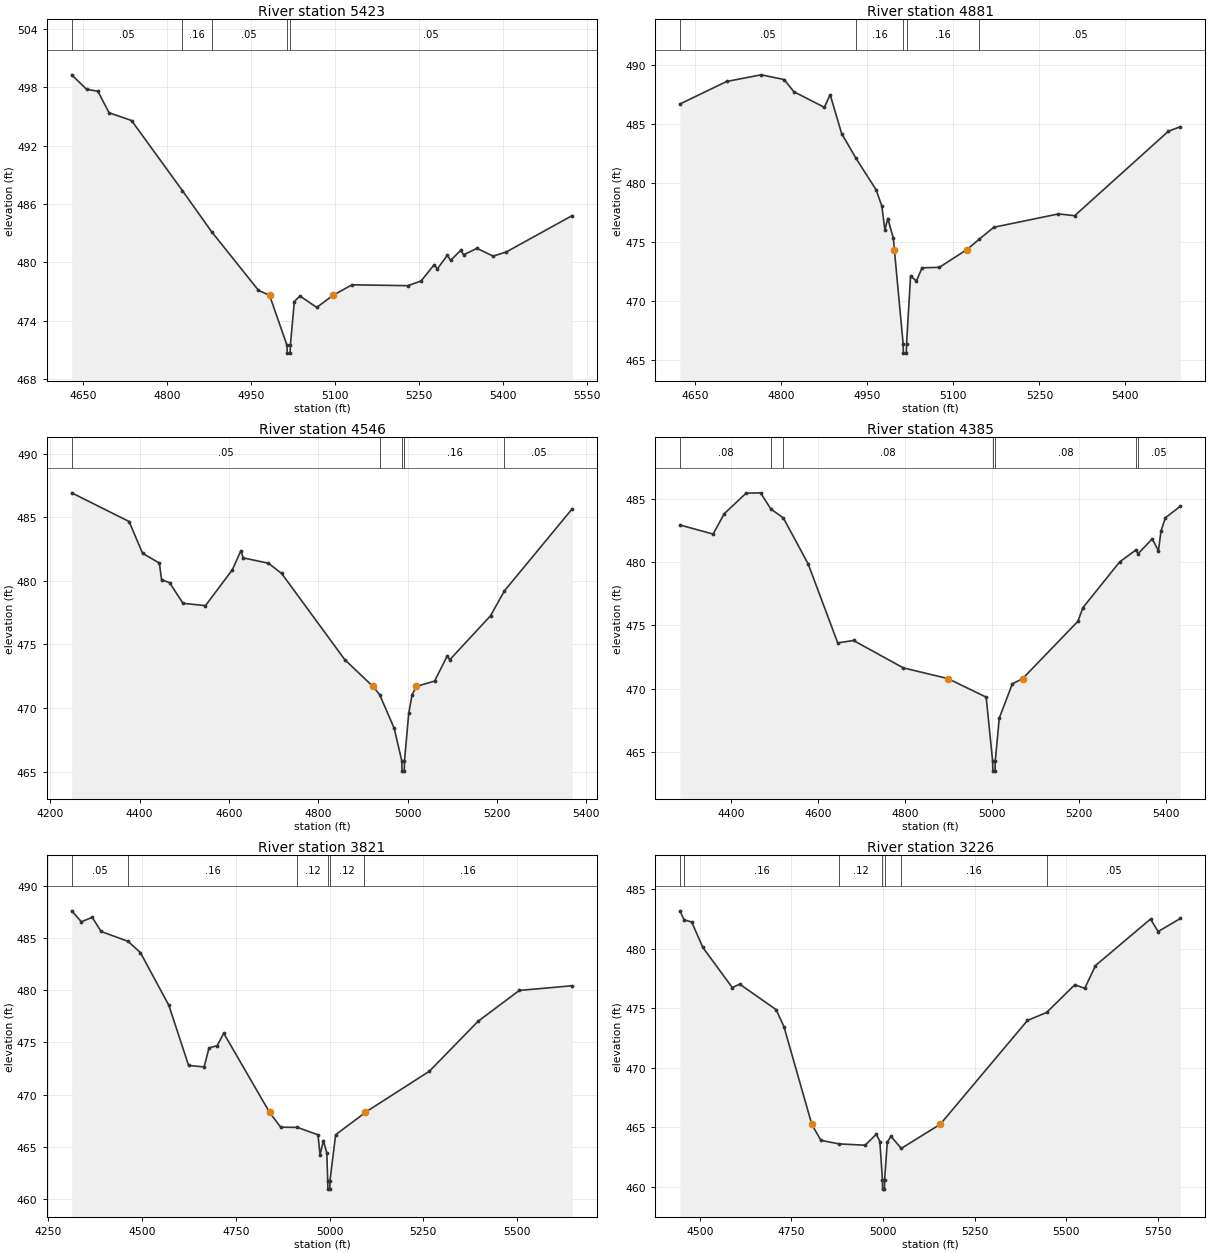
Type RM Length L Ch R = 1,5423,542,542,542
BEGIN DESCRIPTION:
UNT 023 in Running Cr Watershed 7.0
END DESCRIPTION:
XS GIS Cut Line= 3
      2921612.42      7059488.39      2921651.49      7059961.51
      2921816.40      7060347.75
#Sta/Elev= 30
  4629.0  499.30  4655.7  497.81  4675.8  497.61  4695.8  495.40  4736.0  494.60
  4827.0  487.38  4879.0  483.17  4962.9  477.13  4982.8  476.61  5013.9  471.47
  5014.4  470.67  5019.4  470.67  5019.9  471.47  5027.0  475.98  5037.0  476.55
  5067.1  475.37  5095.9  476.61  5130.1  477.70  5229.9  477.61  5253.5  478.09
  5277.1  479.77  5282.6  479.33  5300.7  480.75  5306.2  480.20  5324.3  481.24
  5329.8  480.79  5353.4  481.45  5382.4  480.65  5406.0  481.08  5523.7  484.82
#Mann=5,-1,0
  4629.0    0.05       0  4827.0    0.16       0  4879.0    0.05       0
  5013.9    0.03       0  5019.9    0.05       0
Bank Sta=4982.8,5095.9
Exp/Cntr=0.3,0.1

Type RM Length L Ch R = 1,4881,335,335,335
BEGIN DESCRIPTION:
UNT 023 in Running Cr Watershed 6.0
END DESCRIPTION:
XS GIS Cut Line= 3
      2921087.25      7059553.50      2921117.51      7060028.48
      2921290.63      7060385.59
#Sta/Elev= 30
  4623.1  486.66  4704.8  488.57  4764.9  489.13  4805.0  488.73  4821.8  487.70
  4875.1  486.38  4885.1  487.46  4905.2  484.16  4930.4  482.05  4965.3  479.40
  4975.3  478.02  4980.6  476.01  4985.6  476.97  4995.4  475.30  4997.1  474.34
  5012.4  466.38  5012.9  465.58  5017.9  465.58  5018.4  466.38  5025.4  472.11
  5035.4  471.68  5045.5  472.80  5075.5  472.84  5123.6  474.34  5144.8  475.21
  5170.5  476.23  5283.3  477.36  5311.5  477.21  5475.1  484.36  5495.9  484.74
#Mann=5,-1,0
  4623.1    0.05       0  4930.4    0.16       0  5012.4    0.07       0
  5018.4    0.16       0  5144.8    0.05       0
Bank Sta=4997.1,5123.6
Exp/Cntr=0.3,0.1

Type RM Length L Ch R = 1,4546,161,161,161
BEGIN DESCRIPTION:
UNT 023 in Running Cr Watershed 5.0
END DESCRIPTION:
XS GIS Cut Line= 3
      2920861.56      7059167.20      2920805.14      7059683.73
      2920740.18      7060281.30
#Sta/Elev= 30
  4247.9  486.94  4376.5  484.68  4406.6  482.18  4444.2  481.41  4449.2  480.09
  4467.0  479.87  4497.2  478.24  4547.5  478.06  4607.8  480.89  4626.8  482.39
  4631.8  481.82  4688.3  481.40  4718.1  480.59  4859.3  473.81  4922.4  471.70
  4937.5  471.05  4970.0  468.40  4987.1  465.83  4987.6  465.03  4992.6  465.03
  4993.1  465.83  5002.6  469.59  5010.2  471.05  5019.8  471.70  5060.5  472.12
  5089.1  474.12  5094.2  473.79  5185.7  477.26  5217.0  479.23  5368.6  485.68
#Mann=5,-1,0
  4247.9    0.05       0  4937.5    0.16       0  4987.1    0.07       0
  4993.1    0.16       0  5217.0    0.05       0
Bank Sta=4922.4,5019.8
Exp/Cntr=0.3,0.1

Type RM Length L Ch R = 1,4385,564,564,564
BEGIN DESCRIPTION:
UNT 023 in Running Cr Watershed 4.0
END DESCRIPTION:
XS GIS Cut Line= 3
      2920727.01      7059093.45      2920648.89      7059935.47
      2920614.17      7060239.26
#Sta/Elev= 30
  4282.3  482.97  4358.7  482.25  4384.3  483.86  4434.5  485.49  4468.0  485.52
  4491.3  484.25  4520.5  483.52  4577.4  479.88  4645.4  473.62  4681.7  473.81
  4796.1  471.64  4898.7  470.79  4986.9  469.32  5001.8  464.25  5002.3  463.45
  5007.3  463.45  5007.8  464.25  5017.0  467.65  5047.1  470.37  5070.9  470.79
  5197.9  475.33  5209.6  476.42  5293.9  480.04  5331.4  480.99  5336.3  480.69
  5369.0  481.87  5383.2  480.92  5389.2  482.51  5399.2  483.54  5433.7  484.46
#Mann=7,-1,0
  4282.3    0.08       0  4491.3    0.16       0  4520.5    0.08       0
  5001.8    0.07       0  5007.8    0.08       0  5331.4    0.16       0
  5336.3    0.05       0
Bank Sta=4898.7,5070.9
Exp/Cntr=0.3,0.1

Type RM Length L Ch R = 1,3821,595,595,595
BEGIN DESCRIPTION:
UNT 023 in Running Cr Watershed 3.0
END DESCRIPTION:
XS GIS Cut Line= 3
      2920501.30      7058828.75      2920175.00      7059583.91
      2920180.13      7060096.04
#Sta/Elev= 30
  4312.2  487.58  4338.0  486.53  4367.0  486.96  4390.5  485.61  4462.6  484.66
  4495.4  483.59  4571.3  478.55  4624.0  472.80  4665.3  472.66  4678.5  474.47
  4700.3  474.70  4717.7  475.88  4840.0  468.31  4869.6  466.90  4914.3  466.88
  4969.1  466.17  4974.5  464.25  4983.5  465.62  4992.6  464.43  4995.0  461.78
  4995.5  460.98  5000.5  460.98  5001.0  461.78  5016.1  466.18  5092.9  468.24
  5094.7  468.31  5265.9  472.24  5395.9  477.02  5506.0  479.97  5647.0  480.42
#Mann=6,-1,0
  4312.2    0.05       0  4462.6    0.16       0  4914.3    0.12       0
  4995.0    0.07       0  5001.0    0.12       0  5092.9    0.16       0
Bank Sta=4840,5094.7
Exp/Cntr=0.3,0.1

Type RM Length L Ch R = 1,3226,706,706,706
BEGIN DESCRIPTION:
UNT 023 in Running Cr Watershed 2.0
END DESCRIPTION:
XS GIS Cut Line= 3
      2919589.86      7058932.88      2919670.86      7059644.23
      2920058.59      7060165.48
#Sta/Elev= 30
  4445.9  483.18  4457.6  482.42  4478.2  482.24  4508.4  480.11  4588.9  476.73
  4609.1  477.02  4708.5  474.88  4729.8  473.45  4805.8  465.25  4830.5  463.90
  4880.4  463.60  4951.3  463.49  4982.0  464.42  4991.5  463.80  4998.5  460.60
  4999.0  459.80  5004.1  459.80  5004.6  460.60  5011.7  463.74  5021.7  464.24
  5049.9  463.22  5156.3  465.25  5394.2  473.97  5446.4  474.64  5523.5  476.97
  5550.6  476.67  5579.8  478.58  5730.0  482.49  5750.8  481.44  5811.5  482.54
#Mann=7,-1,0
  4445.9    0.05       0  4457.6    0.16       0  4880.4    0.12       0
  4998.5    0.07       0  5004.6    0.12       0  5049.9    0.16       0
  5446.4    0.05       0
Bank Sta=4805.8,5156.3
Exp/Cntr=0.3,0.1

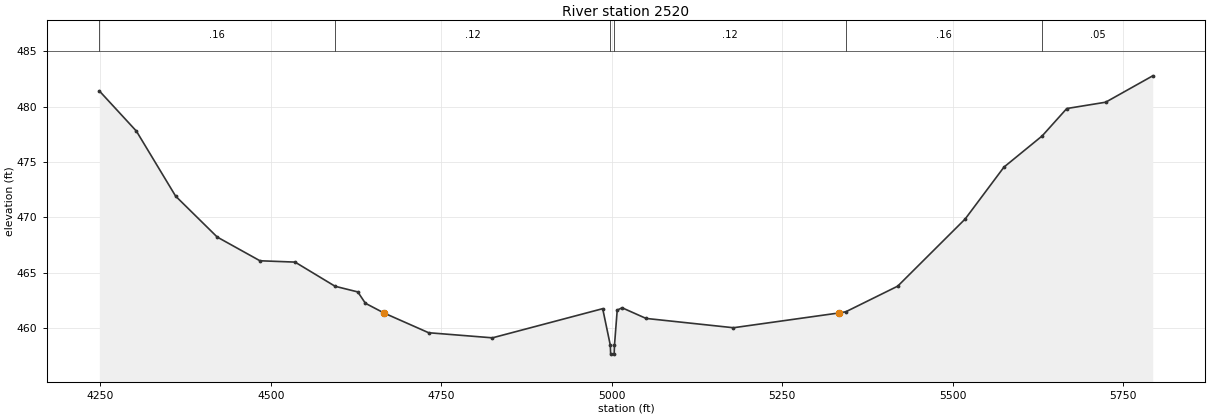
Type RM Length L Ch R = 1,2520,0,0,0
BEGIN DESCRIPTION:
UNT 023 in Running Cr Watershed 1.0
END DESCRIPTION:
XS GIS Cut Line= 3
      2919042.99      7059106.45      2918904.09      7059662.03
      2919636.96      7060301.17
#Sta/Elev= 30
  4248.3  481.41  4302.7  477.78  4360.2  471.92  4421.2  468.23  4483.9  466.09
  4535.4  465.97  4594.1  463.79  4627.4  463.28  4638.5  462.26  4665.8  461.38
  4731.3  459.60  4824.9  459.14  4986.6  461.77  4997.8  458.47  4998.3  457.67
  5003.4  457.67  5003.9  458.47  5007.9  461.64  5015.1  461.85  5050.2  460.89
  5178.4  460.05  5332.7  461.38  5343.2  461.49  5419.3  463.80  5518.3  469.86
  5575.2  474.54  5631.2  477.35  5667.3  479.82  5724.3  480.39  5793.4  482.77
#Mann=6,-1,0
  4248.3    0.16       0  4594.1    0.12       0  4997.8    0.07       0
  5003.9    0.12       0  5343.2    0.16       0  5631.2    0.05       0
Bank Sta=4665.8,5332.7
Exp/Cntr=0.3,0.1

Chan Stop Cuts=-1