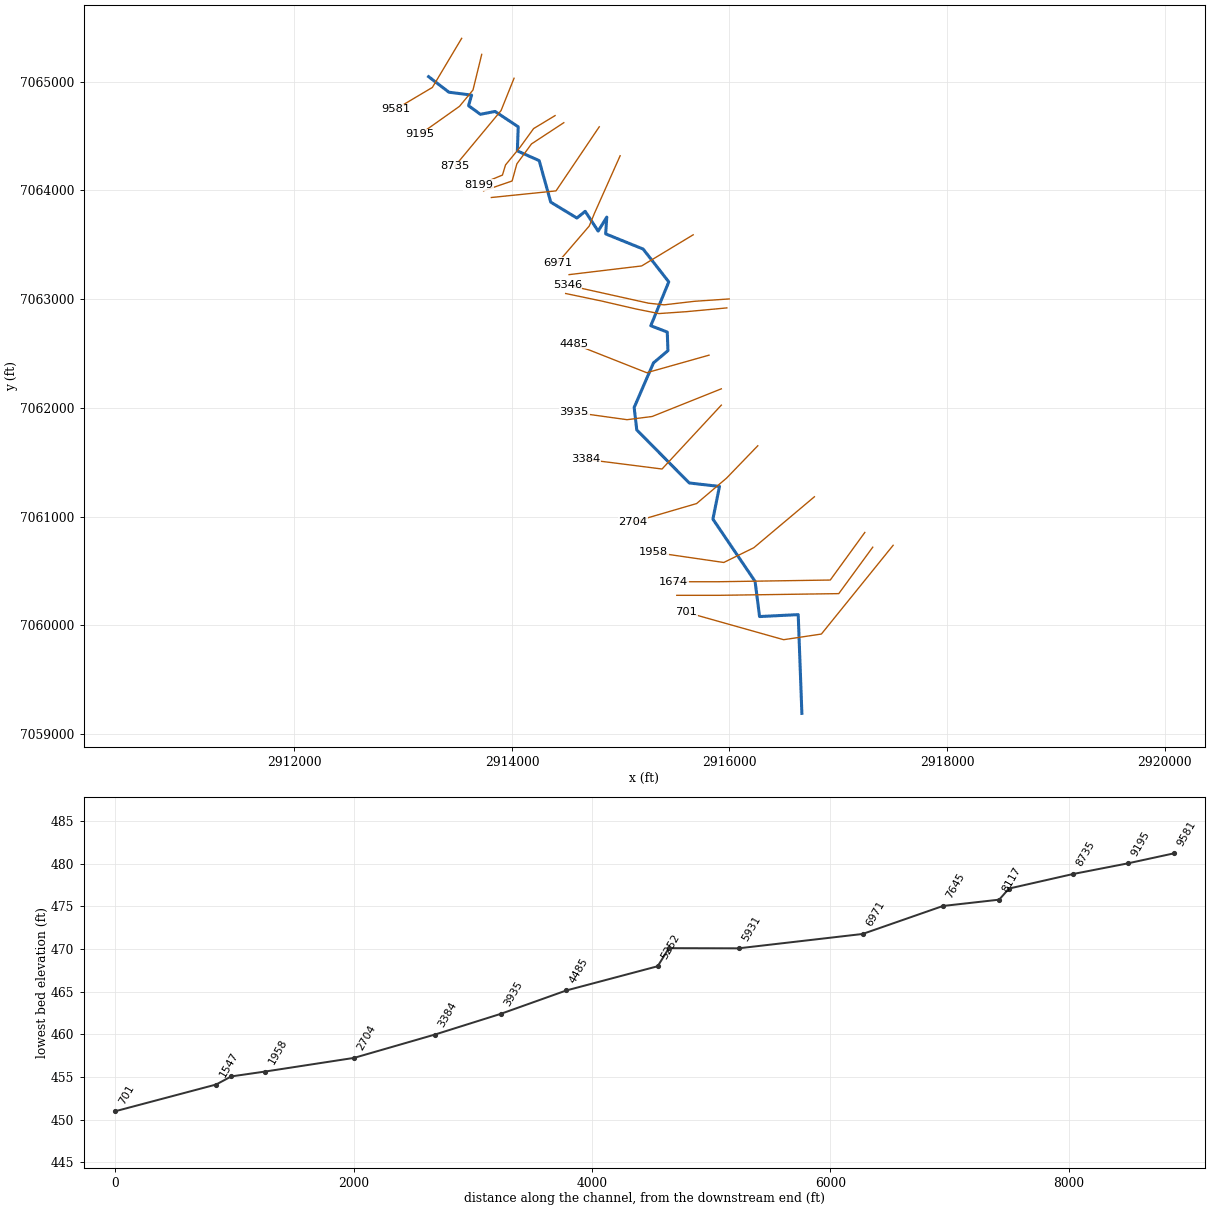
--- UNT 024 in Running Cr Watershed.prj (project) ---

Proj Title=UNT 024 in Running Cr Watershed Base Level Engineering
Current Plan=p01
Default Exp/Contr=0.3,0.1
English Units
Geom File=g01
Flow File=f01
Plan File=p01
BEGIN DESCRIPTION:
UNT 024 in Running Cr Watershed
END DESCRIPTION:

--- UNT 024 in Running Cr Watershed.p01 (plan) ---

Plan Title=Multiple Run
Short Identifier=Multiple
Geom File=g01
Flow File=f01
Subcritical Flow
K Sum by GR= 0
Std Step Tol= 0.01
Critical Tol= 0.01
Num of Std Step Trials= 20
Max Error Tol= 0.3
Flow Tol Ratio= 0.001
Split Flow NTrial= 30
Split Flow Tol= 0.02
Split Flow Ratio= 0.02
Log Output Level= 0
Friction Slope Method= 1
Unsteady Friction Slope Method= 2
Unsteady Bridges Friction Slope Method= 1
Parabolic Critical Depth
Global Vel Dist=  1 , 1 , 1
Global Log Level= 0
CheckData=True
Encroach Param= -1, 0, 0, 0
BEGIN DESCRIPTION:
Multiple Run
END DESCRIPTION:

--- UNT 024 in Running Cr Watershed.f01 (steady flow) ---

Flow Title=Multiple
Number of Profiles=7
Profile Names=10-year,25-year,50-year,1pct_min,100-year,1pct_plu,500-year
River Rch & RM= UNT 024 in Runni,Reach-1,9581
     775    1041    1256     752    1500    2992    2132
River Rch & RM= UNT 024 in Runni,Reach-1,8199
     946    1281    1555     934    1864    3719    2675
Boundary for River Rch & Prof#=UNT 024 in Runni,Reach-1,1
Up Type=0
Dn Type=3
Dn Slope=0.005
Boundary for River Rch & Prof#=UNT 024 in Runni,Reach-1,2
Up Type=0
Dn Type=3
Dn Slope=0.005
Boundary for River Rch & Prof#=UNT 024 in Runni,Reach-1,3
Up Type=0
Dn Type=3
Dn Slope=0.005
Boundary for River Rch & Prof#=UNT 024 in Runni,Reach-1,4
Up Type=0
Dn Type=3
Dn Slope=0.005
Boundary for River Rch & Prof#=UNT 024 in Runni,Reach-1,5
Up Type=0
Dn Type=3
Dn Slope=0.005
Boundary for River Rch & Prof#=UNT 024 in Runni,Reach-1,6
Up Type=0
Dn Type=3
Dn Slope=0.005
Boundary for River Rch & Prof#=UNT 024 in Runni,Reach-1,7
Up Type=0
Dn Type=3
Dn Slope=0.005

--- UNT 024 in Running Cr Watershed.g01 (geometry) ---

Geom Title=Existing Conditions

River Reach=UNT 024 in Runni,Reach-1
Reach XY= 30
      2913233.45      7065044.98      2913419.99      7064902.40
      2913628.68      7064875.56      2913600.79      7064778.17
      2913709.35      7064699.15      2913844.69      7064725.37
      2914057.16      7064584.12      2914049.51      7064362.63
      2914250.05      7064273.19      2914356.38      7063891.57
      2914596.78      7063745.37      2914673.19      7063806.88
      2914792.47      7063625.25      2914871.62      7063753.58
      2914861.32      7063599.61      2915205.70      7063460.22
      2915441.76      7063158.46      2915276.35      7062755.28
      2915427.88      7062696.63      2915433.94      7062525.77
      2915300.81      7062413.09      2915123.34      7062003.52
      2915147.50      7061796.94      2915629.96      7061309.24
      2915907.96      7061277.30      2915847.55      7060976.73
      2916235.38      7060404.26      2916276.52      7060080.94
      2916631.85      7060098.74      2916665.59      7059190.71

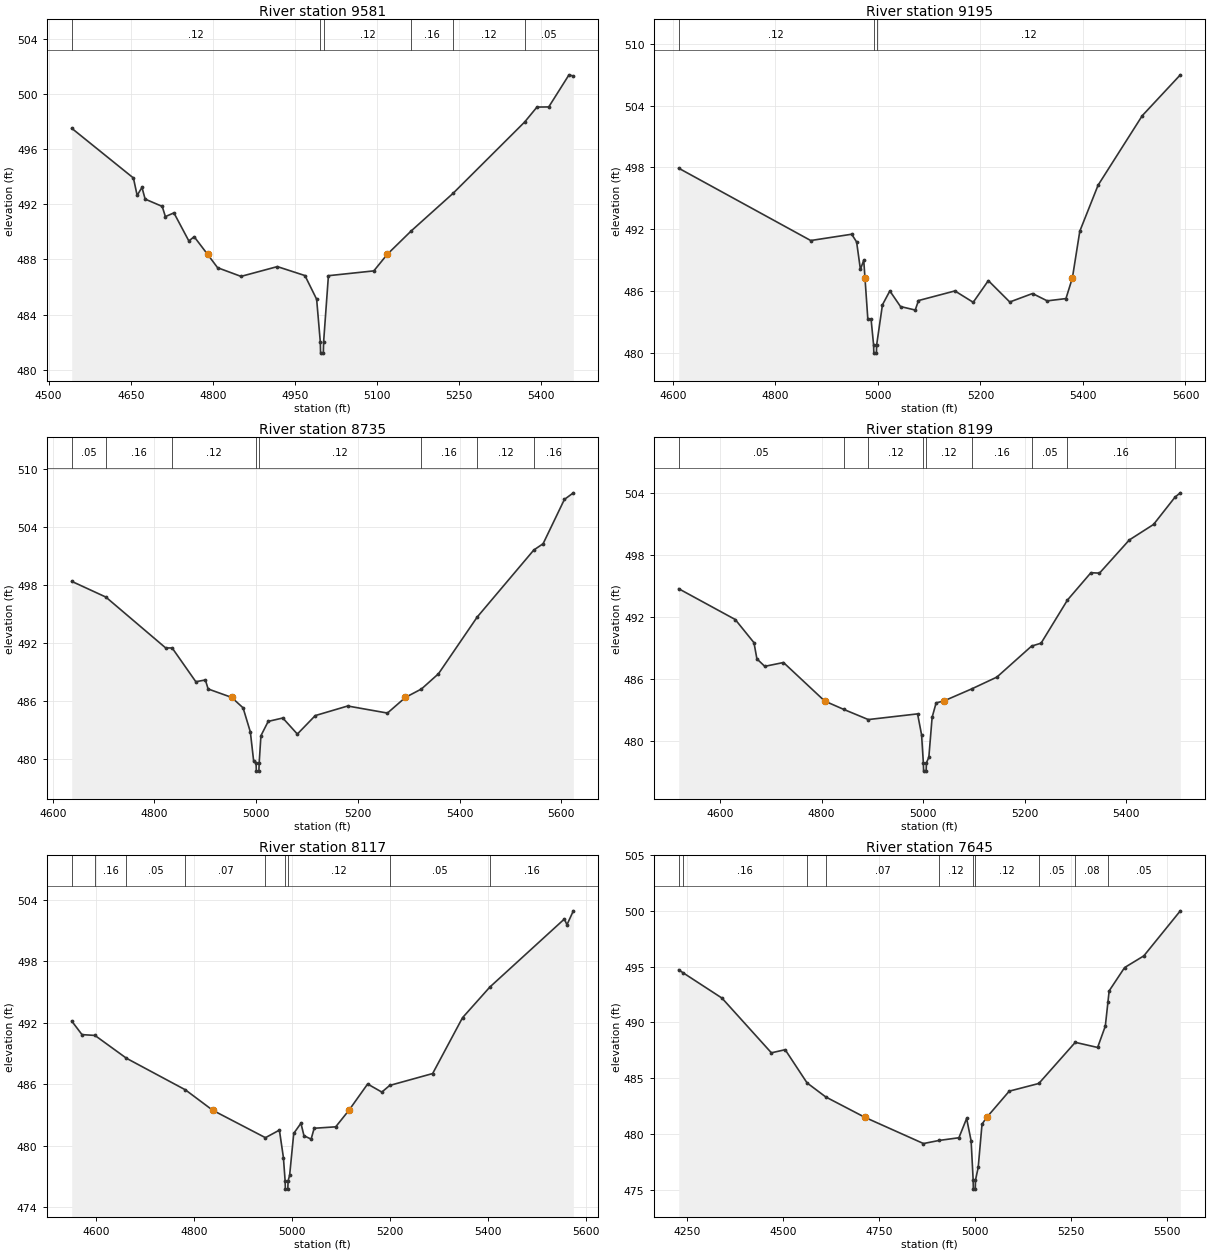
Type RM Length L Ch R = 1,9581,386,386,386
BEGIN DESCRIPTION:
UNT 024 in Running Cr Watershed 11.0
END DESCRIPTION:
XS GIS Cut Line= 3
      2913537.23      7065397.68      2913268.16      7064946.32
      2912931.82      7064746.69
#Sta/Elev= 30
  4542.3  497.52  4655.0  493.91  4661.8  492.65  4670.6  493.23  4676.4  492.38
  4707.6  491.85  4713.4  491.11  4729.0  491.38  4756.3  489.34  4766.0  489.65
  4790.5  488.37  4808.8  487.40  4851.6  486.77  4918.0  487.48  4968.4  486.83
  4989.8  485.11  4996.5  482.00  4997.0  481.20  5002.0  481.20  5002.5  482.00
  5011.3  486.82  5094.3  487.17  5118.8  488.37  5162.6  490.07  5239.1  492.80
  5370.0  497.98  5392.4  499.06  5413.9  499.07  5450.9  501.40  5458.9  501.31
#Mann=6,-1,0
  4542.3    0.12       0  4996.5    0.07       0  5002.5    0.12       0
  5162.6    0.16       0  5239.1    0.12       0  5370.0    0.05       0
Bank Sta=4790.5,5118.8
Exp/Cntr=0.3,0.1

Type RM Length L Ch R = 1,9195,460,460,460
BEGIN DESCRIPTION:
Mapping XS df595e13
END DESCRIPTION:
XS GIS Cut Line= 4
      2913721.71      7065250.14      2913641.42      7064922.45
      2913517.72      7064772.71      2913153.13      7064514.46
#Sta/Elev= 30
  4611.6  497.93  4869.1  490.93  4949.0  491.54  4958.6  490.79  4966.0  488.14
  4972.5  489.02  4974.9  487.32  4980.4  483.38  4986.8  483.32  4991.7  480.83
  4992.2  480.03  4997.2  480.03  4997.7  480.83  5009.0  484.71  5023.4  486.05
  5044.2  484.54  5072.9  484.20  5079.3  485.12  5150.3  486.05  5186.0  484.95
  5215.5  487.05  5257.3  484.98  5301.7  485.80  5330.4  485.09  5366.9  485.31
  5379.5  487.32  5393.9  491.83  5429.6  496.29  5515.8  503.02  5590.0  506.97
#Mann=3,-1,0
  4611.6    0.12       0  4991.7    0.07       0  4997.7    0.12       0
Bank Sta=4974.9,5379.5
Exp/Cntr=0.3,0.1

Type RM Length L Ch R = 1,8735,536,536,536
BEGIN DESCRIPTION:
UNT 024 in Running Cr Watershed 10.0
END DESCRIPTION:
XS GIS Cut Line= 3
      2914019.01      7065030.92      2913899.67      7064733.65
      2913474.31      7064221.48
#Sta/Elev= 30
  4637.4  498.39  4704.4  496.77  4822.1  491.51  4834.8  491.51  4881.3  488.02
  4900.1  488.20  4905.5  487.27  4951.7  486.40  4974.2  485.32  4988.5  482.83
  4995.0  479.82  4999.8  479.58  5000.3  478.78  5005.3  478.78  5005.8  479.58
  5009.3  482.44  5023.6  483.92  5052.3  484.27  5080.9  482.61  5116.1  484.52
  5179.9  485.51  5258.0  484.78  5293.4  486.40  5324.9  487.27  5358.3  488.84
  5434.4  494.70  5545.7  501.63  5564.0  502.28  5605.9  506.86  5623.5  507.54
#Mann=8,-1,0
  4637.4    0.05       0  4704.4    0.16       0  4834.8    0.12       0
  4999.8    0.07       0  5005.8    0.12       0  5324.9    0.16       0
  5434.4    0.12       0  5545.7    0.16       0
Bank Sta=4951.7,5293.4
Exp/Cntr=0.3,0.1

Type RM Length L Ch R = 1,8199,82,82,82
BEGIN DESCRIPTION:
Mapping XS 46fb05bc
END DESCRIPTION:
XS GIS Cut Line= 6
      2914396.25      7064687.19      2914198.80      7064567.85
      2914072.93      7064394.24      2913940.55      7064233.65
      2913912.34      7064140.33      2913691.95      7064049.58
#Sta/Elev= 30
  4518.1  494.73  4629.6  491.75  4666.5  489.51  4672.3  487.94  4687.8  487.22
  4724.7  487.59  4806.0  483.86  4843.2  483.06  4891.9  482.07  4989.1  482.62
  4997.0  480.59  5000.5  477.88  5001.0  477.08  5006.0  477.08  5006.5  477.88
  5011.3  478.42  5017.8  482.29  5025.7  483.69  5040.5  483.86  5095.5  485.03
  5145.5  486.18  5213.9  489.18  5232.6  489.46  5284.7  493.64  5330.9  496.28
  5347.8  496.24  5406.6  499.45  5454.4  500.95  5497.0  503.61  5507.2  504.01
#Mann=9,-1,0
  4518.1    0.05       0  4843.2    0.07       0  4891.9    0.12       0
  5000.5    0.07       0  5006.5    0.12       0  5095.5    0.16       0
  5213.9    0.05       0  5284.7    0.16       0  5497.0    0.07       0
Bank Sta=4806,5040.5
Exp/Cntr=0.3,0.1

Type RM Length L Ch R = 1,8117,472,472,472
BEGIN DESCRIPTION:
UNT 024 in Running Cr Watershed 9.0
END DESCRIPTION:
XS GIS Cut Line= 5
      2914476.55      7064622.09      2914179.27      7064426.79
      2914044.88      7064243.49      2914001.32      7064086.08
      2913738.28      7063995.52
#Sta/Elev= 30
  4550.4  492.18  4571.3  490.86  4597.8  490.78  4662.2  488.55  4782.5  485.47
  4838.2  483.48  4946.0  480.80  4974.5  481.54  4982.7  478.86  4986.2  476.58
  4986.7  475.78  4991.7  475.78  4992.2  476.58  4995.4  477.13  5003.8  481.22
  5018.5  482.21  5024.7  480.99  5039.3  480.66  5045.5  481.72  5089.5  481.86
  5116.6  483.48  5154.7  486.04  5183.7  485.25  5199.8  485.90  5287.5  487.06
  5348.5  492.51  5404.3  495.50  5556.5  502.14  5561.8  501.58  5574.9  502.94
#Mann=9,-1,0
  4550.4    0.05       0  4597.8    0.16       0  4662.2    0.05       0
  4782.5    0.07       0  4946.0    0.12       0  4986.2    0.07       0
  4992.2    0.12       0  5199.8    0.05       0  5404.3    0.16       0
Bank Sta=4838.2,5116.6
Exp/Cntr=0.3,0.1

Type RM Length L Ch R = 1,7645,674,674,674
BEGIN DESCRIPTION:
UNT 024 in Running Cr Watershed 8.0
END DESCRIPTION:
XS GIS Cut Line= 3
      2914802.57      7064584.42      2914404.96      7063994.93
      2913810.30      7063934.16
#Sta/Elev= 30
  4227.1  494.72  4238.5  494.45  4340.0  492.18  4468.9  487.27  4504.9  487.55
  4562.0  484.57  4610.8  483.31  4713.0  481.48  4865.7  479.13  4906.9  479.41
  4958.2  479.65  4978.3  481.38  4990.0  479.38  4995.4  475.84  4995.9  475.04
  5000.9  475.04  5001.4  475.84  5008.5  476.99  5018.5  480.87  5030.8  481.48
  5089.5  483.83  5166.7  484.52  5261.8  488.21  5320.1  487.75  5340.2  489.67
  5347.0  491.82  5350.2  492.83  5390.5  494.92  5440.7  495.97  5535.9  500.01
#Mann=10,-1,0
  4227.1    0.05       0  4238.5    0.16       0  4562.0    0.12       0
  4610.8    0.07       0  4906.9    0.12       0  4995.4    0.07       0
  5001.4    0.12       0  5166.7    0.05       0  5261.8    0.08       0
  5347.0    0.05       0
Bank Sta=4713,5030.8
Exp/Cntr=0.3,0.1

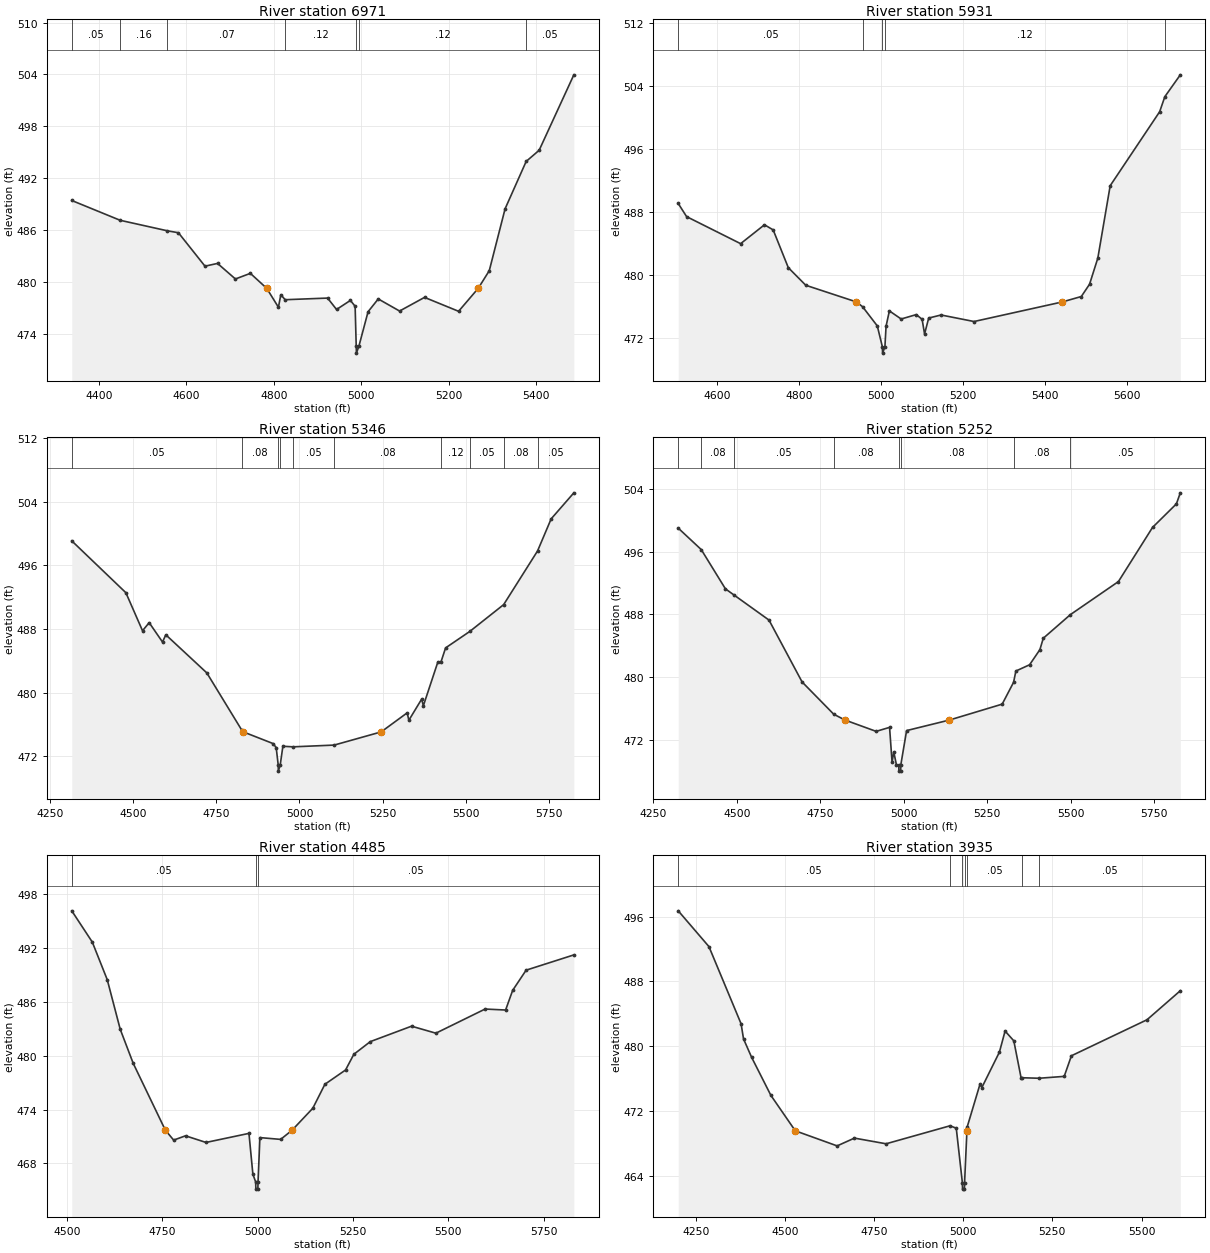
Type RM Length L Ch R = 1,6971,1040,1040,1040
BEGIN DESCRIPTION:
UNT 024 in Running Cr Watershed 7.0
END DESCRIPTION:
XS GIS Cut Line= 4
      2914994.37      7064317.84      2914757.39      7063786.60
      2914710.52      7063672.02      2914421.45      7063336.07
#Sta/Elev= 30
  4337.9  489.42  4448.6  487.13  4556.9  485.91  4581.9  485.69  4642.7  481.82
  4671.4  482.14  4712.3  480.34  4746.5  480.99  4783.9  479.26  4810.7  477.07
  4816.2  478.52  4826.1  477.94  4923.2  478.13  4943.7  476.81  4975.4  477.86
  4986.2  477.18  4988.7  472.56  4989.2  471.76  4994.8  472.56  5015.8  476.55
  5039.1  478.03  5087.9  476.63  5145.0  478.21  5222.9  476.60  5267.9  479.26
  5293.1  481.30  5329.3  488.46  5377.5  493.94  5407.2  495.23  5486.6  503.96
#Mann=7,-1,0
  4337.9    0.05       0  4448.6    0.16       0  4556.9    0.07       0
  4826.1    0.12       0  4988.7    0.07       0  4994.8    0.12       0
  5377.5    0.05       0
Bank Sta=4783.9,5267.9
Exp/Cntr=0.3,0.1

Type RM Length L Ch R = 1,5931,585,585,585
BEGIN DESCRIPTION:
UNT 024 in Running Cr Watershed 6.0
END DESCRIPTION:
XS GIS Cut Line= 4
      2915666.21      7063591.26      2915317.29      7063380.35
      2915192.29      7063304.83      2914525.00      7063225.00
#Sta/Elev= 30
  4505.2  489.11  4525.6  487.44  4657.5  484.00  4715.7  486.40  4737.0  485.75
  4773.9  480.95  4816.6  478.71  4940.3  476.59  4955.3  475.98  4991.2  473.54
  5003.6  470.88  5004.1  470.08  5009.8  470.88  5012.6  473.50  5020.7  475.45
  5049.5  474.42  5086.4  474.98  5100.6  474.38  5106.6  472.52  5116.7  474.54
  5146.9  474.93  5227.4  474.10  5442.9  476.59  5489.3  477.28  5509.4  478.84
  5529.6  482.16  5559.8  491.37  5680.6  500.78  5693.2  502.69  5731.0  505.47
#Mann=5,-1,0
  4505.2    0.05       0  4955.3    0.12       0  5003.6    0.07       0
  5009.8    0.12       0  5693.2    0.16       0
Bank Sta=4940.3,5442.9
Exp/Cntr=0.3,0.1

Type RM Length L Ch R = 1,5346,94,94,94
BEGIN DESCRIPTION:
UNT 024 in Running Cr Watershed 5.0
END DESCRIPTION:
XS GIS Cut Line= 5
      2915997.38      7063001.44      2915678.40      7062979.74
      2915398.45      7062947.19      2915255.22      7062962.38
      2914508.29      7063128.22
#Sta/Elev= 30
  4314.9  499.10  4477.7  492.57  4527.8  487.78  4547.8  488.80  4587.9  486.36
  4597.9  487.27  4721.3  482.47  4826.6  475.25  4831.1  475.04  4920.7  473.57
  4930.0  473.06  4936.0  470.90  4936.5  470.10  4942.2  470.90  4950.1  473.23
  4981.0  473.16  5104.4  473.38  5245.8  475.04  5324.1  477.44  5329.2  476.51
  5367.7  479.17  5372.8  478.33  5416.3  483.83  5426.2  483.90  5439.7  485.62
  5512.4  487.69  5614.4  491.07  5716.4  497.83  5757.3  501.87  5825.6  505.15
#Mann=10,-1,0
  4314.9    0.05       0  4826.6    0.08       0  4936.0    0.03       0
  4942.2    0.08       0  4981.0    0.05       0  5104.4    0.08       0
  5426.2    0.12       0  5512.4    0.05       0  5614.4    0.08       0
  5716.4    0.05       0
Bank Sta=4831.1,5245.8
Exp/Cntr=0.3,0.1

Type RM Length L Ch R = 1,5252,767,767,767
BEGIN DESCRIPTION:
Mapping XS 5ac212bb
END DESCRIPTION:
XS GIS Cut Line= 6
      2915975.75      7062918.98      2915602.44      7062884.26
      2915350.71      7062866.89      2915144.54      7062908.13
      2914825.53      7062981.91      2914493.55      7063051.35
#Sta/Elev= 30
  4324.5  499.03  4393.4  496.29  4465.9  491.27  4492.7  490.45  4596.4  487.28
  4695.6  479.37  4790.4  475.25  4824.0  474.51  4917.4  473.06  4957.6  473.57
  4965.1  469.12  4970.2  470.44  4978.0  468.81  4985.1  468.78  4985.6  467.98
  4990.8  467.98  4991.3  468.78  5008.6  473.16  5137.1  474.51  5295.0  476.54
  5329.1  479.33  5336.0  480.77  5377.1  481.57  5407.9  483.50  5418.1  484.96
  5499.4  487.98  5643.2  492.20  5745.4  499.12  5816.9  502.13  5828.6  503.54
#Mann=8,-1,0
  4324.5    0.05       0  4393.4    0.08       0  4492.7    0.05       0
  4790.4    0.08       0  4985.1    0.04       0  4991.3    0.08       0
  5329.1    0.08       0  5499.4    0.05       0
Bank Sta=4824,5137.1
Exp/Cntr=0.3,0.1

Type RM Length L Ch R = 1,4485,550,550,550
BEGIN DESCRIPTION:
UNT 024 in Running Cr Watershed 4.0
END DESCRIPTION:
XS GIS Cut Line= 3
      2915812.05      7062484.51      2915239.16      7062323.06
      2914568.66      7062588.14
#Sta/Elev= 30
  4512.7  496.14  4566.5  492.66  4605.7  488.47  4639.7  482.95  4673.7  479.16
  4758.0  471.71  4779.8  470.60  4810.9  471.08  4864.6  470.34  4977.2  471.35
  4987.5  466.80  4994.8  465.94  4995.3  465.14  5000.5  465.14  5001.0  465.94
  5005.9  470.88  5060.3  470.68  5090.4  471.71  5144.6  474.15  5176.3  476.82
  5230.4  478.41  5252.2  480.16  5295.3  481.57  5403.4  483.29  5467.2  482.51
  5596.3  485.20  5650.0  485.09  5668.5  487.28  5703.8  489.53  5828.9  491.23
#Mann=3,-1,0
  4512.7    0.05       0  4994.8    0.03       0  5001.0    0.05       0
Bank Sta=4758,5090.4
Exp/Cntr=0.3,0.1

Type RM Length L Ch R = 1,3935,551,551,551
BEGIN DESCRIPTION:
UNT 024 in Running Cr Watershed 3.0
END DESCRIPTION:
XS GIS Cut Line= 4
      2915924.97      7062174.99      2915288.73      7061920.49
      2915058.37      7061891.16      2914572.48      7061958.48
#Sta/Elev= 30
  4200.8  496.71  4286.9  492.30  4377.1  482.78  4383.9  480.92  4406.7  478.64
  4460.6  473.96  4529.1  469.59  4646.4  467.73  4694.9  468.69  4783.7  467.99
  4963.1  470.21  4980.5  469.91  4997.6  463.20  4998.1  462.40  5003.3  462.40
  5003.8  463.20  5010.4  469.59  5011.3  470.09  5047.2  475.36  5052.2  474.92
  5101.5  479.29  5117.4  481.89  5141.9  480.68  5162.1  476.16  5165.9  476.13
  5212.8  476.07  5283.2  476.30  5303.4  478.84  5515.4  483.28  5608.8  486.86
#Mann=7,-1,0
  4200.8    0.05       0  4963.1    0.07       0  4997.6    0.07       0
  5003.8    0.07       0  5011.3    0.05       0  5165.9    0.07       0
  5212.8    0.05       0
Bank Sta=4529.1,5010.4
Exp/Cntr=0.3,0.1

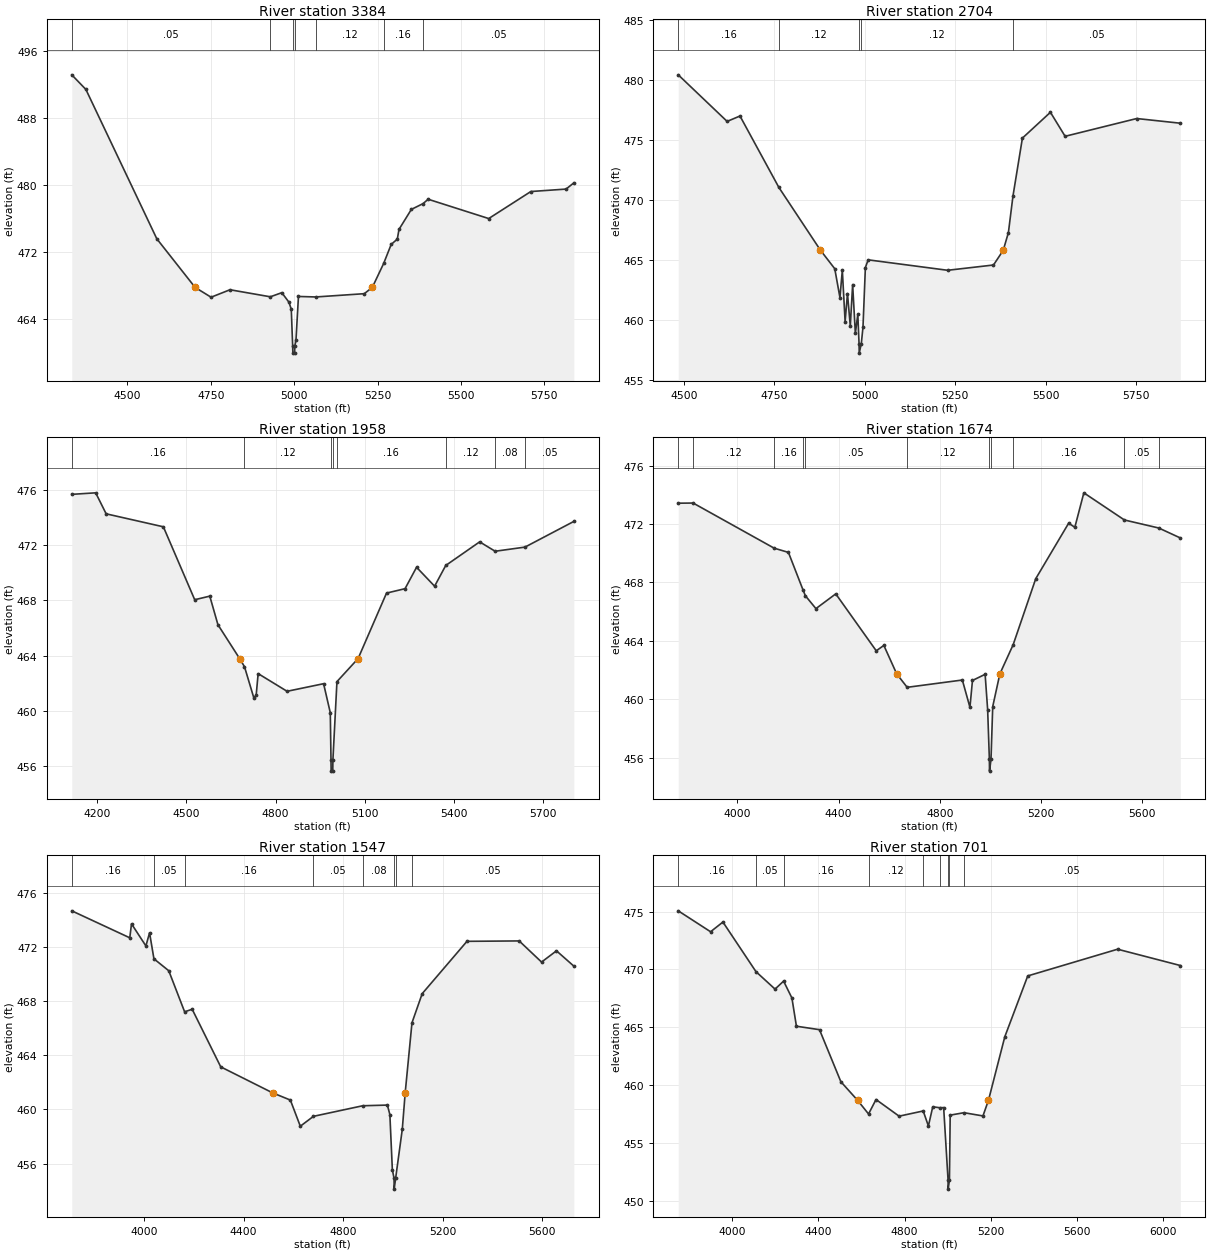
Type RM Length L Ch R = 1,3384,680,680,680
BEGIN DESCRIPTION:
UNT 024 in Running Cr Watershed 2.0
END DESCRIPTION:
XS GIS Cut Line= 3
      2915925.02      7062025.03      2915379.79      7061437.64
      2914681.82      7061526.19
#Sta/Elev= 30
  4333.2  493.13  4375.5  491.39  4588.1  473.60  4702.9  467.81  4750.8  466.64
  4807.5  467.53  4928.4  466.69  4962.8  467.18  4984.3  466.04  4991.2  465.20
  4995.4  460.78  4995.9  459.98  5001.2  459.98  5001.7  460.78  5005.3  461.56
  5012.7  466.73  5064.8  466.67  5210.0  467.06  5234.1  467.81  5268.1  470.66
  5290.7  472.93  5309.0  473.56  5314.1  474.72  5351.1  477.10  5386.2  477.79
  5401.5  478.31  5583.0  476.01  5709.3  479.23  5814.8  479.52  5838.2  480.26
#Mann=7,-1,0
  4333.2    0.05       0  4928.4    0.07       0  4995.4    0.07       0
  5001.7    0.07       0  5064.8    0.12       0  5268.1    0.16       0
  5386.2    0.05       0
Bank Sta=4702.9,5234.1
Exp/Cntr=0.3,0.1

Type RM Length L Ch R = 1,2704,746,746,746
BEGIN DESCRIPTION:
Mapping XS bf4a417e
END DESCRIPTION:
XS GIS Cut Line= 4
      2916260.02      7061651.21      2915973.54      7061354.31
      2915697.50      7061119.93      2915109.46      7060948.21
#Sta/Elev= 30
  4484.9  480.42  4620.0  476.54  4655.5  476.99  4763.0  471.04  4877.9  465.81
  4917.4  464.27  4931.7  461.87  4938.3  464.14  4946.0  459.87  4952.5  462.20
  4960.3  459.51  4966.8  462.95  4974.3  458.89  4981.1  460.47  4984.5  458.04
  4985.0  457.24  4990.8  458.04  4995.4  459.41  5002.0  464.37  5009.7  465.01
  5229.3  464.14  5356.0  464.58  5383.0  465.81  5397.2  467.28  5409.8  470.32
  5435.9  475.15  5513.3  477.30  5553.9  475.30  5751.8  476.78  5872.2  476.39
#Mann=5,-1,0
  4484.9    0.16       0  4763.0    0.12       0  4984.5    0.07       0
  4990.8    0.12       0  5409.8    0.05       0
Bank Sta=4877.9,5383
Exp/Cntr=0.3,0.1

Type RM Length L Ch R = 1,1958,284,284,284
BEGIN DESCRIPTION:
Mapping XS 538563ab
END DESCRIPTION:
XS GIS Cut Line= 4
      2916780.80      7061182.41      2916223.54      7060713.68
      2915947.50      7060578.27      2915301.62      7060672.02
#Sta/Elev= 30
  4114.4  475.68  4194.8  475.79  4230.0  474.27  4422.4  473.33  4527.8  468.05
  4578.5  468.31  4605.9  466.24  4678.8  463.79  4695.2  463.20  4726.8  460.93
  4734.6  461.16  4741.1  462.70  4838.4  461.42  4961.2  461.97  4983.7  459.87
  4986.1  456.44  4986.6  455.64  4992.0  455.64  4992.5  456.44  5006.1  462.12
  5077.2  463.79  5172.8  468.53  5235.1  468.85  5273.8  470.40  5334.5  469.03
  5371.9  470.53  5486.0  472.24  5538.0  471.56  5638.4  471.86  5802.7  473.72
#Mann=8,-1,0
  4114.4    0.16       0  4695.2    0.12       0  4986.1    0.07       0
  4992.5    0.12       0  5006.1    0.16       0  5371.9    0.12       0
  5538.0    0.08       0  5638.4    0.05       0
Bank Sta=4678.8,5077.2
Exp/Cntr=0.3,0.1

Type RM Length L Ch R = 1,1674,127,127,127
BEGIN DESCRIPTION:
Mapping XS 5e5594a4
END DESCRIPTION:
XS GIS Cut Line= 4
      2917244.34      7060854.27      2916926.66      7060416.81
      2915900.62      7060401.18      2915483.92      7060401.18
#Sta/Elev= 30
  3766.6  473.42  3825.5  473.43  4145.5  470.34  4201.9  470.05  4259.8  467.47
  4268.9  467.08  4310.6  466.20  4388.9  467.21  4548.9  463.31  4578.9  463.68
  4629.7  461.73  4671.0  460.81  4889.0  461.31  4919.0  459.44  4929.0  461.28
  4979.0  461.70  4989.0  459.27  4995.8  455.87  4996.3  455.07  5002.2  455.87
  5009.0  459.49  5037.2  461.73  5089.8  463.73  5179.0  468.25  5309.0  472.05
  5333.4  471.77  5369.0  474.13  5529.3  472.27  5665.1  471.72  5750.1  471.04
#Mann=11,-1,0
  3766.6    0.16       0  3825.5    0.12       0  4145.5    0.16       0
  4259.8    0.12       0  4268.9    0.05       0  4671.0    0.12       0
  4995.8    0.07       0  5002.2    0.12       0  5089.8    0.16       0
  5529.3    0.05       0  5665.1    0.08       0
Bank Sta=4629.7,5037.2
Exp/Cntr=0.3,0.1

Type RM Length L Ch R = 1,1547,846,846,846
BEGIN DESCRIPTION:
Mapping XS c50b63aa
END DESCRIPTION:
XS GIS Cut Line= 4
      2917317.28      7060718.89      2917004.79      7060291.81
      2915900.62      7060276.18      2915515.20      7060276.18
#Sta/Elev= 30
  3709.2  474.65  3942.5  472.66  3949.4  473.69  4007.3  472.06  4022.0  473.03
  4039.6  471.11  4099.2  470.23  4163.0  467.20  4193.4  467.39  4308.2  463.14
  4517.1  461.22  4588.2  460.69  4628.2  458.76  4681.0  459.49  4879.1  460.27
  4978.3  460.32  4988.3  459.62  4998.3  455.55  5005.1  454.92  5005.6  454.12
  5011.5  454.92  5038.3  458.54  5049.9  461.22  5077.2  466.39  5118.3  468.54
  5298.3  472.40  5508.3  472.43  5598.3  470.87  5658.3  471.70  5728.1  470.57
#Mann=8,-1,0
  3709.2    0.16       0  4039.6    0.05       0  4163.0    0.16       0
  4681.0    0.05       0  4879.1    0.08       0  5005.1    0.07       0
  5011.5    0.08       0  5077.2    0.05       0
Bank Sta=4517.1,5049.9
Exp/Cntr=0.3,0.1

Type RM Length L Ch R = 1,701,0,0,0
BEGIN DESCRIPTION:
UNT 024 in Running Cr Watershed 1.0
END DESCRIPTION:
XS GIS Cut Line= 4
      2917504.78      7060736.24      2916845.07      7059920.28
      2916497.84      7059868.20      2915603.71      7060119.94
#Sta/Elev= 30
  3750.0  475.06  3900.1  473.25  3957.3  474.09  4110.6  469.80  4199.1  468.29
  4238.8  468.98  4277.4  467.52  4298.3  465.08  4405.4  464.78  4504.5  460.28
  4581.7  458.68  4632.9  457.49  4667.6  458.74  4774.7  457.30  4886.5  457.75
  4910.6  456.45  4930.8  458.11  4963.5  458.03  4981.4  458.04  5001.8  451.79
  5002.3  450.99  5008.2  451.79  5011.7  457.39  5075.8  457.60  5163.7  457.32
  5189.4  458.68  5265.1  464.17  5371.5  469.43  5788.3  471.74  6079.3  470.33
#Mann=9,-1,0
  3750.0    0.16       0  4110.6    0.05       0  4238.8    0.16       0
  4632.9    0.12       0  4886.5    0.16       0  4963.5    0.12       0
  5001.8    0.07       0  5008.2    0.12       0  5075.8    0.05       0
Bank Sta=4581.7,5189.4
Exp/Cntr=0.3,0.1

Chan Stop Cuts=-1