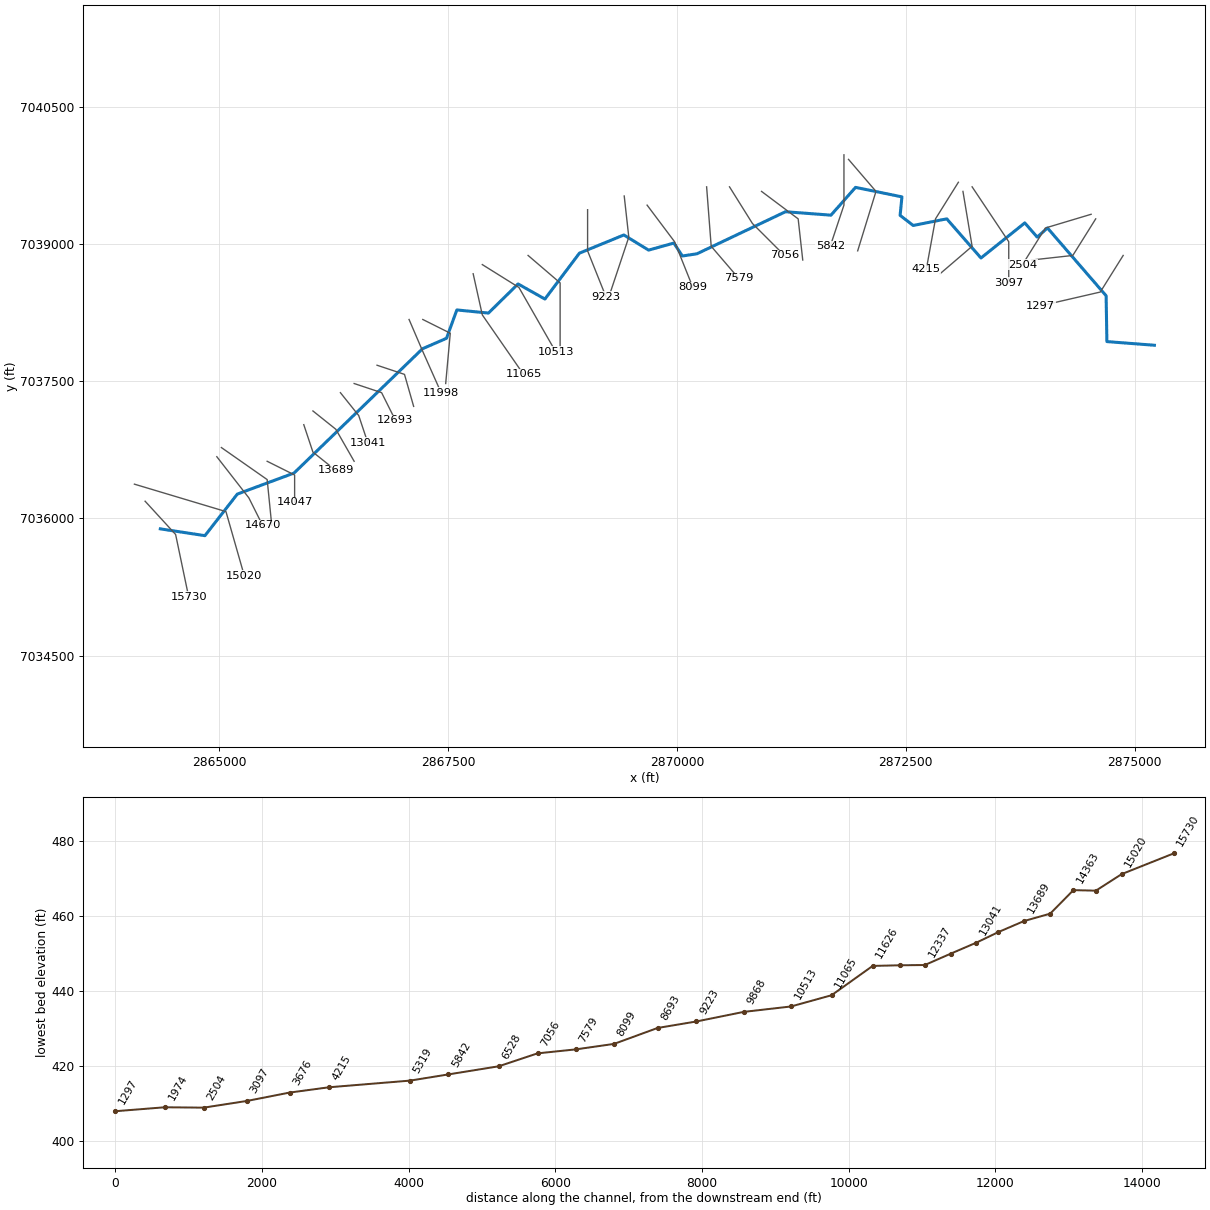
--- UNT 025 in Running Cr Watershed.prj (project) ---

Proj Title=UNT 025 in Running Cr Watershed Base Level Engineering
Current Plan=p01
Default Exp/Contr=0.3,0.1
English Units
Geom File=g01
Flow File=f01
Plan File=p01
BEGIN DESCRIPTION:
UNT 025 in Running Cr Watershed
END DESCRIPTION:

--- UNT 025 in Running Cr Watershed.p01 (plan) ---

Plan Title=Multiple Run
Short Identifier=Multiple
Geom File=g01
Flow File=f01
Subcritical Flow
K Sum by GR= 0
Std Step Tol= 0.01
Critical Tol= 0.01
Num of Std Step Trials= 20
Max Error Tol= 0.3
Flow Tol Ratio= 0.001
Split Flow NTrial= 30
Split Flow Tol= 0.02
Split Flow Ratio= 0.02
Log Output Level= 0
Friction Slope Method= 1
Unsteady Friction Slope Method= 2
Unsteady Bridges Friction Slope Method= 1
Parabolic Critical Depth
Global Vel Dist=  1 , 1 , 1
Global Log Level= 0
CheckData=True
Encroach Param= -1, 0, 0, 0
BEGIN DESCRIPTION:
Multiple Run
END DESCRIPTION:

--- UNT 025 in Running Cr Watershed.f01 (steady flow) ---

Flow Title=Multiple
Number of Profiles=7
Profile Names=10-year,25-year,50-year,1pct_min,100-year,1pct_plu,500-year
River Rch & RM= UNT 025 in Runni,Reach-1,15730
     141     171     194     110     219     438     279
River Rch & RM= UNT 025 in Runni,Reach-1,13689
     218     273     316     182     363     724     479
River Rch & RM= UNT 025 in Runni,Reach-1,12337
     294     377     441     257     514    1025     696
River Rch & RM= UNT 025 in Runni,Reach-1,11626
     421     552     656     388     775    1546    1081
River Rch & RM= UNT 025 in Runni,Reach-1,11065
     698     940    1138     684    1364    2722    1966
River Rch & RM= UNT 025 in Runni,Reach-1,5319
    1293    1795    2215    1355    2704    5395    4038
Boundary for River Rch & Prof#=UNT 025 in Runni,Reach-1,1
Up Type=0
Dn Type=3
Dn Slope=0.005
Boundary for River Rch & Prof#=UNT 025 in Runni,Reach-1,2
Up Type=0
Dn Type=3
Dn Slope=0.005
Boundary for River Rch & Prof#=UNT 025 in Runni,Reach-1,3
Up Type=0
Dn Type=3
Dn Slope=0.005
Boundary for River Rch & Prof#=UNT 025 in Runni,Reach-1,4
Up Type=0
Dn Type=3
Dn Slope=0.005
Boundary for River Rch & Prof#=UNT 025 in Runni,Reach-1,5
Up Type=0
Dn Type=3
Dn Slope=0.005
Boundary for River Rch & Prof#=UNT 025 in Runni,Reach-1,6
Up Type=0
Dn Type=3
Dn Slope=0.005
Boundary for River Rch & Prof#=UNT 025 in Runni,Reach-1,7
Up Type=0
Dn Type=3
Dn Slope=0.005

--- UNT 025 in Running Cr Watershed.g01 (geometry) ---

Geom Title=Existing Conditions

River Reach=UNT 025 in Runni,Reach-1
Reach XY= 30
      2864358.12      7035886.31      2864845.27      7035812.00
      2865199.44      7036266.86      2865818.25      7036496.06
      2867222.28      7037855.53      2867483.84      7037969.17
      2867596.61      7038279.29      2867941.90      7038245.13
      2868265.53      7038563.53      2868558.71      7038398.37
      2868935.40      7038899.68      2869421.22      7039098.81
      2869691.16      7038933.27      2869967.99      7039010.57
      2870059.44      7038868.93      2870219.56      7038893.17
      2871186.39      7039352.84      2871683.42      7039315.25
      2871951.50      7039619.07      2872458.34      7039515.47
      2872438.51      7039312.81      2872581.50      7039202.58
      2872948.24      7039275.17      2873321.52      7038847.03
      2873800.20      7039230.56      2873935.50      7039075.37
      2874048.24      7039175.32      2874688.69      7038434.26
      2874697.16      7037933.35      2875216.22      7037893.29

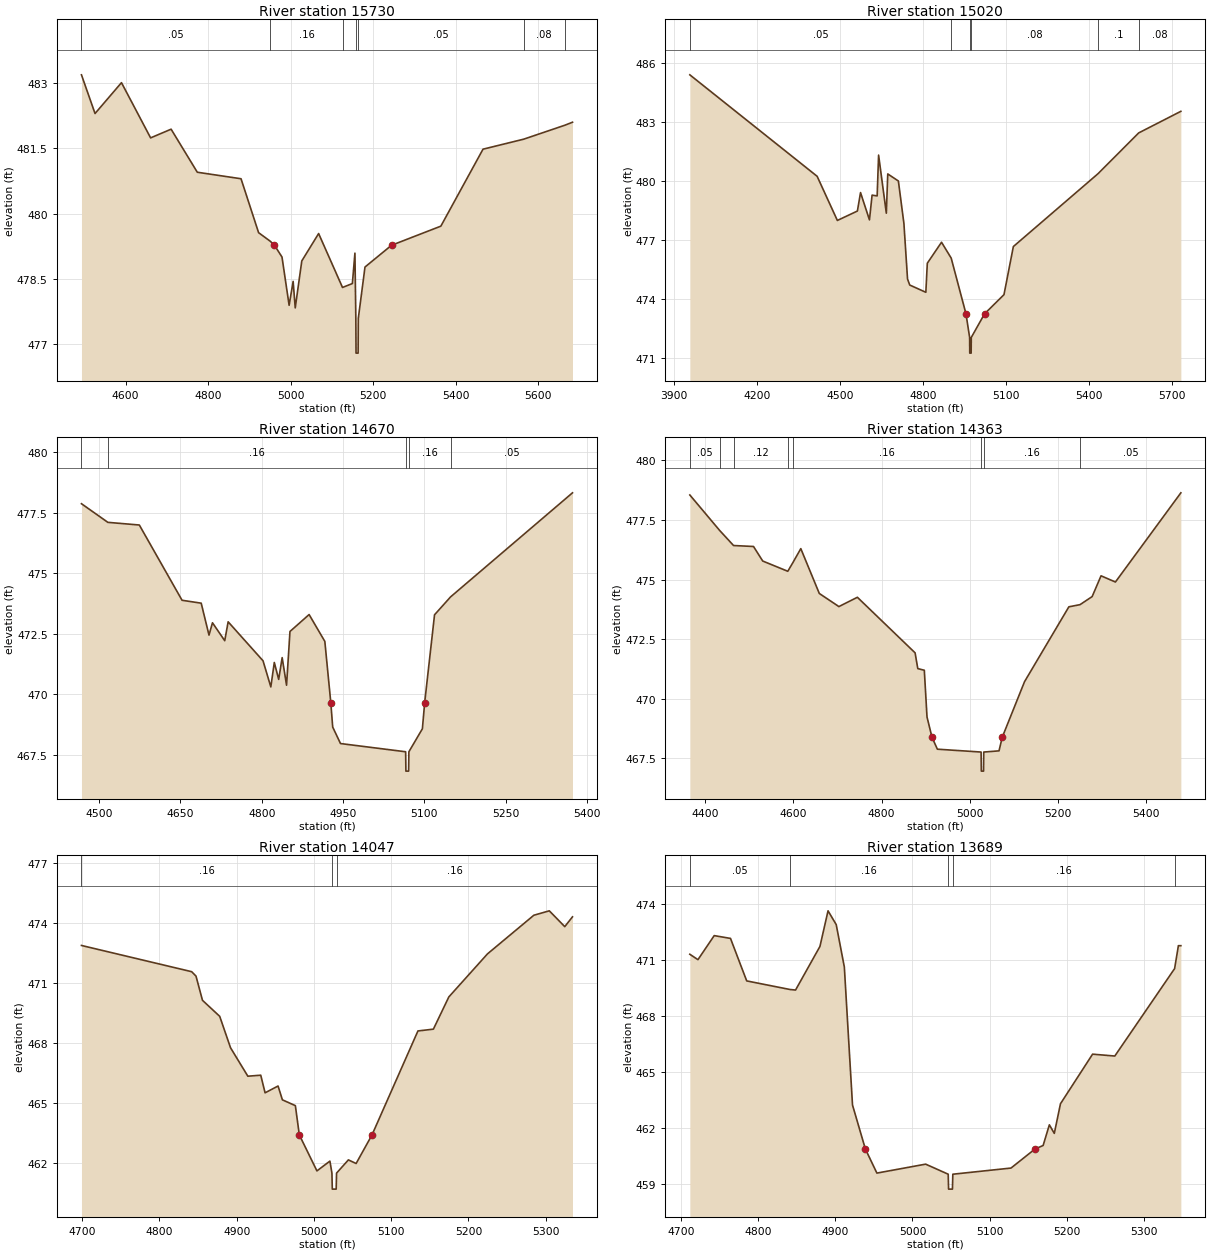
Type RM Length L Ch R = 1,15730,710,710,710
BEGIN DESCRIPTION:
UNT 025 in Running Cr Watershed 29.0
END DESCRIPTION:
XS GIS Cut Line= 3
      2864191.74      7036188.56      2864525.00      7035825.00
      2864667.75      7035142.67
#Sta/Elev= 30
  4493.2  483.19  4526.1  482.30  4590.2  483.01  4660.8  481.74  4710.5  481.94
  4774.0  480.95  4880.0  480.80  4922.6  479.56  4951.3  479.36  4961.1  479.27
  4979.3  479.00  4996.6  477.89  5006.3  478.44  5011.4  477.83  5027.3  478.91
  5068.1  479.54  5126.0  478.30  5149.9  478.39  5156.1  479.09  5158.3  477.59
  5158.8  476.79  5163.8  476.79  5164.3  477.59  5180.5  478.77  5244.8  479.27
  5364.4  479.71  5466.6  481.48  5565.2  481.71  5664.7  482.03  5683.5  482.10
#Mann=7,-1,0
  4493.2    0.05       0  4951.3    0.16       0  5126.0    0.05       0
  5158.3    0.07       0  5164.3    0.05       0  5565.2    0.08       0
  5664.7    0.05       0
Bank Sta=4961.1,5244.8
Exp/Cntr=0.3,0.1

Type RM Length L Ch R = 1,15020,350,350,350
BEGIN DESCRIPTION:
UNT 025 in Running Cr Watershed 28.0
END DESCRIPTION:
XS GIS Cut Line= 3
      2864075.01      7036375.00      2865075.00      7036075.00
      2865274.99      7035375.03
#Sta/Elev= 30
  3958.5  485.42  4417.9  480.25  4490.9  478.00  4563.2  478.48  4574.5  479.42
  4606.7  478.03  4616.2  479.29  4634.5  479.25  4639.7  481.33  4667.6  478.37
  4672.8  480.37  4711.1  480.01  4731.1  477.84  4744.1  475.02  4752.0  474.71
  4810.2  474.34  4815.5  475.82  4866.8  476.89  4901.7  476.08  4955.1  473.24
  4968.2  472.04  4968.7  471.24  4973.7  471.24  4974.2  472.04  5022.0  473.24
  5092.2  474.22  5126.0  476.67  5431.4  480.38  5578.3  482.46  5730.5  483.56
#Mann=6,-1,0
  3958.5    0.05       0  4901.7    0.08       0  4968.2    0.07       0
  4974.2    0.08       0  5431.4     0.1       0  5578.3    0.08       0
Bank Sta=4955.1,5022
Exp/Cntr=0.3,0.1

Type RM Length L Ch R = 1,14670,307,307,307
BEGIN DESCRIPTION:
UNT 025 in Running Cr Watershed 27.0
END DESCRIPTION:
XS GIS Cut Line= 3
      2864975.03      7036674.97      2865325.00      7036225.00
      2865475.02      7035924.96
#Sta/Elev= 30
  4467.6  477.88  4516.3  477.11  4574.3  477.00  4653.1  473.89  4688.4  473.77
  4702.8  472.45  4709.2  472.96  4731.8  472.22  4738.1  473.00  4802.4  471.39
  4816.8  470.31  4823.2  471.32  4831.3  470.62  4837.7  471.52  4845.8  470.38
  4852.1  472.60  4887.4  473.30  4916.4  472.19  4927.4  469.66  4930.9  468.65
  4945.3  467.97  5065.4  467.63  5065.9  466.83  5070.9  466.83  5071.4  467.63
  5096.3  468.58  5100.5  469.66  5118.7  473.29  5148.3  474.03  5373.1  478.33
#Mann=5,-1,0
  4467.6    0.05       0  4516.3    0.16       0  5065.4    0.07       0
  5071.4    0.16       0  5148.3    0.05       0
Bank Sta=4927.4,5100.5
Exp/Cntr=0.3,0.1

Type RM Length L Ch R = 1,14363,316,316,316
BEGIN DESCRIPTION:
UNT 025 in Running Cr Watershed 26.0
END DESCRIPTION:
XS GIS Cut Line= 3
      2865025.03      7036774.98      2865525.00      7036425.00
      2865575.00      7035924.98
#Sta/Elev= 30
  4365.5  478.55  4433.2  477.06  4464.6  476.43  4509.8  476.39  4530.7  475.78
  4587.5  475.35  4598.3  475.69  4617.0  476.30  4658.9  474.42  4703.3  473.87
  4745.2  474.26  4876.0  471.93  4882.1  471.27  4896.9  471.20  4903.0  469.24
  4914.3  468.39  4926.5  467.89  5025.6  467.77  5026.1  466.97  5031.1  466.97
  5031.6  467.77  5066.2  467.82  5073.5  468.39  5124.0  470.72  5224.5  473.86
  5249.7  473.95  5277.3  474.29  5297.4  475.16  5330.0  474.90  5478.3  478.64
#Mann=8,-1,0
  4365.5    0.05       0  4433.2    0.16       0  4464.6    0.12       0
  4587.5    0.07       0  4598.3    0.16       0  5025.6    0.07       0
  5031.6    0.16       0  5249.7    0.05       0
Bank Sta=4914.3,5073.5
Exp/Cntr=0.3,0.1

Type RM Length L Ch R = 1,14047,358,358,358
BEGIN DESCRIPTION:
UNT 025 in Running Cr Watershed 25.0
END DESCRIPTION:
XS GIS Cut Line= 3
      2865524.97      7036625.02      2865825.00      7036475.00
      2865825.00      7036175.05
#Sta/Elev= 30
  4699.2  472.86  4841.8  471.55  4847.4  471.33  4855.8  470.12  4878.1  469.32
  4892.1  467.75  4914.5  466.33  4931.2  466.38  4936.8  465.50  4953.6  465.84
  4959.2  465.15  4976.0  464.86  4981.1  463.40  5003.9  461.60  5020.7  462.09
  5023.3  461.49  5023.8  460.69  5028.8  460.69  5029.3  461.49  5044.6  462.15
  5054.6  461.97  5075.2  463.40  5134.6  468.59  5154.6  468.68  5174.6  470.29
  5224.6  472.44  5284.6  474.37  5304.6  474.59  5324.6  473.80  5334.6  474.29
#Mann=3,-1,0
  4699.2    0.16       0  5023.3    0.07       0  5029.3    0.16       0
Bank Sta=4981.1,5075.2
Exp/Cntr=0.3,0.1

Type RM Length L Ch R = 1,13689,348,348,348
BEGIN DESCRIPTION:
UNT 025 in Running Cr Watershed 24.0
END DESCRIPTION:
XS GIS Cut Line= 3
      2865925.01      7037024.96      2866025.00      7036725.00
      2866274.97      7036525.02
#Sta/Elev= 30
  4711.5  471.30  4722.0  471.01  4743.1  472.30  4764.2  472.15  4785.2  469.87
  4841.2  469.41  4848.5  469.38  4880.1  471.72  4890.6  473.63  4901.2  472.89
  4911.7  470.62  4922.3  463.21  4939.0  460.85  4953.9  459.56  5017.1  460.04
  5046.3  459.50  5046.8  458.70  5051.8  458.70  5052.3  459.50  5127.7  459.83
  5158.7  460.85  5169.3  461.04  5177.4  462.15  5183.8  461.69  5191.8  463.28
  5233.4  465.94  5262.2  465.84  5339.7  470.53  5344.6  471.76  5347.8  471.76
#Mann=5,-1,0
  4711.5    0.05       0  4841.2    0.16       0  5046.3    0.07       0
  5052.3    0.16       0  5339.7    0.05       0
Bank Sta=4939,5158.7
Exp/Cntr=0.3,0.1

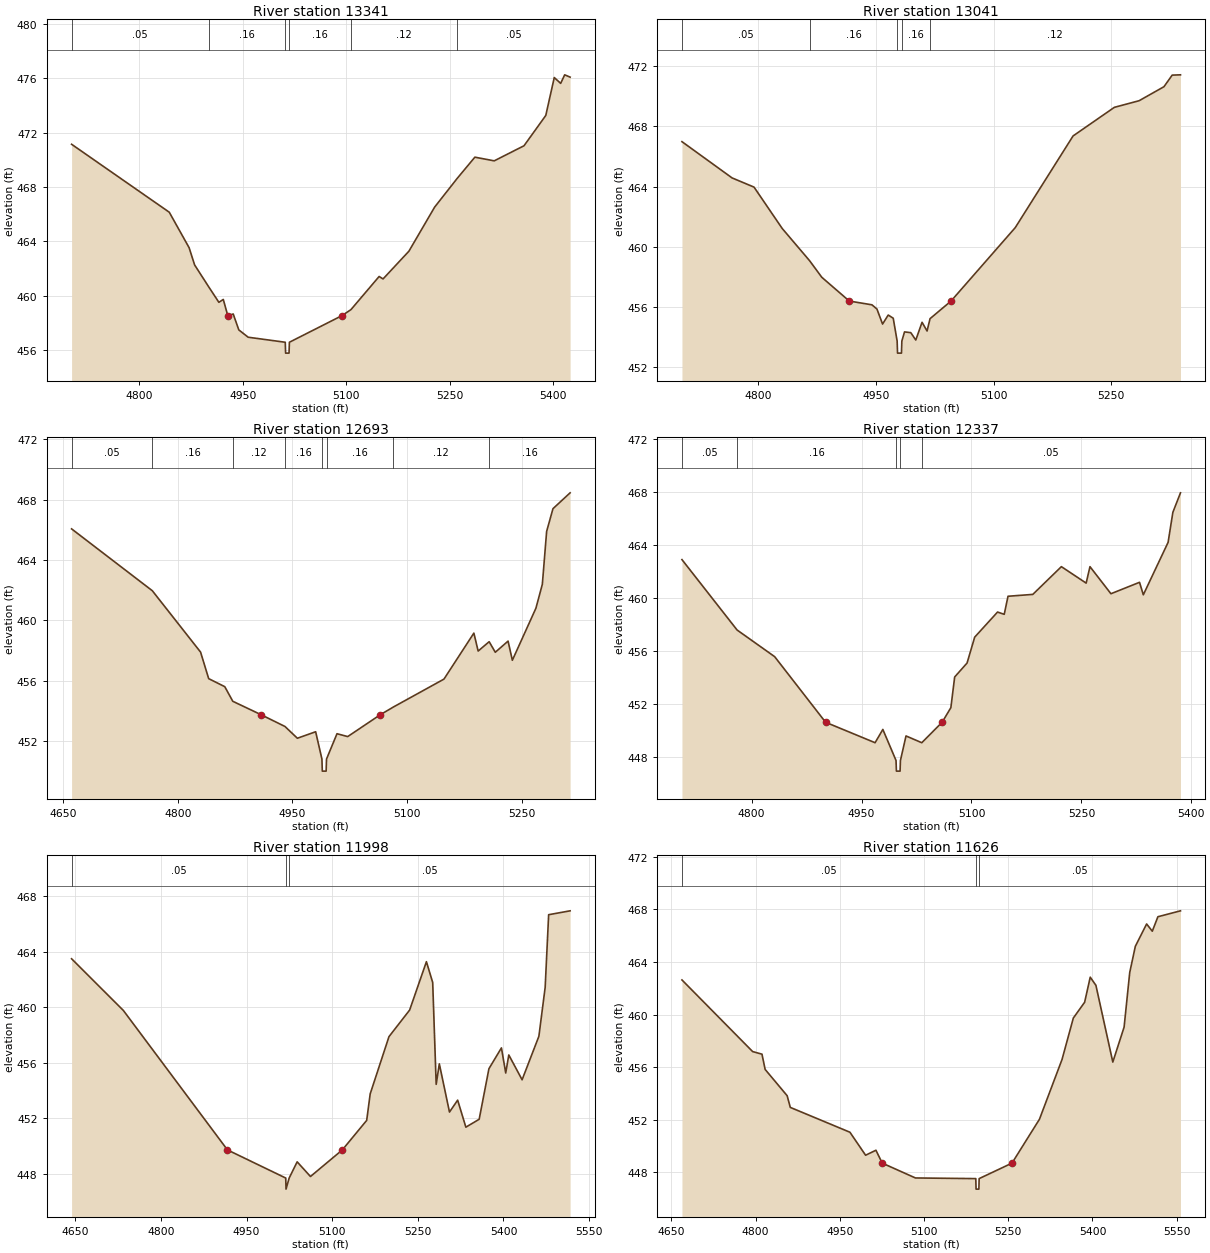
Type RM Length L Ch R = 1,13341,300,300,300
BEGIN DESCRIPTION:
UNT 025 in Running Cr Watershed 23.0
END DESCRIPTION:
XS GIS Cut Line= 3
      2866024.97      7037175.02      2866275.00      7036975.00
      2866475.00      7036625.00
#Sta/Elev= 30
  4701.5  471.14  4843.2  466.14  4872.0  463.53  4880.0  462.26  4900.8  460.62
  4915.2  459.51  4921.6  459.72  4928.1  458.53  4936.0  458.65  4944.1  457.48
  4957.7  456.94  5011.5  456.57  5012.0  455.77  5017.0  455.77  5017.5  456.57
  5093.8  458.53  5106.8  458.97  5147.7  461.41  5153.4  461.23  5190.9  463.27
  5228.3  466.52  5261.3  468.65  5286.6  470.19  5314.7  469.92  5357.9  471.03
  5389.5  473.26  5401.8  476.05  5411.1  475.62  5416.9  476.25  5424.8  476.08
#Mann=6,-1,0
  4701.5    0.05       0  4900.8    0.16       0  5011.5    0.07       0
  5017.5    0.16       0  5106.8    0.12       0  5261.3    0.05       0
Bank Sta=4928.1,5093.8
Exp/Cntr=0.3,0.1

Type RM Length L Ch R = 1,13041,348,348,348
BEGIN DESCRIPTION:
UNT 025 in Running Cr Watershed 22.0
END DESCRIPTION:
XS GIS Cut Line= 3
      2866325.02      7037374.98      2866525.00      7037125.00
      2866625.01      7036824.96
#Sta/Elev= 30
  4702.3  466.99  4766.3  464.58  4794.3  463.97  4830.3  461.22  4865.4  459.07
  4880.8  457.98  4915.9  456.40  4944.8  456.15  4951.2  455.87  4958.4  454.87
  4965.6  455.47  4972.0  455.26  4977.0  453.74  4977.5  452.94  4982.5  452.94
  4983.0  453.74  4986.4  454.35  4994.4  454.30  5000.8  453.81  5008.8  454.99
  5015.2  454.41  5019.0  455.23  5045.8  456.40  5127.8  461.28  5201.6  467.37
  5254.3  469.27  5285.9  469.71  5317.6  470.64  5328.1  471.41  5338.7  471.43
#Mann=5,-1,0
  4702.3    0.05       0  4865.4    0.16       0  4977.0    0.07       0
  4983.0    0.16       0  5019.0    0.12       0
Bank Sta=4915.9,5045.8
Exp/Cntr=0.3,0.1

Type RM Length L Ch R = 1,12693,356,356,356
BEGIN DESCRIPTION:
UNT 025 in Running Cr Watershed 21.0
END DESCRIPTION:
XS GIS Cut Line= 3
      2866475.03      7037474.99      2866775.00      7037375.00
      2866925.00      7037075.00
#Sta/Elev= 30
  4661.3  466.07  4766.8  461.97  4829.9  457.90  4840.5  456.14  4861.5  455.61
  4872.0  454.64  4909.4  453.74  4940.2  452.97  4956.4  452.19  4980.3  452.62
  4988.5  450.81  4989.0  450.01  4994.0  450.01  4994.5  450.81  5008.2  452.49
  5022.2  452.30  5064.5  453.74  5081.9  454.26  5148.0  456.11  5187.1  459.16
  5192.7  457.97  5207.1  458.59  5215.1  457.89  5231.8  458.63  5237.4  457.36
  5268.2  460.81  5276.6  462.40  5282.2  465.90  5290.5  467.41  5312.9  468.46
#Mann=8,-1,0
  4661.3    0.05       0  4766.8    0.16       0  4872.0    0.12       0
  4940.2    0.16       0  4988.5    0.07       0  4994.5    0.16       0
  5081.9    0.12       0  5207.1    0.16       0
Bank Sta=4909.4,5064.5
Exp/Cntr=0.3,0.1

Type RM Length L Ch R = 1,12337,339,339,339
BEGIN DESCRIPTION:
UNT 025 in Running Cr Watershed 20.0
END DESCRIPTION:
XS GIS Cut Line= 3
      2866725.01      7037675.00      2867025.00      7037575.00
      2867124.99      7037225.02
#Sta/Elev= 30
  4705.0  462.88  4780.2  457.58  4831.5  455.57  4901.0  450.63  4968.5  449.09
  4979.1  450.09  4997.1  447.75  4997.6  446.95  5002.6  446.95  5003.1  447.75
  5010.7  449.60  5032.2  449.09  5060.0  450.63  5071.9  451.73  5077.1  454.04
  5094.0  455.09  5104.4  457.04  5135.6  458.93  5144.7  458.76  5149.9  460.12
  5183.7  460.26  5222.7  462.35  5256.5  461.11  5261.7  462.35  5290.3  460.31
  5329.3  461.17  5334.5  460.23  5368.3  464.18  5374.8  466.44  5385.2  467.91
#Mann=5,-1,0
  4705.0    0.05       0  4780.2    0.16       0  4997.1    0.07       0
  5003.1    0.16       0  5032.2    0.05       0
Bank Sta=4901,5060
Exp/Cntr=0.3,0.1

Type RM Length L Ch R = 1,11998,372,372,372
BEGIN DESCRIPTION:
UNT 025 in Running Cr Watershed 19.0
END DESCRIPTION:
XS GIS Cut Line= 3
      2867075.00      7038174.99      2867225.00      7037825.00
      2867424.99      7037375.02
#Sta/Elev= 30
  4643.6  463.50  4734.3  459.77  4916.6  449.71  5018.7  447.68  5019.2  446.88
  5024.7  447.68  5038.7  448.85  5062.0  447.79  5117.8  449.71  5160.5  451.84
  5166.6  453.75  5199.5  457.88  5235.7  459.80  5265.1  463.29  5276.1  461.79
  5282.2  454.44  5287.7  455.92  5305.5  452.44  5319.8  453.30  5334.2  451.35
  5357.5  451.92  5374.6  455.57  5396.5  457.07  5404.0  455.26  5409.4  456.56
  5432.7  454.77  5462.1  457.91  5473.1  461.44  5479.2  466.68  5516.8  466.96
#Mann=3,-1,0
  4643.6    0.05       0  5018.7   0.035       0  5024.7    0.05       0
Bank Sta=4916.6,5117.8
Exp/Cntr=0.3,0.1

Type RM Length L Ch R = 1,11626,561,561,561
BEGIN DESCRIPTION:
UNT 025 in Running Cr Watershed 18.0
END DESCRIPTION:
XS GIS Cut Line= 3
      2867225.00      7038175.00      2867525.00      7038025.00
      2867475.00      7037474.97
#Sta/Elev= 30
  4669.0  462.63  4794.8  457.18  4811.5  456.98  4817.1  455.82  4856.3  453.82
  4861.9  452.93  4968.1  451.04  4996.0  449.29  5014.4  449.67  5025.6  448.69
  5084.7  447.56  5192.2  447.51  5192.7  446.71  5197.7  446.71  5198.2  447.51
  5256.7  448.69  5305.6  452.03  5345.8  456.58  5365.9  459.73  5386.0  460.93
  5396.0  462.84  5406.1  462.22  5436.2  456.38  5456.3  459.04  5466.3  463.19
  5476.3  465.19  5496.4  466.89  5506.5  466.34  5516.5  467.44  5556.7  467.89
#Mann=3,-1,0
  4669.0    0.05       0  5192.2    0.03       0  5198.2    0.05       0
Bank Sta=5025.6,5256.7
Exp/Cntr=0.3,0.1

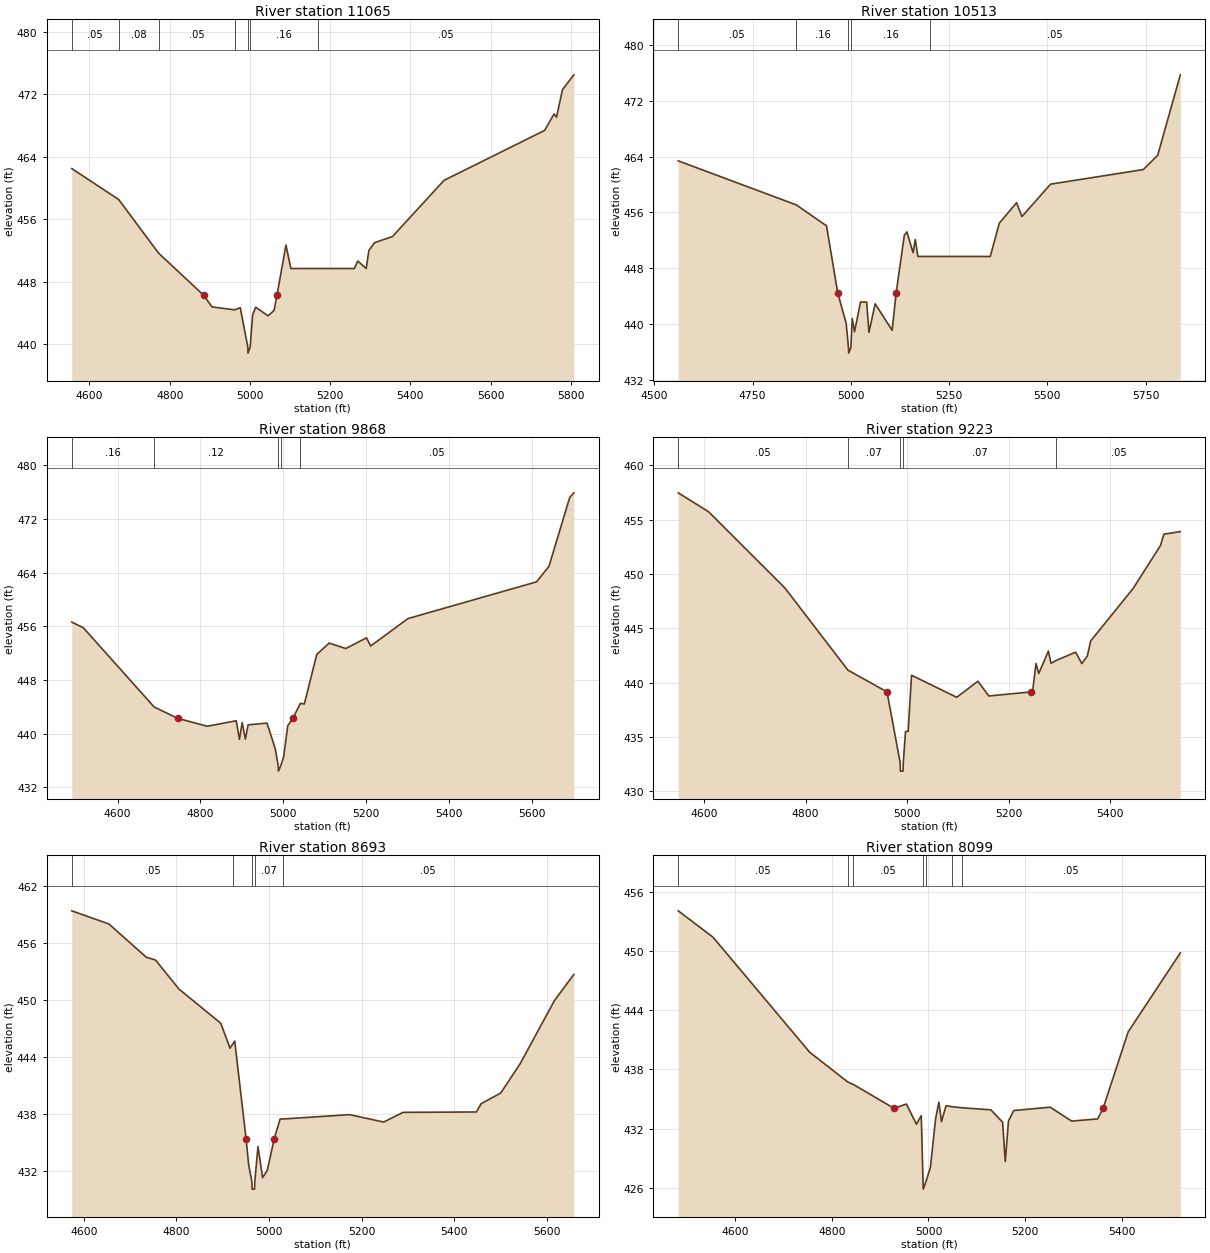
Type RM Length L Ch R = 1,11065,552,552,552
BEGIN DESCRIPTION:
UNT 025 in Running Cr Watershed 17.0
END DESCRIPTION:
XS GIS Cut Line= 3
      2867775.00      7038674.99      2867875.00      7038225.00
      2868324.98      7037575.03
#Sta/Elev= 30
  4555.9  462.50  4672.8  458.54  4772.5  451.66  4884.9  446.27  4905.5  444.79
  4961.8  444.41  4975.9  444.69  4994.7  439.67  4995.2  438.87  5000.7  439.67
  5006.6  443.74  5014.3  444.75  5045.2  443.64  5060.1  444.34  5067.4  446.27
  5089.8  452.70  5102.0  449.70  5170.2  449.70  5260.1  449.70  5268.9  450.66
  5289.8  449.71  5296.6  452.03  5310.8  453.01  5355.4  453.80  5483.8  460.99
  5734.5  467.38  5758.1  469.49  5764.2  469.07  5779.1  472.60  5807.4  474.50
#Mann=7,-1,0
  4555.9    0.05       0  4672.8    0.08       0  4772.5    0.05       0
  4961.8    0.16       0  4994.7    0.07       0  5000.7    0.16       0
  5170.2    0.05       0
Bank Sta=4884.9,5067.4
Exp/Cntr=0.3,0.1

Type RM Length L Ch R = 1,10513,645,645,645
BEGIN DESCRIPTION:
UNT 025 in Running Cr Watershed 16.0
END DESCRIPTION:
XS GIS Cut Line= 3
      2867874.99      7038775.01      2868275.00      7038525.00
      2868674.98      7037825.03
#Sta/Elev= 30
  4560.6  463.39  4861.3  457.08  4938.0  454.09  4966.4  444.54  4988.1  440.11
  4993.9  436.67  4994.4  435.87  5000.0  436.67  5003.4  440.83  5009.3  438.92
  5024.6  443.19  5040.2  443.17  5046.0  438.84  5061.8  442.93  5105.0  439.14
  5115.4  444.54  5136.0  452.73  5142.5  453.22  5158.3  450.25  5164.0  452.14
  5170.5  449.71  5201.3  449.71  5354.8  449.70  5377.8  454.47  5421.8  457.40
  5435.4  455.41  5508.1  460.05  5744.2  462.14  5781.0  464.19  5838.5  475.70
#Mann=5,-1,0
  4560.6    0.05       0  4861.3    0.16       0  4993.9    0.07       0
  5000.0    0.16       0  5201.3    0.05       0
Bank Sta=4966.4,5115.4
Exp/Cntr=0.3,0.1

Type RM Length L Ch R = 1,9868,645,645,645
BEGIN DESCRIPTION:
UNT 025 in Running Cr Watershed 15.0
END DESCRIPTION:
XS GIS Cut Line= 3
      2868375.04      7038874.97      2868725.00      7038575.00
      2868725.00      7037825.03
#Sta/Elev= 30
  4489.6  456.63  4517.5  455.79  4688.1  443.99  4744.6  442.30  4816.1  441.11
  4886.3  441.93  4894.0  439.16  4900.6  441.66  4908.3  439.20  4914.9  441.32
  4960.5  441.58  4980.5  437.73  4987.5  435.22  4988.0  434.42  4993.6  435.22
  5000.5  436.52  5010.5  441.19  5023.1  442.30  5040.8  444.51  5050.5  444.43
  5080.5  451.81  5110.5  453.50  5150.5  452.69  5200.5  454.29  5210.5  453.07
  5300.5  457.16  5610.5  462.63  5640.5  464.94  5690.5  475.20  5700.5  475.90
#Mann=5,-1,0
  4489.6    0.16       0  4688.1    0.12       0  4987.5    0.07       0
  4993.6    0.12       0  5040.8    0.05       0
Bank Sta=4744.6,5023.1
Exp/Cntr=0.3,0.1

Type RM Length L Ch R = 1,9223,530,530,530
BEGIN DESCRIPTION:
UNT 025 in Running Cr Watershed 14.0
END DESCRIPTION:
XS GIS Cut Line= 3
      2869025.00      7039374.98      2869025.00      7038925.00
      2869225.00      7038425.00
#Sta/Elev= 30
  4549.1  457.46  4609.1  455.71  4759.1  448.71  4883.2  441.15  4960.1  439.15
  4986.0  432.66  4986.5  431.86  4991.7  431.86  4992.2  432.66  4996.6  435.51
  5001.8  435.51  5008.5  440.68  5097.4  438.65  5139.1  440.13  5160.6  438.77
  5244.1  439.15  5246.8  439.22  5253.5  441.76  5258.9  440.84  5277.8  442.90
  5283.1  441.78  5293.6  442.05  5331.6  442.80  5343.7  441.75  5354.5  442.44
  5361.2  443.84  5444.7  448.66  5498.6  452.62  5505.3  453.66  5537.6  453.89
#Mann=5,-1,0
  4549.1    0.05       0  4883.2    0.07       0  4986.0    0.07       0
  4992.2    0.07       0  5293.6    0.05       0
Bank Sta=4960.1,5244.1
Exp/Cntr=0.3,0.1

Type RM Length L Ch R = 1,8693,594,594,594
BEGIN DESCRIPTION:
UNT 025 in Running Cr Watershed 13.0
END DESCRIPTION:
XS GIS Cut Line= 3
      2869425.00      7039525.02      2869475.00      7039075.00
      2869275.01      7038475.04
#Sta/Elev= 30
  4573.7  459.41  4654.2  458.02  4734.7  454.53  4754.8  454.23  4805.1  451.19
  4895.7  447.58  4915.8  444.95  4922.5  445.45  4925.9  445.71  4950.5  435.40
  4956.1  432.66  4963.0  430.92  4963.5  430.12  4968.8  430.12  4969.3  430.92
  4976.2  434.60  4986.2  431.33  4996.3  432.09  5011.2  435.40  5024.0  437.50
  5029.7  437.50  5174.1  437.96  5247.8  437.18  5290.0  438.20  5448.1  438.24
  5458.7  439.12  5500.8  440.23  5543.0  443.33  5616.8  449.95  5658.9  452.72
#Mann=5,-1,0
  4573.7    0.05       0  4922.5    0.07       0  4963.0    0.07       0
  4969.3    0.07       0  5029.7    0.05       0
Bank Sta=4950.5,5011.2
Exp/Cntr=0.3,0.1

Type RM Length L Ch R = 1,8099,520,520,520
BEGIN DESCRIPTION:
UNT 025 in Running Cr Watershed 12.0
END DESCRIPTION:
XS GIS Cut Line= 3
      2869674.98      7039425.02      2869975.00      7039025.00
      2870174.98      7038525.04
#Sta/Elev= 30
  4482.4  454.08  4554.3  451.41  4754.3  439.74  4833.2  436.72  4844.4  436.48
  4929.0  434.05  4954.3  434.49  4975.1  432.44  4985.1  433.31  4988.7  426.66
  4989.2  425.86  4995.0  426.66  5004.0  428.07  5014.7  432.98  5021.5  434.68
  5026.9  432.70  5036.3  434.32  5049.2  434.21  5069.6  434.11  5129.2  433.90
  5153.4  432.64  5158.8  428.66  5165.5  432.77  5176.3  433.83  5251.7  434.17
  5296.1  432.76  5350.0  432.98  5361.2  434.05  5413.2  441.82  5520.9  449.81
#Mann=7,-1,0
  4482.4    0.05       0  4833.2    0.07       0  4844.4    0.05       0
  4988.7    0.03       0  4995.0    0.05       0  5049.2    0.07       0
  5069.6    0.05       0
Bank Sta=4929,5361.2
Exp/Cntr=0.3,0.1

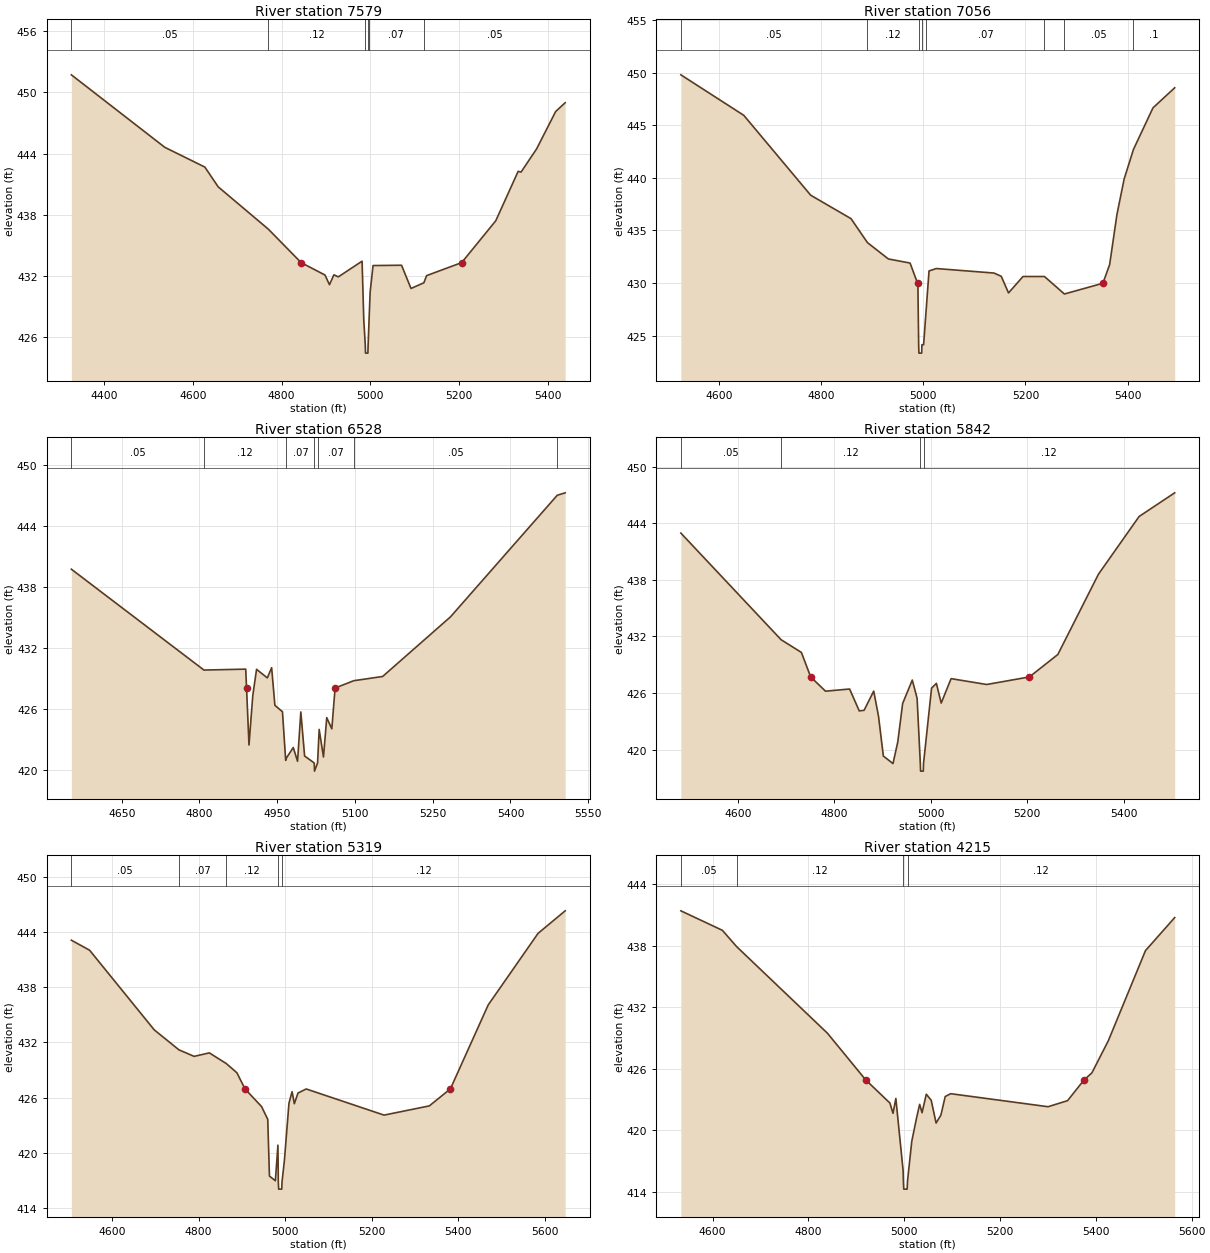
Type RM Length L Ch R = 1,7579,523,523,523
BEGIN DESCRIPTION:
UNT 025 in Running Cr Watershed 11.0
END DESCRIPTION:
XS GIS Cut Line= 3
      2870325.00      7039624.97      2870375.00      7038975.00
      2870675.02      7038624.97
#Sta/Elev= 30
  4326.2  451.73  4536.8  444.61  4627.1  442.67  4657.1  440.73  4770.0  436.58
  4844.0  433.29  4897.8  432.07  4907.9  431.12  4917.9  432.09  4927.9  431.89
  4981.4  433.43  4985.2  427.68  4988.6  425.20  4989.1  424.40  4994.5  424.40
  4995.0  425.20  4996.2  426.58  4999.5  430.36  5006.1  433.00  5070.3  433.03
  5091.7  430.75  5120.7  431.31  5126.8  432.01  5205.9  433.29  5282.7  437.40
  5333.1  442.25  5339.7  442.18  5374.9  444.47  5417.7  448.13  5439.1  448.99
#Mann=6,-1,0
  4326.2    0.05       0  4770.0    0.12       0  4988.6    0.07       0
  4995.0    0.12       0  4996.2    0.07       0  5120.7    0.05       0
Bank Sta=4844,5205.9
Exp/Cntr=0.3,0.1

Type RM Length L Ch R = 1,7056,528,528,528
BEGIN DESCRIPTION:
UNT 025 in Running Cr Watershed 10.0
END DESCRIPTION:
XS GIS Cut Line= 3
      2870575.01      7039624.98      2870825.00      7039225.00
      2871175.03      7038874.97
#Sta/Elev= 30
  4525.4  449.78  4648.6  445.93  4779.5  438.34  4858.5  436.11  4890.7  433.83
  4931.6  432.28  4974.1  431.89  4988.8  429.97  4989.4  429.85  4990.9  424.13
  4991.4  423.33  4996.8  423.33  4997.3  424.13  5000.6  424.13  5005.8  427.57
  5011.2  431.14  5025.4  431.37  5138.5  430.94  5152.6  430.63  5166.8  429.05
  5195.1  430.61  5237.2  430.61  5276.2  428.95  5351.6  429.97  5364.8  431.75
  5378.9  436.46  5393.1  439.87  5411.4  442.69  5449.6  446.64  5492.1  448.55
#Mann=8,-1,0
  4525.4    0.05       0  4890.7    0.12       0  4990.9    0.07       0
  4997.3    0.12       0  5005.8    0.07       0  5237.2    0.12       0
  5276.2    0.05       0  5411.4     0.1       0
Bank Sta=4988.8,5351.6
Exp/Cntr=0.3,0.1

Type RM Length L Ch R = 1,6528,686,686,686
BEGIN DESCRIPTION:
UNT 025 in Running Cr Watershed 9.0
END DESCRIPTION:
XS GIS Cut Line= 3
      2870925.03      7039574.98      2871325.00      7039275.00
      2871375.00      7038825.04
#Sta/Elev= 30
  4552.8  439.74  4808.6  429.82  4889.2  429.91  4890.8  428.05  4895.5  422.45
  4902.8  427.30  4910.1  429.89  4930.9  429.05  4939.2  430.05  4945.5  426.35
  4960.1  425.72  4966.3  420.94  4967.8  421.18  4980.9  422.20  4989.2  420.85
  4995.5  425.70  5002.8  421.37  5021.4  420.68  5021.9  419.88  5027.8  420.68
  5030.9  423.98  5039.2  421.27  5045.5  425.14  5055.3  424.04  5061.6  428.05
  5097.5  428.77  5153.4  429.19  5284.2  435.05  5490.2  447.01  5505.5  447.25
#Mann=7,-1,0
  4552.8    0.05       0  4808.6    0.12       0  4967.8    0.07       0
  5021.4    0.07       0  5027.8    0.07       0  5097.5    0.05       0
  5490.2     0.1       0
Bank Sta=4890.8,5061.6
Exp/Cntr=0.3,0.1

Type RM Length L Ch R = 1,5842,523,523,523
BEGIN DESCRIPTION:
UNT 025 in Running Cr Watershed 8.0
END DESCRIPTION:
XS GIS Cut Line= 3
      2871825.00      7039974.95      2871825.00      7039425.00
      2871675.00      7038974.99
#Sta/Elev= 30
  4481.8  442.96  4689.7  431.65  4731.8  430.30  4751.1  427.70  4781.8  426.19
  4831.8  426.42  4851.8  424.10  4861.8  424.16  4881.8  426.20  4891.8  423.52
  4901.8  419.31  4921.8  418.51  4931.8  420.83  4941.8  424.88  4961.8  427.37
  4971.8  425.44  4978.5  418.51  4979.0  417.71  4984.6  417.71  4985.1  418.51
  5001.8  426.51  5011.8  427.02  5021.8  424.93  5042.3  427.52  5116.1  426.90
  5204.7  427.70  5263.7  430.08  5348.0  438.60  5432.3  444.72  5506.1  447.23
#Mann=4,-1,0
  4481.8    0.05       0  4689.7    0.12       0  4978.5    0.07       0
  4985.1    0.12       0
Bank Sta=4751.1,5204.7
Exp/Cntr=0.3,0.1

Type RM Length L Ch R = 1,5319,1104,1104,1104
BEGIN DESCRIPTION:
UNT 025 in Running Cr Watershed 7.0
END DESCRIPTION:
XS GIS Cut Line= 3
      2871875.02      7039924.98      2872175.00      7039575.00
      2871975.01      7038925.03
#Sta/Elev= 30
  4505.8  443.09  4548.0  442.00  4697.3  433.35  4754.4  431.18  4789.5  430.47
  4824.6  430.85  4863.8  429.69  4888.3  428.69  4907.0  426.94  4945.4  425.01
  4959.6  423.63  4963.5  417.47  4977.2  416.96  4983.1  420.83  4984.0  416.85
  4984.8  416.05  4991.9  416.05  4992.6  416.85  4998.1  419.19  5008.6  425.39
  5015.8  426.63  5021.0  425.33  5029.5  426.49  5048.5  426.93  5228.3  424.09
  5332.9  425.09  5381.6  426.94  5469.0  436.06  5584.1  443.83  5646.8  446.28
#Mann=5,-1,0
  4505.8    0.05       0  4754.4    0.07       0  4863.8    0.12       0
  4984.0    0.07       0  4992.6    0.12       0
Bank Sta=4907,5381.6
Exp/Cntr=0.3,0.1

Type RM Length L Ch R = 1,4215,539,539,539
BEGIN DESCRIPTION:
UNT 025 in Running Cr Watershed 6.0
END DESCRIPTION:
XS GIS Cut Line= 3
      2873074.99      7039674.99      2872825.00      7039275.00
      2872725.00      7038725.00
#Sta/Elev= 30
  4533.9  441.39  4620.6  439.49  4650.1  437.91  4839.9  429.46  4919.8  424.91
  4970.2  422.66  4976.7  421.66  4982.6  423.11  4997.9  416.02  4998.3  415.07
  4999.1  414.27  5006.2  414.27  5007.0  415.07  5015.8  418.92  5025.9  421.22
  5032.3  422.53  5037.3  421.72  5046.2  423.52  5056.4  422.93  5066.6  420.71
  5076.7  421.49  5085.6  423.29  5097.1  423.57  5300.3  422.30  5341.0  422.89
  5375.4  424.91  5391.8  425.60  5426.1  428.73  5503.6  437.51  5564.6  440.73
#Mann=4,-1,0
  4533.9    0.05       0  4650.1    0.12       0  4998.3    0.07       0
  5007.0    0.12       0
Bank Sta=4919.8,5375.4
Exp/Cntr=0.3,0.1

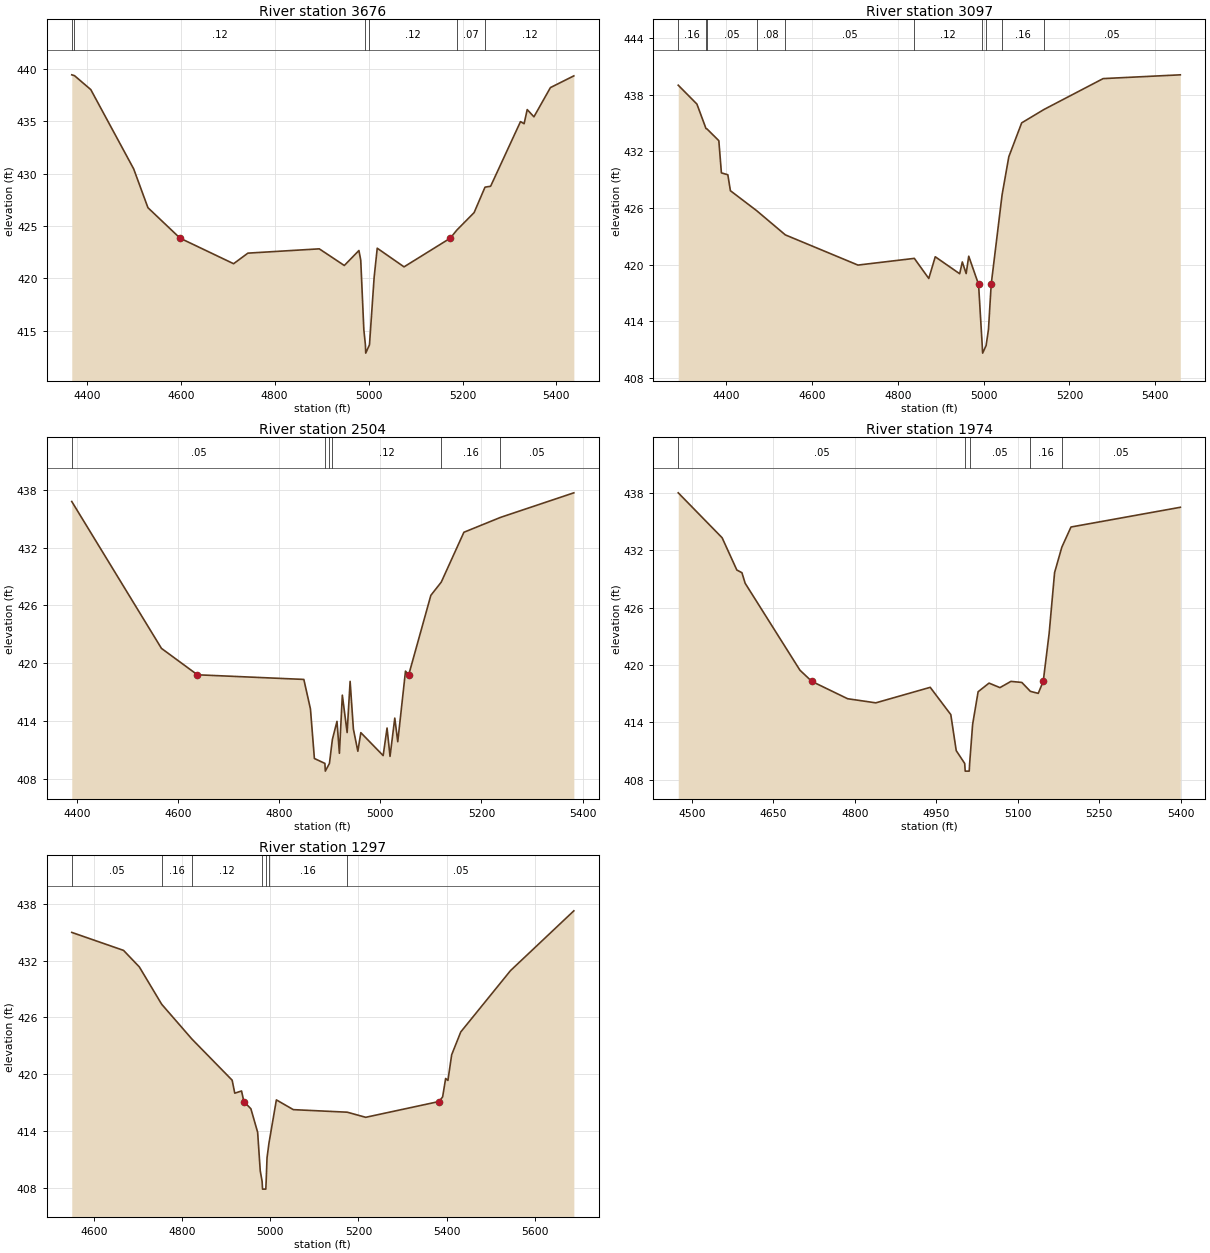
Type RM Length L Ch R = 1,3676,579,579,579
BEGIN DESCRIPTION:
UNT 025 in Running Cr Watershed 5.0
END DESCRIPTION:
XS GIS Cut Line= 3
      2873125.01      7039574.96      2873225.00      7038975.00
      2872875.01      7038675.01
#Sta/Elev= 30
  4367.9  439.43  4373.7  439.35  4408.4  438.02  4499.7  430.45  4530.1  426.74
  4598.5  423.83  4712.5  421.39  4743.0  422.40  4895.0  422.81  4948.3  421.22
  4979.4  422.65  4983.3  421.73  4989.9  415.08  4993.2  413.65  4993.9  412.85
  5001.9  413.65  5011.8  420.08  5018.4  422.87  5075.5  421.09  5174.0  423.83
  5187.9  424.60  5224.7  426.27  5247.9  428.70  5259.9  428.79  5323.5  434.96
  5331.2  434.76  5337.8  436.11  5352.1  435.42  5387.2  438.21  5437.1  439.33
#Mann=6,-1,0
  4367.9    0.05       0  4373.7    0.12       0  4993.2    0.07       0
  5001.9    0.12       0  5187.9    0.07       0  5247.9    0.12       0
Bank Sta=4598.5,5174
Exp/Cntr=0.3,0.1

Type RM Length L Ch R = 1,3097,593,593,593
BEGIN DESCRIPTION:
UNT 025 in Running Cr Watershed 4.0
END DESCRIPTION:
XS GIS Cut Line= 3
      2873224.98      7039625.03      2873625.00      7039025.00
      2873625.00      7038575.05
#Sta/Elev= 30
  4287.6  439.01  4331.2  437.01  4352.4  434.41  4354.6  434.38  4382.3  433.13
  4388.3  429.72  4403.3  429.52  4409.3  427.83  4470.4  425.72  4537.4  423.15
  4706.8  419.95  4838.3  420.66  4872.0  418.53  4887.1  420.83  4944.1  419.03
  4950.2  420.28  4959.2  419.05  4965.2  420.89  4988.1  417.91  4996.7  411.42
  4997.6  410.62  5005.7  411.42  5011.2  413.12  5017.6  417.91  5043.0  427.40
  5058.7  431.43  5088.7  435.02  5140.8  436.44  5278.7  439.71  5458.7  440.11
#Mann=10,-1,0
  4287.6    0.16       0  4352.4    0.08       0  4354.6    0.05       0
  4470.4    0.08       0  4537.4    0.05       0  4838.3    0.12       0
  4996.7    0.07       0  5005.7    0.12       0  5043.0    0.16       0
  5140.8    0.05       0
Bank Sta=4988.1,5017.6
Exp/Cntr=0.3,0.1

Type RM Length L Ch R = 1,2504,530,530,530
BEGIN DESCRIPTION:
UNT 025 in Running Cr Watershed 3.0
END DESCRIPTION:
XS GIS Cut Line= 3
      2874524.97      7039324.99      2874025.00      7039175.00
      2873774.99      7038774.99
#Sta/Elev= 30
  4389.1  436.78  4566.6  421.55  4637.8  418.81  4848.4  418.33  4861.5  415.27
  4869.3  410.13  4890.1  409.62  4890.9  408.82  4899.1  409.62  4904.9  412.11
  4914.0  413.98  4918.8  410.67  4924.6  416.70  4934.1  412.82  4940.0  418.13
  4946.5  413.18  4955.3  410.88  4961.2  412.81  5005.4  410.43  5013.1  413.29
  5019.0  410.35  5028.4  414.32  5034.3  411.87  5049.6  419.19  5056.0  418.81
  5099.8  427.05  5120.4  428.42  5165.2  433.59  5237.5  435.13  5382.8  437.68
#Mann=6,-1,0
  4389.1    0.05       0  4890.1    0.07       0  4899.1    0.05       0
  4904.9    0.12       0  5120.4    0.16       0  5237.5    0.05       0
Bank Sta=4637.8,5056
Exp/Cntr=0.3,0.1

Type RM Length L Ch R = 1,1974,677,677,677
BEGIN DESCRIPTION:
UNT 025 in Running Cr Watershed 2.0
END DESCRIPTION:
XS GIS Cut Line= 3
      2874575.00      7039274.99      2874325.00      7038875.00
      2873874.96      7038825.00
#Sta/Elev= 30
  4474.7  437.98  4555.5  433.29  4582.6  429.92  4592.0  429.64  4597.9  428.54
  4698.8  419.46  4720.7  418.29  4786.6  416.48  4838.5  416.05  4938.7  417.67
  4976.6  414.82  4986.6  411.06  5002.2  409.72  5003.1  408.92  5010.5  408.92
  5011.3  409.72  5016.8  413.81  5026.9  417.21  5047.0  418.11  5067.1  417.64
  5087.3  418.29  5107.4  418.18  5123.1  417.25  5137.6  417.04  5146.8  418.29
  5157.7  423.31  5167.7  429.65  5181.0  432.30  5197.9  434.41  5399.2  436.47
#Mann=5,-1,0
  4474.7    0.05       0  5002.2    0.03       0  5011.3    0.05       0
  5123.1    0.16       0  5181.0    0.05       0
Bank Sta=4720.7,5146.8
Exp/Cntr=0.3,0.1

Type RM Length L Ch R = 1,1297,0,0,0
BEGIN DESCRIPTION:
UNT 025 in Running Cr Watershed 1.0
END DESCRIPTION:
XS GIS Cut Line= 3
      2874875.02      7038875.04      2874625.00      7038475.00
      2873975.02      7038325.01
#Sta/Elev= 30
  4549.9  434.99  4667.3  433.09  4703.2  431.34  4753.8  427.40  4822.4  423.72
  4913.7  419.37  4919.6  418.00  4935.0  418.23  4940.2  417.12  4956.2  416.35
  4971.5  413.87  4977.4  409.80  4981.7  408.66  4982.6  407.86  4990.0  407.86
  4990.8  408.66  4992.8  411.17  4997.1  412.70  5014.0  417.29  5052.4  416.26
  5174.7  415.99  5216.6  415.45  5383.0  417.12  5391.1  417.61  5397.9  419.55
  5403.1  419.35  5411.6  422.06  5432.2  424.47  5545.0  430.95  5688.7  437.27
#Mann=7,-1,0
  4549.9    0.05       0  4753.8    0.16       0  4822.4    0.12       0
  4981.7    0.07       0  4990.8    0.12       0  4997.1    0.16       0
  5174.7    0.05       0
Bank Sta=4940.2,5383
Exp/Cntr=0.3,0.1

Chan Stop Cuts=-1