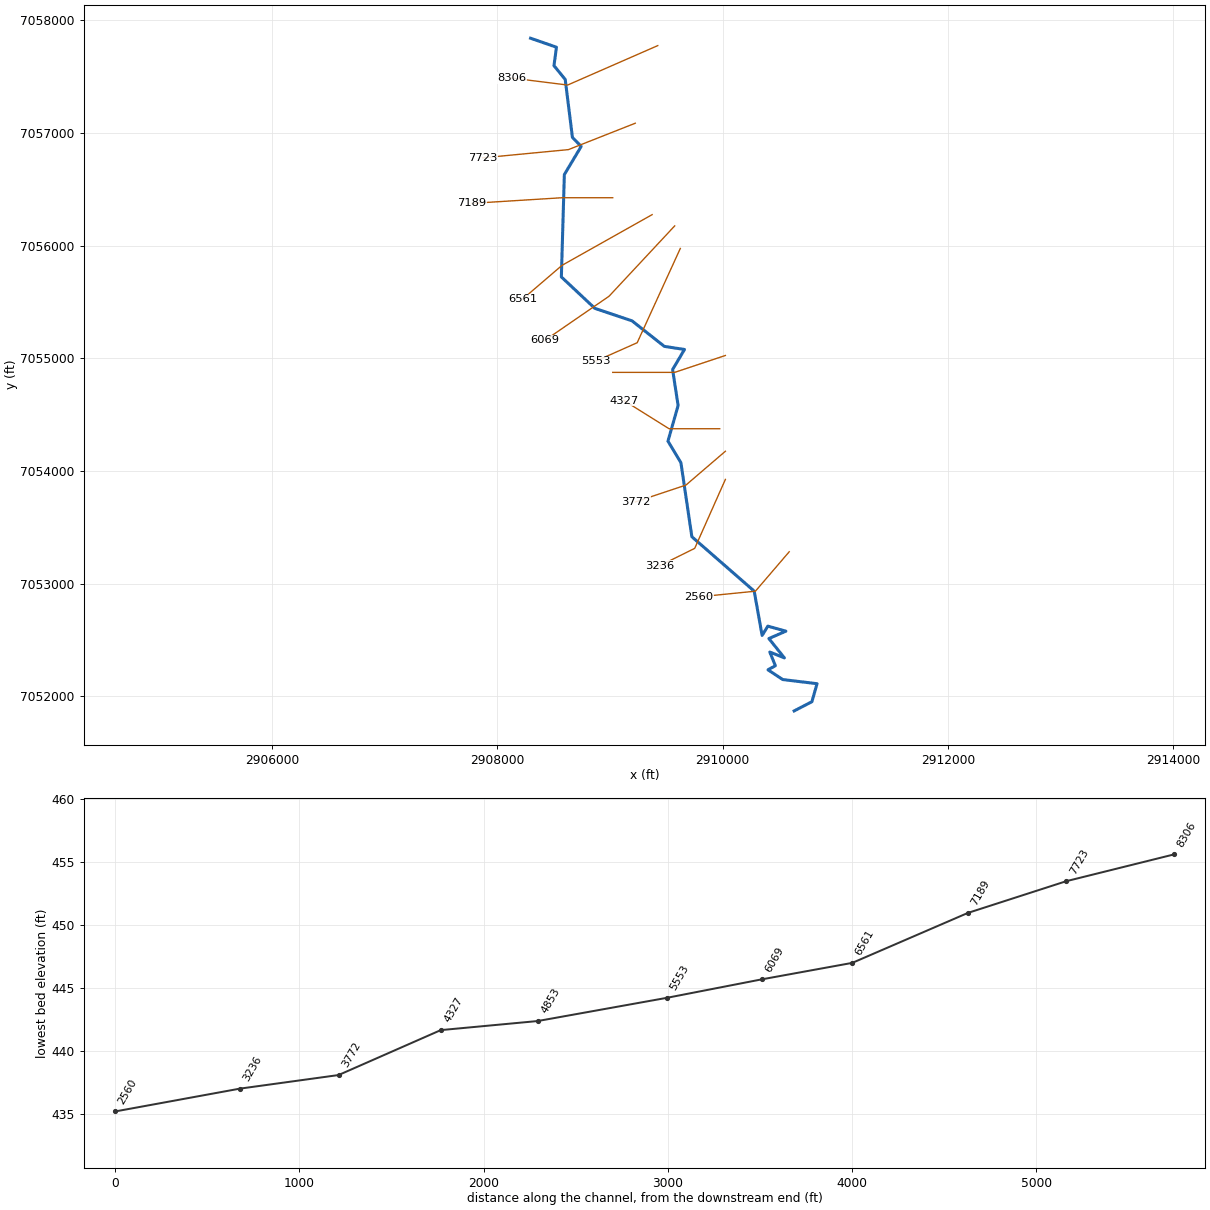
--- UNT 026 in Running Cr Watershed.prj (project) ---

Proj Title=UNT 026 in Running Cr Watershed Base Level Engineering
Current Plan=p01
Default Exp/Contr=0.3,0.1
English Units
Geom File=g01
Flow File=f01
Plan File=p01
BEGIN DESCRIPTION:
UNT 026 in Running Cr Watershed
END DESCRIPTION:

--- UNT 026 in Running Cr Watershed.p01 (plan) ---

Plan Title=Multiple Run
Short Identifier=Multiple
Geom File=g01
Flow File=f01
Subcritical Flow
K Sum by GR= 0
Std Step Tol= 0.01
Critical Tol= 0.01
Num of Std Step Trials= 20
Max Error Tol= 0.3
Flow Tol Ratio= 0.001
Split Flow NTrial= 30
Split Flow Tol= 0.02
Split Flow Ratio= 0.02
Log Output Level= 0
Friction Slope Method= 1
Unsteady Friction Slope Method= 2
Unsteady Bridges Friction Slope Method= 1
Parabolic Critical Depth
Global Vel Dist=  1 , 1 , 1
Global Log Level= 0
CheckData=True
Encroach Param= -1, 0, 0, 0
BEGIN DESCRIPTION:
Multiple Run
END DESCRIPTION:

--- UNT 026 in Running Cr Watershed.f01 (steady flow) ---

Flow Title=Multiple
Number of Profiles=7
Profile Names=10-year,25-year,50-year,1pct_min,100-year,1pct_plu,500-year
River Rch & RM= UNT 026 in Runni,Reach-1,8306
     911    1240    1510     912    1820    3631    2644
Boundary for River Rch & Prof#=UNT 026 in Runni,Reach-1,1
Up Type=0
Dn Type=3
Dn Slope=0.005
Boundary for River Rch & Prof#=UNT 026 in Runni,Reach-1,2
Up Type=0
Dn Type=3
Dn Slope=0.005
Boundary for River Rch & Prof#=UNT 026 in Runni,Reach-1,3
Up Type=0
Dn Type=3
Dn Slope=0.005
Boundary for River Rch & Prof#=UNT 026 in Runni,Reach-1,4
Up Type=0
Dn Type=3
Dn Slope=0.005
Boundary for River Rch & Prof#=UNT 026 in Runni,Reach-1,5
Up Type=0
Dn Type=3
Dn Slope=0.005
Boundary for River Rch & Prof#=UNT 026 in Runni,Reach-1,6
Up Type=0
Dn Type=3
Dn Slope=0.005
Boundary for River Rch & Prof#=UNT 026 in Runni,Reach-1,7
Up Type=0
Dn Type=3
Dn Slope=0.005

--- UNT 026 in Running Cr Watershed.g01 (geometry) ---

Geom Title=Existing Conditions

River Reach=UNT 026 in Runni,Reach-1
Reach XY= 30
      2908295.73      7057840.54      2908525.59      7057760.71
      2908503.48      7057597.18      2908603.20      7057474.99
      2908667.34      7056959.99      2908745.00      7056880.40
      2908595.59      7056630.71      2908569.08      7055722.06
      2908866.54      7055443.01      2909196.29      7055332.48
      2909483.02      7055105.82      2909661.97      7055078.31
      2909556.61      7054900.24      2909605.47      7054580.76
      2909515.31      7054264.58      2909630.22      7054073.95
      2909727.53      7053416.41      2910280.86      7052933.59
      2910351.04      7052540.57      2910401.84      7052622.90
      2910561.96      7052578.49      2910411.19      7052512.91
      2910548.77      7052341.22      2910419.22      7052393.19
      2910468.79      7052271.74      2910403.00      7052235.46
      2910534.20      7052149.18      2910838.76      7052112.16
      2910792.93      7051952.37      2910635.59      7051870.71

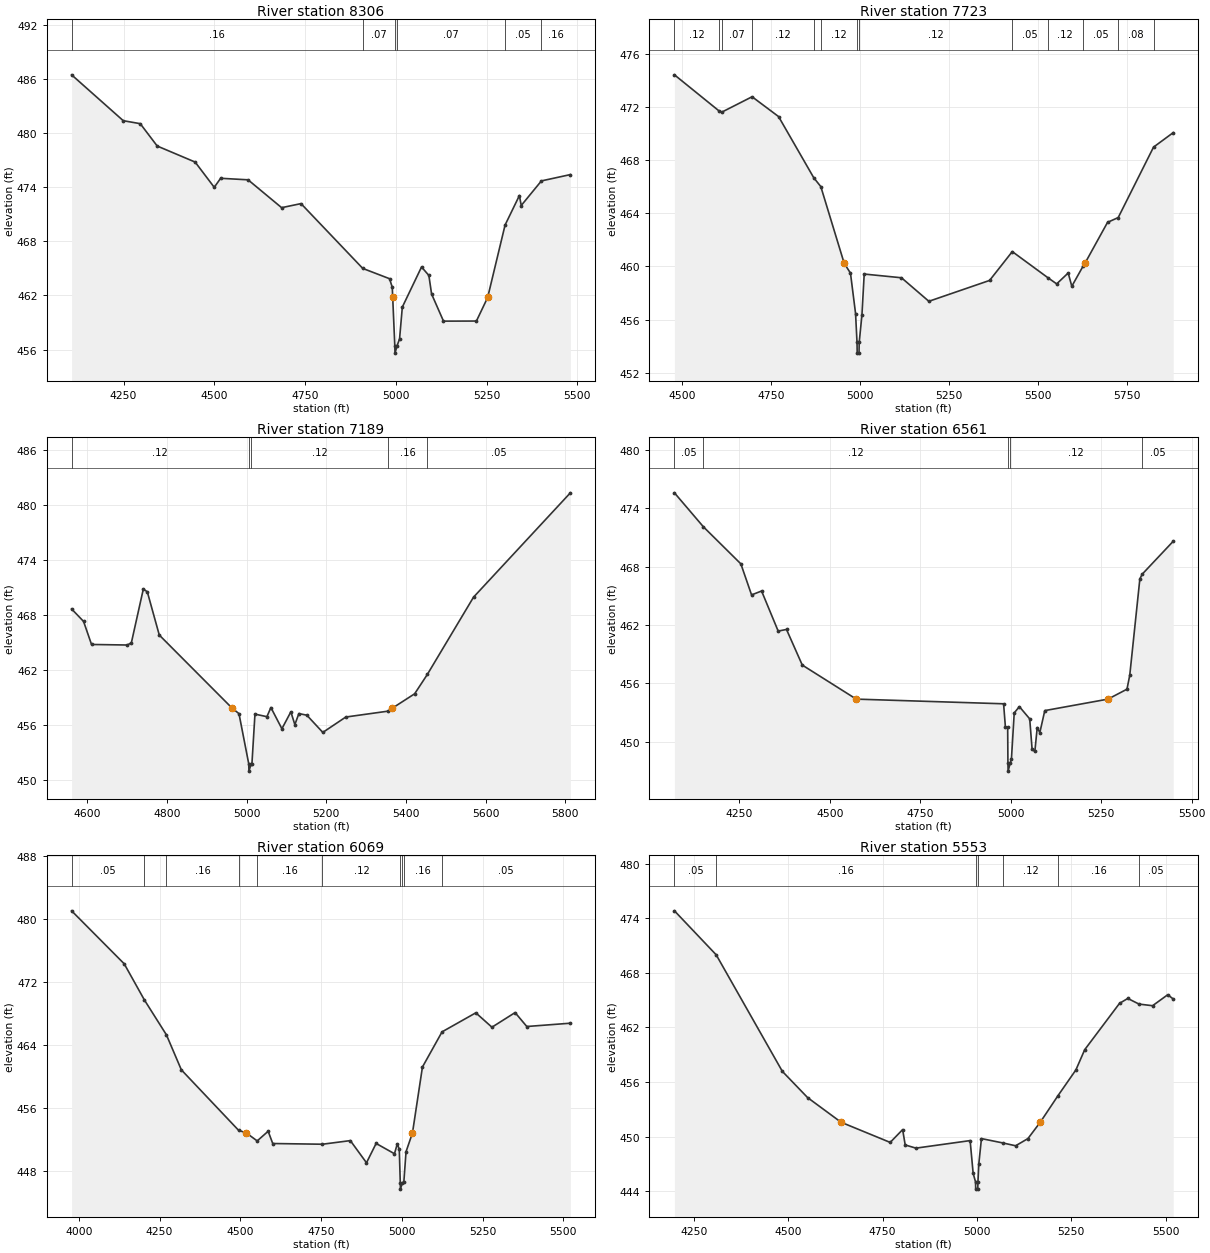
Type RM Length L Ch R = 1,8306,583,583,583
BEGIN DESCRIPTION:
UNT 026 in Running Cr Watershed 11.0
END DESCRIPTION:
XS GIS Cut Line= 3
      2909425.00      7057775.00      2908625.00      7057425.00
      2908128.18      7057487.10
#Sta/Elev= 30
  4106.9  486.48  4249.2  481.39  4296.0  481.06  4342.7  478.58  4447.2  476.80
  4499.8  474.00  4517.4  475.00  4593.0  474.83  4685.4  471.74  4738.8  472.19
  4908.9  465.00  4982.6  463.86  4990.2  462.91  4991.4  461.78  4997.2  456.40
  4997.7  455.60  5003.3  456.40  5010.3  457.19  5017.9  460.71  5070.8  465.16
  5091.0  464.22  5098.5  462.16  5131.3  459.15  5222.0  459.16  5253.0  461.78
  5300.9  469.81  5340.4  473.09  5345.4  471.98  5401.0  474.71  5480.8  475.41
#Mann=6,-1,0
  4106.9    0.16       0  4908.9    0.07       0  4997.2    0.07       0
  5003.3    0.07       0  5300.9    0.05       0  5401.0    0.16       0
Bank Sta=4991.4,5253
Exp/Cntr=0.3,0.1

Type RM Length L Ch R = 1,7723,534,534,534
BEGIN DESCRIPTION:
UNT 026 in Running Cr Watershed 10.0
END DESCRIPTION:
XS GIS Cut Line= 3
      2909225.33      7057086.26      2908631.60      7056851.90
      2907871.20      7056778.98
#Sta/Elev= 30
  4478.0  474.42  4603.1  471.71  4611.7  471.62  4696.3  472.77  4770.7  471.28
  4869.8  466.67  4889.5  466.01  4955.2  460.24  4972.9  459.50  4987.2  456.46
  4991.3  454.28  4991.8  453.48  4996.9  453.48  4997.4  454.28  5005.1  456.34
  5011.5  459.43  5116.3  459.15  5193.3  457.38  5364.0  458.95  5427.8  461.12
  5527.1  459.17  5552.6  458.69  5585.0  459.51  5595.1  458.51  5626.3  460.00
  5632.1  460.24  5695.6  463.32  5725.6  463.68  5824.9  468.98  5880.2  470.07
#Mann=13,-1,0
  4478.0    0.12       0  4603.1    0.16       0  4611.7    0.07       0
  4696.3    0.12       0  4869.8    0.16       0  4889.5    0.12       0
  4991.3    0.07       0  4997.4    0.12       0  5427.8    0.05       0
  5527.1    0.12       0  5626.3    0.05       0  5725.6    0.08       0
  5824.9    0.16       0
Bank Sta=4955.2,5632.1
Exp/Cntr=0.3,0.1

Type RM Length L Ch R = 1,7189,628,628,628
BEGIN DESCRIPTION:
UNT 026 in Running Cr Watershed 9.0
END DESCRIPTION:
XS GIS Cut Line= 3
      2909025.03      7056425.00      2908575.00      7056425.00
      2907774.99      7056375.00
#Sta/Elev= 30
  4560.9  468.68  4590.9  467.32  4610.9  464.80  4700.9  464.74  4710.9  464.99
  4740.9  470.86  4750.9  470.55  4780.9  465.83  4963.5  457.85  4980.9  457.24
  5005.4  451.76  5005.9  450.96  5011.5  451.76  5013.4  451.76  5021.0  457.19
  5051.0  456.91  5061.0  457.91  5088.6  455.59  5111.1  457.44  5121.1  456.04
  5131.2  457.25  5151.2  457.07  5191.3  455.19  5248.9  456.87  5354.4  457.51
  5366.1  457.85  5421.7  459.41  5453.5  461.52  5569.5  469.97  5812.5  481.37
#Mann=5,-1,0
  4560.9    0.12       0  5005.4    0.07       0  5011.5    0.12       0
  5354.4    0.16       0  5453.5    0.05       0
Bank Sta=4963.5,5366.1
Exp/Cntr=0.3,0.1

Type RM Length L Ch R = 1,6561,492,492,492
BEGIN DESCRIPTION:
UNT 026 in Running Cr Watershed 8.0
END DESCRIPTION:
XS GIS Cut Line= 3
      2909374.99      7056274.99      2908575.00      7055825.00
      2908225.03      7055525.02
#Sta/Elev= 30
  4070.2  475.59  4150.2  472.10  4253.8  468.29  4283.4  465.10  4311.1  465.50
  4357.0  461.38  4380.0  461.55  4423.6  457.89  4572.9  454.39  4980.1  453.91
  4985.2  451.48  4991.4  451.48  4992.1  447.79  4992.6  446.99  4998.2  447.79
  5001.8  448.25  5009.5  452.97  5023.7  453.62  5052.3  452.36  5058.9  449.25
  5066.5  449.01  5073.1  451.47  5080.3  450.95  5094.0  453.21  5268.7  454.39
  5321.2  455.41  5328.9  456.85  5356.8  466.74  5363.3  467.23  5449.0  470.61
#Mann=5,-1,0
  4070.2    0.05       0  4150.2    0.12       0  4992.1    0.07       0
  4998.2    0.12       0  5363.3    0.05       0
Bank Sta=4572.9,5268.7
Exp/Cntr=0.3,0.1

Type RM Length L Ch R = 1,6069,516,516,516
BEGIN DESCRIPTION:
UNT 026 in Running Cr Watershed 7.0
END DESCRIPTION:
XS GIS Cut Line= 3
      2909574.98      7056174.98      2908992.47      7055550.86
      2908423.89      7055159.62
#Sta/Elev= 30
  3977.7  481.07  4140.6  474.33  4202.8  469.75  4271.2  465.30  4317.4  460.85
  4494.6  453.16  4518.7  452.82  4552.2  451.81  4586.1  453.04  4600.3  451.48
  4754.3  451.39  4840.5  451.85  4890.5  449.03  4920.3  451.49  4977.1  450.18
  4985.9  451.44  4992.0  450.73  4995.1  446.48  4995.6  445.68  5001.5  446.48
  5006.1  446.59  5012.9  450.44  5032.8  452.82  5063.7  461.21  5124.4  465.68
  5228.9  468.10  5278.8  466.27  5350.5  468.13  5386.7  466.36  5521.6  466.78
#Mann=10,-1,0
  3977.7    0.05       0  4202.8    0.12       0  4271.2    0.16       0
  4494.6    0.12       0  4552.2    0.16       0  4754.3    0.12       0
  4995.1    0.07       0  5001.5    0.12       0  5006.1    0.16       0
  5124.4    0.05       0
Bank Sta=4518.7,5032.8
Exp/Cntr=0.3,0.1

Type RM Length L Ch R = 1,5553,700,700,700
BEGIN DESCRIPTION:
UNT 026 in Running Cr Watershed 6.0
END DESCRIPTION:
XS GIS Cut Line= 3
      2909625.02      7055975.03      2909242.20      7055138.20
      2908874.98      7054974.99
#Sta/Elev= 30
  4198.1  474.83  4308.8  469.99  4484.1  457.17  4551.1  454.28  4639.8  451.57
  4770.0  449.35  4803.0  450.76  4809.8  449.07  4838.3  448.72  4981.9  449.55
  4989.9  445.95  4996.2  445.01  4996.7  444.21  5002.1  444.21  5002.6  445.01
  5004.9  446.98  5011.9  449.77  5069.9  449.28  5102.5  448.98  5135.1  449.77
  5167.8  451.57  5214.9  454.50  5262.3  457.33  5285.6  459.55  5377.9  464.65
  5399.8  465.19  5429.5  464.57  5465.5  464.39  5505.8  465.60  5520.2  465.13
#Mann=7,-1,0
  4198.1    0.05       0  4308.8    0.16       0  4996.2    0.07       0
  5002.6    0.16       0  5069.9    0.12       0  5214.9    0.16       0
  5429.5    0.05       0
Bank Sta=4639.8,5167.8
Exp/Cntr=0.3,0.1

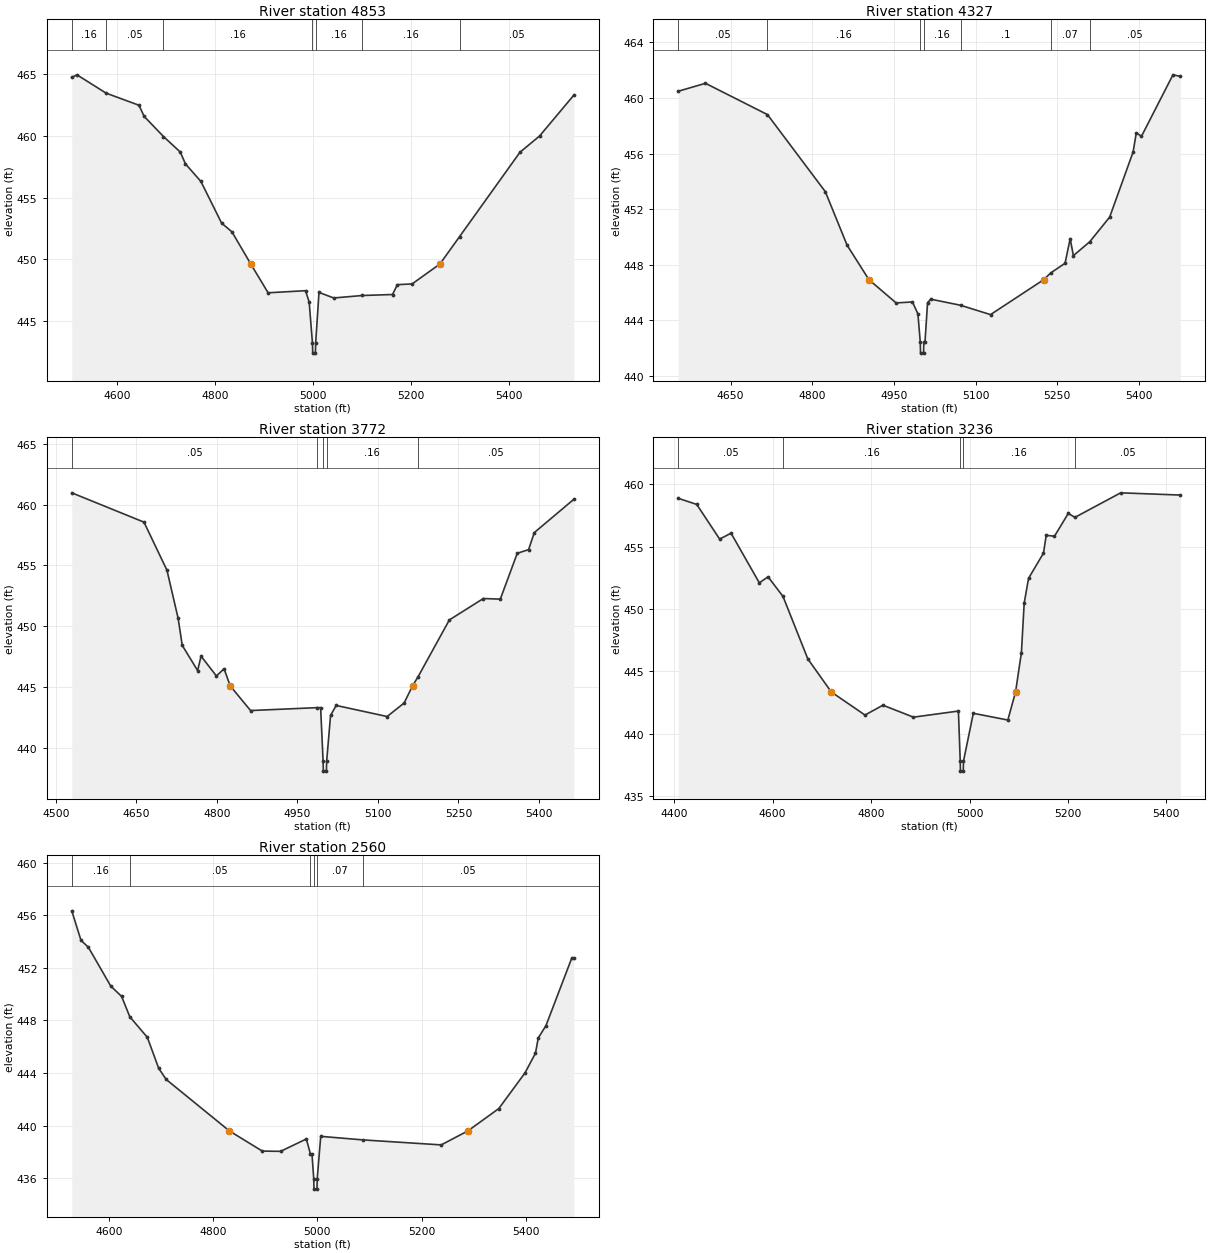
Type RM Length L Ch R = 1,4853,526,526,526
BEGIN DESCRIPTION:
UNT 026 in Running Cr Watershed 5.0
END DESCRIPTION:
XS GIS Cut Line= 3
      2910025.03      7055025.01      2909575.00      7054875.00
      2909024.97      7054875.00
#Sta/Elev= 30
  4507.9  464.76  4518.5  464.97  4578.1  463.48  4645.0  462.50  4655.5  461.60
  4695.0  459.96  4729.3  458.70  4739.8  457.74  4771.4  456.31  4813.6  452.93
  4834.7  452.22  4873.1  449.61  4908.5  447.27  4984.8  447.44  4992.3  446.52
  4999.0  443.17  4999.5  442.37  5005.0  442.37  5005.5  443.17  5012.3  447.30
  5042.3  446.85  5101.0  447.05  5162.3  447.13  5172.3  447.93  5202.3  447.99
  5259.1  449.61  5299.1  451.83  5422.3  458.68  5462.3  460.00  5532.3  463.32
#Mann=7,-1,0
  4507.9    0.16       0  4578.1    0.05       0  4695.0    0.16       0
  4999.0    0.07       0  5005.5    0.16       0  5101.0    0.16       0
  5299.1    0.05       0
Bank Sta=4873.1,5259.1
Exp/Cntr=0.3,0.1

Type RM Length L Ch R = 1,4327,555,555,555
BEGIN DESCRIPTION:
UNT 026 in Running Cr Watershed 4.0
END DESCRIPTION:
XS GIS Cut Line= 3
      2909975.03      7054375.00      2909525.00      7054375.00
      2909125.02      7054624.99
#Sta/Elev= 30
  4554.0  460.48  4604.0  461.05  4717.8  458.80  4824.0  453.26  4864.0  449.41
  4904.1  446.93  4954.0  445.26  4984.0  445.33  4994.0  444.47  4998.3  442.45
  4998.8  441.65  5004.3  441.65  5004.8  442.45  5007.0  442.45  5011.7  445.28
  5017.6  445.53  5072.4  445.09  5127.3  444.42  5224.9  446.93  5237.9  447.42
  5264.1  448.11  5273.5  449.88  5279.4  448.66  5309.5  449.66  5346.0  451.43
  5389.1  456.12  5394.9  457.49  5404.4  457.24  5462.2  461.66  5475.7  461.55
#Mann=7,-1,0
  4554.0    0.05       0  4717.8    0.16       0  4998.3    0.07       0
  5004.8    0.16       0  5072.4     0.1       0  5237.9    0.07       0
  5309.5    0.05       0
Bank Sta=4904.1,5224.9
Exp/Cntr=0.3,0.1

Type RM Length L Ch R = 1,3772,536,536,536
BEGIN DESCRIPTION:
UNT 026 in Running Cr Watershed 3.0
END DESCRIPTION:
XS GIS Cut Line= 3
      2910025.02      7054175.02      2909675.00      7053875.00
      2909225.04      7053725.01
#Sta/Elev= 30
  4529.6  460.96  4664.1  458.55  4706.9  454.60  4727.7  450.65  4735.4  448.42
  4764.0  446.35  4770.5  447.53  4799.1  445.90  4813.3  446.50  4824.7  445.09
  4862.7  443.06  4987.3  443.30  4993.2  443.30  4997.8  438.88  4998.3  438.08
  5003.9  438.08  5004.4  438.88  5011.7  442.66  5022.2  443.48  5117.1  442.57
  5148.7  443.68  5164.4  445.09  5174.6  445.83  5233.0  450.51  5296.3  452.27
  5327.9  452.22  5359.5  455.99  5380.6  456.29  5391.2  457.69  5464.9  460.43
#Mann=5,-1,0
  4529.6    0.05       0  4987.3    0.16       0  4997.8    0.07       0
  5004.4    0.16       0  5174.6    0.05       0
Bank Sta=4824.7,5164.4
Exp/Cntr=0.3,0.1

Type RM Length L Ch R = 1,3236,676,676,676
BEGIN DESCRIPTION:
UNT 026 in Running Cr Watershed 2.0
END DESCRIPTION:
XS GIS Cut Line= 3
      2910024.99      7053924.98      2909752.70      7053313.27
      2909438.75      7053157.60
#Sta/Elev= 30
  4408.2  458.89  4445.8  458.40  4492.3  455.62  4515.5  456.09  4572.9  452.11
  4590.7  452.59  4621.0  451.02  4671.4  446.01  4719.2  443.35  4787.6  441.50
  4824.1  442.29  4886.0  441.33  4977.4  441.82  4981.1  437.80  4981.6  437.00
  4987.2  437.00  4987.7  437.80  5007.7  441.64  5077.8  441.10  5093.5  443.35
  5105.4  446.51  5111.0  450.47  5119.9  452.47  5150.2  454.49  5155.8  455.92
  5172.6  455.85  5200.6  457.68  5214.0  457.36  5307.1  459.33  5428.2  459.15
#Mann=5,-1,0
  4408.2    0.05       0  4621.0    0.16       0  4981.1    0.07       0
  4987.7    0.16       0  5214.0    0.05       0
Bank Sta=4719.2,5093.5
Exp/Cntr=0.3,0.1

Type RM Length L Ch R = 1,2560,0,0,0
BEGIN DESCRIPTION:
UNT 026 in Running Cr Watershed 1.0
END DESCRIPTION:
XS GIS Cut Line= 3
      2910591.68      7053283.21      2910291.70      7052933.23
      2909791.74      7052883.24
#Sta/Elev= 30
  4528.8  456.33  4546.5  454.09  4560.7  453.56  4603.5  450.62  4624.4  449.83
  4640.2  448.28  4673.8  446.72  4695.7  444.36  4710.0  443.52  4831.3  439.61
  4894.4  438.08  4929.5  438.06  4978.9  439.00  4986.8  437.86  4989.7  437.86
  4993.1  435.99  4993.6  435.19  4999.3  435.19  4999.8  435.99  5006.5  439.20
  5087.1  438.93  5237.7  438.55  5288.8  439.61  5348.2  441.31  5398.5  444.02
  5418.6  445.52  5423.9  446.67  5438.7  447.61  5488.1  452.73  5492.2  452.73
#Mann=6,-1,0
  4528.8    0.16       0  4640.2    0.05       0  4986.8    0.07       0
  4993.1    0.07       0  4999.8    0.07       0  5087.1    0.05       0
Bank Sta=4831.3,5288.8
Exp/Cntr=0.3,0.1

Chan Stop Cuts=-1