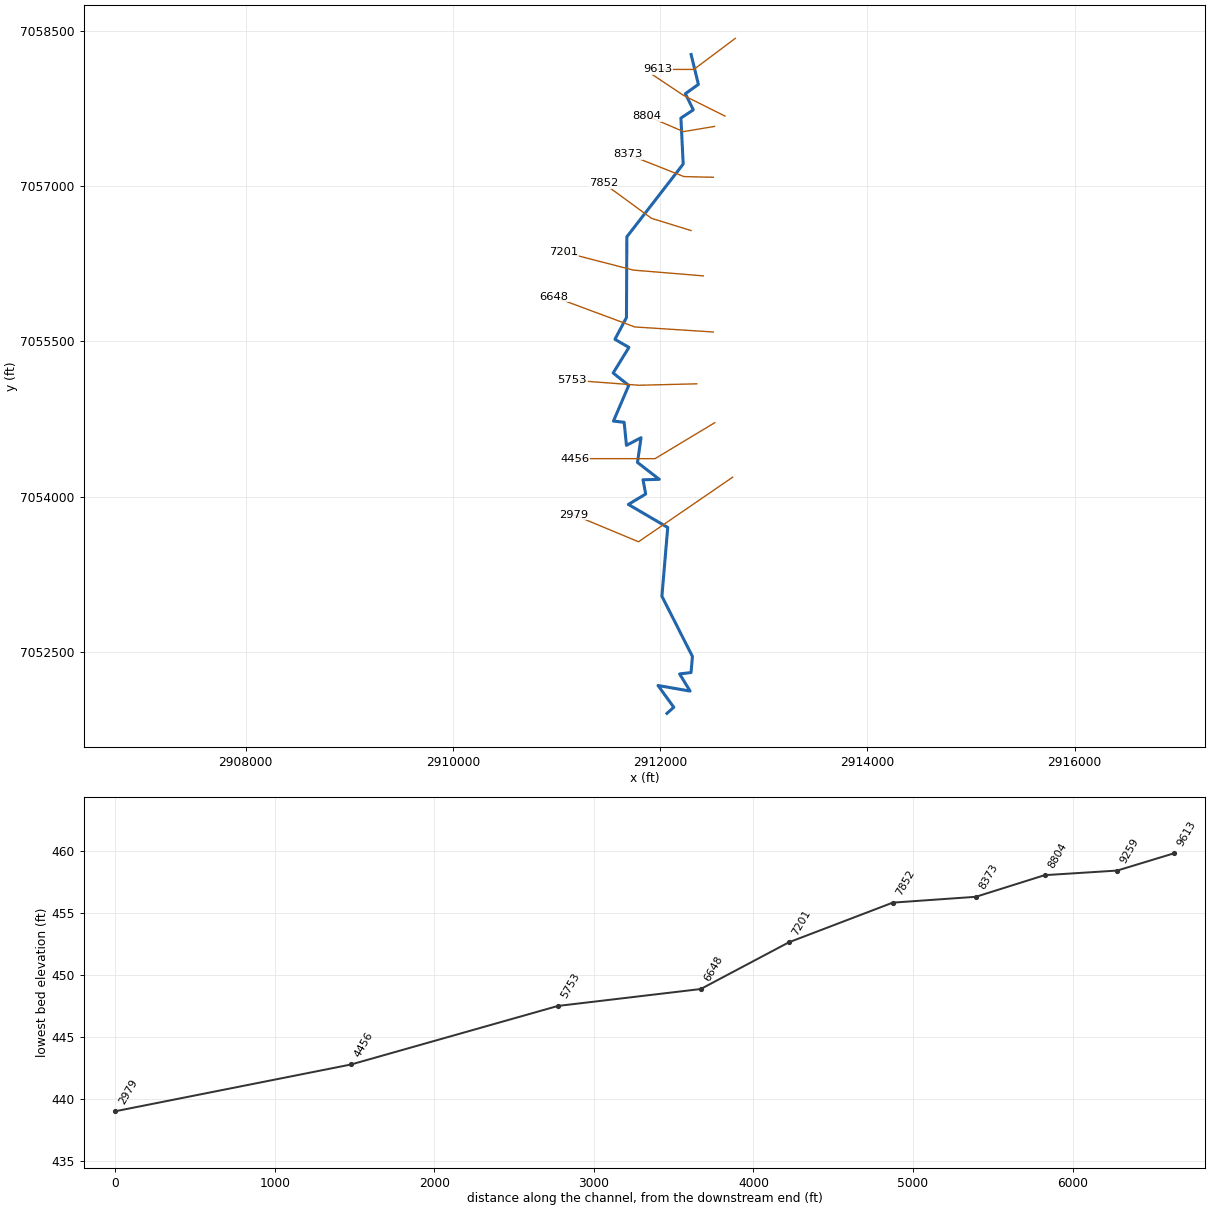
--- UNT 027 in Running Cr Watershed.prj (project) ---

Proj Title=UNT 027 in Running Cr Watershed Base Level Engineering
Current Plan=p01
Default Exp/Contr=0.3,0.1
English Units
Geom File=g01
Flow File=f01
Plan File=p01
BEGIN DESCRIPTION:
UNT 027 in Running Cr Watershed
END DESCRIPTION:

--- UNT 027 in Running Cr Watershed.p01 (plan) ---

Plan Title=Multiple Run
Short Identifier=Multiple
Geom File=g01
Flow File=f01
Subcritical Flow
K Sum by GR= 0
Std Step Tol= 0.01
Critical Tol= 0.01
Num of Std Step Trials= 20
Max Error Tol= 0.3
Flow Tol Ratio= 0.001
Split Flow NTrial= 30
Split Flow Tol= 0.02
Split Flow Ratio= 0.02
Log Output Level= 0
Friction Slope Method= 1
Unsteady Friction Slope Method= 2
Unsteady Bridges Friction Slope Method= 1
Parabolic Critical Depth
Global Vel Dist=  1 , 1 , 1
Global Log Level= 0
CheckData=True
Encroach Param= -1, 0, 0, 0
BEGIN DESCRIPTION:
Multiple Run
END DESCRIPTION:

--- UNT 027 in Running Cr Watershed.f01 (steady flow) ---

Flow Title=Multiple
Number of Profiles=7
Profile Names=10-year,25-year,50-year,1pct_min,100-year,1pct_plu,500-year
River Rch & RM= UNT 027 in Runni,Reach-1,9613
     691     926    1116     667    1331    2657    1893
River Rch & RM= UNT 027 in Runni,Reach-1,8373
     811    1096    1329     799    1595    3182    2296
Boundary for River Rch & Prof#=UNT 027 in Runni,Reach-1,1
Up Type=0
Dn Type=3
Dn Slope=0.005
Boundary for River Rch & Prof#=UNT 027 in Runni,Reach-1,2
Up Type=0
Dn Type=3
Dn Slope=0.005
Boundary for River Rch & Prof#=UNT 027 in Runni,Reach-1,3
Up Type=0
Dn Type=3
Dn Slope=0.005
Boundary for River Rch & Prof#=UNT 027 in Runni,Reach-1,4
Up Type=0
Dn Type=3
Dn Slope=0.005
Boundary for River Rch & Prof#=UNT 027 in Runni,Reach-1,5
Up Type=0
Dn Type=3
Dn Slope=0.005
Boundary for River Rch & Prof#=UNT 027 in Runni,Reach-1,6
Up Type=0
Dn Type=3
Dn Slope=0.005
Boundary for River Rch & Prof#=UNT 027 in Runni,Reach-1,7
Up Type=0
Dn Type=3
Dn Slope=0.005

--- UNT 027 in Running Cr Watershed.g01 (geometry) ---

Geom Title=Existing Conditions

River Reach=UNT 027 in Runni,Reach-1
Reach XY= 30
      2912298.43      7058269.03      2912368.80      7057980.69
      2912243.19      7057890.61      2912319.58      7057734.72
      2912200.11      7057655.44      2912222.19      7057211.80
      2911678.30      7056509.59      2911674.68      7055730.94
      2911563.15      7055520.50      2911698.60      7055442.62
      2911546.46      7055195.51      2911696.70      7055075.45
      2911549.08      7054731.57      2911652.35      7054719.74
      2911674.55      7054497.07      2911815.18      7054570.98
      2911780.89      7054332.51      2911991.20      7054169.32
      2911834.25      7054164.86      2911860.40      7054027.59
      2911693.05      7053927.13      2912072.99      7053704.65
      2912016.69      7053041.14      2912311.30      7052459.82
      2912297.94      7052304.67      2912187.65      7052291.37
      2912288.71      7052125.61      2911979.34      7052179.81
      2912131.17      7051969.74      2912065.59      7051910.71

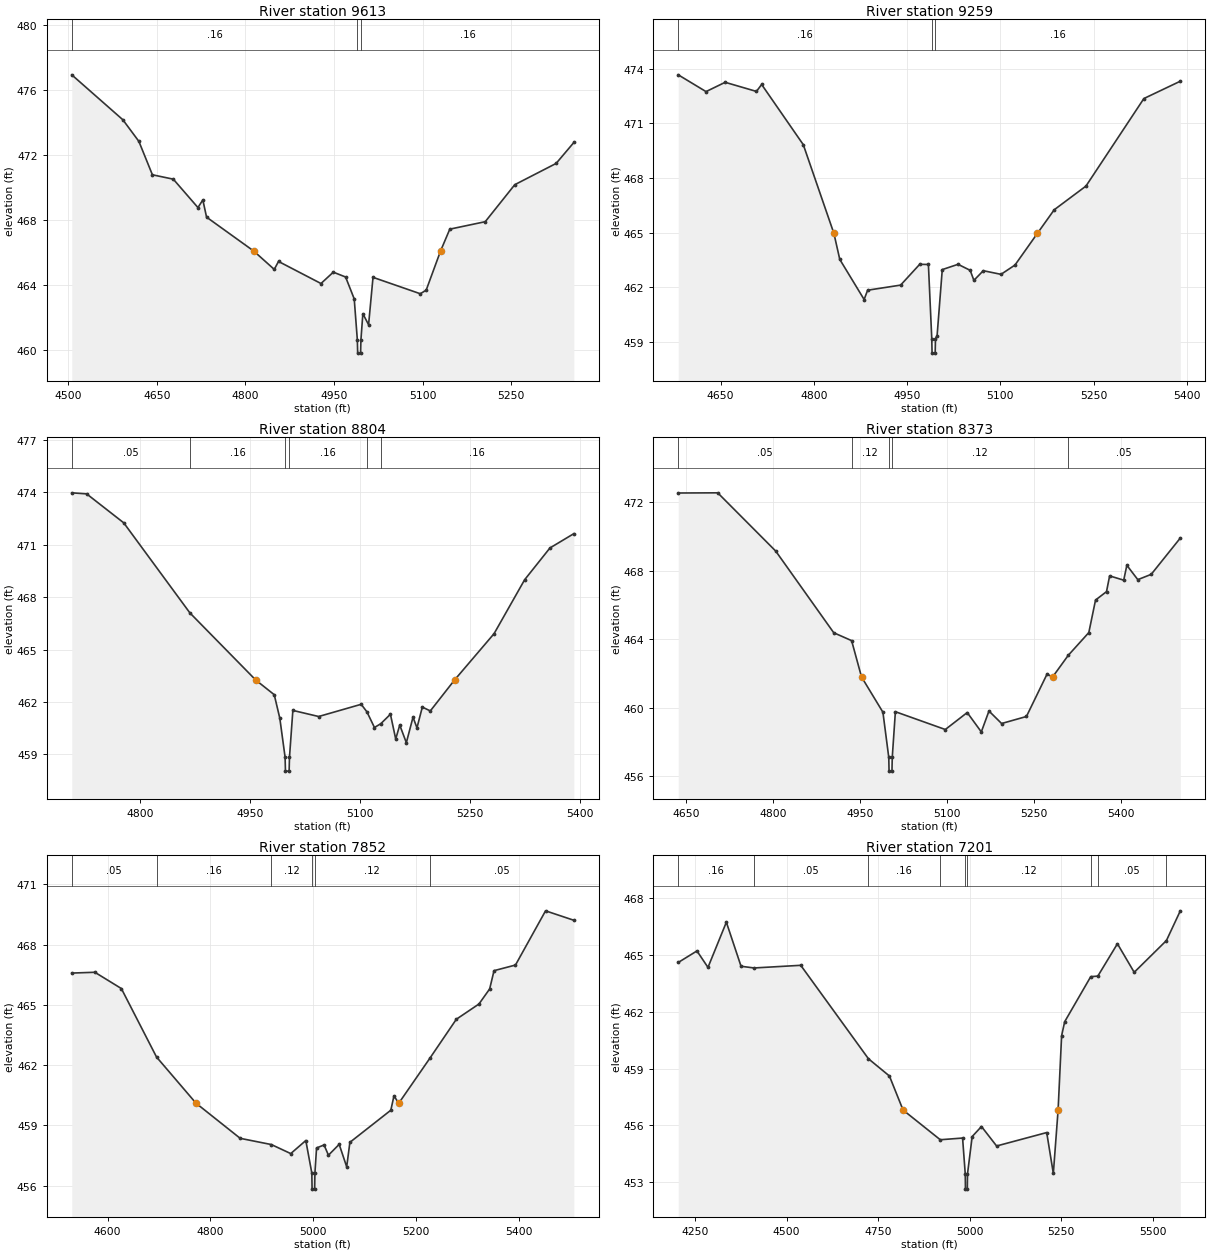
Type RM Length L Ch R = 1,9613,354,354,354
BEGIN DESCRIPTION:
UNT 027 in Running Cr Watershed 4.0
END DESCRIPTION:
XS GIS Cut Line= 3
      2912725.04      7058425.03      2912325.00      7058125.00
      2911975.04      7058125.00
#Sta/Elev= 30
  4506.0  476.93  4592.5  474.16  4619.6  472.83  4642.5  470.77  4677.9  470.50
  4719.6  468.75  4727.9  469.22  4734.2  468.16  4814.1  466.07  4848.8  464.94
  4856.0  465.43  4927.9  464.07  4948.8  464.77  4969.6  464.47  4984.2  463.12
  4989.5  460.58  4990.0  459.78  4995.0  459.78  4995.5  460.58  4998.8  462.21
  5008.5  461.53  5016.0  464.45  5096.0  463.44  5106.0  463.66  5130.3  466.07
  5146.0  467.42  5206.0  467.88  5256.0  470.16  5326.0  471.47  5356.0  472.76
#Mann=3,-1,0
  4506.0    0.16       0  4989.5    0.07       0  4995.5    0.16       0
Bank Sta=4814.1,5130.3
Exp/Cntr=0.3,0.1

Type RM Length L Ch R = 1,9259,455,455,455
BEGIN DESCRIPTION:
UNT 027 in Running Cr Watershed 3.0
END DESCRIPTION:
XS GIS Cut Line= 3
      2912624.99      7057675.01      2912225.00      7057875.00
      2911924.96      7058075.02
#Sta/Elev= 30
  4581.8  473.66  4626.5  472.74  4657.3  473.25  4707.6  472.75  4716.0  473.13
  4783.0  469.83  4832.3  464.96  4841.7  463.54  4880.9  461.34  4886.5  461.85
  4939.6  462.13  4970.3  463.27  4984.3  463.26  4989.7  459.20  4990.2  458.40
  4995.2  458.40  4995.7  459.20  4998.3  459.36  5006.6  462.98  5032.0  463.27
  5051.5  462.94  5057.5  462.39  5072.6  462.92  5101.1  462.72  5123.6  463.23
  5159.5  464.96  5186.7  466.26  5237.8  467.56  5331.0  472.36  5389.6  473.31
#Mann=3,-1,0
  4581.8    0.16       0  4989.7    0.07       0  4995.7    0.16       0
Bank Sta=4832.3,5159.5
Exp/Cntr=0.3,0.1

Type RM Length L Ch R = 1,8804,431,431,431
BEGIN DESCRIPTION:
UNT 027 in Running Cr Watershed 2.0
END DESCRIPTION:
XS GIS Cut Line= 3
      2912524.98      7057575.00      2912225.00      7057525.00
      2911875.01      7057675.00
#Sta/Elev= 30
  4706.4  473.98  4726.7  473.92  4777.3  472.26  4867.5  467.10  4957.4  463.25
  4982.6  462.41  4990.2  461.06  4997.4  458.83  4997.9  458.03  5002.9  458.03
  5003.4  458.83  5008.0  461.51  5043.2  461.16  5101.2  461.86  5109.0  461.43
  5119.3  460.53  5128.0  460.75  5141.1  461.29  5148.3  459.87  5153.8  460.67
  5162.8  459.66  5171.9  461.12  5177.3  460.51  5184.6  461.70  5195.5  461.48
  5228.5  463.25  5282.5  465.91  5324.2  469.00  5358.7  470.82  5391.3  471.64
#Mann=6,-1,0
  4706.4    0.05       0  4867.5    0.16       0  4997.4    0.07       0
  5003.4    0.16       0  5109.0    0.12       0  5128.0    0.16       0
Bank Sta=4957.4,5228.5
Exp/Cntr=0.3,0.1

Type RM Length L Ch R = 1,8373,521,521,521
BEGIN DESCRIPTION:
Mapping XS 7d25b081
END DESCRIPTION:
XS GIS Cut Line= 3
      2912513.07      7057084.10      2912228.39      7057091.05
      2911688.34      7057305.68
#Sta/Elev= 30
  4635.9  472.53  4704.0  472.54  4804.0  469.14  4904.1  464.37  4934.9  463.91
  4952.0  461.79  4988.9  459.73  4999.0  457.09  4999.5  456.29  5004.5  456.29
  5005.0  457.09  5010.4  459.76  5096.5  458.72  5134.3  459.71  5158.6  458.58
  5171.8  459.80  5193.6  459.07  5236.4  459.48  5271.9  461.95  5281.6  461.79
  5308.5  463.05  5344.0  464.38  5355.6  466.28  5374.5  466.77  5379.9  467.69
  5404.2  467.44  5409.6  468.31  5428.5  467.47  5451.6  467.78  5501.8  469.90
#Mann=5,-1,0
  4635.9    0.05       0  4934.9    0.12       0  4999.0    0.07       0
  5005.0    0.12       0  5308.5    0.05       0
Bank Sta=4952,5281.6
Exp/Cntr=0.3,0.1

Type RM Length L Ch R = 1,7852,651,651,651
BEGIN DESCRIPTION:
Mapping XS 614de93e
END DESCRIPTION:
XS GIS Cut Line= 3
      2912297.88      7056570.20      2911915.89      7056688.27
      2911450.57      7057028.58
#Sta/Elev= 30
  4530.4  466.58  4575.3  466.62  4626.8  465.81  4695.2  462.40  4772.0  460.10
  4857.9  458.35  4918.5  458.04  4956.2  457.59  4985.5  458.24  4997.2  456.62
  4997.7  455.82  5002.7  455.82  5003.2  456.62  5006.4  457.87  5021.0  458.02
  5029.5  457.51  5050.4  458.05  5065.0  456.93  5071.2  458.15  5150.8  459.75
  5156.9  460.46  5166.3  460.10  5226.5  462.33  5278.2  464.28  5322.2  465.04
  5343.0  465.79  5351.5  466.70  5393.2  466.98  5451.7  469.68  5506.7  469.21
#Mann=6,-1,0
  4530.4    0.05       0  4695.2    0.16       0  4918.5    0.12       0
  4997.2    0.07       0  5003.2    0.12       0  5226.5    0.05       0
Bank Sta=4772,5166.3
Exp/Cntr=0.3,0.1

Type RM Length L Ch R = 1,7201,553,553,553
BEGIN DESCRIPTION:
Mapping XS 24b126cb
END DESCRIPTION:
XS GIS Cut Line= 3
      2912415.93      7056132.71      2911742.28      7056188.27
      2911069.31      7056361.72
#Sta/Elev= 30
  4204.2  464.61  4255.3  465.22  4285.4  464.35  4335.6  466.74  4375.7  464.41
  4411.2  464.32  4538.7  464.46  4723.6  459.52  4780.8  458.61  4818.1  456.81
  4919.7  455.24  4980.6  455.33  4987.9  453.43  4988.4  452.63  4993.5  452.63
  4994.0  453.43  5006.8  455.41  5032.2  455.94  5073.5  454.91  5210.3  455.62
  5228.4  453.46  5241.4  456.81  5251.0  460.74  5259.4  461.48  5330.5  463.86
  5349.9  463.89  5403.4  465.60  5449.2  464.09  5537.2  465.77  5575.1  467.34
#Mann=9,-1,0
  4204.2    0.16       0  4411.2    0.05       0  4723.6    0.16       0
  4919.7    0.12       0  4987.9    0.07       0  4994.0    0.12       0
  5330.5    0.16       0  5349.9    0.05       0  5537.2    0.16       0
Bank Sta=4818.1,5241.4
Exp/Cntr=0.3,0.1

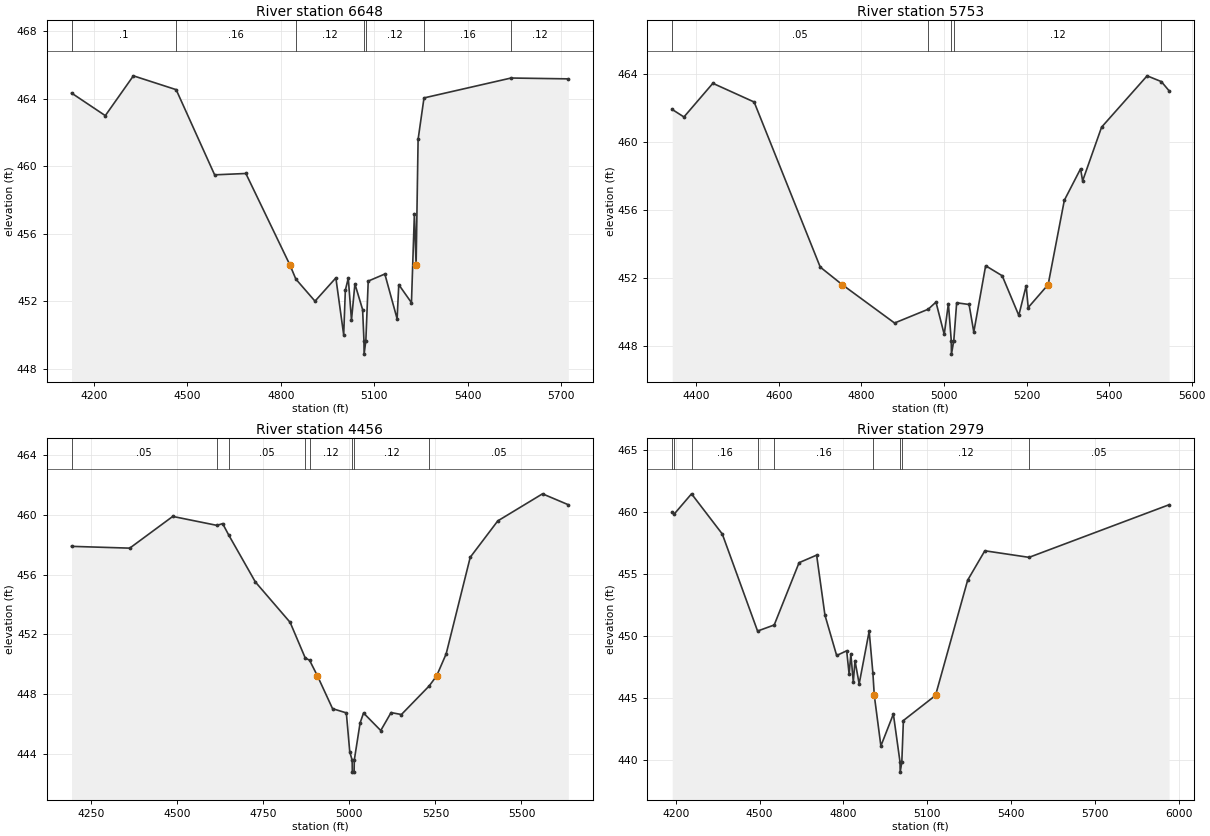
Type RM Length L Ch R = 1,6648,895,895,895
BEGIN DESCRIPTION:
Mapping XS fdc23054
END DESCRIPTION:
XS GIS Cut Line= 3
      2912513.13      7055591.05      2911756.17      7055639.66
      2910973.23      7055930.66
#Sta/Elev= 30
  4128.6  464.35  4237.0  463.01  4327.1  465.37  4464.3  464.55  4587.7  459.50
  4687.9  459.58  4829.4  454.15  4848.2  453.32  4909.7  452.01  4976.6  453.39
  5001.7  450.01  5007.0  452.66  5016.4  453.37  5026.7  450.89  5037.7  453.03
  5062.4  451.51  5066.7  449.67  5067.2  448.87  5072.8  449.67  5080.4  453.20
  5133.7  453.62  5173.1  450.96  5178.4  452.99  5219.1  451.92  5228.5  457.20
  5234.0  454.15  5240.4  461.60  5259.3  464.06  5538.6  465.24  5722.4  465.19
#Mann=7,-1,0
  4128.6     0.1       0  4464.3    0.16       0  4848.2    0.12       0
  5066.7    0.07       0  5072.8    0.12       0  5259.3    0.16       0
  5538.6    0.12       0
Bank Sta=4829.4,5234
Exp/Cntr=0.3,0.1

Type RM Length L Ch R = 1,5753,1297,1297,1297
BEGIN DESCRIPTION:
Mapping XS 9a1756b0
END DESCRIPTION:
XS GIS Cut Line= 3
      2912353.38      7055091.05      2911797.83      7055077.16
      2911151.98      7055125.77
#Sta/Elev= 30
  4341.9  461.90  4370.3  461.46  4440.3  463.44  4540.3  462.34  4700.4  452.63
  4753.5  451.60  4880.4  449.34  4961.8  450.15  4980.7  450.57  5000.7  448.67
  5010.8  450.48  5017.7  448.31  5018.2  447.51  5023.9  448.31  5030.8  450.53
  5060.9  450.43  5072.3  448.81  5101.0  452.71  5141.1  452.12  5181.3  449.79
  5199.1  451.53  5204.1  450.25  5252.4  451.60  5291.6  456.56  5330.9  458.41
  5335.9  457.70  5381.8  460.86  5492.1  463.88  5526.6  463.54  5545.3  463.00
#Mann=5,-1,0
  4341.9    0.05       0  4961.8    0.12       0  5017.7    0.07       0
  5023.9    0.12       0  5526.6    0.05       0
Bank Sta=4753.5,5252.4
Exp/Cntr=0.3,0.1

Type RM Length L Ch R = 1,4456,1477,1477,1477
BEGIN DESCRIPTION:
Mapping XS 5ce66fef
END DESCRIPTION:
XS GIS Cut Line= 3
      2912526.99      7054716.04      2911950.61      7054368.83
      2911179.90      7054368.83
#Sta/Elev= 30
  4192.7  457.89  4361.9  457.77  4486.9  459.89  4615.5  459.29  4631.8  459.41
  4649.4  458.65  4726.9  455.51  4827.9  452.81  4871.8  450.43  4884.3  450.28
  4907.3  449.23  4951.2  447.04  4991.2  446.76  5001.2  444.15  5008.1  443.60
  5008.6  442.80  5013.8  442.80  5014.3  443.60  5031.2  446.09  5041.2  446.75
  5091.2  445.58  5121.2  446.78  5151.2  446.65  5231.9  448.56  5253.5  449.23
  5281.2  450.70  5351.2  457.16  5431.2  459.59  5561.2  461.40  5636.3  460.67
#Mann=8,-1,0
  4192.7    0.05       0  4615.5    0.16       0  4649.4    0.05       0
  4871.8    0.16       0  4884.3    0.12       0  5008.1    0.07       0
  5014.3    0.12       0  5231.9    0.05       0
Bank Sta=4907.3,5253.5
Exp/Cntr=0.3,0.1

Type RM Length L Ch R = 1,2979,0,0,0
BEGIN DESCRIPTION:
UNT 027 in Running Cr Watershed 1.0
END DESCRIPTION:
XS GIS Cut Line= 3
      2912699.85      7054190.09      2911790.89      7053566.74
      2911165.93      7053827.14
#Sta/Elev= 30
  4187.0  459.97  4194.1  459.84  4256.1  461.47  4366.3  458.23  4492.6  450.41
  4552.2  450.90  4641.2  455.92  4704.1  456.53  4733.9  451.69  4775.8  448.44
  4811.7  448.82  4820.5  446.93  4826.6  448.56  4835.4  446.30  4841.5  448.02
  4856.4  446.15  4892.3  450.40  4905.6  447.01  4910.6  445.22  4934.2  441.15
  4978.9  443.72  5002.8  439.84  5003.3  439.04  5009.1  439.84  5014.8  443.20
  5129.8  445.22  5244.9  454.51  5306.4  456.88  5464.8  456.35  5966.2  460.59
#Mann=9,-1,0
  4187.0    0.08       0  4194.1    0.05       0  4256.1    0.16       0
  4492.6    0.12       0  4552.2    0.16       0  4905.6    0.12       0
  5002.8    0.07       0  5009.1    0.12       0  5464.8    0.05       0
Bank Sta=4910.6,5129.8
Exp/Cntr=0.3,0.1

Chan Stop Cuts=-1