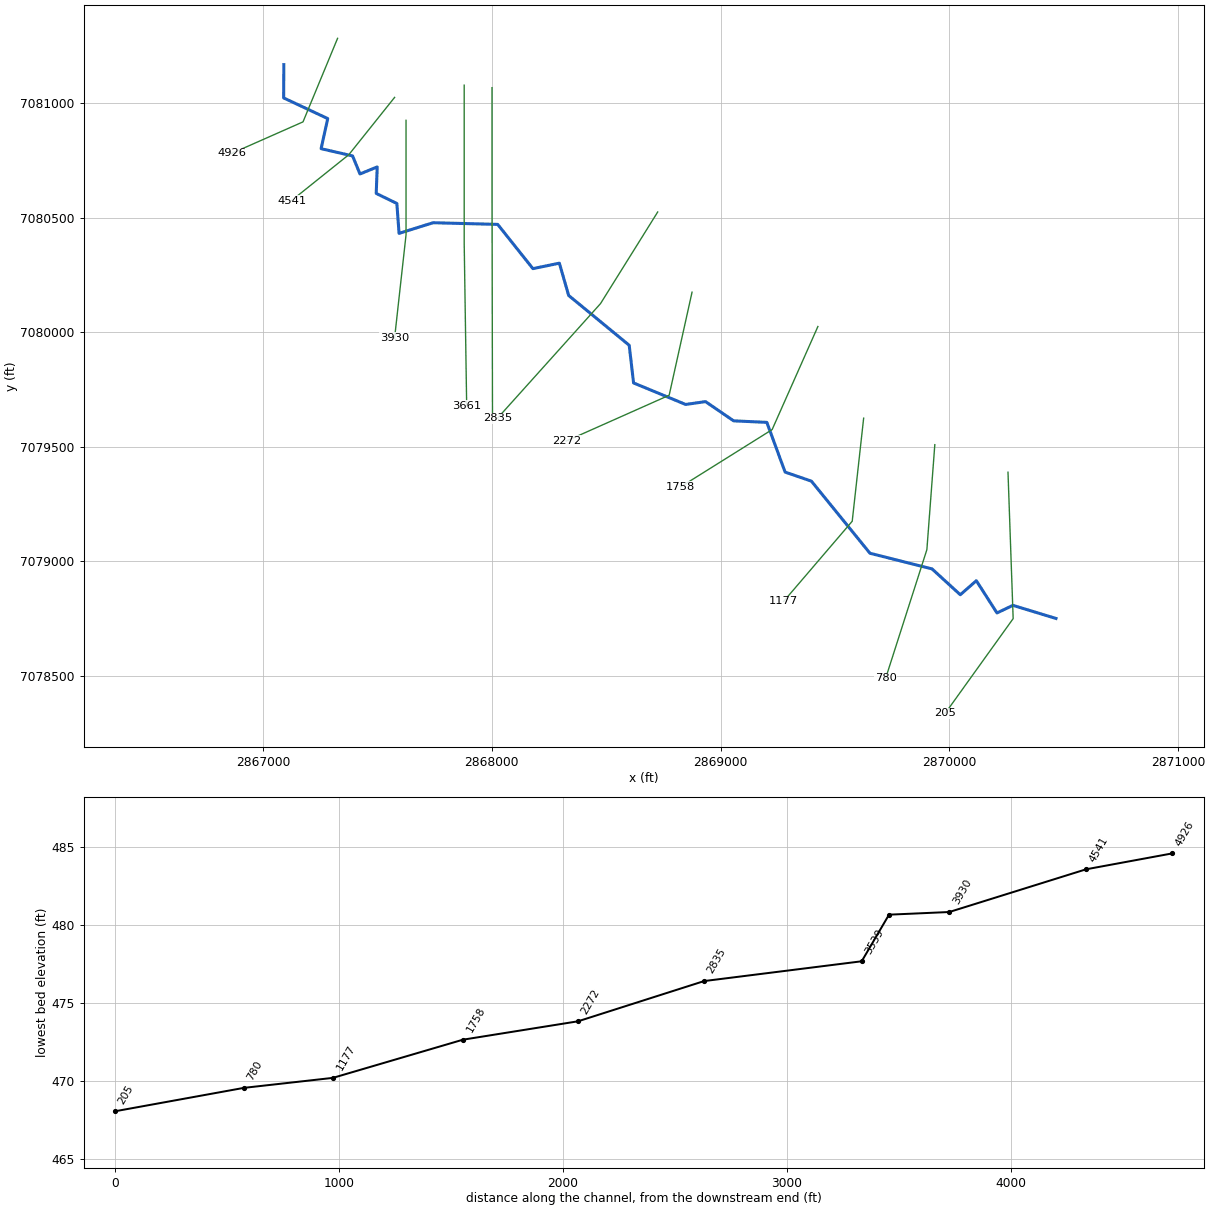
--- UNT 028 in Running Cr Watershed.prj (project) ---

Proj Title=UNT 028 in Running Cr Watershed Base Level Engineering
Current Plan=p01
Default Exp/Contr=0.3,0.1
English Units
Geom File=g01
Flow File=f01
Plan File=p01
BEGIN DESCRIPTION:
UNT 028 in Running Cr Watershed
END DESCRIPTION:

--- UNT 028 in Running Cr Watershed.p01 (plan) ---

Plan Title=Multiple Run
Short Identifier=Multiple
Geom File=g01
Flow File=f01
Subcritical Flow
K Sum by GR= 0
Std Step Tol= 0.01
Critical Tol= 0.01
Num of Std Step Trials= 20
Max Error Tol= 0.3
Flow Tol Ratio= 0.001
Split Flow NTrial= 30
Split Flow Tol= 0.02
Split Flow Ratio= 0.02
Log Output Level= 0
Friction Slope Method= 1
Unsteady Friction Slope Method= 2
Unsteady Bridges Friction Slope Method= 1
Parabolic Critical Depth
Global Vel Dist=  1 , 1 , 1
Global Log Level= 0
CheckData=True
Encroach Param= -1, 0, 0, 0
BEGIN DESCRIPTION:
Multiple Run
END DESCRIPTION:

--- UNT 028 in Running Cr Watershed.f01 (steady flow) ---

Flow Title=Multiple
Number of Profiles=7
Profile Names=10-year,25-year,50-year,1pct_min,100-year,1pct_plu,500-year
River Rch & RM= UNT 028 in Runni,Reach-1,4926
     824    1111    1345     808    1612    3216    2308
River Rch & RM= UNT 028 in Runni,Reach-1,3930
    1213    1665    2039    1236    2467    4921    3601
Boundary for River Rch & Prof#=UNT 028 in Runni,Reach-1,1
Up Type=0
Dn Type=3
Dn Slope=0.005
Boundary for River Rch & Prof#=UNT 028 in Runni,Reach-1,2
Up Type=0
Dn Type=3
Dn Slope=0.005
Boundary for River Rch & Prof#=UNT 028 in Runni,Reach-1,3
Up Type=0
Dn Type=3
Dn Slope=0.005
Boundary for River Rch & Prof#=UNT 028 in Runni,Reach-1,4
Up Type=0
Dn Type=3
Dn Slope=0.005
Boundary for River Rch & Prof#=UNT 028 in Runni,Reach-1,5
Up Type=0
Dn Type=3
Dn Slope=0.005
Boundary for River Rch & Prof#=UNT 028 in Runni,Reach-1,6
Up Type=0
Dn Type=3
Dn Slope=0.005
Boundary for River Rch & Prof#=UNT 028 in Runni,Reach-1,7
Up Type=0
Dn Type=3
Dn Slope=0.005

--- UNT 028 in Running Cr Watershed.g01 (geometry) ---

Geom Title=Existing Conditions

River Reach=UNT 028 in Runni,Reach-1
Reach XY= 30
      2867090.95      7081168.14      2867090.07      7081022.76
      2867282.75      7080932.56      2867253.84      7080801.19
      2867391.34      7080769.67      2867423.74      7080690.85
      2867499.06      7080721.50      2867494.68      7080605.90
      2867584.89      7080562.11      2867594.52      7080431.62
      2867743.40      7080478.03      2868025.59      7080470.71
      2868179.47      7080277.64      2868295.16      7080301.46
      2868335.74      7080160.53      2868600.34      7079943.20
      2868619.47      7079778.71      2868847.02      7079684.81
      2868933.96      7079697.21      2869056.74      7079613.27
      2869201.83      7079606.62      2869281.73      7079389.55
      2869396.74      7079350.00      2869652.56      7079035.35
      2869924.04      7078966.97      2870047.33      7078854.20
      2870117.46      7078915.51      2870207.74      7078774.79
      2870277.25      7078807.97      2870465.59      7078750.71

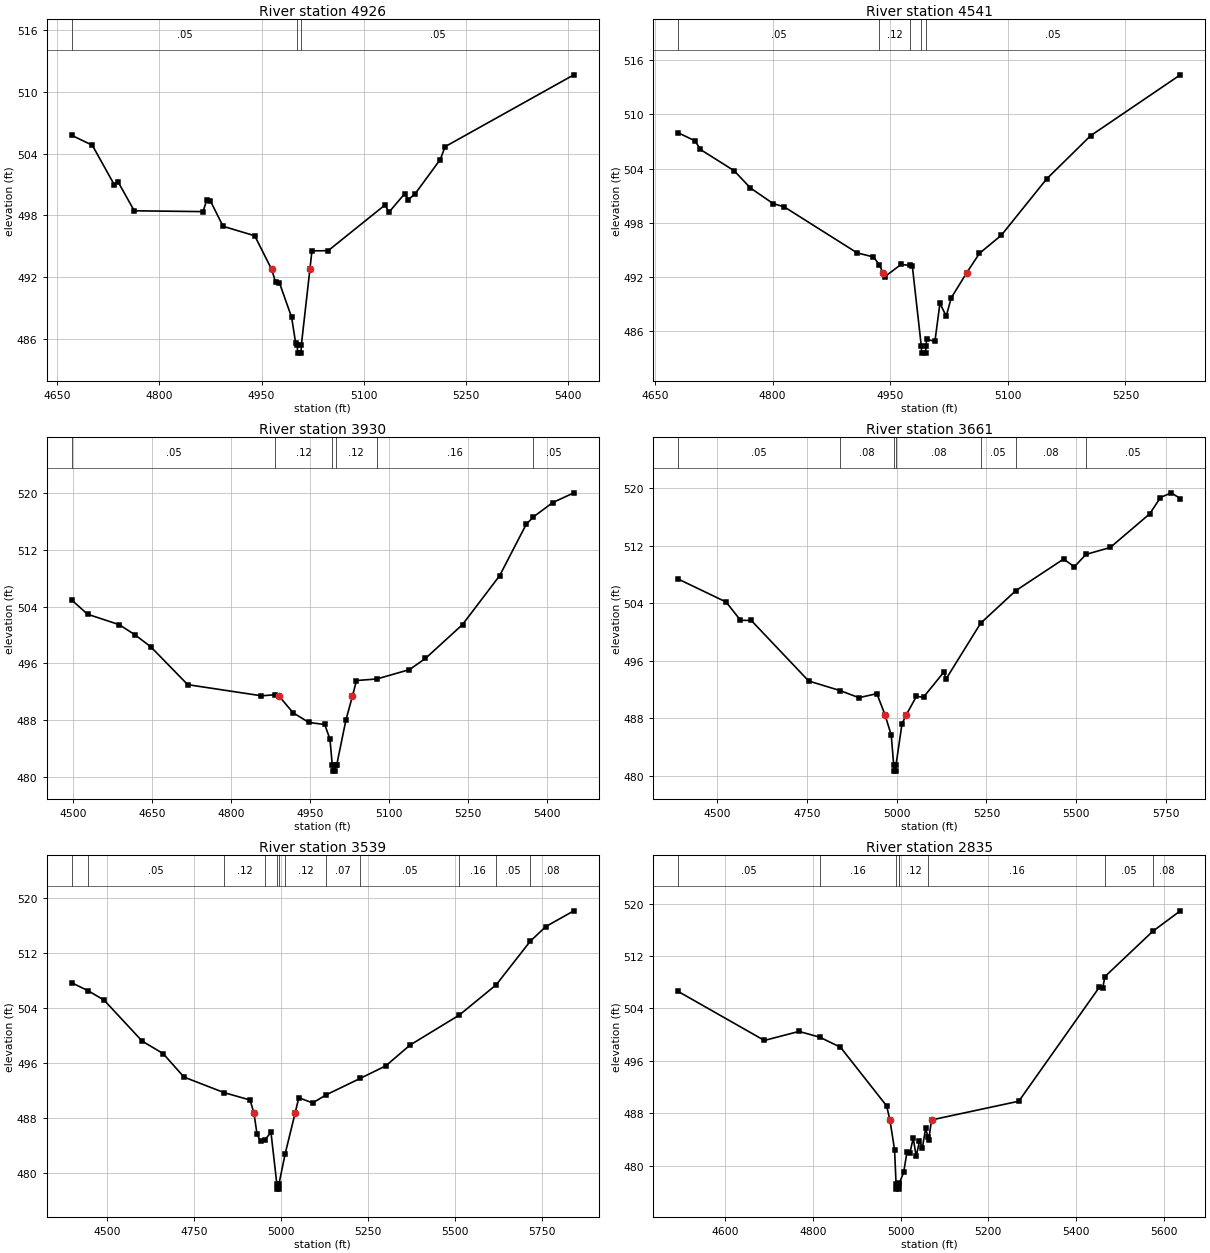
Type RM Length L Ch R = 1,4926,385,385,385
BEGIN DESCRIPTION:
UNT 028 in Running Cr Watershed 9.0
END DESCRIPTION:
XS GIS Cut Line= 3
      2867325.82      7081282.84      2867174.77      7080918.24
      2866862.25      7080780.21
#Sta/Elev= 30
  4671.7  505.78  4701.8  504.82  4734.0  500.98  4739.4  501.28  4763.3  498.44
  4864.2  498.36  4869.7  499.49  4875.1  499.39  4893.6  496.93  4940.0  496.01
  4964.9  492.73  4970.7  491.47  4976.1  491.46  4994.1  488.08  5000.0  485.58
  5002.4  485.39  5002.9  484.59  5007.9  484.59  5008.4  485.39  5020.9  492.73
  5023.9  494.54  5047.7  494.56  5131.2  499.01  5136.7  498.29  5160.0  500.11
  5165.5  499.53  5175.4  500.11  5212.1  503.43  5219.2  504.68  5408.0  511.67
#Mann=3,-1,0
  4671.7    0.05       0  5002.4    0.03       0  5008.4    0.05       0
Bank Sta=4964.9,5020.9
Exp/Cntr=0.3,0.1

Type RM Length L Ch R = 1,4541,611,611,611
BEGIN DESCRIPTION:
UNT 028 in Running Cr Watershed 8.0
END DESCRIPTION:
XS GIS Cut Line= 3
      2867575.03      7081025.03      2867375.00      7080775.00
      2867124.97      7080574.97
#Sta/Elev= 30
  4679.6  507.97  4701.3  507.06  4707.7  506.13  4750.9  503.77  4771.7  501.86
  4800.5  500.14  4814.9  499.76  4907.8  494.67  4928.6  494.22  4936.1  493.36
  4940.8  492.45  4943.0  492.03  4963.8  493.39  4975.7  493.28  4978.2  493.20
  4989.6  484.37  4990.1  483.57  4995.1  483.57  4995.6  484.37  4996.6  485.11
  5007.0  484.87  5013.4  489.09  5021.4  487.66  5027.8  489.69  5047.4  492.45
  5063.8  494.62  5091.8  496.63  5149.5  502.86  5205.5  507.64  5320.0  514.39
#Mann=5,-1,0
  4679.6    0.05       0  4936.1    0.12       0  4975.7    0.05       0
  4989.6    0.03       0  4995.6    0.05       0
Bank Sta=4940.8,5047.4
Exp/Cntr=0.3,0.1

Type RM Length L Ch R = 1,3930,269,269,269
BEGIN DESCRIPTION:
UNT 028 in Running Cr Watershed 7.0
END DESCRIPTION:
XS GIS Cut Line= 3
      2867625.00      7080925.03      2867625.00      7080425.00
      2867575.00      7079975.00
#Sta/Elev= 30
  4498.2  504.92  4528.2  502.93  4588.2  501.46  4618.2  500.03  4648.2  498.34
  4718.2  493.01  4858.2  491.44  4884.3  491.59  4892.0  491.36  4918.2  489.05
  4948.2  487.68  4978.2  487.40  4988.2  485.33  4992.6  481.63  4993.1  480.83
  4998.3  480.83  4998.8  481.63  5000.8  481.63  5018.4  488.01  5030.7  491.36
  5038.5  493.59  5077.1  493.81  5139.1  495.13  5169.3  496.70  5239.7  501.47
  5310.1  508.35  5360.5  515.58  5373.7  516.61  5410.8  518.65  5451.0  520.03
#Mann=6,-1,0
  4498.2    0.05       0  4884.3    0.12       0  4992.6    0.07       0
  4998.8    0.12       0  5077.1    0.16       0  5373.7    0.05       0
Bank Sta=4892,5030.7
Exp/Cntr=0.3,0.1

Type RM Length L Ch R = 1,3661,122,122,122
BEGIN DESCRIPTION:
Mapping XS 48d79bfb
END DESCRIPTION:
XS GIS Cut Line= 3
      2867879.20      7081078.44      2867879.20      7080388.29
      2867890.00      7079679.82
#Sta/Elev= 30
  4391.5  507.36  4524.9  504.17  4564.9  501.63  4594.9  501.61  4754.9  493.19
  4842.9  491.85  4894.9  490.87  4944.9  491.43  4967.4  488.50  4984.9  485.67
  4991.8  481.46  4992.3  480.66  4997.5  480.66  4998.0  481.46  5014.9  487.24
  5026.9  488.50  5054.9  491.04  5074.9  490.95  5132.1  494.47  5137.1  493.43
  5234.1  501.23  5331.9  505.75  5465.0  510.14  5495.0  509.07  5527.5  510.79
  5595.0  511.75  5705.0  516.43  5735.0  518.70  5765.0  519.35  5790.2  518.55
#Mann=7,-1,0
  4391.5    0.05       0  4842.9    0.08       0  4991.8    0.07       0
  4998.0    0.08       0  5234.1    0.05       0  5331.9    0.08       0
  5527.5    0.05       0
Bank Sta=4967.4,5026.9
Exp/Cntr=0.3,0.1

Type RM Length L Ch R = 1,3539,704,704,704
BEGIN DESCRIPTION:
UNT 028 in Running Cr Watershed 6.0
END DESCRIPTION:
XS GIS Cut Line= 3
      2868000.73      7081067.50      2868000.73      7080590.11
      2868002.90      7079624.41
#Sta/Elev= 30
  4398.4  507.68  4444.7  506.54  4490.9  505.18  4600.9  499.19  4660.9  497.39
  4720.9  493.97  4836.0  491.71  4910.9  490.63  4922.1  488.70  4930.9  485.67
  4940.9  484.64  4954.0  484.84  4970.9  485.96  4987.7  478.47  4988.2  477.67
  4993.6  477.67  4994.1  478.47  5011.9  482.84  5040.2  488.70  5050.9  490.96
  5090.9  490.21  5129.4  491.38  5227.2  493.77  5300.9  495.60  5370.9  498.63
  5512.6  503.00  5618.5  507.40  5716.3  513.73  5760.9  515.86  5841.5  518.15
#Mann=12,-1,0
  4398.4    0.08       0  4444.7    0.05       0  4836.0    0.12       0
  4954.0    0.07       0  4987.7    0.07       0  4994.1    0.07       0
  5011.9    0.12       0  5129.4    0.07       0  5227.2    0.05       0
  5512.6    0.16       0  5618.5    0.05       0  5716.3    0.08       0
Bank Sta=4922.1,5040.2
Exp/Cntr=0.3,0.1

Type RM Length L Ch R = 1,2835,563,563,563
BEGIN DESCRIPTION:
UNT 028 in Running Cr Watershed 5.0
END DESCRIPTION:
XS GIS Cut Line= 3
      2868724.98      7080524.97      2868475.00      7080125.00
      2868025.03      7079625.03
#Sta/Elev= 30
  4493.4  506.59  4689.7  499.11  4768.7  500.49  4815.8  499.61  4863.1  498.08
  4968.4  489.11  4975.8  486.97  4986.4  482.44  4989.9  477.20  4990.4  476.40
  4995.8  476.40  4996.3  477.20  4997.3  477.29  5007.3  479.00  5014.8  482.10
  5021.5  481.93  5029.0  484.22  5035.7  481.41  5043.2  483.70  5049.9  482.74
  5057.4  485.71  5062.5  484.30  5064.1  483.86  5070.7  486.97  5269.6  489.83
  5453.5  507.27  5461.0  507.15  5465.8  508.86  5574.7  515.77  5637.7  518.91
#Mann=8,-1,0
  4493.4    0.05       0  4815.8    0.16       0  4989.9    0.07       0
  4996.3    0.16       0  4997.3    0.12       0  5062.5    0.16       0
  5465.8    0.05       0  5574.7    0.08       0
Bank Sta=4975.8,5070.7
Exp/Cntr=0.3,0.1

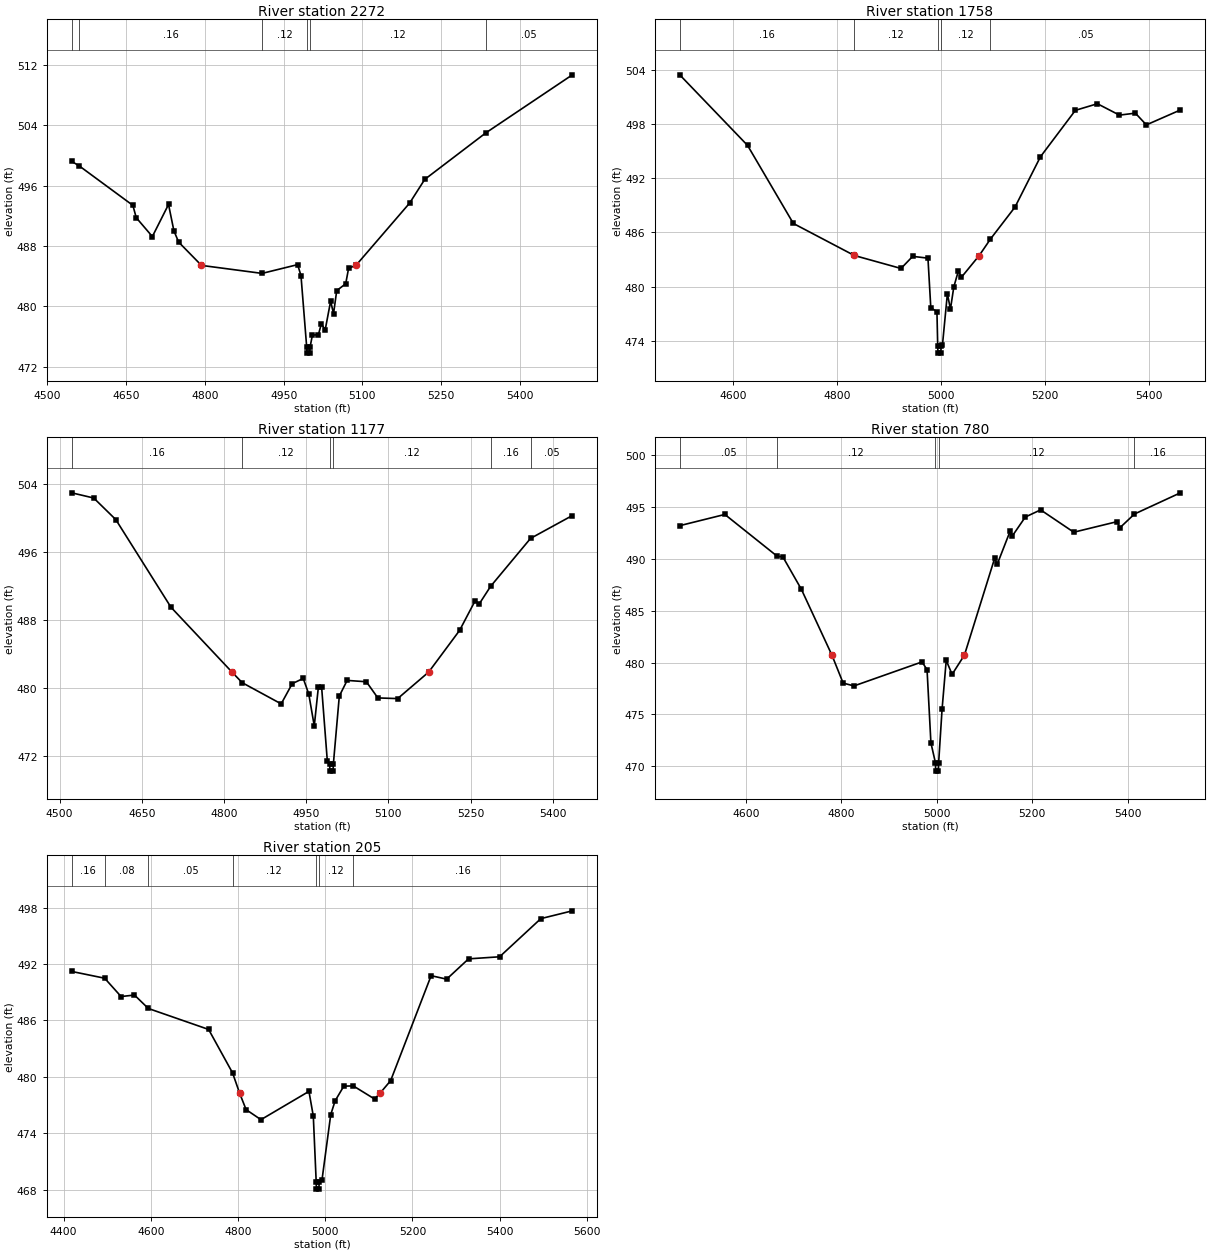
Type RM Length L Ch R = 1,2272,514,514,514
BEGIN DESCRIPTION:
UNT 028 in Running Cr Watershed 4.0
END DESCRIPTION:
XS GIS Cut Line= 3
      2868874.99      7080174.97      2868775.00      7079725.00
      2868324.99      7079524.99
#Sta/Elev= 30
  4546.4  499.21  4560.5  498.63  4662.9  493.39  4669.3  491.76  4700.0  489.26
  4730.8  493.51  4741.0  490.03  4750.0  488.53  4793.5  485.44  4908.9  484.38
  4976.6  485.54  4983.0  484.10  4993.9  474.62  4994.4  473.82  4999.8  473.82
  5000.3  474.62  5004.8  476.21  5016.2  476.26  5021.7  477.68  5029.2  476.93
  5039.5  480.71  5045.0  479.04  5051.1  482.10  5068.2  483.01  5073.7  485.06
  5087.7  485.44  5190.0  493.70  5218.7  496.83  5335.0  502.99  5499.8  510.68
#Mann=6,-1,0
  4546.4    0.12       0  4560.5    0.16       0  4908.9    0.12       0
  4993.9    0.07       0  5000.3    0.12       0  5335.0    0.05       0
Bank Sta=4793.5,5087.7
Exp/Cntr=0.3,0.1

Type RM Length L Ch R = 1,1758,581,581,581
BEGIN DESCRIPTION:
UNT 028 in Running Cr Watershed 3.0
END DESCRIPTION:
XS GIS Cut Line= 3
      2869424.98      7080024.96      2869225.00      7079575.00
      2868825.00      7079325.00
#Sta/Elev= 30
  4497.0  503.44  4627.6  495.63  4715.8  486.99  4832.7  483.46  4832.9  483.45
  4923.1  482.01  4945.6  483.35  4975.0  483.15  4980.5  477.65  4992.3  477.24
  4993.8  473.44  4994.3  472.64  4999.8  472.64  5000.3  473.44  5003.0  473.58
  5012.4  479.21  5018.3  477.51  5024.8  479.97  5033.6  481.74  5039.5  481.04
  5073.7  483.44  5095.3  485.26  5142.7  488.81  5191.6  494.37  5258.9  499.51
  5301.3  500.24  5343.8  498.98  5374.4  499.20  5395.6  497.90  5461.1  499.55
#Mann=5,-1,0
  4497.0    0.16       0  4832.7    0.12       0  4993.8    0.07       0
  5000.3    0.12       0  5095.3    0.05       0
Bank Sta=4832.9,5073.7
Exp/Cntr=0.3,0.1

Type RM Length L Ch R = 1,1177,397,397,397
BEGIN DESCRIPTION:
UNT 028 in Running Cr Watershed 2.0
END DESCRIPTION:
XS GIS Cut Line= 3
      2869625.00      7079624.99      2869575.00      7079175.00
      2869275.02      7078825.03
#Sta/Elev= 30
  4522.1  502.92  4562.3  502.31  4602.6  499.77  4703.2  489.47  4814.6  481.84
  4833.3  480.59  4904.4  478.10  4924.6  480.48  4944.7  481.09  4954.7  479.27
  4964.8  475.51  4972.3  480.08  4978.2  480.08  4988.6  471.39  4992.9  470.99
  4993.4  470.19  4999.1  470.19  4999.6  470.99  5010.5  479.02  5024.8  480.86
  5059.9  480.70  5080.8  478.80  5117.0  478.72  5173.6  481.84  5230.0  486.74
  5258.6  490.25  5265.2  489.79  5286.6  491.92  5359.5  497.56  5435.8  500.25
#Mann=6,-1,0
  4522.1    0.16       0  4833.3    0.12       0  4992.9    0.07       0
  4999.6    0.12       0  5286.6    0.16       0  5359.5    0.05       0
Bank Sta=4814.6,5173.6
Exp/Cntr=0.3,0.1

Type RM Length L Ch R = 1,780,575,575,575
BEGIN DESCRIPTION:
Mapping XS a2fcf8b0
END DESCRIPTION:
XS GIS Cut Line= 3
      2869936.05      7079509.35      2869901.33      7079051.05
      2869721.02      7078489.30
#Sta/Elev= 30
  4461.1  493.17  4555.7  494.25  4665.6  490.22  4677.3  490.17  4716.2  487.04
  4780.1  480.72  4803.7  478.02  4826.5  477.75  4969.1  480.06  4979.6  479.31
  4987.7  472.27  4997.2  470.35  4997.7  469.55  5003.4  469.55  5003.9  470.35
  5011.1  475.51  5019.8  480.21  5032.1  478.86  5058.0  480.72  5121.4  490.04
  5126.6  489.44  5153.5  492.61  5158.7  492.20  5185.6  494.00  5217.7  494.69
  5287.2  492.54  5378.3  493.56  5383.5  492.95  5414.4  494.29  5510.7  496.33
#Mann=5,-1,0
  4461.1    0.05       0  4665.6    0.12       0  4997.2    0.07       0
  5003.9    0.12       0  5414.4    0.16       0
Bank Sta=4780.1,5058
Exp/Cntr=0.3,0.1

Type RM Length L Ch R = 1,205,0,0,0
BEGIN DESCRIPTION:
UNT 028 in Running Cr Watershed 1.0
END DESCRIPTION:
XS GIS Cut Line= 3
      2870255.85      7079388.94      2870278.42      7078750.01
      2869981.24      7078336.44
#Sta/Elev= 30
  4418.4  491.21  4494.0  490.49  4531.7  488.54  4562.4  488.70  4594.2  487.27
  4732.5  485.04  4787.4  480.42  4803.8  478.24  4818.5  476.51  4852.6  475.44
  4962.7  478.45  4972.7  475.82  4979.3  468.85  4979.8  468.05  4985.6  468.05
  4986.1  468.85  4992.7  469.05  5012.7  475.98  5022.7  477.44  5042.7  479.01
  5064.5  479.03  5113.2  477.64  5125.5  478.24  5150.1  479.59  5243.0  490.76
  5278.6  490.39  5328.9  492.55  5400.1  492.77  5494.7  496.83  5567.0  497.66
#Mann=7,-1,0
  4418.4    0.16       0  4494.0    0.08       0  4594.2    0.05       0
  4787.4    0.12       0  4979.3    0.07       0  4986.1    0.12       0
  5064.5    0.16       0
Bank Sta=4803.8,5125.5
Exp/Cntr=0.3,0.1

Chan Stop Cuts=-1