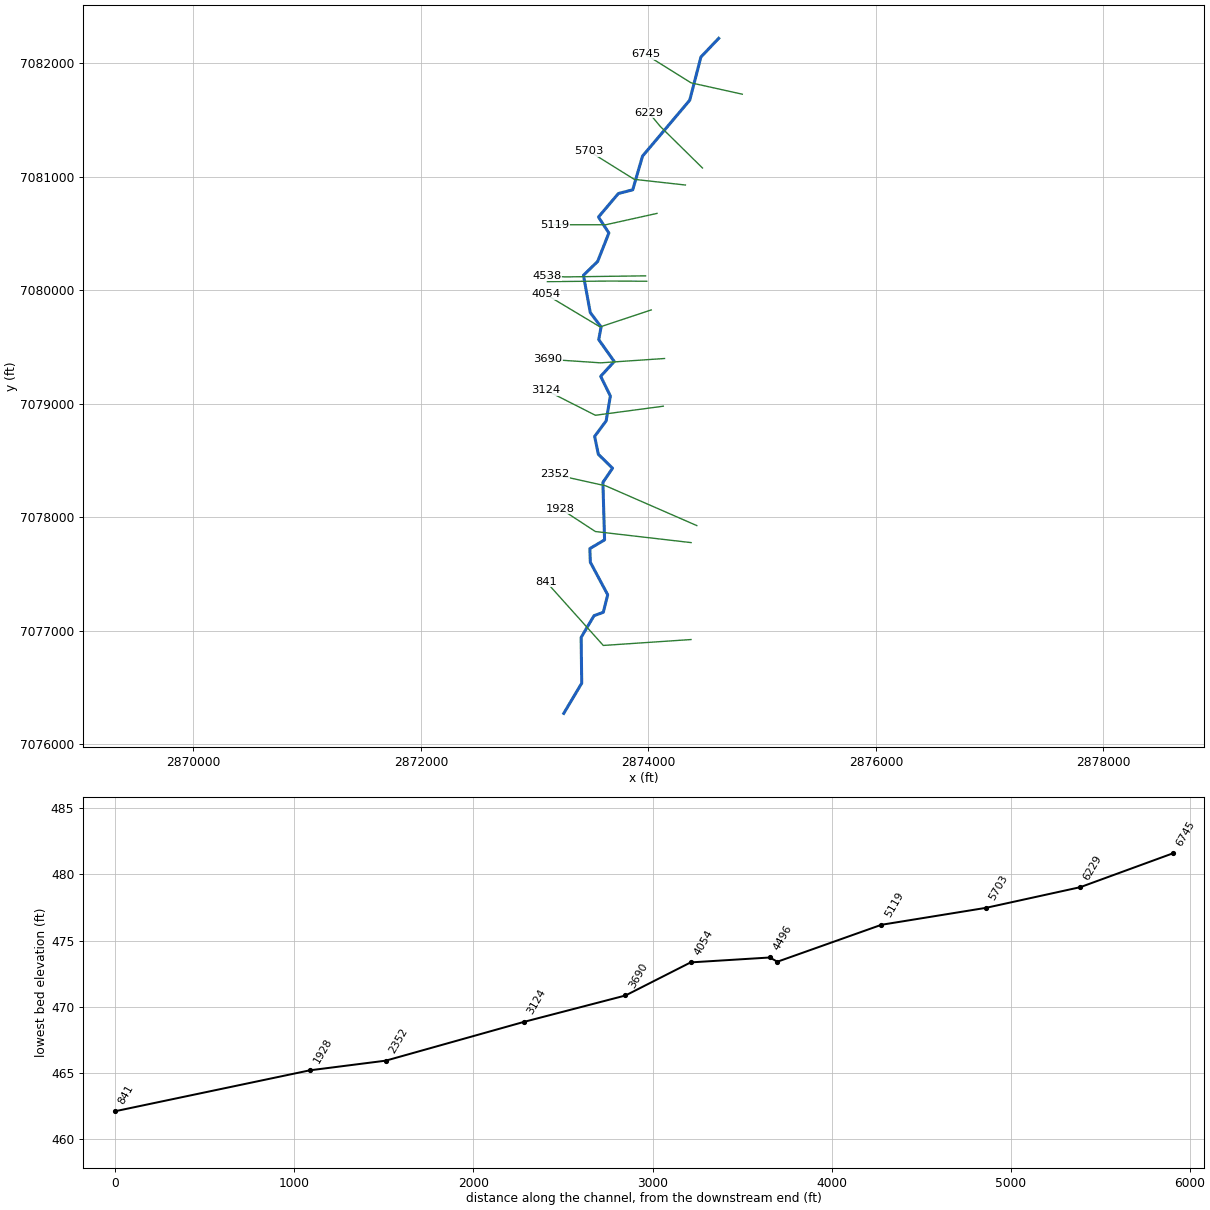
--- UNT 029 in Running Cr Watershed.prj (project) ---

Proj Title=UNT 029 in Running Cr Watershed Base Level Engineering
Current Plan=p01
Default Exp/Contr=0.3,0.1
English Units
Geom File=g01
Flow File=f01
Plan File=p01
BEGIN DESCRIPTION:
UNT 029 in Running Cr Watershed
END DESCRIPTION:

--- UNT 029 in Running Cr Watershed.p01 (plan) ---

Plan Title=Multiple Run
Short Identifier=Multiple
Geom File=g01
Flow File=f01
Subcritical Flow
K Sum by GR= 0
Std Step Tol= 0.01
Critical Tol= 0.01
Num of Std Step Trials= 20
Max Error Tol= 0.3
Flow Tol Ratio= 0.001
Split Flow NTrial= 30
Split Flow Tol= 0.02
Split Flow Ratio= 0.02
Log Output Level= 0
Friction Slope Method= 1
Unsteady Friction Slope Method= 2
Unsteady Bridges Friction Slope Method= 1
Parabolic Critical Depth
Global Vel Dist=  1 , 1 , 1
Global Log Level= 0
CheckData=True
Encroach Param= -1, 0, 0, 0
BEGIN DESCRIPTION:
Multiple Run
END DESCRIPTION:

--- UNT 029 in Running Cr Watershed.f01 (steady flow) ---

Flow Title=Multiple
Number of Profiles=7
Profile Names=10-year,25-year,50-year,1pct_min,100-year,1pct_plu,500-year
River Rch & RM= UNT 029 in Runni,Reach-1,6745
    1114    1520    1854    1120    2234    4457    3235
Boundary for River Rch & Prof#=UNT 029 in Runni,Reach-1,1
Up Type=0
Dn Type=3
Dn Slope=0.005
Boundary for River Rch & Prof#=UNT 029 in Runni,Reach-1,2
Up Type=0
Dn Type=3
Dn Slope=0.005
Boundary for River Rch & Prof#=UNT 029 in Runni,Reach-1,3
Up Type=0
Dn Type=3
Dn Slope=0.005
Boundary for River Rch & Prof#=UNT 029 in Runni,Reach-1,4
Up Type=0
Dn Type=3
Dn Slope=0.005
Boundary for River Rch & Prof#=UNT 029 in Runni,Reach-1,5
Up Type=0
Dn Type=3
Dn Slope=0.005
Boundary for River Rch & Prof#=UNT 029 in Runni,Reach-1,6
Up Type=0
Dn Type=3
Dn Slope=0.005
Boundary for River Rch & Prof#=UNT 029 in Runni,Reach-1,7
Up Type=0
Dn Type=3
Dn Slope=0.005

--- UNT 029 in Running Cr Watershed.g01 (geometry) ---

Geom Title=Existing Conditions

River Reach=UNT 029 in Runni,Reach-1
Reach XY= 30
      2874617.50      7082217.18      2874461.20      7082052.60
      2874362.88      7081672.24      2873948.07      7081179.68
      2873861.77      7080882.76      2873735.54      7080850.12
      2873560.69      7080642.99      2873652.09      7080502.30
      2873553.32      7080251.58      2873428.63      7080129.73
      2873488.48      7079801.90      2873583.69      7079674.73
      2873562.92      7079563.20      2873699.17      7079370.32
      2873580.13      7079239.88      2873665.34      7079066.24
      2873628.06      7078847.21      2873526.96      7078710.40
      2873559.64      7078552.97      2873684.50      7078430.41
      2873599.70      7078305.78      2873614.28      7077799.14
      2873485.03      7077722.28      2873489.07      7077602.16
      2873641.82      7077315.77      2873603.20      7077161.22
      2873521.76      7077131.58      2873408.25      7076939.55
      2873413.50      7076536.71      2873255.59      7076270.71

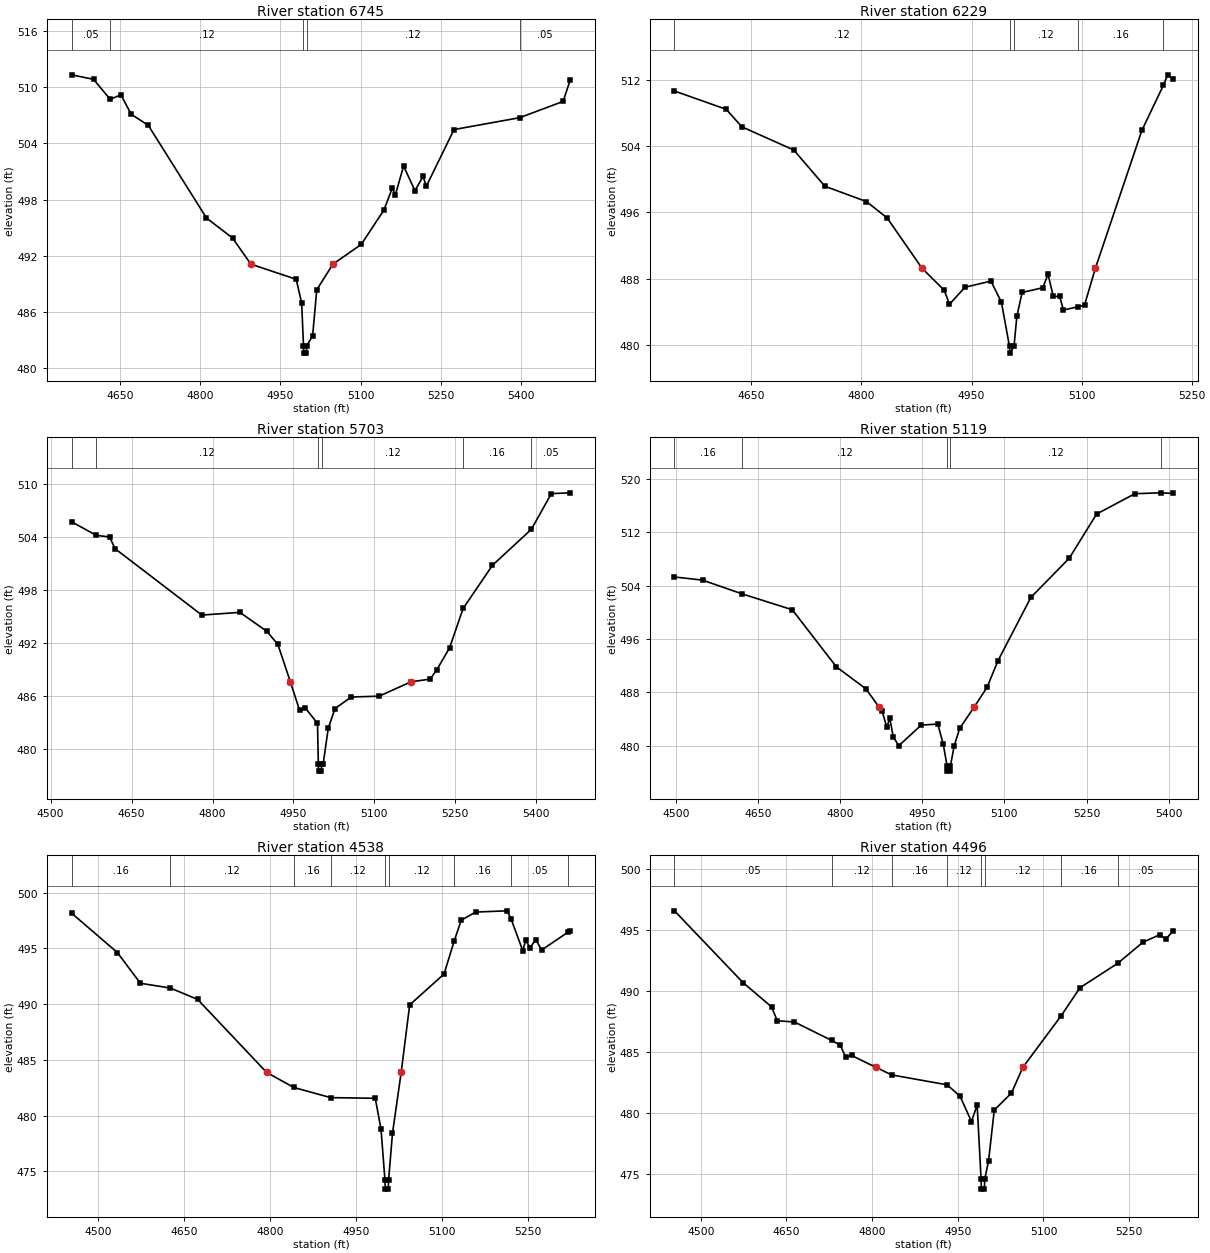
Type RM Length L Ch R = 1,6745,516,516,516
BEGIN DESCRIPTION:
UNT 029 in Running Cr Watershed 11.0
END DESCRIPTION:
XS GIS Cut Line= 3
      2874824.99      7081725.00      2874375.00      7081825.00
      2873974.97      7082075.02
#Sta/Elev= 30
  4559.5  511.33  4600.5  510.85  4631.7  508.71  4651.7  509.20  4670.9  507.12
  4702.9  505.93  4811.7  496.03  4860.4  493.89  4894.7  491.10  4979.5  489.48
  4989.7  486.94  4993.1  482.39  4993.6  481.59  4998.6  481.59  4999.1  482.39
  5010.2  483.43  5017.9  488.36  5048.2  491.10  5101.2  493.21  5143.7  496.90
  5159.0  499.20  5164.9  498.50  5180.3  501.58  5201.5  498.96  5216.8  500.47
  5222.7  499.41  5274.6  505.48  5397.4  506.75  5478.6  508.49  5492.2  510.83
#Mann=5,-1,0
  4559.5    0.05       0  4631.7    0.12       0  4993.1    0.07       0
  4999.1    0.12       0  5397.4    0.05       0
Bank Sta=4894.7,5048.2
Exp/Cntr=0.3,0.1

Type RM Length L Ch R = 1,6229,526,526,526
BEGIN DESCRIPTION:
UNT 029 in Running Cr Watershed 10.0
END DESCRIPTION:
XS GIS Cut Line= 3
      2874474.97      7081075.03      2874103.07      7081441.96
      2874003.25      7081563.47
#Sta/Elev= 30
  4545.1  510.63  4615.7  508.42  4637.0  506.31  4707.7  503.52  4750.1  499.15
  4806.7  497.31  4835.0  495.33  4882.3  489.29  4912.7  486.62  4919.9  484.93
  4941.0  486.98  4976.4  487.72  4990.6  485.20  5001.7  479.84  5002.2  479.04
  5007.8  479.84  5011.7  483.47  5018.9  486.35  5047.1  486.92  5054.2  488.55
  5061.3  485.89  5070.0  485.87  5075.2  484.24  5095.5  484.63  5103.9  484.82
  5118.8  489.29  5182.1  505.89  5211.5  511.34  5217.2  512.58  5224.8  512.13
#Mann=5,-1,0
  4545.1    0.12       0  5001.7    0.07       0  5007.8    0.12       0
  5095.5    0.16       0  5211.5    0.05       0
Bank Sta=4882.3,5118.8
Exp/Cntr=0.3,0.1

Type RM Length L Ch R = 1,5703,584,584,584
BEGIN DESCRIPTION:
UNT 029 in Running Cr Watershed 9.0
END DESCRIPTION:
XS GIS Cut Line= 3
      2874324.96      7080925.00      2873875.00      7080975.00
      2873475.03      7081224.98
#Sta/Elev= 30
  4538.8  505.74  4584.6  504.21  4609.2  504.03  4619.3  502.70  4780.2  495.17
  4850.7  495.48  4901.0  493.31  4921.1  491.84  4944.2  487.61  4961.3  484.37
  4971.4  484.69  4994.5  482.89  4996.1  478.28  4996.6  477.48  5001.7  477.48
  5002.2  478.28  5005.1  478.34  5014.5  482.36  5026.9  484.57  5057.0  485.88
  5108.9  485.98  5168.0  487.61  5203.2  487.91  5215.6  488.97  5239.2  491.44
  5264.4  495.92  5318.8  500.82  5391.0  504.90  5427.9  508.94  5463.2  509.03
#Mann=6,-1,0
  4538.8    0.16       0  4584.6    0.12       0  4996.1    0.07       0
  5002.2    0.12       0  5264.4    0.16       0  5391.0    0.05       0
Bank Sta=4944.2,5168
Exp/Cntr=0.3,0.1

Type RM Length L Ch R = 1,5119,581,581,581
BEGIN DESCRIPTION:
UNT 029 in Running Cr Watershed 8.0
END DESCRIPTION:
XS GIS Cut Line= 3
      2874075.04      7080675.01      2873625.00      7080575.00
      2873175.02      7080575.00
#Sta/Elev= 30
  4497.4  505.29  4548.7  504.82  4621.3  502.75  4712.6  500.38  4793.2  491.82
  4847.0  488.54  4871.2  485.79  4876.5  485.22  4885.4  482.76  4890.6  484.16
  4897.0  481.34  4907.2  480.01  4948.2  483.10  4978.4  483.25  4988.4  480.23
  4995.3  477.00  4995.8  476.20  5001.0  476.20  5001.5  477.00  5008.4  480.01
  5018.4  482.61  5044.8  485.79  5068.4  488.77  5088.4  492.76  5148.4  502.23
  5218.4  508.09  5268.4  514.72  5338.4  517.77  5385.9  517.90  5408.4  517.81
#Mann=5,-1,0
  4497.4    0.16       0  4621.3    0.12       0  4995.3    0.07       0
  5001.5    0.12       0  5385.9    0.05       0
Bank Sta=4871.2,5044.8
Exp/Cntr=0.3,0.1

Type RM Length L Ch R = 1,4538,42,42,42
BEGIN DESCRIPTION:
UNT 029 in Running Cr Watershed 7.0
END DESCRIPTION:
XS GIS Cut Line= 3
      2873974.98      7080125.00      2873269.74      7080115.57
      2873104.78      7080124.25
#Sta/Elev= 30
  4453.5  498.17  4533.5  494.63  4573.5  491.88  4626.0  491.45  4673.5  490.43
  4793.9  483.88  4841.4  482.53  4905.6  481.62  4983.5  481.56  4993.5  478.79
  5000.4  474.21  5000.9  473.41  5006.2  473.41  5006.7  474.21  5013.5  478.41
  5028.7  483.88  5043.5  489.94  5103.5  492.71  5121.2  495.67  5133.5  497.54
  5158.7  498.27  5213.6  498.38  5220.5  497.65  5240.9  494.80  5245.9  495.73
  5253.7  495.08  5263.7  495.80  5273.7  494.86  5319.8  496.46  5324.0  496.54
#Mann=9,-1,0
  4453.5    0.16       0  4626.0    0.12       0  4841.4    0.16       0
  4905.6    0.12       0  5000.4    0.07       0  5006.7    0.12       0
  5121.2    0.16       0  5220.5    0.05       0  5319.8    0.16       0
Bank Sta=4793.9,5028.7
Exp/Cntr=0.3,0.1

Type RM Length L Ch R = 1,4496,442,442,442
BEGIN DESCRIPTION:
Mapping XS 7e0474b4
END DESCRIPTION:
XS GIS Cut Line= 3
      2873985.03      7080077.37      2873667.31      7080079.11
      2873111.76      7080073.90
#Sta/Elev= 30
  4453.9  496.54  4573.9  490.66  4623.9  488.67  4633.9  487.53  4663.9  487.43
  4729.0  485.92  4743.9  485.54  4753.9  484.55  4763.9  484.69  4806.7  483.71
  4834.4  483.09  4931.2  482.28  4953.9  481.35  4973.9  479.27  4983.9  480.62
  4990.8  474.53  4991.3  473.73  4996.6  473.73  4997.1  474.53  5003.9  476.06
  5013.9  480.21  5044.0  481.61  5063.9  483.71  5130.7  487.92  5164.0  490.24
  5229.8  492.23  5274.0  493.96  5304.0  494.59  5314.0  494.20  5327.2  494.91
#Mann=8,-1,0
  4453.9    0.05       0  4729.0    0.12       0  4834.4    0.16       0
  4931.2    0.12       0  4990.8    0.07       0  4997.1    0.12       0
  5130.7    0.16       0  5229.8    0.05       0
Bank Sta=4806.7,5063.9
Exp/Cntr=0.3,0.1

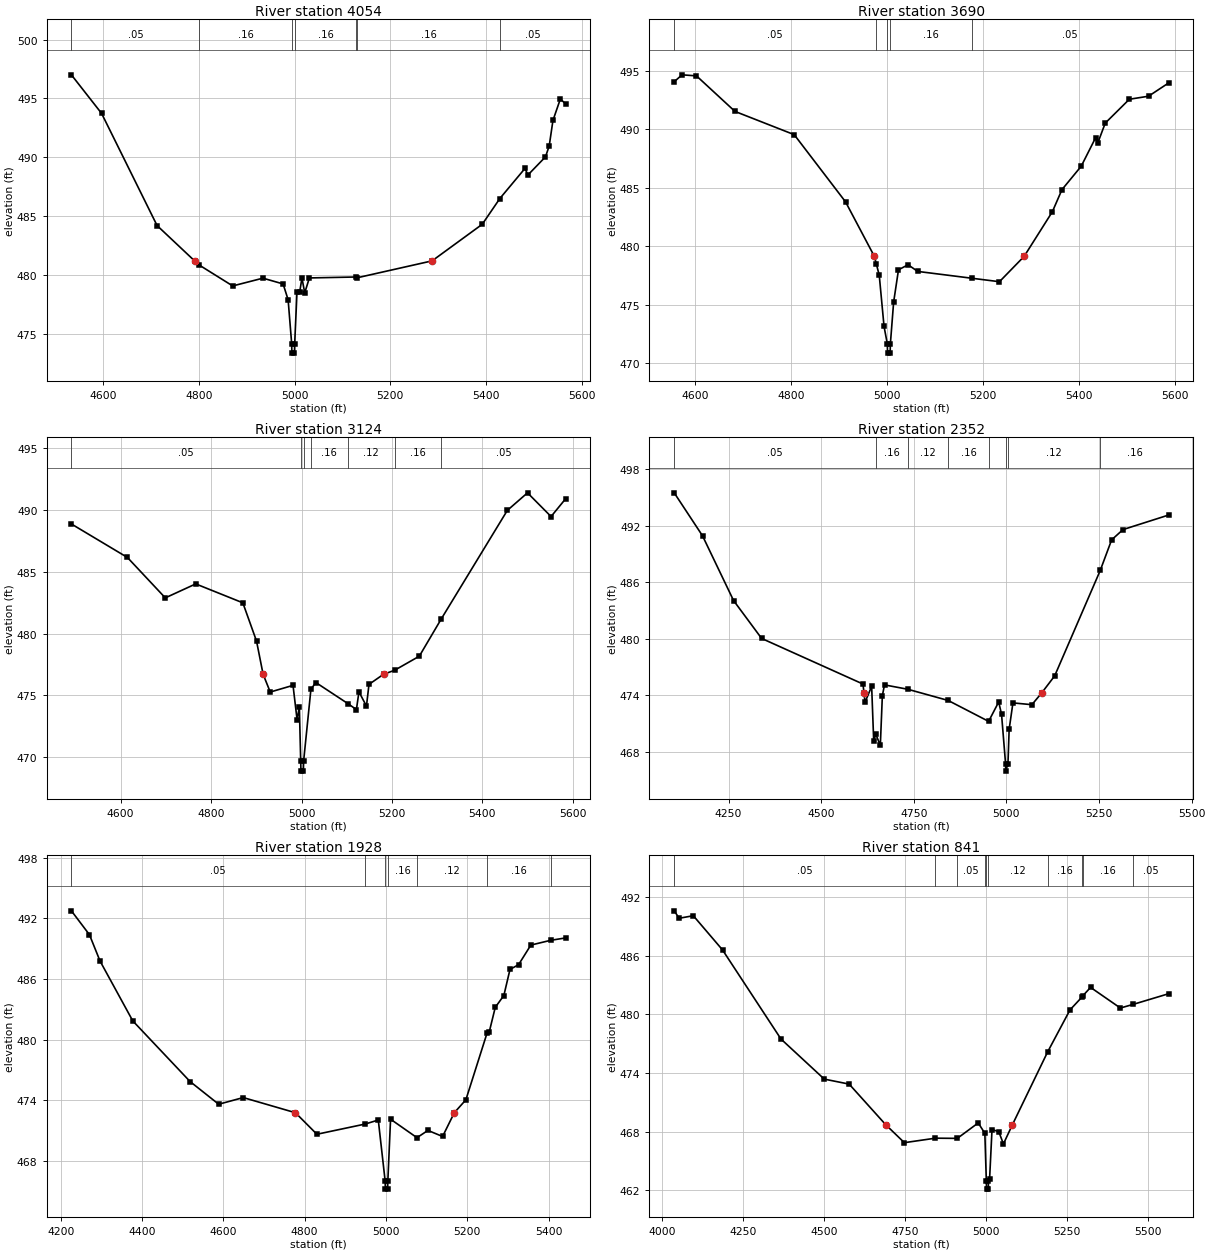
Type RM Length L Ch R = 1,4054,364,364,364
BEGIN DESCRIPTION:
UNT 029 in Running Cr Watershed 6.0
END DESCRIPTION:
XS GIS Cut Line= 3
      2874024.96      7079824.99      2873575.00      7079675.00
      2873095.40      7079962.76
#Sta/Elev= 30
  4533.3  497.01  4596.5  493.73  4712.5  484.20  4790.9  481.20  4800.8  480.84
  4870.6  479.07  4933.8  479.73  4976.0  479.24  4986.5  477.89  4993.9  474.16
  4994.4  473.36  4999.7  473.36  5000.2  474.16  5005.0  478.52  5010.5  478.52
  5015.4  479.74  5021.2  478.48  5030.9  479.75  5128.8  479.83  5131.4  479.77
  5287.5  481.20  5392.4  484.31  5429.2  486.50  5481.8  489.06  5487.7  488.49
  5524.6  490.04  5532.4  490.97  5540.2  493.13  5555.7  494.96  5566.9  494.53
#Mann=7,-1,0
  4533.3    0.05       0  4800.8    0.16       0  4993.9    0.07       0
  5000.2    0.16       0  5128.8    0.05       0  5131.4    0.16       0
  5429.2    0.05       0
Bank Sta=4790.9,5287.5
Exp/Cntr=0.3,0.1

Type RM Length L Ch R = 1,3690,566,566,566
BEGIN DESCRIPTION:
UNT 029 in Running Cr Watershed 5.0
END DESCRIPTION:
XS GIS Cut Line= 3
      2874141.29      7079396.82      2873578.76      7079358.62
      2873113.44      7079389.88
#Sta/Elev= 30
  4556.5  494.08  4572.8  494.67  4602.9  494.58  4683.1  491.54  4806.6  489.55
  4913.6  483.80  4973.6  479.14  4977.8  478.48  4983.8  477.52  4993.8  473.14
  5000.6  471.66  5001.1  470.86  5006.5  470.86  5007.0  471.66  5013.8  475.23
  5023.9  477.99  5043.9  478.42  5064.0  477.85  5176.2  477.27  5234.3  476.97
  5285.8  479.14  5344.6  482.96  5364.6  484.85  5404.7  486.85  5434.6  489.28
  5439.6  488.88  5454.8  490.54  5505.0  492.58  5545.0  492.84  5586.7  493.97
#Mann=5,-1,0
  4556.5    0.05       0  4977.8    0.16       0  5000.6    0.07       0
  5007.0    0.16       0  5176.2    0.05       0
Bank Sta=4973.6,5285.8
Exp/Cntr=0.3,0.1

Type RM Length L Ch R = 1,3124,772,772,772
BEGIN DESCRIPTION:
UNT 029 in Running Cr Watershed 4.0
END DESCRIPTION:
XS GIS Cut Line= 3
      2874130.89      7078976.68      2873533.62      7078896.82
      2873096.11      7079119.05
#Sta/Elev= 30
  4491.0  488.87  4614.9  486.16  4698.7  482.89  4766.0  484.02  4870.2  482.49
  4900.5  479.39  4915.0  476.71  4930.8  475.27  4981.2  475.81  4990.2  473.02
  4995.2  474.08  4998.2  469.67  4998.7  468.87  5004.1  468.87  5004.6  469.67
  5020.8  475.50  5031.7  476.04  5102.3  474.34  5121.4  473.85  5127.0  475.29
  5143.6  474.13  5149.2  475.89  5181.5  476.71  5205.8  477.03  5260.5  478.17
  5308.8  481.17  5455.2  489.97  5499.8  491.39  5551.9  489.47  5584.3  490.92
#Mann=7,-1,0
  4491.0    0.05       0  4998.2    0.03       0  5004.6    0.05       0
  5020.8    0.16       0  5102.3    0.12       0  5205.8    0.16       0
  5308.8    0.05       0
Bank Sta=4915,5181.5
Exp/Cntr=0.3,0.1

Type RM Length L Ch R = 1,2352,424,424,424
BEGIN DESCRIPTION:
UNT 029 in Running Cr Watershed 3.0
END DESCRIPTION:
XS GIS Cut Line= 3
      2874425.03      7077924.99      2873625.00      7078275.00
      2873175.02      7078375.00
#Sta/Elev= 30
  4103.4  495.47  4179.8  490.91  4263.6  484.04  4339.3  480.02  4612.9  475.18
  4615.5  474.27  4618.4  473.24  4636.3  474.94  4641.8  469.15  4647.6  469.84
  4659.7  468.67  4665.2  473.96  4671.0  475.09  4733.5  474.63  4842.7  473.44
  4952.0  471.22  4979.2  473.28  4986.9  471.96  4997.7  466.74  4998.2  465.94
  5004.2  466.74  5007.4  470.38  5017.6  473.18  5068.8  472.99  5095.9  474.27
  5130.3  476.05  5253.2  487.23  5284.0  490.48  5314.7  491.57  5437.6  493.11
#Mann=8,-1,0
  4103.4    0.05       0  4647.6    0.16       0  4733.5    0.12       0
  4842.7    0.16       0  4952.0    0.12       0  4997.7    0.07       0
  5004.2    0.12       0  5253.2    0.16       0
Bank Sta=4615.5,5095.9
Exp/Cntr=0.3,0.1

Type RM Length L Ch R = 1,1928,1087,1087,1087
BEGIN DESCRIPTION:
UNT 029 in Running Cr Watershed 2.0
END DESCRIPTION:
XS GIS Cut Line= 3
      2874375.00      7077775.00      2873533.62      7077872.51
      2873225.02      7078074.98
#Sta/Elev= 30
  4226.1  492.75  4270.5  490.39  4296.6  487.78  4377.1  481.86  4518.0  475.86
  4588.5  473.61  4648.9  474.27  4777.3  472.77  4830.1  470.64  4948.8  471.65
  4981.1  472.05  4998.0  466.01  4998.5  465.21  5004.1  465.21  5004.6  466.01
  5011.3  472.13  5076.3  470.30  5103.2  471.02  5139.3  470.42  5168.1  472.77
  5196.6  474.05  5248.5  480.63  5253.8  480.72  5268.9  483.20  5290.0  484.37
  5305.1  486.95  5326.2  487.42  5356.4  489.36  5404.9  489.83  5442.2  490.07
#Mann=7,-1,0
  4226.1    0.05       0  4948.8    0.16       0  4998.0    0.07       0
  5004.6    0.16       0  5076.3    0.12       0  5248.5    0.16       0
  5404.9    0.05       0
Bank Sta=4777.3,5168.1
Exp/Cntr=0.3,0.1

Type RM Length L Ch R = 1,841,0,0,0
BEGIN DESCRIPTION:
UNT 029 in Running Cr Watershed 1.0
END DESCRIPTION:
XS GIS Cut Line= 3
      2874373.88      7076921.12      2873603.07      7076869.04
      2873100.52      7077430.51
#Sta/Elev= 30
  4037.1  490.58  4052.4  489.82  4096.1  490.08  4186.3  486.58  4366.7  477.47
  4500.4  473.37  4577.2  472.86  4690.3  468.70  4747.6  466.87  4843.6  467.33
  4911.1  467.31  4975.6  468.89  4996.1  467.83  5000.7  462.92  5001.2  462.12
  5006.8  462.12  5007.3  462.92  5010.7  463.13  5018.2  468.21  5039.1  468.00
  5053.4  466.74  5081.1  468.70  5189.9  476.15  5259.0  480.45  5295.6  481.75
  5299.4  481.92  5322.5  482.75  5414.5  480.64  5453.6  481.01  5563.2  482.10
#Mann=10,-1,0
  4037.1    0.05       0  4843.6    0.16       0  4911.1    0.05       0
  4996.1    0.12       0  5000.7    0.07       0  5007.3    0.12       0
  5189.9    0.16       0  5295.6    0.12       0  5299.4    0.16       0
  5453.6    0.05       0
Bank Sta=4690.3,5081.1
Exp/Cntr=0.3,0.1

Chan Stop Cuts=-1