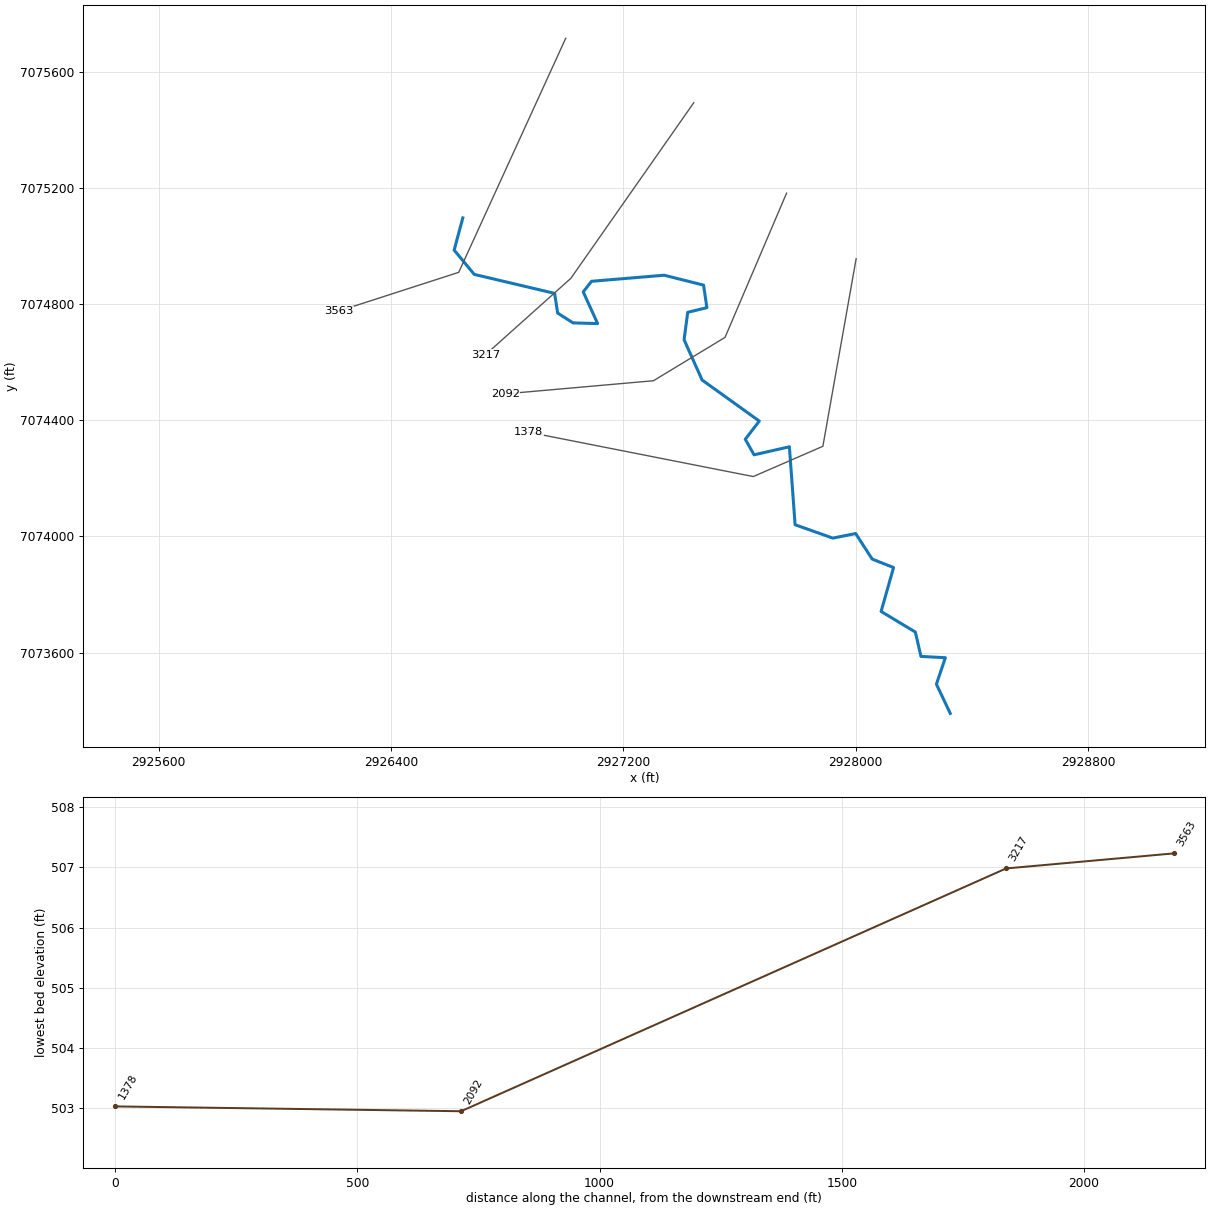
--- UNT 030 in Running Cr Watershed.prj (project) ---

Proj Title=UNT 030 in Running Cr Watershed Base Level Engineering
Current Plan=p01
Default Exp/Contr=0.3,0.1
English Units
Geom File=g01
Flow File=f01
Plan File=p01
BEGIN DESCRIPTION:
UNT 030 in Running Cr Watershed
END DESCRIPTION:

--- UNT 030 in Running Cr Watershed.p01 (plan) ---

Plan Title=Multiple Run
Short Identifier=Multiple
Geom File=g01
Flow File=f01
Subcritical Flow
K Sum by GR= 0
Std Step Tol= 0.01
Critical Tol= 0.01
Num of Std Step Trials= 20
Max Error Tol= 0.3
Flow Tol Ratio= 0.001
Split Flow NTrial= 30
Split Flow Tol= 0.02
Split Flow Ratio= 0.02
Log Output Level= 0
Friction Slope Method= 1
Unsteady Friction Slope Method= 2
Unsteady Bridges Friction Slope Method= 1
Parabolic Critical Depth
Global Vel Dist=  1 , 1 , 1
Global Log Level= 0
CheckData=True
Encroach Param= -1, 0, 0, 0
BEGIN DESCRIPTION:
Multiple Run
END DESCRIPTION:

--- UNT 030 in Running Cr Watershed.f01 (steady flow) ---

Flow Title=Multiple
Number of Profiles=7
Profile Names=10-year,25-year,50-year,1pct_min,100-year,1pct_plu,500-year
River Rch & RM= UNT 030 in Runni,Reach-1,3563
     814    1094    1321     791    1579    3150    2248
River Rch & RM= UNT 030 in Runni,Reach-1,2092
     826    1110    1341     802    1601    3194    2276
Boundary for River Rch & Prof#=UNT 030 in Runni,Reach-1,1
Up Type=0
Dn Type=3
Dn Slope=0.005
Boundary for River Rch & Prof#=UNT 030 in Runni,Reach-1,2
Up Type=0
Dn Type=3
Dn Slope=0.005
Boundary for River Rch & Prof#=UNT 030 in Runni,Reach-1,3
Up Type=0
Dn Type=3
Dn Slope=0.005
Boundary for River Rch & Prof#=UNT 030 in Runni,Reach-1,4
Up Type=0
Dn Type=3
Dn Slope=0.005
Boundary for River Rch & Prof#=UNT 030 in Runni,Reach-1,5
Up Type=0
Dn Type=3
Dn Slope=0.005
Boundary for River Rch & Prof#=UNT 030 in Runni,Reach-1,6
Up Type=0
Dn Type=3
Dn Slope=0.005
Boundary for River Rch & Prof#=UNT 030 in Runni,Reach-1,7
Up Type=0
Dn Type=3
Dn Slope=0.005

--- UNT 030 in Running Cr Watershed.g01 (geometry) ---

Geom Title=Existing Conditions

River Reach=UNT 030 in Runni,Reach-1
Reach XY= 30
      2926647.46      7075096.52      2926617.72      7074985.80
      2926686.86      7074902.01      2926963.51      7074836.69
      2926974.05      7074768.90      2927026.91      7074735.04
      2927111.48      7074732.74      2927062.11      7074841.66
      2927090.67      7074878.28      2927340.64      7074899.14
      2927476.33      7074865.07      2927487.85      7074787.40
      2927421.82      7074771.58      2927409.24      7074677.00
      2927471.35      7074538.36      2927668.18      7074397.03
      2927619.96      7074334.43      2927650.19      7074280.86
      2927771.79      7074308.53      2927791.50      7074040.15
      2927921.24      7073994.08      2927999.99      7074009.80
      2928056.83      7073921.89      2928130.46      7073892.82
      2928087.56      7073741.55      2928205.43      7073670.66
      2928224.78      7073586.83      2928308.74      7073582.32
      2928277.98      7073491.10      2928325.59      7073390.71

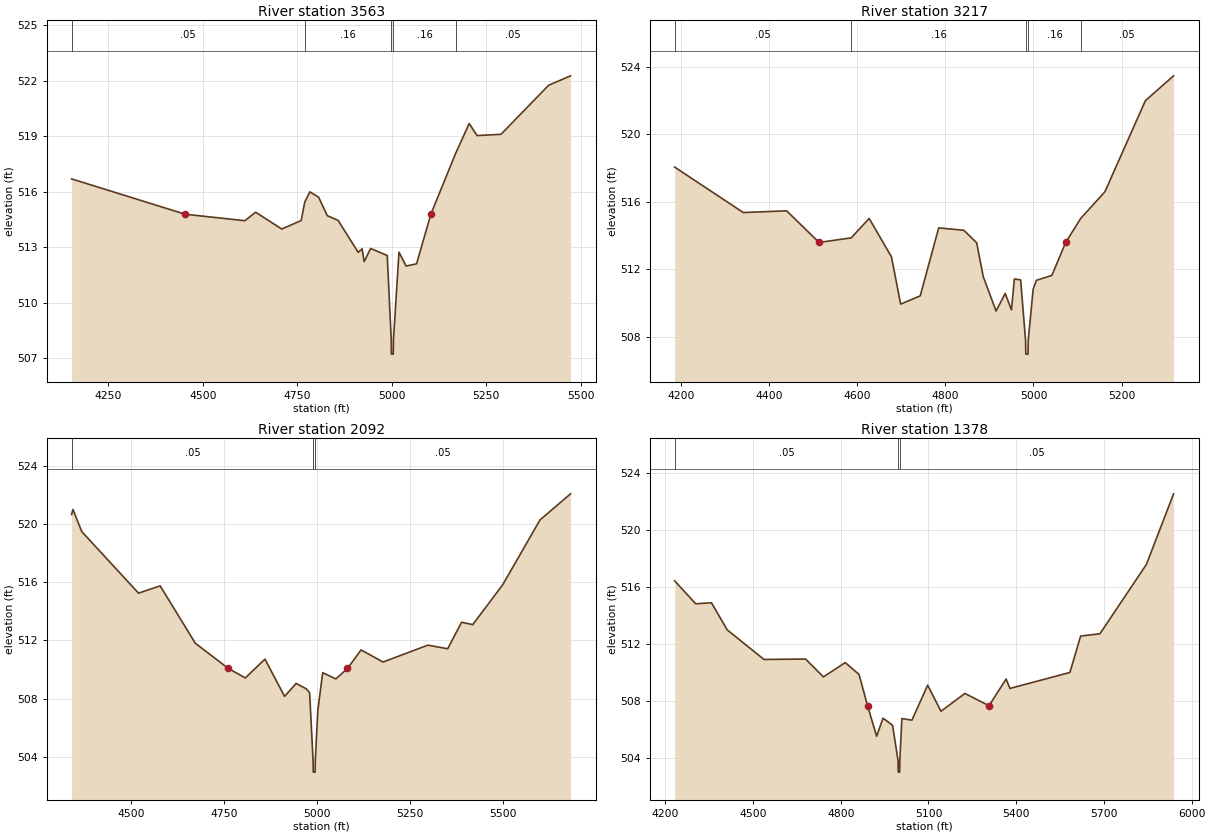
Type RM Length L Ch R = 1,3563,346,346,346
BEGIN DESCRIPTION:
UNT 030 in Running Cr Watershed 3.0
END DESCRIPTION:
XS GIS Cut Line= 3
      2927001.68      7075714.70      2926633.39      7074909.09
      2926219.82      7074775.54
#Sta/Elev= 30
  4153.1  516.70  4453.6  514.79  4611.6  514.44  4640.1  514.90  4709.2  513.99
  4760.7  514.45  4770.0  515.44  4783.7  516.00  4806.8  515.71  4829.8  514.71
  4858.3  514.46  4911.5  512.73  4921.9  512.92  4927.4  512.23  4944.4  512.94
  4988.4  512.56  4998.9  508.03  4999.4  507.23  5004.4  507.23  5004.9  508.03
  5019.5  512.74  5038.4  511.99  5066.0  512.11  5103.8  514.79  5169.2  518.07
  5205.3  519.69  5226.2  519.04  5289.4  519.11  5415.5  521.76  5473.5  522.27
#Mann=5,-1,0
  4153.1    0.05       0  4770.0    0.16       0  4998.9    0.07       0
  5004.9    0.16       0  5169.2    0.05       0
Bank Sta=4453.6,5103.8
Exp/Cntr=0.3,0.1

Type RM Length L Ch R = 1,3217,1125,1125,1125
BEGIN DESCRIPTION:
UNT 030 in Running Cr Watershed 2.0
END DESCRIPTION:
XS GIS Cut Line= 3
      2927442.63      7075493.04      2927019.39      7074888.41
      2926724.98      7074624.98
#Sta/Elev= 30
  4185.1  518.05  4341.0  515.36  4439.5  515.46  4513.1  513.59  4586.1  513.86
  4626.9  515.01  4677.5  512.74  4698.4  509.94  4742.9  510.43  4784.8  514.45
  4841.9  514.31  4871.1  513.57  4885.9  511.57  4915.1  509.53  4935.8  510.57
  4950.0  509.60  4956.7  511.43  4970.9  511.37  4982.1  507.78  4982.6  506.98
  4987.6  506.98  4988.1  507.78  4999.3  510.82  5006.8  511.35  5041.9  511.64
  5073.2  513.59  5107.3  515.01  5162.3  516.59  5254.2  521.98  5318.2  523.45
#Mann=5,-1,0
  4185.1    0.05       0  4586.1    0.16       0  4982.1    0.07       0
  4988.1    0.16       0  5107.3    0.05       0
Bank Sta=4513.1,5073.2
Exp/Cntr=0.3,0.1

Type RM Length L Ch R = 1,2092,714,714,714
BEGIN DESCRIPTION:
Mapping XS c3ad7a45
END DESCRIPTION:
XS GIS Cut Line= 4
      2927762.10      7075181.73      2927550.29      7074685.18
      2927303.76      7074535.88      2926793.31      7074490.73
#Sta/Elev= 30
  4340.9  520.64  4344.5  520.99  4368.1  519.47  4520.7  515.24  4578.8  515.74
  4673.3  511.80  4761.9  510.07  4807.6  509.42  4860.3  510.71  4913.1  508.15
  4944.1  509.04  4971.3  508.67  4980.4  508.40  4989.6  503.75  4990.1  502.95
  4995.1  502.95  4995.6  503.75  5002.3  507.16  5015.5  509.78  5050.8  509.35
  5082.1  510.07  5118.6  511.34  5177.7  510.51  5298.2  511.67  5351.3  511.42
  5388.6  513.24  5418.7  513.08  5499.0  515.81  5599.4  520.27  5681.4  522.06
#Mann=3,-1,0
  4340.9    0.05       0  4989.6    0.03       0  4995.6    0.05       0
Bank Sta=4761.9,5082.1
Exp/Cntr=0.3,0.1

Type RM Length L Ch R = 1,1378,0,0,0
BEGIN DESCRIPTION:
UNT 030 in Running Cr Watershed 1.0
END DESCRIPTION:
XS GIS Cut Line= 4
      2928001.67      7074955.99      2927887.09      7074310.18
      2927647.51      7074206.01      2926873.18      7074358.80
#Sta/Elev= 30
  4231.8  516.43  4303.9  514.82  4357.8  514.89  4411.8  512.99  4537.5  510.92
  4679.7  510.95  4740.6  509.70  4815.3  510.70  4862.5  509.87  4891.6  507.68
  4922.7  505.54  4944.5  506.81  4977.2  506.31  4996.0  503.83  4996.5  503.03
  5001.5  503.03  5002.0  503.83  5009.0  506.78  5043.4  506.67  5097.2  509.12
  5142.6  507.29  5224.6  508.54  5307.1  507.68  5365.5  509.55  5378.5  508.89
  5583.7  510.01  5620.4  512.56  5686.4  512.72  5845.4  517.58  5938.2  522.52
#Mann=3,-1,0
  4231.8    0.05       0  4996.0    0.03       0  5002.0    0.05       0
Bank Sta=4891.6,5307.1
Exp/Cntr=0.3,0.1

Chan Stop Cuts=-1