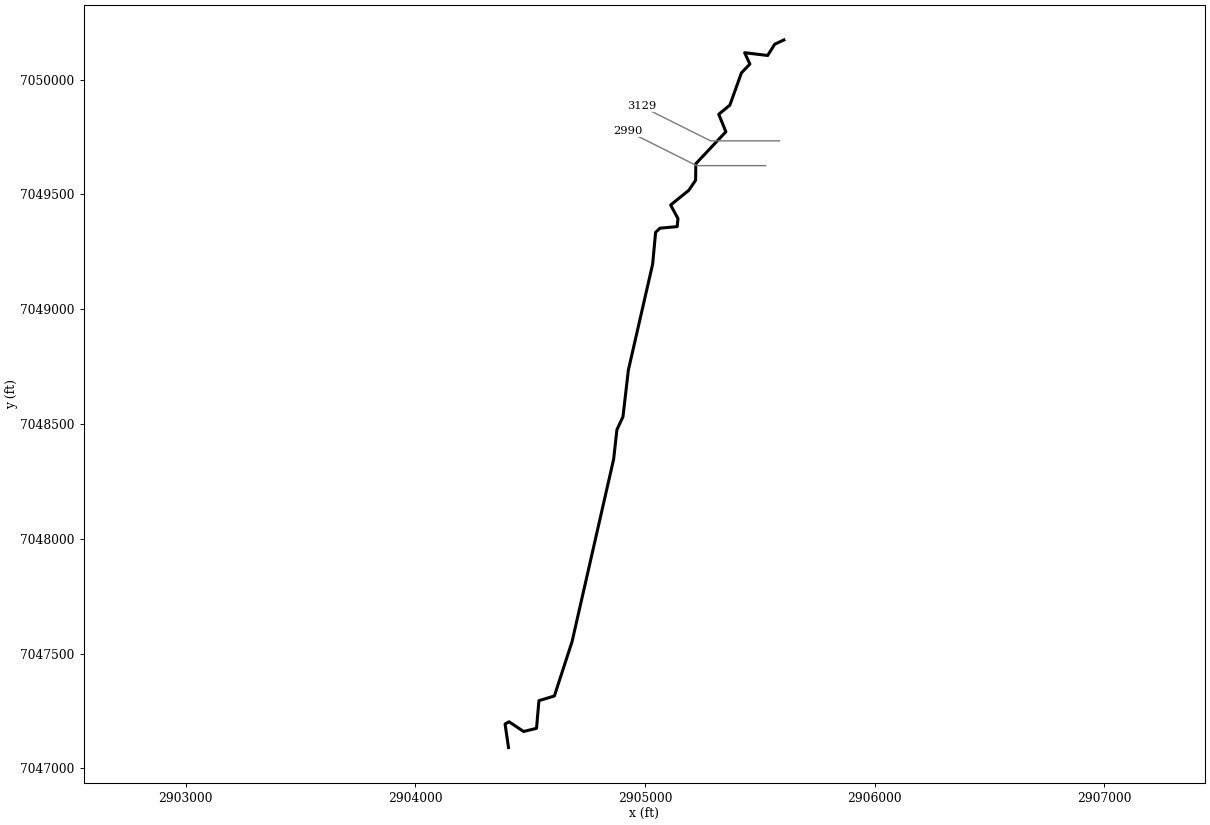
--- UNT 031 in Running Cr Watershed.prj (project) ---

Proj Title=UNT 031 in Running Cr Watershed Base Level Engineering
Current Plan=p01
Default Exp/Contr=0.3,0.1
English Units
Geom File=g01
Flow File=f01
Plan File=p01
BEGIN DESCRIPTION:
UNT 031 in Running Cr Watershed
END DESCRIPTION:

--- UNT 031 in Running Cr Watershed.p01 (plan) ---

Plan Title=Multiple Run
Short Identifier=Multiple
Geom File=g01
Flow File=f01
Subcritical Flow
K Sum by GR= 0
Std Step Tol= 0.01
Critical Tol= 0.01
Num of Std Step Trials= 20
Max Error Tol= 0.3
Flow Tol Ratio= 0.001
Split Flow NTrial= 30
Split Flow Tol= 0.02
Split Flow Ratio= 0.02
Log Output Level= 0
Friction Slope Method= 1
Unsteady Friction Slope Method= 2
Unsteady Bridges Friction Slope Method= 1
Parabolic Critical Depth
Global Vel Dist=  1 , 1 , 1
Global Log Level= 0
CheckData=True
Encroach Param= -1, 0, 0, 0
BEGIN DESCRIPTION:
Multiple Run
END DESCRIPTION:

--- UNT 031 in Running Cr Watershed.f01 (steady flow) ---

Flow Title=Multiple
Number of Profiles=7
Profile Names=10-year,25-year,50-year,1pct_min,100-year,1pct_plu,500-year
River Rch & RM= UNT 031 in Runni,Reach-1,3129
     541     721     865     517    1031    2057    1466
Boundary for River Rch & Prof#=UNT 031 in Runni,Reach-1,1
Up Type=0
Dn Type=3
Dn Slope=0.005
Boundary for River Rch & Prof#=UNT 031 in Runni,Reach-1,2
Up Type=0
Dn Type=3
Dn Slope=0.005
Boundary for River Rch & Prof#=UNT 031 in Runni,Reach-1,3
Up Type=0
Dn Type=3
Dn Slope=0.005
Boundary for River Rch & Prof#=UNT 031 in Runni,Reach-1,4
Up Type=0
Dn Type=3
Dn Slope=0.005
Boundary for River Rch & Prof#=UNT 031 in Runni,Reach-1,5
Up Type=0
Dn Type=3
Dn Slope=0.005
Boundary for River Rch & Prof#=UNT 031 in Runni,Reach-1,6
Up Type=0
Dn Type=3
Dn Slope=0.005
Boundary for River Rch & Prof#=UNT 031 in Runni,Reach-1,7
Up Type=0
Dn Type=3
Dn Slope=0.005

--- UNT 031 in Running Cr Watershed.g01 (geometry) ---

Geom Title=Existing Conditions

River Reach=UNT 031 in Runni,Reach-1
Reach XY= 30
      2905604.89      7050172.30      2905565.00      7050153.96
      2905534.12      7050104.70      2905433.91      7050116.83
      2905456.77      7050067.38      2905419.97      7050029.08
      2905369.51      7049888.28      2905321.10      7049848.72
      2905352.18      7049772.48      2905221.27      7049633.24
      2905220.47      7049561.71      2905190.99      7049517.86
      2905111.72      7049453.51      2905143.62      7049394.21
      2905140.10      7049359.50      2905064.88      7049352.48
      2905046.18      7049334.29      2905033.33      7049196.31
      2904927.60      7048734.87      2904904.04      7048531.35
      2904877.76      7048475.14      2904863.43      7048346.60
      2904682.33      7047552.06      2904605.34      7047315.37
      2904538.05      7047295.02      2904527.62      7047174.50
      2904471.11      7047160.82      2904408.17      7047202.98
      2904390.58      7047193.58      2904405.59      7047090.71

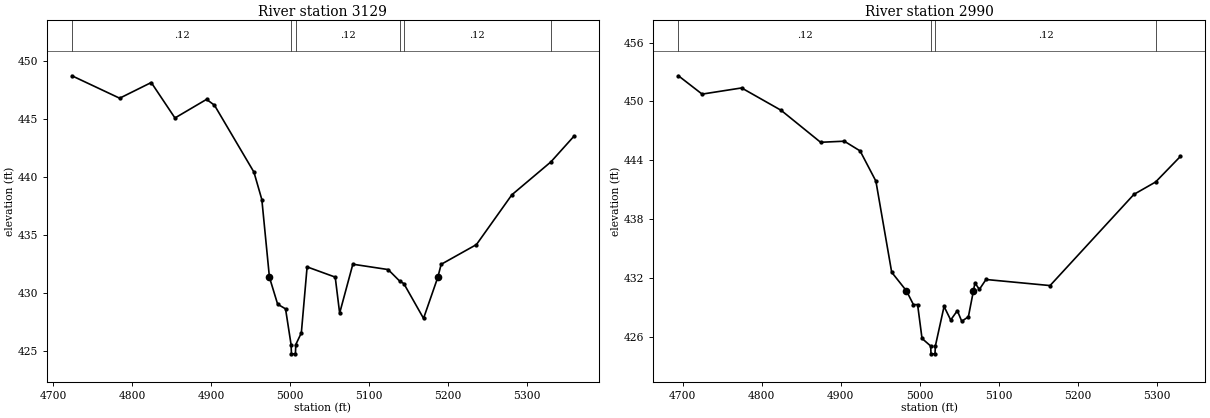
Type RM Length L Ch R = 1,3129,139,139,139
BEGIN DESCRIPTION:
UNT 031 in Running Cr Watershed 2.0
END DESCRIPTION:
XS GIS Cut Line= 3
      2905585.43      7049732.95      2905285.45      7049732.95
      2904985.44      7049882.96
#Sta/Elev= 30
  4723.6  448.71  4784.0  446.78  4824.0  448.13  4854.0  445.08  4894.0  446.68
  4904.0  446.18  4954.0  440.42  4964.0  438.06  4973.6  431.38  4984.0  429.06
  4994.0  428.66  5001.0  425.59  5001.5  424.79  5006.5  424.79  5007.0  425.59
  5014.0  426.59  5021.3  432.27  5056.9  431.39  5062.5  428.29  5079.2  432.50
  5123.9  432.04  5138.9  431.02  5143.7  430.84  5168.7  427.84  5186.8  431.38
  5191.0  432.49  5235.7  434.19  5280.5  438.47  5329.9  441.30  5359.0  443.50
#Mann=6,-1,0
  4723.6    0.12       0  5001.0    0.07       0  5007.0    0.12       0
  5138.9    0.16       0  5143.7    0.12       0  5329.9    0.16       0
Bank Sta=4973.6,5186.8
Exp/Cntr=0.3,0.1

Type RM Length L Ch R = 1,2990,0,0,0
BEGIN DESCRIPTION:
UNT 031 in Running Cr Watershed 1.0
END DESCRIPTION:
XS GIS Cut Line= 3
      2905524.97      7049625.00      2905225.00      7049625.00
      2904924.98      7049775.01
#Sta/Elev= 30
  4694.6  452.62  4724.6  450.75  4774.6  451.38  4824.6  449.10  4874.6  445.84
  4904.6  445.95  4924.6  444.96  4944.6  441.88  4964.6  432.59  4983.3  430.69
  4992.1  429.29  4997.4  429.29  5003.0  425.84  5013.9  425.07  5014.4  424.27
  5019.4  424.27  5019.9  425.07  5030.9  429.10  5039.3  427.72  5047.7  428.67
  5053.3  427.59  5061.7  428.05  5068.1  430.70  5070.0  431.50  5075.6  430.84
  5084.0  431.85  5165.1  431.23  5271.3  440.53  5298.7  441.79  5330.0  444.39
#Mann=4,-1,0
  4694.6    0.12       0  5013.9    0.07       0  5019.9    0.12       0
  5298.7    0.16       0
Bank Sta=4983.3,5068.1
Exp/Cntr=0.3,0.1

Chan Stop Cuts=-1