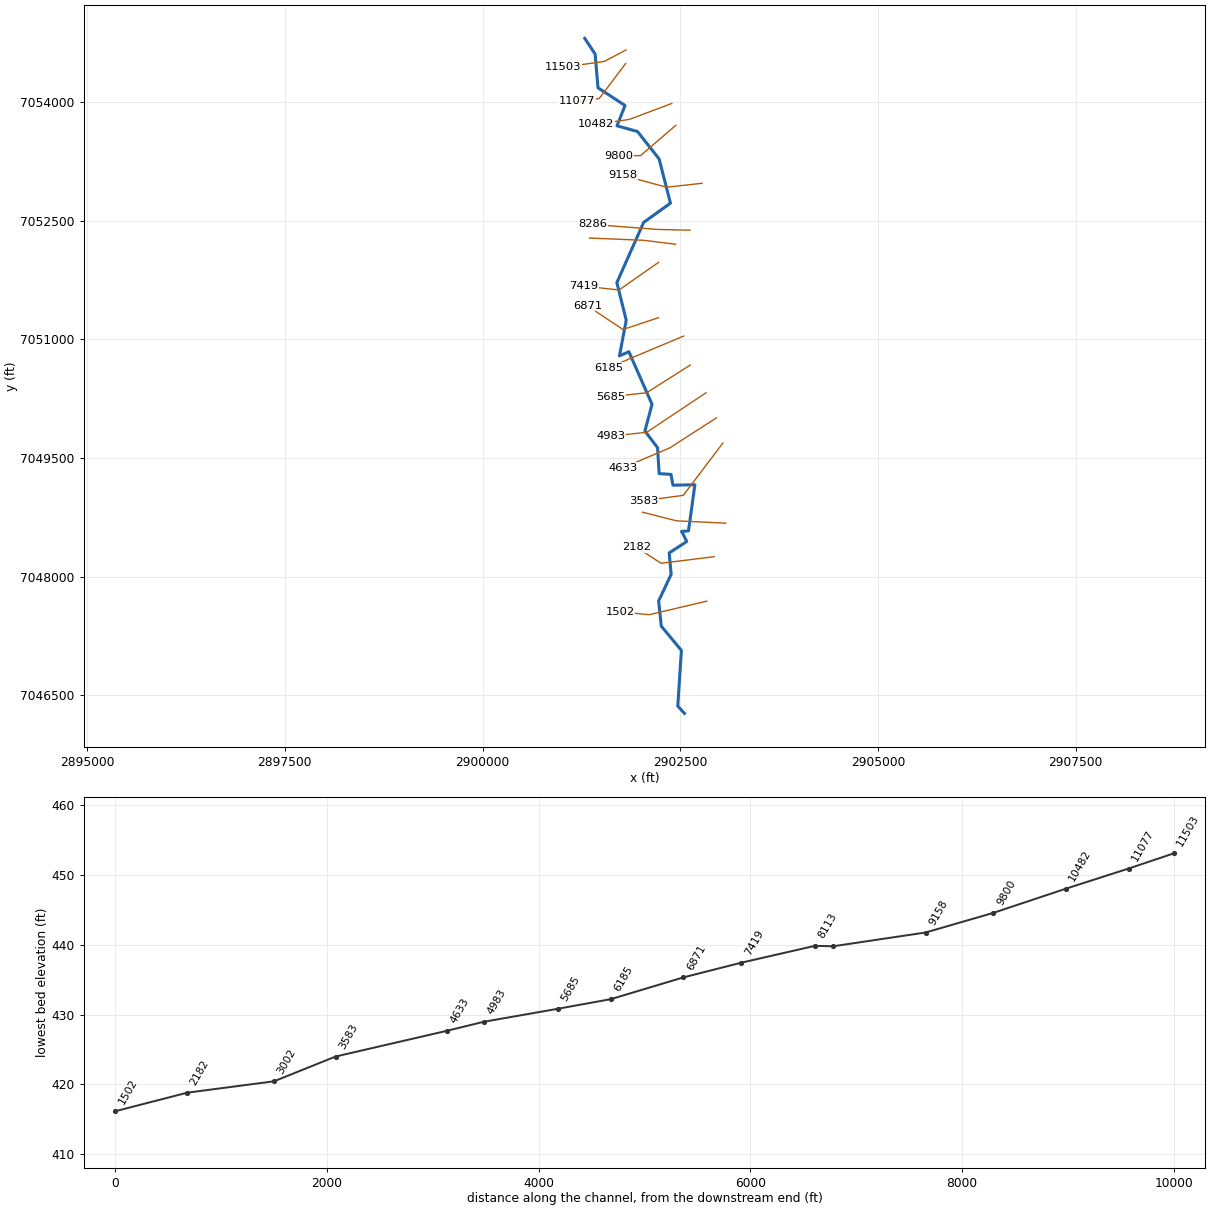
--- UNT 032 in Running Cr Watershed.prj (project) ---

Proj Title=UNT 032 in Running Cr Watershed Base Level Engineering
Current Plan=p01
Default Exp/Contr=0.3,0.1
English Units
Geom File=g01
Flow File=f01
Plan File=p01
BEGIN DESCRIPTION:
UNT 032 in Running Cr Watershed
END DESCRIPTION:

--- UNT 032 in Running Cr Watershed.p01 (plan) ---

Plan Title=Multiple Run
Short Identifier=Multiple
Geom File=g01
Flow File=f01
Subcritical Flow
K Sum by GR= 0
Std Step Tol= 0.01
Critical Tol= 0.01
Num of Std Step Trials= 20
Max Error Tol= 0.3
Flow Tol Ratio= 0.001
Split Flow NTrial= 30
Split Flow Tol= 0.02
Split Flow Ratio= 0.02
Log Output Level= 0
Friction Slope Method= 1
Unsteady Friction Slope Method= 2
Unsteady Bridges Friction Slope Method= 1
Parabolic Critical Depth
Global Vel Dist=  1 , 1 , 1
Global Log Level= 0
CheckData=True
Encroach Param= -1, 0, 0, 0
BEGIN DESCRIPTION:
Multiple Run
END DESCRIPTION:

--- UNT 032 in Running Cr Watershed.f01 (steady flow) ---

Flow Title=Multiple
Number of Profiles=7
Profile Names=10-year,25-year,50-year,1pct_min,100-year,1pct_plu,500-year
River Rch & RM= UNT 032 in Runni,Reach-1,11503
     560     744     891     531    1060    2114    1498
River Rch & RM= UNT 032 in Runni,Reach-1,9800
     841    1142    1388     837    1671    3334    2426
Boundary for River Rch & Prof#=UNT 032 in Runni,Reach-1,1
Up Type=0
Dn Type=3
Dn Slope=0.005
Boundary for River Rch & Prof#=UNT 032 in Runni,Reach-1,2
Up Type=0
Dn Type=3
Dn Slope=0.005
Boundary for River Rch & Prof#=UNT 032 in Runni,Reach-1,3
Up Type=0
Dn Type=3
Dn Slope=0.005
Boundary for River Rch & Prof#=UNT 032 in Runni,Reach-1,4
Up Type=0
Dn Type=3
Dn Slope=0.005
Boundary for River Rch & Prof#=UNT 032 in Runni,Reach-1,5
Up Type=0
Dn Type=3
Dn Slope=0.005
Boundary for River Rch & Prof#=UNT 032 in Runni,Reach-1,6
Up Type=0
Dn Type=3
Dn Slope=0.005
Boundary for River Rch & Prof#=UNT 032 in Runni,Reach-1,7
Up Type=0
Dn Type=3
Dn Slope=0.005

--- UNT 032 in Running Cr Watershed.g01 (geometry) ---

Geom Title=Existing Conditions

River Reach=UNT 032 in Runni,Reach-1
Reach XY= 30
      2901291.79      7054809.02      2901422.95      7054609.52
      2901459.25      7054182.88      2901801.11      7053959.74
      2901699.28      7053701.98      2901958.68      7053630.13
      2902231.53      7053283.72      2902375.22      7052723.48
      2902036.51      7052480.57      2901697.81      7051718.97
      2901815.83      7051242.11      2901730.64      7050791.02
      2901849.20      7050843.85      2902142.27      7050179.00
      2902052.31      7049841.03      2902212.35      7049629.19
      2902232.21      7049301.61      2902382.16      7049291.94
      2902406.02      7049155.42      2902684.11      7049160.55
      2902603.39      7048576.46      2902516.35      7048570.92
      2902581.68      7048442.28      2902359.23      7048298.62
      2902383.79      7048026.51      2902225.74      7047690.53
      2902259.03      7047372.22      2902513.63      7047064.90
      2902467.86      7046360.52      2902552.13      7046268.24

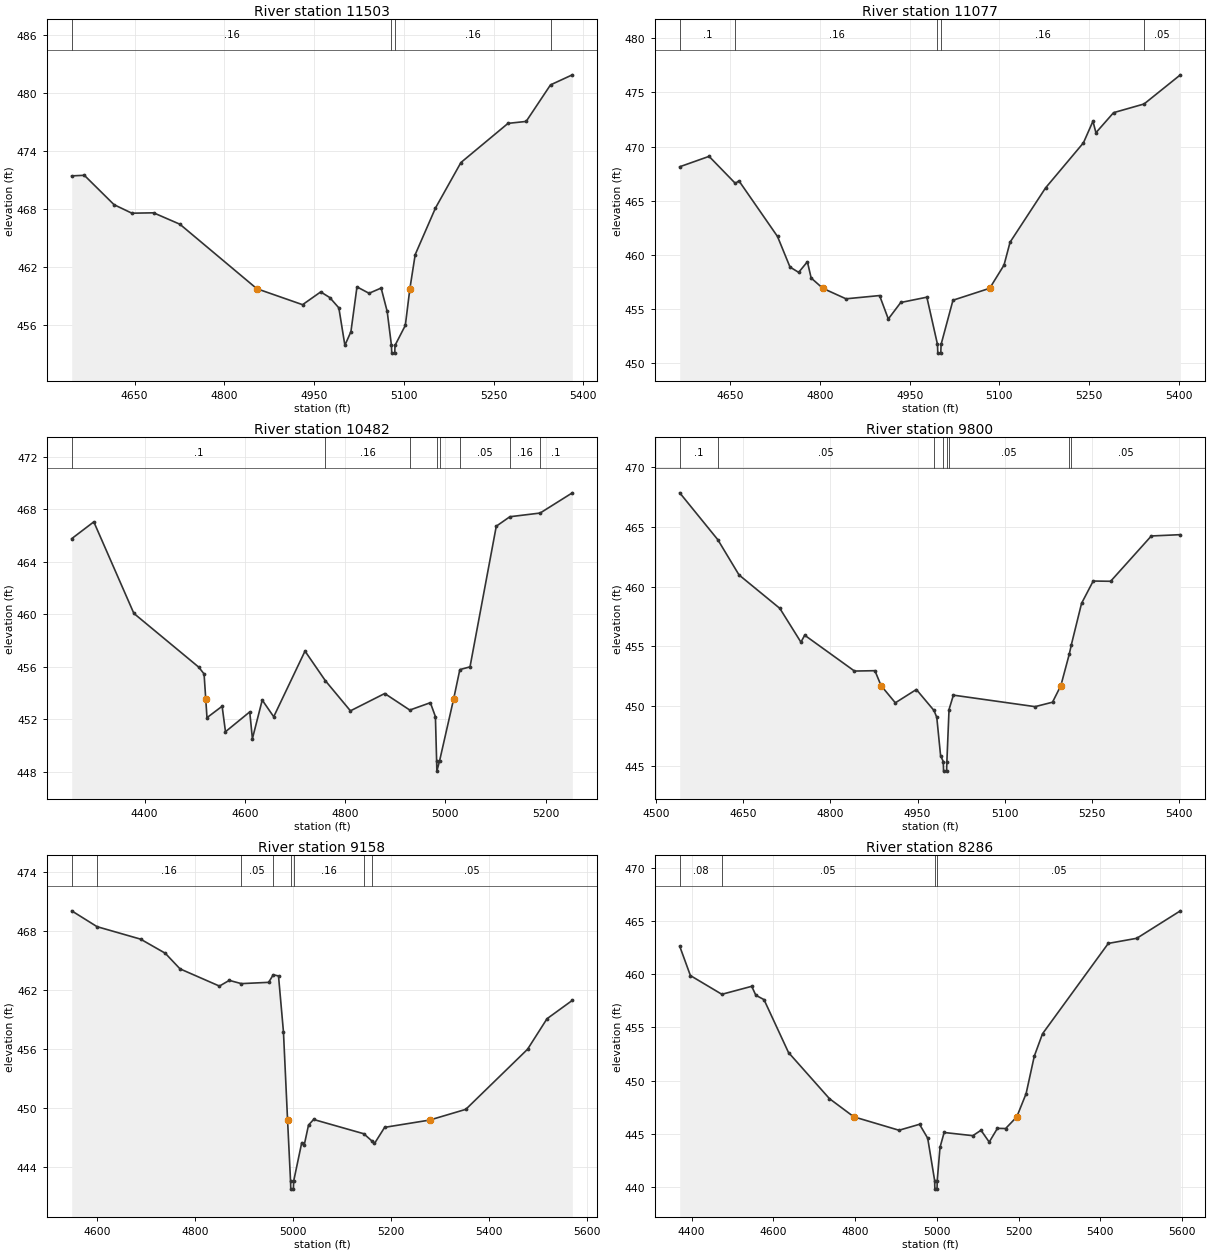
Type RM Length L Ch R = 1,11503,426,426,426
BEGIN DESCRIPTION:
UNT 032 in Running Cr Watershed 17.0
END DESCRIPTION:
XS GIS Cut Line= 3
      2901813.93      7054662.34      2901537.85      7054516.48
      2901018.56      7054443.78
#Sta/Elev= 30
  4545.0  471.45  4566.1  471.51  4615.8  468.47  4645.6  467.59  4681.8  467.63
  4725.8  466.45  4854.4  459.78  4930.8  458.13  4961.1  459.45  4976.2  458.87
  4991.4  457.80  5001.5  453.93  5011.6  455.34  5021.7  459.97  5041.9  459.31
  5062.1  459.85  5072.2  457.43  5079.3  453.92  5079.8  453.12  5084.8  453.12
  5085.3  453.92  5102.5  455.99  5110.1  459.78  5119.0  463.31  5152.9  468.13
  5195.4  472.83  5274.1  476.88  5304.4  477.08  5345.1  480.86  5381.6  481.90
#Mann=4,-1,0
  4545.0    0.16       0  5079.3    0.07       0  5085.3    0.16       0
  5345.1    0.05       0
Bank Sta=4854.4,5110.1
Exp/Cntr=0.3,0.1

Type RM Length L Ch R = 1,11077,595,595,595
BEGIN DESCRIPTION:
UNT 032 in Running Cr Watershed 16.0
END DESCRIPTION:
XS GIS Cut Line= 3
      2901808.67      7054490.42      2901475.35      7054047.73
      2901194.15      7054011.28
#Sta/Elev= 30
  4565.2  468.14  4614.3  469.10  4658.2  466.61  4664.3  466.84  4728.8  461.71
  4749.7  458.89  4764.2  458.40  4778.8  459.38  4785.1  457.88  4804.6  456.93
  4843.4  455.96  4899.6  456.26  4914.2  454.10  4935.0  455.62  4978.7  456.11
  4996.5  451.75  4997.0  450.95  5002.0  450.95  5002.5  451.75  5022.4  455.83
  5083.8  456.93  5107.8  459.07  5117.9  461.18  5177.3  466.19  5240.7  470.35
  5256.6  472.34  5261.6  471.28  5291.1  473.13  5342.1  473.93  5402.9  476.62
#Mann=5,-1,0
  4565.2     0.1       0  4658.2    0.16       0  4996.5    0.07       0
  5002.5    0.16       0  5342.1    0.05       0
Bank Sta=4804.6,5083.8
Exp/Cntr=0.3,0.1

Type RM Length L Ch R = 1,10482,682,682,682
BEGIN DESCRIPTION:
UNT 032 in Running Cr Watershed 15.0
END DESCRIPTION:
XS GIS Cut Line= 3
      2902392.03      7053985.24      2901857.72      7053784.06
      2901435.00      7053719.81
#Sta/Elev= 30
  4254.7  465.75  4298.8  467.03  4378.7  460.06  4508.0  455.97  4518.7  455.45
  4522.1  453.52  4524.5  452.12  4554.7  452.99  4561.4  451.05  4609.8  452.56
  4615.1  450.52  4634.7  453.46  4657.6  452.19  4720.0  457.19  4760.5  454.94
  4810.6  452.64  4879.0  453.96  4929.0  452.70  4970.0  453.26  4980.1  452.20
  4982.5  448.85  4983.0  448.05  4988.5  448.85  5016.3  453.52  5028.8  455.78
  5049.1  455.99  5101.5  466.70  5128.6  467.42  5188.9  467.70  5253.2  469.24
#Mann=8,-1,0
  4254.7     0.1       0  4760.5    0.16       0  4929.0    0.07       0
  4982.5    0.07       0  4988.5    0.07       0  5028.8    0.05       0
  5128.6    0.16       0  5188.9     0.1       0
Bank Sta=4522.1,5016.3
Exp/Cntr=0.3,0.1

Type RM Length L Ch R = 1,9800,642,642,642
BEGIN DESCRIPTION:
UNT 032 in Running Cr Watershed 14.0
END DESCRIPTION:
XS GIS Cut Line= 3
      2902444.13      7053709.22      2901996.19      7053325.00
      2901725.04      7053325.00
#Sta/Elev= 30
  4540.8  467.82  4606.3  463.91  4642.8  460.97  4713.0  458.18  4749.3  455.36
  4755.8  455.94  4841.4  452.95  4876.6  452.98  4887.1  451.74  4911.7  450.30
  4947.9  451.41  4978.2  449.66  4983.0  449.09  4989.6  445.88  4994.2  445.40
  4994.7  444.60  4999.9  444.60  5000.4  445.40  5004.1  449.74  5011.6  450.94
  5152.1  449.98  5182.1  450.35  5196.5  451.74  5210.9  454.35  5214.6  455.16
  5232.1  458.60  5252.1  460.46  5282.1  460.44  5352.1  464.22  5402.1  464.33
#Mann=8,-1,0
  4540.8     0.1       0  4606.3    0.05       0  4978.2    0.12       0
  4994.2    0.07       0  5000.4    0.12       0  5004.1    0.05       0
  5210.9    0.16       0  5214.6    0.05       0
Bank Sta=4887.1,5196.5
Exp/Cntr=0.3,0.1

Type RM Length L Ch R = 1,9158,872,872,872
BEGIN DESCRIPTION:
UNT 032 in Running Cr Watershed 13.0
END DESCRIPTION:
XS GIS Cut Line= 3
      2902774.96      7052975.00      2902325.00      7052925.00
      2901775.01      7053075.00
#Sta/Elev= 30
  4547.8  470.07  4599.6  468.46  4688.6  467.19  4738.9  465.76  4769.1  464.17
  4849.6  462.42  4869.7  463.00  4894.4  462.67  4950.2  462.80  4959.5  463.57
  4970.3  463.45  4980.4  457.77  4988.8  448.80  4994.9  442.58  4995.4  441.78
  5000.7  441.78  5001.2  442.58  5017.8  446.51  5023.0  446.30  5031.6  448.29
  5042.0  448.86  5144.5  447.41  5160.8  446.69  5166.4  446.42  5187.1  448.06
  5279.1  448.80  5352.9  449.89  5479.1  456.00  5518.8  459.10  5570.6  460.97
#Mann=8,-1,0
  4547.8    0.05       0  4599.6    0.16       0  4894.4    0.05       0
  4959.5    0.16       0  4994.9    0.07       0  5001.2    0.16       0
  5144.5    0.12       0  5160.8    0.05       0
Bank Sta=4988.8,5279.1
Exp/Cntr=0.3,0.1

Type RM Length L Ch R = 1,8286,173,173,173
BEGIN DESCRIPTION:
UNT 032 in Running Cr Watershed 12.0
END DESCRIPTION:
XS GIS Cut Line= 3
      2902621.14      7052381.07      2902209.73      7052391.48
      2901398.57      7052453.88
#Sta/Elev= 30
  4371.0  462.62  4397.1  459.87  4474.1  458.11  4547.2  458.86  4557.2  458.02
  4577.2  457.61  4637.2  452.64  4737.3  448.31  4797.1  446.60  4907.6  445.34
  4957.8  445.90  4977.8  444.59  4994.8  440.61  4995.3  439.81  5000.6  439.81
  5001.1  440.61  5007.9  443.73  5018.0  445.13  5088.2  444.83  5108.2  445.34
  5128.3  444.23  5148.4  445.52  5168.4  445.50  5195.8  446.60  5218.6  448.78
  5238.6  452.30  5258.7  454.40  5419.7  462.89  5489.4  463.37  5596.1  465.95
#Mann=4,-1,0
  4371.0    0.08       0  4474.1    0.05       0  4994.8    0.03       0
  5001.1    0.05       0
Bank Sta=4797.1,5195.8
Exp/Cntr=0.3,0.1

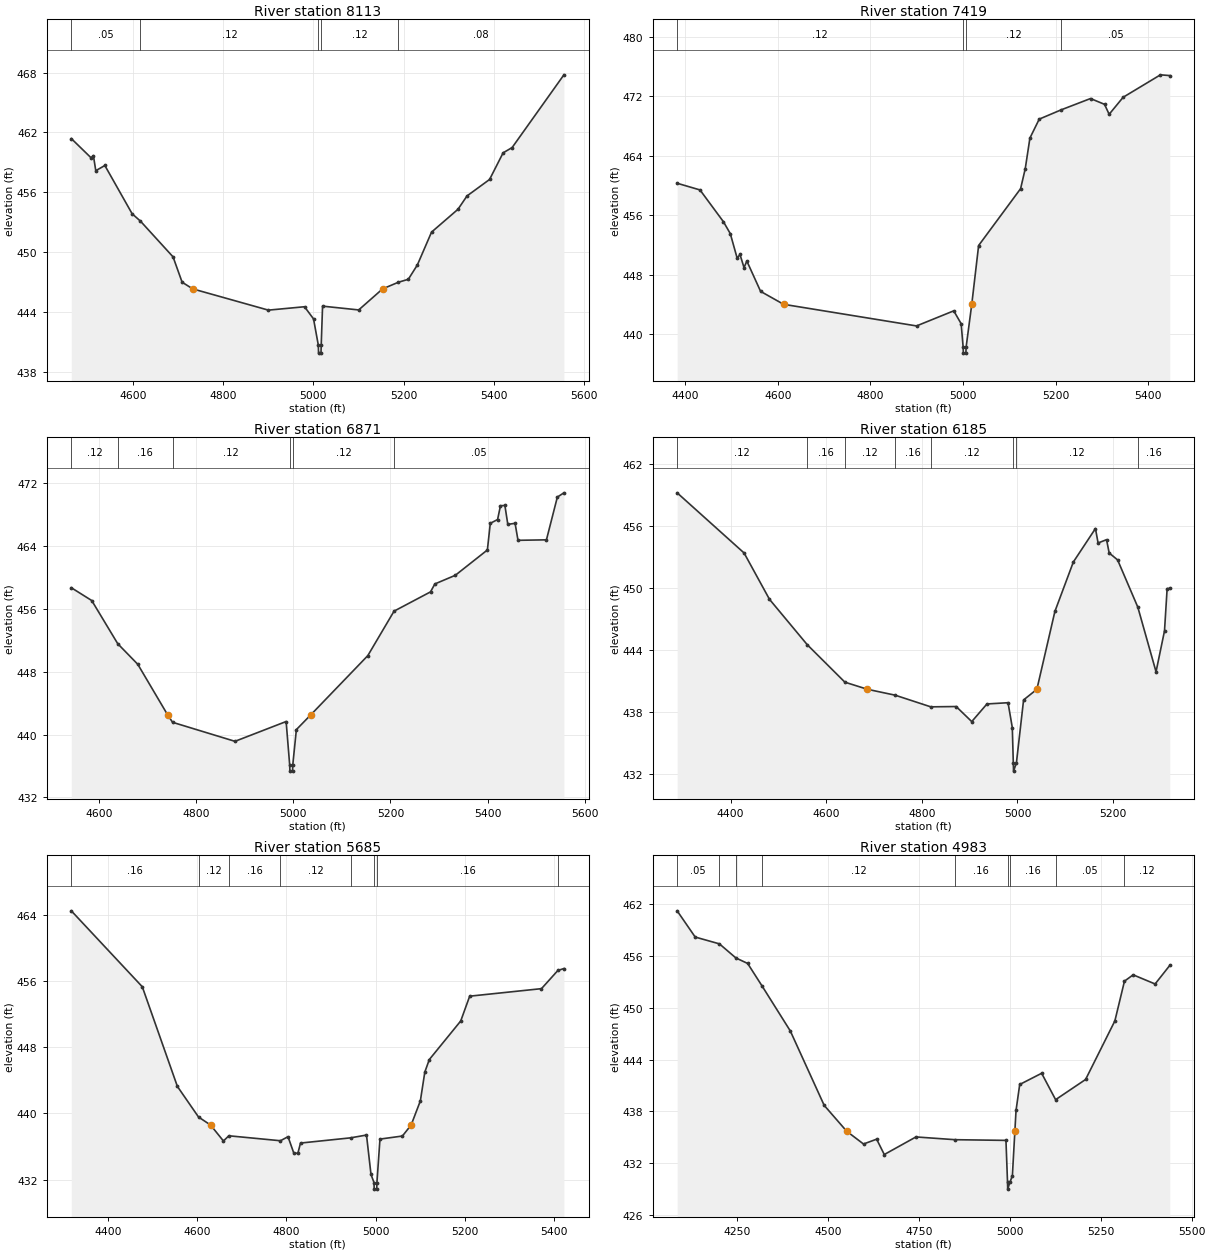
Type RM Length L Ch R = 1,8113,694,694,694
BEGIN DESCRIPTION:
UNT 032 in Running Cr Watershed 11.0
END DESCRIPTION:
XS GIS Cut Line= 3
      2902438.85      7052203.99      2902035.42      7052254.17
      2901350.33      7052282.11
#Sta/Elev= 30
  4463.2  461.38  4507.1  459.45  4512.2  459.67  4517.5  458.16  4537.6  458.68
  4598.1  453.84  4616.6  453.10  4688.8  449.52  4708.9  446.98  4732.5  446.31
  4900.2  444.18  4980.3  444.52  5000.3  443.30  5010.9  440.67  5011.4  439.87
  5016.8  439.87  5017.3  440.67  5020.3  444.58  5100.4  444.20  5153.4  446.31
  5188.6  446.98  5210.4  447.27  5230.5  448.71  5261.9  452.00  5320.5  454.29
  5340.6  455.63  5390.6  457.28  5420.6  459.95  5440.6  460.48  5555.4  467.77
#Mann=5,-1,0
  4463.2    0.05       0  4616.6    0.12       0  5010.9    0.07       0
  5017.3    0.12       0  5188.6    0.08       0
Bank Sta=4732.5,5153.4
Exp/Cntr=0.3,0.1

Type RM Length L Ch R = 1,7419,548,548,548
BEGIN DESCRIPTION:
UNT 032 in Running Cr Watershed 10.0
END DESCRIPTION:
XS GIS Cut Line= 3
      2902225.04      7051975.03      2901725.00      7051625.00
      2901275.04      7051675.00
#Sta/Elev= 30
  4383.0  460.32  4432.3  459.42  4482.9  455.14  4497.7  453.54  4512.5  450.24
  4518.6  450.74  4527.3  448.97  4533.4  449.85  4563.1  445.77  4612.7  444.03
  4899.6  441.12  4979.9  443.15  4995.9  441.42  5000.2  438.26  5000.7  437.46
  5006.1  437.46  5006.6  438.26  5018.8  444.03  5033.6  451.94  5124.2  459.59
  5134.2  462.27  5144.3  466.40  5164.4  468.95  5212.2  470.21  5275.1  471.72
  5305.3  470.94  5315.3  469.60  5345.5  471.89  5426.0  474.91  5446.1  474.81
#Mann=4,-1,0
  4383.0    0.12       0  5000.2    0.07       0  5006.6    0.12       0
  5212.2    0.05       0
Bank Sta=4612.7,5018.8
Exp/Cntr=0.3,0.1

Type RM Length L Ch R = 1,6871,686,686,686
BEGIN DESCRIPTION:
UNT 032 in Running Cr Watershed 9.0
END DESCRIPTION:
XS GIS Cut Line= 3
      2902224.96      7051274.99      2901775.00      7051125.00
      2901325.03      7051424.98
#Sta/Elev= 30
  4542.3  458.68  4584.4  457.05  4638.1  451.55  4679.3  448.94  4740.8  442.51
  4751.0  441.56  4879.6  439.14  4985.0  441.66  4992.3  436.15  4992.8  435.35
  4998.2  435.35  4998.7  436.15  5006.1  440.63  5035.8  442.51  5153.3  450.04
  5207.4  455.70  5282.5  458.15  5291.5  459.16  5333.6  460.26  5399.7  463.48
  5405.7  466.87  5420.7  467.35  5426.7  469.11  5435.8  469.14  5441.8  466.74
  5456.8  466.87  5462.8  464.71  5521.4  464.77  5543.9  470.21  5557.4  470.75
#Mann=6,-1,0
  4542.3    0.12       0  4638.1    0.16       0  4751.0    0.12       0
  4992.3    0.07       0  4998.7    0.12       0  5207.4    0.05       0
Bank Sta=4740.8,5035.8
Exp/Cntr=0.3,0.1

Type RM Length L Ch R = 1,6185,500,500,500
BEGIN DESCRIPTION:
UNT 032 in Running Cr Watershed 8.0
END DESCRIPTION:
XS GIS Cut Line= 3
      2902543.07      7051042.53      2901850.35      7050751.85
      2901596.01      7050637.24
#Sta/Elev= 30
  4288.3  459.20  4428.3  453.37  4481.4  448.88  4560.4  444.48  4639.1  440.85
  4686.3  440.16  4744.2  439.59  4818.7  438.46  4871.8  438.49  4904.4  437.03
  4936.2  438.74  4980.3  438.86  4989.2  436.45  4991.3  433.03  4991.8  432.23
  4997.8  433.03  5012.8  439.13  5040.6  440.16  5078.3  447.71  5116.9  452.50
  5163.1  455.74  5168.6  454.34  5186.3  454.66  5191.8  453.37  5209.4  452.70
  5251.7  448.12  5289.8  441.86  5307.5  445.82  5313.0  449.92  5318.5  449.94
#Mann=8,-1,0
  4288.3    0.12       0  4560.4    0.16       0  4639.1    0.12       0
  4744.2    0.16       0  4818.7    0.12       0  4991.3    0.07       0
  4997.8    0.12       0  5251.7    0.16       0
Bank Sta=4686.3,5040.6
Exp/Cntr=0.3,0.1

Type RM Length L Ch R = 1,5685,702,702,702
BEGIN DESCRIPTION:
UNT 032 in Running Cr Watershed 7.0
END DESCRIPTION:
XS GIS Cut Line= 3
      2902625.03      7050675.02      2902075.00      7050325.00
      2901625.03      7050275.00
#Sta/Elev= 30
  4317.7  464.50  4476.9  455.32  4555.6  443.27  4603.0  439.57  4630.0  438.60
  4658.9  436.67  4671.0  437.30  4786.7  436.70  4803.7  437.19  4816.4  435.25
  4825.7  435.16  4831.7  436.42  4943.9  437.05  4979.7  437.39  4989.8  432.62
  4996.5  431.65  4997.0  430.85  5002.6  430.85  5003.1  431.65  5009.9  436.90
  5060.2  437.27  5079.8  438.60  5100.5  441.52  5110.5  445.01  5120.6  446.52
  5191.0  451.18  5211.1  454.18  5372.1  455.09  5408.9  457.29  5422.4  457.52
#Mann=8,-1,0
  4317.7    0.16       0  4603.0    0.12       0  4671.0    0.16       0
  4786.7    0.12       0  4943.9    0.16       0  4996.5    0.07       0
  5003.1    0.16       0  5408.9    0.05       0
Bank Sta=4630,5079.8
Exp/Cntr=0.3,0.1

Type RM Length L Ch R = 1,4983,350,350,350
BEGIN DESCRIPTION:
UNT 032 in Running Cr Watershed 6.0
END DESCRIPTION:
XS GIS Cut Line= 3
      2902825.03      7050325.02      2902075.00      7049825.00
      2901624.99      7049775.00
#Sta/Elev= 30
  4085.6  461.24  4135.2  458.20  4201.8  457.41  4247.0  455.78  4279.4  455.14
  4319.0  452.53  4396.6  447.32  4489.8  438.69  4551.7  435.69  4597.9  434.21
  4634.0  434.77  4655.0  432.99  4742.1  435.03  4849.5  434.71  4989.5  434.63
  4993.8  429.78  4994.3  428.98  5000.4  429.78  5007.1  430.51  5014.0  435.69
  5017.2  438.10  5027.3  441.11  5087.6  442.41  5126.0  439.35  5208.4  441.69
  5288.9  448.48  5315.3  453.09  5339.2  453.82  5399.5  452.76  5439.8  454.91
#Mann=9,-1,0
  4085.6    0.05       0  4201.8    0.16       0  4247.0    0.05       0
  4319.0    0.12       0  4849.5    0.16       0  4993.8    0.07       0
  5000.4    0.16       0  5126.0    0.05       0  5315.3    0.12       0
Bank Sta=4551.7,5014
Exp/Cntr=0.3,0.1

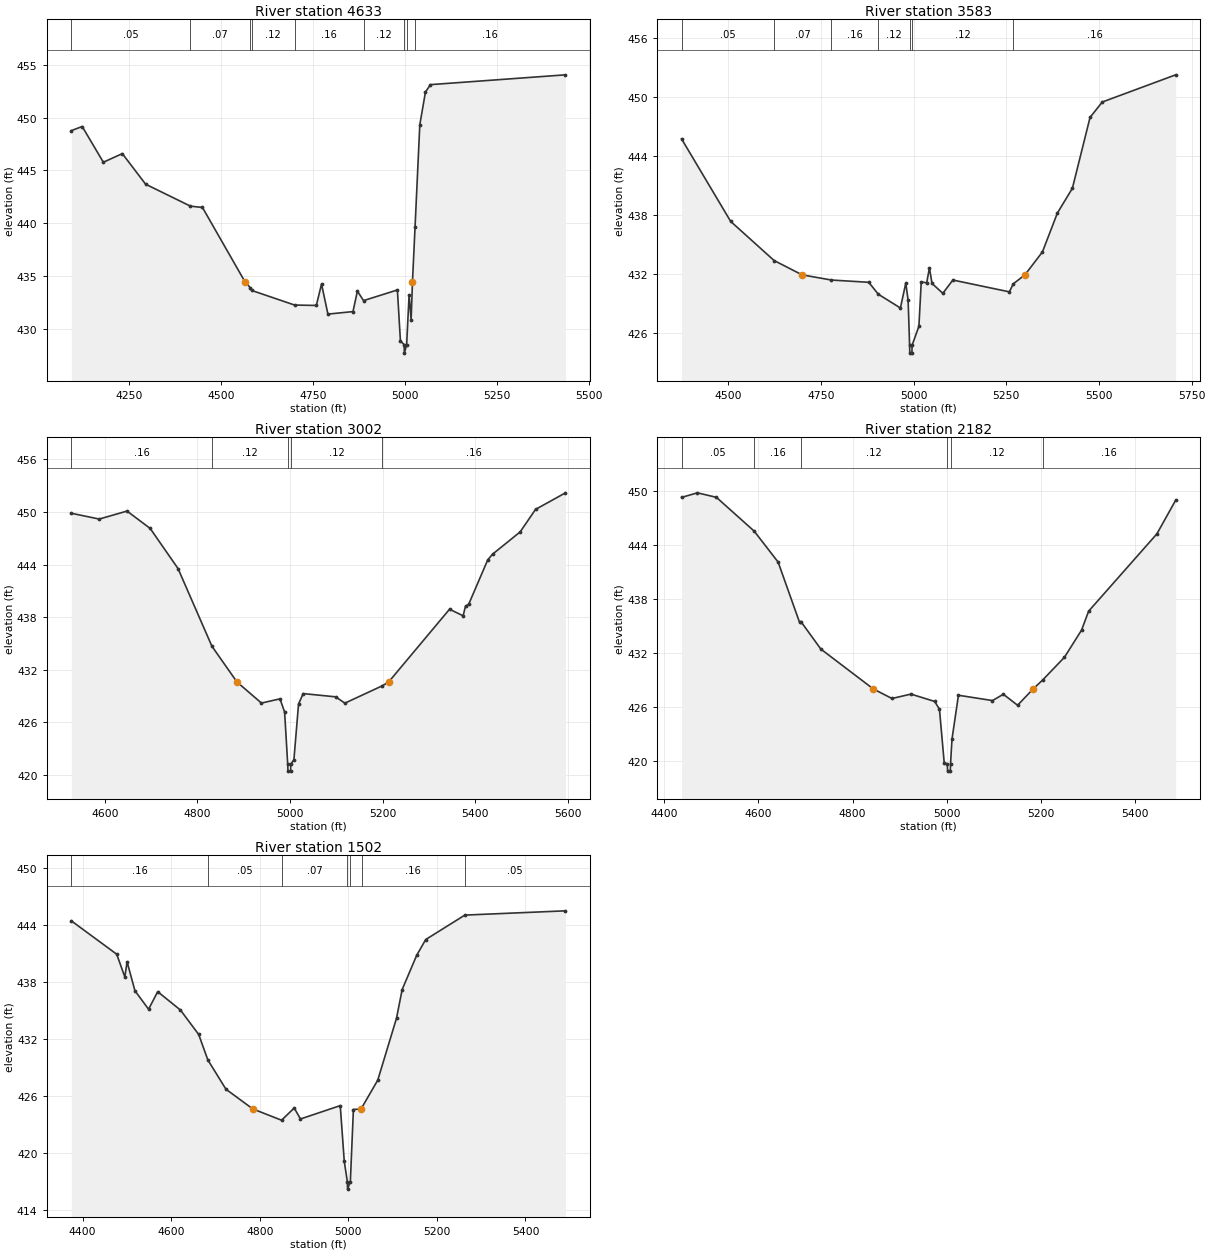
Type RM Length L Ch R = 1,4633,1050,1050,1050
BEGIN DESCRIPTION:
UNT 032 in Running Cr Watershed 5.0
END DESCRIPTION:
XS GIS Cut Line= 3
      2902954.53      7050006.07      2902367.19      7049627.78
      2901775.01      7049375.00
#Sta/Elev= 30
  4093.9  448.78  4123.3  449.17  4180.8  445.78  4232.3  446.60  4295.6  443.70
  4417.3  441.62  4450.1  441.49  4565.2  434.47  4579.8  433.89  4584.2  433.62
  4700.3  432.24  4759.4  432.20  4773.6  434.23  4790.9  431.38  4859.0  431.62
  4871.0  433.56  4887.7  432.66  4979.7  433.67  4987.9  428.85  4998.1  428.48
  4998.6  427.68  5004.8  428.48  5011.5  433.20  5017.0  430.85  5020.7  434.47
  5027.7  439.67  5040.6  449.34  5055.9  452.44  5069.6  453.14  5436.4  454.07
#Mann=9,-1,0
  4093.9    0.05       0  4417.3    0.07       0  4579.8    0.16       0
  4584.2    0.12       0  4700.3    0.16       0  4887.7    0.12       0
  4998.1    0.07       0  5004.8    0.12       0  5027.7    0.16       0
Bank Sta=4565.2,5020.7
Exp/Cntr=0.3,0.1

Type RM Length L Ch R = 1,3583,581,581,581
BEGIN DESCRIPTION:
UNT 032 in Running Cr Watershed 4.0
END DESCRIPTION:
XS GIS Cut Line= 3
      2903037.86      7049688.36      2902537.85      7049026.90
      2902038.88      7048959.33
#Sta/Elev= 30
  4374.2  445.75  4506.7  437.37  4623.8  433.40  4699.1  431.95  4778.2  431.42
  4879.1  431.19  4904.9  429.98  4964.5  428.58  4979.0  431.11  4985.3  429.37
  4989.3  424.80  4989.8  424.00  4995.5  424.00  4996.0  424.80  5014.4  426.73
  5020.7  431.24  5035.3  431.13  5042.8  432.65  5049.8  431.07  5078.9  430.07
  5106.0  431.42  5258.3  430.22  5268.8  431.03  5300.4  431.95  5347.5  434.27
  5387.9  438.22  5428.3  440.73  5476.0  447.93  5509.0  449.49  5706.9  452.25
#Mann=7,-1,0
  4374.2    0.05       0  4623.8    0.07       0  4778.2    0.16       0
  4904.9    0.12       0  4989.3    0.07       0  4996.0    0.12       0
  5268.8    0.16       0
Bank Sta=4699.1,5300.4
Exp/Cntr=0.3,0.1

Type RM Length L Ch R = 1,3002,820,820,820
BEGIN DESCRIPTION:
UNT 032 in Running Cr Watershed 3.0
END DESCRIPTION:
XS GIS Cut Line= 3
      2903075.05      7048675.00      2902454.52      7048703.98
      2902022.25      7048813.35
#Sta/Elev= 30
  4527.8  449.85  4587.9  449.19  4648.0  450.10  4698.0  448.12  4758.1  443.55
  4831.3  434.69  4885.5  430.61  4938.3  428.21  4978.3  428.69  4988.3  427.19
  4995.0  421.25  4995.5  420.45  5001.2  420.45  5001.7  421.25  5008.4  421.76
  5018.4  428.10  5028.4  429.29  5098.5  428.92  5118.5  428.20  5199.7  430.19
  5212.9  430.61  5344.5  438.91  5373.8  438.16  5379.0  439.26  5385.8  439.47
  5427.0  444.54  5437.3  445.18  5496.9  447.72  5530.2  450.29  5594.9  452.18
#Mann=5,-1,0
  4527.8    0.16       0  4831.3    0.12       0  4995.0    0.07       0
  5001.7    0.12       0  5199.7    0.16       0
Bank Sta=4885.5,5212.9
Exp/Cntr=0.3,0.1

Type RM Length L Ch R = 1,2182,680,680,680
BEGIN DESCRIPTION:
UNT 032 in Running Cr Watershed 2.0
END DESCRIPTION:
XS GIS Cut Line= 3
      2902928.43      7048250.85      2902256.60      7048167.52
      2901944.60      7048370.33
#Sta/Elev= 30
  4437.0  449.27  4470.7  449.78  4511.0  449.28  4591.2  445.52  4642.0  442.08
  4687.5  435.38  4690.7  435.44  4732.7  432.40  4844.2  427.96  4883.8  426.90
  4924.1  427.39  4974.5  426.57  4984.6  425.70  4994.7  419.74  5001.3  419.62
  5001.8  418.82  5007.6  418.82  5008.1  419.62  5011.2  422.38  5024.9  427.26
  5097.2  426.67  5120.2  427.37  5150.5  426.15  5183.4  427.96  5203.6  428.95
  5250.0  431.49  5286.2  434.50  5301.4  436.62  5446.3  445.22  5486.1  448.96
#Mann=6,-1,0
  4437.0    0.05       0  4591.2    0.16       0  4690.7    0.12       0
  5001.3    0.07       0  5008.1    0.12       0  5203.6    0.16       0
Bank Sta=4844.2,5183.4
Exp/Cntr=0.3,0.1

Type RM Length L Ch R = 1,1502,0,0,0
BEGIN DESCRIPTION:
UNT 032 in Running Cr Watershed 1.0
END DESCRIPTION:
XS GIS Cut Line= 3
      2902834.70      7047688.35      2902105.56      7047516.48
      2901741.00      7047552.94
#Sta/Elev= 30
  4374.8  444.46  4477.2  440.94  4495.5  438.54  4500.6  440.14  4518.3  437.09
  4549.1  435.14  4569.7  436.99  4621.1  435.05  4662.2  432.48  4682.9  429.79
  4723.8  426.70  4784.4  424.62  4849.3  423.43  4877.9  424.72  4892.0  423.56
  4981.8  424.97  4990.9  419.08  4997.8  416.96  4998.3  416.16  5004.6  416.96
  5011.5  424.56  5029.1  424.62  5029.8  424.70  5066.5  427.66  5108.8  434.19
  5121.6  437.22  5154.4  440.83  5174.7  442.49  5263.1  445.07  5490.3  445.52
#Mann=7,-1,0
  4374.8    0.16       0  4682.9    0.05       0  4849.3    0.07       0
  4997.8    0.07       0  5004.6    0.07       0  5029.8    0.16       0
  5263.1    0.05       0
Bank Sta=4784.4,5029.1
Exp/Cntr=0.3,0.1

Chan Stop Cuts=-1