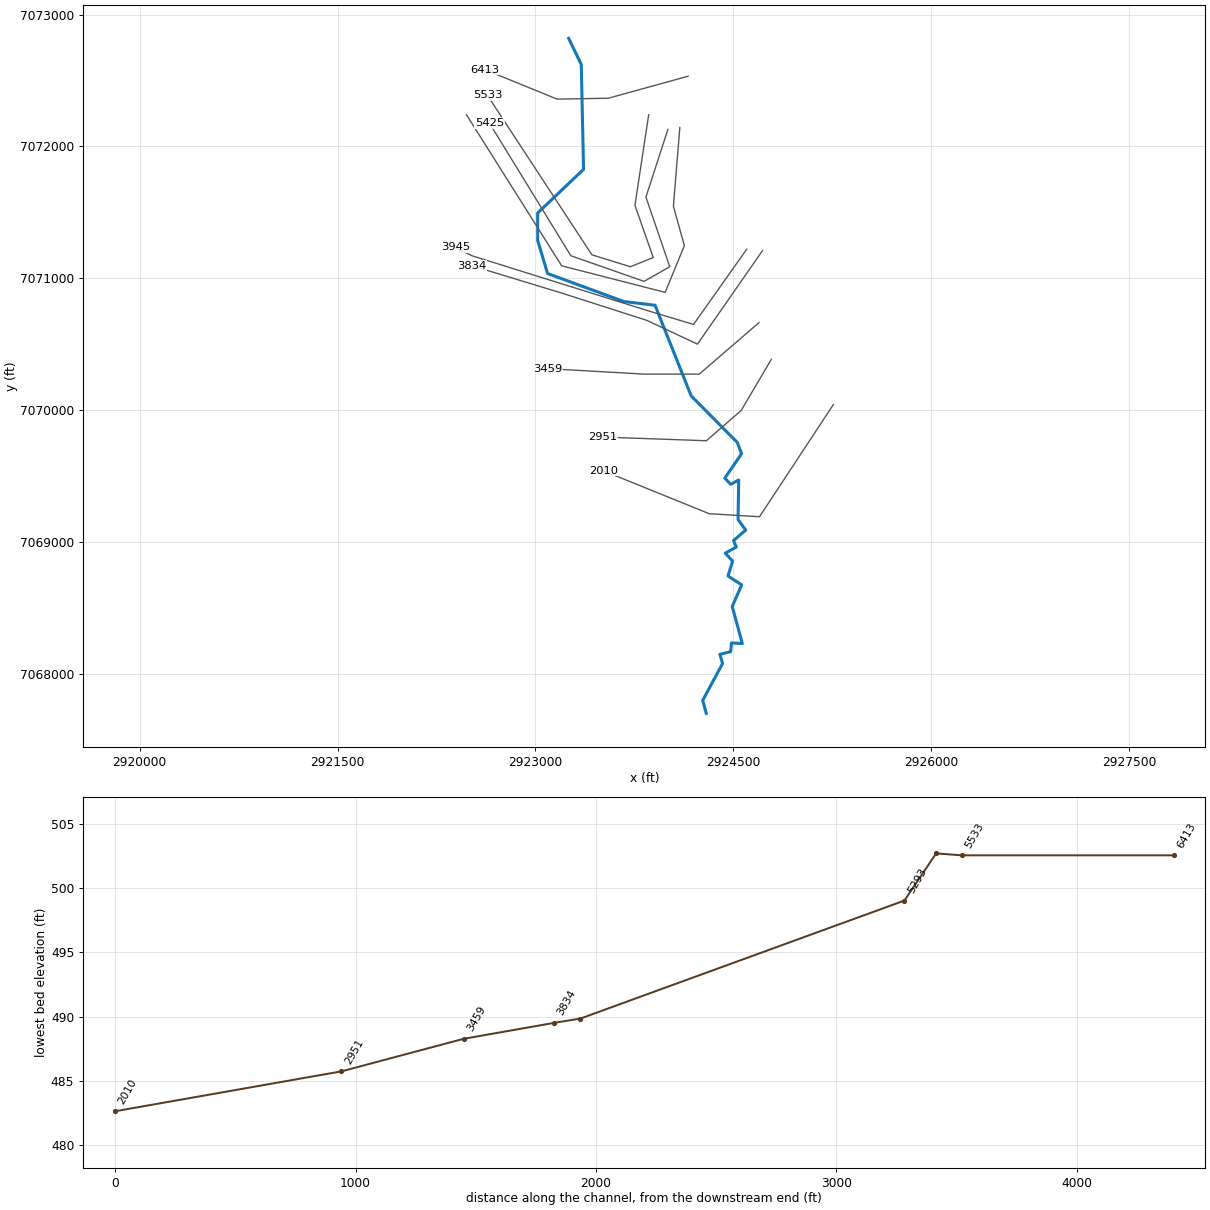
--- UNT 033 in Running Cr Watershed.prj (project) ---

Proj Title=UNT 033 in Running Cr Watershed Base Level Engineering
Current Plan=p01
Default Exp/Contr=0.3,0.1
English Units
Geom File=g01
Flow File=f01
Plan File=p01
BEGIN DESCRIPTION:
UNT 033 in Running Cr Watershed
END DESCRIPTION:

--- UNT 033 in Running Cr Watershed.p01 (plan) ---

Plan Title=Multiple Run
Short Identifier=Multiple
Geom File=g01
Flow File=f01
Subcritical Flow
K Sum by GR= 0
Std Step Tol= 0.01
Critical Tol= 0.01
Num of Std Step Trials= 20
Max Error Tol= 0.3
Flow Tol Ratio= 0.001
Split Flow NTrial= 30
Split Flow Tol= 0.02
Split Flow Ratio= 0.02
Log Output Level= 0
Friction Slope Method= 1
Unsteady Friction Slope Method= 2
Unsteady Bridges Friction Slope Method= 1
Parabolic Critical Depth
Global Vel Dist=  1 , 1 , 1
Global Log Level= 0
CheckData=True
Encroach Param= -1, 0, 0, 0
BEGIN DESCRIPTION:
Multiple Run
END DESCRIPTION:

--- UNT 033 in Running Cr Watershed.f01 (steady flow) ---

Flow Title=Multiple
Number of Profiles=7
Profile Names=10-year,25-year,50-year,1pct_min,100-year,1pct_plu,500-year
River Rch & RM= UNT 033 in Runni,Reach-1,6413
     752    1004    1206     719    1434    2861    2020
River Rch & RM= UNT 033 in Runni,Reach-1,3945
     975    1319    1599     960    1916    3822    2743
Boundary for River Rch & Prof#=UNT 033 in Runni,Reach-1,1
Up Type=0
Dn Type=3
Dn Slope=0.005
Boundary for River Rch & Prof#=UNT 033 in Runni,Reach-1,2
Up Type=0
Dn Type=3
Dn Slope=0.005
Boundary for River Rch & Prof#=UNT 033 in Runni,Reach-1,3
Up Type=0
Dn Type=3
Dn Slope=0.005
Boundary for River Rch & Prof#=UNT 033 in Runni,Reach-1,4
Up Type=0
Dn Type=3
Dn Slope=0.005
Boundary for River Rch & Prof#=UNT 033 in Runni,Reach-1,5
Up Type=0
Dn Type=3
Dn Slope=0.005
Boundary for River Rch & Prof#=UNT 033 in Runni,Reach-1,6
Up Type=0
Dn Type=3
Dn Slope=0.005
Boundary for River Rch & Prof#=UNT 033 in Runni,Reach-1,7
Up Type=0
Dn Type=3
Dn Slope=0.005

--- UNT 033 in Running Cr Watershed.g01 (geometry) ---

Geom Title=Existing Conditions

River Reach=UNT 033 in Runni,Reach-1
Reach XY= 30
      2923252.30      7072819.35      2923347.99      7072620.90
      2923365.21      7071825.87      2923017.35      7071495.11
      2923017.51      7071286.51      2923092.41      7071035.96
      2923671.65      7070823.27      2923907.38      7070795.56
      2924181.02      7070108.24      2924531.41      7069754.71
      2924563.34      7069669.20      2924436.59      7069485.18
      2924480.94      7069437.56      2924541.78      7069470.13
      2924536.65      7069171.26      2924594.81      7069090.25
      2924502.67      7069011.69      2924523.65      7068961.45
      2924439.69      7068915.96      2924495.33      7068855.35
      2924460.54      7068742.54      2924564.14      7068675.27
      2924492.65      7068511.02      2924569.26      7068230.39
      2924487.07      7068235.07      2924480.83      7068168.79
      2924399.41      7068148.47      2924419.04      7068078.12
      2924268.81      7067799.53      2924295.59      7067700.71

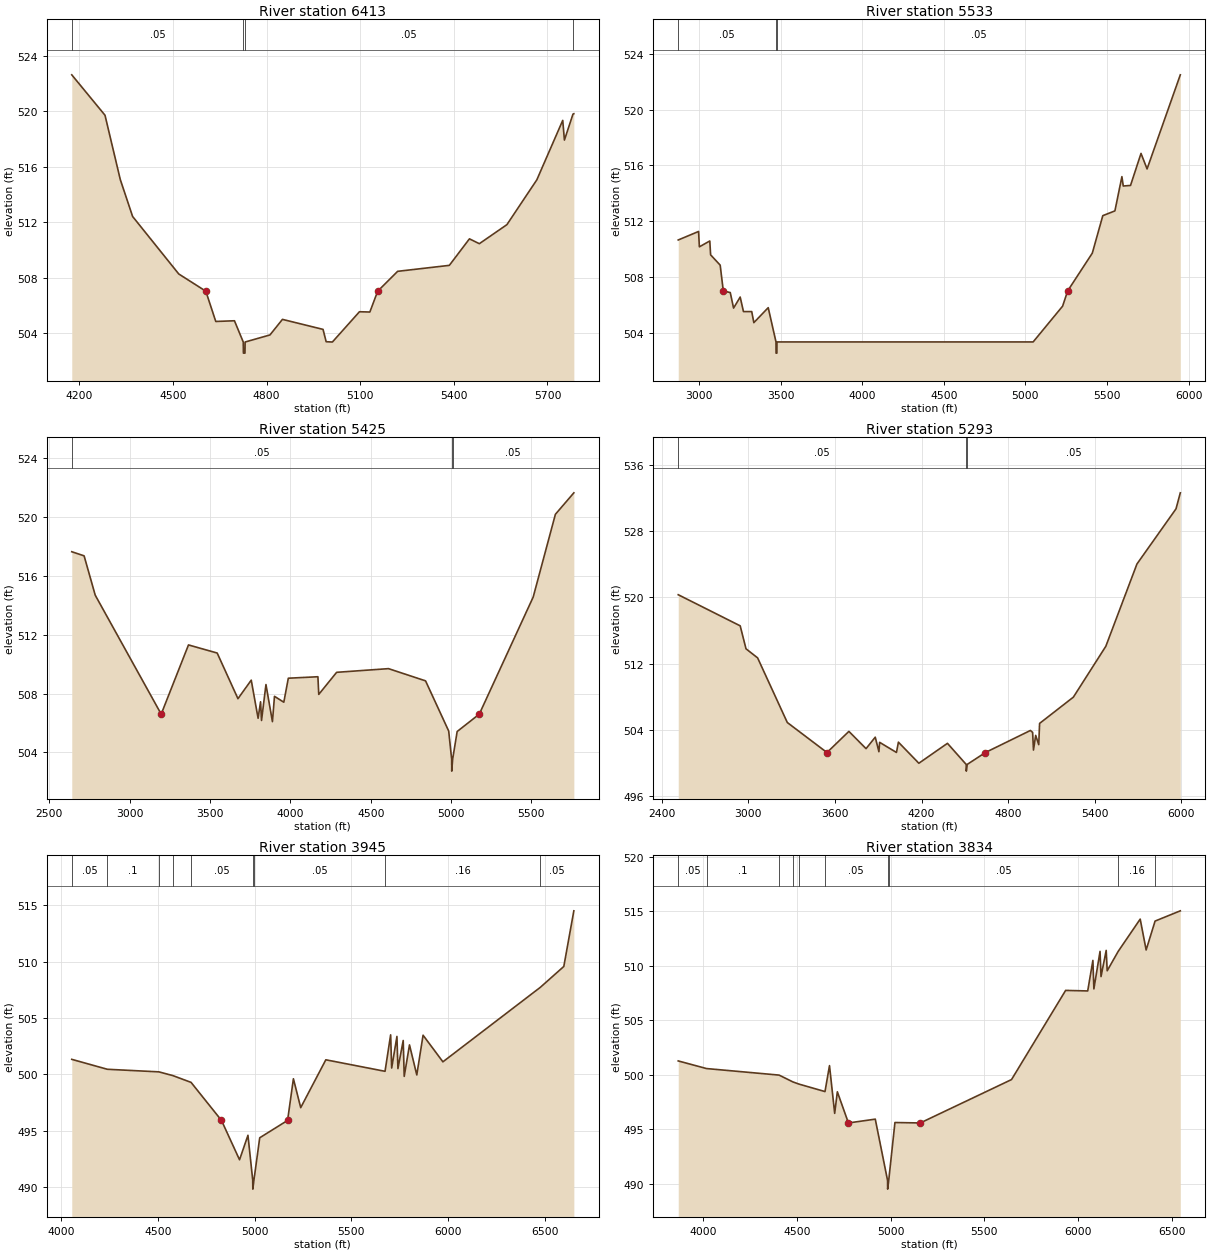
Type RM Length L Ch R = 1,6413,880,880,880
BEGIN DESCRIPTION:
UNT 033 in Running Cr Watershed 3.0
END DESCRIPTION:
XS GIS Cut Line= 4
      2924157.67      7072531.96      2923553.54      7072365.30
      2923164.65      7072358.36      2922615.25      7072582.72
#Sta/Elev= 30
  4175.4  522.62  4281.9  519.71  4330.9  515.08  4370.4  512.42  4518.3  508.28
  4605.0  507.04  4636.9  504.86  4696.8  504.91  4725.0  503.38  4725.5  502.58
  4730.5  502.58  4731.0  503.38  4810.6  503.89  4850.6  505.01  4980.7  504.29
  4990.7  503.40  5010.7  503.38  5097.4  505.56  5130.7  505.54  5155.9  507.04
  5219.8  508.47  5385.5  508.90  5449.9  510.81  5481.6  510.46  5569.9  511.83
  5665.9  515.06  5748.9  519.34  5754.3  517.92  5781.7  519.79  5784.5  519.82
#Mann=4,-1,0
  4175.4    0.05       0  4725.0    0.03       0  4731.0    0.05       0
  5781.7    0.08       0
Bank Sta=4605,5155.9
Exp/Cntr=0.3,0.1

Type RM Length L Ch R = 1,5533,108,108,108
BEGIN DESCRIPTION:
Mapping XS e960d586
END DESCRIPTION:
XS GIS Cut Line= 6
      2923859.10      7072240.30      2923754.93      7071552.80
      2923893.82      7071156.97      2923720.21      7071087.53
      2923428.54      7071177.80      2922636.89      7072386.11
#Sta/Elev= 30
  2872.5  510.67  2997.1  511.28  3002.1  510.18  3065.9  510.60  3070.9  509.61
  3129.6  508.87  3148.6  507.03  3191.4  506.91  3211.6  505.80  3252.1  506.59
  3272.3  505.55  3322.9  505.55  3335.9  504.76  3424.0  505.83  3471.6  503.38
  3472.1  502.58  3477.1  502.58  3477.6  503.38  5047.5  503.38  5228.2  505.94
  5259.1  507.03  5410.1  509.73  5474.4  512.41  5548.6  512.75  5591.5  515.20
  5599.8  514.53  5644.3  514.57  5708.6  516.86  5745.7  515.75  5949.4  522.48
#Mann=3,-1,0
  2872.5    0.05       0  3471.6    0.03       0  3477.6    0.05       0
Bank Sta=3148.6,5259.1
Exp/Cntr=0.3,0.1

Type RM Length L Ch R = 1,5425,132,132,132
BEGIN DESCRIPTION:
Mapping XS b1451fe5
END DESCRIPTION:
XS GIS Cut Line= 6
      2924004.93      7072129.17      2923838.27      7071615.30
      2924018.82      7071087.53      2923824.38      7070976.41
      2923268.82      7071170.86      2922650.75      7072177.83
#Sta/Elev= 30
  2639.1  517.63  2715.9  517.35  2785.1  514.68  3195.8  506.60  3365.7  511.30
  3544.4  510.75  3673.7  507.65  3756.4  508.91  3799.0  506.32  3814.4  507.44
  3820.3  506.17  3848.0  508.61  3888.3  506.09  3901.0  507.81  3959.1  507.41
  3987.2  509.04  4171.4  509.14  4176.6  507.94  4288.0  509.44  4610.8  509.69
  4841.5  508.86  4985.6  505.45  5004.0  503.53  5004.5  502.73  5010.0  503.53
  5038.2  505.42  5176.0  506.60  5511.5  514.55  5649.7  520.17  5764.6  521.63
#Mann=3,-1,0
  2639.1    0.05       0  5004.0    0.03       0  5010.0    0.05       0
Bank Sta=3195.8,5176
Exp/Cntr=0.3,0.1

Type RM Length L Ch R = 1,5293,1348,1348,1348
BEGIN DESCRIPTION:
Mapping XS 5f0405ba
END DESCRIPTION:
XS GIS Cut Line= 6
      2924095.21      7072143.06      2924046.60      7071545.86
      2924129.93      7071247.25      2923984.10      7070893.08
      2923199.38      7071094.47      2922477.25      7072240.15
#Sta/Elev= 30
  2513.8  520.31  2943.0  516.56  2983.4  513.79  3063.7  512.70  3269.4  504.91
  3544.3  501.29  3696.1  503.84  3815.0  501.76  3878.7  503.14  3904.1  501.39
  3909.1  502.52  4025.7  501.30  4039.2  502.54  4180.8  500.00  4378.9  502.40
  4509.1  499.85  4509.6  499.05  4515.1  499.85  4641.7  501.29  4953.7  503.95
  4969.0  503.72  4974.9  501.59  4990.2  503.36  5011.4  502.24  5017.3  504.80
  5251.5  507.97  5476.3  514.10  5691.7  524.01  5962.4  530.66  5992.2  532.59
#Mann=3,-1,0
  2513.8    0.05       0  4509.1    0.03       0  4515.1    0.05       0
Bank Sta=3544.3,4641.7
Exp/Cntr=0.3,0.1

Type RM Length L Ch R = 1,3945,111,111,111
BEGIN DESCRIPTION:
Mapping XS 19b4e1e7
END DESCRIPTION:
XS GIS Cut Line= 5
      2924602.17      7071219.50      2924199.38      7070650.03
      2923852.15      7070754.19      2922518.82      7071170.86
      2922393.83      7071233.35
#Sta/Elev= 30
  4054.8  501.34  4238.8  500.46  4505.6  500.23  4577.5  499.90  4671.7  499.30
  4829.1  495.93  4922.5  492.44  4966.0  494.61  4990.7  490.64  4991.2  489.84
  4996.9  490.64  5026.9  494.39  5171.0  495.93  5201.1  499.62  5238.9  497.06
  5368.8  501.30  5675.0  500.28  5704.0  503.51  5709.3  500.57  5736.5  503.37
  5741.7  500.52  5769.0  503.01  5774.2  499.83  5801.5  502.62  5839.2  499.96
  5871.7  503.48  5974.3  501.12  6478.1  507.72  6599.6  509.57  6651.5  514.50
#Mann=9,-1,0
  4054.8    0.05       0  4238.8     0.1       0  4505.6    0.16       0
  4577.5     0.1       0  4671.7    0.05       0  4990.7    0.03       0
  4996.9    0.05       0  5675.0    0.16       0  6478.1    0.05       0
Bank Sta=4829.1,5171
Exp/Cntr=0.3,0.1

Type RM Length L Ch R = 1,3834,375,375,375
BEGIN DESCRIPTION:
Mapping XS b1a06c4d
END DESCRIPTION:
XS GIS Cut Line= 5
      2924721.93      7071209.04      2924228.89      7070500.72
      2923843.47      7070681.28      2923204.59      7070886.14
      2922520.57      7071094.47
#Sta/Elev= 30
  3868.9  501.26  4019.7  500.56  4406.3  499.96  4480.3  499.33  4513.1  499.13
  4650.7  498.45  4674.7  500.83  4702.3  496.45  4716.5  498.43  4775.5  495.57
  4918.6  495.92  4984.0  490.30  4984.5  489.50  4990.2  490.30  5023.3  495.61
  5158.2  495.57  5644.4  499.55  5932.6  507.73  6050.2  507.68  6077.8  510.48
  6083.1  507.87  6115.9  511.31  6121.1  509.00  6148.7  511.40  6154.0  509.53
  6212.6  511.31  6329.8  514.27  6361.5  511.44  6409.1  514.09  6543.5  515.03
#Mann=10,-1,0
  3868.9    0.05       0  4019.7     0.1       0  4406.3    0.05       0
  4480.3     0.1       0  4513.1    0.16       0  4650.7    0.05       0
  4984.0    0.03       0  4990.2    0.05       0  6212.6    0.16       0
  6409.1    0.05       0
Bank Sta=4775.5,5158.2
Exp/Cntr=0.3,0.1

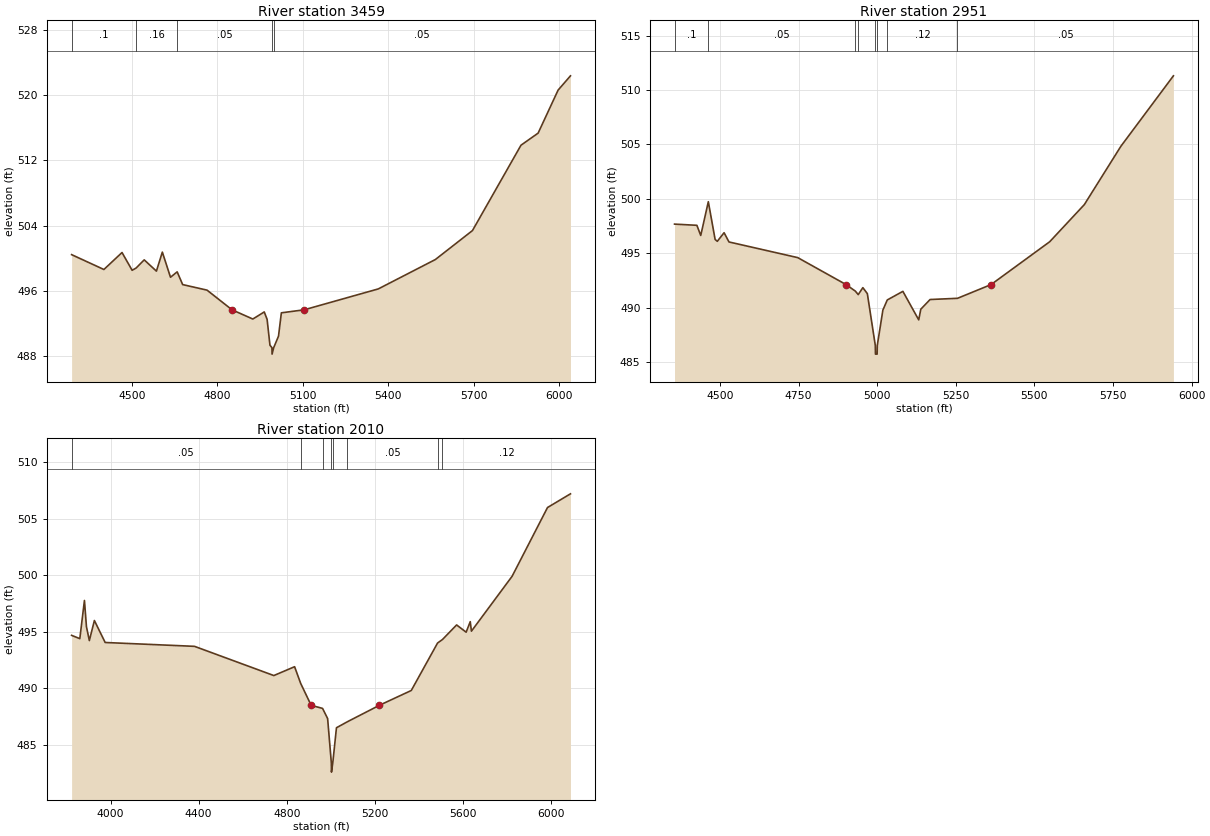
Type RM Length L Ch R = 1,3459,508,508,508
BEGIN DESCRIPTION:
Mapping XS e86518d9
END DESCRIPTION:
XS GIS Cut Line= 4
      2924695.88      7070663.89      2924242.78      7070273.29
      2923820.90      7070273.29      2923091.69      7070314.96
#Sta/Elev= 30
  4288.4  500.45  4401.7  498.63  4465.3  500.71  4500.8  498.53  4514.7  498.81
  4543.2  499.81  4586.0  498.43  4606.8  500.76  4635.4  497.68  4658.8  498.34
  4678.1  496.78  4763.7  496.10  4851.3  493.69  4924.4  492.56  4964.4  493.43
  4974.4  492.52  4984.4  489.35  4991.3  489.06  4991.8  488.26  4997.6  489.06
  5014.4  490.46  5024.4  493.32  5104.4  493.69  5364.5  496.25  5564.8  499.85
  5695.0  503.40  5865.3  513.86  5925.4  515.34  5995.5  520.61  6038.9  522.36
#Mann=5,-1,0
  4288.4     0.1       0  4514.7    0.16       0  4658.8    0.05       0
  4991.3    0.03       0  4997.6    0.05       0
Bank Sta=4851.3,5104.4
Exp/Cntr=0.3,0.1

Type RM Length L Ch R = 1,2951,941,941,941
BEGIN DESCRIPTION:
UNT 033 in Running Cr Watershed 2.0
END DESCRIPTION:
XS GIS Cut Line= 4
      2924789.67      7070386.17      2924560.49      7069997.25
      2924296.60      7069768.08      2923511.92      7069795.86
#Sta/Elev= 30
  4355.9  497.67  4426.9  497.56  4439.2  496.63  4463.3  499.73  4484.9  496.26
  4491.9  496.09  4513.4  496.88  4529.0  496.03  4747.6  494.59  4901.4  492.11
  4930.8  491.51  4939.9  491.19  4954.6  491.83  4968.9  491.28  4994.2  486.52
  4994.7  485.72  5000.0  485.72  5000.5  486.52  5018.3  489.77  5032.3  490.70
  5081.9  491.49  5132.2  488.87  5138.9  489.85  5168.4  490.74  5255.5  490.85
  5362.1  492.11  5548.7  496.05  5658.7  499.46  5775.1  504.83  5942.0  511.30
#Mann=8,-1,0
  4355.9     0.1       0  4463.3    0.05       0  4930.8    0.12       0
  4939.9    0.07       0  4994.2    0.07       0  5000.5    0.07       0
  5032.3    0.12       0  5255.5    0.05       0
Bank Sta=4901.4,5362.1
Exp/Cntr=0.3,0.1

Type RM Length L Ch R = 1,2010,0,0,0
BEGIN DESCRIPTION:
UNT 033 in Running Cr Watershed 1.0
END DESCRIPTION:
XS GIS Cut Line= 4
      2925259.68      7070042.34      2924699.38      7069191.69
      2924318.30      7069214.70      2923515.62      7069540.11
#Sta/Elev= 30
  3822.7  494.69  3860.0  494.40  3881.0  497.77  3890.1  495.46  3903.3  494.23
  3926.2  496.00  3975.2  494.06  4381.0  493.72  4741.5  491.14  4835.8  491.92
  4863.4  490.45  4911.0  488.51  4962.8  488.24  4985.9  487.34  5002.8  483.41
  5003.3  482.61  5009.2  483.41  5026.0  486.53  5075.7  487.06  5220.8  488.51
  5365.9  489.82  5485.3  494.01  5507.5  494.32  5571.9  495.61  5615.2  494.97
  5633.9  495.90  5639.2  495.06  5824.1  499.91  5984.9  505.98  6089.2  507.19
#Mann=8,-1,0
  3822.7    0.05       0  4863.4    0.16       0  4962.8    0.07       0
  5002.8    0.07       0  5009.2    0.07       0  5075.7    0.05       0
  5485.3    0.16       0  5507.5    0.12       0
Bank Sta=4911,5220.8
Exp/Cntr=0.3,0.1

Chan Stop Cuts=-1