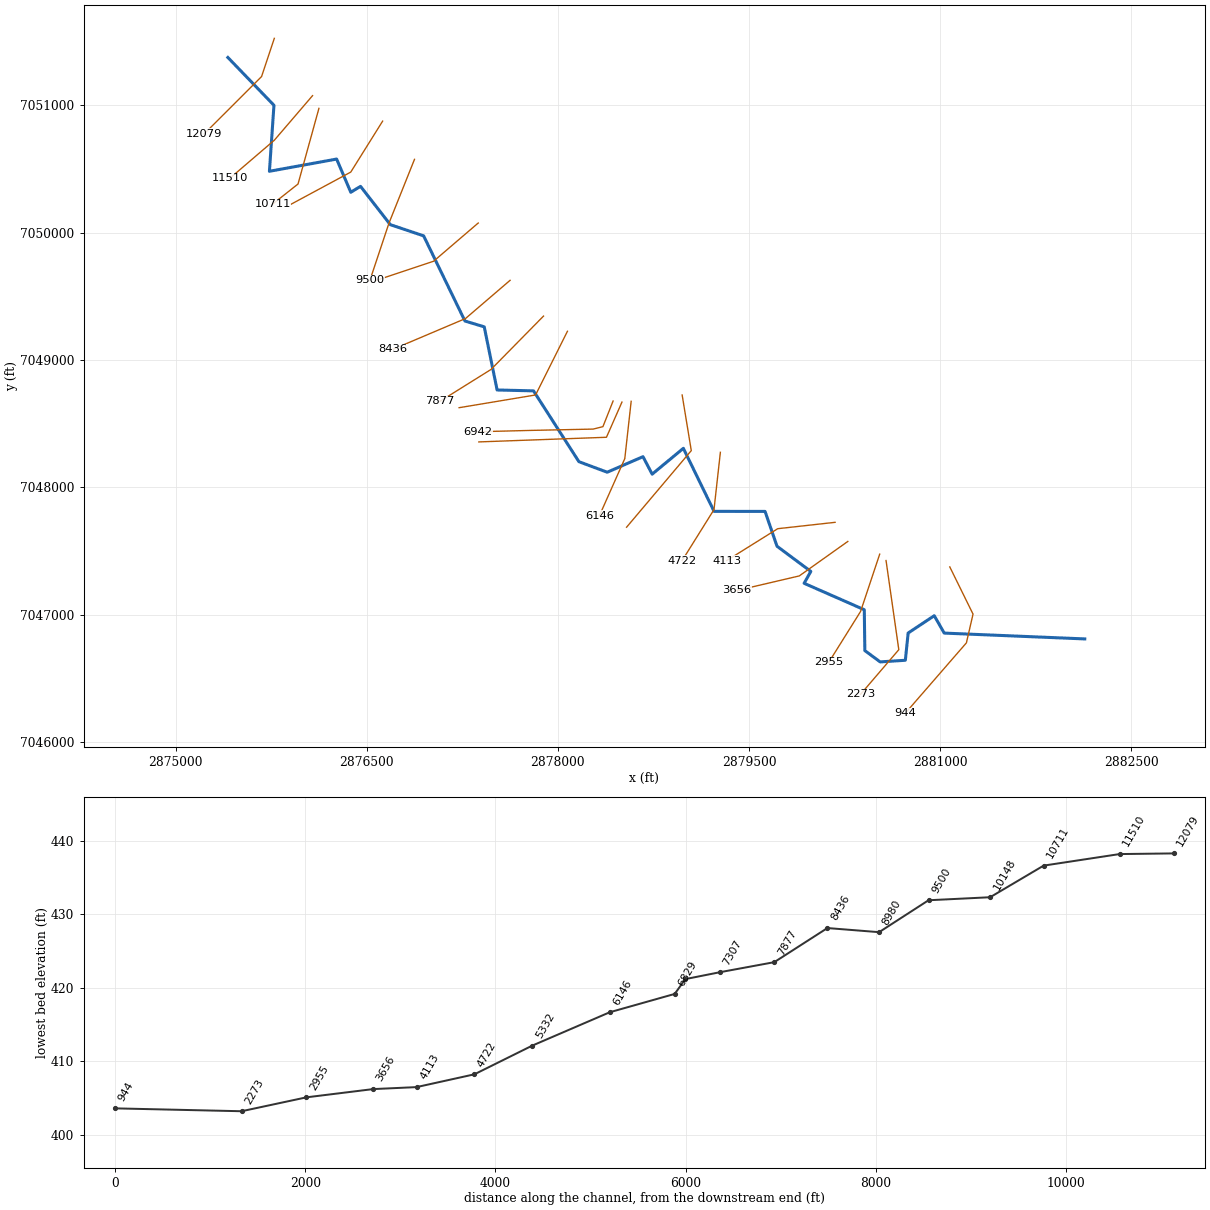
--- UNT 034 in Running Cr Watershed.prj (project) ---

Proj Title=UNT 034 in Running Cr Watershed Base Level Engineering
Current Plan=p01
Default Exp/Contr=0.3,0.1
English Units
Geom File=g01
Flow File=f01
Plan File=p01
BEGIN DESCRIPTION:
UNT 034 in Running Cr Watershed
END DESCRIPTION:

--- UNT 034 in Running Cr Watershed.p01 (plan) ---

Plan Title=Multiple Run
Short Identifier=Multiple
Geom File=g01
Flow File=f01
Subcritical Flow
K Sum by GR= 0
Std Step Tol= 0.01
Critical Tol= 0.01
Num of Std Step Trials= 20
Max Error Tol= 0.3
Flow Tol Ratio= 0.001
Split Flow NTrial= 30
Split Flow Tol= 0.02
Split Flow Ratio= 0.02
Log Output Level= 0
Friction Slope Method= 1
Unsteady Friction Slope Method= 2
Unsteady Bridges Friction Slope Method= 1
Parabolic Critical Depth
Global Vel Dist=  1 , 1 , 1
Global Log Level= 0
CheckData=True
Encroach Param= -1, 0, 0, 0
BEGIN DESCRIPTION:
Multiple Run
END DESCRIPTION:

--- UNT 034 in Running Cr Watershed.f01 (steady flow) ---

Flow Title=Multiple
Number of Profiles=7
Profile Names=10-year,25-year,50-year,1pct_min,100-year,1pct_plu,500-year
River Rch & RM= UNT 034 in Runni,Reach-1,12079
     514     679     811     482     961    1918    1351
River Rch & RM= UNT 034 in Runni,Reach-1,11510
     734     989    1196     718    1433    2860    2062
River Rch & RM= UNT 034 in Runni,Reach-1,4113
     939    1279    1558     942    1879    3749    2738
Boundary for River Rch & Prof#=UNT 034 in Runni,Reach-1,1
Up Type=0
Dn Type=3
Dn Slope=0.005
Boundary for River Rch & Prof#=UNT 034 in Runni,Reach-1,2
Up Type=0
Dn Type=3
Dn Slope=0.005
Boundary for River Rch & Prof#=UNT 034 in Runni,Reach-1,3
Up Type=0
Dn Type=3
Dn Slope=0.005
Boundary for River Rch & Prof#=UNT 034 in Runni,Reach-1,4
Up Type=0
Dn Type=3
Dn Slope=0.005
Boundary for River Rch & Prof#=UNT 034 in Runni,Reach-1,5
Up Type=0
Dn Type=3
Dn Slope=0.005
Boundary for River Rch & Prof#=UNT 034 in Runni,Reach-1,6
Up Type=0
Dn Type=3
Dn Slope=0.005
Boundary for River Rch & Prof#=UNT 034 in Runni,Reach-1,7
Up Type=0
Dn Type=3
Dn Slope=0.005

--- UNT 034 in Running Cr Watershed.g01 (geometry) ---

Geom Title=Existing Conditions

River Reach=UNT 034 in Runni,Reach-1
Reach XY= 30
      2875410.63      7051374.75      2875772.18      7050999.27
      2875736.61      7050481.20      2876263.97      7050577.10
      2876374.92      7050316.27      2876451.37      7050362.83
      2876685.19      7050062.08      2876946.59      7049974.25
      2877270.72      7049305.62      2877422.21      7049259.78
      2877523.18      7048764.14      2877808.74      7048757.09
      2878164.84      7048201.25      2878387.16      7048118.34
      2878667.78      7048240.55      2878739.75      7048103.21
      2878984.48      7048305.99      2879225.37      7047811.14
      2879625.59      7047810.71      2879719.37      7047537.16
      2879984.65      7047339.56      2879932.03      7047246.40
      2880404.20      7047038.76      2880408.47      7046718.05
      2880528.64      7046629.16      2880726.33      7046641.96
      2880748.38      7046856.01      2880953.17      7046991.83
      2881031.39      7046855.30      2882133.92      7046809.60

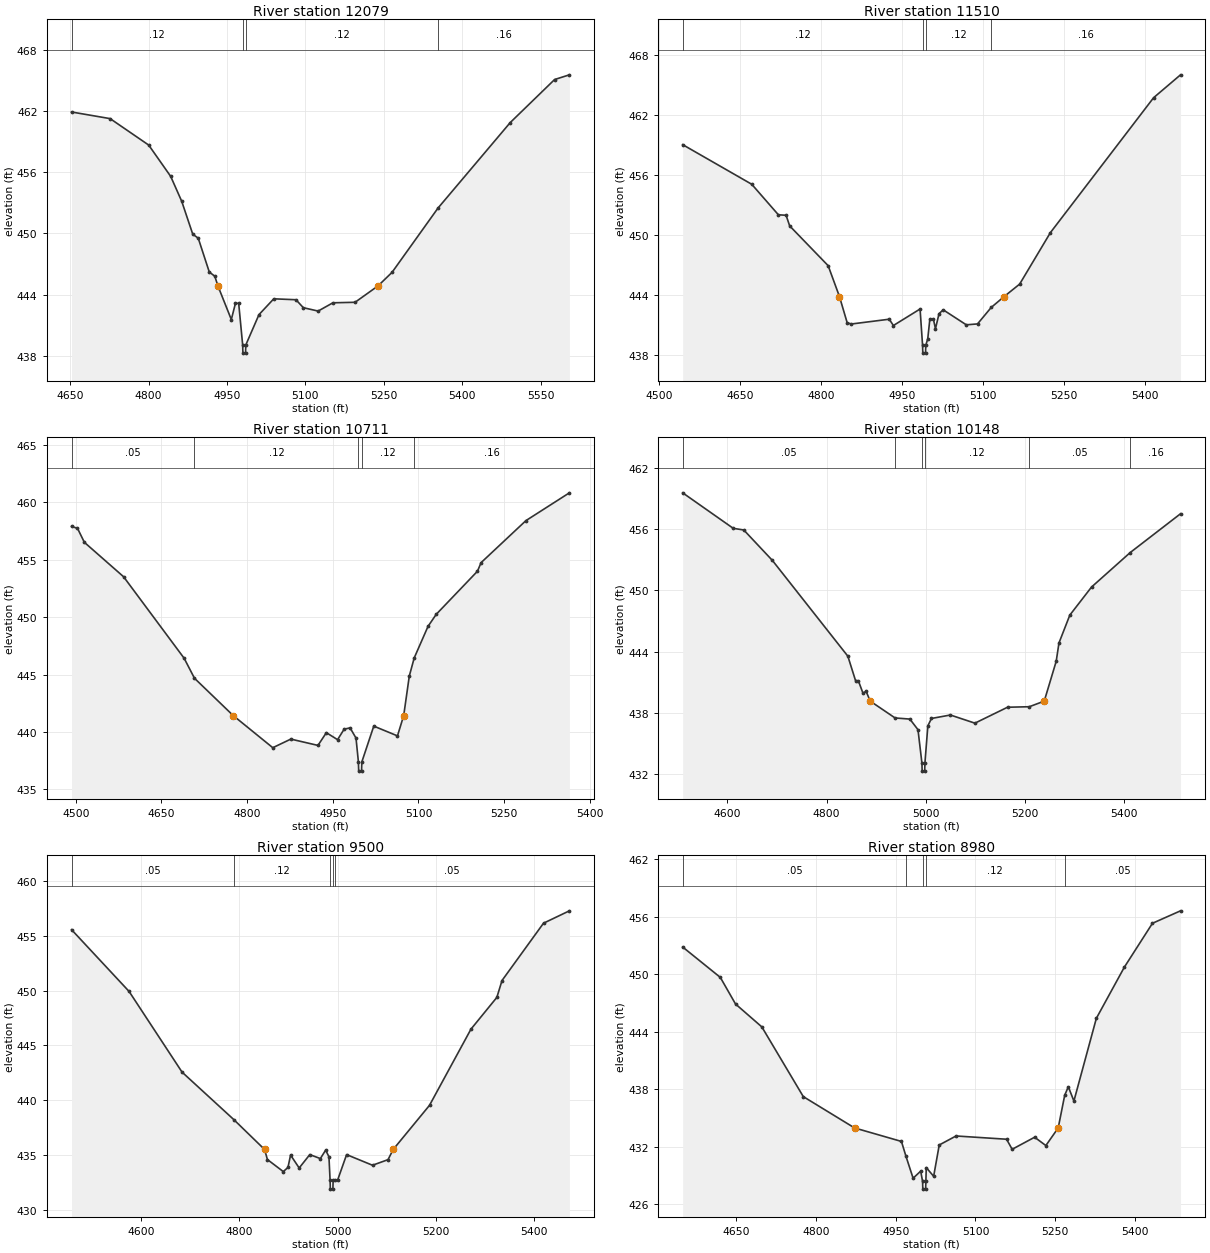
Type RM Length L Ch R = 1,12079,569,569,569
BEGIN DESCRIPTION:
UNT 034 in Running Cr Watershed 18.0
END DESCRIPTION:
XS GIS Cut Line= 3
      2875775.00      7051524.99      2875675.00      7051225.00
      2875225.01      7050775.01
#Sta/Elev= 30
  4652.7  461.88  4726.5  461.23  4800.3  458.64  4842.4  455.57  4863.5  453.13
  4884.6  449.91  4895.1  449.52  4916.2  446.21  4926.8  445.79  4932.7  444.85
  4958.4  441.55  4966.3  443.14  4972.5  443.14  4980.1  439.06  4980.6  438.26
  4985.6  438.26  4986.1  439.06  5011.3  442.03  5039.6  443.58  5082.1  443.49
  5096.2  442.71  5124.5  442.38  5152.8  443.19  5195.2  443.24  5239.2  444.85
  5265.9  446.17  5353.9  452.47  5492.2  460.85  5577.0  465.06  5605.3  465.52
#Mann=4,-1,0
  4652.7    0.12       0  4980.1    0.07       0  4986.1    0.12       0
  5353.9    0.16       0
Bank Sta=4932.7,5239.2
Exp/Cntr=0.3,0.1

Type RM Length L Ch R = 1,11510,799,799,799
BEGIN DESCRIPTION:
UNT 034 in Running Cr Watershed 17.0
END DESCRIPTION:
XS GIS Cut Line= 3
      2876074.99      7051074.99      2875775.00      7050725.00
      2875425.03      7050425.03
#Sta/Elev= 30
  4543.4  459.01  4671.3  455.05  4720.6  452.00  4734.9  451.95  4741.5  450.89
  4812.8  446.91  4833.7  443.83  4848.0  441.21  4855.6  441.08  4925.9  441.56
  4933.6  440.93  4983.0  442.58  4987.6  438.97  4988.1  438.17  4993.1  438.17
  4993.6  438.97  4997.2  439.59  5001.1  441.56  5007.7  441.56  5011.5  440.61
  5018.1  442.11  5025.8  442.50  5068.6  441.00  5089.4  441.09  5114.8  442.74
  5138.8  443.83  5167.4  445.07  5224.4  450.22  5415.4  463.70  5465.3  465.99
#Mann=4,-1,0
  4543.4    0.12       0  4987.6    0.07       0  4993.6    0.12       0
  5114.8    0.16       0
Bank Sta=4833.7,5138.8
Exp/Cntr=0.3,0.1

Type RM Length L Ch R = 1,10711,563,563,563
BEGIN DESCRIPTION:
UNT 034 in Running Cr Watershed 16.0
END DESCRIPTION:
XS GIS Cut Line= 3
      2876125.01      7050975.02      2875961.13      7050381.42
      2875760.63      7050222.58
#Sta/Elev= 30
  4492.6  457.91  4503.0  457.75  4515.0  456.53  4583.7  453.53  4689.7  446.43
  4707.8  444.69  4775.6  441.44  4844.9  438.64  4876.5  439.39  4924.0  438.84
  4938.7  439.95  4958.3  439.34  4969.8  440.25  4980.2  440.37  4990.6  439.48
  4994.8  437.40  4995.3  436.60  5000.3  436.60  5000.8  437.40  5021.7  440.52
  5063.2  439.67  5074.1  441.44  5083.9  444.88  5092.5  446.46  5116.7  449.21
  5131.1  450.26  5203.2  454.01  5209.6  454.76  5288.1  458.42  5364.2  460.84
#Mann=5,-1,0
  4492.6    0.05       0  4707.8    0.12       0  4994.8    0.07       0
  5000.8    0.12       0  5092.5    0.16       0
Bank Sta=4775.6,5074.1
Exp/Cntr=0.3,0.1

Type RM Length L Ch R = 1,10148,648,648,648
BEGIN DESCRIPTION:
UNT 034 in Running Cr Watershed 15.0
END DESCRIPTION:
XS GIS Cut Line= 3
      2876625.00      7050875.00      2876375.00      7050475.00
      2875906.47      7050222.58
#Sta/Elev= 30
  4509.8  459.57  4611.8  456.09  4633.0  455.93  4690.8  452.94  4842.9  443.56
  4858.3  441.18  4864.2  441.13  4873.6  439.91  4879.5  440.14  4888.0  439.16
  4938.1  437.51  4967.9  437.40  4984.3  436.36  4992.2  433.10  4992.7  432.30
  4997.8  432.30  4998.3  433.10  5004.2  436.74  5011.5  437.46  5049.6  437.80
  5099.1  437.00  5164.8  438.56  5208.7  438.61  5238.9  439.16  5263.0  443.06
  5268.6  444.86  5290.5  447.59  5334.3  450.34  5412.3  453.72  5513.7  457.52
#Mann=6,-1,0
  4509.8    0.05       0  4938.1    0.12       0  4992.2    0.07       0
  4998.3    0.12       0  5208.7    0.05       0  5412.3    0.16       0
Bank Sta=4888,5238.9
Exp/Cntr=0.3,0.1

Type RM Length L Ch R = 1,9500,520,520,520
BEGIN DESCRIPTION:
UNT 034 in Running Cr Watershed 14.0
END DESCRIPTION:
XS GIS Cut Line= 3
      2876875.01      7050575.01      2876675.00      7050075.00
      2876524.99      7049624.98
#Sta/Elev= 30
  4458.8  455.57  4575.9  449.93  4683.6  442.57  4788.8  438.24  4851.5  435.51
  4857.3  434.59  4889.6  433.49  4899.1  433.87  4904.4  435.00  4921.9  433.82
  4943.5  435.04  4965.0  434.68  4975.8  435.45  4982.5  434.84  4984.8  432.69
  4985.3  431.89  4990.5  431.89  4991.0  432.69  4995.2  432.70  5000.0  432.70
  5018.4  435.04  5071.1  434.07  5102.7  434.58  5113.2  435.51  5187.1  439.54
  5271.4  446.49  5324.1  449.39  5334.6  450.93  5419.0  456.16  5471.7  457.29
#Mann=5,-1,0
  4458.8    0.05       0  4788.8    0.12       0  4984.8    0.03       0
  4991.0    0.12       0  4995.2    0.05       0
Bank Sta=4851.5,5113.2
Exp/Cntr=0.3,0.1

Type RM Length L Ch R = 1,8980,544,544,544
BEGIN DESCRIPTION:
UNT 034 in Running Cr Watershed 13.0
END DESCRIPTION:
XS GIS Cut Line= 3
      2877374.96      7050074.97      2877025.00      7049775.00
      2876574.97      7049624.99
#Sta/Elev= 30
  4549.9  452.83  4620.6  449.66  4649.2  446.88  4698.6  444.49  4776.5  437.21
  4872.8  433.94  4960.9  432.53  4969.5  430.96  4982.8  428.69  4997.1  429.43
  5000.6  428.35  5001.1  427.55  5006.3  427.55  5006.8  428.35  5007.5  429.80
  5021.4  428.89  5031.9  432.16  5063.5  433.10  5158.4  432.76  5168.9  431.71
  5211.1  432.97  5232.2  432.10  5255.4  433.94  5267.6  437.35  5274.4  438.24
  5284.9  436.75  5327.1  445.39  5379.8  450.74  5432.5  455.31  5485.2  456.61
#Mann=5,-1,0
  4549.9    0.05       0  4969.5    0.12       0  5000.6    0.07       0
  5006.8    0.12       0  5267.6    0.05       0
Bank Sta=4872.8,5255.4
Exp/Cntr=0.3,0.1

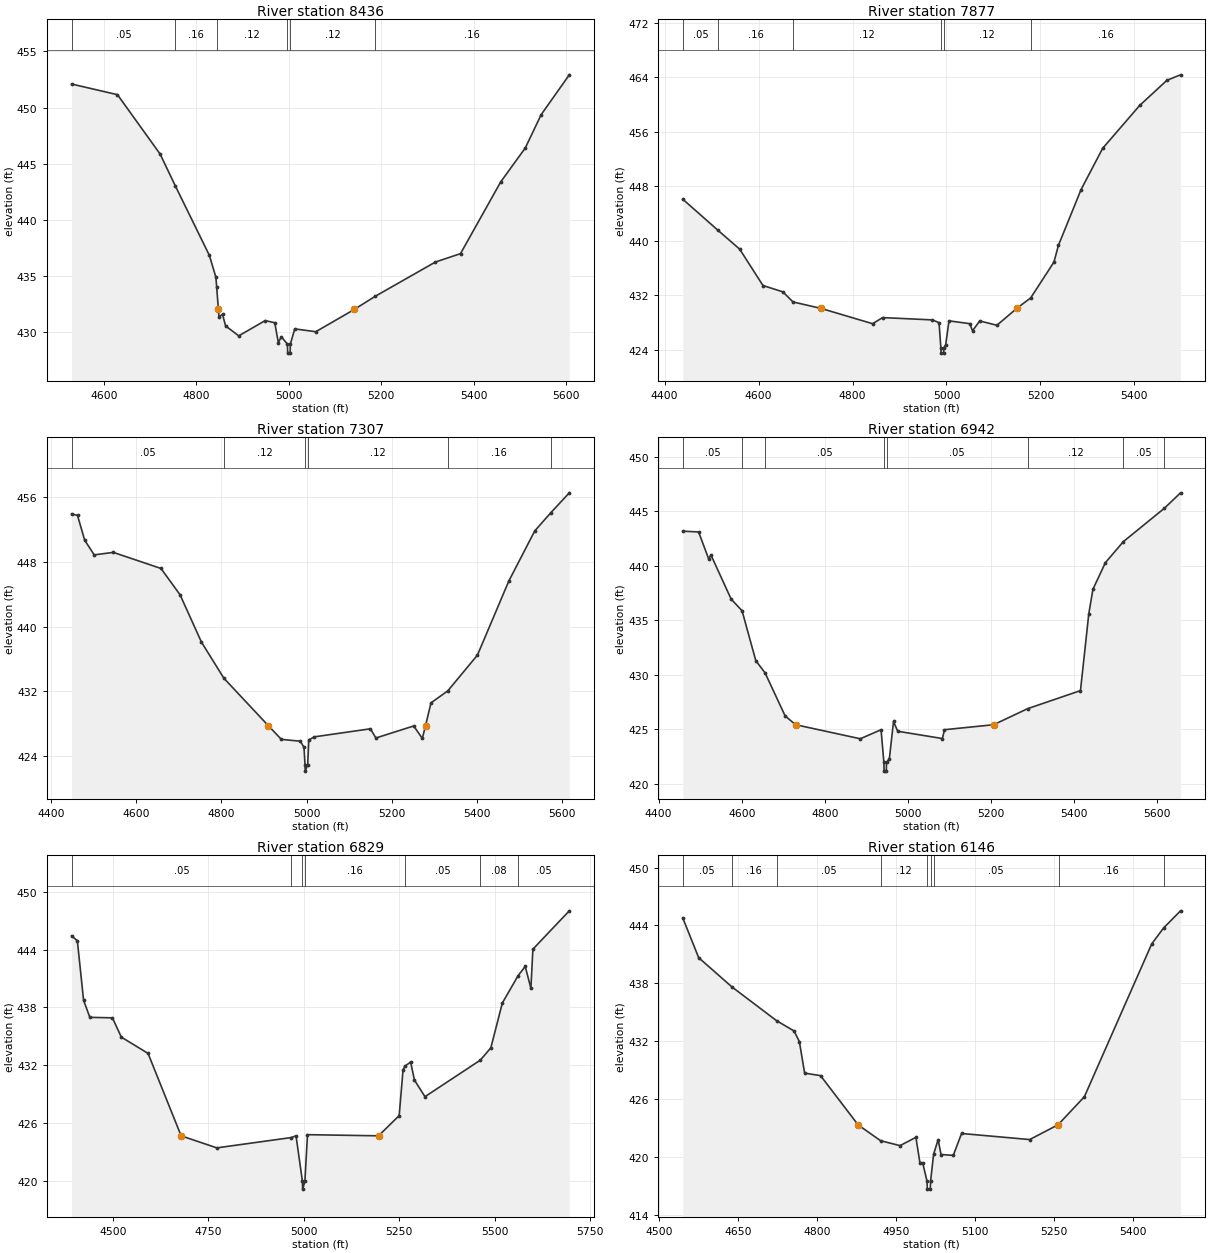
Type RM Length L Ch R = 1,8436,559,559,559
BEGIN DESCRIPTION:
UNT 034 in Running Cr Watershed 12.0
END DESCRIPTION:
XS GIS Cut Line= 3
      2877624.98      7049624.98      2877275.00      7049325.00
      2876708.38      7049084.48
#Sta/Elev= 30
  4530.5  452.10  4629.8  451.15  4722.0  445.86  4754.7  443.04  4828.5  436.83
  4842.7  434.87  4844.4  433.97  4848.1  432.00  4849.3  431.35  4857.0  431.57
  4863.6  430.54  4892.1  429.65  4949.2  431.01  4970.0  430.82  4977.7  429.05
  4984.3  429.57  4997.4  428.91  4997.9  428.11  5003.2  428.11  5003.7  428.91
  5013.2  430.27  5058.7  430.02  5141.9  432.00  5186.5  433.16  5317.4  436.23
  5371.7  436.98  5458.6  443.37  5511.8  446.40  5546.3  449.38  5607.0  452.92
#Mann=6,-1,0
  4530.5    0.05       0  4754.7    0.16       0  4844.4    0.12       0
  4997.4    0.07       0  5003.7    0.12       0  5186.5    0.16       0
Bank Sta=4848.1,5141.9
Exp/Cntr=0.3,0.1

Type RM Length L Ch R = 1,7877,570,570,570
BEGIN DESCRIPTION:
UNT 034 in Running Cr Watershed 11.0
END DESCRIPTION:
XS GIS Cut Line= 3
      2877887.24      7049344.17      2877475.00      7048925.00
      2877075.01      7048675.01
#Sta/Elev= 30
  4438.7  446.08  4514.0  441.49  4559.9  438.74  4609.4  433.40  4651.8  432.47
  4673.3  430.99  4733.5  430.03  4842.8  427.79  4864.0  428.69  4970.1  428.35
  4984.2  427.94  4988.1  424.27  4988.6  423.47  4993.9  423.47  4994.4  424.27
  4998.4  424.70  5005.4  428.21  5049.6  427.80  5055.5  426.75  5070.8  428.20
  5107.4  427.56  5149.4  430.03  5179.3  431.58  5228.9  436.85  5238.3  439.29
  5286.6  447.50  5332.6  453.56  5411.6  459.87  5469.4  463.55  5498.3  464.35
#Mann=6,-1,0
  4438.7    0.05       0  4514.0    0.16       0  4673.3    0.12       0
  4988.1    0.07       0  4994.4    0.12       0  5179.3    0.16       0
Bank Sta=4733.5,5149.4
Exp/Cntr=0.3,0.1

Type RM Length L Ch R = 1,7307,365,365,365
BEGIN DESCRIPTION:
UNT 034 in Running Cr Watershed 10.0
END DESCRIPTION:
XS GIS Cut Line= 3
      2878075.01      7049225.03      2877825.00      7048725.00
      2877225.03      7048625.00
#Sta/Elev= 30
  4448.8  453.95  4462.8  453.75  4479.6  450.69  4501.9  448.87  4546.7  449.18
  4658.5  447.19  4703.2  443.94  4753.5  438.07  4806.0  433.61  4910.0  427.75
  4940.8  426.04  4985.5  425.81  4993.9  425.05  4996.3  422.91  4996.8  422.11
  5002.6  422.91  5005.1  425.97  5018.0  426.35  5149.8  427.35  5162.5  426.21
  5251.2  427.70  5271.4  426.16  5279.0  427.74  5291.7  430.56  5331.1  432.04
  5400.7  436.47  5474.2  445.63  5535.0  451.83  5572.8  454.09  5616.1  456.55
#Mann=6,-1,0
  4448.8    0.05       0  4806.0    0.12       0  4996.3    0.07       0
  5002.6    0.12       0  5331.1    0.16       0  5572.8    0.05       0
Bank Sta=4910,5279
Exp/Cntr=0.3,0.1

Type RM Length L Ch R = 1,6942,113,113,113
BEGIN DESCRIPTION:
Mapping XS af0bd646
END DESCRIPTION:
XS GIS Cut Line= 5
      2878433.23      7048677.46      2878353.39      7048476.12
      2878277.00      7048457.02      2877783.95      7048446.60
      2877374.18      7048436.19
#Sta/Elev= 30
  4458.1  443.19  4496.2  443.12  4520.5  440.64  4525.9  441.01  4574.5  436.96
  4600.8  435.89  4633.9  431.31  4656.3  430.18  4704.5  426.24  4729.6  425.43
  4885.5  424.14  4935.5  424.97  4942.3  421.97  4942.8  421.17  4948.1  421.17
  4948.6  421.97  4955.5  422.31  4965.5  425.73  4975.5  424.83  5083.2  424.16
  5088.2  424.97  5206.6  425.43  5288.3  426.90  5415.6  428.56  5435.6  435.60
  5445.6  437.86  5475.6  440.30  5518.8  442.23  5617.8  445.30  5656.5  446.71
#Mann=8,-1,0
  4458.1    0.05       0  4600.8    0.12       0  4656.3    0.05       0
  4942.3    0.04       0  4948.6    0.05       0  5288.3    0.12       0
  5518.8    0.05       0  5617.8    0.08       0
Bank Sta=4729.6,5206.6
Exp/Cntr=0.3,0.1

Type RM Length L Ch R = 1,6829,683,683,683
BEGIN DESCRIPTION:
UNT 034 in Running Cr Watershed 9.0
END DESCRIPTION:
XS GIS Cut Line= 3
      2878502.71      7048668.87      2878381.17      7048392.78
      2877379.69      7048356.33
#Sta/Elev= 30
  4392.1  445.43  4407.3  444.92  4423.6  438.74  4440.0  436.97  4499.1  436.92
  4522.5  434.92  4592.5  433.23  4679.1  424.68  4772.6  423.43  4967.6  424.50
  4980.1  424.68  4996.9  419.95  4997.4  419.15  5003.3  419.95  5010.1  424.80
  5196.2  424.68  5250.3  426.78  5260.3  431.47  5264.7  431.89  5280.3  432.33
  5290.3  430.46  5317.8  428.74  5462.8  432.53  5490.4  433.81  5520.5  438.46
  5561.9  441.30  5580.5  442.25  5595.3  439.98  5600.5  444.04  5695.9  448.02
#Mann=7,-1,0
  4392.1    0.05       0  4967.6    0.16       0  4996.9    0.07       0
  5003.3    0.16       0  5264.7    0.05       0  5462.8    0.08       0
  5561.9    0.05       0
Bank Sta=4679.1,5196.2
Exp/Cntr=0.3,0.1

Type RM Length L Ch R = 1,6146,814,814,814
BEGIN DESCRIPTION:
UNT 034 in Running Cr Watershed 8.0
END DESCRIPTION:
XS GIS Cut Line= 3
      2878575.00      7048675.02      2878525.00      7048225.00
      2878325.01      7047775.03
#Sta/Elev= 30
  4544.8  444.78  4575.0  440.66  4637.9  437.64  4723.1  434.12  4756.1  433.06
  4766.2  431.96  4776.2  428.69  4806.4  428.43  4878.0  423.31  4920.5  421.68
  4957.3  421.17  4987.5  422.03  4995.1  419.40  5000.3  419.40  5008.7  417.46
  5009.2  416.66  5014.8  416.66  5015.3  417.46  5021.2  420.30  5029.7  421.79
  5035.2  420.25  5058.5  420.16  5074.2  422.43  5203.5  421.80  5256.7  423.31
  5258.4  423.39  5307.4  426.24  5435.3  442.09  5457.8  443.74  5490.0  445.52
#Mann=9,-1,0
  4544.8    0.05       0  4637.9    0.16       0  4723.1    0.05       0
  4920.5    0.12       0  5008.7    0.07       0  5015.3    0.12       0
  5021.2    0.05       0  5258.4    0.16       0  5457.8    0.05       0
Bank Sta=4878,5256.7
Exp/Cntr=0.3,0.1

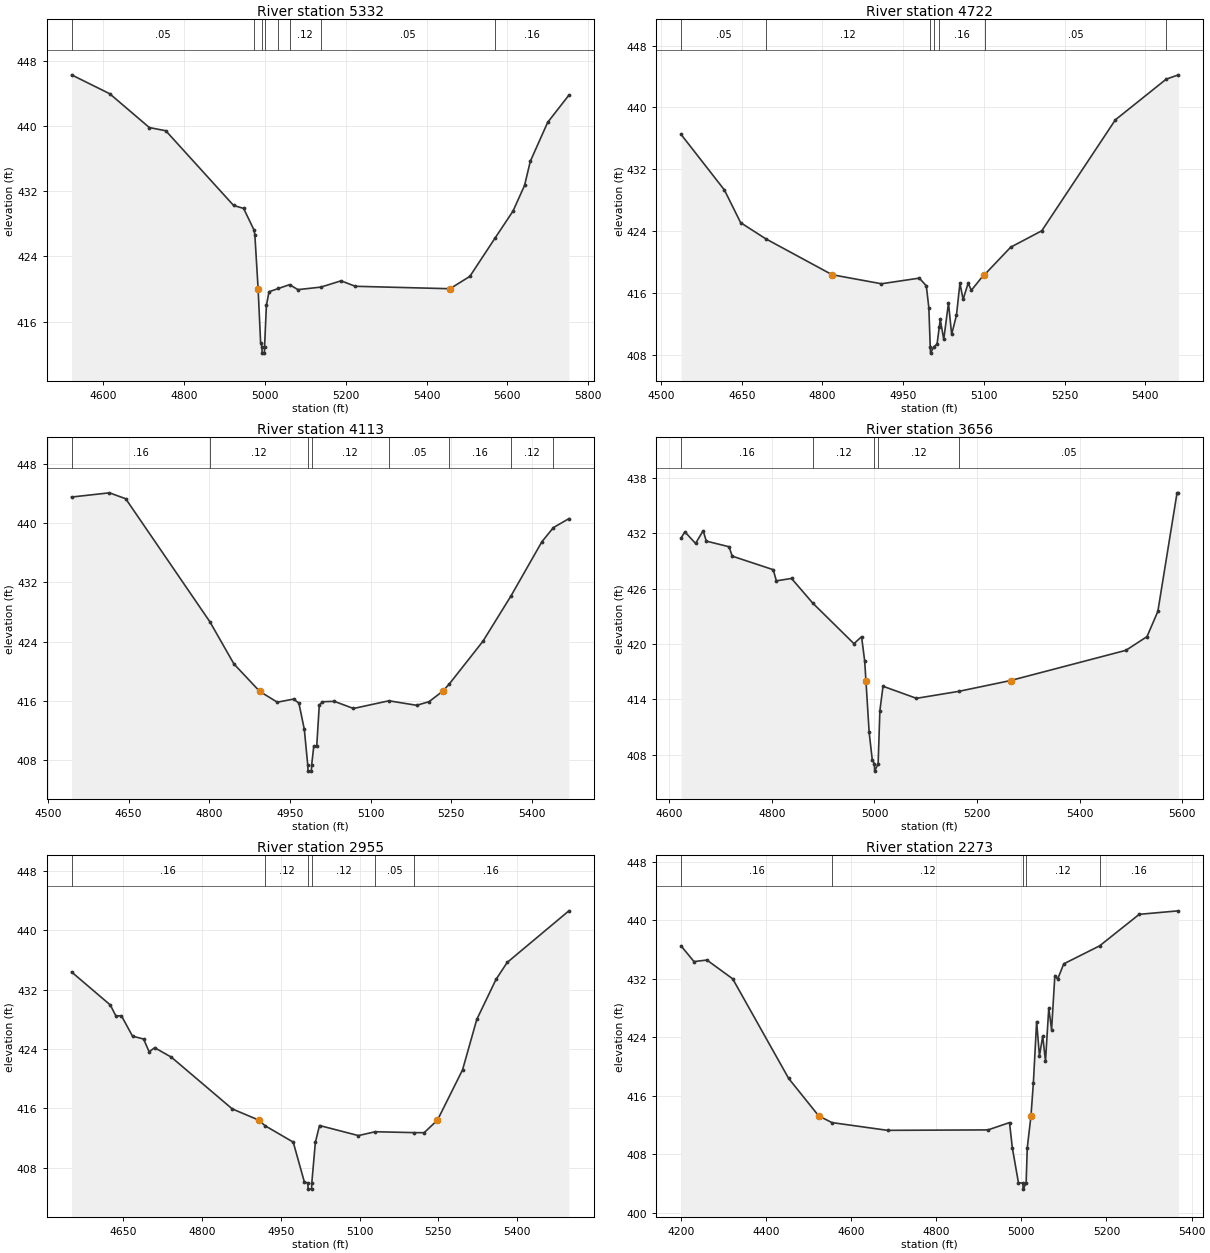
Type RM Length L Ch R = 1,5332,610,610,610
BEGIN DESCRIPTION:
UNT 034 in Running Cr Watershed 7.0
END DESCRIPTION:
XS GIS Cut Line= 3
      2878975.00      7048724.98      2879046.76      7048287.99
      2878538.94      7047686.55
#Sta/Elev= 30
  4522.1  446.27  4616.5  443.95  4714.6  439.80  4755.2  439.41  4922.8  430.25
  4947.7  429.88  4973.1  427.26  4975.4  426.68  4983.5  420.03  4989.7  413.42
  4992.9  412.93  4993.4  412.13  4999.0  412.13  4999.5  412.93  5004.0  417.99
  5010.5  419.66  5033.7  420.06  5061.3  420.53  5082.0  419.92  5138.8  420.23
  5188.6  421.00  5223.8  420.33  5458.1  420.03  5507.2  421.55  5569.8  426.27
  5613.8  429.55  5642.4  432.70  5656.7  435.67  5699.6  440.44  5752.1  443.78
#Mann=8,-1,0
  4522.1    0.05       0  4973.1    0.12       0  4992.9    0.07       0
  4999.5    0.12       0  5033.7    0.16       0  5061.3    0.12       0
  5138.8    0.05       0  5569.8    0.16       0
Bank Sta=4983.5,5458.1
Exp/Cntr=0.3,0.1

Type RM Length L Ch R = 1,4722,609,609,609
BEGIN DESCRIPTION:
UNT 034 in Running Cr Watershed 6.0
END DESCRIPTION:
XS GIS Cut Line= 3
      2879275.00      7048275.04      2879225.00      7047825.00
      2878975.01      7047425.01
#Sta/Elev= 30
  4537.2  436.50  4617.7  429.32  4647.9  425.09  4694.2  423.02  4817.9  418.36
  4909.5  417.19  4980.0  417.92  4993.0  416.92  4997.7  414.10  5000.3  409.02
  5000.8  408.22  5006.9  409.02  5013.0  409.40  5017.2  411.66  5018.9  412.58
  5025.4  409.99  5034.2  414.70  5040.1  410.65  5049.0  413.10  5055.5  417.26
  5061.4  415.17  5070.8  417.27  5076.7  416.34  5100.0  418.36  5102.7  418.47
  5149.8  421.92  5207.6  424.04  5344.4  438.39  5438.9  443.65  5461.7  444.21
#Mann=7,-1,0
  4537.2    0.05       0  4694.2    0.12       0  5000.3    0.07       0
  5006.9    0.12       0  5017.2    0.16       0  5102.7    0.05       0
  5438.9    0.16       0
Bank Sta=4817.9,5100
Exp/Cntr=0.3,0.1

Type RM Length L Ch R = 1,4113,457,457,457
BEGIN DESCRIPTION:
UNT 034 in Running Cr Watershed 5.0
END DESCRIPTION:
XS GIS Cut Line= 3
      2880175.03      7047725.00      2879725.00      7047675.00
      2879325.00      7047425.00
#Sta/Elev= 30
  4544.1  443.54  4614.6  444.11  4644.8  443.31  4801.2  426.68  4846.0  420.97
  4893.8  417.27  4926.5  415.80  4956.7  416.22  4966.7  415.68  4976.8  412.12
  4983.2  407.28  4983.8  406.48  4989.9  406.48  4990.4  407.28  4994.4  409.89
  4999.9  409.89  5004.6  415.40  5010.5  415.86  5032.3  415.92  5068.2  414.95
  5134.0  415.99  5185.6  415.38  5208.6  415.87  5233.8  417.27  5246.0  418.24
  5308.8  424.04  5361.1  430.19  5418.5  437.51  5439.8  439.41  5468.6  440.62
#Mann=8,-1,0
  4544.1    0.16       0  4801.2    0.12       0  4983.2    0.07       0
  4990.4    0.12       0  5134.0    0.05       0  5246.0    0.16       0
  5361.1    0.12       0  5439.8    0.05       0
Bank Sta=4893.8,5233.8
Exp/Cntr=0.3,0.1

Type RM Length L Ch R = 1,3656,701,701,701
BEGIN DESCRIPTION:
UNT 034 in Running Cr Watershed 4.0
END DESCRIPTION:
XS GIS Cut Line= 3
      2880274.97      7047574.98      2879894.12      7047304.21
      2879405.32      7047189.81
#Sta/Elev= 30
  4623.1  431.50  4630.4  432.18  4651.3  430.92  4666.1  432.30  4672.2  431.17
  4716.5  430.56  4722.7  429.54  4802.6  428.07  4808.8  426.86  4838.3  427.12
  4879.6  424.45  4960.0  420.04  4974.8  420.80  4980.9  418.16  4983.3  416.04
  4989.6  410.41  4995.7  407.43  4999.7  407.01  5000.3  406.21  5007.1  407.01
  5010.5  412.77  5016.6  415.42  5081.8  414.11  5164.5  414.87  5265.1  416.04
  5490.0  419.32  5531.1  420.81  5552.2  423.54  5589.6  436.40  5592.4  436.41
#Mann=5,-1,0
  4623.1    0.16       0  4879.6    0.12       0  4999.7    0.07       0
  5007.1    0.12       0  5164.5    0.05       0
Bank Sta=4983.3,5265.1
Exp/Cntr=0.3,0.1

Type RM Length L Ch R = 1,2955,682,682,682
BEGIN DESCRIPTION:
UNT 034 in Running Cr Watershed 3.0
END DESCRIPTION:
XS GIS Cut Line= 3
      2880525.01      7047475.02      2880375.00      7047025.00
      2880124.98      7046624.97
#Sta/Elev= 30
  4552.2  434.38  4626.0  429.92  4636.5  428.45  4647.1  428.47  4668.2  425.72
  4689.3  425.33  4699.8  423.61  4710.3  424.16  4742.0  422.89  4857.9  415.91
  4908.3  414.40  4920.1  413.65  4973.9  411.43  4994.9  406.10  5001.7  405.89
  5002.3  405.09  5008.7  405.09  5009.2  405.89  5016.0  411.40  5023.9  413.67
  5097.9  412.31  5129.8  412.83  5203.3  412.71  5222.9  412.70  5248.3  414.40
  5296.0  421.18  5323.1  427.98  5359.7  433.38  5380.9  435.66  5498.3  442.62
#Mann=6,-1,0
  4552.2    0.16       0  4920.1    0.12       0  5001.7    0.07       0
  5009.2    0.12       0  5129.8    0.05       0  5203.3    0.16       0
Bank Sta=4908.3,5248.3
Exp/Cntr=0.3,0.1

Type RM Length L Ch R = 1,2273,1329,1329,1329
BEGIN DESCRIPTION:
UNT 034 in Running Cr Watershed 2.0
END DESCRIPTION:
XS GIS Cut Line= 3
      2880575.00      7047425.02      2880675.00      7046725.00
      2880375.00      7046375.00
#Sta/Elev= 30
  4201.0  436.46  4231.3  434.32  4261.6  434.53  4322.2  431.96  4453.6  418.34
  4524.3  413.21  4555.3  412.30  4685.9  411.24  4921.8  411.30  4972.3  412.30
  4978.9  408.86  4993.2  404.10  5003.7  404.00  5004.3  403.20  5011.3  404.00
  5014.0  408.84  5022.7  413.21  5028.3  417.69  5036.0  426.12  5042.6  421.41
  5050.3  424.14  5056.8  420.70  5064.5  427.97  5071.1  425.01  5078.8  432.41
  5085.4  431.93  5099.7  434.01  5183.9  436.47  5276.9  440.78  5369.1  441.26
#Mann=5,-1,0
  4201.0    0.16       0  4555.3    0.12       0  5003.7    0.07       0
  5011.3    0.12       0  5183.9    0.16       0
Bank Sta=4524.3,5022.7
Exp/Cntr=0.3,0.1

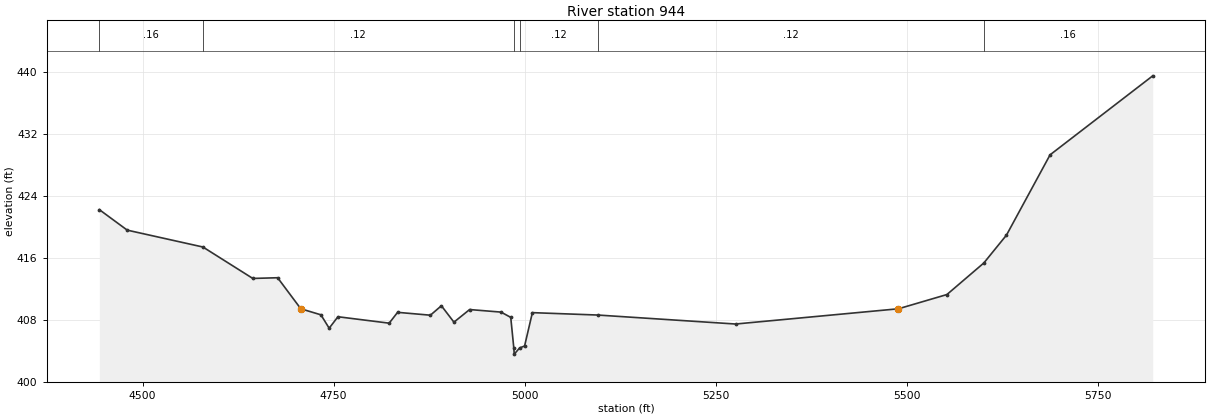
Type RM Length L Ch R = 1,944,0,0,0
BEGIN DESCRIPTION:
UNT 034 in Running Cr Watershed 1.0
END DESCRIPTION:
XS GIS Cut Line= 4
      2881074.98      7047375.04      2881257.47      7047004.33
      2881205.39      7046778.63      2880725.01      7046225.01
#Sta/Elev= 30
  4443.5  422.26  4480.0  419.61  4579.0  417.43  4644.2  413.37  4676.7  413.46
  4707.0  409.45  4733.3  408.67  4744.1  406.94  4755.6  408.42  4822.6  407.59
  4833.6  408.99  4876.5  408.62  4890.9  409.84  4907.3  407.72  4927.8  409.35
  4968.9  409.02  4981.6  408.34  4985.6  404.39  4986.2  403.59  4993.2  404.39
  4999.7  404.64  5009.9  408.95  5095.5  408.64  5275.7  407.48  5488.7  409.45
  5552.1  411.29  5600.4  415.37  5630.0  418.97  5687.0  429.34  5821.3  439.55
#Mann=6,-1,0
  4443.5    0.16       0  4579.0    0.12       0  4985.6    0.04       0
  4993.2    0.12       0  5095.5    0.12       0  5600.4    0.16       0
Bank Sta=4707,5488.7
Exp/Cntr=0.3,0.1

Chan Stop Cuts=-1