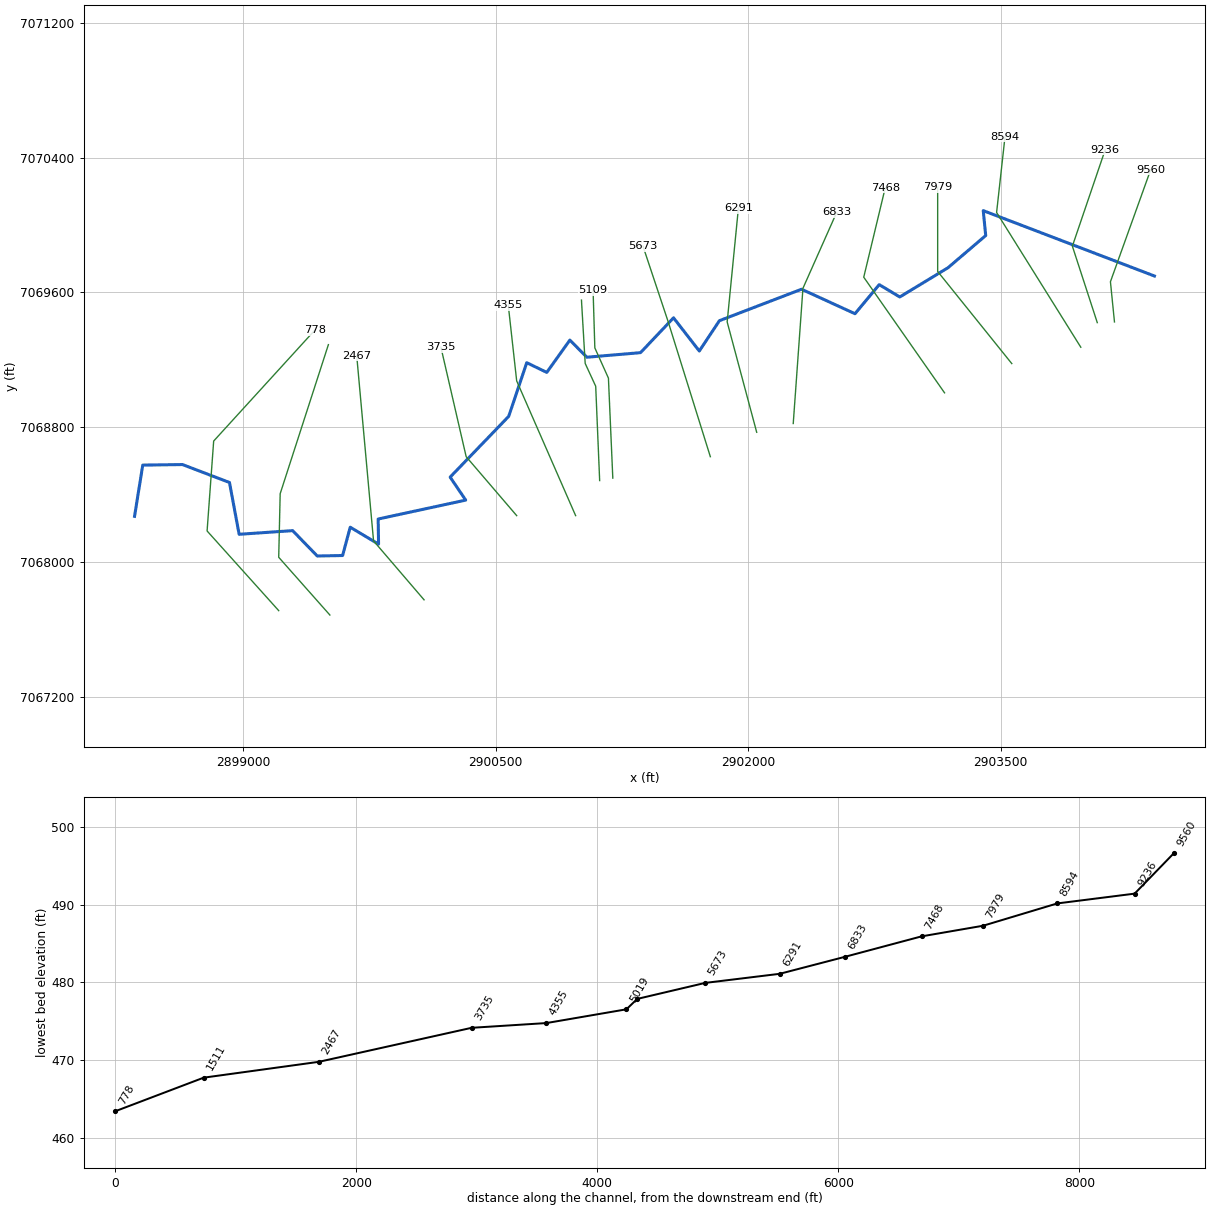
--- UNT 035 in Running Cr Watershed.prj (project) ---

Proj Title=UNT 035 in Running Cr Watershed Base Level Engineering
Current Plan=p01
Default Exp/Contr=0.3,0.1
English Units
Geom File=g01
Flow File=f01
Plan File=p01
BEGIN DESCRIPTION:
UNT 035 in Running Cr Watershed
END DESCRIPTION:

--- UNT 035 in Running Cr Watershed.p01 (plan) ---

Plan Title=Multiple Run
Short Identifier=Multiple
Geom File=g01
Flow File=f01
Subcritical Flow
K Sum by GR= 0
Std Step Tol= 0.01
Critical Tol= 0.01
Num of Std Step Trials= 20
Max Error Tol= 0.3
Flow Tol Ratio= 0.001
Split Flow NTrial= 30
Split Flow Tol= 0.02
Split Flow Ratio= 0.02
Log Output Level= 0
Friction Slope Method= 1
Unsteady Friction Slope Method= 2
Unsteady Bridges Friction Slope Method= 1
Parabolic Critical Depth
Global Vel Dist=  1 , 1 , 1
Global Log Level= 0
CheckData=True
Encroach Param= -1, 0, 0, 0
BEGIN DESCRIPTION:
Multiple Run
END DESCRIPTION:

--- UNT 035 in Running Cr Watershed.f01 (steady flow) ---

Flow Title=Multiple
Number of Profiles=7
Profile Names=10-year,25-year,50-year,1pct_min,100-year,1pct_plu,500-year
River Rch & RM= UNT 035 in Runni,Reach-1,9560
     771    1035    1249     747    1491    2975    2120
River Rch & RM= UNT 035 in Runni,Reach-1,8594
    1092    1490    1817    1097    2188    4366    3169
Boundary for River Rch & Prof#=UNT 035 in Runni,Reach-1,1
Up Type=0
Dn Type=3
Dn Slope=0.005
Boundary for River Rch & Prof#=UNT 035 in Runni,Reach-1,2
Up Type=0
Dn Type=3
Dn Slope=0.005
Boundary for River Rch & Prof#=UNT 035 in Runni,Reach-1,3
Up Type=0
Dn Type=3
Dn Slope=0.005
Boundary for River Rch & Prof#=UNT 035 in Runni,Reach-1,4
Up Type=0
Dn Type=3
Dn Slope=0.005
Boundary for River Rch & Prof#=UNT 035 in Runni,Reach-1,5
Up Type=0
Dn Type=3
Dn Slope=0.005
Boundary for River Rch & Prof#=UNT 035 in Runni,Reach-1,6
Up Type=0
Dn Type=3
Dn Slope=0.005
Boundary for River Rch & Prof#=UNT 035 in Runni,Reach-1,7
Up Type=0
Dn Type=3
Dn Slope=0.005

--- UNT 035 in Running Cr Watershed.g01 (geometry) ---

Geom Title=Existing Conditions

River Reach=UNT 035 in Runni,Reach-1
Reach XY= 30
      2904412.26      7069697.86      2903395.74      7070085.99
      2903410.35      7069938.14      2903186.47      7069747.00
      2902900.06      7069573.36      2902777.99      7069646.54
      2902634.08      7069473.86      2902316.63      7069619.27
      2901828.88      7069432.49      2901709.48      7069252.36
      2901556.40      7069449.63      2901360.50      7069242.70
      2901041.86      7069215.54      2900940.84      7069317.14
      2900803.68      7069125.47      2900684.76      7069183.13
      2900577.62      7068864.47      2900229.78      7068503.55
      2900322.25      7068367.10      2899802.35      7068254.88
      2899804.81      7068105.70      2899636.50      7068206.24
      2899591.16      7068038.10      2899440.60      7068035.35
      2899294.38      7068185.90      2898976.77      7068164.13
      2898919.39      7068471.76      2898640.27      7068578.24
      2898404.43      7068575.00      2898355.59      7068270.71

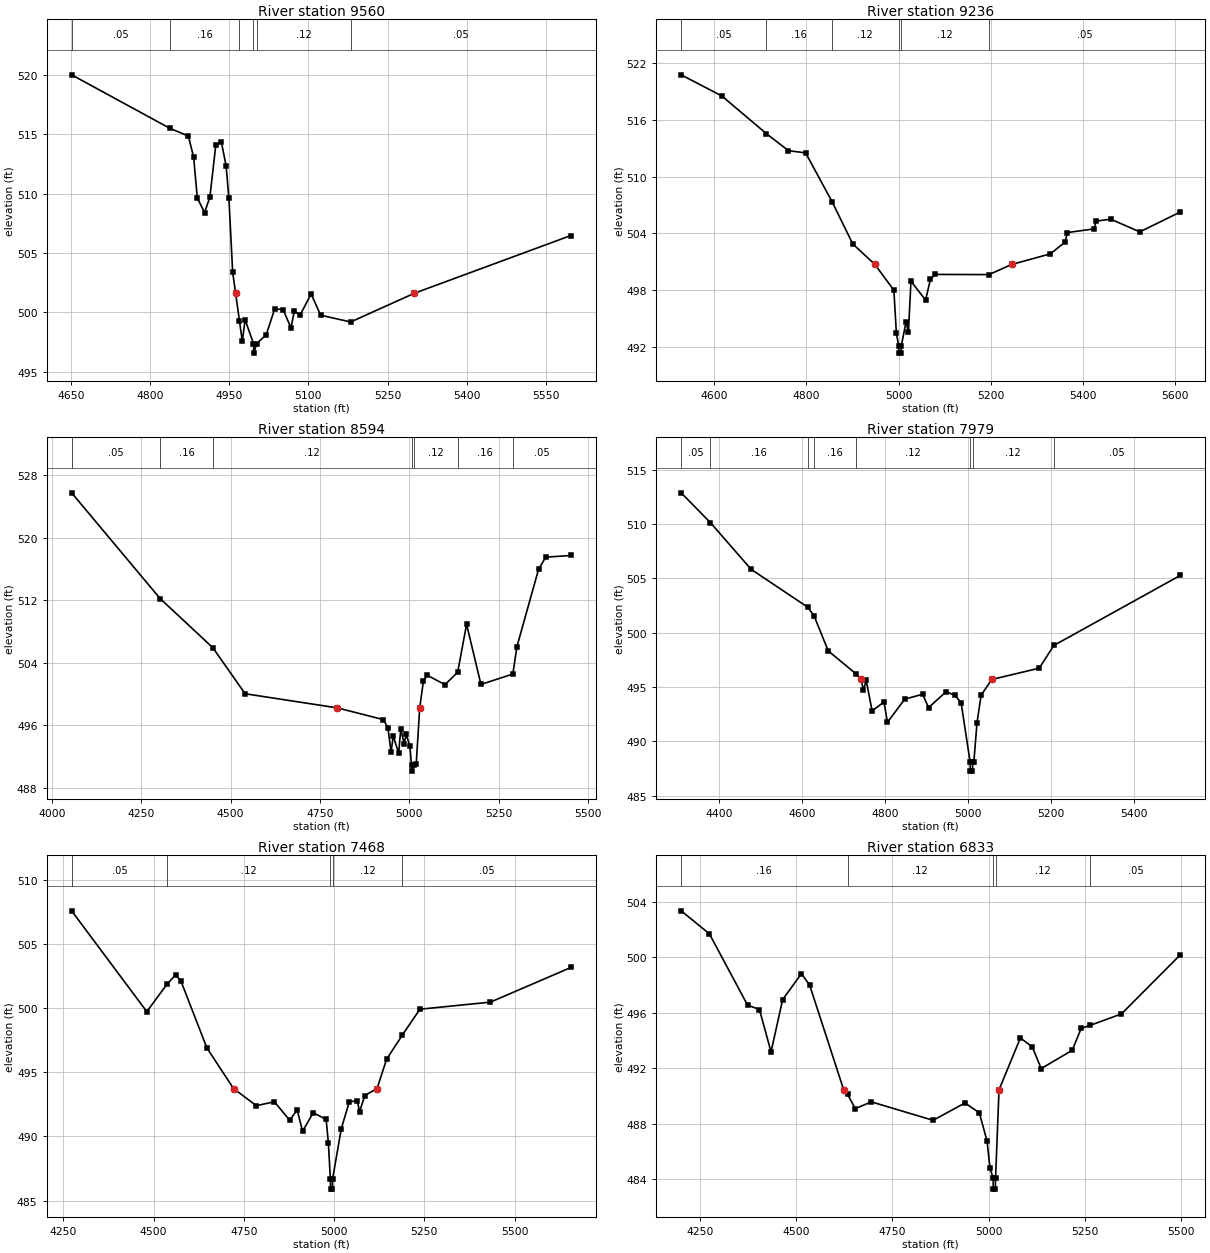
Type RM Length L Ch R = 1,9560,324,324,324
BEGIN DESCRIPTION:
UNT 035 in Running Cr Watershed 13.0
END DESCRIPTION:
XS GIS Cut Line= 3
      2904175.00      7069425.04      2904151.05      7069663.97
      2904389.77      7070328.04
#Sta/Elev= 30
  4651.6  519.98  4837.4  515.49  4872.7  514.83  4882.7  513.06  4889.7  509.62
  4903.4  508.40  4913.5  509.70  4924.7  514.07  4935.3  514.32  4944.2  512.33
  4949.5  509.61  4956.6  503.41  4962.2  501.61  4969.5  499.29  4974.9  497.58
  4980.2  499.39  4996.1  497.38  4996.6  496.58  5002.1  497.38  5020.3  498.13
  5036.3  500.31  5052.2  500.24  5067.1  498.70  5073.5  500.14  5084.1  499.76
  5105.3  501.56  5123.2  499.77  5180.1  499.20  5300.6  501.61  5597.4  506.47
#Mann=6,-1,0
  4651.6    0.05       0  4837.4    0.16       0  4969.5    0.12       0
  4996.1    0.07       0  5002.1    0.12       0  5180.1    0.05       0
Bank Sta=4962.2,5300.6
Exp/Cntr=0.3,0.1

Type RM Length L Ch R = 1,9236,642,642,642
BEGIN DESCRIPTION:
UNT 035 in Running Cr Watershed 12.0
END DESCRIPTION:
XS GIS Cut Line= 3
      2904072.92      7069420.93      2903925.00      7069875.00
      2904120.34      7070448.59
#Sta/Elev= 30
  4528.0  520.71  4616.4  518.48  4712.6  514.53  4760.9  512.72  4798.1  512.49
  4855.5  507.35  4900.4  502.90  4948.4  500.74  4989.6  498.03  4995.0  493.53
  4999.9  492.20  5000.4  491.40  5005.4  491.40  5005.9  492.20  5016.0  494.69
  5021.2  493.63  5026.7  498.97  5058.4  496.99  5068.9  499.16  5078.7  499.69
  5195.8  499.67  5245.4  500.74  5329.5  501.86  5360.9  503.09  5366.2  504.10
  5423.6  504.48  5428.9  505.30  5460.2  505.51  5523.2  504.17  5611.5  506.27
#Mann=6,-1,0
  4528.0    0.05       0  4712.6    0.16       0  4855.5    0.12       0
  4999.9    0.07       0  5005.9    0.12       0  5195.8    0.05       0
Bank Sta=4948.4,5245.4
Exp/Cntr=0.3,0.1

Type RM Length L Ch R = 1,8594,615,615,615
BEGIN DESCRIPTION:
UNT 035 in Running Cr Watershed 11.0
END DESCRIPTION:
XS GIS Cut Line= 3
      2903974.99      7069275.01      2903475.00      7070075.00
      2903525.01      7070525.05
#Sta/Elev= 30
  4055.4  525.71  4303.0  512.19  4450.1  505.92  4540.6  500.03  4798.8  498.22
  4927.4  496.72  4939.8  495.67  4948.7  492.59  4954.6  494.62  4969.9  492.44
  4975.8  495.53  4985.2  493.66  4991.1  494.86  5001.3  493.29  5005.8  490.94
  5006.3  490.14  5011.9  490.94  5018.9  491.00  5028.7  498.22  5039.0  501.61
  5049.1  502.41  5099.4  501.19  5134.9  502.78  5159.8  508.91  5200.0  501.22
  5289.2  502.55  5300.6  506.05  5361.0  515.92  5381.1  517.49  5451.6  517.70
#Mann=7,-1,0
  4055.4    0.05       0  4303.0    0.16       0  4450.1    0.12       0
  5005.8    0.07       0  5011.9    0.12       0  5134.9    0.16       0
  5289.2    0.05       0
Bank Sta=4798.8,5028.7
Exp/Cntr=0.3,0.1

Type RM Length L Ch R = 1,7979,511,511,511
BEGIN DESCRIPTION:
UNT 035 in Running Cr Watershed 10.0
END DESCRIPTION:
XS GIS Cut Line= 3
      2903565.09      7069177.88      2903125.00      7069725.00
      2903125.00      7070225.05
#Sta/Elev= 30
  4309.0  512.87  4379.4  510.13  4477.6  505.83  4613.8  502.35  4629.1  501.54
  4663.2  498.33  4730.2  496.21  4742.5  495.70  4748.0  494.70  4754.5  495.63
  4768.8  492.81  4797.6  493.64  4805.6  491.75  4847.2  493.89  4890.4  494.34
  4904.8  493.11  4947.0  494.58  4968.7  494.23  4983.1  493.56  5004.9  488.07
  5005.4  487.27  5010.5  487.27  5011.0  488.07  5013.7  488.07  5021.2  491.67
  5031.2  494.25  5056.9  495.70  5171.2  496.74  5206.3  498.83  5511.2  505.28
#Mann=8,-1,0
  4309.0    0.05       0  4379.4    0.16       0  4613.8    0.12       0
  4629.1    0.16       0  4730.2    0.12       0  5004.9    0.07       0
  5011.0    0.12       0  5206.3    0.05       0
Bank Sta=4742.5,5056.9
Exp/Cntr=0.3,0.1

Type RM Length L Ch R = 1,7468,635,635,635
BEGIN DESCRIPTION:
UNT 035 in Running Cr Watershed 9.0
END DESCRIPTION:
XS GIS Cut Line= 3
      2903165.80      7069004.25      2902686.05      7069690.74
      2902813.77      7070221.89
#Sta/Elev= 30
  4272.6  507.57  4480.9  499.72  4537.0  501.86  4561.1  502.59  4576.0  502.07
  4647.5  496.89  4721.4  493.73  4784.4  492.40  4834.7  492.70  4876.8  491.27
  4897.8  492.06  4912.6  490.41  4942.3  491.85  4978.0  491.33  4984.1  489.51
  4989.7  486.70  4990.2  485.90  4995.4  485.90  4995.9  486.70  5019.9  490.60
  5042.1  492.70  5064.4  492.78  5070.5  491.93  5085.3  493.19  5119.1  493.73
  5145.3  496.00  5189.4  497.91  5237.9  499.91  5433.3  500.46  5656.4  503.16
#Mann=5,-1,0
  4272.6    0.05       0  4537.0    0.12       0  4989.7    0.07       0
  4995.9    0.12       0  5189.4    0.05       0
Bank Sta=4721.4,5119.1
Exp/Cntr=0.3,0.1

Type RM Length L Ch R = 1,6833,542,542,542
BEGIN DESCRIPTION:
UNT 035 in Running Cr Watershed 8.0
END DESCRIPTION:
XS GIS Cut Line= 3
      2902267.37      7068821.96      2902325.00      7069625.00
      2902525.02      7070075.05
#Sta/Elev= 30
  4201.2  503.33  4274.4  501.68  4373.7  496.54  4404.8  496.21  4434.8  493.16
  4464.9  496.93  4513.7  498.80  4535.1  497.98  4623.6  490.43  4633.7  490.10
  4653.7  489.07  4695.5  489.56  4855.9  488.23  4938.8  489.48  4976.2  488.77
  4996.3  486.72  5003.8  484.78  5012.0  484.07  5012.5  483.27  5017.8  483.27
  5018.3  484.07  5027.3  490.43  5082.9  494.17  5113.7  493.52  5136.9  491.96
  5217.6  493.28  5240.9  494.86  5264.6  495.08  5345.5  495.90  5498.8  500.17
#Mann=5,-1,0
  4201.2    0.16       0  4633.7    0.12       0  5012.0    0.07       0
  5018.3    0.12       0  5264.6    0.05       0
Bank Sta=4623.6,5027.3
Exp/Cntr=0.3,0.1

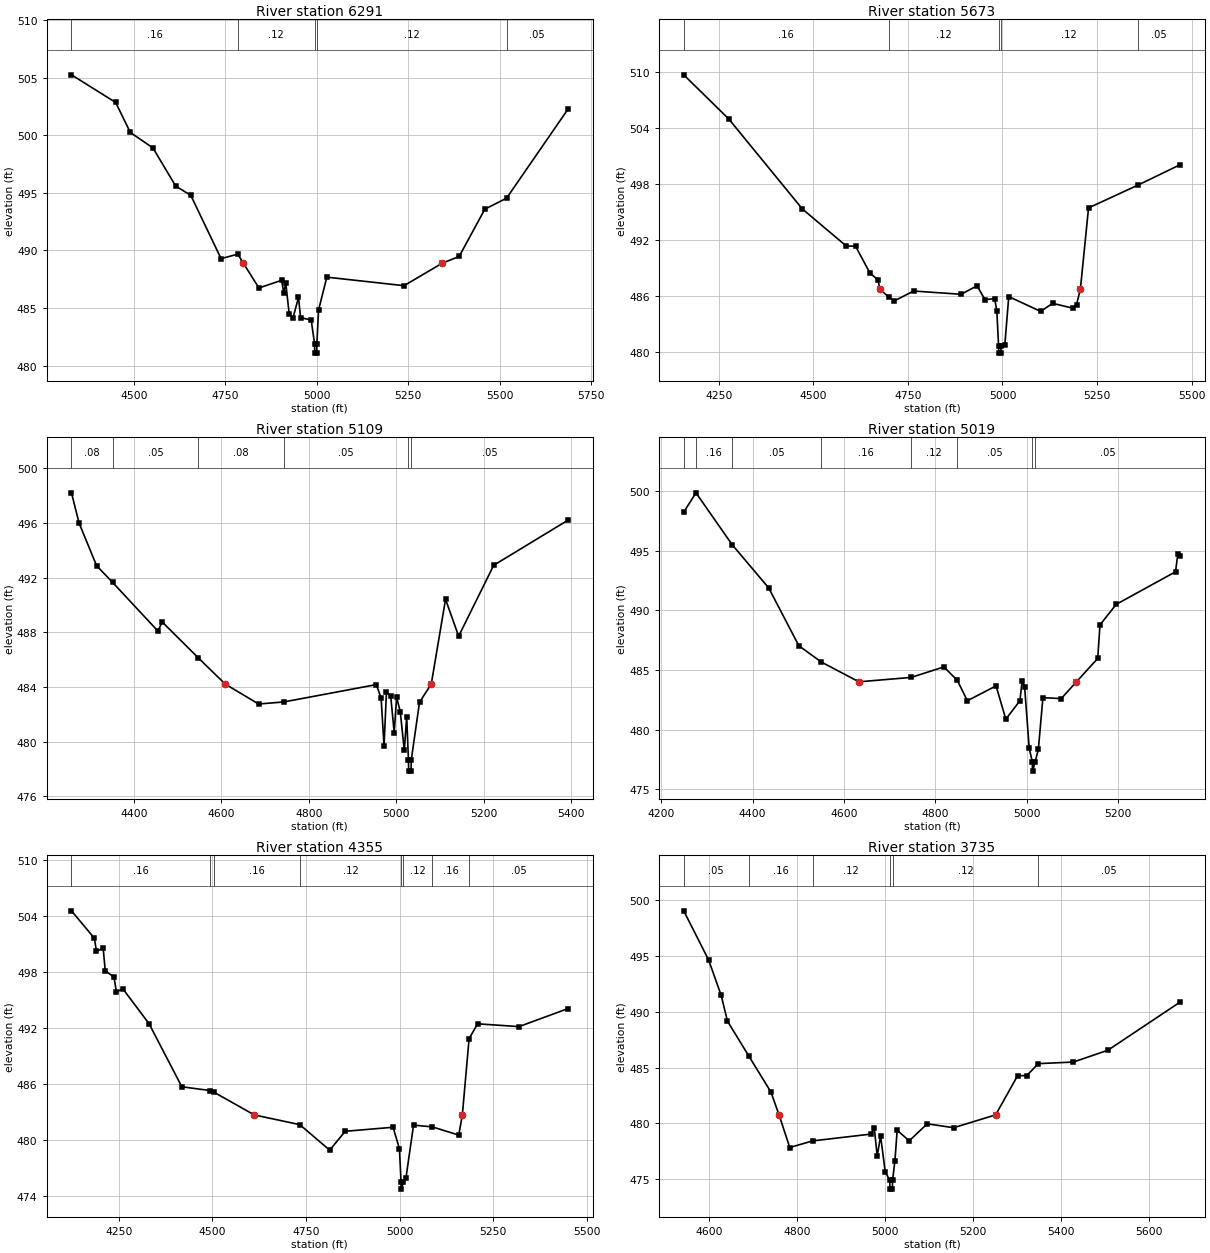
Type RM Length L Ch R = 1,6291,618,618,618
BEGIN DESCRIPTION:
UNT 035 in Running Cr Watershed 7.0
END DESCRIPTION:
XS GIS Cut Line= 3
      2902050.34      7068769.91      2901875.00      7069425.00
      2901941.73      7070101.17
#Sta/Elev= 30
  4329.6  505.26  4450.4  502.86  4490.5  500.25  4552.3  498.91  4614.4  495.60
  4655.8  494.79  4738.6  489.29  4784.4  489.68  4799.7  488.89  4842.1  486.74
  4904.2  487.41  4910.2  486.27  4915.4  487.21  4924.9  484.47  4935.3  484.13
  4950.3  485.93  4956.0  484.16  4985.1  483.96  4994.2  481.88  4994.7  481.08
  5000.0  481.08  5000.5  481.88  5005.2  484.83  5027.8  487.68  5238.9  486.94
  5343.1  488.89  5389.6  489.48  5459.9  493.59  5519.2  494.54  5687.2  502.28
#Mann=5,-1,0
  4329.6    0.16       0  4784.4    0.12       0  4994.2    0.07       0
  5000.5    0.12       0  5519.2    0.05       0
Bank Sta=4799.7,5343.1
Exp/Cntr=0.3,0.1

Type RM Length L Ch R = 1,5673,564,564,564
BEGIN DESCRIPTION:
UNT 035 in Running Cr Watershed 6.0
END DESCRIPTION:
XS GIS Cut Line= 3
      2901775.00      7068624.99      2901525.00      7069425.00
      2901375.00      7069875.00
#Sta/Elev= 30
  4157.4  509.71  4276.3  504.99  4471.2  495.34  4587.0  491.38  4611.6  491.36
  4649.8  488.47  4670.8  487.77  4676.0  486.75  4699.2  485.92  4714.3  485.51
  4765.1  486.56  4890.8  486.21  4932.7  487.12  4953.7  485.64  4979.3  485.74
  4985.1  484.43  4989.7  480.71  4990.2  479.91  4995.6  479.91  4996.1  480.71
  5006.1  480.76  5016.6  485.96  5101.0  484.38  5132.6  485.24  5185.3  484.73
  5195.8  485.11  5205.9  486.75  5227.5  495.46  5357.5  497.89  5469.9  500.09
#Mann=5,-1,0
  4157.4    0.16       0  4699.2    0.12       0  4989.7    0.07       0
  4996.1    0.12       0  5357.5    0.05       0
Bank Sta=4676,5205.9
Exp/Cntr=0.3,0.1

Type RM Length L Ch R = 1,5109,90,90,90
BEGIN DESCRIPTION:
Mapping XS ceea9397
END DESCRIPTION:
XS GIS Cut Line= 4
      2901195.86      7068497.68      2901169.82      7069091.41
      2901089.09      7069271.09      2901078.68      7069614.85
#Sta/Elev= 30
  4257.1  498.21  4274.4  496.00  4314.5  492.88  4351.0  491.66  4454.6  488.10
  4464.6  488.76  4546.6  486.15  4608.5  484.22  4684.8  482.76  4742.3  482.91
  4954.0  484.18  4965.0  483.19  4971.7  479.69  4977.2  483.63  4986.9  483.35
  4994.9  480.67  5000.4  483.24  5008.8  482.21  5018.0  479.36  5023.5  481.84
  5027.5  478.65  5028.0  477.85  5033.4  477.85  5033.9  478.65  5052.8  482.89
  5079.7  484.22  5112.3  490.42  5142.3  487.72  5222.4  492.91  5392.3  496.21
#Mann=6,-1,0
  4257.1    0.08       0  4351.0    0.05       0  4546.6    0.08       0
  4742.3    0.05       0  5027.5    0.04       0  5033.9    0.05       0
Bank Sta=4608.5,5079.7
Exp/Cntr=0.3,0.1

Type RM Length L Ch R = 1,5019,664,664,664
BEGIN DESCRIPTION:
UNT 035 in Running Cr Watershed 5.0
END DESCRIPTION:
XS GIS Cut Line= 4
      2901117.74      7068483.32      2901094.30      7069043.23
      2901031.80      7069178.64      2901009.67      7069554.95
#Sta/Elev= 30
  4249.5  498.26  4276.3  499.88  4355.2  495.54  4435.5  491.89  4501.4  487.04
  4550.6  485.67  4632.9  484.01  4747.2  484.38  4818.8  485.26  4848.2  484.13
  4870.2  482.42  4933.0  483.67  4954.3  480.87  4985.1  482.42  4990.1  484.10
  4995.5  483.58  5005.5  478.42  5012.3  477.31  5012.8  476.51  5018.7  477.31
  5025.5  478.33  5035.5  482.68  5075.6  482.60  5108.8  484.01  5155.4  485.97
  5160.4  488.79  5195.8  490.51  5325.7  493.25  5330.7  494.75  5336.0  494.54
#Mann=8,-1,0
  4249.5    0.08       0  4276.3    0.16       0  4355.2    0.05       0
  4550.6    0.16       0  4747.2    0.12       0  4848.2    0.05       0
  5012.3    0.04       0  5018.7    0.05       0
Bank Sta=4632.9,5108.8
Exp/Cntr=0.3,0.1

Type RM Length L Ch R = 1,4355,620,620,620
BEGIN DESCRIPTION:
UNT 035 in Running Cr Watershed 4.0
END DESCRIPTION:
XS GIS Cut Line= 3
      2900975.02      7068274.97      2900625.00      7069075.00
      2900575.00      7069524.98
#Sta/Elev= 30
  4123.7  504.52  4184.9  501.58  4190.4  500.18  4208.3  500.53  4213.8  498.11
  4237.2  497.43  4243.8  495.82  4260.6  496.19  4330.7  492.45  4418.4  485.69
  4494.1  485.29  4505.5  485.08  4611.9  482.68  4733.4  481.64  4813.3  478.91
  4854.7  480.93  4982.5  481.36  4999.5  479.06  5003.8  475.54  5004.3  474.74
  5010.3  475.54  5017.1  475.98  5037.2  481.59  5087.5  481.40  5157.9  480.52
  5167.5  482.67  5185.6  490.85  5208.2  492.43  5318.9  492.13  5449.7  494.06
#Mann=8,-1,0
  4123.7    0.16       0  4494.1    0.05       0  4505.5    0.16       0
  4733.4    0.12       0  5003.8    0.07       0  5010.3    0.12       0
  5087.5    0.16       0  5185.6    0.05       0
Bank Sta=4611.9,5167.5
Exp/Cntr=0.3,0.1

Type RM Length L Ch R = 1,3735,1268,1268,1268
BEGIN DESCRIPTION:
UNT 035 in Running Cr Watershed 3.0
END DESCRIPTION:
XS GIS Cut Line= 3
      2900624.99      7068275.01      2900325.00      7068625.00
      2900175.01      7069274.95
#Sta/Elev= 30
  4543.2  499.01  4599.7  494.62  4628.3  491.45  4642.5  489.15  4690.7  486.05
  4741.3  482.81  4759.7  480.77  4784.1  477.85  4835.8  478.44  4968.5  479.05
  4976.2  479.57  4982.8  477.08  4990.4  478.89  5000.9  475.70  5011.2  474.93
  5011.7  474.13  5017.2  474.13  5017.7  474.93  5023.0  476.68  5028.1  479.39
  5055.5  478.45  5096.5  479.97  5156.4  479.62  5251.9  480.77  5301.8  484.28
  5322.3  484.27  5348.8  485.35  5428.4  485.49  5507.0  486.55  5671.2  490.86
#Mann=6,-1,0
  4543.2    0.05       0  4690.7    0.16       0  4835.8    0.12       0
  5011.2    0.07       0  5017.7    0.12       0  5348.8    0.05       0
Bank Sta=4759.7,5251.9
Exp/Cntr=0.3,0.1

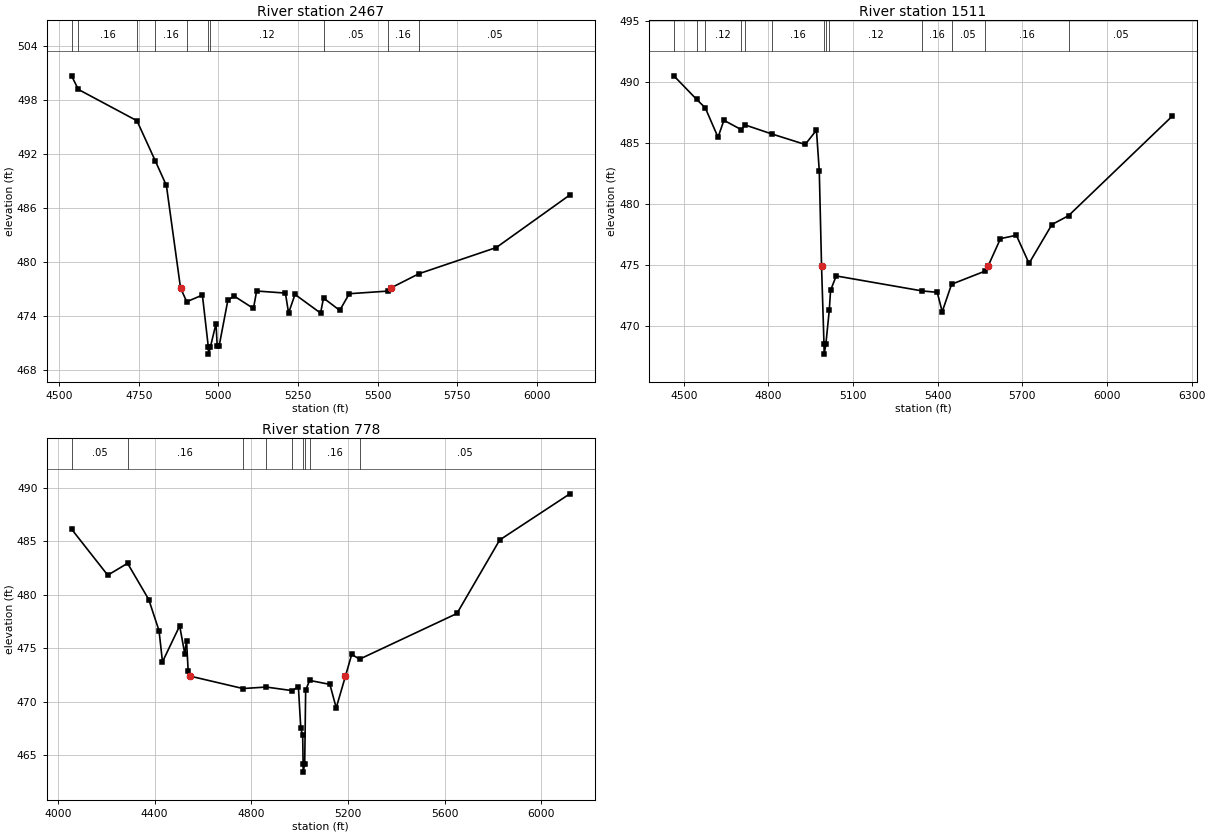
Type RM Length L Ch R = 1,2467,956,956,956
BEGIN DESCRIPTION:
UNT 035 in Running Cr Watershed 2.0
END DESCRIPTION:
XS GIS Cut Line= 3
      2900074.97      7067775.04      2899775.00      7068125.00
      2899675.00      7069225.03
#Sta/Elev= 30
  4538.6  500.66  4559.8  499.15  4744.0  495.67  4801.4  491.23  4836.5  488.48
  4880.9  477.10  4900.4  475.57  4949.6  476.31  4968.2  470.55  4968.7  469.75
  4974.8  470.55  4992.4  473.15  4996.2  470.62  5002.0  470.62  5029.7  475.75
  5049.7  476.19  5110.0  474.82  5120.0  476.76  5210.4  476.53  5220.4  474.31
  5240.5  476.38  5320.9  474.31  5330.1  475.98  5381.1  474.61  5411.2  476.46
  5531.9  476.75  5541.7  477.10  5629.9  478.68  5873.1  481.59  6104.1  487.43
#Mann=10,-1,0
  4538.6    0.05       0  4559.8    0.16       0  4744.0    0.12       0
  4801.4    0.16       0  4900.4    0.12       0  4968.2    0.07       0
  4974.8    0.12       0  5330.1    0.05       0  5531.9    0.16       0
  5629.9    0.05       0
Bank Sta=4880.9,5541.7
Exp/Cntr=0.3,0.1

Type RM Length L Ch R = 1,1511,733,733,733
BEGIN DESCRIPTION:
Mapping XS 85558655
END DESCRIPTION:
XS GIS Cut Line= 4
      2899515.60      7067684.84      2899211.81      7068027.68
      2899220.49      7068405.29      2899506.83      7069290.34
#Sta/Elev= 30
  4464.8  490.49  4545.5  488.56  4576.1  487.87  4621.3  485.46  4642.2  486.85
  4704.1  486.08  4717.1  486.47  4812.3  485.73  4930.2  484.87  4970.2  486.04
  4980.2  482.70  4988.2  474.95  4996.9  468.51  4997.4  467.71  5003.5  468.51
  5015.8  471.35  5020.2  472.93  5040.2  474.11  5345.5  472.88  5398.3  472.77
  5415.9  471.18  5449.1  473.43  5567.2  474.50  5579.1  474.95  5622.3  477.16
  5678.6  477.44  5723.6  475.14  5804.8  478.32  5863.5  479.04  6230.8  487.18
#Mann=13,-1,0
  4464.8    0.16       0  4545.5    0.05       0  4576.1    0.12       0
  4704.1    0.16       0  4717.1    0.05       0  4812.3    0.16       0
  4996.9    0.07       0  5003.5    0.16       0  5015.8    0.12       0
  5345.5    0.16       0  5449.1    0.05       0  5567.2    0.16       0
  5863.5    0.05       0
Bank Sta=4988.2,5579.1
Exp/Cntr=0.3,0.1

Type RM Length L Ch R = 1,778,0,0,0
BEGIN DESCRIPTION:
UNT 035 in Running Cr Watershed 1.0
END DESCRIPTION:
XS GIS Cut Line= 4
      2899211.83      7067710.82      2898786.46      7068183.93
      2898825.53      7068717.79      2899424.97      7069374.97
#Sta/Elev= 30
  4056.4  486.15  4206.0  481.84  4287.9  482.95  4375.6  479.56  4418.2  476.63
  4432.4  473.72  4503.5  477.09  4524.4  474.50  4531.9  475.71  4538.6  472.87
  4547.2  472.38  4765.4  471.22  4861.6  471.36  4969.9  471.02  4994.5  471.41
  5004.5  467.49  5012.3  466.86  5014.0  464.19  5014.5  463.39  5020.7  464.19
  5024.6  471.07  5041.1  471.98  5124.8  471.61  5151.0  469.41  5189.2  472.38
  5215.1  474.42  5247.5  473.97  5650.3  478.25  5827.3  485.14  6117.4  489.46
#Mann=9,-1,0
  4056.4    0.05       0  4287.9    0.16       0  4765.4    0.12       0
  4861.6    0.16       0  4969.9    0.12       0  5014.0    0.07       0
  5020.7    0.12       0  5041.1    0.16       0  5247.5    0.05       0
Bank Sta=4547.2,5189.2
Exp/Cntr=0.3,0.1

Chan Stop Cuts=-1