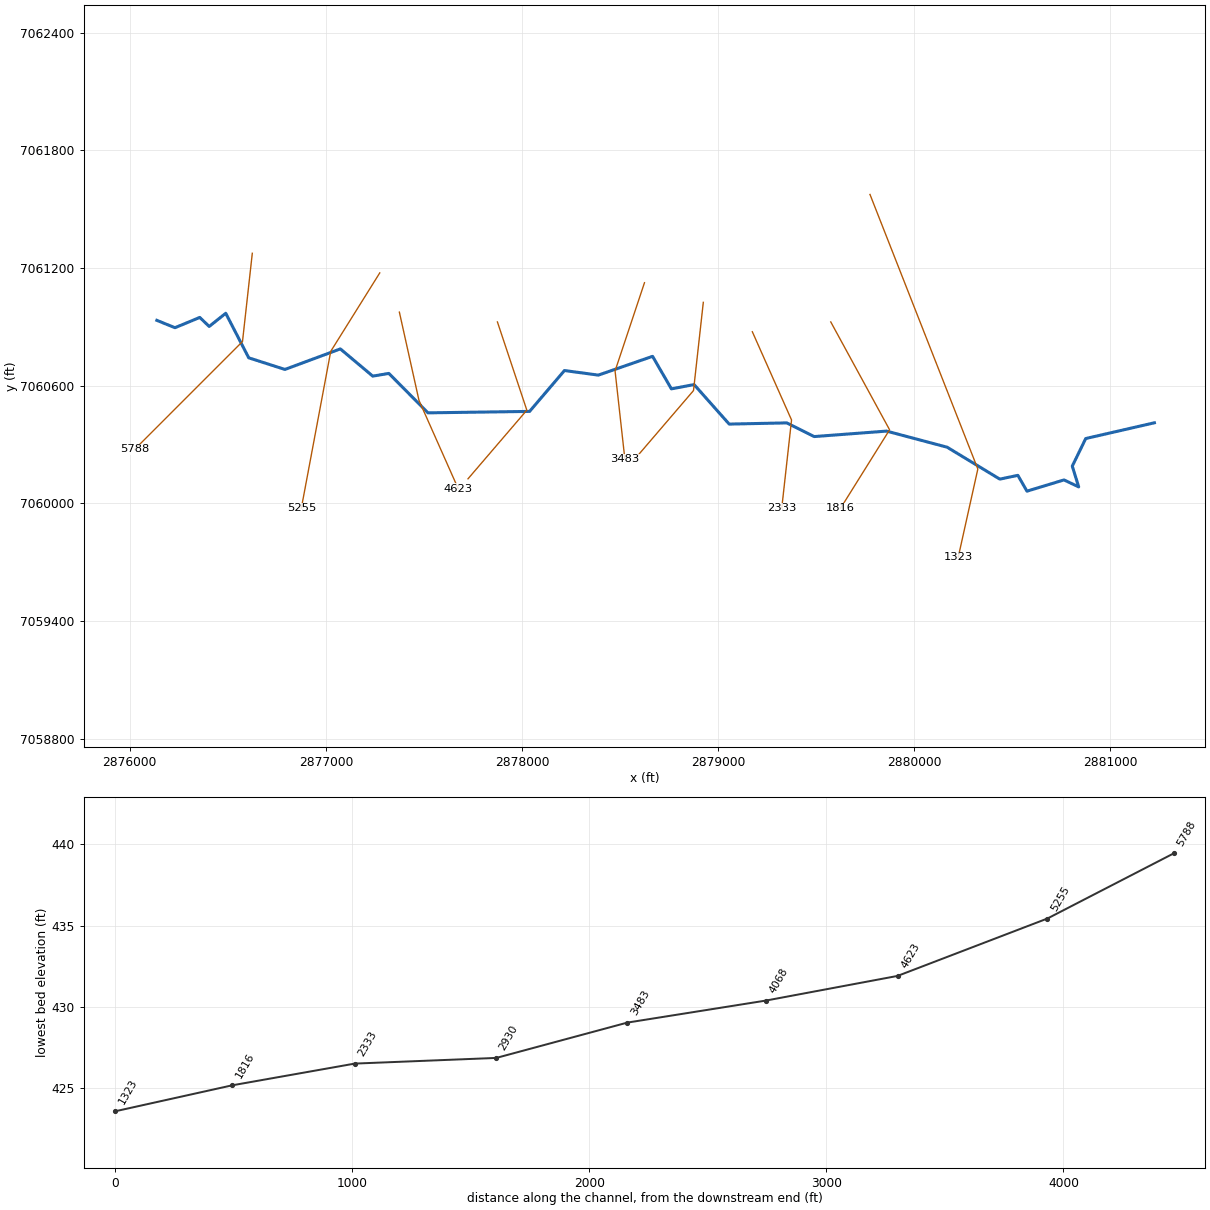
--- UNT 036 in Running Cr Watershed.prj (project) ---

Proj Title=UNT 036 in Running Cr Watershed Base Level Engineering
Current Plan=p01
Default Exp/Contr=0.3,0.1
English Units
Geom File=g01
Flow File=f01
Plan File=p01
BEGIN DESCRIPTION:
UNT 036 in Running Cr Watershed
END DESCRIPTION:

--- UNT 036 in Running Cr Watershed.p01 (plan) ---

Plan Title=Multiple Run
Short Identifier=Multiple
Geom File=g01
Flow File=f01
Subcritical Flow
K Sum by GR= 0
Std Step Tol= 0.01
Critical Tol= 0.01
Num of Std Step Trials= 20
Max Error Tol= 0.3
Flow Tol Ratio= 0.001
Split Flow NTrial= 30
Split Flow Tol= 0.02
Split Flow Ratio= 0.02
Log Output Level= 0
Friction Slope Method= 1
Unsteady Friction Slope Method= 2
Unsteady Bridges Friction Slope Method= 1
Parabolic Critical Depth
Global Vel Dist=  1 , 1 , 1
Global Log Level= 0
CheckData=True
Encroach Param= -1, 0, 0, 0
BEGIN DESCRIPTION:
Multiple Run
END DESCRIPTION:

--- UNT 036 in Running Cr Watershed.f01 (steady flow) ---

Flow Title=Multiple
Number of Profiles=7
Profile Names=10-year,25-year,50-year,1pct_min,100-year,1pct_plu,500-year
River Rch & RM= UNT 036 in Runni,Reach-1,5788
     948    1291    1574     951    1897    3784    2752
Boundary for River Rch & Prof#=UNT 036 in Runni,Reach-1,1
Up Type=0
Dn Type=3
Dn Slope=0.005
Boundary for River Rch & Prof#=UNT 036 in Runni,Reach-1,2
Up Type=0
Dn Type=3
Dn Slope=0.005
Boundary for River Rch & Prof#=UNT 036 in Runni,Reach-1,3
Up Type=0
Dn Type=3
Dn Slope=0.005
Boundary for River Rch & Prof#=UNT 036 in Runni,Reach-1,4
Up Type=0
Dn Type=3
Dn Slope=0.005
Boundary for River Rch & Prof#=UNT 036 in Runni,Reach-1,5
Up Type=0
Dn Type=3
Dn Slope=0.005
Boundary for River Rch & Prof#=UNT 036 in Runni,Reach-1,6
Up Type=0
Dn Type=3
Dn Slope=0.005
Boundary for River Rch & Prof#=UNT 036 in Runni,Reach-1,7
Up Type=0
Dn Type=3
Dn Slope=0.005

--- UNT 036 in Running Cr Watershed.g01 (geometry) ---

Geom Title=Existing Conditions

River Reach=UNT 036 in Runni,Reach-1
Reach XY= 30
      2876138.07      7060933.18      2876230.60      7060895.46
      2876357.05      7060947.93      2876405.25      7060901.87
      2876489.49      7060969.10      2876606.87      7060741.90
      2876791.48      7060682.72      2877074.03      7060787.39
      2877239.18      7060648.64      2877321.50      7060662.42
      2877520.77      7060461.38      2878039.15      7060468.72
      2878216.86      7060677.12      2878389.75      7060653.77
      2878666.27      7060749.52      2878762.28      7060583.62
      2878878.00      7060605.52      2879056.94      7060404.09
      2879350.63      7060410.12      2879490.59      7060340.41
      2879859.58      7060368.28      2880168.41      7060286.15
      2880436.94      7060123.45      2880529.03      7060142.66
      2880575.49      7060062.05      2880764.44      7060119.33
      2880839.40      7060083.77      2880806.63      7060189.71
      2880875.30      7060330.39      2881225.59      7060410.71

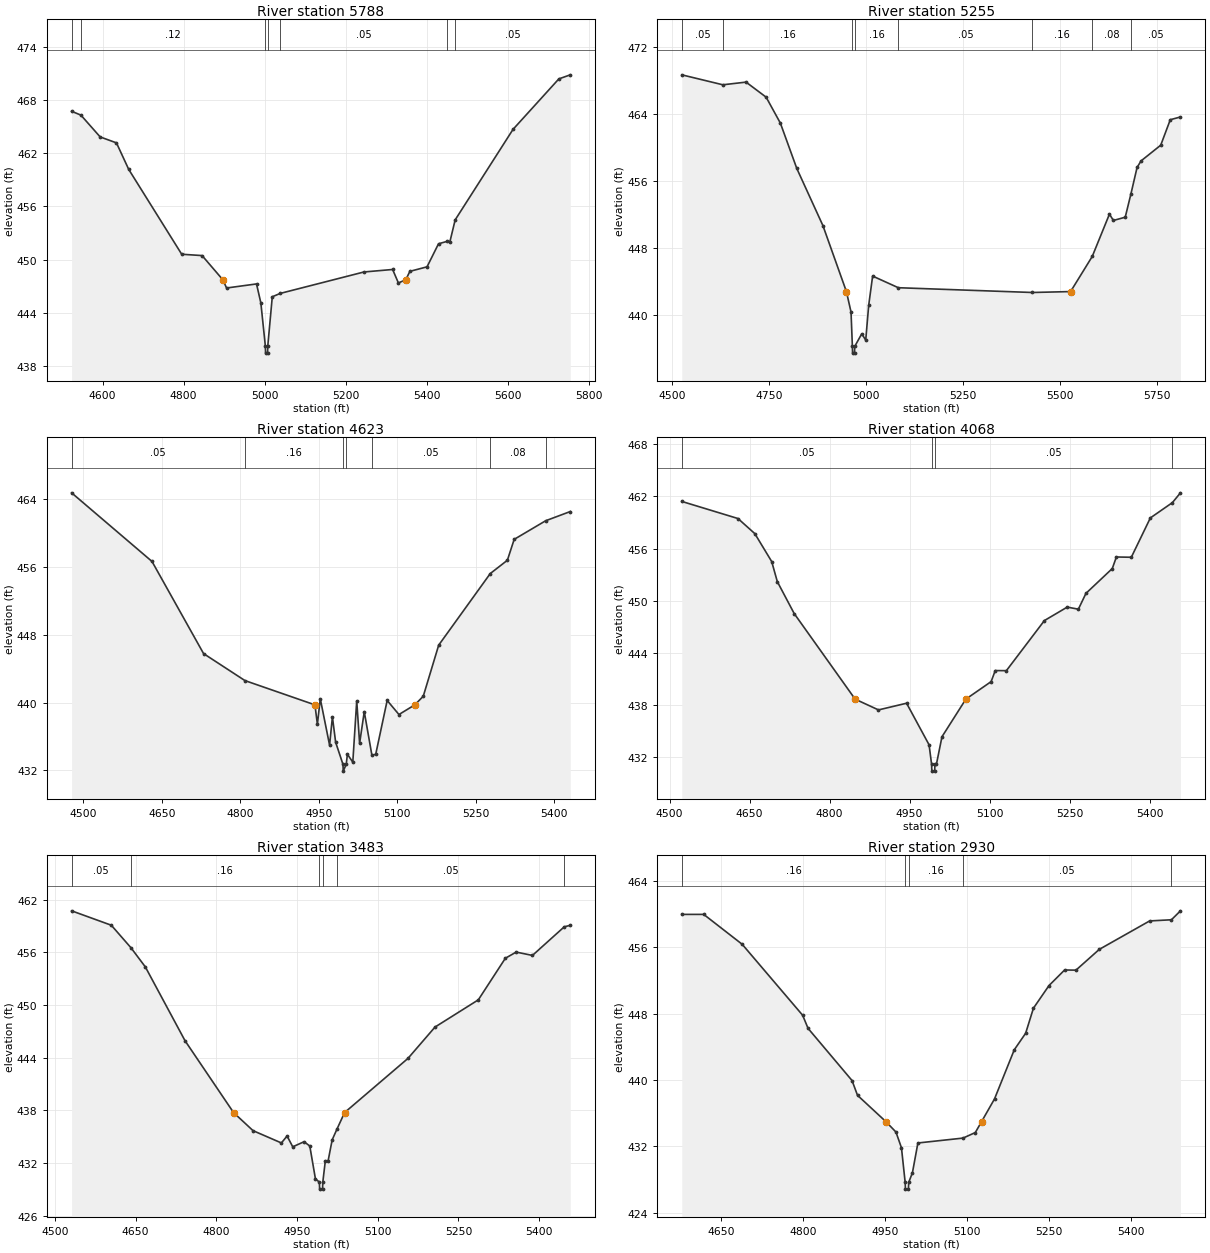
Type RM Length L Ch R = 1,5788,533,533,533
BEGIN DESCRIPTION:
UNT 036 in Running Cr Watershed 9.0
END DESCRIPTION:
XS GIS Cut Line= 3
      2876625.00      7061275.04      2876575.00      7060825.00
      2876025.02      7060275.02
#Sta/Elev= 30
  4523.5  466.75  4546.5  466.31  4594.0  463.85  4634.2  463.18  4664.4  460.19
  4795.2  450.61  4845.5  450.46  4896.7  447.73  4905.9  446.80  4979.8  447.26
  4990.5  445.12  5001.6  440.25  5002.1  439.45  5007.1  439.45  5007.6  440.25
  5018.7  445.81  5038.3  446.19  5245.0  448.61  5315.7  448.89  5329.9  447.37
  5348.2  447.73  5358.2  448.68  5400.6  449.19  5428.9  451.79  5449.0  452.05
  5457.1  452.04  5470.0  454.49  5612.7  464.70  5725.8  470.40  5754.1  470.86
#Mann=7,-1,0
  4523.5    0.05       0  4546.5    0.12       0  5001.6    0.07       0
  5007.6    0.12       0  5038.3    0.05       0  5449.0    0.08       0
  5470.0    0.05       0
Bank Sta=4896.7,5348.2
Exp/Cntr=0.3,0.1

Type RM Length L Ch R = 1,5255,632,632,632
BEGIN DESCRIPTION:
UNT 036 in Running Cr Watershed 8.0
END DESCRIPTION:
XS GIS Cut Line= 3
      2877274.98      7061174.97      2877025.00      7060775.00
      2876875.00      7059975.01
#Sta/Elev= 30
  4525.5  468.66  4631.4  467.47  4691.2  467.79  4743.0  465.99  4779.6  462.90
  4822.0  457.48  4889.3  450.66  4949.9  442.78  4961.8  440.34  4965.3  436.23
  4965.8  435.43  4970.8  435.43  4971.3  436.23  4989.5  437.74  4999.7  436.98
  5007.3  441.12  5017.5  444.63  5083.8  443.24  5429.4  442.67  5527.8  442.78
  5583.6  446.97  5628.0  452.03  5638.1  451.27  5668.7  451.66  5683.6  454.49
  5699.2  457.60  5709.4  458.38  5760.2  460.26  5784.8  463.30  5811.1  463.63
#Mann=8,-1,0
  4525.5    0.05       0  4631.4    0.16       0  4965.3    0.07       0
  4971.3    0.16       0  5083.8    0.05       0  5429.4    0.16       0
  5583.6    0.08       0  5683.6    0.05       0
Bank Sta=4949.9,5527.8
Exp/Cntr=0.3,0.1

Type RM Length L Ch R = 1,4623,555,555,555
BEGIN DESCRIPTION:
UNT 036 in Running Cr Watershed 7.0
END DESCRIPTION:
XS GIS Cut Line= 3
      2877374.99      7060975.03      2877475.00      7060525.00
      2877674.98      7060075.05
#Sta/Elev= 30
  4477.6  464.78  4631.3  456.67  4729.9  445.78  4809.0  442.59  4942.8  439.72
  4947.5  437.42  4953.0  440.45  4970.8  434.96  4976.2  438.29  4982.4  435.30
  4996.4  432.69  4996.9  431.89  5002.6  432.69  5004.9  433.88  5015.2  432.95
  5022.7  440.20  5028.2  435.17  5037.1  438.92  5051.7  433.77  5059.0  433.88
  5080.9  440.24  5103.4  438.58  5133.7  439.72  5149.9  440.74  5179.4  446.78
  5278.0  455.24  5310.7  456.81  5323.7  459.28  5383.9  461.48  5431.0  462.57
#Mann=7,-1,0
  4477.6    0.05       0  4809.0    0.16       0  4996.4    0.07       0
  5002.6    0.16       0  5051.7    0.05       0  5278.0    0.08       0
  5383.9    0.05       0
Bank Sta=4942.8,5133.7
Exp/Cntr=0.3,0.1

Type RM Length L Ch R = 1,4068,585,585,585
BEGIN DESCRIPTION:
UNT 036 in Running Cr Watershed 6.0
END DESCRIPTION:
XS GIS Cut Line= 3
      2877875.01      7060924.97      2878025.00      7060475.00
      2877724.99      7060124.99
#Sta/Elev= 30
  4522.8  461.43  4628.2  459.46  4659.8  457.72  4691.4  454.51  4702.0  452.19
  4733.6  448.52  4847.9  438.66  4891.7  437.42  4944.4  438.19  4986.6  433.40
  4991.3  431.17  4991.8  430.37  4997.1  430.37  4997.6  431.17  5000.4  431.17
  5010.8  434.33  5055.6  438.66  5103.0  440.68  5110.7  441.95  5131.6  441.94
  5202.9  447.71  5245.7  449.26  5266.6  449.02  5280.8  450.84  5330.2  453.70
  5337.9  455.03  5365.9  455.00  5401.6  459.53  5442.9  461.29  5458.1  462.42
#Mann=4,-1,0
  4522.8    0.05       0  4991.3    0.03       0  4997.6    0.05       0
  5442.9    0.08       0
Bank Sta=4847.9,5055.6
Exp/Cntr=0.3,0.1

Type RM Length L Ch R = 1,3483,553,553,553
BEGIN DESCRIPTION:
UNT 036 in Running Cr Watershed 5.0
END DESCRIPTION:
XS GIS Cut Line= 3
      2878625.01      7061125.03      2878475.00      7060675.00
      2878524.99      7060225.05
#Sta/Elev= 30
  4530.9  460.71  4604.7  459.07  4641.3  456.50  4668.0  454.32  4741.8  445.91
  4832.0  437.73  4868.2  435.67  4920.9  434.27  4931.5  435.06  4942.0  433.83
  4963.1  434.41  4973.7  433.92  4984.2  430.18  4991.5  429.81  4992.0  429.01
  4997.4  429.01  4997.9  429.81  5002.6  432.24  5007.8  432.24  5015.3  434.62
  5024.1  435.83  5038.4  437.73  5156.2  443.90  5206.5  447.47  5287.0  450.57
  5337.3  455.31  5357.4  456.01  5387.6  455.63  5446.8  458.89  5458.0  459.06
#Mann=6,-1,0
  4530.9    0.05       0  4641.3    0.16       0  4991.5    0.07       0
  4997.9    0.16       0  5024.1    0.05       0  5446.8    0.08       0
Bank Sta=4832,5038.4
Exp/Cntr=0.3,0.1

Type RM Length L Ch R = 1,2930,597,597,597
BEGIN DESCRIPTION:
UNT 036 in Running Cr Watershed 4.0
END DESCRIPTION:
XS GIS Cut Line= 3
      2878925.00      7061025.00      2878875.00      7060575.00
      2878575.03      7060225.04
#Sta/Elev= 30
  4577.6  459.99  4617.8  459.99  4688.3  456.38  4799.0  447.82  4809.0  446.23
  4889.5  439.94  4899.6  438.15  4951.7  434.97  4970.0  433.72  4980.1  431.82
  4986.9  427.63  4987.4  426.83  4992.8  426.83  4993.3  427.63  5000.2  428.81
  5010.2  432.40  5092.9  432.99  5115.4  433.66  5126.8  434.97  5150.6  437.72
  5186.8  443.65  5207.6  445.64  5221.9  448.67  5250.4  451.40  5279.0  453.28
  5299.8  453.26  5342.6  455.77  5434.8  459.20  5474.7  459.34  5491.3  460.42
#Mann=5,-1,0
  4577.6    0.16       0  4986.9    0.07       0  4993.3    0.16       0
  5092.9    0.05       0  5474.7    0.08       0
Bank Sta=4951.7,5126.8
Exp/Cntr=0.3,0.1

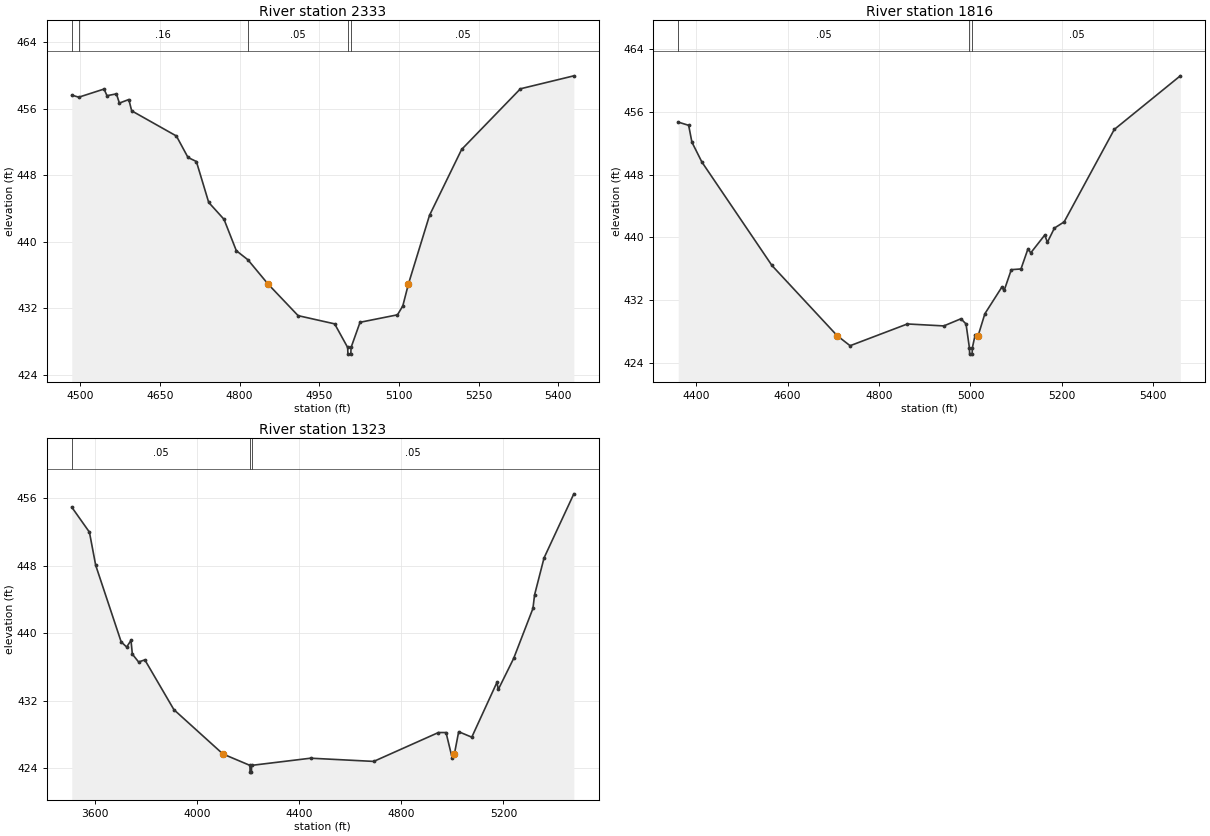
Type RM Length L Ch R = 1,2333,517,517,517
BEGIN DESCRIPTION:
UNT 036 in Running Cr Watershed 3.0
END DESCRIPTION:
XS GIS Cut Line= 3
      2879175.01      7060874.98      2879375.00      7060425.00
      2879325.00      7059974.99
#Sta/Elev= 30
  4484.2  457.64  4497.4  457.39  4545.0  458.37  4550.5  457.57  4568.3  457.79
  4573.8  456.68  4591.6  457.11  4597.0  455.75  4681.2  452.72  4703.0  450.14
  4718.8  449.65  4742.0  444.73  4770.8  442.70  4794.0  438.92  4815.8  437.83
  4853.6  434.92  4910.3  431.11  4979.1  430.12  5003.6  427.28  5004.1  426.48
  5009.5  426.48  5010.0  427.28  5026.9  430.31  5097.4  431.21  5107.4  432.28
  5118.0  434.92  5157.7  443.18  5218.1  451.10  5328.8  458.40  5429.4  459.96
#Mann=5,-1,0
  4484.2    0.05       0  4497.4    0.16       0  4815.8    0.05       0
  5003.6    0.03       0  5010.0    0.05       0
Bank Sta=4853.6,5118
Exp/Cntr=0.3,0.1

Type RM Length L Ch R = 1,1816,493,493,493
BEGIN DESCRIPTION:
UNT 036 in Running Cr Watershed 2.0
END DESCRIPTION:
XS GIS Cut Line= 3
      2879575.00      7060925.00      2879875.00      7060375.00
      2879625.00      7059975.00
#Sta/Elev= 30
  4360.8  454.67  4383.6  454.26  4390.7  452.12  4412.5  449.59  4565.8  436.42
  4708.1  427.51  4736.7  426.21  4862.0  428.98  4941.7  428.73  4979.2  429.64
  4990.3  428.98  4997.7  425.94  4998.2  425.14  5003.6  425.14  5004.1  425.94
  5010.3  427.61  5016.9  427.51  5031.5  430.28  5068.1  433.62  5074.0  433.29
  5089.3  435.89  5110.5  435.98  5125.9  438.56  5131.8  438.02  5162.4  440.29
  5168.3  439.38  5183.6  441.18  5204.9  441.97  5314.5  453.73  5459.0  460.56
#Mann=3,-1,0
  4360.8    0.05       0  4997.7    0.03       0  5004.1    0.05       0
Bank Sta=4708.1,5016.9
Exp/Cntr=0.3,0.1

Type RM Length L Ch R = 1,1323,0,0,0
BEGIN DESCRIPTION:
UNT 036 in Running Cr Watershed 1.0
END DESCRIPTION:
XS GIS Cut Line= 3
      2879774.99      7061575.03      2880325.00      7060175.00
      2880224.99      7059724.97
#Sta/Elev= 30
  3510.2  454.93  3579.3  451.97  3603.8  448.05  3703.6  438.97  3725.1  438.36
  3742.0  439.15  3747.3  437.52  3771.8  436.59  3796.2  436.84  3910.0  430.94
  4101.8  425.69  4207.6  424.34  4208.1  423.54  4213.5  423.54  4214.0  424.34
  4445.0  425.19  4692.1  424.81  4945.3  428.23  4975.1  428.23  4999.5  425.18
  5007.9  425.69  5024.6  428.33  5075.9  427.68  5174.5  434.18  5179.6  433.33
  5239.8  437.01  5315.3  442.93  5321.7  444.54  5358.8  448.92  5475.4  456.51
#Mann=3,-1,0
  3510.2    0.05       0  4207.6    0.03       0  4214.0    0.05       0
Bank Sta=4101.8,5007.9
Exp/Cntr=0.3,0.1

Chan Stop Cuts=-1