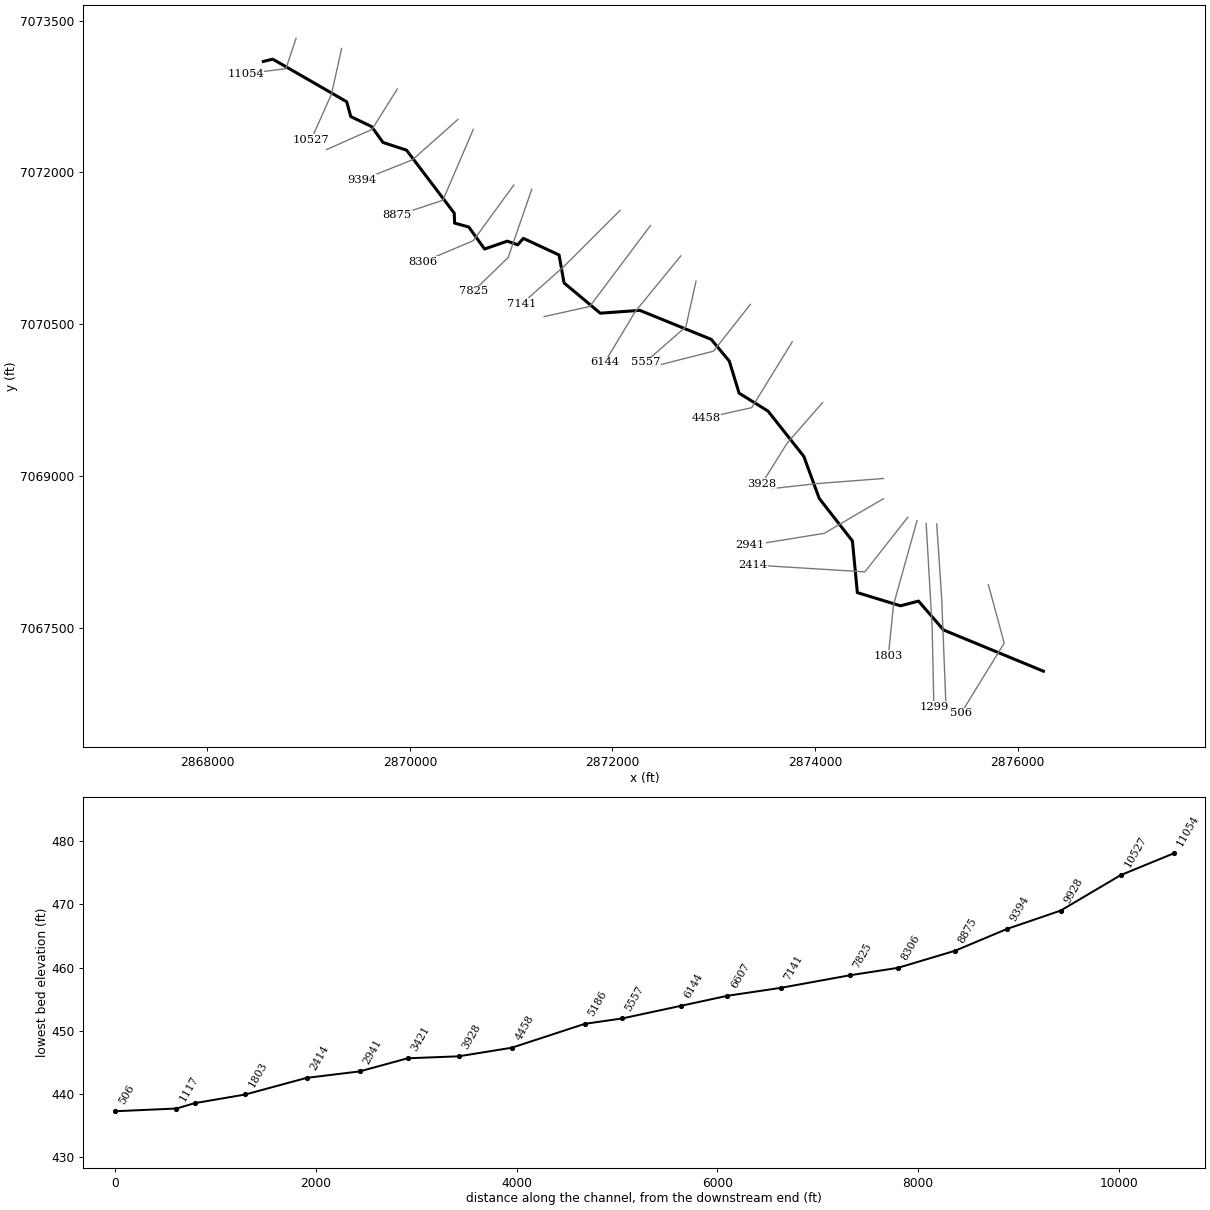
--- UNT 037 in Running Cr Watershed.prj (project) ---

Proj Title=UNT 037 in Running Cr Watershed Base Level Engineering
Current Plan=p01
Default Exp/Contr=0.3,0.1
English Units
Geom File=g01
Flow File=f01
Plan File=p01
BEGIN DESCRIPTION:
UNT 037 in Running Cr Watershed
END DESCRIPTION:

--- UNT 037 in Running Cr Watershed.p01 (plan) ---

Plan Title=Multiple Run
Short Identifier=Multiple
Geom File=g01
Flow File=f01
Subcritical Flow
K Sum by GR= 0
Std Step Tol= 0.01
Critical Tol= 0.01
Num of Std Step Trials= 20
Max Error Tol= 0.3
Flow Tol Ratio= 0.001
Split Flow NTrial= 30
Split Flow Tol= 0.02
Split Flow Ratio= 0.02
Log Output Level= 0
Friction Slope Method= 1
Unsteady Friction Slope Method= 2
Unsteady Bridges Friction Slope Method= 1
Parabolic Critical Depth
Global Vel Dist=  1 , 1 , 1
Global Log Level= 0
CheckData=True
Encroach Param= -1, 0, 0, 0
BEGIN DESCRIPTION:
Multiple Run
END DESCRIPTION:

--- UNT 037 in Running Cr Watershed.f01 (steady flow) ---

Flow Title=Multiple
Number of Profiles=7
Profile Names=10-year,25-year,50-year,1pct_min,100-year,1pct_plu,500-year
River Rch & RM= UNT 037 in Runni,Reach-1,11054
     712     953    1149     687    1370    2734    1944
River Rch & RM= UNT 037 in Runni,Reach-1,10527
    1224    1694    2086    1273    2539    5066    3754
River Rch & RM= UNT 037 in Runni,Reach-1,7825
    1301    1803    2222    1355    2705    5396    4001
River Rch & RM= UNT 037 in Runni,Reach-1,4458
    1380    1915    2362    1442    2877    5741    4261
River Rch & RM= UNT 037 in Runni,Reach-1,1803
    1865    2627    3274    2017    4024    8028    6071
Boundary for River Rch & Prof#=UNT 037 in Runni,Reach-1,1
Up Type=0
Dn Type=3
Dn Slope=0.005
Boundary for River Rch & Prof#=UNT 037 in Runni,Reach-1,2
Up Type=0
Dn Type=3
Dn Slope=0.005
Boundary for River Rch & Prof#=UNT 037 in Runni,Reach-1,3
Up Type=0
Dn Type=3
Dn Slope=0.005
Boundary for River Rch & Prof#=UNT 037 in Runni,Reach-1,4
Up Type=0
Dn Type=3
Dn Slope=0.005
Boundary for River Rch & Prof#=UNT 037 in Runni,Reach-1,5
Up Type=0
Dn Type=3
Dn Slope=0.005
Boundary for River Rch & Prof#=UNT 037 in Runni,Reach-1,6
Up Type=0
Dn Type=3
Dn Slope=0.005
Boundary for River Rch & Prof#=UNT 037 in Runni,Reach-1,7
Up Type=0
Dn Type=3
Dn Slope=0.005

--- UNT 037 in Running Cr Watershed.g01 (geometry) ---

Geom Title=Existing Conditions

River Reach=UNT 037 in Runni,Reach-1
Reach XY= 30
      2868551.78      7073096.74      2868644.71      7073119.37
      2869375.22      7072698.19      2869415.01      7072552.06
      2869621.42      7072452.63      2869733.05      7072296.26
      2869965.73      7072219.97      2870437.25      7071596.99
      2870440.49      7071498.94      2870580.50      7071460.84
      2870736.55      7071242.94      2870960.69      7071320.63
      2871064.19      7071284.62      2871119.58      7071348.12
      2871472.39      7071183.97      2871521.32      7070908.22
      2871879.33      7070608.67      2872270.32      7070636.62
      2872975.23      7070349.83      2873153.59      7070134.93
      2873250.50      7069818.20      2873535.96      7069641.11
      2873889.74      7069193.26      2874041.42      7068778.41
      2874369.63      7068357.51      2874418.09      7067846.98
      2874844.97      7067716.82      2875022.40      7067763.52
      2875269.25      7067478.16      2876255.59      7067070.71

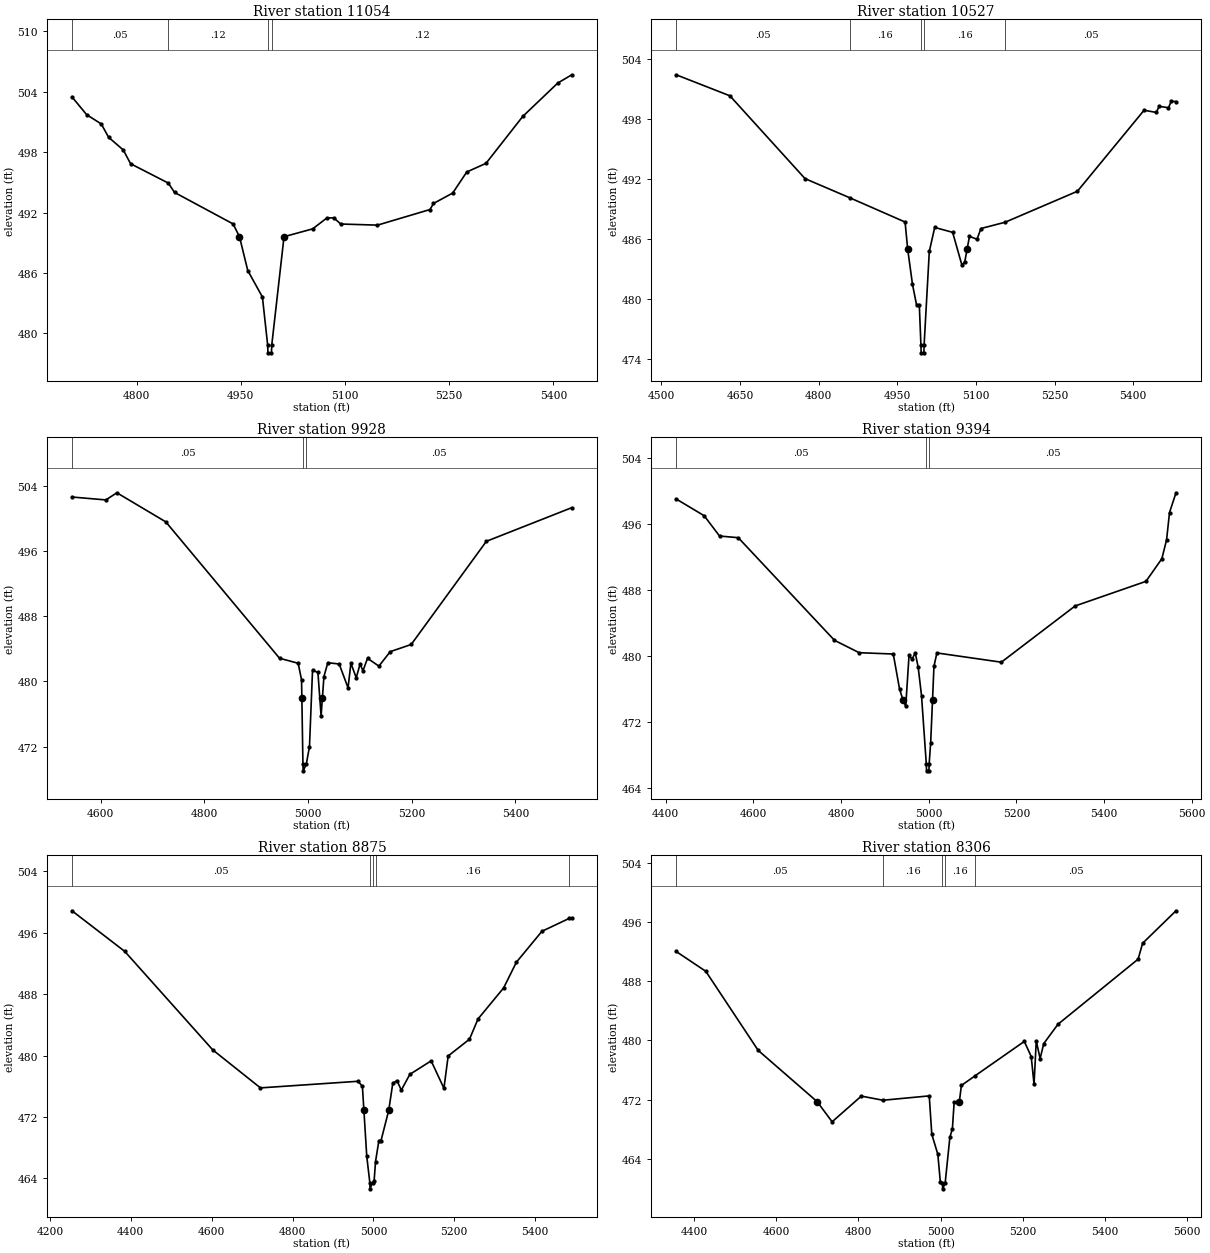
Type RM Length L Ch R = 1,11054,527,527,527
BEGIN DESCRIPTION:
UNT 037 in Running Cr Watershed 20.0
END DESCRIPTION:
XS GIS Cut Line= 3
      2868875.01      7073325.02      2868775.00      7073025.00
      2868374.96      7072975.00
#Sta/Elev= 30
  4707.1  503.49  4728.2  501.73  4749.3  500.80  4759.8  499.48  4780.9  498.22
  4791.5  496.85  4845.7  494.93  4854.7  494.00  4939.0  490.87  4948.2  489.60
  4960.1  486.24  4981.2  483.61  4988.7  478.86  4989.2  478.06  4994.2  478.06
  4994.7  478.86  5012.3  489.60  5053.6  490.38  5073.7  491.45  5083.8  491.48
  5093.9  490.86  5146.8  490.75  5222.4  492.30  5227.4  492.90  5255.1  493.94
  5275.3  496.03  5303.0  496.89  5355.9  501.55  5406.3  504.87  5426.5  505.69
#Mann=4,-1,0
  4707.1    0.05       0  4845.7    0.12       0  4988.7    0.07       0
  4994.7    0.12       0
Bank Sta=4948.2,5012.3
Exp/Cntr=0.3,0.1

Type RM Length L Ch R = 1,10527,599,599,599
BEGIN DESCRIPTION:
UNT 037 in Running Cr Watershed 19.0
END DESCRIPTION:
XS GIS Cut Line= 3
      2869325.01      7073225.05      2869225.00      7072775.00
      2869024.99      7072324.97
#Sta/Elev= 30
  4528.0  502.39  4630.5  500.29  4773.9  492.02  4859.2  490.11  4964.7  487.69
  4969.6  485.00  4978.8  481.47  4986.5  479.43  4991.8  479.43  4994.9  475.43
  4995.4  474.63  5000.5  474.63  5001.0  475.43  5010.9  484.75  5021.2  487.15
  5055.4  486.66  5073.2  483.37  5078.6  483.74  5083.1  485.00  5087.5  486.26
  5101.9  485.97  5109.4  487.04  5155.6  487.67  5293.4  490.76  5420.6  498.85
  5443.9  498.63  5449.3  499.24  5467.1  499.10  5472.6  499.75  5481.5  499.71
#Mann=5,-1,0
  4528.0    0.05       0  4859.2    0.16       0  4994.9    0.07       0
  5001.0    0.16       0  5155.6    0.05       0
Bank Sta=4969.6,5083.1
Exp/Cntr=0.3,0.1

Type RM Length L Ch R = 1,9928,534,534,534
BEGIN DESCRIPTION:
UNT 037 in Running Cr Watershed 18.0
END DESCRIPTION:
XS GIS Cut Line= 3
      2869874.97      7072824.96      2869625.00      7072425.00
      2869174.99      7072225.00
#Sta/Elev= 30
  4544.8  502.69  4610.2  502.33  4631.4  503.21  4725.8  499.63  4945.1  482.86
  4981.1  482.24  4987.6  480.21  4988.2  478.03  4990.3  469.81  4990.8  469.01
  4996.7  469.81  5002.9  471.98  5008.8  481.38  5019.2  481.11  5025.3  475.78
  5027.9  478.03  5030.8  480.61  5038.3  482.31  5060.2  482.15  5077.3  479.22
  5082.8  482.24  5093.1  480.46  5100.6  482.16  5106.0  481.30  5114.9  482.85
  5136.8  481.89  5158.7  483.67  5199.1  484.55  5344.1  497.24  5508.9  501.38
#Mann=3,-1,0
  4544.8    0.05       0  4990.3    0.03       0  4996.7    0.05       0
Bank Sta=4988.2,5027.9
Exp/Cntr=0.3,0.1

Type RM Length L Ch R = 1,9394,519,519,519
BEGIN DESCRIPTION:
UNT 037 in Running Cr Watershed 17.0
END DESCRIPTION:
XS GIS Cut Line= 3
      2870474.96      7072524.97      2870025.00      7072125.00
      2869525.04      7071925.02
#Sta/Elev= 30
  4423.8  499.04  4487.7  497.01  4522.8  494.55  4565.5  494.35  4785.0  481.92
  4841.4  480.42  4919.2  480.26  4933.4  476.05  4941.0  474.74  4947.6  473.93
  4955.2  480.12  4961.9  479.63  4969.4  480.39  4976.1  478.63  4983.6  475.23
  4994.6  466.91  4995.1  466.11  5000.5  466.11  5001.0  466.91  5004.5  469.50
  5008.8  474.75  5012.0  478.76  5018.7  480.39  5165.8  479.27  5334.1  486.08
  5495.7  489.06  5532.0  491.80  5542.8  494.09  5549.5  497.40  5564.3  499.79
#Mann=3,-1,0
  4423.8    0.05       0  4994.6    0.03       0  5001.0    0.05       0
Bank Sta=4941,5008.8
Exp/Cntr=0.3,0.1

Type RM Length L Ch R = 1,8875,569,569,569
BEGIN DESCRIPTION:
UNT 037 in Running Cr Watershed 16.0
END DESCRIPTION:
XS GIS Cut Line= 3
      2870625.00      7072424.99      2870325.00      7071725.00
      2869875.01      7071575.00
#Sta/Elev= 30
  4254.7  498.87  4385.2  493.58  4602.8  480.75  4720.7  475.80  4961.9  476.66
  4972.8  476.01  4976.5  472.89  4983.6  466.88  4991.2  463.45  4991.7  462.65
  4997.8  463.45  5001.8  463.68  5005.3  466.21  5013.6  468.94  5018.9  468.94
  5038.0  472.89  5047.9  476.40  5058.4  476.75  5069.0  475.50  5090.1  477.56
  5142.8  479.32  5174.4  475.75  5184.9  479.96  5237.6  482.14  5258.7  484.78
  5322.0  488.82  5353.6  492.17  5416.8  496.20  5484.7  497.89  5490.6  497.88
#Mann=5,-1,0
  4254.7    0.05       0  4991.2    0.03       0  4997.8    0.05       0
  5005.3    0.16       0  5484.7    0.05       0
Bank Sta=4976.5,5038
Exp/Cntr=0.3,0.1

Type RM Length L Ch R = 1,8306,481,481,481
BEGIN DESCRIPTION:
UNT 037 in Running Cr Watershed 15.0
END DESCRIPTION:
XS GIS Cut Line= 3
      2871024.99      7071874.98      2870625.00      7071325.00
      2870130.11      7071116.17
#Sta/Elev= 30
  4356.2  492.02  4428.4  489.34  4555.9  478.66  4699.5  471.73  4736.0  469.01
  4807.1  472.48  4859.8  471.92  4972.5  472.51  4978.7  467.32  4993.4  464.62
  4999.5  460.88  5004.7  460.75  5005.2  459.95  5011.3  460.75  5022.7  466.90
  5028.9  468.09  5033.2  471.70  5045.8  471.73  5050.8  473.92  5083.8  475.21
  5204.0  479.87  5220.8  477.83  5227.7  474.08  5233.1  479.93  5242.5  477.55
  5251.4  479.58  5286.0  482.19  5481.1  490.98  5492.1  493.13  5573.4  497.52
#Mann=5,-1,0
  4356.2    0.05       0  4859.8    0.16       0  5004.7    0.07       0
  5011.3    0.16       0  5083.8    0.05       0
Bank Sta=4699.5,5045.8
Exp/Cntr=0.3,0.1

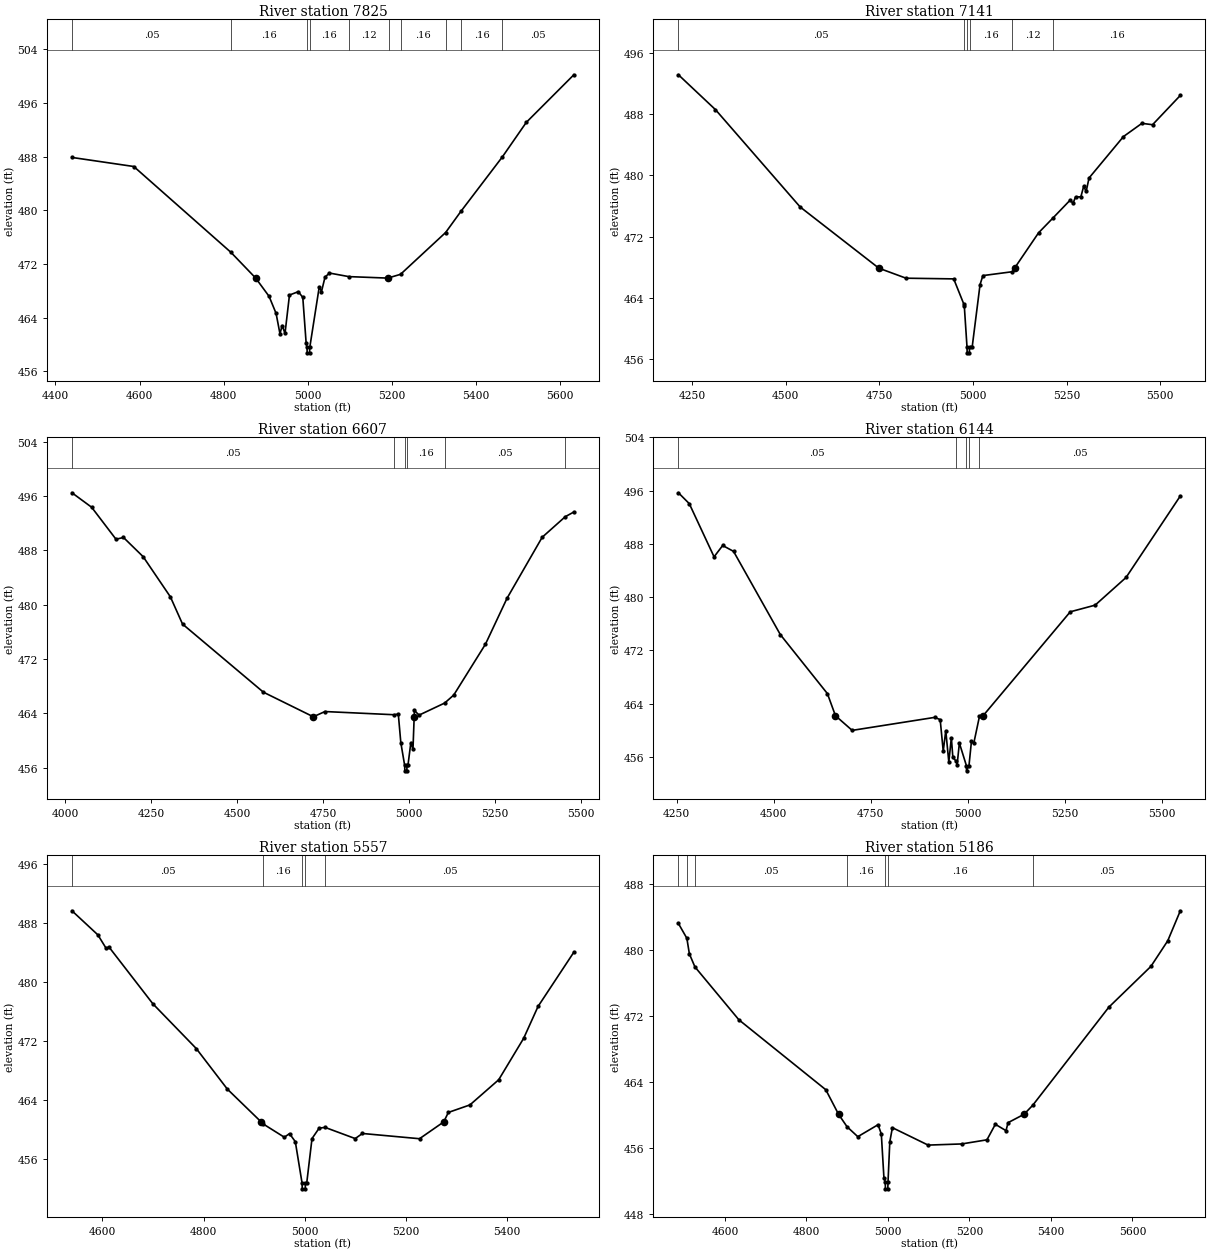
Type RM Length L Ch R = 1,7825,684,684,684
BEGIN DESCRIPTION:
UNT 037 in Running Cr Watershed 14.0
END DESCRIPTION:
XS GIS Cut Line= 3
      2871202.99      7071834.05      2870969.63      7071159.25
      2870625.00      7070825.00
#Sta/Elev= 30
  4439.2  487.89  4586.3  486.54  4817.4  473.75  4876.2  469.92  4908.2  467.19
  4924.9  464.64  4934.1  461.61  4939.3  462.84  4946.1  461.67  4956.7  467.38
  4977.8  467.89  4988.4  467.03  4996.4  460.20  4998.4  459.57  4998.9  458.77
  5004.5  458.77  5005.0  459.57  5027.6  468.62  5032.9  467.90  5041.3  470.06
  5051.9  470.66  5097.9  470.13  5190.2  469.91  5193.3  469.96  5220.9  470.47
  5328.2  476.70  5364.9  479.88  5463.2  487.97  5520.2  493.12  5633.3  500.21
#Mann=10,-1,0
  4439.2    0.05       0  4817.4    0.16       0  4998.4    0.07       0
  5005.0    0.16       0  5097.9    0.12       0  5193.3    0.05       0
  5220.9    0.16       0  5328.2    0.05       0  5364.9    0.16       0
  5463.2    0.05       0
Bank Sta=4876.2,5190.2
Exp/Cntr=0.3,0.1

Type RM Length L Ch R = 1,7141,534,534,534
BEGIN DESCRIPTION:
UNT 037 in Running Cr Watershed 13.0
END DESCRIPTION:
XS GIS Cut Line= 3
      2872075.00      7071625.00      2871525.00      7071075.00
      2871104.01      7070701.21
#Sta/Elev= 30
  4213.2  493.15  4312.2  488.59  4538.5  475.86  4748.7  467.86  4821.3  466.55
  4948.6  466.46  4975.0  463.24  4976.9  462.94  4984.1  457.59  4984.6  456.79
  4990.4  456.79  4990.9  457.59  4998.1  457.60  5019.0  465.72  5026.6  466.89
  5105.6  467.40  5111.1  467.86  5175.4  472.49  5214.3  474.45  5259.9  476.77
  5267.4  476.34  5274.1  477.18  5288.3  477.19  5295.8  478.56  5302.5  477.90
  5310.1  479.65  5402.1  485.07  5451.4  486.80  5479.8  486.62  5554.0  490.45
#Mann=6,-1,0
  4213.2    0.05       0  4975.0    0.16       0  4984.1    0.07       0
  4990.9    0.16       0  5105.6    0.12       0  5214.3    0.16       0
Bank Sta=4748.7,5111.1
Exp/Cntr=0.3,0.1

Type RM Length L Ch R = 1,6607,463,463,463
BEGIN DESCRIPTION:
UNT 037 in Running Cr Watershed 12.0
END DESCRIPTION:
XS GIS Cut Line= 3
      2872375.02      7071475.03      2871775.00      7070675.00
      2871325.02      7070575.00
#Sta/Elev= 30
  4019.0  496.47  4076.3  494.34  4147.2  489.63  4169.0  489.89  4226.3  487.06
  4305.5  481.15  4340.9  477.14  4576.3  467.11  4721.6  463.49  4755.5  464.26
  4956.9  463.79  4969.0  463.88  4976.3  459.69  4987.5  456.33  4988.0  455.53
  4993.8  455.53  4994.3  456.33  4997.2  456.39  5005.5  459.68  5011.7  458.71
  5015.2  463.49  5015.9  464.43  5029.3  463.73  5103.9  465.51  5130.4  466.69
  5222.6  474.17  5285.4  480.93  5387.8  489.92  5455.0  492.95  5480.0  493.64
#Mann=6,-1,0
  4019.0    0.05       0  4956.9    0.16       0  4987.5    0.07       0
  4994.3    0.16       0  5103.9    0.05       0  5455.0    0.16       0
Bank Sta=4721.6,5015.2
Exp/Cntr=0.3,0.1

Type RM Length L Ch R = 1,6144,587,587,587
BEGIN DESCRIPTION:
UNT 037 in Running Cr Watershed 11.0
END DESCRIPTION:
XS GIS Cut Line= 3
      2872675.00      7071175.00      2872225.00      7070625.00
      2871925.02      7070125.03
#Sta/Elev= 30
  4254.5  495.66  4282.5  494.03  4346.4  486.05  4368.6  487.75  4396.6  486.87
  4517.2  474.38  4638.5  465.53  4659.3  462.21  4702.4  460.01  4914.9  461.96
  4929.2  461.63  4937.1  456.89  4943.6  459.97  4951.5  455.26  4958.0  458.92
  4961.9  455.95  4970.6  455.38  4972.9  454.86  4978.7  458.11  4996.7  454.74
  4997.2  453.94  5003.5  454.74  5009.8  458.37  5015.7  458.05  5030.5  462.12
  5039.9  462.21  5264.5  477.80  5328.6  478.80  5408.3  482.95  5548.2  495.18
#Mann=5,-1,0
  4254.5    0.05       0  4970.6    0.16       0  4996.7    0.07       0
  5003.5    0.16       0  5030.5    0.05       0
Bank Sta=4659.3,5039.9
Exp/Cntr=0.3,0.1

Type RM Length L Ch R = 1,5557,371,371,371
BEGIN DESCRIPTION:
UNT 037 in Running Cr Watershed 10.0
END DESCRIPTION:
XS GIS Cut Line= 3
      2872824.99      7070924.97      2872725.00      7070475.00
      2872324.96      7070124.97
#Sta/Elev= 30
  4539.7  489.61  4590.9  486.35  4607.5  484.50  4612.7  484.72  4699.7  477.01
  4785.5  470.95  4847.0  465.45  4913.8  461.01  4918.3  460.71  4959.7  458.93
  4969.9  459.42  4981.4  458.33  4994.7  452.74  4995.2  451.94  5001.0  451.94
  5001.5  452.74  5004.0  452.74  5014.4  458.75  5028.6  460.17  5040.4  460.26
  5099.8  458.75  5114.1  459.44  5227.0  458.73  5274.9  461.01  5284.0  462.29
  5326.7  463.31  5383.6  466.72  5433.0  472.34  5461.4  476.65  5532.2  484.00
#Mann=5,-1,0
  4539.7    0.05       0  4918.3    0.16       0  4994.7    0.07       0
  5001.5    0.16       0  5040.4    0.05       0
Bank Sta=4913.8,5274.9
Exp/Cntr=0.3,0.1

Type RM Length L Ch R = 1,5186,728,728,728
BEGIN DESCRIPTION:
UNT 037 in Running Cr Watershed 9.0
END DESCRIPTION:
XS GIS Cut Line= 3
      2873362.20      7070696.13      2872996.39      7070232.47
      2872375.02      7070075.01
#Sta/Elev= 30
  4485.9  483.24  4506.6  481.45  4512.8  479.56  4526.4  477.98  4634.3  471.57
  4847.5  463.10  4878.9  460.12  4899.6  458.62  4926.1  457.41  4975.8  458.86
  4983.8  457.73  4990.2  452.43  4993.4  451.89  4993.9  451.09  4999.7  451.09
  5000.2  451.89  5004.6  456.79  5011.0  458.50  5098.6  456.39  5181.1  456.53
  5243.0  457.03  5263.6  458.91  5289.7  458.14  5294.9  459.11  5333.9  460.12
  5355.1  461.20  5542.1  473.10  5645.3  478.04  5686.6  481.14  5717.5  484.78
#Mann=7,-1,0
  4485.9    0.05       0  4506.6    0.08       0  4526.4    0.05       0
  4899.6    0.16       0  4993.4    0.07       0  5000.2    0.16       0
  5355.1    0.05       0
Bank Sta=4878.9,5333.9
Exp/Cntr=0.3,0.1

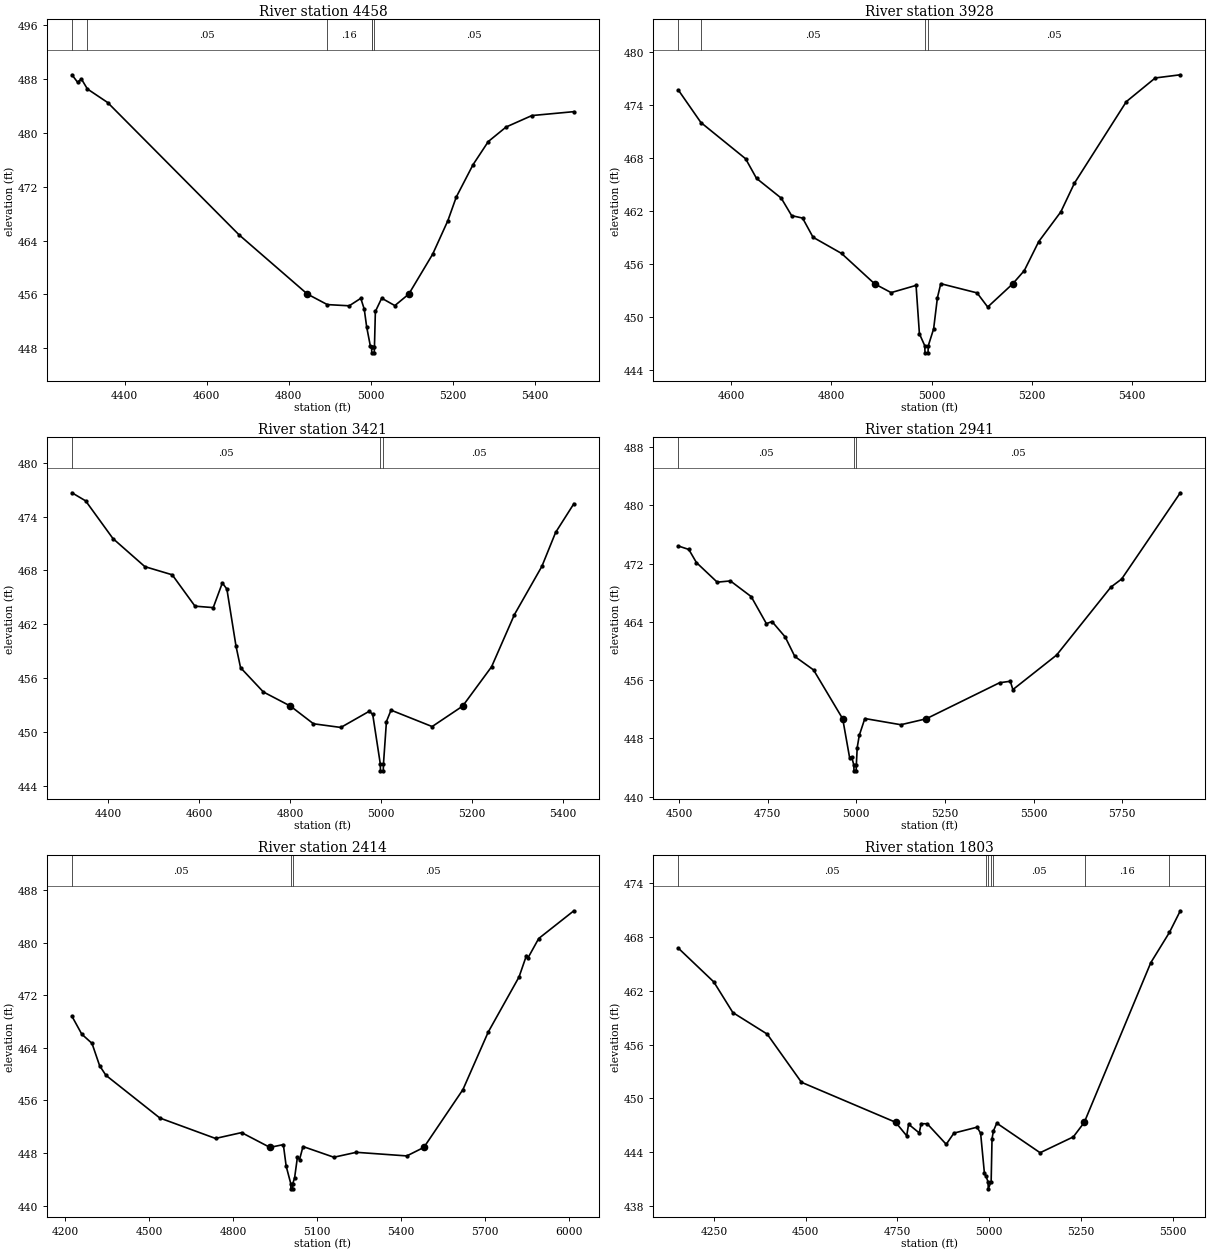
Type RM Length L Ch R = 1,4458,530,530,530
BEGIN DESCRIPTION:
UNT 037 in Running Cr Watershed 8.0
END DESCRIPTION:
XS GIS Cut Line= 3
      2873775.01      7070325.02      2873375.00      7069675.00
      2872925.02      7069575.00
#Sta/Elev= 30
  4271.4  488.63  4285.0  487.53  4294.5  488.00  4309.1  486.52  4358.4  484.51
  4679.1  464.84  4845.5  456.05  4894.2  454.48  4947.7  454.30  4975.9  455.41
  4984.4  453.79  4990.2  451.18  4999.4  448.27  5002.1  448.12  5002.2  448.11
  5002.7  447.31  5008.7  447.31  5009.2  448.11  5011.5  453.46  5026.9  455.43
  5059.0  454.33  5093.1  456.05  5151.2  461.97  5188.3  466.95  5208.8  470.46
  5249.8  475.28  5286.9  478.71  5330.4  480.87  5393.2  482.57  5495.6  483.15
#Mann=6,-1,0
  4271.4    0.08       0  4309.1    0.05       0  4894.2    0.16       0
  5002.1    0.05       0  5002.2    0.07       0  5009.2    0.05       0
Bank Sta=4845.5,5093.1
Exp/Cntr=0.3,0.1

Type RM Length L Ch R = 1,3928,507,507,507
BEGIN DESCRIPTION:
UNT 037 in Running Cr Watershed 7.0
END DESCRIPTION:
XS GIS Cut Line= 3
      2874074.98      7069724.98      2873725.00      7069325.00
      2873474.99      7068924.99
#Sta/Elev= 30
  4494.1  475.70  4539.1  472.03  4628.4  467.93  4650.2  465.71  4699.6  463.47
  4720.4  461.49  4742.3  461.21  4763.2  459.04  4820.1  457.21  4886.4  453.76
  4919.3  452.77  4969.1  453.59  4975.8  448.11  4986.5  446.75  4987.0  445.95
  4993.0  445.95  4993.5  446.75  5004.2  448.66  5011.8  452.20  5018.5  453.78
  5091.0  452.74  5112.3  451.14  5162.2  453.76  5185.4  455.26  5214.3  458.55
  5258.5  461.92  5285.6  465.16  5389.4  474.40  5447.2  477.08  5497.3  477.44
#Mann=4,-1,0
  4494.1    0.08       0  4539.1    0.05       0  4986.5    0.03       0
  4993.5    0.05       0
Bank Sta=4886.4,5162.2
Exp/Cntr=0.3,0.1

Type RM Length L Ch R = 1,3421,480,480,480
BEGIN DESCRIPTION:
UNT 037 in Running Cr Watershed 6.0
END DESCRIPTION:
XS GIS Cut Line= 3
      2874675.04      7068975.00      2874025.00      7068925.00
      2873575.03      7068875.00
#Sta/Elev= 30
  4319.6  476.66  4349.7  475.76  4409.9  471.55  4480.1  468.42  4540.3  467.51
  4590.4  464.01  4630.6  463.85  4650.6  466.60  4660.6  465.92  4680.7  459.55
  4690.7  457.15  4740.9  454.44  4800.6  452.86  4851.2  450.89  4911.4  450.48
  4974.1  452.29  4981.6  451.93  4998.2  446.44  4998.7  445.64  5004.8  445.64
  5005.3  446.44  5011.8  451.14  5021.9  452.41  5112.4  450.58  5179.5  452.86
  5243.2  457.25  5293.5  463.07  5353.9  468.45  5384.1  472.23  5424.3  475.44
#Mann=3,-1,0
  4319.6    0.05       0  4998.2    0.03       0  5005.3    0.05       0
Bank Sta=4800.6,5179.5
Exp/Cntr=0.3,0.1

Type RM Length L Ch R = 1,2941,527,527,527
BEGIN DESCRIPTION:
UNT 037 in Running Cr Watershed 5.0
END DESCRIPTION:
XS GIS Cut Line= 3
      2874674.96      7068774.98      2874090.82      7068432.91
      2873361.64      7068314.84
#Sta/Elev= 30
  4498.5  474.42  4527.8  473.95  4549.3  472.15  4607.9  469.46  4645.1  469.63
  4703.7  467.48  4746.7  463.76  4762.4  464.06  4799.6  461.94  4826.8  459.26
  4879.7  457.41  4961.9  450.70  4981.3  445.38  4987.1  445.49  4993.2  444.36
  4993.7  443.56  4999.8  443.56  5000.3  444.36  5002.8  446.76  5008.6  448.43
  5024.3  450.74  5125.9  449.89  5197.2  450.70  5404.2  455.65  5434.6  455.86
  5441.8  454.71  5565.1  459.45  5718.2  468.78  5748.6  469.89  5914.1  481.73
#Mann=3,-1,0
  4498.5    0.05       0  4993.2    0.03       0  5000.3    0.05       0
Bank Sta=4961.9,5197.2
Exp/Cntr=0.3,0.1

Type RM Length L Ch R = 1,2414,611,611,611
BEGIN DESCRIPTION:
UNT 037 in Running Cr Watershed 4.0
END DESCRIPTION:
XS GIS Cut Line= 3
      2874917.18      7068592.59      2874492.04      7068052.09
      2873389.72      7068120.38
#Sta/Elev= 30
  4225.1  468.81  4260.2  466.08  4296.7  464.68  4323.9  461.28  4346.4  459.82
  4538.9  453.32  4737.7  450.21  4830.8  451.10  4931.9  448.85  4979.9  449.27
  4990.0  445.99  5006.4  443.34  5006.9  442.54  5013.0  442.54  5013.5  443.34
  5020.0  444.18  5030.0  447.31  5037.8  447.00  5050.1  448.98  5160.3  447.35
  5240.4  448.10  5420.8  447.55  5481.7  448.85  5621.2  457.65  5711.3  466.39
  5821.5  474.79  5847.9  478.05  5853.0  477.66  5891.7  480.64  6017.2  484.86
#Mann=3,-1,0
  4225.1    0.05       0  5006.4    0.03       0  5013.5    0.05       0
Bank Sta=4931.9,5481.7
Exp/Cntr=0.3,0.1

Type RM Length L Ch R = 1,1803,504,504,504
BEGIN DESCRIPTION:
UNT 037 in Running Cr Watershed 3.0
END DESCRIPTION:
XS GIS Cut Line= 3
      2875007.48      7068557.87      2874775.00      7067725.00
      2874725.00      7067225.01
#Sta/Elev= 30
  4153.3  466.76  4249.7  463.00  4301.6  459.58  4395.1  457.18  4488.5  451.80
  4744.9  447.34  4775.1  445.83  4780.3  447.12  4809.3  446.15  4814.5  447.18
  4831.1  447.17  4882.8  444.88  4903.8  446.13  4966.8  446.79  4976.5  446.12
  4986.9  441.63  4991.2  441.30  4996.6  440.71  4997.4  439.91  5005.2  440.71
  5007.6  445.52  5011.5  446.38  5020.5  447.24  5138.6  443.94  5229.1  445.71
  5259.3  447.35  5259.6  447.40  5440.1  465.15  5490.9  468.53  5520.5  470.94
#Mann=7,-1,0
  4153.3    0.05       0  4991.2    0.07       0  4996.6    0.07       0
  5005.2    0.07       0  5011.5    0.05       0  5259.6    0.16       0
  5490.9    0.05       0
Bank Sta=4744.9,5259.3
Exp/Cntr=0.3,0.1

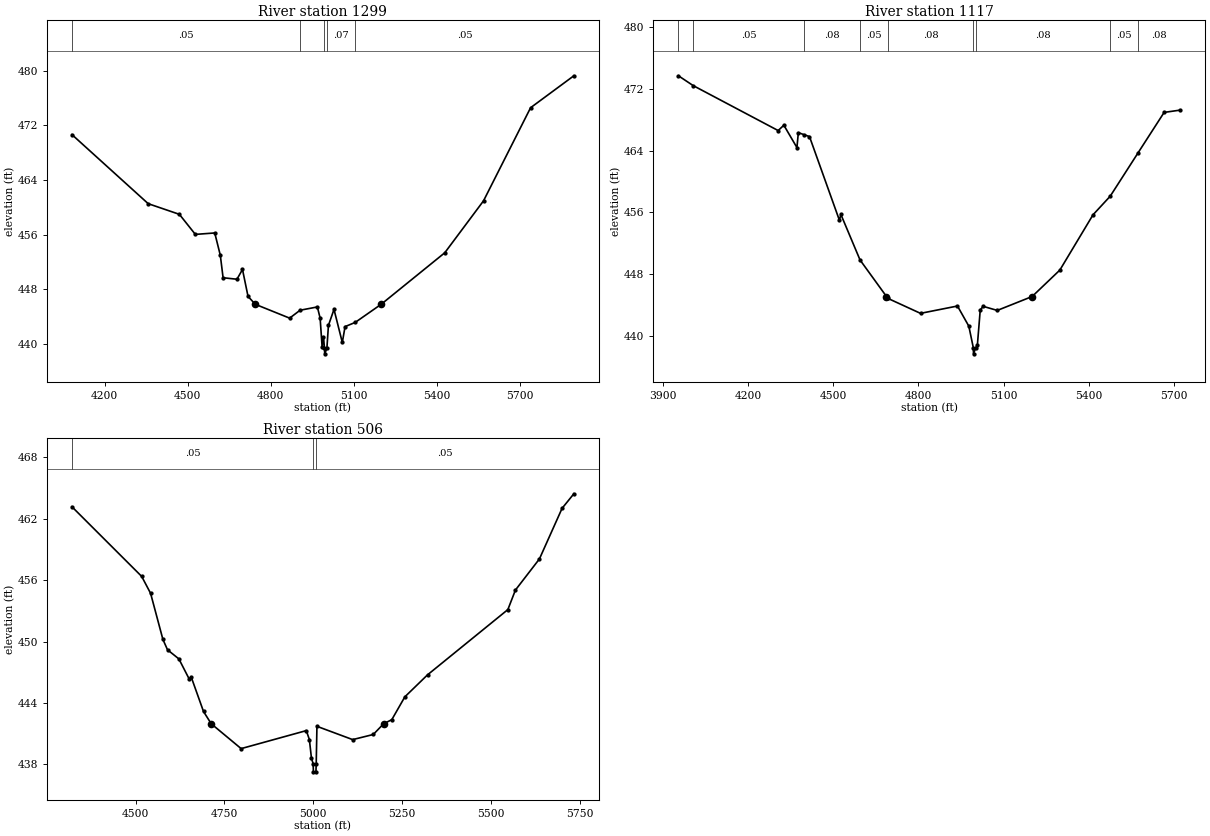
Type RM Length L Ch R = 1,1299,182,182,182
BEGIN DESCRIPTION:
UNT 037 in Running Cr Watershed 2.0
END DESCRIPTION:
XS GIS Cut Line= 3
      2875097.77      7068530.08      2875156.75      7067509.03
      2875174.13      7066718.77
#Sta/Elev= 30
  4082.1  470.66  4357.6  460.54  4470.2  458.98  4527.9  456.04  4598.0  456.25
  4618.1  452.98  4628.1  449.69  4678.2  449.47  4698.2  450.90  4718.2  446.96
  4744.4  445.80  4868.5  443.77  4906.3  444.93  4968.7  445.41  4978.7  443.77
  4985.8  439.59  4990.8  441.05  4994.4  439.34  4995.2  438.54  5003.1  439.34
  5008.7  442.71  5028.8  445.05  5058.8  440.21  5068.8  442.53  5105.2  443.14
  5199.2  445.80  5429.0  453.35  5569.0  460.96  5739.0  474.60  5895.3  479.28
#Mann=5,-1,0
  4082.1    0.05       0  4906.3    0.07       0  4994.4    0.07       0
  5003.1    0.07       0  5105.2    0.05       0
Bank Sta=4744.4,5199.2
Exp/Cntr=0.3,0.1

Type RM Length L Ch R = 1,1117,611,611,611
BEGIN DESCRIPTION:
Mapping XS 9900b895
END DESCRIPTION:
XS GIS Cut Line= 3
      2875201.93      7068525.25      2875250.54      7067802.98
      2875292.21      7066761.32
#Sta/Elev= 30
  3955.5  473.68  4007.4  472.41  4306.5  466.59  4326.6  467.28  4372.6  464.39
  4377.6  466.32  4399.0  466.04  4416.8  465.81  4522.2  454.97  4527.2  455.74
  4594.7  449.84  4687.8  445.11  4692.6  444.87  4807.5  442.93  4937.6  443.88
  4977.6  441.27  4993.3  438.49  4994.1  437.69  5002.0  438.49  5007.6  438.79
  5017.7  443.35  5027.7  443.84  5077.7  443.31  5200.4  445.11  5297.9  448.53
  5414.7  455.69  5475.1  458.09  5572.9  463.69  5664.9  468.94  5721.9  469.24
#Mann=9,-1,0
  3955.5    0.08       0  4007.4    0.05       0  4399.0    0.08       0
  4594.7    0.05       0  4692.6    0.08       0  4993.3    0.07       0
  5002.0    0.08       0  5475.1    0.05       0  5572.9    0.08       0
Bank Sta=4687.8,5200.4
Exp/Cntr=0.3,0.1

Type RM Length L Ch R = 1,506,0,0,0
BEGIN DESCRIPTION:
UNT 037 in Running Cr Watershed 1.0
END DESCRIPTION:
XS GIS Cut Line= 3
      2875712.35      7067924.49      2875868.60      7067348.12
      2875441.53      7066653.71
#Sta/Elev= 30
  4320.8  463.17  4517.1  456.36  4542.1  454.71  4576.7  450.21  4589.7  449.19
  4621.7  448.30  4651.2  446.30  4656.4  446.53  4691.0  443.16  4712.7  441.96
  4796.9  439.53  4980.3  441.29  4988.9  440.42  4994.8  438.59  4999.5  438.06
  5000.3  437.26  5007.4  437.26  5008.2  438.06  5010.2  441.71  5110.8  440.41
  5168.7  440.91  5197.9  441.96  5220.9  442.36  5257.6  444.59  5321.4  446.74
  5547.5  453.12  5568.8  455.03  5636.3  458.07  5700.1  463.02  5733.2  464.44
#Mann=3,-1,0
  4320.8    0.05       0  4999.5    0.03       0  5008.2    0.05       0
Bank Sta=4712.7,5197.9
Exp/Cntr=0.3,0.1

Chan Stop Cuts=-1