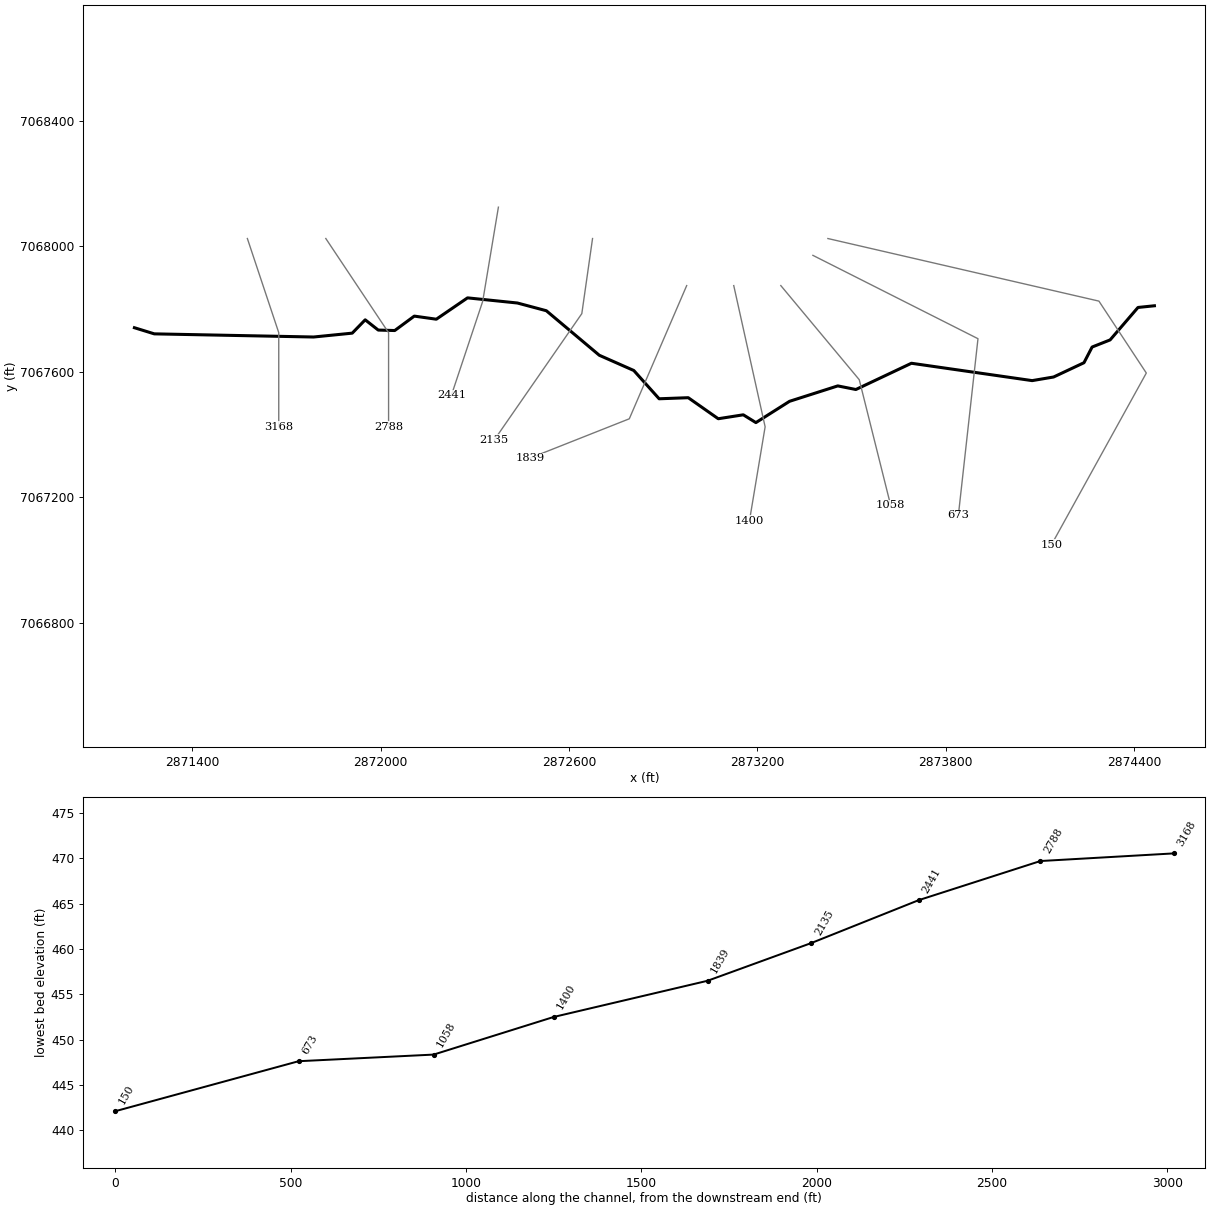
--- UNT 038 in Running Cr Watershed.prj (project) ---

Proj Title=UNT 038 in Running Cr Watershed Base Level Engineering
Current Plan=p01
Default Exp/Contr=0.3,0.1
English Units
Geom File=g01
Flow File=f01
Plan File=p01
BEGIN DESCRIPTION:
UNT 038 in Running Cr Watershed
END DESCRIPTION:

--- UNT 038 in Running Cr Watershed.p01 (plan) ---

Plan Title=Multiple Run
Short Identifier=Multiple
Geom File=g01
Flow File=f01
Subcritical Flow
K Sum by GR= 0
Std Step Tol= 0.01
Critical Tol= 0.01
Num of Std Step Trials= 20
Max Error Tol= 0.3
Flow Tol Ratio= 0.001
Split Flow NTrial= 30
Split Flow Tol= 0.02
Split Flow Ratio= 0.02
Log Output Level= 0
Friction Slope Method= 1
Unsteady Friction Slope Method= 2
Unsteady Bridges Friction Slope Method= 1
Parabolic Critical Depth
Global Vel Dist=  1 , 1 , 1
Global Log Level= 0
CheckData=True
Encroach Param= -1, 0, 0, 0
BEGIN DESCRIPTION:
Multiple Run
END DESCRIPTION:

--- UNT 038 in Running Cr Watershed.f01 (steady flow) ---

Flow Title=Multiple
Number of Profiles=7
Profile Names=10-year,25-year,50-year,1pct_min,100-year,1pct_plu,500-year
River Rch & RM= UNT 038 in Runni,Reach-1,3168
     766    1032    1249     750    1496    2985    2140
Boundary for River Rch & Prof#=UNT 038 in Runni,Reach-1,1
Up Type=0
Dn Type=3
Dn Slope=0.005
Boundary for River Rch & Prof#=UNT 038 in Runni,Reach-1,2
Up Type=0
Dn Type=3
Dn Slope=0.005
Boundary for River Rch & Prof#=UNT 038 in Runni,Reach-1,3
Up Type=0
Dn Type=3
Dn Slope=0.005
Boundary for River Rch & Prof#=UNT 038 in Runni,Reach-1,4
Up Type=0
Dn Type=3
Dn Slope=0.005
Boundary for River Rch & Prof#=UNT 038 in Runni,Reach-1,5
Up Type=0
Dn Type=3
Dn Slope=0.005
Boundary for River Rch & Prof#=UNT 038 in Runni,Reach-1,6
Up Type=0
Dn Type=3
Dn Slope=0.005
Boundary for River Rch & Prof#=UNT 038 in Runni,Reach-1,7
Up Type=0
Dn Type=3
Dn Slope=0.005

--- UNT 038 in Running Cr Watershed.g01 (geometry) ---

Geom Title=Existing Conditions

River Reach=UNT 038 in Runni,Reach-1
Reach XY= 30
      2871215.03      7067740.77      2871278.38      7067721.21
      2871786.01      7067711.16      2871909.18      7067723.48
      2871950.48      7067765.95      2871992.04      7067733.29
      2872044.64      7067731.79      2872106.94      7067777.78
      2872177.13      7067767.89      2872276.59      7067835.91
      2872435.54      7067819.53      2872527.70      7067794.92
      2872696.54      7067652.99      2872806.47      7067604.45
      2872887.20      7067514.33      2872980.00      7067517.76
      2873075.59      7067450.71      2873155.40      7067463.24
      2873195.58      7067438.38      2873302.82      7067506.26
      2873456.50      7067555.36      2873514.22      7067543.87
      2873691.20      7067627.51      2874075.96      7067572.19
      2874144.29      7067583.72      2874241.09      7067629.22
      2874267.04      7067679.24      2874324.40      7067701.92
      2874413.24      7067805.33      2874465.59      7067810.71

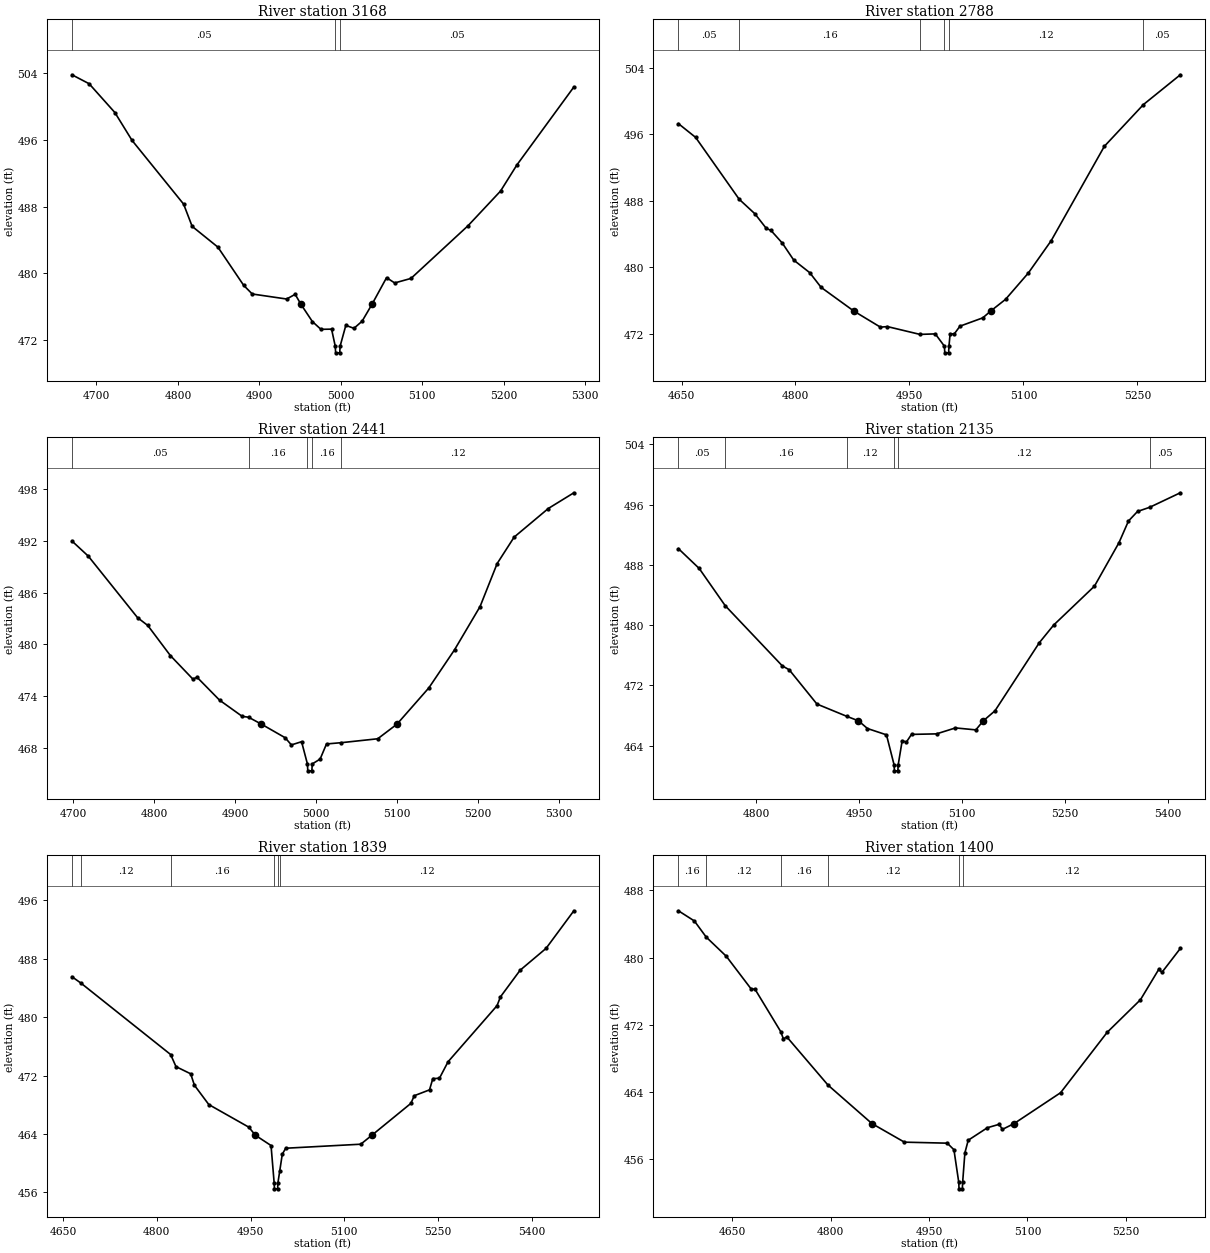
Type RM Length L Ch R = 1,3168,380,380,380
BEGIN DESCRIPTION:
UNT 038 in Running Cr Watershed 8.0
END DESCRIPTION:
XS GIS Cut Line= 3
      2871574.99      7068025.04      2871675.00      7067725.00
      2871675.00      7067424.97
#Sta/Elev= 30
  4669.9  503.74  4691.0  502.67  4722.6  499.23  4743.7  495.90  4807.0  488.29
  4817.5  485.63  4849.1  483.15  4880.8  478.58  4891.3  477.55  4933.5  476.95
  4944.0  477.51  4951.0  476.33  4965.1  474.26  4975.6  473.33  4988.7  473.35
  4993.2  471.32  4993.7  470.52  4998.7  470.52  4999.2  471.32  5006.2  473.80
  5016.2  473.45  5026.2  474.30  5038.4  476.33  5056.2  479.50  5066.2  478.87
  5086.2  479.41  5156.2  485.70  5196.2  489.85  5216.2  492.96  5286.2  502.28
#Mann=3,-1,0
  4669.9    0.05       0  4993.2    0.03       0  4999.2    0.05       0
Bank Sta=4951,5038.4
Exp/Cntr=0.3,0.1

Type RM Length L Ch R = 1,2788,347,347,347
BEGIN DESCRIPTION:
UNT 038 in Running Cr Watershed 7.0
END DESCRIPTION:
XS GIS Cut Line= 3
      2871824.98      7068025.03      2872025.00      7067725.00
      2872025.00      7067424.99
#Sta/Elev= 30
  4645.9  497.26  4668.5  495.61  4725.9  488.16  4746.6  486.41  4761.6  484.65
  4767.6  484.42  4782.6  482.89  4797.7  480.84  4818.7  479.33  4833.7  477.56
  4876.9  474.70  4911.8  472.77  4920.9  472.84  4963.8  471.90  4984.0  471.96
  4996.0  470.48  4996.5  469.68  5001.5  469.68  5002.0  470.48  5003.5  471.96
  5009.0  471.96  5016.5  472.89  5046.5  473.89  5056.8  474.70  5076.5  476.12
  5106.5  479.29  5136.5  483.17  5206.5  494.53  5258.0  499.56  5306.5  503.14
#Mann=6,-1,0
  4645.9    0.05       0  4725.9    0.16       0  4963.8    0.12       0
  4996.0    0.07       0  5002.0    0.12       0  5258.0    0.05       0
Bank Sta=4876.9,5056.8
Exp/Cntr=0.3,0.1

Type RM Length L Ch R = 1,2441,306,306,306
BEGIN DESCRIPTION:
UNT 038 in Running Cr Watershed 6.0
END DESCRIPTION:
XS GIS Cut Line= 3
      2872374.99      7068124.96      2872325.00      7067825.00
      2872225.01      7067525.03
#Sta/Elev= 30
  4698.3  491.96  4718.5  490.21  4779.4  483.09  4792.0  482.19  4819.9  478.71
  4847.8  475.98  4852.9  476.20  4880.7  473.55  4908.6  471.68  4916.6  471.57
  4932.5  470.77  4961.8  469.20  4969.5  468.37  4982.1  468.74  4989.3  466.17
  4989.8  465.37  4994.8  465.37  4995.3  466.17  5005.0  466.73  5012.9  468.48
  5031.4  468.63  5076.2  469.08  5100.0  470.77  5139.4  474.97  5171.1  479.37
  5202.7  484.38  5223.8  489.35  5244.8  492.41  5287.0  495.72  5318.6  497.54
#Mann=5,-1,0
  4698.3    0.05       0  4916.6    0.16       0  4989.3    0.07       0
  4995.3    0.16       0  5031.4    0.12       0
Bank Sta=4932.5,5100
Exp/Cntr=0.3,0.1

Type RM Length L Ch R = 1,2135,296,296,296
BEGIN DESCRIPTION:
UNT 038 in Running Cr Watershed 5.0
END DESCRIPTION:
XS GIS Cut Line= 3
      2872675.00      7068025.02      2872640.81      7067785.67
      2872361.64      7067382.82
#Sta/Elev= 30
  4686.6  490.16  4716.9  487.53  4754.8  482.59  4838.1  474.59  4848.2  474.07
  4888.6  469.52  4932.1  467.89  4949.2  467.29  4962.3  466.27  4990.0  465.43
  5001.1  461.45  5001.6  460.65  5006.6  460.65  5007.1  461.45  5012.9  464.65
  5019.0  464.47  5026.5  465.49  5063.0  465.56  5090.6  466.35  5120.3  466.09
  5131.2  467.29  5148.2  468.62  5212.9  477.67  5233.8  480.01  5293.3  485.18
  5329.1  490.96  5342.9  493.83  5356.1  495.10  5373.8  495.65  5418.5  497.58
#Mann=6,-1,0
  4686.6    0.05       0  4754.8    0.16       0  4932.1    0.12       0
  5001.1    0.07       0  5007.1    0.12       0  5373.8    0.05       0
Bank Sta=4949.2,5131.2
Exp/Cntr=0.3,0.1

Type RM Length L Ch R = 1,1839,439,439,439
BEGIN DESCRIPTION:
UNT 038 in Running Cr Watershed 4.0
END DESCRIPTION:
XS GIS Cut Line= 3
      2872975.00      7067874.99      2872792.13      7067450.53
      2872475.04      7067325.02
#Sta/Elev= 30
  4664.2  485.53  4678.4  484.67  4822.1  474.88  4830.7  473.22  4854.2  472.24
  4860.2  470.67  4883.2  468.03  4947.3  464.93  4957.7  463.83  4982.8  462.42
  4987.8  457.29  4988.3  456.49  4993.3  456.49  4993.8  457.29  4996.8  458.98
  5000.8  461.23  5006.3  462.05  5126.4  462.60  5144.2  463.83  5206.6  468.19
  5212.0  469.24  5236.4  470.04  5241.7  471.58  5252.3  471.63  5266.1  473.89
  5344.5  481.57  5349.9  482.77  5381.4  486.42  5422.9  489.41  5467.4  494.56
#Mann=6,-1,0
  4664.2    0.16       0  4678.4    0.12       0  4822.1    0.16       0
  4987.8    0.07       0  4993.8    0.16       0  4996.8    0.12       0
Bank Sta=4957.7,5144.2
Exp/Cntr=0.3,0.1

Type RM Length L Ch R = 1,1400,342,342,342
BEGIN DESCRIPTION:
UNT 038 in Running Cr Watershed 3.0
END DESCRIPTION:
XS GIS Cut Line= 3
      2873125.00      7067875.01      2873225.00      7067425.00
      2873175.00      7067125.03
#Sta/Elev= 30
  4568.0  485.56  4592.3  484.35  4610.4  482.43  4641.0  480.15  4679.4  476.21
  4684.5  476.27  4723.9  471.20  4728.1  470.32  4733.2  470.57  4796.1  464.83
  4863.0  460.26  4912.5  458.05  4977.8  457.93  4988.0  457.15  4995.3  453.30
  4995.8  452.50  5000.8  452.50  5001.3  453.30  5004.7  456.78  5009.8  458.28
  5039.1  459.77  5056.9  460.17  5061.9  459.57  5079.7  460.26  5150.6  463.93
  5221.6  471.11  5272.3  474.98  5300.2  478.59  5305.2  478.25  5333.1  481.08
#Mann=6,-1,0
  4568.0    0.16       0  4610.4    0.12       0  4723.9    0.16       0
  4796.1    0.12       0  4995.3    0.07       0  5001.3    0.12       0
Bank Sta=4863,5079.7
Exp/Cntr=0.3,0.1

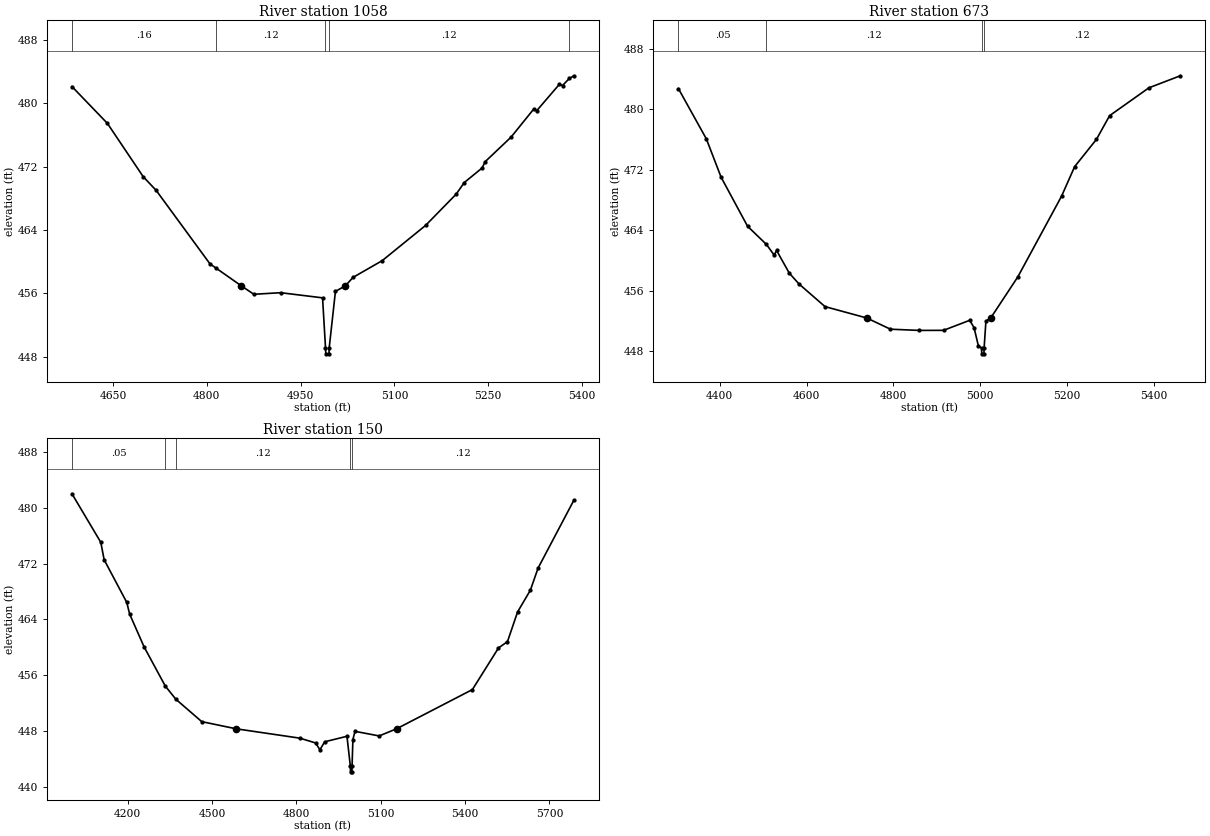
Type RM Length L Ch R = 1,1058,385,385,385
BEGIN DESCRIPTION:
UNT 038 in Running Cr Watershed 2.0
END DESCRIPTION:
XS GIS Cut Line= 3
      2873274.98      7067875.03      2873525.00      7067575.00
      2873625.01      7067174.96
#Sta/Elev= 30
  4584.2  482.11  4640.9  477.46  4698.1  470.74  4719.0  468.99  4804.9  459.73
  4814.4  459.20  4855.4  456.93  4875.2  455.88  4918.1  456.08  4985.1  455.43
  4989.8  449.16  4990.3  448.36  4995.3  448.36  4995.8  449.16  5005.7  456.25
  5021.3  456.93  5034.0  458.02  5080.4  460.12  5150.0  464.58  5198.9  468.53
  5211.8  469.99  5240.2  471.82  5245.3  472.63  5286.6  475.72  5322.6  479.24
  5327.8  479.07  5363.9  482.39  5369.0  482.24  5379.8  483.13  5387.1  483.47
#Mann=5,-1,0
  4584.2    0.16       0  4814.4    0.12       0  4989.8    0.07       0
  4995.8    0.12       0  5379.8    0.16       0
Bank Sta=4855.4,5021.3
Exp/Cntr=0.3,0.1

Type RM Length L Ch R = 1,673,523,523,523
BEGIN DESCRIPTION:
Mapping XS de483547
END DESCRIPTION:
XS GIS Cut Line= 3
      2873377.28      7067971.38      2873903.32      7067705.76
      2873840.82      7067143.22
#Sta/Elev= 30
  4305.0  482.73  4369.3  476.08  4403.3  471.00  4464.1  464.52  4507.6  462.11
  4525.4  460.70  4531.0  461.31  4560.1  458.32  4582.5  456.88  4642.5  453.88
  4738.8  452.37  4793.0  450.89  4859.8  450.73  4915.2  450.74  4975.6  452.07
  4985.6  451.08  4995.7  448.62  5002.7  448.43  5003.2  447.63  5008.2  447.63
  5008.7  448.43  5012.8  451.95  5023.8  452.37  5086.2  457.81  5186.9  468.49
  5217.0  472.40  5267.3  476.02  5297.5  479.15  5388.1  482.84  5460.3  484.43
#Mann=4,-1,0
  4305.0    0.05       0  4507.6    0.12       0  5002.7    0.07       0
  5008.7    0.12       0
Bank Sta=4738.8,5023.8
Exp/Cntr=0.3,0.1

Type RM Length L Ch R = 1,150,0,0,0
BEGIN DESCRIPTION:
UNT 038 in Running Cr Watershed 1.0
END DESCRIPTION:
XS GIS Cut Line= 4
      2873424.99      7068025.00      2874288.74      7067825.55
      2874439.78      7067596.38      2874137.84      7067049.78
#Sta/Elev= 30
  4001.6  482.00  4104.2  475.04  4116.2  472.53  4196.6  466.42  4206.9  464.74
  4258.2  460.04  4333.8  454.41  4371.3  452.53  4463.3  449.32  4586.0  448.29
  4812.4  446.95  4868.6  446.26  4883.6  445.28  4900.7  446.43  4979.9  447.22
  4992.0  442.92  4992.5  442.12  4997.5  442.12  4998.0  442.92  5001.0  446.75
  5008.5  447.93  5094.3  447.27  5156.2  448.29  5426.1  453.92  5518.8  459.88
  5550.9  460.80  5586.8  465.05  5632.3  468.17  5659.8  471.35  5787.0  481.07
#Mann=5,-1,0
  4001.6    0.05       0  4333.8    0.16       0  4371.3    0.12       0
  4992.0    0.07       0  4998.0    0.12       0
Bank Sta=4586,5156.2
Exp/Cntr=0.3,0.1

Chan Stop Cuts=-1