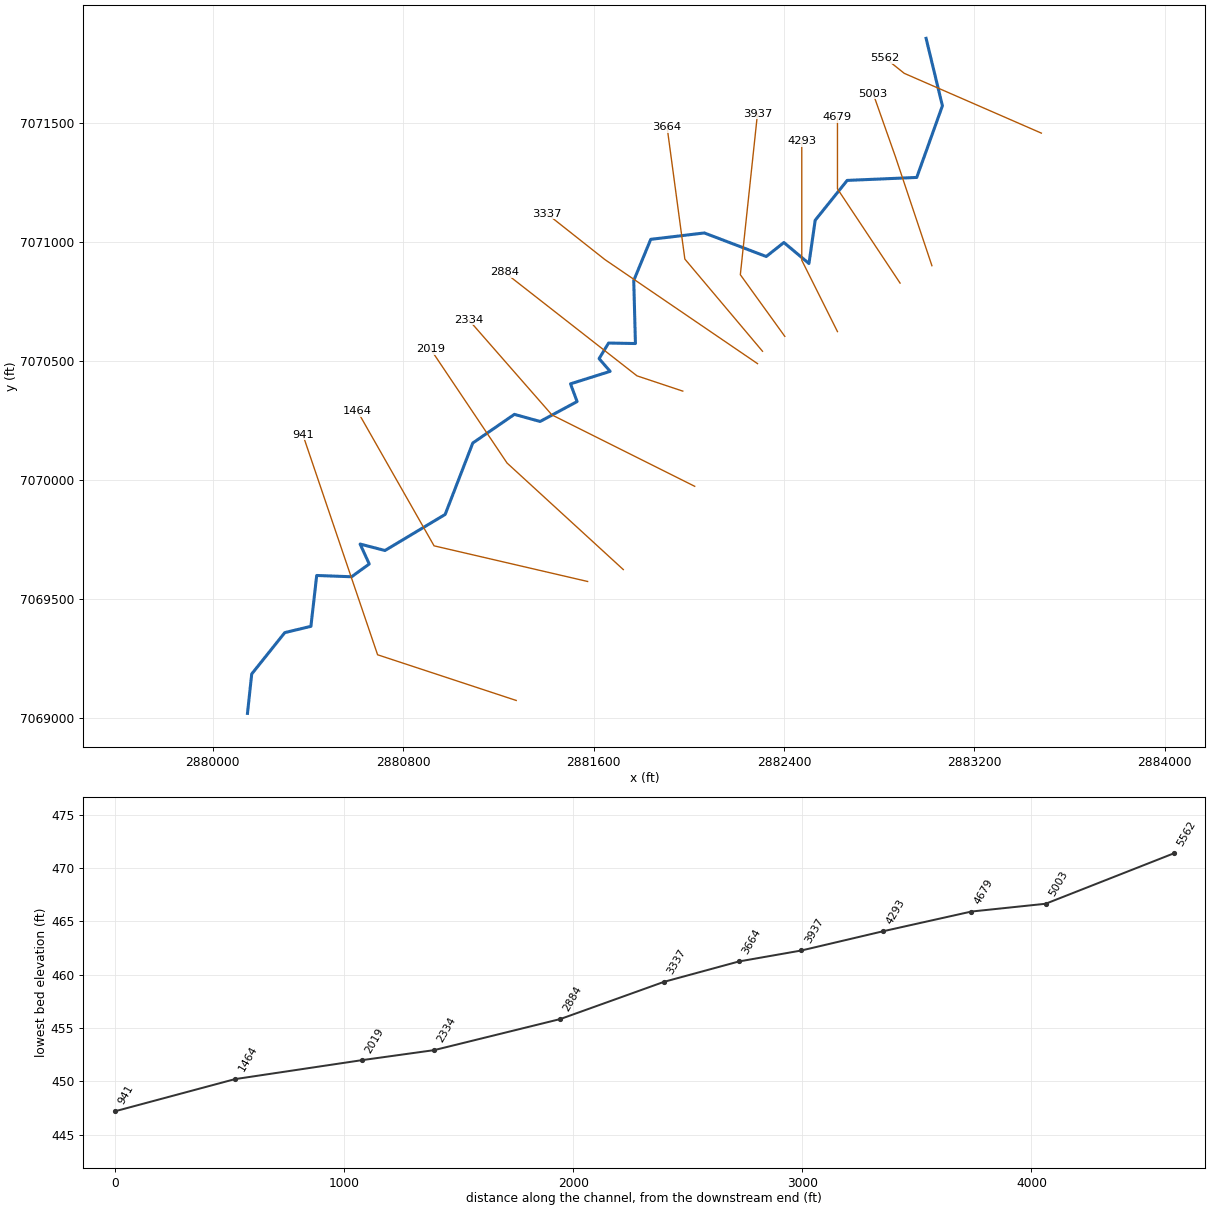
--- UNT 039 in Running Cr Watershed.prj (project) ---

Proj Title=UNT 039 in Running Cr Watershed Base Level Engineering
Current Plan=p01
Default Exp/Contr=0.3,0.1
English Units
Geom File=g01
Flow File=f01
Plan File=p01
BEGIN DESCRIPTION:
UNT 039 in Running Cr Watershed
END DESCRIPTION:

--- UNT 039 in Running Cr Watershed.p01 (plan) ---

Plan Title=Multiple Run
Short Identifier=Multiple
Geom File=g01
Flow File=f01
Subcritical Flow
K Sum by GR= 0
Std Step Tol= 0.01
Critical Tol= 0.01
Num of Std Step Trials= 20
Max Error Tol= 0.3
Flow Tol Ratio= 0.001
Split Flow NTrial= 30
Split Flow Tol= 0.02
Split Flow Ratio= 0.02
Log Output Level= 0
Friction Slope Method= 1
Unsteady Friction Slope Method= 2
Unsteady Bridges Friction Slope Method= 1
Parabolic Critical Depth
Global Vel Dist=  1 , 1 , 1
Global Log Level= 0
CheckData=True
Encroach Param= -1, 0, 0, 0
BEGIN DESCRIPTION:
Multiple Run
END DESCRIPTION:

--- UNT 039 in Running Cr Watershed.f01 (steady flow) ---

Flow Title=Multiple
Number of Profiles=7
Profile Names=10-year,25-year,50-year,1pct_min,100-year,1pct_plu,500-year
River Rch & RM= UNT 039 in Runni,Reach-1,5562
     876    1192    1452     877    1751    3493    2538
Boundary for River Rch & Prof#=UNT 039 in Runni,Reach-1,1
Up Type=0
Dn Type=3
Dn Slope=0.005
Boundary for River Rch & Prof#=UNT 039 in Runni,Reach-1,2
Up Type=0
Dn Type=3
Dn Slope=0.005
Boundary for River Rch & Prof#=UNT 039 in Runni,Reach-1,3
Up Type=0
Dn Type=3
Dn Slope=0.005
Boundary for River Rch & Prof#=UNT 039 in Runni,Reach-1,4
Up Type=0
Dn Type=3
Dn Slope=0.005
Boundary for River Rch & Prof#=UNT 039 in Runni,Reach-1,5
Up Type=0
Dn Type=3
Dn Slope=0.005
Boundary for River Rch & Prof#=UNT 039 in Runni,Reach-1,6
Up Type=0
Dn Type=3
Dn Slope=0.005
Boundary for River Rch & Prof#=UNT 039 in Runni,Reach-1,7
Up Type=0
Dn Type=3
Dn Slope=0.005

--- UNT 039 in Running Cr Watershed.g01 (geometry) ---

Geom Title=Existing Conditions

River Reach=UNT 039 in Runni,Reach-1
Reach XY= 30
      2882997.43      7071857.53      2883066.04      7071573.91
      2882958.20      7071272.97      2882665.85      7071260.48
      2882531.41      7071092.98      2882505.20      7070911.19
      2882399.85      7070999.47      2882325.68      7070940.68
      2882065.47      7071039.65      2881840.29      7071012.78
      2881768.85      7070839.67      2881775.98      7070574.96
      2881663.17      7070577.04      2881623.25      7070511.52
      2881669.65      7070458.01      2881503.14      7070405.55
      2881530.84      7070331.12      2881375.31      7070247.38
      2881267.27      7070277.30      2881092.34      7070156.76
      2880976.33      7069856.64      2880723.47      7069705.17
      2880618.88      7069732.32      2880657.35      7069648.50
      2880583.19      7069594.85      2880436.52      7069600.21
      2880412.16      7069386.48      2880302.39      7069360.15
      2880163.42      7069186.31      2880145.59      7069020.71

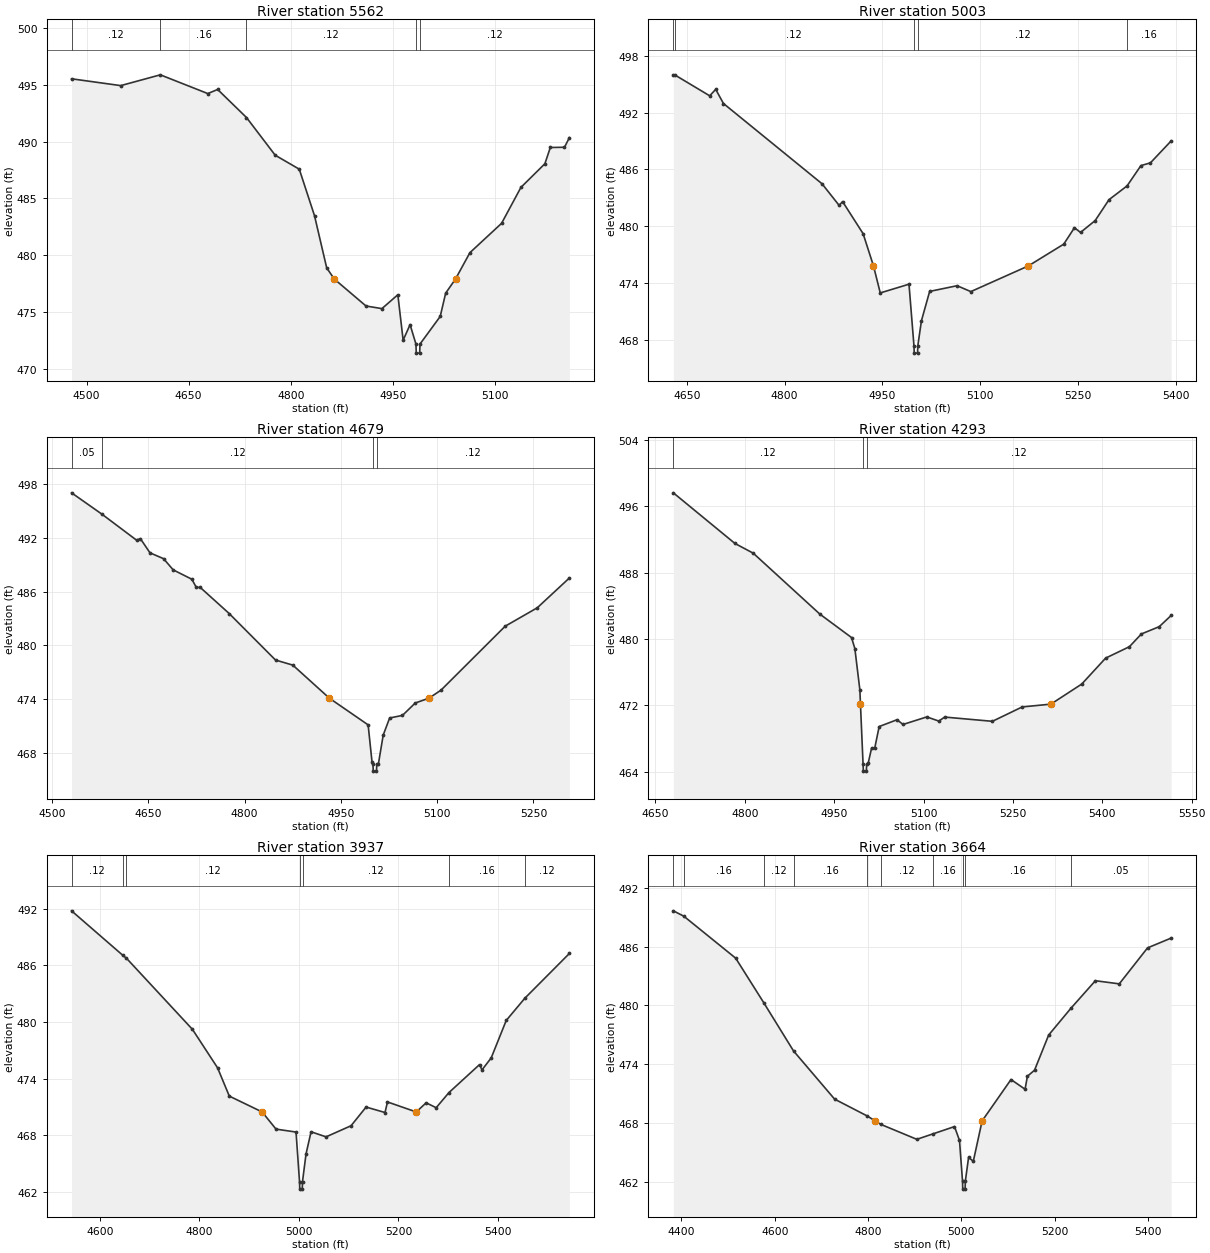
Type RM Length L Ch R = 1,5562,559,559,559
BEGIN DESCRIPTION:
UNT 039 in Running Cr Watershed 12.0
END DESCRIPTION:
XS GIS Cut Line= 3
      2883481.85      7071459.16      2882905.74      7071710.41
      2882825.01      7071774.99
#Sta/Elev= 30
  4477.8  495.54  4550.1  494.94  4608.3  495.89  4678.1  494.24  4692.6  494.60
  4735.0  492.13  4777.2  488.81  4812.6  487.58  4835.0  483.48  4852.9  478.89
  4864.0  477.91  4910.7  475.53  4934.1  475.30  4957.5  476.52  4965.3  472.52
  4975.5  473.89  4984.1  472.18  4984.6  471.38  4989.6  471.38  4990.1  472.18
  5019.8  474.61  5027.8  476.66  5042.3  477.91  5063.5  480.23  5110.0  482.81
  5138.5  485.98  5173.7  488.06  5181.7  489.49  5202.5  489.51  5209.7  490.36
#Mann=5,-1,0
  4477.8    0.12       0  4608.3    0.16       0  4735.0    0.12       0
  4984.1    0.07       0  4990.1    0.12       0
Bank Sta=4864,5042.3
Exp/Cntr=0.3,0.1

Type RM Length L Ch R = 1,5003,324,324,324
BEGIN DESCRIPTION:
UNT 039 in Running Cr Watershed 11.0
END DESCRIPTION:
XS GIS Cut Line= 3
      2883021.88      7070902.08      2882868.53      7071360.11
      2882775.01      7071624.97
#Sta/Elev= 30
  4629.3  495.97  4631.3  495.97  4685.1  493.76  4694.3  494.44  4706.2  492.95
  4857.4  484.50  4883.7  482.22  4889.0  482.62  4920.5  479.24  4936.4  475.85
  4946.8  473.00  4990.9  473.92  4998.5  467.46  4999.0  466.66  5004.0  466.66
  5004.5  467.46  5010.0  470.07  5022.6  473.16  5064.7  473.76  5085.8  473.14
  5174.2  475.85  5228.4  478.14  5244.8  479.87  5254.1  479.37  5276.6  480.62
  5297.8  482.82  5325.5  484.27  5346.8  486.41  5361.4  486.70  5393.2  489.01
#Mann=5,-1,0
  4629.3    0.05       0  4631.3    0.12       0  4998.5    0.07       0
  5004.5    0.12       0  5325.5    0.16       0
Bank Sta=4936.4,5174.2
Exp/Cntr=0.3,0.1

Type RM Length L Ch R = 1,4679,386,386,386
BEGIN DESCRIPTION:
UNT 039 in Running Cr Watershed 10.0
END DESCRIPTION:
XS GIS Cut Line= 3
      2882888.11      7070828.92      2882625.00      7071225.00
      2882625.00      7071525.00
#Sta/Elev= 30
  4530.5  497.04  4577.9  494.65  4631.7  491.75  4637.7  491.92  4652.7  490.33
  4673.8  489.68  4688.8  488.43  4717.9  487.38  4724.9  486.46  4730.9  486.47
  4776.0  483.55  4848.2  478.35  4875.2  477.78  4932.2  474.08  4992.5  471.10
  4998.5  466.99  5000.0  466.73  5000.5  465.93  5005.5  465.93  5006.0  466.73
  5008.5  466.73  5016.0  469.96  5026.0  471.87  5046.0  472.16  5066.0  473.55
  5087.2  474.08  5106.0  474.98  5206.0  482.13  5256.0  484.19  5306.0  487.52
#Mann=4,-1,0
  4530.5    0.05       0  4577.9    0.12       0  5000.0    0.07       0
  5006.0    0.12       0
Bank Sta=4932.2,5087.2
Exp/Cntr=0.3,0.1

Type RM Length L Ch R = 1,4293,356,356,356
BEGIN DESCRIPTION:
UNT 039 in Running Cr Watershed 9.0
END DESCRIPTION:
XS GIS Cut Line= 3
      2882624.98      7070625.04      2882475.00      7070925.00
      2882475.00      7071425.04
#Sta/Elev= 30
  4680.2  497.60  4783.6  491.50  4814.3  490.33  4926.1  482.99  4979.2  480.17
  4984.8  478.84  4993.2  473.87  4994.2  472.15  4998.6  464.88  4999.1  464.08
  5004.1  464.08  5004.6  464.88  5007.2  465.04  5012.8  466.83  5018.1  466.83
  5025.6  469.45  5055.6  470.27  5065.6  469.70  5105.6  470.61  5125.6  470.11
  5135.6  470.59  5215.6  470.08  5265.6  471.81  5313.8  472.15  5365.6  474.57
  5405.6  477.69  5445.6  479.07  5465.6  480.60  5495.6  481.48  5515.6  482.83
#Mann=3,-1,0
  4680.2    0.12       0  4998.6    0.07       0  5004.6    0.12       0
Bank Sta=4994.2,5313.8
Exp/Cntr=0.3,0.1

Type RM Length L Ch R = 1,3937,273,273,273
BEGIN DESCRIPTION:
UNT 039 in Running Cr Watershed 8.0
END DESCRIPTION:
XS GIS Cut Line= 3
      2882403.70      7070605.01      2882216.80      7070864.23
      2882288.98      7071541.22
#Sta/Elev= 30
  4543.0  491.78  4646.1  487.06  4653.4  486.75  4786.0  479.21  4836.4  475.14
  4860.0  472.14  4926.0  470.46  4953.9  468.64  4994.1  468.33  5001.1  463.08
  5001.6  462.28  5006.6  462.28  5007.1  463.08  5014.2  466.01  5024.3  468.36
  5054.4  467.82  5104.7  469.00  5134.9  470.98  5172.9  470.40  5177.9  471.52
  5235.7  470.46  5255.6  471.43  5275.7  470.91  5301.5  472.52  5362.8  475.48
  5367.8  474.92  5386.3  476.19  5416.5  480.16  5454.0  482.52  5543.4  487.26
#Mann=7,-1,0
  4543.0    0.12       0  4646.1    0.16       0  4653.4    0.12       0
  5001.1    0.07       0  5007.1    0.12       0  5301.5    0.16       0
  5454.0    0.12       0
Bank Sta=4926,5235.7
Exp/Cntr=0.3,0.1

Type RM Length L Ch R = 1,3664,327,327,327
BEGIN DESCRIPTION:
UNT 039 in Running Cr Watershed 7.0
END DESCRIPTION:
XS GIS Cut Line= 3
      2882309.96      7070542.50      2881983.62      7070929.96
      2881908.92      7071485.18
#Sta/Elev= 30
  4382.8  489.64  4405.3  489.09  4516.4  484.81  4576.9  480.24  4640.3  475.35
  4728.4  470.43  4798.4  468.71  4815.2  468.21  4827.7  467.85  4904.6  466.33
  4939.4  466.89  4985.3  467.63  4996.0  466.22  5002.5  462.05  5003.0  461.25
  5008.0  461.25  5008.5  462.05  5015.5  464.49  5025.6  464.09  5044.5  468.21
  5106.4  472.43  5136.5  471.44  5141.6  472.77  5156.8  473.38  5187.1  476.97
  5234.6  479.69  5287.2  482.51  5338.4  482.19  5399.0  485.86  5449.6  486.86
#Mann=10,-1,0
  4382.8    0.12       0  4405.3    0.16       0  4576.9    0.12       0
  4640.3    0.16       0  4798.4    0.05       0  4827.7    0.12       0
  4939.4    0.16       0  5002.5    0.07       0  5008.5    0.16       0
  5234.6    0.05       0
Bank Sta=4815.2,5044.5
Exp/Cntr=0.3,0.1

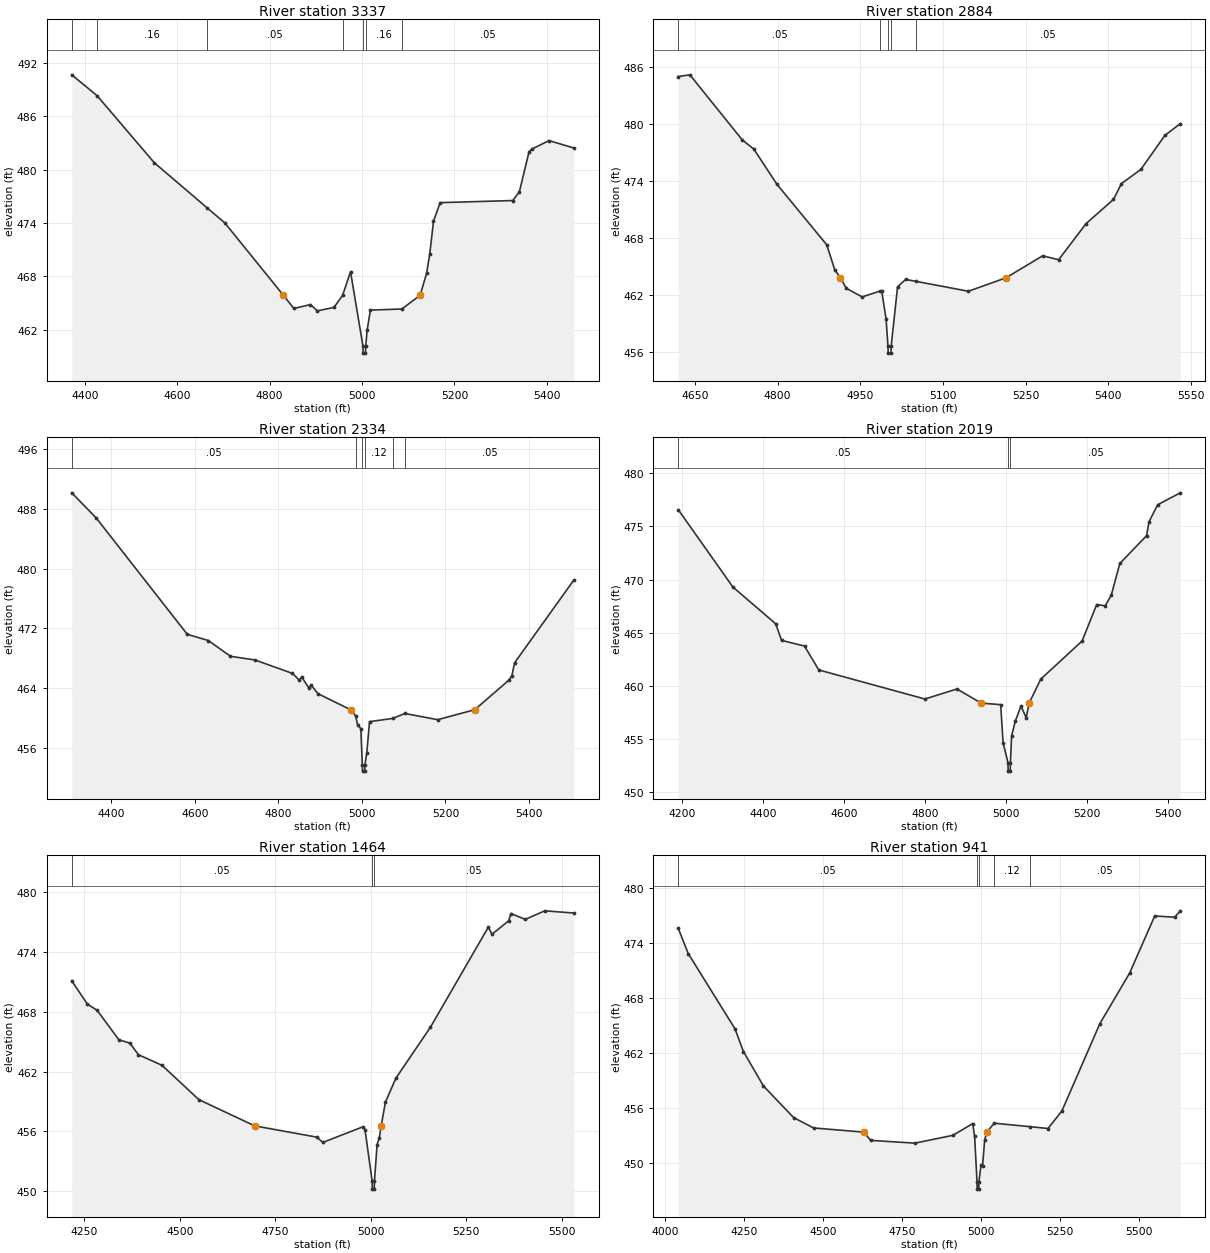
Type RM Length L Ch R = 1,3337,453,453,453
BEGIN DESCRIPTION:
UNT 039 in Running Cr Watershed 6.0
END DESCRIPTION:
XS GIS Cut Line= 3
      2882289.09      7070490.44      2881647.70      7070927.76
      2881404.11      7071120.31
#Sta/Elev= 30
  4371.7  490.69  4426.5  488.34  4550.3  480.79  4664.8  475.70  4702.8  474.02
  4829.7  465.86  4852.5  464.37  4888.4  464.81  4903.3  464.10  4939.2  464.49
  4957.9  465.84  4975.1  468.51  5002.0  460.14  5002.5  459.34  5007.5  459.34
  5008.0  460.14  5011.0  461.90  5018.1  464.19  5086.2  464.31  5125.8  465.86
  5139.7  468.32  5146.6  470.52  5154.7  474.19  5169.1  476.29  5326.3  476.53
  5340.7  477.53  5361.5  482.02  5368.1  482.34  5404.8  483.28  5458.5  482.45
#Mann=7,-1,0
  4371.7    0.12       0  4426.5    0.16       0  4664.8    0.05       0
  4957.9    0.16       0  5002.0    0.07       0  5008.0    0.16       0
  5086.2    0.05       0
Bank Sta=4829.7,5125.8
Exp/Cntr=0.3,0.1

Type RM Length L Ch R = 1,2884,550,550,550
BEGIN DESCRIPTION:
UNT 039 in Running Cr Watershed 5.0
END DESCRIPTION:
XS GIS Cut Line= 3
      2881975.01      7070375.00      2881782.46      7070439.18
      2881224.98      7070875.02
#Sta/Elev= 30
  4619.8  485.00  4640.9  485.18  4735.8  478.33  4756.8  477.36  4799.0  473.63
  4889.2  467.26  4903.7  464.63  4914.0  463.79  4924.5  462.69  4953.4  461.77
  4986.6  462.41  4988.7  462.44  4996.8  459.44  5000.1  456.65  5000.6  455.85
  5005.6  455.85  5006.1  456.65  5017.6  462.84  5032.1  463.61  5050.6  463.42
  5146.0  462.37  5214.3  463.79  5280.8  466.11  5309.7  465.69  5359.5  469.50
  5409.2  472.05  5423.7  473.72  5458.9  475.21  5502.3  478.79  5530.4  480.04
#Mann=5,-1,0
  4619.8    0.05       0  4986.6    0.16       0  5000.1    0.07       0
  5006.1    0.16       0  5050.6    0.05       0
Bank Sta=4914,5214.3
Exp/Cntr=0.3,0.1

Type RM Length L Ch R = 1,2334,315,315,315
BEGIN DESCRIPTION:
UNT 039 in Running Cr Watershed 4.0
END DESCRIPTION:
XS GIS Cut Line= 3
      2882025.02      7069974.99      2881425.00      7070275.00
      2881075.03      7070674.97
#Sta/Elev= 30
  4305.1  490.12  4363.8  486.75  4581.8  471.21  4632.1  470.39  4685.2  468.28
  4743.9  467.79  4833.4  466.00  4850.2  465.08  4855.7  465.54  4872.5  464.06
  4878.1  464.44  4894.9  463.28  4972.7  461.15  4984.9  460.32  4989.7  459.11
  4997.3  458.62  5000.9  453.74  5001.4  452.94  5006.4  452.94  5006.9  453.74
  5011.5  455.34  5018.2  459.55  5073.6  459.98  5102.9  460.64  5181.4  459.81
  5270.2  461.15  5351.3  465.07  5358.9  465.66  5365.6  467.42  5507.4  478.47
#Mann=6,-1,0
  4305.1    0.05       0  4984.9    0.12       0  5000.9    0.07       0
  5006.9    0.12       0  5073.6    0.07       0  5102.9    0.05       0
Bank Sta=4972.7,5270.2
Exp/Cntr=0.3,0.1

Type RM Length L Ch R = 1,2019,555,555,555
BEGIN DESCRIPTION:
UNT 039 in Running Cr Watershed 3.0
END DESCRIPTION:
XS GIS Cut Line= 3
      2881725.02      7069624.98      2881236.31      7070072.96
      2880915.09      7070551.48
#Sta/Elev= 30
  4190.4  476.58  4325.2  469.31  4431.2  465.84  4445.4  464.29  4502.1  463.76
  4537.3  461.51  4799.3  458.78  4878.3  459.72  4938.6  458.39  4986.3  458.25
  4992.3  454.66  5004.3  452.80  5004.8  452.00  5009.8  452.00  5010.3  452.80
  5013.3  455.32  5022.3  456.69  5036.5  458.12  5049.3  457.01  5056.5  458.39
  5085.3  460.65  5187.3  464.23  5223.3  467.66  5244.4  467.54  5259.4  468.55
  5280.4  471.52  5346.4  474.13  5352.4  475.43  5373.7  477.04  5429.7  478.16
#Mann=3,-1,0
  4190.4    0.05       0  5004.3    0.03       0  5010.3    0.05       0
Bank Sta=4938.6,5056.5
Exp/Cntr=0.3,0.1

Type RM Length L Ch R = 1,1464,523,523,523
BEGIN DESCRIPTION:
UNT 039 in Running Cr Watershed 2.0
END DESCRIPTION:
XS GIS Cut Line= 3
      2881575.00      7069575.00      2880929.75      7069724.80
      2880607.54      7070291.26
#Sta/Elev= 30
  4217.2  471.09  4258.3  468.75  4283.7  468.14  4340.4  465.19  4369.0  464.86
  4391.7  463.69  4453.3  462.63  4549.8  459.19  4695.9  456.56  4858.6  455.43
  4874.2  454.90  4978.9  456.46  4984.7  456.19  5003.4  451.02  5003.9  450.22
  5008.9  450.22  5009.4  451.02  5016.4  454.69  5022.2  455.37  5027.1  456.56
  5038.0  458.92  5065.4  461.33  5156.0  466.45  5307.6  476.48  5317.0  475.76
  5360.9  477.12  5366.7  477.84  5404.1  477.25  5455.1  478.11  5531.3  477.89
#Mann=3,-1,0
  4217.2    0.05       0  5003.4    0.03       0  5009.4    0.05       0
Bank Sta=4695.9,5027.1
Exp/Cntr=0.3,0.1

Type RM Length L Ch R = 1,941,0,0,0
BEGIN DESCRIPTION:
UNT 039 in Running Cr Watershed 1.0
END DESCRIPTION:
XS GIS Cut Line= 3
      2881274.96      7069075.01      2880692.41      7069267.02
      2880378.27      7070191.75
#Sta/Elev= 30
  4040.9  475.58  4072.4  472.83  4220.8  464.63  4247.3  462.17  4310.9  458.42
  4406.2  454.99  4469.7  453.86  4628.1  453.41  4650.3  452.51  4790.4  452.21
  4910.7  453.06  4973.5  454.34  4979.5  452.95  4987.1  448.01  4987.6  447.21
  4992.6  447.21  4993.1  448.01  4999.6  449.78  5004.8  449.76  5011.2  452.53
  5017.8  453.41  5041.7  454.38  5155.4  454.00  5211.9  453.80  5255.9  455.71
  5376.2  465.21  5470.4  470.70  5549.8  476.91  5613.2  476.78  5630.9  477.47
#Mann=5,-1,0
  4040.9    0.05       0  4987.1    0.03       0  4993.1    0.05       0
  5041.7    0.12       0  5155.4    0.05       0
Bank Sta=4628.1,5017.8
Exp/Cntr=0.3,0.1

Chan Stop Cuts=-1