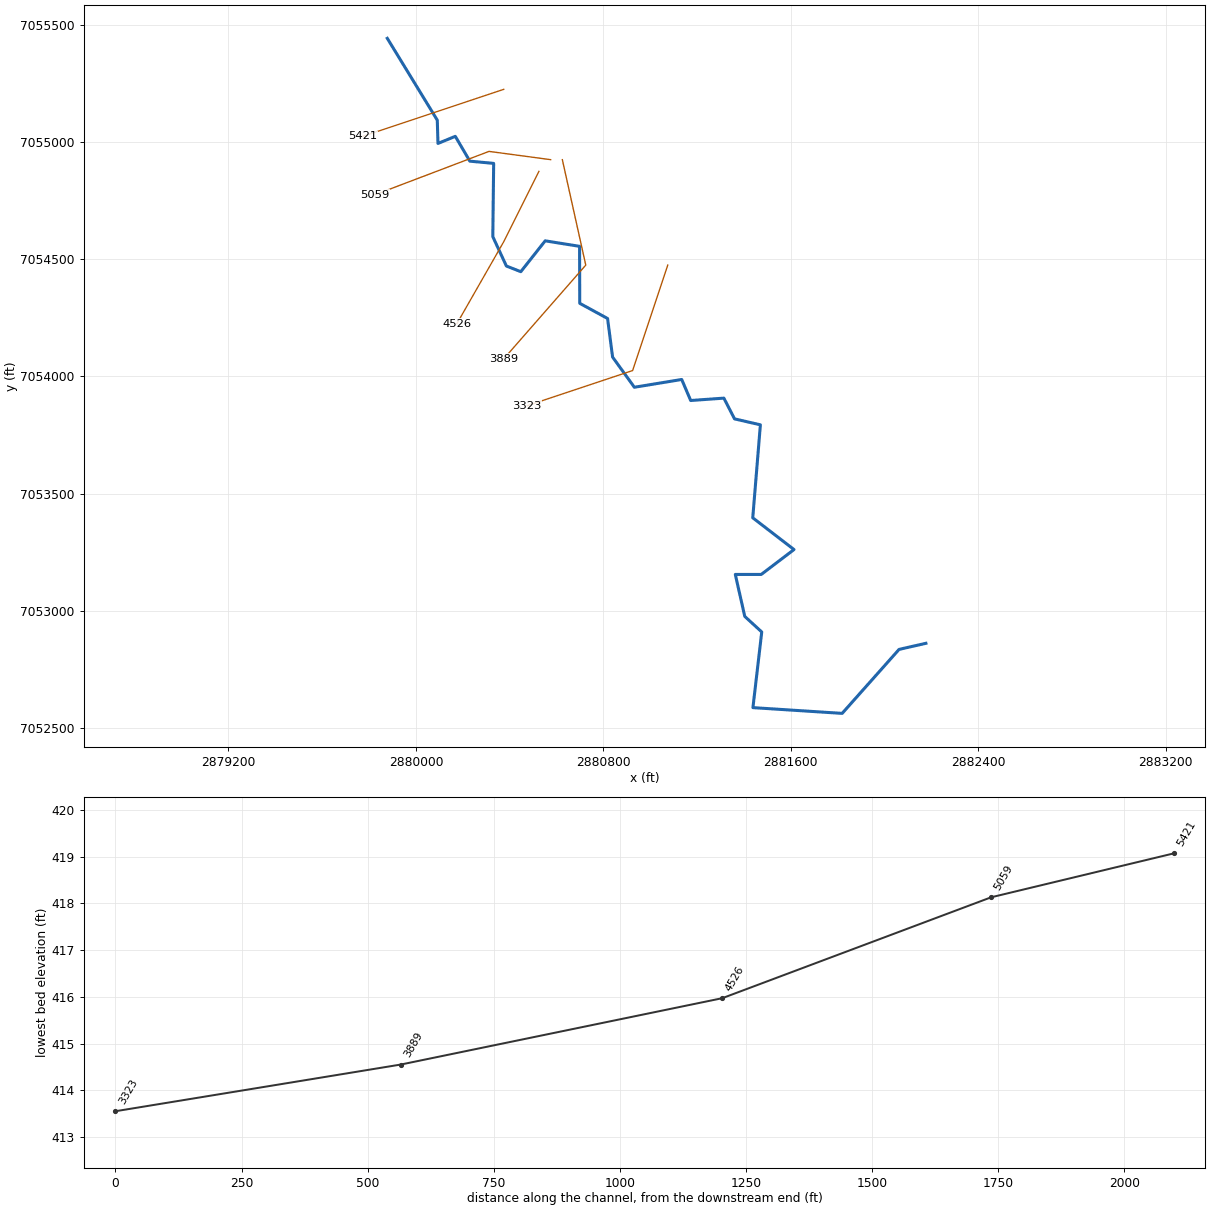
--- UNT 040 in Running Cr Watershed.prj (project) ---

Proj Title=UNT 040 in Running Cr Watershed Base Level Engineering
Current Plan=p01
Default Exp/Contr=0.3,0.1
English Units
Geom File=g01
Flow File=f01
Plan File=p01
BEGIN DESCRIPTION:
UNT 040 in Running Cr Watershed
END DESCRIPTION:

--- UNT 040 in Running Cr Watershed.p01 (plan) ---

Plan Title=Multiple Run
Short Identifier=Multiple
Geom File=g01
Flow File=f01
Subcritical Flow
K Sum by GR= 0
Std Step Tol= 0.01
Critical Tol= 0.01
Num of Std Step Trials= 20
Max Error Tol= 0.3
Flow Tol Ratio= 0.001
Split Flow NTrial= 30
Split Flow Tol= 0.02
Split Flow Ratio= 0.02
Log Output Level= 0
Friction Slope Method= 1
Unsteady Friction Slope Method= 2
Unsteady Bridges Friction Slope Method= 1
Parabolic Critical Depth
Global Vel Dist=  1 , 1 , 1
Global Log Level= 0
CheckData=True
Encroach Param= -1, 0, 0, 0
BEGIN DESCRIPTION:
Multiple Run
END DESCRIPTION:

--- UNT 040 in Running Cr Watershed.f01 (steady flow) ---

Flow Title=Multiple
Number of Profiles=7
Profile Names=10-year,25-year,50-year,1pct_min,100-year,1pct_plu,500-year
River Rch & RM= UNT 040 in Runni,Reach-1,5421
     591     792     955     573    1144    2283    1642
River Rch & RM= UNT 040 in Runni,Reach-1,3889
     595     795     958     573    1144    2282    1634
Boundary for River Rch & Prof#=UNT 040 in Runni,Reach-1,1
Up Type=0
Dn Type=3
Dn Slope=0.005
Boundary for River Rch & Prof#=UNT 040 in Runni,Reach-1,2
Up Type=0
Dn Type=3
Dn Slope=0.005
Boundary for River Rch & Prof#=UNT 040 in Runni,Reach-1,3
Up Type=0
Dn Type=3
Dn Slope=0.005
Boundary for River Rch & Prof#=UNT 040 in Runni,Reach-1,4
Up Type=0
Dn Type=3
Dn Slope=0.005
Boundary for River Rch & Prof#=UNT 040 in Runni,Reach-1,5
Up Type=0
Dn Type=3
Dn Slope=0.005
Boundary for River Rch & Prof#=UNT 040 in Runni,Reach-1,6
Up Type=0
Dn Type=3
Dn Slope=0.005
Boundary for River Rch & Prof#=UNT 040 in Runni,Reach-1,7
Up Type=0
Dn Type=3
Dn Slope=0.005

--- UNT 040 in Running Cr Watershed.g01 (geometry) ---

Geom Title=Existing Conditions

River Reach=UNT 040 in Runni,Reach-1
Reach XY= 30
      2879877.93      7055442.76      2880091.35      7055093.53
      2880094.27      7054994.13      2880168.23      7055024.56
      2880230.31      7054918.53      2880331.94      7054909.10
      2880328.26      7054596.39      2880386.23      7054470.98
      2880447.82      7054446.86      2880551.82      7054578.54
      2880698.57      7054555.05      2880699.32      7054311.83
      2880818.08      7054247.07      2880839.48      7054082.32
      2880932.44      7053953.65      2881134.48      7053986.83
      2881172.78      7053897.06      2881314.43      7053907.19
      2881359.90      7053818.75      2881470.23      7053793.31
      2881437.67      7053396.52      2881613.71      7053260.95
      2881474.01      7053154.81      2881363.19      7053154.81
      2881403.56      7052975.72      2881476.02      7052909.21
      2881438.42      7052586.35      2881819.31      7052561.83
      2882062.07      7052834.83      2882176.64      7052860.89

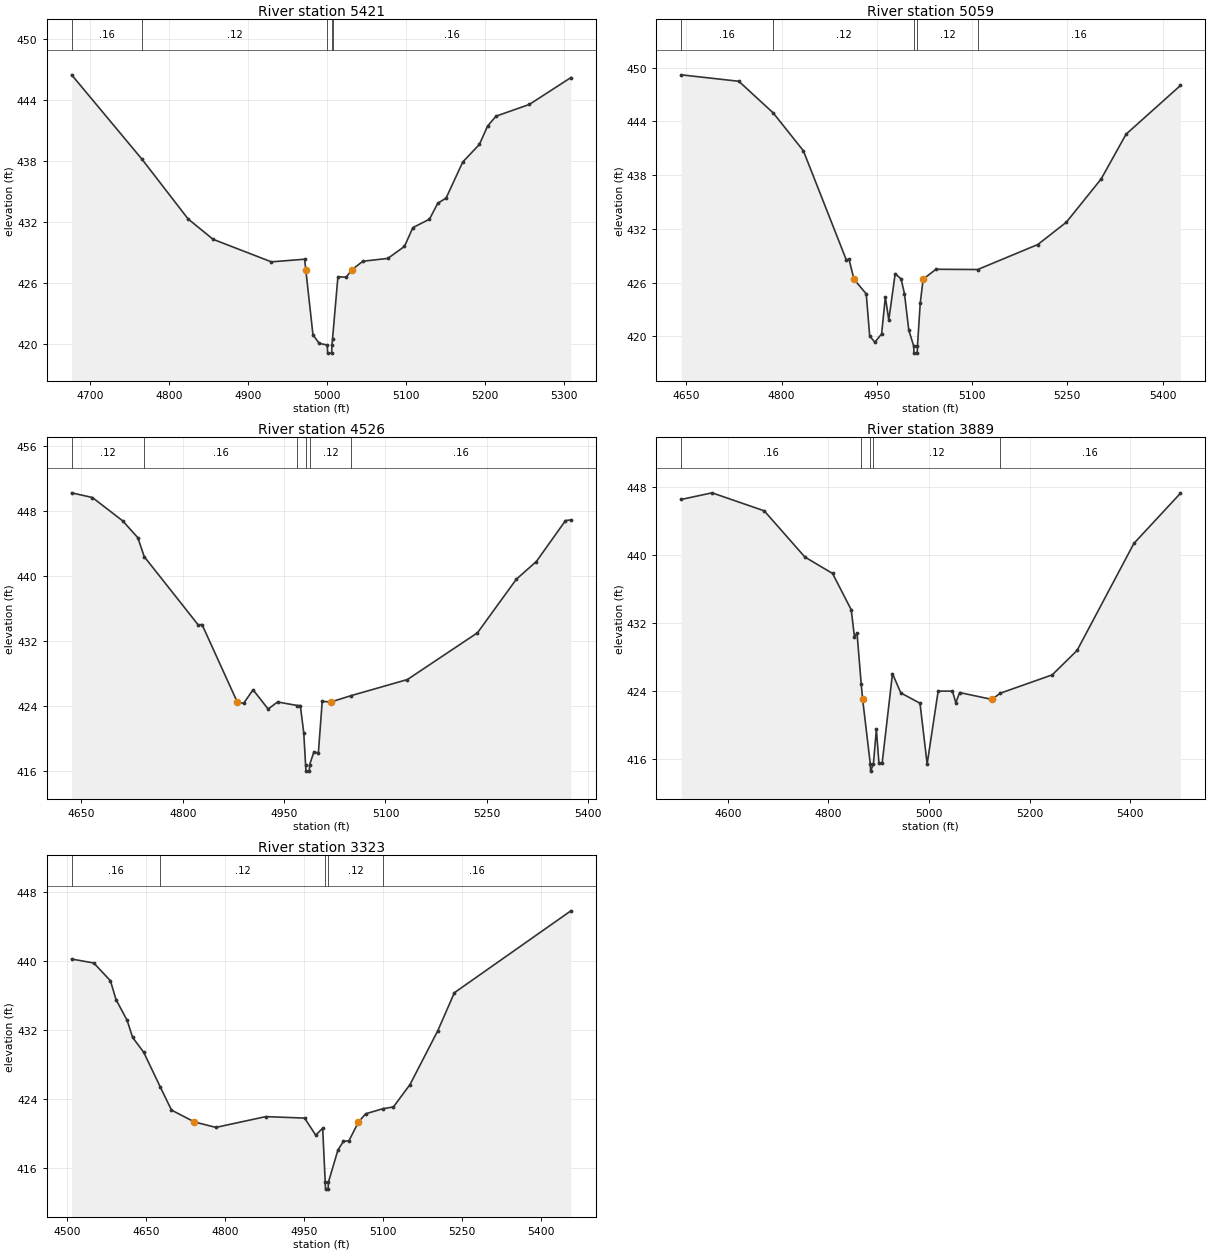
Type RM Length L Ch R = 1,5421,362,362,362
BEGIN DESCRIPTION:
UNT 040 in Running Cr Watershed 5.0
END DESCRIPTION:
XS GIS Cut Line= 3
      2880374.99      7055225.00      2880075.00      7055125.00
      2879775.04      7055025.01
#Sta/Elev= 30
  4676.1  446.48  4765.4  438.15  4823.7  432.28  4855.3  430.28  4929.1  428.06
  4971.2  428.32  4972.7  427.27  4981.8  420.87  4989.7  420.03  4999.9  419.87
  5000.4  419.07  5005.4  419.07  5005.9  419.87  5006.6  420.50  5013.4  426.59
  5023.9  426.55  5030.9  427.27  5045.0  428.12  5076.6  428.40  5097.7  429.58
  5108.3  431.43  5129.3  432.26  5139.9  433.83  5150.4  434.34  5171.5  437.89
  5192.6  439.63  5203.1  441.45  5213.7  442.41  5255.8  443.56  5308.5  446.21
#Mann=5,-1,0
  4676.1    0.16       0  4765.4    0.12       0  4999.9    0.07       0
  5005.9    0.12       0  5006.6    0.16       0
Bank Sta=4972.7,5030.9
Exp/Cntr=0.3,0.1

Type RM Length L Ch R = 1,5059,533,533,533
BEGIN DESCRIPTION:
UNT 040 in Running Cr Watershed 4.0
END DESCRIPTION:
XS GIS Cut Line= 3
      2880575.02      7054925.00      2880312.11      7054960.25
      2879825.00      7054775.00
#Sta/Elev= 30
  4641.8  449.19  4732.6  448.47  4786.9  444.93  4834.3  440.71  4902.1  428.50
  4906.1  428.64  4913.9  426.38  4933.3  424.74  4938.7  420.06  4946.8  419.34
  4957.5  420.28  4963.4  424.39  4968.8  421.83  4978.9  427.00  4988.2  426.41
  4993.5  424.76  5000.3  420.70  5008.0  418.93  5008.5  418.13  5013.5  418.13
  5014.0  418.93  5018.3  423.68  5022.9  426.38  5043.1  427.49  5108.9  427.46
  5203.5  430.25  5248.5  432.74  5303.4  437.58  5342.6  442.57  5428.2  448.00
#Mann=5,-1,0
  4641.8    0.16       0  4786.9    0.12       0  5008.0    0.07       0
  5014.0    0.12       0  5108.9    0.16       0
Bank Sta=4913.9,5022.9
Exp/Cntr=0.3,0.1

Type RM Length L Ch R = 1,4526,637,637,637
BEGIN DESCRIPTION:
UNT 040 in Running Cr Watershed 3.0
END DESCRIPTION:
XS GIS Cut Line= 3
      2880525.02      7054875.03      2880375.00      7054575.00
      2880174.98      7054224.97
#Sta/Elev= 30
  4635.7  450.25  4666.5  449.67  4711.2  446.80  4733.6  444.73  4743.1  442.39
  4823.0  433.98  4828.6  434.03  4880.7  424.49  4890.1  424.32  4904.1  425.99
  4926.4  423.62  4940.4  424.49  4969.8  424.05  4974.0  424.05  4979.1  420.69
  4981.8  416.77  4982.3  415.97  4987.3  415.97  4987.8  416.77  4994.2  418.35
  5000.7  418.19  5006.4  424.56  5019.3  424.49  5049.6  425.28  5132.4  427.25
  5236.1  433.01  5293.6  439.61  5323.2  441.79  5366.3  446.83  5374.3  446.92
#Mann=6,-1,0
  4635.7    0.12       0  4743.1    0.16       0  4969.8    0.12       0
  4981.8    0.07       0  4987.8    0.12       0  5049.6    0.16       0
Bank Sta=4880.7,5019.3
Exp/Cntr=0.3,0.1

Type RM Length L Ch R = 1,3889,566,566,566
BEGIN DESCRIPTION:
UNT 040 in Running Cr Watershed 2.0
END DESCRIPTION:
XS GIS Cut Line= 3
      2880625.01      7054924.97      2880725.00      7054475.00
      2880375.03      7054075.04
#Sta/Elev= 30
  4507.5  446.52  4568.9  447.30  4672.6  445.18  4753.3  439.75  4808.4  437.81
  4845.5  433.54  4851.9  430.36  4857.0  430.81  4865.4  424.77  4868.2  422.99
  4883.5  415.35  4884.0  414.55  4889.5  415.35  4895.5  419.47  4900.6  415.46
  4907.0  415.51  4927.5  426.02  4944.1  423.75  4982.2  422.54  4996.4  415.39
  5018.3  423.97  5046.7  423.96  5053.4  422.60  5061.0  423.80  5124.9  422.99
  5141.8  423.72  5245.1  425.88  5294.5  428.76  5407.4  441.35  5499.9  447.25
#Mann=5,-1,0
  4507.5    0.16       0  4865.4    0.12       0  4883.5    0.07       0
  4889.5    0.12       0  5141.8    0.16       0
Bank Sta=4868.2,5124.9
Exp/Cntr=0.3,0.1

Type RM Length L Ch R = 1,3323,0,0,0
BEGIN DESCRIPTION:
UNT 040 in Running Cr Watershed 1.0
END DESCRIPTION:
XS GIS Cut Line= 3
      2881075.00      7054474.99      2880925.00      7054025.00
      2880474.98      7053874.99
#Sta/Elev= 30
  4508.5  440.27  4550.7  439.81  4582.3  437.74  4592.8  435.57  4613.9  433.16
  4624.4  431.17  4645.5  429.44  4676.6  425.46  4698.2  422.73  4741.9  421.35
  4782.6  420.72  4877.4  421.97  4951.2  421.80  4972.3  419.82  4985.5  420.62
  4990.4  414.35  4990.9  413.55  4995.9  413.55  4996.4  414.35  5014.5  418.09
  5025.0  419.10  5035.5  419.17  5053.6  421.35  5067.2  422.30  5100.0  422.89
  5119.9  423.09  5151.5  425.70  5204.2  431.94  5235.8  436.36  5457.2  445.87
#Mann=5,-1,0
  4508.5    0.16       0  4676.6    0.12       0  4990.4    0.07       0
  4996.4    0.12       0  5100.0    0.16       0
Bank Sta=4741.9,5053.6
Exp/Cntr=0.3,0.1

Chan Stop Cuts=-1