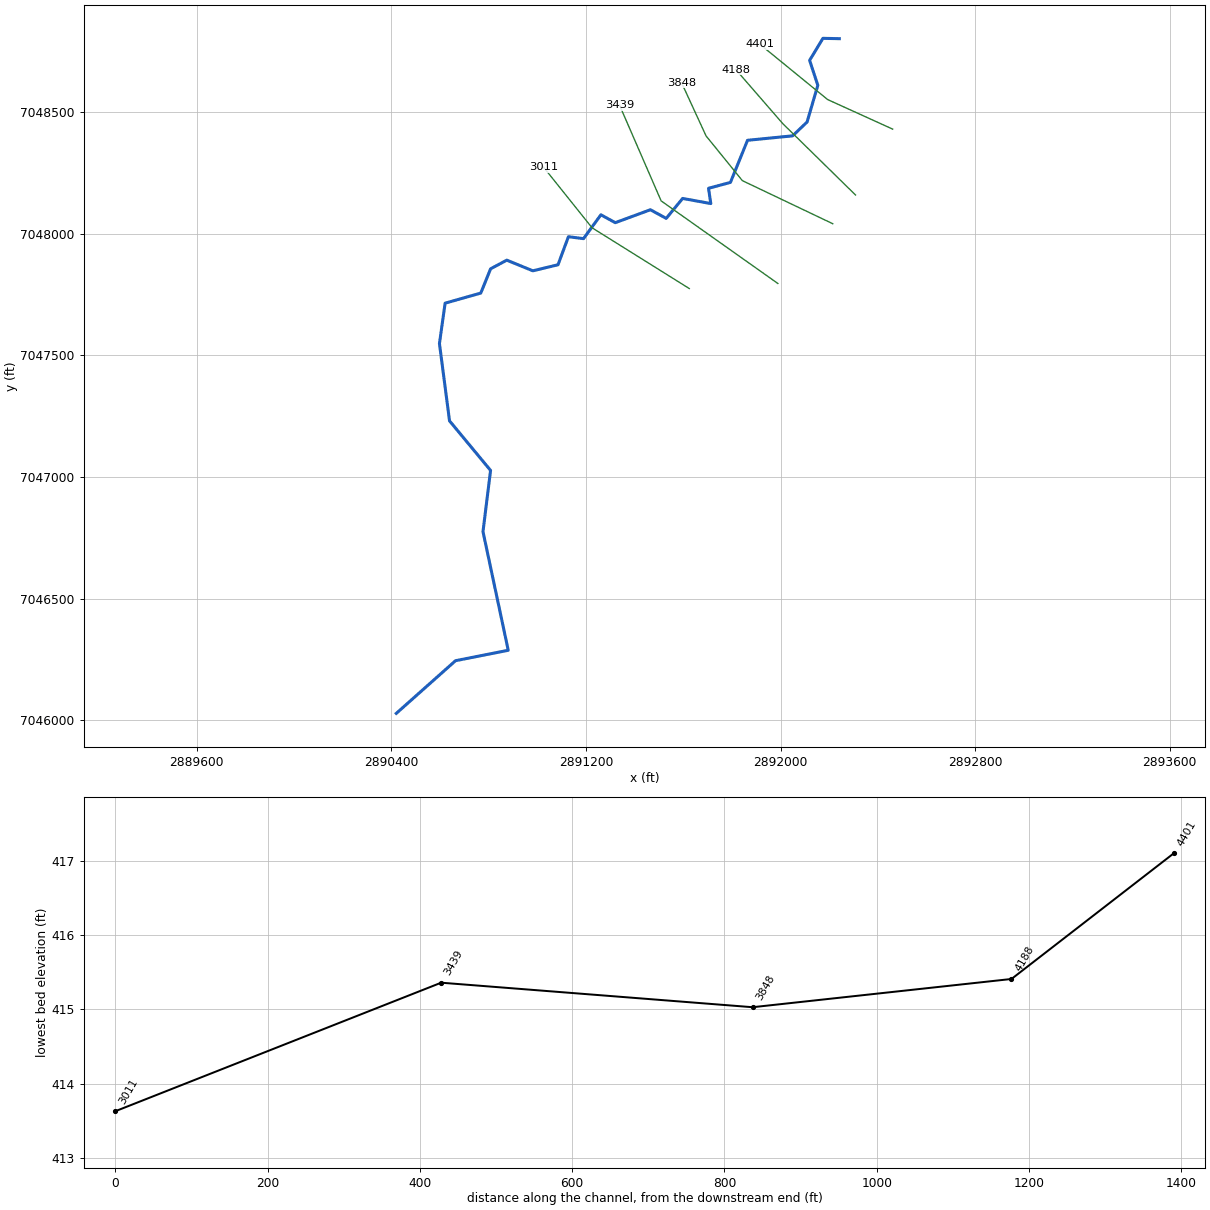
--- UNT 041 in Running Cr Watershed.prj (project) ---

Proj Title=UNT 041 in Running Cr Watershed Base Level Engineering
Current Plan=p01
Default Exp/Contr=0.3,0.1
English Units
Geom File=g01
Flow File=f01
Plan File=p01
BEGIN DESCRIPTION:
UNT 041 in Running Cr Watershed
END DESCRIPTION:

--- UNT 041 in Running Cr Watershed.p01 (plan) ---

Plan Title=Multiple Run
Short Identifier=Multiple
Geom File=g01
Flow File=f01
Subcritical Flow
K Sum by GR= 0
Std Step Tol= 0.01
Critical Tol= 0.01
Num of Std Step Trials= 20
Max Error Tol= 0.3
Flow Tol Ratio= 0.001
Split Flow NTrial= 30
Split Flow Tol= 0.02
Split Flow Ratio= 0.02
Log Output Level= 0
Friction Slope Method= 1
Unsteady Friction Slope Method= 2
Unsteady Bridges Friction Slope Method= 1
Parabolic Critical Depth
Global Vel Dist=  1 , 1 , 1
Global Log Level= 0
CheckData=True
Encroach Param= -1, 0, 0, 0
BEGIN DESCRIPTION:
Multiple Run
END DESCRIPTION:

--- UNT 041 in Running Cr Watershed.f01 (steady flow) ---

Flow Title=Multiple
Number of Profiles=7
Profile Names=10-year,25-year,50-year,1pct_min,100-year,1pct_plu,500-year
River Rch & RM= UNT 041 in Runni,Reach-1,4401
     466     609     723     426     851    1697    1179
Boundary for River Rch & Prof#=UNT 041 in Runni,Reach-1,1
Up Type=0
Dn Type=3
Dn Slope=0.005
Boundary for River Rch & Prof#=UNT 041 in Runni,Reach-1,2
Up Type=0
Dn Type=3
Dn Slope=0.005
Boundary for River Rch & Prof#=UNT 041 in Runni,Reach-1,3
Up Type=0
Dn Type=3
Dn Slope=0.005
Boundary for River Rch & Prof#=UNT 041 in Runni,Reach-1,4
Up Type=0
Dn Type=3
Dn Slope=0.005
Boundary for River Rch & Prof#=UNT 041 in Runni,Reach-1,5
Up Type=0
Dn Type=3
Dn Slope=0.005
Boundary for River Rch & Prof#=UNT 041 in Runni,Reach-1,6
Up Type=0
Dn Type=3
Dn Slope=0.005
Boundary for River Rch & Prof#=UNT 041 in Runni,Reach-1,7
Up Type=0
Dn Type=3
Dn Slope=0.005

--- UNT 041 in Running Cr Watershed.g01 (geometry) ---

Geom Title=Existing Conditions

River Reach=UNT 041 in Runni,Reach-1
Reach XY= 30
      2892241.80      7048802.45      2892174.49      7048803.84
      2892119.66      7048713.45      2892153.40      7048610.76
      2892109.25      7048459.83      2892049.79      7048402.90
      2891864.37      7048384.62      2891794.10      7048211.45
      2891703.95      7048187.23      2891713.37      7048124.48
      2891597.57      7048145.56      2891530.08      7048063.44
      2891465.11      7048099.09      2891320.56      7048045.93
      2891261.48      7048078.30      2891189.98      7047980.23
      2891127.96      7047988.17      2891085.14      7047872.86
      2890981.80      7047847.95      2890874.54      7047891.74
      2890808.00      7047856.26      2890767.60      7047756.42
      2890620.99      7047714.90      2890597.64      7047548.83
      2890639.15      7047230.95      2890807.82      7047027.25
      2890776.68      7046775.55      2890880.48      7046287.71
      2890663.80      7046244.89      2890420.22      7046028.29

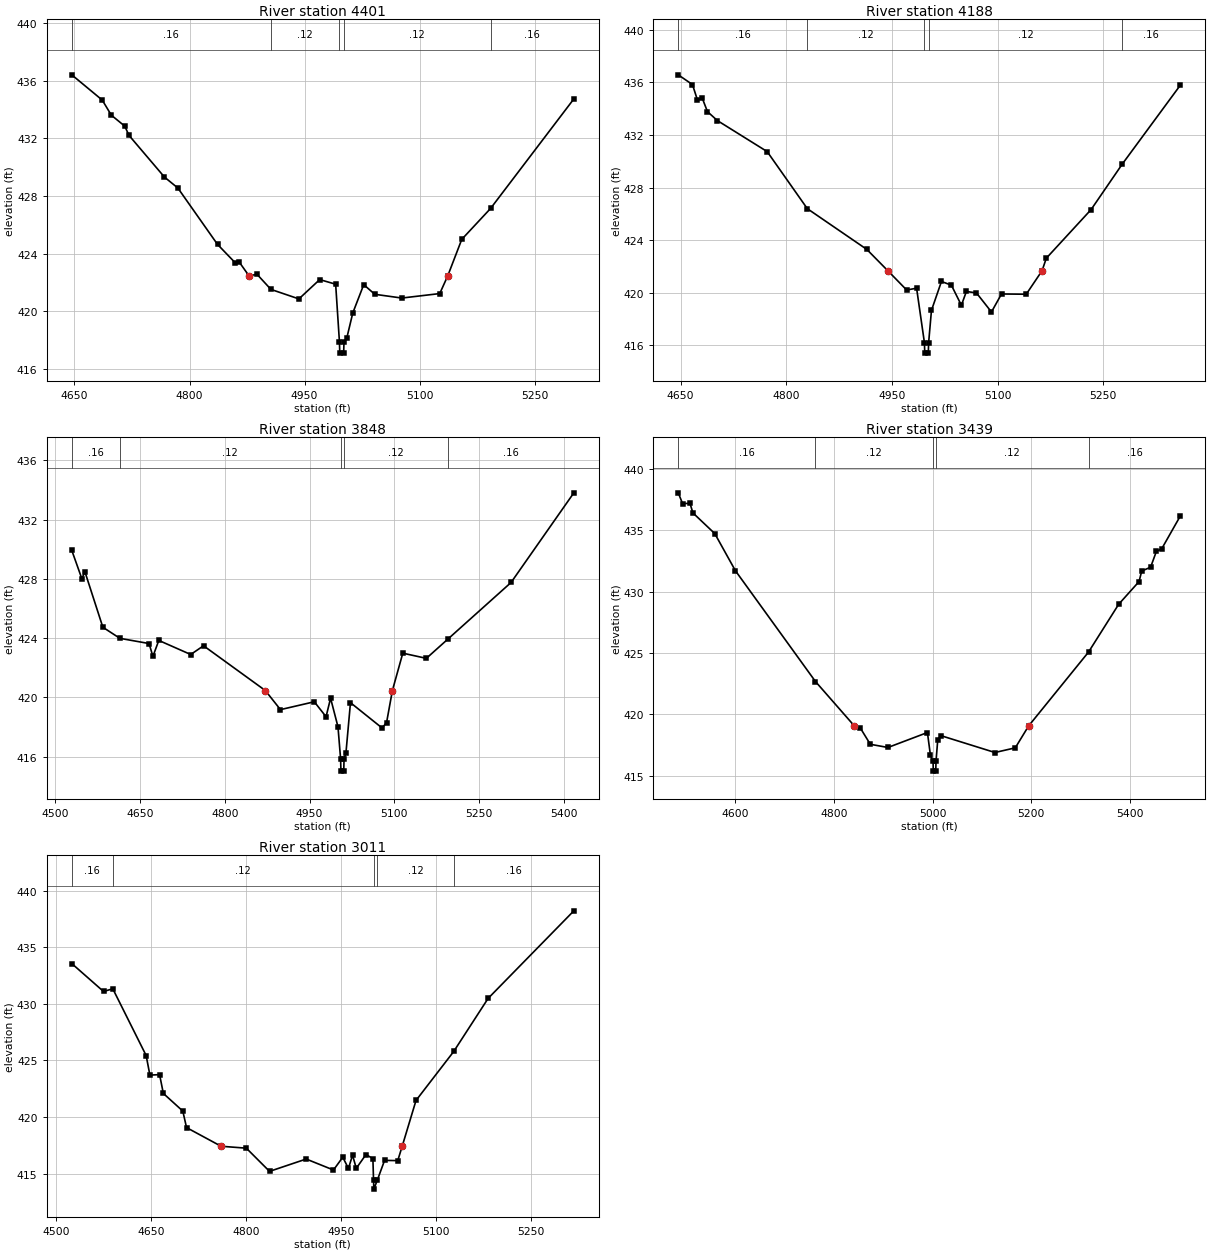
Type RM Length L Ch R = 1,4401,213,213,213
BEGIN DESCRIPTION:
UNT 041 in Running Cr Watershed 4.0
END DESCRIPTION:
XS GIS Cut Line= 3
      2892461.12      7048430.57      2892193.80      7048552.08
      2891914.25      7048780.27
#Sta/Elev= 30
  4646.5  436.40  4686.2  434.65  4698.1  433.60  4715.6  432.84  4721.1  432.20
  4767.3  429.31  4784.8  428.55  4836.5  424.64  4859.5  423.37  4865.0  423.40
  4877.4  422.47  4888.1  422.56  4906.1  421.52  4942.6  420.86  4969.7  422.20
  4990.5  421.88  4995.4  417.90  4995.9  417.10  5000.9  417.10  5001.4  417.90
  5004.9  418.12  5012.8  419.88  5027.1  421.85  5041.5  421.18  5076.7  420.92
  5126.2  421.23  5136.7  422.47  5154.9  424.99  5192.4  427.13  5301.0  434.73
#Mann=5,-1,0
  4646.5    0.16       0  4906.1    0.12       0  4995.4    0.07       0
  5001.4    0.12       0  5192.4    0.16       0
Bank Sta=4877.4,5136.7
Exp/Cntr=0.3,0.1

Type RM Length L Ch R = 1,4188,340,340,340
BEGIN DESCRIPTION:
UNT 041 in Running Cr Watershed 3.0
END DESCRIPTION:
XS GIS Cut Line= 3
      2892308.36      7048159.74      2892009.34      7048453.04
      2891816.52      7048675.17
#Sta/Elev= 30
  4646.6  436.58  4666.8  435.84  4673.9  434.66  4680.9  434.78  4688.1  433.78
  4702.2  433.10  4772.9  430.74  4829.9  426.40  4914.4  423.30  4944.2  421.68
  4971.0  420.21  4985.1  420.35  4996.2  416.21  4996.7  415.41  5001.7  415.41
  5002.2  416.21  5006.2  418.66  5020.4  420.86  5034.5  420.58  5048.7  419.05
  5055.8  420.10  5070.1  419.99  5091.4  418.54  5105.7  419.91  5140.8  419.89
  5163.3  421.68  5169.3  422.63  5232.9  426.33  5277.3  429.80  5359.6  435.79
#Mann=5,-1,0
  4646.6    0.16       0  4829.9    0.12       0  4996.2    0.07       0
  5002.2    0.12       0  5277.3    0.16       0
Bank Sta=4944.2,5163.3
Exp/Cntr=0.3,0.1

Type RM Length L Ch R = 1,3848,409,409,409
BEGIN DESCRIPTION:
Mapping XS e1ad1f2c
END DESCRIPTION:
XS GIS Cut Line= 4
      2892214.63      7048041.67      2891843.10      7048218.75
      2891693.80      7048402.78      2891593.46      7048620.74
#Sta/Elev= 30
  4529.2  429.93  4547.0  428.02  4552.5  428.48  4584.2  424.74  4614.4  423.99
  4666.0  423.64  4672.8  422.77  4683.2  423.85  4739.7  422.90  4762.4  423.49
  4871.7  420.47  4898.5  419.18  4958.4  419.71  4979.2  418.70  4987.2  419.95
  5000.3  418.02  5005.0  415.83  5005.5  415.03  5010.5  415.03  5011.0  415.83
  5014.4  416.26  5022.4  419.65  5078.4  417.94  5086.3  418.31  5096.6  420.47
  5115.0  422.99  5156.7  422.64  5194.8  423.94  5306.6  427.76  5417.7  433.81
#Mann=5,-1,0
  4529.2    0.16       0  4614.4    0.12       0  5005.0    0.07       0
  5011.0    0.12       0  5194.8    0.16       0
Bank Sta=4871.7,5096.6
Exp/Cntr=0.3,0.1

Type RM Length L Ch R = 1,3439,428,428,428
BEGIN DESCRIPTION:
UNT 041 in Running Cr Watershed 2.0
END DESCRIPTION:
XS GIS Cut Line= 3
      2891988.89      7047796.03      2891509.12      7048135.56
      2891337.90      7048529.50
#Sta/Elev= 30
  4484.6  438.07  4493.5  437.18  4508.3  437.22  4514.4  436.43  4558.7  434.74
  4600.5  431.71  4762.7  422.67  4841.4  419.05  4852.9  418.92  4873.8  417.55
  4909.5  417.29  4989.5  418.51  4995.6  416.65  5000.9  416.16  5001.4  415.36
  5006.4  415.36  5006.9  416.16  5010.4  417.90  5016.5  418.26  5126.3  416.88
  5167.5  417.26  5194.6  419.05  5316.0  425.08  5377.1  428.98  5418.3  430.83
  5423.7  431.69  5441.7  432.00  5453.4  433.29  5464.3  433.51  5501.9  436.18
#Mann=5,-1,0
  4484.6    0.16       0  4762.7    0.12       0  5000.9    0.07       0
  5006.9    0.12       0  5316.0    0.16       0
Bank Sta=4841.4,5194.6
Exp/Cntr=0.3,0.1

Type RM Length L Ch R = 1,3011,0,0,0
BEGIN DESCRIPTION:
UNT 041 in Running Cr Watershed 1.0
END DESCRIPTION:
XS GIS Cut Line= 3
      2891624.97      7047775.02      2891225.00      7048025.00
      2891025.01      7048274.98
#Sta/Elev= 30
  4525.2  433.57  4575.3  431.10  4589.9  431.34  4642.5  425.44  4648.4  423.71
  4663.7  423.75  4669.6  422.09  4700.3  420.53  4706.2  419.07  4760.7  417.42
  4800.5  417.25  4837.1  415.20  4894.9  416.29  4937.9  415.32  4952.6  416.45
  4961.5  415.46  4968.0  416.63  4973.9  415.47  4989.2  416.69  5000.1  416.32
  5001.1  414.43  5001.6  413.63  5007.1  414.43  5018.5  416.17  5039.3  416.15
  5046.3  417.42  5068.1  421.47  5127.6  425.80  5181.8  430.49  5317.0  438.23
#Mann=5,-1,0
  4525.2    0.16       0  4589.9    0.12       0  5001.1    0.07       0
  5007.1    0.12       0  5127.6    0.16       0
Bank Sta=4760.7,5046.3
Exp/Cntr=0.3,0.1

Chan Stop Cuts=-1