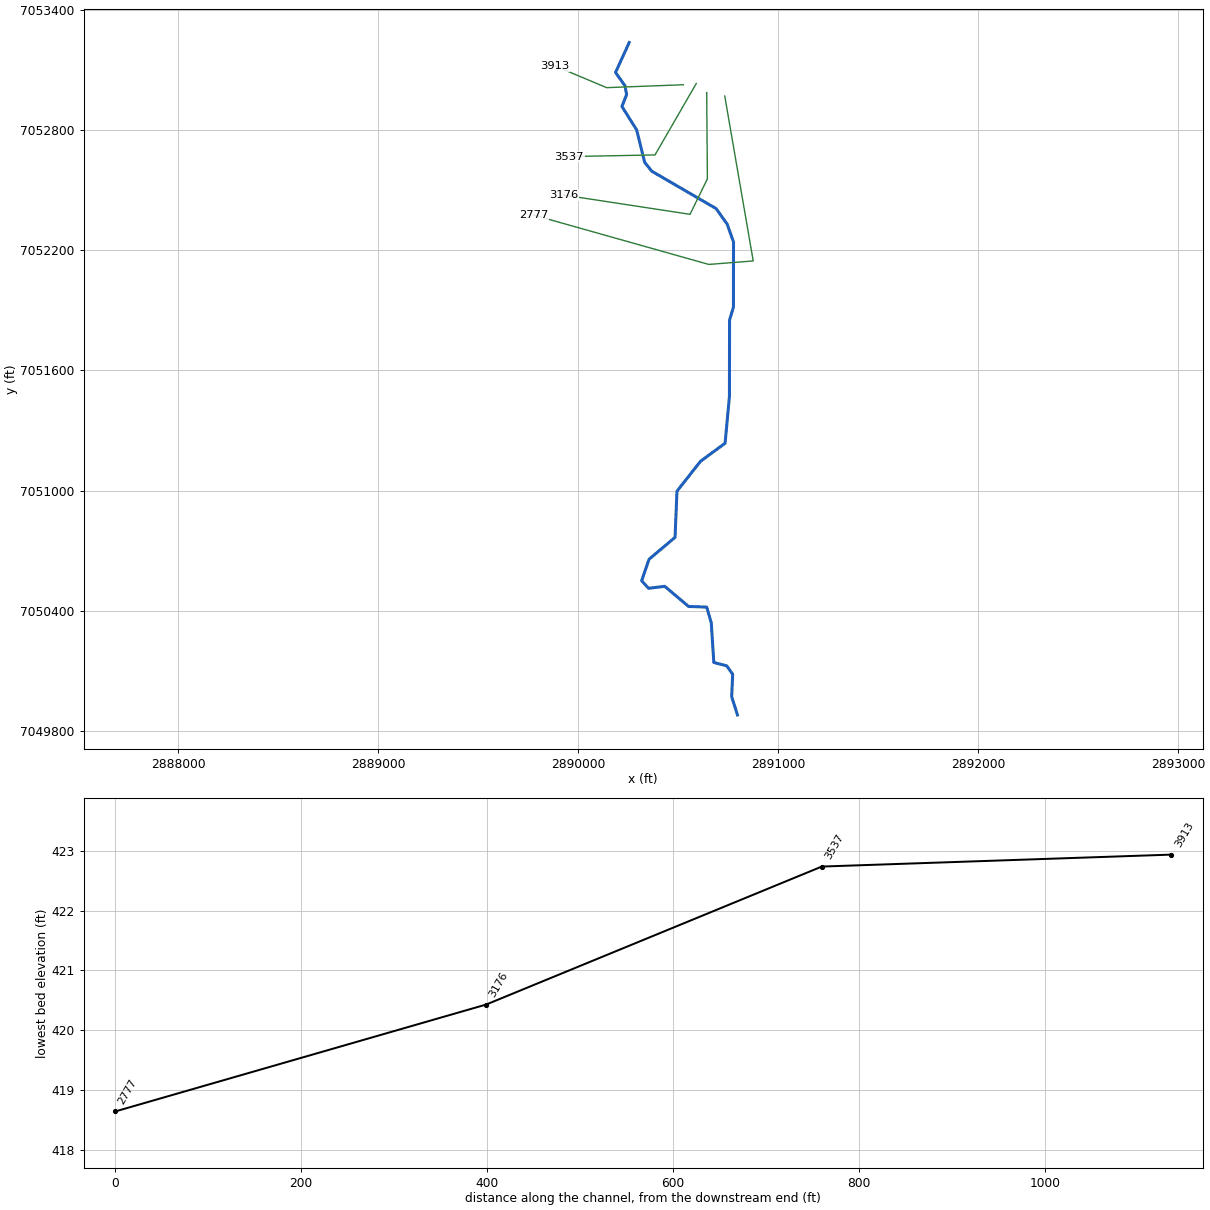
--- UNT 042 in Running Cr Watershed.prj (project) ---

Proj Title=UNT 042 in Running Cr Watershed Base Level Engineering
Current Plan=p01
Default Exp/Contr=0.3,0.1
English Units
Geom File=g01
Flow File=f01
Plan File=p01
BEGIN DESCRIPTION:
UNT 042 in Running Cr Watershed
END DESCRIPTION:

--- UNT 042 in Running Cr Watershed.p01 (plan) ---

Plan Title=Multiple Run
Short Identifier=Multiple
Geom File=g01
Flow File=f01
Subcritical Flow
K Sum by GR= 0
Std Step Tol= 0.01
Critical Tol= 0.01
Num of Std Step Trials= 20
Max Error Tol= 0.3
Flow Tol Ratio= 0.001
Split Flow NTrial= 30
Split Flow Tol= 0.02
Split Flow Ratio= 0.02
Log Output Level= 0
Friction Slope Method= 1
Unsteady Friction Slope Method= 2
Unsteady Bridges Friction Slope Method= 1
Parabolic Critical Depth
Global Vel Dist=  1 , 1 , 1
Global Log Level= 0
CheckData=True
Encroach Param= -1, 0, 0, 0
BEGIN DESCRIPTION:
Multiple Run
END DESCRIPTION:

--- UNT 042 in Running Cr Watershed.f01 (steady flow) ---

Flow Title=Multiple
Number of Profiles=7
Profile Names=10-year,25-year,50-year,1pct_min,100-year,1pct_plu,500-year
River Rch & RM= UNT 042 in Runni,Reach-1,3913
     489     644     766     454     905    1806    1264
Boundary for River Rch & Prof#=UNT 042 in Runni,Reach-1,1
Up Type=0
Dn Type=3
Dn Slope=0.005
Boundary for River Rch & Prof#=UNT 042 in Runni,Reach-1,2
Up Type=0
Dn Type=3
Dn Slope=0.005
Boundary for River Rch & Prof#=UNT 042 in Runni,Reach-1,3
Up Type=0
Dn Type=3
Dn Slope=0.005
Boundary for River Rch & Prof#=UNT 042 in Runni,Reach-1,4
Up Type=0
Dn Type=3
Dn Slope=0.005
Boundary for River Rch & Prof#=UNT 042 in Runni,Reach-1,5
Up Type=0
Dn Type=3
Dn Slope=0.005
Boundary for River Rch & Prof#=UNT 042 in Runni,Reach-1,6
Up Type=0
Dn Type=3
Dn Slope=0.005
Boundary for River Rch & Prof#=UNT 042 in Runni,Reach-1,7
Up Type=0
Dn Type=3
Dn Slope=0.005

--- UNT 042 in Running Cr Watershed.g01 (geometry) ---

Geom Title=Existing Conditions

River Reach=UNT 042 in Runni,Reach-1
Reach XY= 30
      2890254.24      7053235.90      2890185.84      7053086.20
      2890233.26      7053019.65      2890241.16      7052976.00
      2890217.87      7052916.67      2890291.72      7052799.11
      2890331.33      7052638.23      2890367.17      7052593.55
      2890688.91      7052407.03      2890743.76      7052329.97
      2890775.79      7052240.79      2890775.47      7051915.76
      2890756.00      7051850.54      2890755.43      7051470.17
      2890733.63      7051236.35      2890610.92      7051146.42
      2890493.04      7050997.05      2890483.42      7050766.83
      2890353.36      7050657.34      2890316.33      7050549.95
      2890351.05      7050512.58      2890431.84      7050522.35
      2890551.30      7050421.85      2890641.68      7050418.80
      2890664.48      7050340.73      2890677.30      7050142.43
      2890741.63      7050125.88      2890771.69      7050083.88
      2890766.69      7049971.35      2890795.59      7049880.71

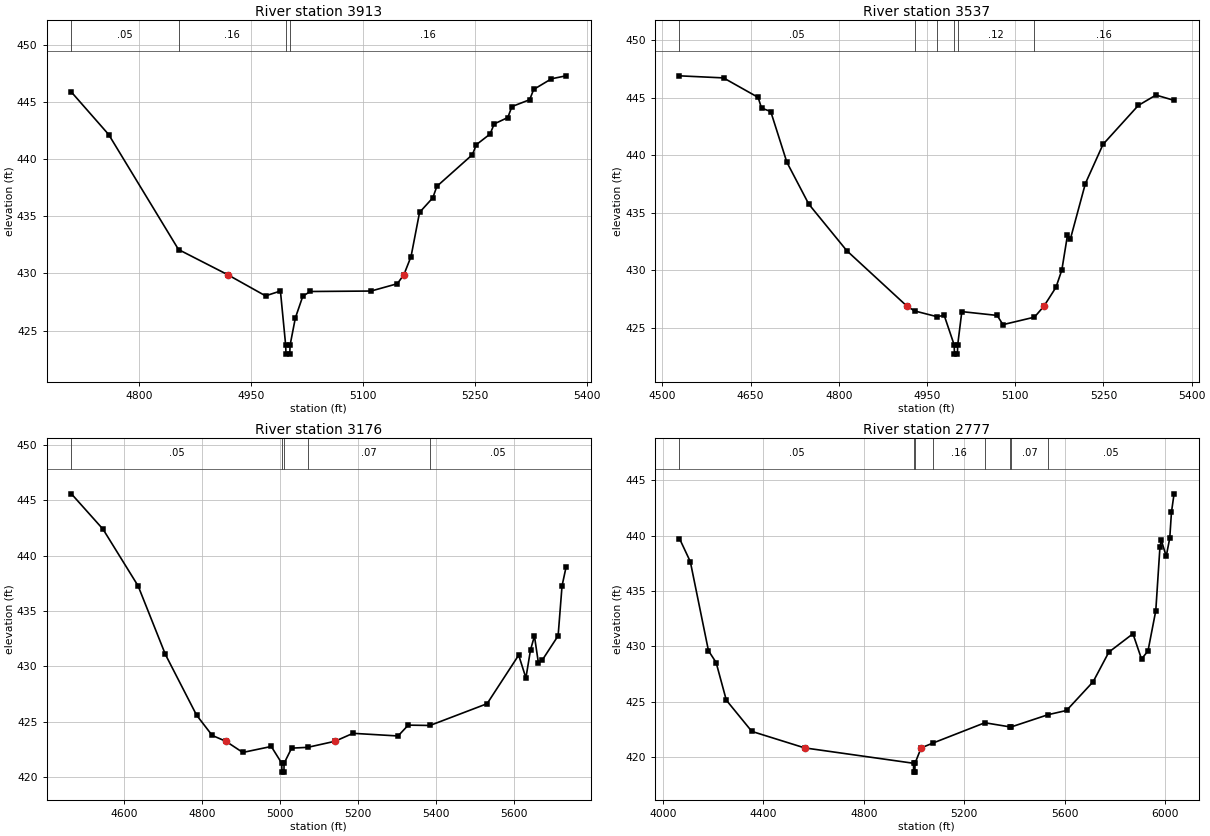
Type RM Length L Ch R = 1,3913,376,376,376
BEGIN DESCRIPTION:
UNT 042 in Running Cr Watershed 4.0
END DESCRIPTION:
XS GIS Cut Line= 3
      2890524.98      7053025.00      2890141.71      7053010.42
      2889883.96      7053118.38
#Sta/Elev= 30
  4709.1  445.87  4759.1  442.15  4852.7  432.09  4918.6  429.89  4969.3  428.04
  4989.3  428.46  4996.3  423.74  4996.8  422.94  5001.8  422.94  5002.3  423.74
  5009.3  426.10  5019.3  428.01  5029.3  428.42  5110.8  428.46  5146.0  429.10
  5154.8  429.89  5164.4  431.48  5175.8  435.34  5193.6  436.62  5199.0  437.62
  5246.6  440.39  5252.0  441.27  5270.4  442.20  5275.8  443.08  5294.1  443.64
  5299.6  444.60  5323.4  445.20  5328.8  446.10  5352.6  447.03  5372.1  447.29
#Mann=4,-1,0
  4709.1    0.05       0  4852.7    0.16       0  4996.3    0.07       0
  5002.3    0.16       0
Bank Sta=4918.6,5154.8
Exp/Cntr=0.3,0.1

Type RM Length L Ch R = 1,3537,361,361,361
BEGIN DESCRIPTION:
UNT 042 in Running Cr Watershed 3.0
END DESCRIPTION:
XS GIS Cut Line= 3
      2890589.61      7053031.21      2890383.23      7052674.76
      2889954.19      7052666.67
#Sta/Elev= 30
  4529.1  446.90  4604.0  446.72  4662.8  445.03  4668.6  444.10  4684.3  443.80
  4711.7  439.40  4749.0  435.76  4813.6  431.72  4916.0  426.90  4928.9  426.49
  4967.1  425.99  4979.2  426.11  4996.2  423.54  4996.7  422.74  5001.7  422.74
  5002.2  423.54  5009.2  426.43  5069.2  426.10  5079.2  425.30  5132.7  425.95
  5148.8  426.90  5169.3  428.54  5179.3  430.05  5188.8  433.05  5193.8  432.73
  5219.3  437.55  5249.3  440.95  5309.3  444.33  5339.3  445.23  5370.1  444.77
#Mann=6,-1,0
  4529.1    0.05       0  4928.9    0.07       0  4967.1    0.12       0
  4996.2    0.07       0  5002.2    0.12       0  5132.7    0.16       0
Bank Sta=4916,5148.8
Exp/Cntr=0.3,0.1

Type RM Length L Ch R = 1,3176,399,399,399
BEGIN DESCRIPTION:
UNT 042 in Running Cr Watershed 2.0
END DESCRIPTION:
XS GIS Cut Line= 4
      2890641.71      7052986.07      2890645.18      7052555.55
      2890558.38      7052378.47      2889925.04      7052474.99
#Sta/Elev= 30
  4464.3  445.60  4545.4  442.40  4635.4  437.27  4705.4  431.07  4785.4  425.58
  4825.4  423.75  4860.5  423.22  4903.8  422.21  4976.9  422.75  5003.8  421.23
  5004.3  420.43  5009.3  420.43  5009.8  421.23  5029.1  422.60  5070.0  422.67
  5140.2  423.22  5186.5  423.94  5302.1  423.70  5328.1  424.68  5383.9  424.65
  5530.4  426.62  5611.4  431.01  5629.9  428.95  5641.7  431.48  5651.8  432.74
  5661.9  430.32  5672.0  430.57  5712.5  432.76  5722.6  437.28  5732.7  438.94
#Mann=5,-1,0
  4464.3    0.05       0  5003.8    0.03       0  5009.8    0.05       0
  5070.0    0.07       0  5383.9    0.05       0
Bank Sta=4860.5,5140.2
Exp/Cntr=0.3,0.1

Type RM Length L Ch R = 1,2777,0,0,0
BEGIN DESCRIPTION:
UNT 042 in Running Cr Watershed 1.0
END DESCRIPTION:
XS GIS Cut Line= 4
      2890731.99      7052968.75      2890874.35      7052145.83
      2890652.13      7052128.47      2889774.96      7052375.01
#Sta/Elev= 30
  4065.9  439.74  4109.1  437.65  4181.3  429.61  4211.8  428.54  4252.4  425.14
  4353.9  422.32  4564.2  420.83  4997.7  419.44  4998.2  418.64  5003.2  418.64
  5003.7  419.44  5028.1  420.83  5076.6  421.28  5281.7  423.10  5383.5  422.72
  5385.0  422.71  5533.7  423.83  5607.0  424.21  5713.0  426.81  5775.4  429.48
  5871.4  431.14  5905.5  428.86  5931.2  429.58  5962.3  433.22  5978.8  438.94
  5984.0  439.60  6003.9  438.14  6018.0  439.79  6024.7  442.12  6035.1  443.78
#Mann=8,-1,0
  4065.9    0.05       0  4997.7    0.03       0  5003.7    0.05       0
  5076.6    0.16       0  5281.7    0.05       0  5383.5    0.16       0
  5385.0    0.07       0  5533.7    0.05       0
Bank Sta=4564.2,5028.1
Exp/Cntr=0.3,0.1

Chan Stop Cuts=-1