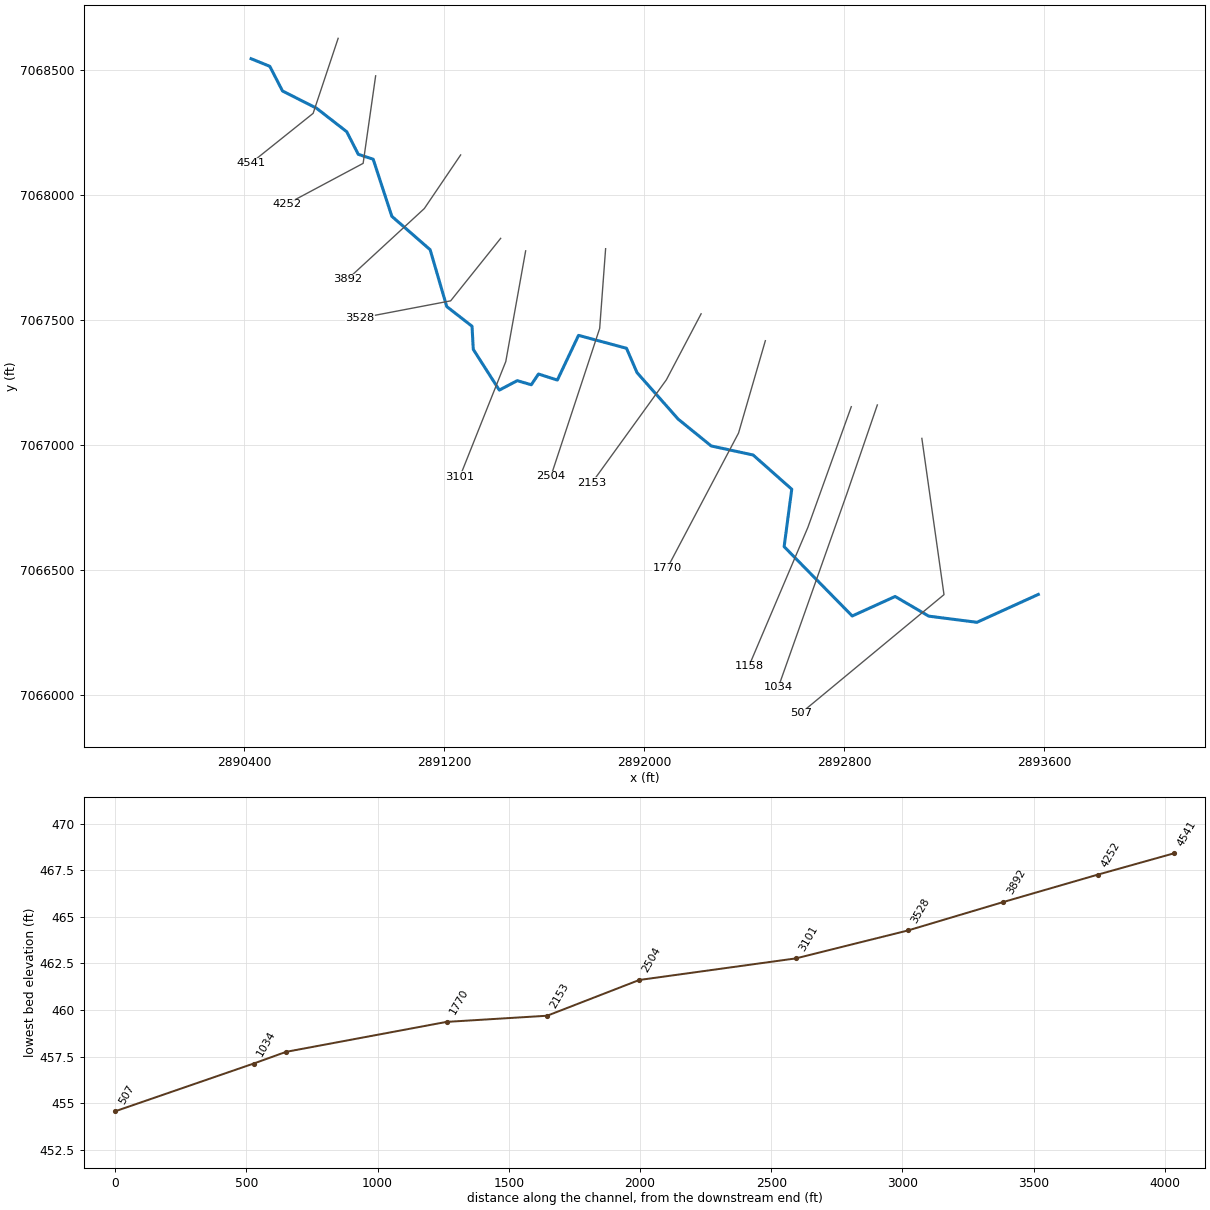
--- UNT 043 in Running Cr Watershed.prj (project) ---

Proj Title=UNT 043 in Running Cr Watershed Base Level Engineering
Current Plan=p01
Default Exp/Contr=0.3,0.1
English Units
Geom File=g01
Flow File=f01
Plan File=p01
BEGIN DESCRIPTION:
UNT 043 in Running Cr Watershed
END DESCRIPTION:

--- UNT 043 in Running Cr Watershed.p01 (plan) ---

Plan Title=Multiple Run
Short Identifier=Multiple
Geom File=g01
Flow File=f01
Subcritical Flow
K Sum by GR= 0
Std Step Tol= 0.01
Critical Tol= 0.01
Num of Std Step Trials= 20
Max Error Tol= 0.3
Flow Tol Ratio= 0.001
Split Flow NTrial= 30
Split Flow Tol= 0.02
Split Flow Ratio= 0.02
Log Output Level= 0
Friction Slope Method= 1
Unsteady Friction Slope Method= 2
Unsteady Bridges Friction Slope Method= 1
Parabolic Critical Depth
Global Vel Dist=  1 , 1 , 1
Global Log Level= 0
CheckData=True
Encroach Param= -1, 0, 0, 0
BEGIN DESCRIPTION:
Multiple Run
END DESCRIPTION:

--- UNT 043 in Running Cr Watershed.f01 (steady flow) ---

Flow Title=Multiple
Number of Profiles=7
Profile Names=10-year,25-year,50-year,1pct_min,100-year,1pct_plu,500-year
River Rch & RM= UNT 043 in Runni,Reach-1,4541
     832    1128    1371     826    1648    3287    2375
River Rch & RM= UNT 043 in Runni,Reach-1,2504
     858    1162    1411     849    1694    3380    2437
Boundary for River Rch & Prof#=UNT 043 in Runni,Reach-1,1
Up Type=0
Dn Type=3
Dn Slope=0.005
Boundary for River Rch & Prof#=UNT 043 in Runni,Reach-1,2
Up Type=0
Dn Type=3
Dn Slope=0.005
Boundary for River Rch & Prof#=UNT 043 in Runni,Reach-1,3
Up Type=0
Dn Type=3
Dn Slope=0.005
Boundary for River Rch & Prof#=UNT 043 in Runni,Reach-1,4
Up Type=0
Dn Type=3
Dn Slope=0.005
Boundary for River Rch & Prof#=UNT 043 in Runni,Reach-1,5
Up Type=0
Dn Type=3
Dn Slope=0.005
Boundary for River Rch & Prof#=UNT 043 in Runni,Reach-1,6
Up Type=0
Dn Type=3
Dn Slope=0.005
Boundary for River Rch & Prof#=UNT 043 in Runni,Reach-1,7
Up Type=0
Dn Type=3
Dn Slope=0.005

--- UNT 043 in Running Cr Watershed.g01 (geometry) ---

Geom Title=Existing Conditions

River Reach=UNT 043 in Runni,Reach-1
Reach XY= 30
      2890426.79      7068543.54      2890501.72      7068513.07
      2890552.47      7068414.48      2890688.40      7068345.66
      2890809.43      7068251.50      2890855.51      7068161.15
      2890915.12      7068141.56      2890989.78      7067913.15
      2891142.96      7067779.66      2891209.39      7067552.21
      2891310.54      7067473.43      2891315.59      7067380.71
      2891419.61      7067217.99      2891491.39      7067255.82
      2891547.64      7067239.37      2891576.39      7067282.39
      2891651.77      7067258.13      2891736.53      7067436.95
      2891928.39      7067385.29      2891970.52      7067287.90
      2892135.35      7067101.71      2892267.29      7066994.60
      2892434.81      7066958.47      2892589.34      7066821.62
      2892558.92      7066591.83      2892831.22      7066314.56
      2893002.91      7066392.52      2893137.22      7066313.93
      2893329.98      7066289.26      2893575.59      7066400.71

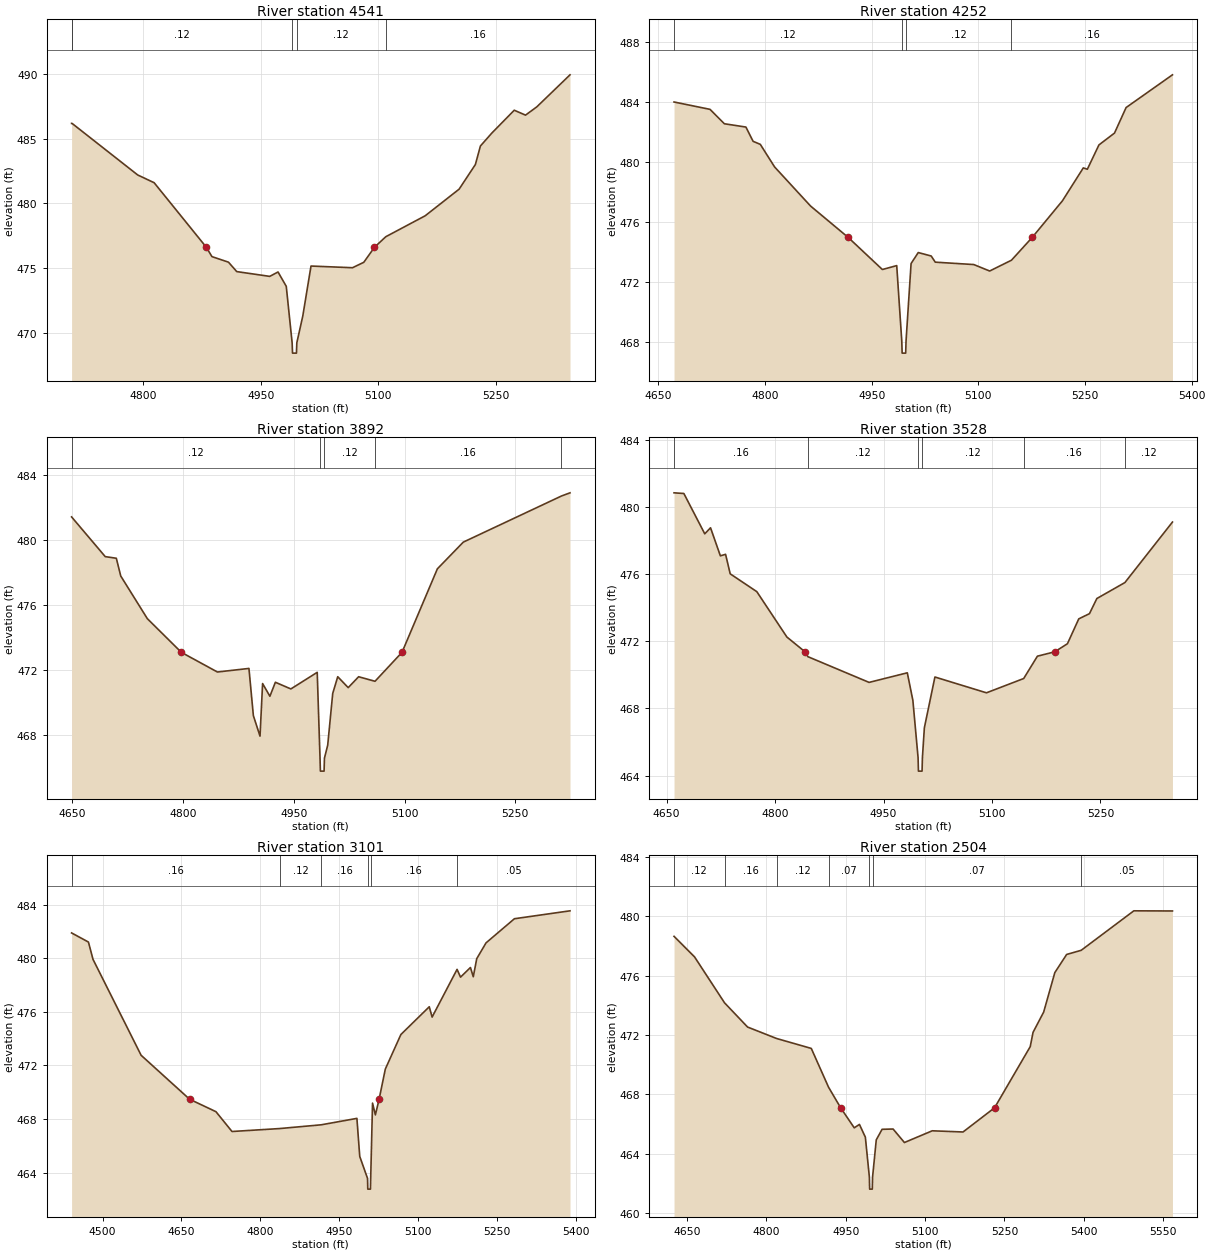
Type RM Length L Ch R = 1,4541,289,289,289
BEGIN DESCRIPTION:
UNT 043 in Running Cr Watershed 11.0
END DESCRIPTION:
XS GIS Cut Line= 3
      2890775.01      7068625.04      2890675.00      7068325.00
      2890425.02      7068125.01
#Sta/Elev= 30
  4708.3  486.19  4708.9  486.19  4792.7  482.20  4813.7  481.60  4880.4  476.60
  4887.5  475.88  4908.6  475.45  4919.2  474.72  4961.3  474.35  4971.9  474.69
  4982.4  473.58  4989.9  469.21  4990.4  468.41  4995.4  468.41  4995.9  469.21
  5003.5  471.28  5014.0  475.15  5067.0  475.02  5081.4  475.44  5095.0  476.60
  5109.5  477.42  5159.8  479.04  5203.1  481.10  5223.9  483.01  5230.3  484.44
  5244.7  485.43  5273.5  487.21  5287.9  486.83  5302.3  487.47  5344.7  489.95
#Mann=5,-1,0
  4708.3    0.16       0  4708.9    0.12       0  4989.9    0.07       0
  4995.9    0.12       0  5109.5    0.16       0
Bank Sta=4880.4,5095
Exp/Cntr=0.3,0.1

Type RM Length L Ch R = 1,4252,360,360,360
BEGIN DESCRIPTION:
UNT 043 in Running Cr Watershed 10.0
END DESCRIPTION:
XS GIS Cut Line= 3
      2890925.01      7068475.05      2890875.00      7068125.00
      2890568.51      7067961.46
#Sta/Elev= 30
  4672.0  484.00  4722.6  483.51  4742.8  482.55  4773.1  482.33  4783.2  481.38
  4793.3  481.18  4813.5  479.67  4864.0  477.07  4916.9  474.98  4965.0  472.84
  4985.2  473.10  4992.3  468.07  4992.8  467.27  4997.8  467.27  4998.3  468.07
  5005.4  473.24  5015.5  473.97  5033.7  473.74  5039.4  473.33  5093.6  473.17
  5115.9  472.74  5146.6  473.46  5175.8  474.98  5218.3  477.42  5247.6  479.61
  5253.3  479.52  5269.6  481.14  5291.5  481.93  5307.8  483.63  5373.0  485.81
#Mann=4,-1,0
  4672.0    0.12       0  4992.3    0.07       0  4998.3    0.12       0
  5146.6    0.16       0
Bank Sta=4916.9,5175.8
Exp/Cntr=0.3,0.1

Type RM Length L Ch R = 1,3892,364,364,364
BEGIN DESCRIPTION:
UNT 043 in Running Cr Watershed 9.0
END DESCRIPTION:
XS GIS Cut Line= 3
      2891265.00      7068158.62      2891119.69      7067944.15
      2890813.60      7067662.08
#Sta/Elev= 30
  4648.9  481.42  4694.5  478.98  4709.5  478.88  4715.5  477.79  4751.5  475.17
  4797.6  473.10  4846.5  471.89  4889.2  472.11  4895.2  469.21  4904.2  467.95
  4907.7  471.18  4917.6  470.40  4925.0  471.26  4946.0  470.85  4981.7  471.87
  4985.5  466.60  4986.0  465.80  4991.0  465.80  4991.5  466.60  4995.9  467.39
  5002.7  470.57  5009.5  471.60  5023.7  470.93  5037.8  471.60  5060.0  471.32
  5096.6  473.10  5144.5  478.23  5179.6  479.87  5312.4  482.70  5324.2  482.90
#Mann=5,-1,0
  4648.9    0.12       0  4985.5    0.07       0  4991.5    0.12       0
  5060.0    0.16       0  5312.4    0.12       0
Bank Sta=4797.6,5096.6
Exp/Cntr=0.3,0.1

Type RM Length L Ch R = 1,3528,427,427,427
BEGIN DESCRIPTION:
UNT 043 in Running Cr Watershed 8.0
END DESCRIPTION:
XS GIS Cut Line= 3
      2891425.02      7067825.03      2891225.00      7067575.00
      2890862.23      7067505.83
#Sta/Elev= 30
  4660.2  480.83  4673.8  480.79  4702.7  478.39  4710.7  478.75  4724.3  477.08
  4731.5  477.17  4737.9  476.01  4774.7  474.95  4816.3  472.25  4841.4  471.37
  4845.4  471.08  4930.0  469.55  4982.9  470.12  4990.6  468.48  4997.8  465.07
  4998.3  464.27  5003.3  464.27  5003.8  465.07  5006.5  466.85  5021.1  469.87
  5092.4  468.93  5143.9  469.78  5162.9  471.11  5186.9  471.37  5204.4  471.85
  5220.1  473.33  5234.9  473.64  5245.1  474.54  5283.9  475.49  5349.7  479.09
#Mann=6,-1,0
  4660.2    0.16       0  4845.4    0.12       0  4997.8    0.07       0
  5003.8    0.12       0  5143.9    0.16       0  5283.9    0.12       0
Bank Sta=4841.4,5186.9
Exp/Cntr=0.3,0.1

Type RM Length L Ch R = 1,3101,597,597,597
BEGIN DESCRIPTION:
UNT 043 in Running Cr Watershed 7.0
END DESCRIPTION:
XS GIS Cut Line= 3
      2891525.00      7067775.03      2891445.55      7067332.22
      2891261.52      7066870.42
#Sta/Elev= 30
  4441.2  481.89  4473.2  481.21  4481.9  479.92  4573.3  472.76  4665.4  469.48
  4715.5  468.55  4746.0  467.07  4836.4  467.29  4915.5  467.57  4983.3  468.05
  4988.7  465.21  5003.5  463.57  5004.0  462.77  5009.0  462.77  5009.5  463.57
  5013.0  469.19  5018.4  468.31  5025.5  469.48  5037.3  471.73  5066.9  474.31
  5120.8  476.38  5126.2  475.61  5173.6  479.17  5180.2  478.59  5199.0  479.31
  5204.4  478.62  5211.0  479.97  5228.7  481.15  5282.6  482.95  5388.2  483.54
#Mann=6,-1,0
  4441.2    0.16       0  4836.4    0.12       0  4915.5    0.16       0
  5003.5    0.07       0  5009.5    0.16       0  5173.6    0.05       0
Bank Sta=4665.4,5025.5
Exp/Cntr=0.3,0.1

Type RM Length L Ch R = 1,2504,351,351,351
BEGIN DESCRIPTION:
UNT 043 in Running Cr Watershed 6.0
END DESCRIPTION:
XS GIS Cut Line= 3
      2891844.85      7067783.64      2891821.13      7067464.99
      2891626.10      7066873.87
#Sta/Elev= 30
  4625.5  478.64  4664.2  477.26  4721.0  474.16  4764.5  472.53  4819.2  471.76
  4884.9  471.09  4917.5  468.48  4940.4  467.09  4966.1  465.74  4975.9  465.97
  4987.1  465.11  4994.7  462.41  4995.2  461.61  5000.2  461.61  5000.7  462.41
  5007.7  464.93  5018.7  465.64  5039.5  465.66  5060.9  464.75  5113.5  465.54
  5171.7  465.46  5231.3  467.09  5298.7  471.21  5304.0  472.17  5324.1  473.54
  5345.2  476.20  5367.5  477.42  5395.0  477.70  5494.5  480.36  5567.5  480.35
#Mann=7,-1,0
  4625.5    0.12       0  4721.0    0.16       0  4819.2    0.12       0
  4917.5    0.07       0  4994.7    0.07       0  5000.7    0.07       0
  5395.0    0.05       0
Bank Sta=4940.4,5231.3
Exp/Cntr=0.3,0.1

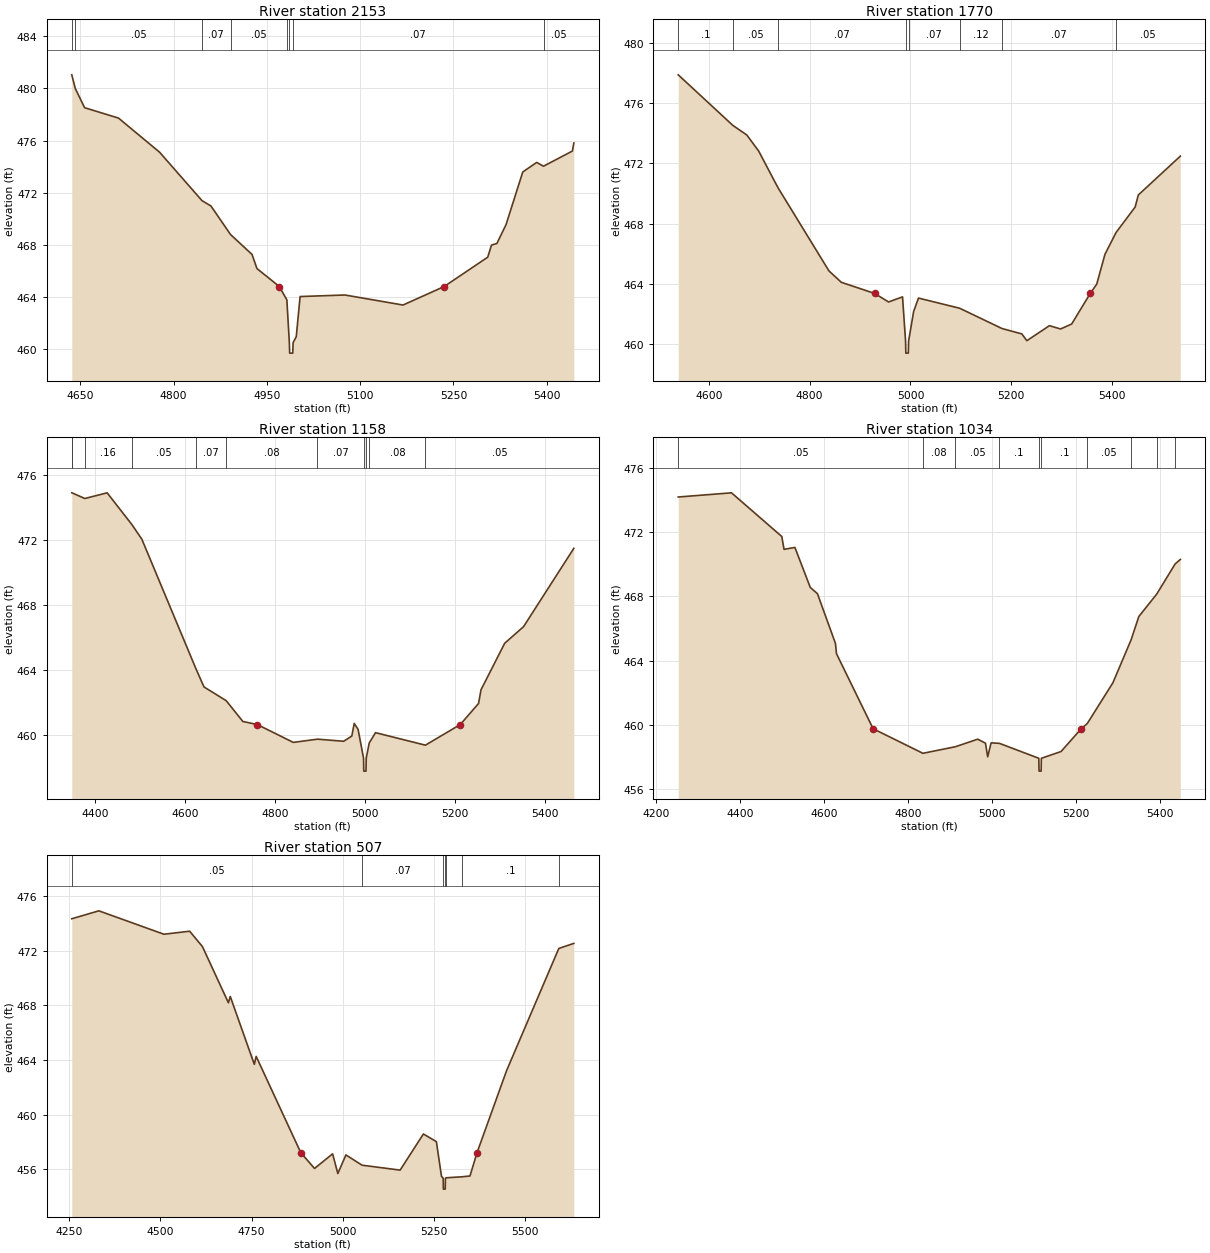
Type RM Length L Ch R = 1,2153,383,383,383
BEGIN DESCRIPTION:
UNT 043 in Running Cr Watershed 5.0
END DESCRIPTION:
XS GIS Cut Line= 3
      2892226.80      7067523.19      2892087.91      7067259.30
      2891789.66      7066846.61
#Sta/Elev= 30
  4636.2  481.04  4641.9  479.99  4656.8  478.52  4711.4  477.72  4777.5  475.10
  4845.6  471.39  4860.0  470.98  4891.5  468.79  4926.1  467.26  4934.0  466.18
  4969.9  464.80  4982.1  463.78  4986.1  460.49  4986.6  459.69  4991.6  459.69
  4992.1  460.49  4997.2  460.95  5003.4  464.03  5075.4  464.15  5168.9  463.38
  5235.1  464.80  5305.1  467.05  5311.2  467.98  5319.8  468.10  5334.5  469.54
  5361.5  473.59  5383.9  474.32  5394.8  474.03  5441.2  475.19  5443.6  475.81
#Mann=8,-1,0
  4636.2     0.1       0  4641.9    0.05       0  4845.6    0.07       0
  4891.5    0.05       0  4982.1    0.07       0  4986.1    0.07       0
  4992.1    0.07       0  5394.8    0.05       0
Bank Sta=4969.9,5235.1
Exp/Cntr=0.3,0.1

Type RM Length L Ch R = 1,1770,612,612,612
BEGIN DESCRIPTION:
UNT 043 in Running Cr Watershed 4.0
END DESCRIPTION:
XS GIS Cut Line= 3
      2892483.75      7067415.57      2892376.56      7067046.32
      2892091.38      7066505.83
#Sta/Elev= 30
  4539.5  477.91  4647.8  474.54  4675.5  473.90  4699.0  472.83  4737.4  470.38
  4838.4  464.84  4862.9  464.08  4928.9  463.34  4956.6  462.77  4984.3  463.11
  4990.3  460.16  4990.8  459.36  4995.8  459.36  4996.3  460.16  5006.3  462.14
  5015.9  463.03  5097.7  462.35  5181.5  461.00  5220.9  460.64  5230.8  460.19
  5275.6  461.19  5297.6  460.97  5319.7  461.30  5356.5  463.34  5369.4  463.96
  5385.7  465.95  5407.7  467.40  5445.6  469.10  5451.8  469.90  5535.1  472.49
#Mann=8,-1,0
  4539.5     0.1       0  4647.8    0.05       0  4737.4    0.07       0
  4990.3    0.07       0  4996.3    0.07       0  5097.7    0.12       0
  5181.5    0.07       0  5407.7    0.05       0
Bank Sta=4928.9,5356.5
Exp/Cntr=0.3,0.1

Type RM Length L Ch R = 1,1158,124,124,124
BEGIN DESCRIPTION:
UNT 043 in Running Cr Watershed 3.0
END DESCRIPTION:
XS GIS Cut Line= 3
      2892827.49      7067151.67      2892653.88      7066669.02
      2892417.76      7066113.44
#Sta/Elev= 30
  4348.2  474.90  4349.5  474.89  4377.2  474.55  4426.9  474.90  4482.0  472.94
  4504.1  472.04  4624.5  464.05  4642.2  462.94  4691.7  462.09  4728.7  460.81
  4760.9  460.62  4840.9  459.52  4894.5  459.72  4952.8  459.59  4971.0  459.91
  4976.4  460.69  4985.0  460.32  4997.1  458.55  4997.6  457.75  5002.6  457.75
  5003.1  458.55  5009.7  459.48  5023.7  460.12  5134.7  459.35  5212.2  460.62
  5252.9  461.92  5258.3  462.76  5311.0  465.63  5352.9  466.65  5464.8  471.48
#Mann=11,-1,0
  4348.2    0.05       0  4349.5     0.1       0  4377.2    0.16       0
  4482.0    0.05       0  4624.5    0.07       0  4691.7    0.08       0
  4894.5    0.07       0  4997.1    0.07       0  5003.1    0.07       0
  5009.7    0.08       0  5134.7    0.05       0
Bank Sta=4760.9,5212.2
Exp/Cntr=0.3,0.1

Type RM Length L Ch R = 1,1034,527,527,527
BEGIN DESCRIPTION:
UNT 043 in Running Cr Watershed 2.0
END DESCRIPTION:
XS GIS Cut Line= 3
      2892931.67      7067158.65      2892810.13      7066804.44
      2892535.84      7066030.17
#Sta/Elev= 30
  4251.8  474.19  4378.7  474.45  4498.5  471.73  4503.8  470.93  4529.7  471.05
  4566.3  468.56  4583.4  468.17  4626.3  465.07  4628.8  464.43  4716.0  459.76
  4834.6  458.23  4912.1  458.64  4965.2  459.11  4983.6  458.86  4988.9  458.01
  4997.0  458.88  5016.7  458.85  5110.7  457.92  5111.2  457.12  5116.2  457.12
  5116.7  457.92  5163.6  458.34  5211.7  459.76  5226.0  460.08  5287.1  462.62
  5330.7  465.31  5348.9  466.75  5391.4  468.14  5435.3  470.02  5447.7  470.30
#Mann=10,-1,0
  4251.8    0.05       0  4834.6    0.08       0  4912.1    0.05       0
  5016.7     0.1       0  5110.7    0.04       0  5116.7     0.1       0
  5226.0    0.05       0  5330.7     0.1       0  5391.4    0.05       0
  5435.3    0.08       0
Bank Sta=4716,5211.7
Exp/Cntr=0.3,0.1

Type RM Length L Ch R = 1,507,0,0,0
BEGIN DESCRIPTION:
UNT 043 in Running Cr Watershed 1.0
END DESCRIPTION:
XS GIS Cut Line= 3
      2893109.79      7067024.90      2893198.32      7066399.93
      2892625.00      7065925.00
#Sta/Elev= 30
  4257.3  474.32  4331.5  474.90  4509.7  473.19  4580.4  473.41  4615.5  472.28
  4686.5  468.18  4691.6  468.64  4757.5  463.68  4762.6  464.26  4884.7  457.23
  4922.5  456.07  4972.0  457.14  4986.3  455.70  5008.5  457.06  5052.6  456.31
  5157.0  455.95  5220.8  458.59  5256.4  458.03  5270.3  455.50  5275.0  455.36
  5275.5  454.56  5280.6  454.56  5281.1  455.36  5283.5  455.39  5326.1  455.46
  5348.4  455.52  5367.8  457.23  5448.7  463.22  5591.8  472.15  5633.0  472.52
#Mann=7,-1,0
  4257.3    0.05       0  5052.6    0.07       0  5275.0    0.03       0
  5281.1    0.07       0  5283.5    0.05       0  5326.1     0.1       0
  5591.8    0.05       0
Bank Sta=4884.7,5367.8
Exp/Cntr=0.3,0.1

Chan Stop Cuts=-1