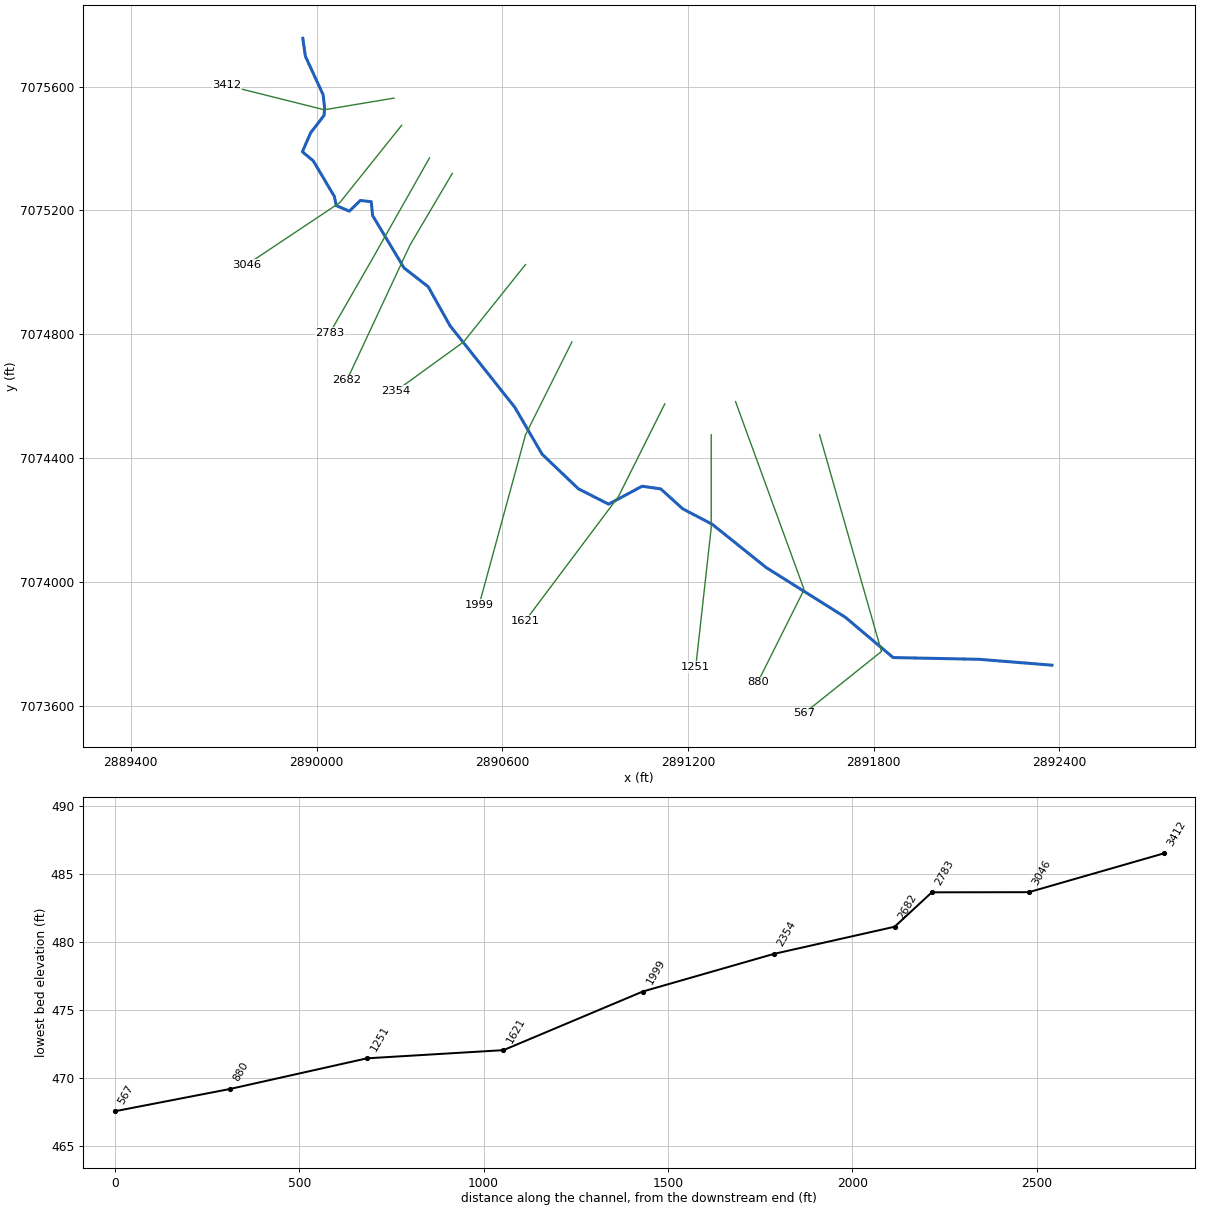
--- UNT 044 in Running Cr Watershed.prj (project) ---

Proj Title=UNT 044 in Running Cr Watershed Base Level Engineering
Current Plan=p01
Default Exp/Contr=0.3,0.1
English Units
Geom File=g01
Flow File=f01
Plan File=p01
BEGIN DESCRIPTION:
UNT 044 in Running Cr Watershed
END DESCRIPTION:

--- UNT 044 in Running Cr Watershed.p01 (plan) ---

Plan Title=Multiple Run
Short Identifier=Multiple
Geom File=g01
Flow File=f01
Subcritical Flow
K Sum by GR= 0
Std Step Tol= 0.01
Critical Tol= 0.01
Num of Std Step Trials= 20
Max Error Tol= 0.3
Flow Tol Ratio= 0.001
Split Flow NTrial= 30
Split Flow Tol= 0.02
Split Flow Ratio= 0.02
Log Output Level= 0
Friction Slope Method= 1
Unsteady Friction Slope Method= 2
Unsteady Bridges Friction Slope Method= 1
Parabolic Critical Depth
Global Vel Dist=  1 , 1 , 1
Global Log Level= 0
CheckData=True
Encroach Param= -1, 0, 0, 0
BEGIN DESCRIPTION:
Multiple Run
END DESCRIPTION:

--- UNT 044 in Running Cr Watershed.f01 (steady flow) ---

Flow Title=Multiple
Number of Profiles=7
Profile Names=10-year,25-year,50-year,1pct_min,100-year,1pct_plu,500-year
River Rch & RM= UNT 044 in Runni,Reach-1,3412
     649     865    1039     620    1237    2468    1747
River Rch & RM= UNT 044 in Runni,Reach-1,1621
     889    1207    1468     886    1767    3526    2554
Boundary for River Rch & Prof#=UNT 044 in Runni,Reach-1,1
Up Type=0
Dn Type=3
Dn Slope=0.005
Boundary for River Rch & Prof#=UNT 044 in Runni,Reach-1,2
Up Type=0
Dn Type=3
Dn Slope=0.005
Boundary for River Rch & Prof#=UNT 044 in Runni,Reach-1,3
Up Type=0
Dn Type=3
Dn Slope=0.005
Boundary for River Rch & Prof#=UNT 044 in Runni,Reach-1,4
Up Type=0
Dn Type=3
Dn Slope=0.005
Boundary for River Rch & Prof#=UNT 044 in Runni,Reach-1,5
Up Type=0
Dn Type=3
Dn Slope=0.005
Boundary for River Rch & Prof#=UNT 044 in Runni,Reach-1,6
Up Type=0
Dn Type=3
Dn Slope=0.005
Boundary for River Rch & Prof#=UNT 044 in Runni,Reach-1,7
Up Type=0
Dn Type=3
Dn Slope=0.005

--- UNT 044 in Running Cr Watershed.g01 (geometry) ---

Geom Title=Existing Conditions

River Reach=UNT 044 in Runni,Reach-1
Reach XY= 30
      2889955.55      7075755.80      2889963.84      7075697.73
      2890021.21      7075573.49      2890026.10      7075530.74
      2890023.92      7075506.56      2889980.80      7075450.47
      2889954.14      7075389.34      2889989.26      7075360.07
      2890057.54      7075244.96      2890063.40      7075215.69
      2890105.67      7075197.48      2890141.44      7075231.95
      2890176.56      7075228.05      2890181.11      7075183.17
      2890282.50      7075014.09      2890360.70      7074953.28
      2890430.79      7074827.87      2890640.66      7074563.38
      2890728.46      7074412.50      2890845.59      7074300.71
      2890943.49      7074250.88      2891051.69      7074308.81
      2891111.85      7074300.17      2891182.78      7074235.88
      2891278.29      7074185.86      2891452.98      7074045.79
      2891708.19      7073885.61      2891862.61      7073755.32
      2892140.32      7073749.65      2892375.59      7073730.71

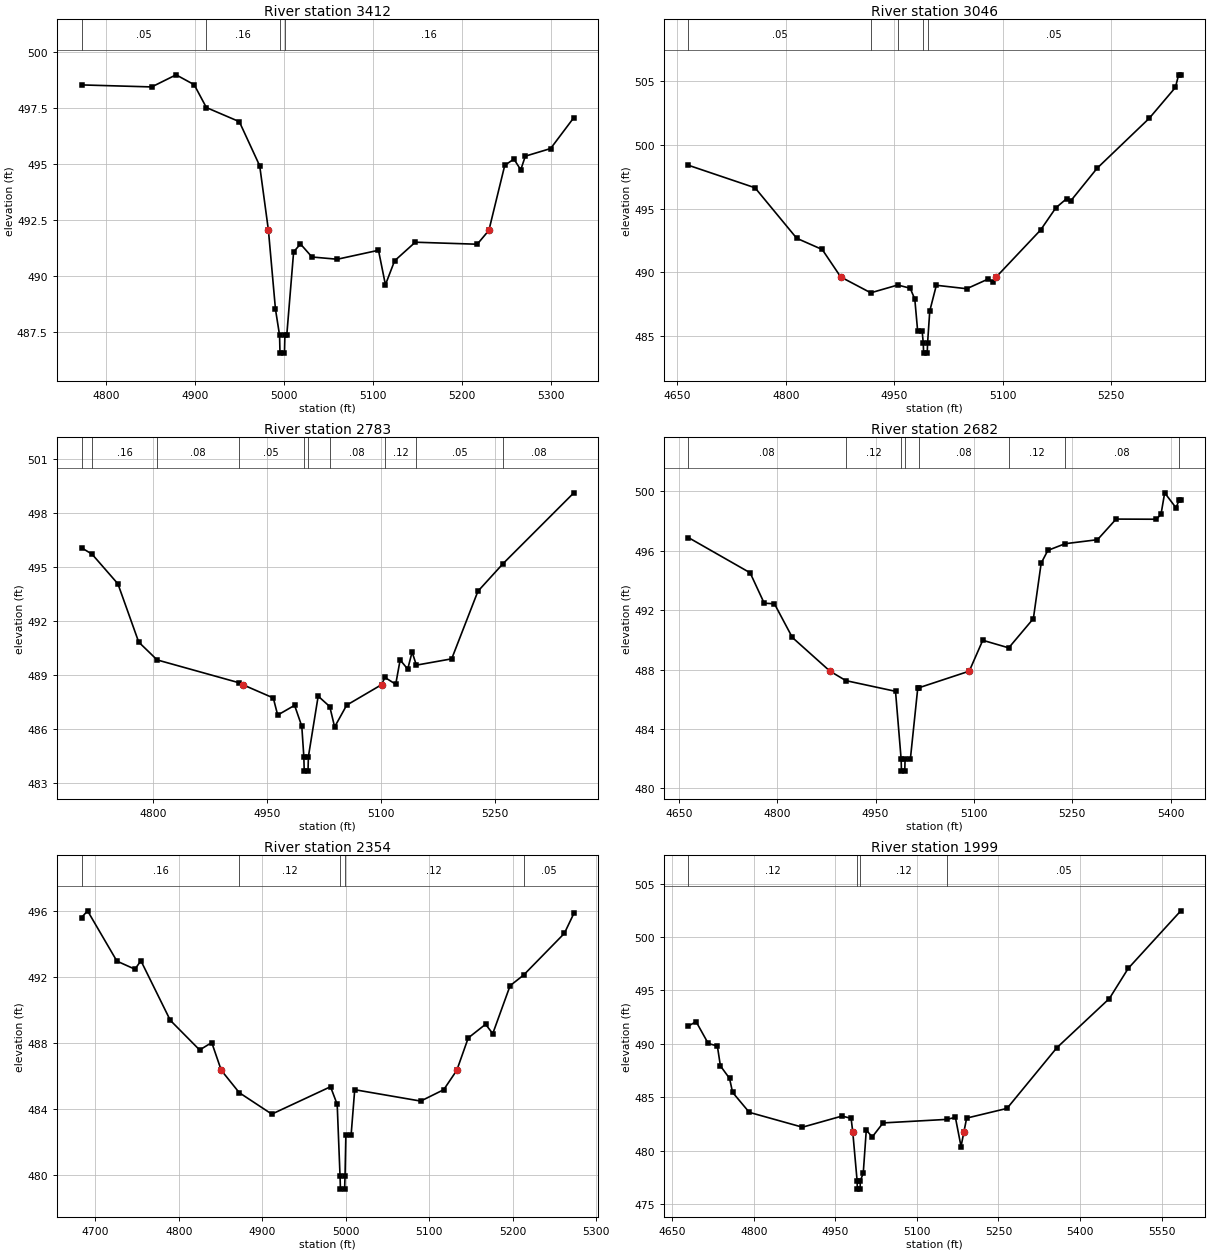
Type RM Length L Ch R = 1,3412,366,366,366
BEGIN DESCRIPTION:
UNT 044 in Running Cr Watershed 9.0
END DESCRIPTION:
XS GIS Cut Line= 3
      2890249.76      7075562.68      2890025.00      7075525.00
      2889709.71      7075603.85
#Sta/Elev= 30
  4772.7  498.51  4851.5  498.42  4878.9  498.96  4899.2  498.52  4912.9  497.50
  4949.9  496.87  4972.8  494.90  4982.6  492.02  4990.5  488.50  4995.1  487.34
  4995.6  486.54  5000.6  486.54  5001.1  487.34  5003.2  487.34  5010.9  491.06
  5018.6  491.41  5031.5  490.83  5059.9  490.73  5106.2  491.13  5114.0  489.59
  5124.3  490.66  5147.5  491.49  5217.1  491.40  5230.2  492.02  5248.0  494.92
  5258.3  495.20  5266.0  494.72  5271.1  495.33  5299.5  495.67  5325.6  497.05
#Mann=4,-1,0
  4772.7    0.05       0  4912.9    0.16       0  4995.1    0.07       0
  5001.1    0.16       0
Bank Sta=4982.6,5230.2
Exp/Cntr=0.3,0.1

Type RM Length L Ch R = 1,3046,263,263,263
BEGIN DESCRIPTION:
UNT 044 in Running Cr Watershed 8.0
END DESCRIPTION:
XS GIS Cut Line= 3
      2890274.98      7075474.97      2890075.00      7075225.00
      2889774.98      7075024.99
#Sta/Elev= 30
  4665.6  498.39  4757.6  496.63  4815.2  492.68  4850.5  491.80  4876.1  489.65
  4917.6  488.41  4954.9  489.02  4972.1  488.77  4978.5  487.92  4982.5  485.39
  4988.7  485.39  4990.2  484.49  4990.7  483.69  4995.7  483.69  4996.2  484.49
  4999.2  486.99  5008.3  489.00  5050.3  488.73  5080.4  489.50  5086.4  489.22
  5091.1  489.65  5152.5  493.33  5173.5  495.06  5188.5  495.78  5194.5  495.63
  5230.6  498.16  5302.7  502.07  5338.8  504.48  5343.3  505.47  5346.3  505.47
#Mann=5,-1,0
  4665.6    0.05       0  4917.6    0.07       0  4954.9    0.05       0
  4990.2    0.03       0  4996.2    0.05       0
Bank Sta=4876.1,5091.1
Exp/Cntr=0.3,0.1

Type RM Length L Ch R = 1,2783,101,101,101
BEGIN DESCRIPTION:
Mapping XS 48869750
END DESCRIPTION:
XS GIS Cut Line= 3
      2890364.84      7075369.58      2890186.87      7075054.87
      2890043.63      7074805.30
#Sta/Elev= 30
  4705.2  496.07  4719.0  495.72  4753.2  494.07  4780.6  490.84  4804.9  489.85
  4912.3  488.59  4917.6  488.48  4958.1  487.74  4963.9  486.79  4986.2  487.33
  4995.7  486.17  4998.4  484.48  4998.9  483.68  5003.9  483.68  5004.4  484.48
  5017.3  487.84  5032.6  487.26  5039.0  486.13  5054.9  487.34  5101.1  488.48
  5105.2  488.88  5119.6  488.50  5125.4  489.85  5135.4  489.34  5141.2  490.29
  5146.8  489.56  5193.4  489.91  5228.0  493.66  5261.1  495.19  5354.5  499.12
#Mann=10,-1,0
  4705.2    0.08       0  4719.0    0.16       0  4804.9    0.08       0
  4912.3    0.05       0  4998.4    0.04       0  5004.4    0.05       0
  5032.6    0.08       0  5105.2    0.12       0  5146.8    0.05       0
  5261.1    0.08       0
Bank Sta=4917.6,5101.1
Exp/Cntr=0.3,0.1

Type RM Length L Ch R = 1,2682,328,328,328
BEGIN DESCRIPTION:
UNT 044 in Running Cr Watershed 7.0
END DESCRIPTION:
XS GIS Cut Line= 3
      2890438.60      7075319.63      2890301.89      7075087.94
      2890097.90      7074651.25
#Sta/Elev= 30
  4664.6  496.89  4758.6  494.52  4780.1  492.47  4795.7  492.43  4823.0  490.16
  4880.4  487.89  4904.7  487.25  4980.4  486.53  4989.0  481.95  4989.5  481.15
  4994.5  481.15  4995.0  481.95  5003.1  481.98  5014.3  486.73  5016.1  486.77
  5092.9  487.89  5113.5  489.97  5153.1  489.46  5190.7  491.43  5202.6  495.17
  5212.8  496.03  5239.1  496.48  5288.5  496.75  5316.9  498.14  5378.4  498.13
  5385.4  498.46  5391.0  499.91  5408.3  498.90  5413.3  499.45  5415.6  499.45
#Mann=8,-1,0
  4664.6    0.08       0  4904.7    0.12       0  4989.0    0.07       0
  4995.0    0.12       0  5016.1    0.08       0  5153.1    0.12       0
  5239.1    0.08       0  5413.3    0.05       0
Bank Sta=4880.4,5092.9
Exp/Cntr=0.3,0.1

Type RM Length L Ch R = 1,2354,355,355,355
BEGIN DESCRIPTION:
UNT 044 in Running Cr Watershed 6.0
END DESCRIPTION:
XS GIS Cut Line= 3
      2890674.99      7075024.98      2890475.00      7074775.00
      2890256.32      7074616.52
#Sta/Elev= 30
  4683.3  495.62  4690.5  496.03  4725.7  492.98  4747.3  492.49  4754.5  493.00
  4789.7  489.39  4824.9  487.59  4839.4  488.04  4850.8  486.36  4872.4  485.00
  4911.4  483.70  4981.8  485.36  4989.8  484.29  4993.2  479.95  4993.7  479.15
  4998.7  479.15  4999.2  479.95  5000.2  482.44  5006.5  482.44  5010.8  485.18
  5089.9  484.49  5117.5  485.18  5133.2  486.36  5146.9  488.32  5167.7  489.15
  5176.3  488.58  5197.1  491.49  5213.2  492.13  5262.1  494.66  5273.5  495.87
#Mann=5,-1,0
  4683.3    0.16       0  4872.4    0.12       0  4993.2    0.07       0
  4999.2    0.12       0  5213.2    0.05       0
Bank Sta=4850.8,5133.2
Exp/Cntr=0.3,0.1

Type RM Length L Ch R = 1,1999,378,378,378
BEGIN DESCRIPTION:
UNT 044 in Running Cr Watershed 5.0
END DESCRIPTION:
XS GIS Cut Line= 3
      2890825.01      7074775.01      2890675.00      7074475.00
      2890525.00      7073925.01
#Sta/Elev= 30
  4680.0  491.67  4694.0  492.07  4716.3  490.03  4733.1  489.79  4738.7  487.93
  4755.5  486.76  4761.1  485.45  4791.8  483.58  4889.6  482.19  4962.3  483.23
  4979.1  483.02  4982.2  481.71  4990.1  477.19  4990.6  476.39  4995.6  476.39
  4996.1  477.19  5001.4  477.87  5007.0  481.91  5018.0  481.28  5037.9  482.59
  5155.0  482.92  5170.9  483.11  5181.3  480.38  5186.4  481.71  5191.6  483.04
  5265.9  483.95  5357.5  489.63  5454.2  494.24  5488.8  497.06  5585.5  502.45
#Mann=4,-1,0
  4680.0    0.12       0  4990.1    0.07       0  4996.1    0.12       0
  5155.0    0.05       0
Bank Sta=4982.2,5186.4
Exp/Cntr=0.3,0.1

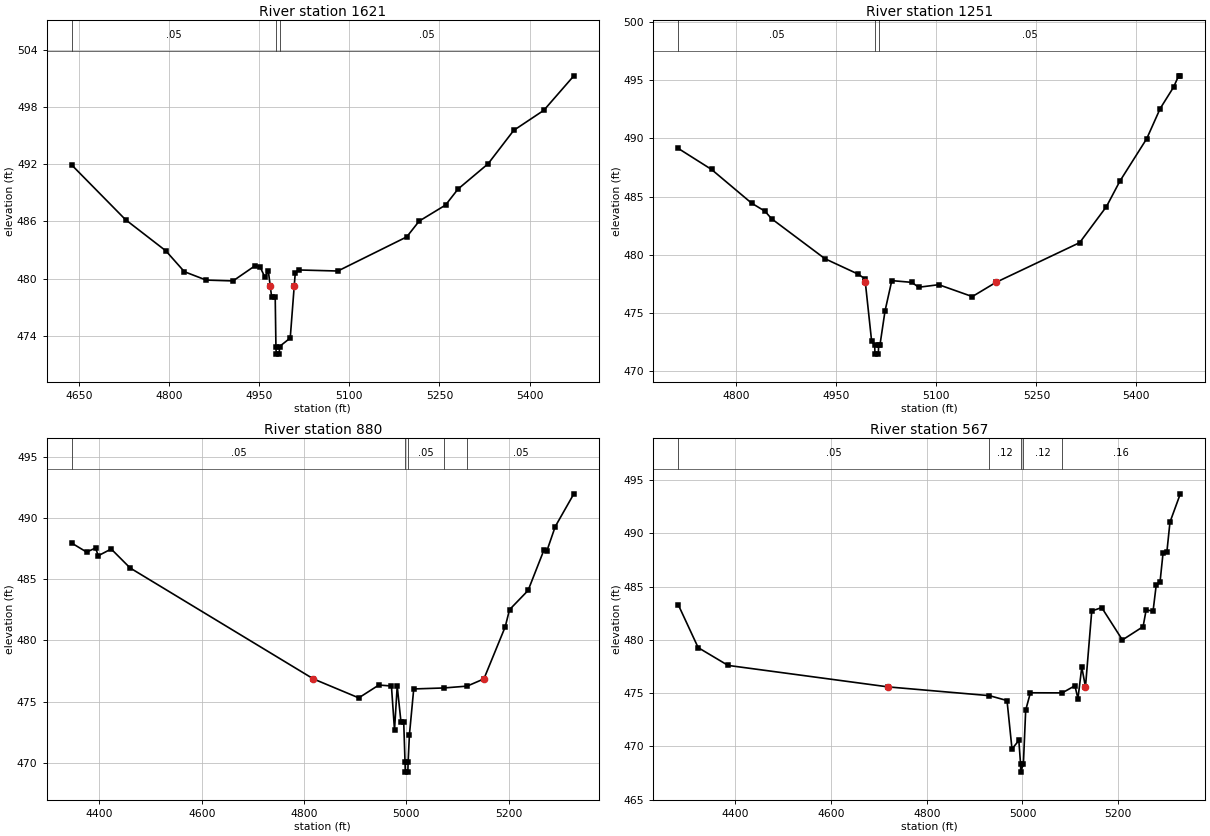
Type RM Length L Ch R = 1,1621,370,370,370
BEGIN DESCRIPTION:
UNT 044 in Running Cr Watershed 4.0
END DESCRIPTION:
XS GIS Cut Line= 3
      2891125.00      7074575.01      2890975.00      7074275.00
      2890675.01      7073875.01
#Sta/Elev= 30
  4638.3  491.92  4727.7  486.19  4794.8  482.92  4825.6  480.73  4861.9  479.85
  4906.6  479.76  4943.0  481.34  4951.4  481.26  4959.7  480.14  4965.3  480.83
  4968.6  479.19  4970.9  478.07  4976.8  478.07  4978.0  472.88  4978.5  472.08
  4983.5  472.08  4984.0  472.88  5001.8  473.77  5008.4  479.19  5010.2  480.64
  5016.4  480.91  5081.0  480.80  5195.6  484.38  5216.4  486.04  5260.2  487.72
  5281.0  489.40  5331.0  492.05  5373.7  495.56  5423.7  497.66  5473.7  501.28
#Mann=3,-1,0
  4638.3    0.05       0  4978.0    0.03       0  4984.0    0.05       0
Bank Sta=4968.6,5008.4
Exp/Cntr=0.3,0.1

Type RM Length L Ch R = 1,1251,371,371,371
BEGIN DESCRIPTION:
UNT 044 in Running Cr Watershed 3.0
END DESCRIPTION:
XS GIS Cut Line= 3
      2891275.00      7074475.03      2891275.00      7074175.00
      2891225.00      7073725.00
#Sta/Elev= 30
  4713.0  489.14  4763.0  487.33  4823.0  484.44  4843.0  483.75  4853.0  483.10
  4933.0  479.67  4983.0  478.34  4993.0  477.94  4993.5  477.65  5003.0  472.57
  5007.5  472.28  5008.0  471.48  5013.0  471.48  5013.5  472.28  5015.5  472.28
  5023.1  475.20  5033.2  477.79  5063.3  477.64  5073.4  477.22  5103.6  477.44
  5153.9  476.42  5189.7  477.65  5314.9  481.05  5355.1  484.15  5375.2  486.33
  5415.5  489.98  5435.6  492.56  5455.7  494.40  5463.3  495.37  5465.8  495.37
#Mann=3,-1,0
  4713.0    0.05       0  5007.5    0.03       0  5013.5    0.05       0
Bank Sta=4993.5,5189.7
Exp/Cntr=0.3,0.1

Type RM Length L Ch R = 1,880,313,313,313
BEGIN DESCRIPTION:
UNT 044 in Running Cr Watershed 2.0
END DESCRIPTION:
XS GIS Cut Line= 3
      2891353.53      7074582.22      2891575.00      7073975.00
      2891424.98      7073674.97
#Sta/Elev= 30
  4345.8  487.95  4374.8  487.22  4392.3  487.55  4397.6  486.92  4422.9  487.47
  4459.9  485.92  4818.3  476.85  4907.0  475.30  4946.3  476.35  4970.9  476.27
  4976.9  472.68  4982.2  476.26  4989.5  473.35  4994.9  473.35  4997.5  470.03
  4998.0  469.23  5003.0  469.23  5003.5  470.03  5006.1  472.30  5014.5  476.03
  5073.4  476.11  5118.8  476.26  5151.7  476.85  5193.4  481.11  5201.8  482.51
  5238.1  484.08  5268.9  487.36  5274.5  487.27  5291.2  489.30  5327.6  491.98
#Mann=5,-1,0
  4345.8    0.05       0  4997.5    0.03       0  5003.5    0.05       0
  5073.4    0.16       0  5118.8    0.05       0
Bank Sta=4818.3,5151.7
Exp/Cntr=0.3,0.1

Type RM Length L Ch R = 1,567,0,0,0
BEGIN DESCRIPTION:
UNT 044 in Running Cr Watershed 1.0
END DESCRIPTION:
XS GIS Cut Line= 3
      2891625.00      7074475.01      2891825.00      7073775.00
      2891574.98      7073574.98
#Sta/Elev= 30
  4281.3  483.31  4322.9  479.28  4385.3  477.61  4720.0  475.59  4931.0  474.77
  4967.7  474.31  4978.1  469.77  4992.4  470.56  4995.9  468.39  4996.4  467.59
  5001.9  468.39  5006.7  473.41  5016.5  475.04  5082.9  475.03  5109.4  475.70
  5115.8  474.50  5123.8  477.45  5131.5  475.59  5144.6  482.72  5165.4  483.04
  5208.6  480.00  5251.8  481.25  5258.2  482.83  5272.6  482.70  5279.1  485.12
  5287.1  485.41  5293.5  488.18  5301.5  488.28  5307.9  491.06  5329.5  493.72
#Mann=5,-1,0
  4281.3    0.05       0  4931.0    0.12       0  4995.9    0.07       0
  5001.9    0.12       0  5082.9    0.16       0
Bank Sta=4720,5131.5
Exp/Cntr=0.3,0.1

Chan Stop Cuts=-1