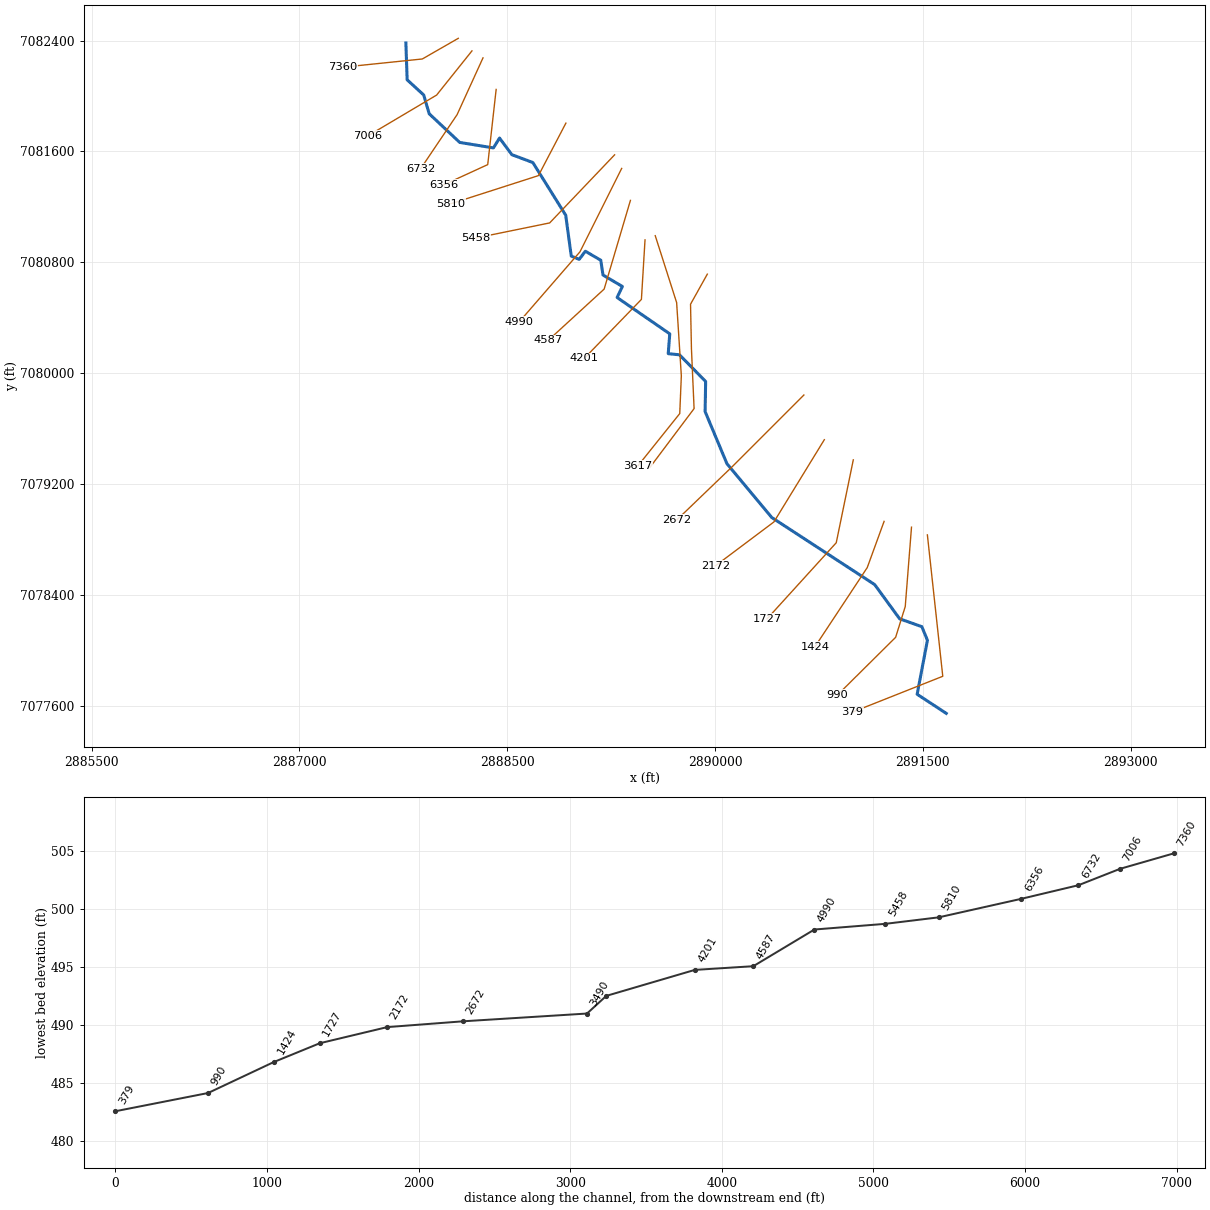
--- UNT 045 in Running Cr Watershed.prj (project) ---

Proj Title=UNT 045 in Running Cr Watershed Base Level Engineering
Current Plan=p01
Default Exp/Contr=0.3,0.1
English Units
Geom File=g01
Flow File=f01
Plan File=p01
BEGIN DESCRIPTION:
UNT 045 in Running Cr Watershed
END DESCRIPTION:

--- UNT 045 in Running Cr Watershed.p01 (plan) ---

Plan Title=Multiple Run
Short Identifier=Multiple
Geom File=g01
Flow File=f01
Subcritical Flow
K Sum by GR= 0
Std Step Tol= 0.01
Critical Tol= 0.01
Num of Std Step Trials= 20
Max Error Tol= 0.3
Flow Tol Ratio= 0.001
Split Flow NTrial= 30
Split Flow Tol= 0.02
Split Flow Ratio= 0.02
Log Output Level= 0
Friction Slope Method= 1
Unsteady Friction Slope Method= 2
Unsteady Bridges Friction Slope Method= 1
Parabolic Critical Depth
Global Vel Dist=  1 , 1 , 1
Global Log Level= 0
CheckData=True
Encroach Param= -1, 0, 0, 0
BEGIN DESCRIPTION:
Multiple Run
END DESCRIPTION:

--- UNT 045 in Running Cr Watershed.f01 (steady flow) ---

Flow Title=Multiple
Number of Profiles=7
Profile Names=10-year,25-year,50-year,1pct_min,100-year,1pct_plu,500-year
River Rch & RM= UNT 045 in Runni,Reach-1,7360
     813    1093    1320     791    1578    3148    2248
River Rch & RM= UNT 045 in Runni,Reach-1,3490
    1047    1425    1734    1046    2086    4163    3012
Boundary for River Rch & Prof#=UNT 045 in Runni,Reach-1,1
Up Type=0
Dn Type=3
Dn Slope=0.005
Boundary for River Rch & Prof#=UNT 045 in Runni,Reach-1,2
Up Type=0
Dn Type=3
Dn Slope=0.005
Boundary for River Rch & Prof#=UNT 045 in Runni,Reach-1,3
Up Type=0
Dn Type=3
Dn Slope=0.005
Boundary for River Rch & Prof#=UNT 045 in Runni,Reach-1,4
Up Type=0
Dn Type=3
Dn Slope=0.005
Boundary for River Rch & Prof#=UNT 045 in Runni,Reach-1,5
Up Type=0
Dn Type=3
Dn Slope=0.005
Boundary for River Rch & Prof#=UNT 045 in Runni,Reach-1,6
Up Type=0
Dn Type=3
Dn Slope=0.005
Boundary for River Rch & Prof#=UNT 045 in Runni,Reach-1,7
Up Type=0
Dn Type=3
Dn Slope=0.005

--- UNT 045 in Running Cr Watershed.g01 (geometry) ---

Geom Title=Existing Conditions

River Reach=UNT 045 in Runni,Reach-1
Reach XY= 30
      2887768.25      7082381.90      2887777.62      7082116.48
      2887897.34      7082006.74      2887936.41      7081871.78
      2888157.01      7081664.66      2888400.23      7081625.03
      2888444.27      7081696.20      2888533.26      7081576.31
      2888684.79      7081519.51      2888922.13      7081139.16
      2888962.06      7080844.33      2889019.34      7080820.46
      2889063.88      7080879.33      2889175.25      7080814.10
      2889191.15      7080707.51      2889331.16      7080624.78
      2889292.97      7080545.23      2889673.20      7080282.73
      2889662.07      7080139.55      2889743.20      7080131.59
      2889932.19      7079939.18      2889928.39      7079721.90
      2890085.78      7079345.73      2890409.18      7078957.32
      2891152.40      7078472.74      2891332.62      7078225.76
      2891492.85      7078169.09      2891533.18      7078070.92
      2891459.01      7077681.13      2891669.12      7077543.18

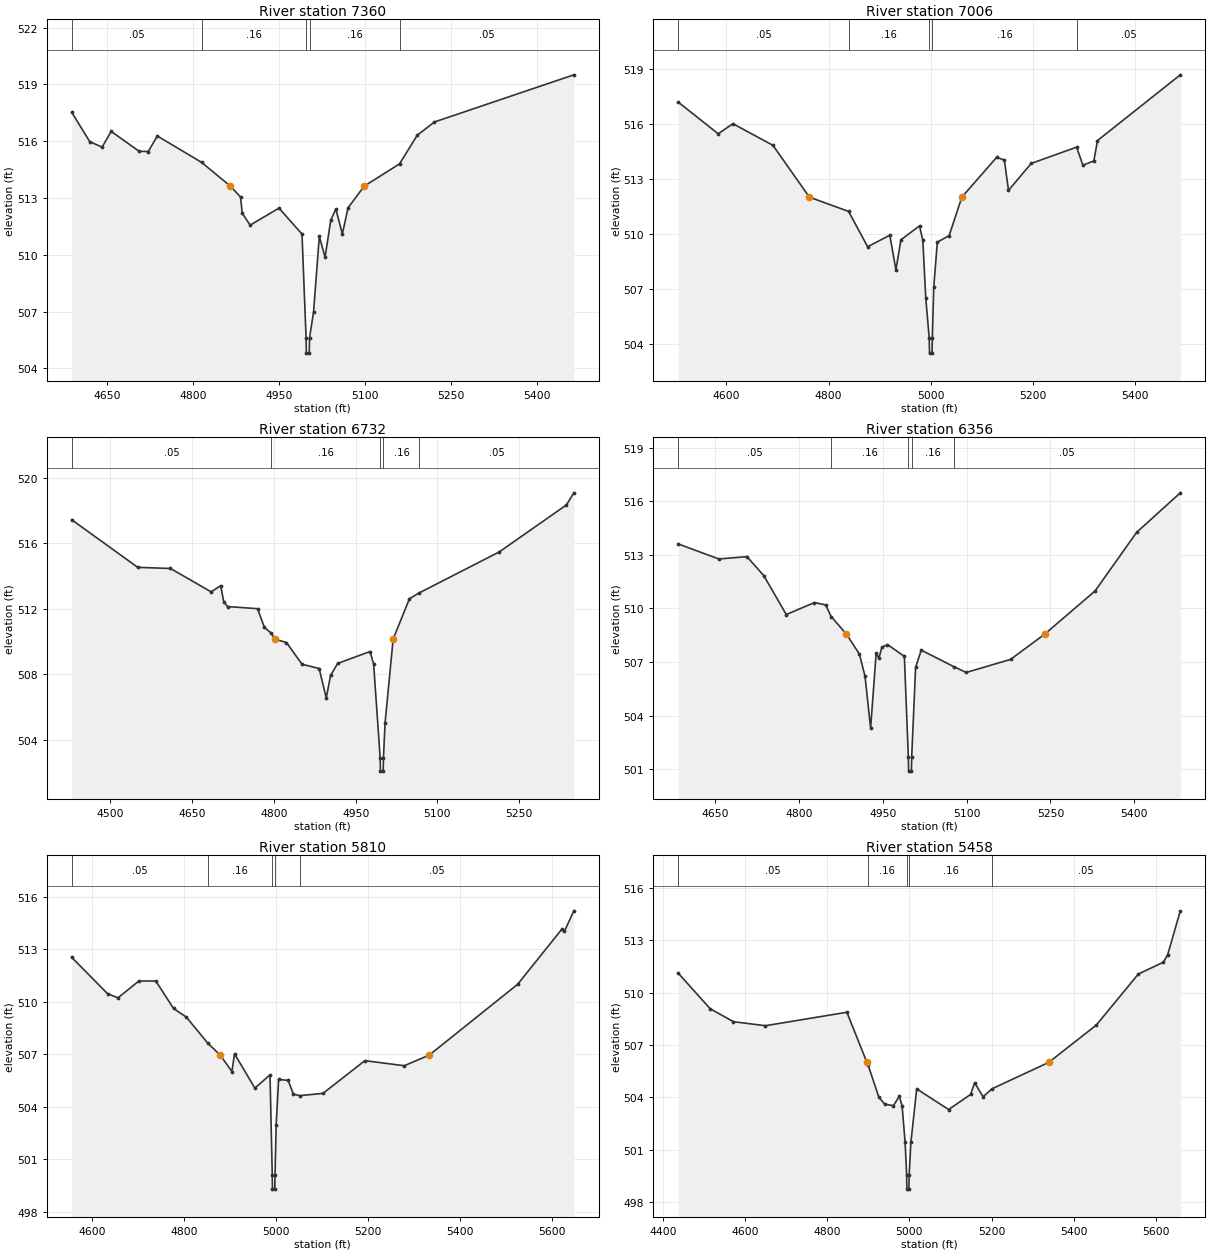
Type RM Length L Ch R = 1,7360,354,354,354
BEGIN DESCRIPTION:
UNT 045 in Running Cr Watershed 15.0
END DESCRIPTION:
XS GIS Cut Line= 3
      2888146.54      7082416.01      2887887.14      7082267.05
      2887313.13      7082207.65
#Sta/Elev= 30
  4588.5  517.53  4619.9  515.98  4641.4  515.69  4657.3  516.52  4706.2  515.47
  4722.0  515.46  4737.8  516.28  4815.4  514.88  4865.2  513.63  4883.0  513.06
  4886.0  512.20  4899.8  511.57  4950.1  512.47  4990.3  511.10  4997.4  505.61
  4997.9  504.81  5002.9  504.81  5003.4  505.61  5010.4  506.97  5020.5  510.98
  5030.5  509.87  5040.6  511.85  5049.4  512.42  5060.7  511.10  5070.7  512.49
  5098.9  513.63  5160.6  514.81  5191.4  516.32  5221.5  517.02  5464.7  519.51
#Mann=5,-1,0
  4588.5    0.05       0  4815.4    0.16       0  4997.4    0.07       0
  5003.4    0.16       0  5160.6    0.05       0
Bank Sta=4865.2,5098.9
Exp/Cntr=0.3,0.1

Type RM Length L Ch R = 1,7006,274,274,274
BEGIN DESCRIPTION:
UNT 045 in Running Cr Watershed 14.0
END DESCRIPTION:
XS GIS Cut Line= 3
      2888245.41      7082325.52      2887990.10      7082006.38
      2887495.43      7081712.85
#Sta/Elev= 30
  4505.5  517.19  4583.8  515.46  4612.6  516.01  4691.1  514.83  4762.5  512.00
  4839.3  511.22  4876.7  509.29  4920.1  509.92  4932.1  508.03  4941.9  509.67
  4978.3  510.43  4984.8  509.65  4990.6  506.49  4997.4  504.28  4997.9  503.48
  5002.9  503.48  5003.4  504.28  5006.2  507.07  5013.2  509.54  5036.4  509.90
  5061.3  512.00  5129.4  514.17  5144.6  514.03  5152.7  512.37  5197.2  513.84
  5286.2  514.73  5298.5  513.74  5320.0  513.98  5327.1  515.09  5489.4  518.68
#Mann=5,-1,0
  4505.5    0.05       0  4839.3    0.16       0  4997.4    0.07       0
  5003.4    0.16       0  5286.2    0.05       0
Bank Sta=4762.5,5061.3
Exp/Cntr=0.3,0.1

Type RM Length L Ch R = 1,6732,376,376,376
BEGIN DESCRIPTION:
UNT 045 in Running Cr Watershed 13.0
END DESCRIPTION:
XS GIS Cut Line= 3
      2888325.02      7082275.04      2888137.82      7081864.77
      2887874.98      7081474.97
#Sta/Elev= 30
  4429.2  517.45  4550.2  514.54  4610.3  514.47  4684.9  513.04  4702.4  513.42
  4707.9  512.45  4715.0  512.14  4770.0  512.01  4782.5  510.87  4794.9  510.52
  4801.9  510.15  4823.1  509.94  4851.6  508.61  4883.0  508.35  4896.1  506.55
  4904.0  507.93  4917.1  508.66  4976.4  509.39  4983.0  508.62  4995.0  502.87
  4995.5  502.07  5000.5  502.07  5001.0  502.87  5004.0  505.03  5018.8  510.15
  5048.7  512.62  5066.8  512.98  5213.8  515.49  5336.7  518.36  5350.3  519.10
#Mann=5,-1,0
  4429.2    0.05       0  4794.9    0.16       0  4995.0    0.07       0
  5001.0    0.16       0  5066.8    0.05       0
Bank Sta=4801.9,5018.8
Exp/Cntr=0.3,0.1

Type RM Length L Ch R = 1,6356,546,546,546
BEGIN DESCRIPTION:
UNT 045 in Running Cr Watershed 12.0
END DESCRIPTION:
XS GIS Cut Line= 3
      2888419.94      7082047.10      2888359.17      7081504.53
      2888039.01      7081357.43
#Sta/Elev= 30
  4584.1  513.61  4656.6  512.77  4707.0  512.90  4737.1  511.84  4777.4  509.66
  4827.7  510.33  4847.8  510.20  4857.7  509.55  4885.1  508.56  4908.2  507.45
  4918.3  506.21  4928.3  503.30  4938.2  507.50  4943.2  507.23  4948.5  507.83
  4958.5  507.98  4988.7  507.32  4995.8  501.70  4996.3  500.90  5001.3  500.90
  5001.8  501.70  5008.8  506.70  5018.9  507.67  5077.4  506.74  5099.4  506.42
  5178.7  507.15  5239.6  508.56  5329.9  510.98  5404.3  514.26  5482.4  516.47
#Mann=5,-1,0
  4584.1    0.05       0  4857.7    0.16       0  4995.8    0.07       0
  5001.8    0.16       0  5077.4    0.05       0
Bank Sta=4885.1,5239.6
Exp/Cntr=0.3,0.1

Type RM Length L Ch R = 1,5810,352,352,352
BEGIN DESCRIPTION:
UNT 045 in Running Cr Watershed 11.0
END DESCRIPTION:
XS GIS Cut Line= 3
      2888923.40      7081803.99      2888725.00      7081425.00
      2888094.43      7081222.41
#Sta/Elev= 30
  4556.7  512.54  4634.6  510.46  4657.2  510.23  4702.3  511.19  4739.2  511.19
  4777.7  509.62  4805.4  509.13  4852.0  507.64  4878.9  506.96  4904.4  506.02
  4910.1  507.03  4954.2  505.07  4987.1  505.83  4992.0  500.10  4992.5  499.30
  4997.5  499.30  4998.0  500.10  5000.5  502.99  5005.8  505.57  5026.5  505.51
  5037.9  504.73  5051.7  504.64  5102.1  504.77  5193.1  506.64  5278.6  506.35
  5333.0  506.96  5524.7  511.00  5621.0  514.16  5626.2  514.02  5646.8  515.20
#Mann=5,-1,0
  4556.7    0.05       0  4852.0    0.16       0  4992.0    0.07       0
  4998.0    0.16       0  5051.7    0.05       0
Bank Sta=4878.9,5333
Exp/Cntr=0.3,0.1

Type RM Length L Ch R = 1,5458,468,468,468
BEGIN DESCRIPTION:
UNT 045 in Running Cr Watershed 10.0
END DESCRIPTION:
XS GIS Cut Line= 3
      2889274.99      7081574.98      2888806.22      7081083.52
      2888274.97      7080974.99
#Sta/Elev= 30
  4437.8  511.11  4515.6  509.07  4572.2  508.33  4649.9  508.10  4848.1  508.87
  4896.7  506.00  4899.4  505.87  4925.8  504.01  4939.9  503.61  4961.3  503.52
  4975.5  504.06  4982.4  503.51  4989.6  501.46  4993.5  499.54  4994.0  498.74
  4999.0  498.74  4999.5  499.54  5003.8  501.42  5017.9  504.48  5095.6  503.30
  5148.8  504.16  5159.0  504.83  5179.4  504.03  5201.3  504.49  5339.2  506.00
  5455.0  508.14  5557.1  511.06  5618.3  511.74  5628.5  512.17  5659.2  514.68
#Mann=5,-1,0
  4437.8    0.05       0  4899.4    0.16       0  4993.5    0.07       0
  4999.5    0.16       0  5201.3    0.05       0
Bank Sta=4896.7,5339.2
Exp/Cntr=0.3,0.1

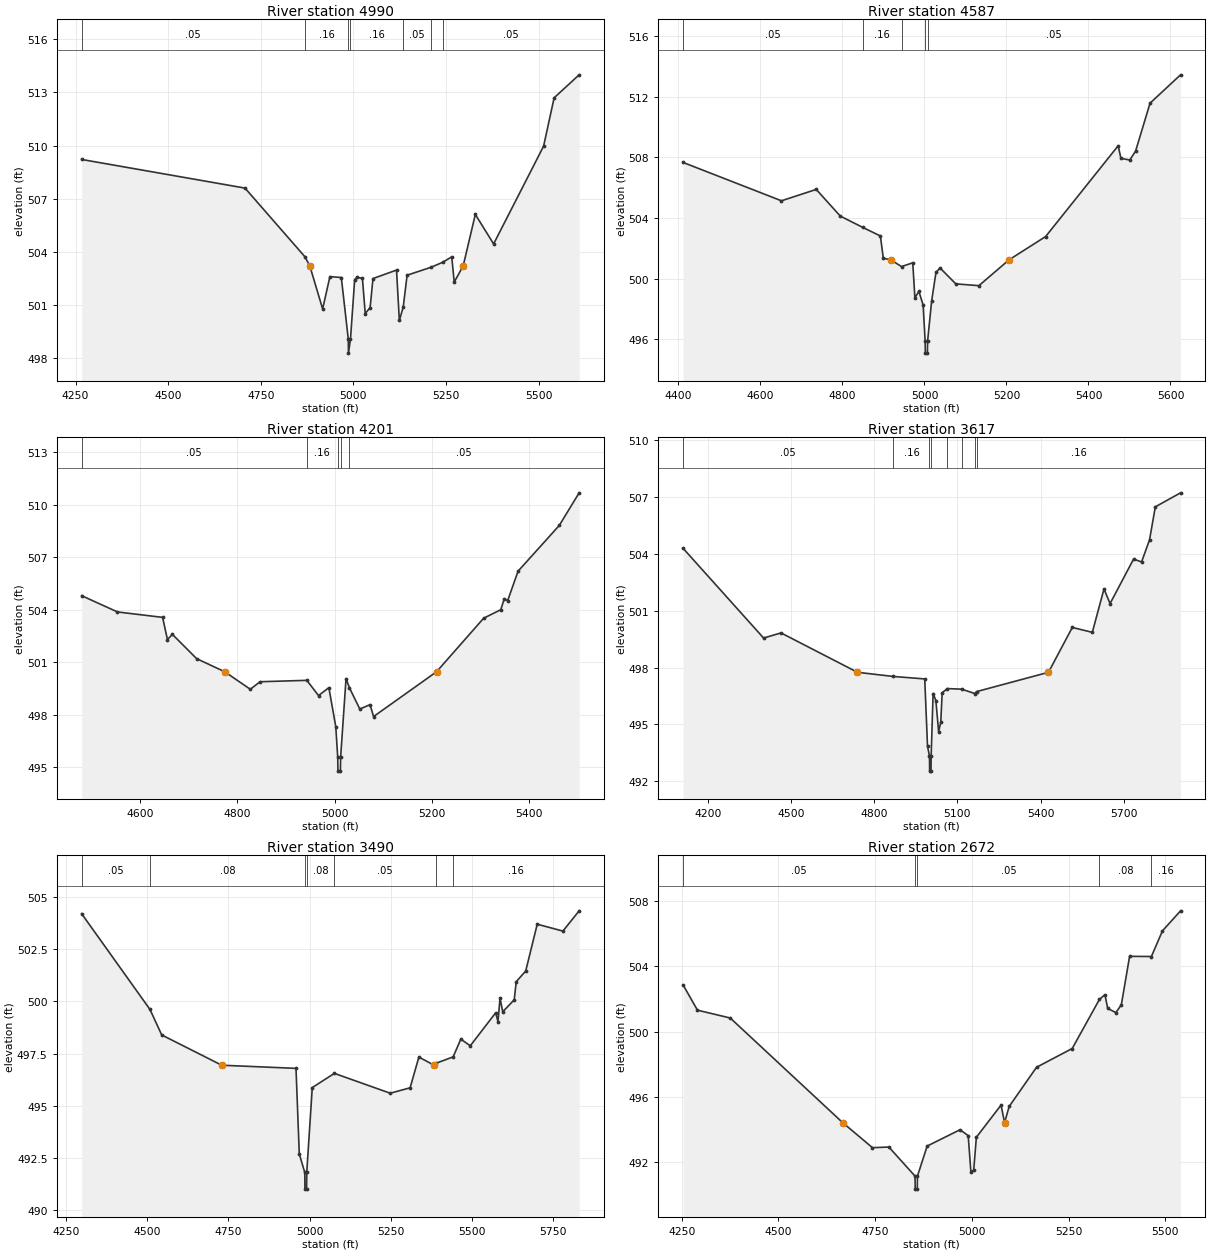
Type RM Length L Ch R = 1,4990,403,403,403
BEGIN DESCRIPTION:
UNT 045 in Running Cr Watershed 9.0
END DESCRIPTION:
XS GIS Cut Line= 3
      2889325.96      7081476.92      2889025.00      7080875.00
      2888586.00      7080368.68
#Sta/Elev= 30
  4266.4  509.21  4707.4  507.59  4868.9  503.71  4882.3  503.19  4917.0  500.75
  4936.6  502.58  4967.4  502.53  4986.2  499.05  4986.7  498.25  4992.2  499.05
  5003.5  502.41  5010.1  502.54  5024.4  502.48  5032.0  500.49  5045.2  500.83
  5052.9  502.47  5116.5  502.95  5124.1  500.10  5134.6  500.86  5145.0  502.66
  5209.9  503.11  5241.0  503.39  5265.6  503.70  5272.2  502.27  5296.5  503.19
  5329.2  506.10  5378.6  504.43  5513.5  509.96  5542.0  512.70  5609.5  514.00
#Mann=7,-1,0
  4266.4    0.05       0  4868.9    0.16       0  4986.2    0.07       0
  4992.2    0.16       0  5134.6    0.05       0  5209.9    0.16       0
  5241.0    0.05       0
Bank Sta=4882.3,5296.5
Exp/Cntr=0.3,0.1

Type RM Length L Ch R = 1,4587,386,386,386
BEGIN DESCRIPTION:
UNT 045 in Running Cr Watershed 8.0
END DESCRIPTION:
XS GIS Cut Line= 3
      2889389.27      7081246.39      2889199.58      7080605.87
      2888797.63      7080237.41
#Sta/Elev= 30
  4411.3  507.67  4651.3  505.14  4736.1  505.89  4794.8  504.13  4849.1  503.39
  4892.5  502.82  4899.7  501.35  4917.5  501.25  4944.2  500.80  4971.5  501.05
  4976.7  498.73  4986.4  499.17  4996.8  498.26  5001.7  495.89  5002.2  495.09
  5007.2  495.09  5007.7  495.89  5017.6  498.54  5028.1  500.41  5038.0  500.71
  5076.4  499.66  5132.7  499.54  5206.6  501.25  5295.5  502.78  5472.5  508.77
  5479.2  507.94  5500.8  507.83  5515.0  508.42  5550.2  511.58  5624.6  513.45
#Mann=5,-1,0
  4411.3    0.05       0  4849.1    0.16       0  4944.2    0.05       0
  5001.7   0.035       0  5007.7    0.05       0
Bank Sta=4917.5,5206.6
Exp/Cntr=0.3,0.1

Type RM Length L Ch R = 1,4201,584,584,584
BEGIN DESCRIPTION:
UNT 045 in Running Cr Watershed 7.0
END DESCRIPTION:
XS GIS Cut Line= 3
      2889494.59      7080961.12      2889468.55      7080531.44
      2889056.20      7080106.06
#Sta/Elev= 30
  4480.0  504.80  4553.6  503.87  4646.4  503.56  4656.4  502.29  4666.5  502.59
  4716.4  501.20  4774.2  500.45  4826.8  499.45  4846.8  499.88  4943.0  499.96
  4967.0  499.09  4988.3  499.54  5002.5  497.31  5006.5  495.57  5007.0  494.77
  5012.0  494.77  5012.5  495.57  5023.6  500.06  5030.3  499.55  5051.9  498.32
  5073.0  498.57  5080.2  497.89  5209.7  500.45  5306.5  503.51  5341.8  504.00
  5349.0  504.63  5356.0  504.52  5377.3  506.20  5462.2  508.82  5502.9  510.68
#Mann=5,-1,0
  4480.0    0.05       0  4943.0    0.16       0  5006.5    0.07       0
  5012.5    0.16       0  5030.3    0.05       0
Bank Sta=4774.2,5209.7
Exp/Cntr=0.3,0.1

Type RM Length L Ch R = 1,3617,127,127,127
BEGIN DESCRIPTION:
UNT 045 in Running Cr Watershed 6.0
END DESCRIPTION:
XS GIS Cut Line= 5
      2889568.38      7080991.48      2889722.89      7080508.00
      2889756.74      7079979.35      2889745.30      7079707.32
      2889442.82      7079329.57
#Sta/Elev= 30
  4111.2  504.30  4401.5  499.56  4464.4  499.83  4740.0  497.75  4869.2  497.53
  4982.5  497.40  4992.5  493.84  4999.6  493.33  5000.1  492.53  5005.1  492.53
  5005.6  493.33  5012.6  496.63  5022.6  496.26  5032.6  494.61  5040.3  495.12
  5045.3  496.67  5063.9  496.89  5115.4  496.86  5162.9  496.63  5169.2  496.73
  5428.6  497.75  5514.5  500.12  5586.6  499.86  5628.7  502.15  5650.6  501.38
  5735.4  503.73  5764.2  503.58  5793.0  504.75  5813.8  506.49  5904.7  507.23
#Mann=8,-1,0
  4111.2    0.05       0  4869.2    0.16       0  4999.6    0.07       0
  5005.6    0.16       0  5063.9    0.05       0  5115.4    0.08       0
  5162.9    0.05       0  5169.2    0.16       0
Bank Sta=4740,5428.6
Exp/Cntr=0.3,0.1

Type RM Length L Ch R = 1,3490,818,818,818
BEGIN DESCRIPTION:
UNT 045 in Running Cr Watershed 5.0
END DESCRIPTION:
XS GIS Cut Line= 5
      2889944.22      7080713.69      2889823.12      7080496.69
      2889829.66      7080177.27      2889848.76      7079743.24
      2889530.44      7079319.40
#Sta/Elev= 30
  4298.1  504.19  4508.5  499.61  4544.7  498.39  4729.7  496.94  4958.4  496.79
  4968.5  492.69  4985.4  491.81  4985.9  491.01  4991.0  491.01  4991.5  491.81
  5008.5  495.87  5076.6  496.55  5248.7  495.60  5309.9  495.86  5336.9  497.33
  5384.0  496.94  5389.1  497.03  5442.5  497.34  5466.1  498.19  5495.2  497.87
  5573.5  499.45  5580.6  499.03  5586.9  500.15  5595.2  499.50  5630.6  500.07
  5636.9  500.94  5666.0  501.45  5701.5  503.69  5780.6  503.36  5830.6  504.33
#Mann=7,-1,0
  4298.1    0.05       0  4508.5    0.08       0  4985.4    0.07       0
  4991.5    0.08       0  5076.6    0.05       0  5389.1    0.08       0
  5442.5    0.16       0
Bank Sta=4729.7,5384
Exp/Cntr=0.3,0.1

Type RM Length L Ch R = 1,2672,500,500,500
BEGIN DESCRIPTION:
UNT 045 in Running Cr Watershed 4.0
END DESCRIPTION:
XS GIS Cut Line= 3
      2890641.28      7079841.28      2890125.00      7079325.00
      2889724.05      7078939.71
#Sta/Elev= 30
  4253.4  502.86  4290.6  501.31  4375.4  500.83  4665.9  494.42  4743.1  492.88
  4785.5  492.92  4853.1  491.14  4853.6  490.34  4858.9  490.34  4859.4  491.14
  4884.5  492.98  4969.4  493.98  4990.6  493.62  4997.5  491.42  5004.8  491.49
  5011.7  493.52  5075.5  495.49  5084.6  494.42  5096.6  495.41  5167.3  497.81
  5259.5  498.96  5329.9  501.97  5344.1  502.26  5351.3  501.42  5372.4  501.16
  5386.5  501.64  5407.9  504.61  5464.3  504.60  5492.8  506.17  5539.6  507.40
#Mann=5,-1,0
  4253.4    0.05       0  4853.1    0.03       0  4859.4    0.05       0
  5329.9    0.08       0  5464.3    0.16       0
Bank Sta=4665.9,5084.6
Exp/Cntr=0.3,0.1

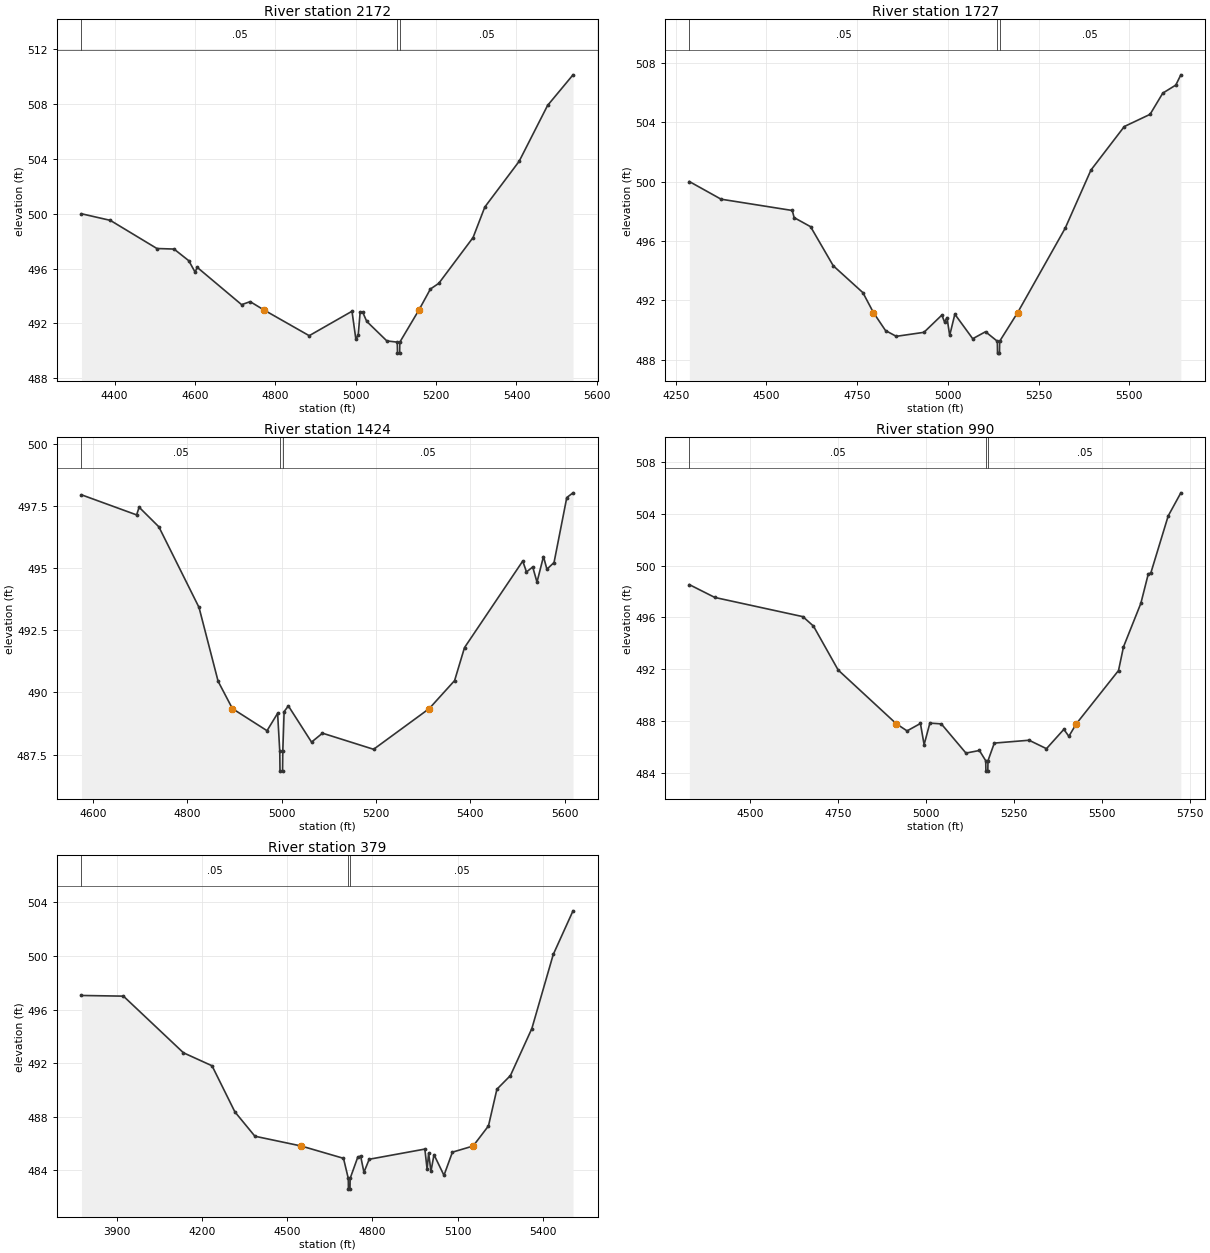
Type RM Length L Ch R = 1,2172,445,445,445
BEGIN DESCRIPTION:
UNT 045 in Running Cr Watershed 3.0
END DESCRIPTION:
XS GIS Cut Line= 3
      2890788.90      7079518.74      2890425.00      7078925.00
      2890003.55      7078608.91
#Sta/Elev= 30
  4317.6  499.99  4389.3  499.51  4505.3  497.46  4547.9  497.42  4584.6  496.57
  4600.1  495.75  4605.9  496.08  4716.1  493.37  4737.4  493.59  4770.7  493.00
  4884.3  491.11  4990.8  492.89  5000.4  490.85  5006.3  491.17  5011.1  492.84
  5017.1  492.84  5027.5  492.15  5077.5  490.73  5103.5  490.64  5104.0  489.84
  5109.3  489.84  5109.8  490.64  5157.7  493.00  5185.9  494.51  5206.7  494.92
  5292.1  498.26  5321.3  500.48  5406.7  503.81  5477.5  507.88  5540.8  510.11
#Mann=3,-1,0
  4317.6    0.05       0  5103.5    0.03       0  5109.8    0.05       0
Bank Sta=4770.7,5157.7
Exp/Cntr=0.3,0.1

Type RM Length L Ch R = 1,1727,303,303,303
BEGIN DESCRIPTION:
UNT 045 in Running Cr Watershed 2.0
END DESCRIPTION:
XS GIS Cut Line= 3
      2890998.07      7079373.47      2890875.00      7078775.00
      2890375.00      7078225.00
#Sta/Elev= 30
  4287.4  500.00  4374.9  498.81  4571.1  498.05  4576.2  497.57  4621.5  496.96
  4684.0  494.33  4765.7  492.52  4794.7  491.18  4828.0  489.97  4857.6  489.58
  4933.9  489.85  4983.2  491.01  4990.6  490.55  4997.4  490.84  5004.8  489.64
  5019.0  491.07  5068.3  489.42  5103.5  489.89  5136.1  489.25  5136.6  488.45
  5142.0  488.45  5142.5  489.25  5192.1  491.18  5323.1  496.86  5394.0  500.77
  5485.9  503.70  5556.9  504.52  5592.0  505.95  5627.8  506.49  5641.7  507.18
#Mann=3,-1,0
  4287.4    0.05       0  5136.1    0.03       0  5142.5    0.05       0
Bank Sta=4794.7,5192.1
Exp/Cntr=0.3,0.1

Type RM Length L Ch R = 1,1424,434,434,434
BEGIN DESCRIPTION:
Mapping XS ed241264
END DESCRIPTION:
XS GIS Cut Line= 3
      2891220.27      7078928.97      2891098.76      7078595.67
      2890720.28      7078022.75
#Sta/Elev= 30
  4576.0  497.97  4692.8  497.16  4698.1  497.47  4739.9  496.68  4825.0  493.43
  4865.5  490.45  4895.8  489.35  4969.1  488.46  4991.5  489.16  4996.1  487.63
  4996.6  486.83  5002.0  486.83  5002.5  487.63  5005.3  489.23  5014.3  489.46
  5063.4  488.00  5086.6  488.36  5194.9  487.71  5312.7  489.35  5366.5  490.48
  5387.5  491.81  5510.9  495.30  5518.8  494.86  5532.0  495.06  5541.1  494.45
  5554.8  495.48  5562.1  494.97  5577.2  495.24  5604.2  497.86  5617.4  498.05
#Mann=3,-1,0
  4576.0    0.05       0  4996.1    0.03       0  5002.5    0.05       0
Bank Sta=4895.8,5312.7
Exp/Cntr=0.3,0.1

Type RM Length L Ch R = 1,990,611,611,611
BEGIN DESCRIPTION:
Mapping XS a89d6172
END DESCRIPTION:
XS GIS Cut Line= 4
      2891418.20      7078887.36      2891373.06      7078314.42
      2891303.62      7078092.20      2890883.51      7077675.57
#Sta/Elev= 30
  4326.1  498.53  4398.7  497.54  4649.5  496.06  4679.6  495.33  4749.8  491.95
  4915.3  487.81  4946.0  487.26  4984.0  487.83  4994.5  486.20  5010.9  487.86
  5043.4  487.80  5113.6  485.55  5151.9  485.75  5169.9  484.96  5170.4  484.16
  5175.8  484.16  5176.3  484.96  5194.3  486.32  5293.3  486.54  5342.8  485.89
  5392.3  487.38  5406.5  486.84  5427.8  487.81  5547.9  491.91  5562.0  493.73
  5611.5  497.09  5632.7  499.36  5639.8  499.42  5689.3  503.82  5725.3  505.60
#Mann=3,-1,0
  4326.1    0.05       0  5169.9    0.03       0  5176.3    0.05       0
Bank Sta=4915.3,5427.8
Exp/Cntr=0.3,0.1

Type RM Length L Ch R = 1,379,0,0,0
BEGIN DESCRIPTION:
UNT 045 in Running Cr Watershed 1.0
END DESCRIPTION:
XS GIS Cut Line= 3
      2891532.79      7078831.77      2891643.90      7077810.95
      2890990.29      7077551.42
#Sta/Elev= 30
  3776.1  497.05  3923.7  497.00  4135.0  492.77  4235.6  491.80  4316.0  488.36
  4386.5  486.54  4549.6  485.81  4698.3  484.89  4715.2  483.39  4715.7  482.59
  4721.2  482.59  4721.7  483.39  4748.6  484.98  4758.6  485.06  4770.3  483.85
  4788.8  484.82  4984.7  485.58  4992.6  484.08  4998.0  485.28  5006.2  483.92
  5016.9  485.16  5052.0  483.62  5081.7  485.35  5154.7  485.81  5208.6  487.31
  5238.3  490.05  5285.9  491.07  5361.3  494.58  5436.6  500.11  5506.2  503.37
#Mann=3,-1,0
  3776.1    0.05       0  4715.2    0.03       0  4721.7    0.05       0
Bank Sta=4549.6,5154.7
Exp/Cntr=0.3,0.1

Chan Stop Cuts=-1