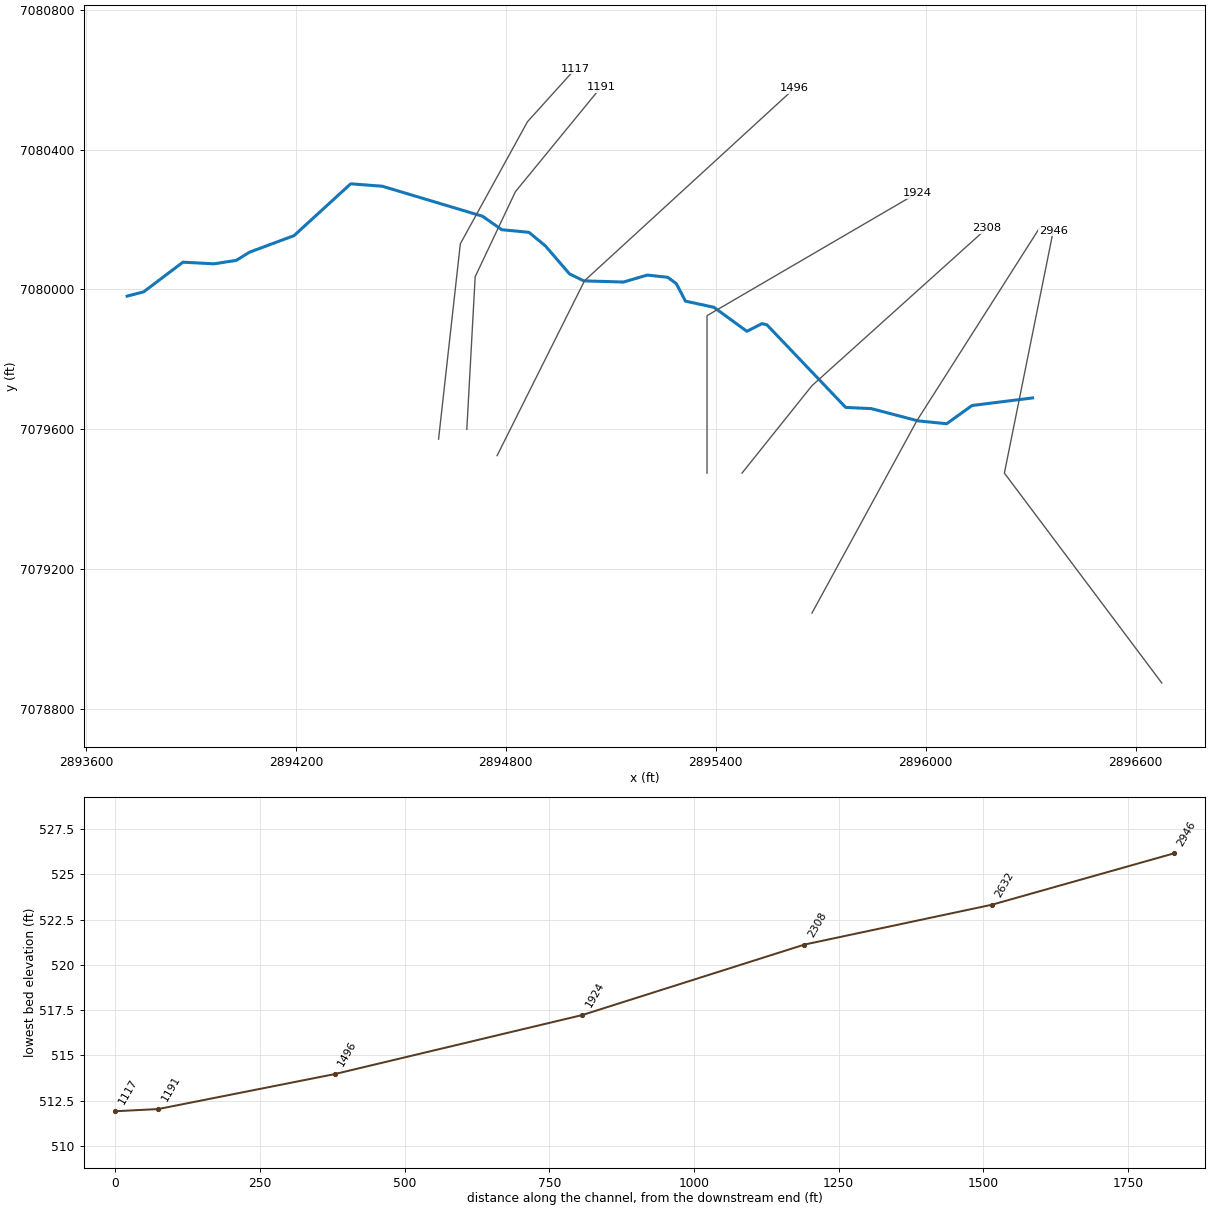
--- UNT 046 in Running Cr Watershed.prj (project) ---

Proj Title=UNT 046 in Running Cr Watershed Base Level Engineering
Current Plan=p01
Default Exp/Contr=0.3,0.1
English Units
Geom File=g01
Flow File=f01
Plan File=p01
BEGIN DESCRIPTION:
UNT 046 in Running Cr Watershed
END DESCRIPTION:

--- UNT 046 in Running Cr Watershed.p01 (plan) ---

Plan Title=Multiple Run
Short Identifier=Multiple
Geom File=g01
Flow File=f01
Subcritical Flow
K Sum by GR= 0
Std Step Tol= 0.01
Critical Tol= 0.01
Num of Std Step Trials= 20
Max Error Tol= 0.3
Flow Tol Ratio= 0.001
Split Flow NTrial= 30
Split Flow Tol= 0.02
Split Flow Ratio= 0.02
Log Output Level= 0
Friction Slope Method= 1
Unsteady Friction Slope Method= 2
Unsteady Bridges Friction Slope Method= 1
Parabolic Critical Depth
Global Vel Dist=  1 , 1 , 1
Global Log Level= 0
CheckData=True
Encroach Param= -1, 0, 0, 0
BEGIN DESCRIPTION:
Multiple Run
END DESCRIPTION:

--- UNT 046 in Running Cr Watershed.f01 (steady flow) ---

Flow Title=Multiple
Number of Profiles=7
Profile Names=10-year,25-year,50-year,1pct_min,100-year,1pct_plu,500-year
River Rch & RM= UNT 046 in Runni,Reach-1,2946
     294     371     429     247     493     985     648
Boundary for River Rch & Prof#=UNT 046 in Runni,Reach-1,1
Up Type=0
Dn Type=3
Dn Slope=0.005
Boundary for River Rch & Prof#=UNT 046 in Runni,Reach-1,2
Up Type=0
Dn Type=3
Dn Slope=0.005
Boundary for River Rch & Prof#=UNT 046 in Runni,Reach-1,3
Up Type=0
Dn Type=3
Dn Slope=0.005
Boundary for River Rch & Prof#=UNT 046 in Runni,Reach-1,4
Up Type=0
Dn Type=3
Dn Slope=0.005
Boundary for River Rch & Prof#=UNT 046 in Runni,Reach-1,5
Up Type=0
Dn Type=3
Dn Slope=0.005
Boundary for River Rch & Prof#=UNT 046 in Runni,Reach-1,6
Up Type=0
Dn Type=3
Dn Slope=0.005
Boundary for River Rch & Prof#=UNT 046 in Runni,Reach-1,7
Up Type=0
Dn Type=3
Dn Slope=0.005

--- UNT 046 in Running Cr Watershed.g01 (geometry) ---

Geom Title=Existing Conditions

River Reach=UNT 046 in Runni,Reach-1
Reach XY= 30
      2896305.62      7079689.90      2896132.44      7079668.20
      2896059.96      7079616.12      2895977.92      7079624.36
      2895844.96      7079659.28      2895771.38      7079662.78
      2895546.09      7079898.94      2895532.26      7079902.30
      2895488.98      7079880.37      2895394.84      7079948.94
      2895313.44      7079966.57      2895287.18      7080016.50
      2895262.69      7080034.74      2895204.00      7080041.08
      2895136.13      7080021.16      2895022.49      7080024.59
      2894981.65      7080044.75      2894912.82      7080124.70
      2894865.78      7080163.37      2894788.44      7080170.69
      2894733.04      7080209.36      2894446.65      7080295.07
      2894356.39      7080301.97      2894194.39      7080153.81
      2894067.30      7080106.56      2894029.51      7080083.15
      2893965.63      7080073.22      2893876.82      7080077.94
      2893764.58      7079993.13      2893717.45      7079980.95

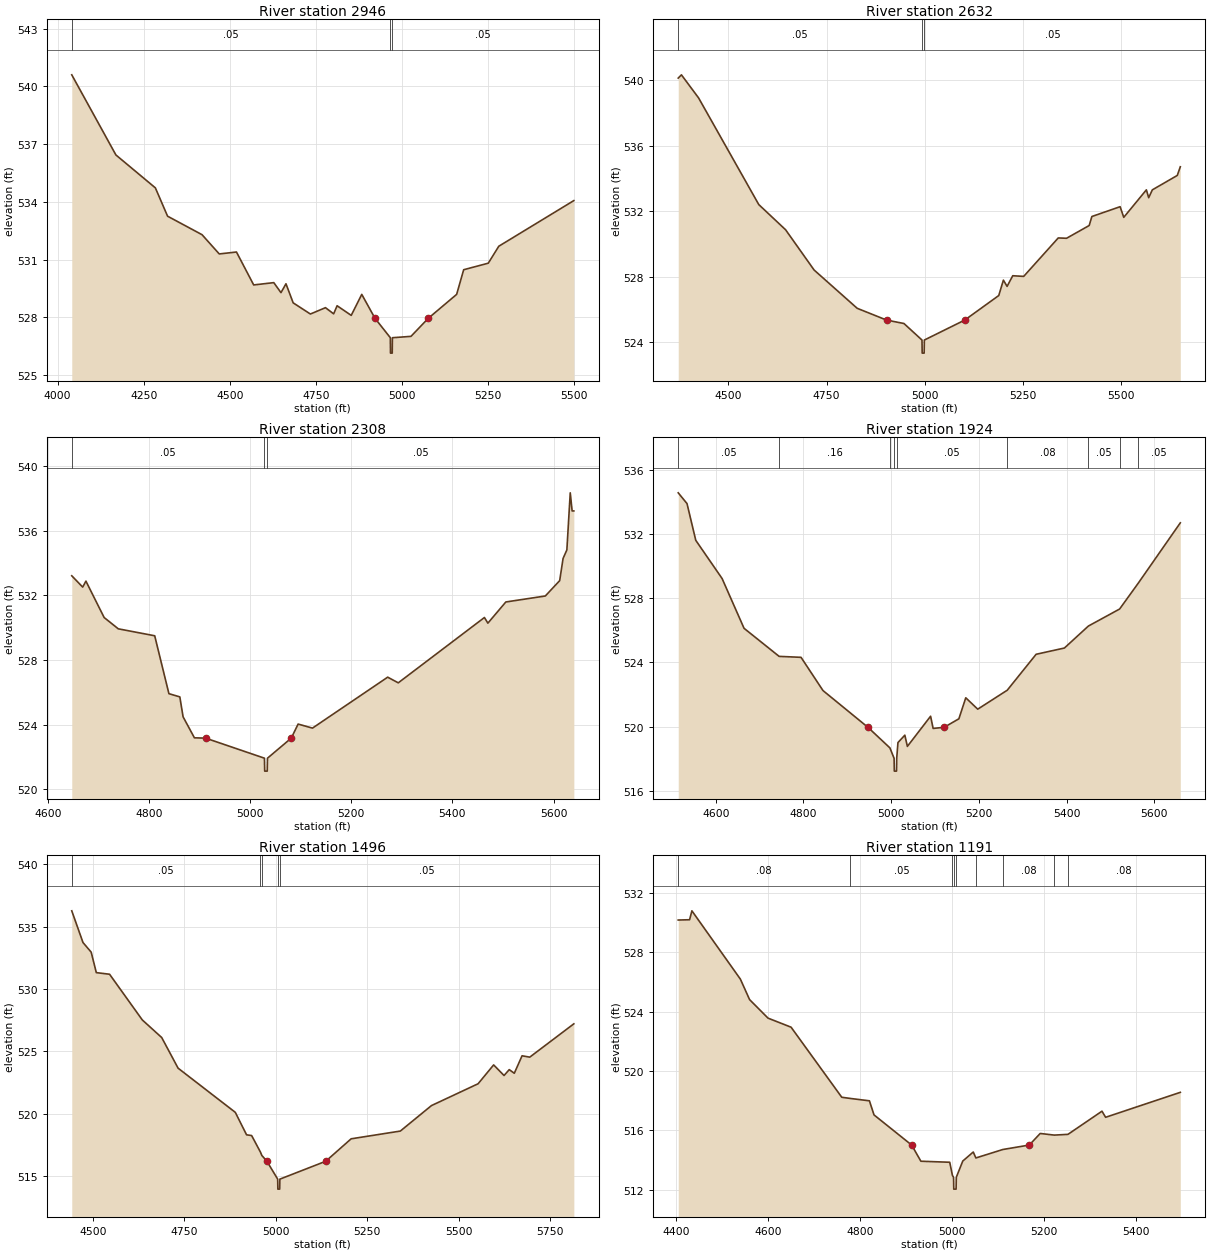
Type RM Length L Ch R = 1,2946,314,314,314
BEGIN DESCRIPTION:
UNT 046 in Running Cr Watershed 6.0
END DESCRIPTION:
XS GIS Cut Line= 3
      2896674.98      7078875.03      2896225.00      7079475.00
      2896364.97      7080168.46
#Sta/Elev= 30
  4041.1  540.60  4169.2  536.44  4283.8  534.73  4319.2  533.26  4419.2  532.30
  4469.2  531.30  4519.2  531.40  4569.2  529.69  4627.5  529.81  4648.4  529.29
  4662.9  529.75  4683.8  528.76  4733.8  528.18  4777.5  528.51  4801.3  528.19
  4811.3  528.61  4852.3  528.11  4882.9  529.20  4921.2  527.96  4965.8  526.95
  4966.3  526.15  4971.3  526.15  4971.8  526.95  5025.7  527.02  5076.1  527.96
  5158.3  529.20  5178.7  530.48  5250.1  530.82  5280.7  531.70  5498.5  534.07
#Mann=3,-1,0
  4041.1    0.05       0  4965.8    0.03       0  4971.8    0.05       0
Bank Sta=4921.2,5076.1
Exp/Cntr=0.3,0.1

Type RM Length L Ch R = 1,2632,324,324,324
BEGIN DESCRIPTION:
UNT 046 in Running Cr Watershed 5.0
END DESCRIPTION:
XS GIS Cut Line= 3
      2895674.98      7079074.96      2895975.00      7079625.00
      2896325.02      7080175.03
#Sta/Elev= 30
  4372.4  540.13  4380.5  540.33  4424.2  538.92  4577.5  532.40  4645.8  530.86
  4718.4  528.40  4828.1  526.06  4903.0  525.34  4947.2  525.13  4993.1  524.12
  4993.6  523.32  4998.6  523.32  4999.1  524.12  5102.0  525.34  5188.6  526.84
  5200.4  527.78  5209.8  527.40  5224.2  528.05  5252.1  528.01  5340.1  530.36
  5361.3  530.34  5418.9  531.12  5425.7  531.67  5497.6  532.27  5506.9  531.62
  5564.5  533.30  5570.4  532.82  5579.7  533.30  5643.2  534.18  5650.9  534.71
#Mann=3,-1,0
  4372.4    0.05       0  4993.1    0.03       0  4999.1    0.05       0
Bank Sta=4903,5102
Exp/Cntr=0.3,0.1

Type RM Length L Ch R = 1,2308,384,384,384
BEGIN DESCRIPTION:
UNT 046 in Running Cr Watershed 4.0
END DESCRIPTION:
XS GIS Cut Line= 3
      2895475.02      7079475.03      2895675.00      7079725.00
      2896175.00      7080175.00
#Sta/Elev= 30
  4647.4  533.20  4669.0  532.50  4675.4  532.87  4711.4  530.62  4739.4  529.92
  4811.4  529.49  4839.5  525.91  4861.1  525.71  4867.5  524.48  4889.9  523.18
  4912.1  523.16  5028.4  521.92  5028.9  521.12  5033.9  521.12  5034.4  521.92
  5081.4  523.16  5095.0  524.03  5123.4  523.78  5272.1  526.93  5293.0  526.58
  5463.4  530.62  5470.2  530.27  5505.7  531.58  5583.8  531.95  5612.2  532.90
  5618.9  534.27  5626.4  534.80  5633.1  538.33  5636.8  537.21  5640.2  537.21
#Mann=3,-1,0
  4647.4    0.05       0  5028.4   0.035       0  5034.4    0.05       0
Bank Sta=4912.1,5081.4
Exp/Cntr=0.3,0.1

Type RM Length L Ch R = 1,1924,428,428,428
BEGIN DESCRIPTION:
UNT 046 in Running Cr Watershed 3.0
END DESCRIPTION:
XS GIS Cut Line= 3
      2895375.00      7079474.98      2895375.00      7079925.00
      2895974.96      7080274.98
#Sta/Elev= 30
  4514.5  534.57  4534.5  533.90  4554.5  531.61  4614.5  529.23  4664.5  526.13
  4744.5  524.38  4794.5  524.32  4844.5  522.25  4947.0  519.96  4997.0  518.68
  5006.6  518.03  5007.1  517.23  5012.1  517.23  5012.6  518.03  5015.4  519.01
  5031.1  519.47  5036.9  518.77  5089.8  520.65  5095.6  519.89  5120.7  519.96
  5154.3  520.49  5170.0  521.80  5197.3  521.09  5264.5  522.27  5330.4  524.51
  5394.9  524.90  5449.6  526.27  5520.7  527.33  5562.7  528.92  5659.1  532.70
#Mann=9,-1,0
  4514.5    0.05       0  4744.5    0.16       0  4997.0    0.05       0
  5006.6   0.035       0  5012.6    0.05       0  5264.5    0.08       0
  5449.6    0.05       0  5520.7    0.08       0  5562.7    0.05       0
Bank Sta=4947,5120.7
Exp/Cntr=0.3,0.1

Type RM Length L Ch R = 1,1496,305,305,305
BEGIN DESCRIPTION:
UNT 046 in Running Cr Watershed 2.0
END DESCRIPTION:
XS GIS Cut Line= 3
      2894775.00      7079525.00      2895025.00      7080025.00
      2895625.03      7080575.03
#Sta/Elev= 30
  4441.8  536.26  4472.5  533.72  4494.9  532.95  4508.9  531.31  4545.2  531.18
  4634.7  527.52  4687.8  526.11  4732.5  523.66  4889.0  520.12  4919.8  518.32
  4933.7  518.26  4957.7  516.94  4961.5  516.67  4975.5  516.20  5004.9  514.77
  5005.4  513.97  5010.4  513.97  5010.9  514.77  5136.2  516.20  5205.8  518.00
  5340.3  518.62  5425.4  520.66  5553.0  522.41  5595.5  523.92  5623.9  523.07
  5638.1  523.54  5652.0  523.25  5673.2  524.65  5694.2  524.54  5814.8  527.21
#Mann=5,-1,0
  4441.8    0.05       0  4957.7    0.16       0  4961.5    0.05       0
  5004.9   0.035       0  5010.9    0.05       0
Bank Sta=4975.5,5136.2
Exp/Cntr=0.3,0.1

Type RM Length L Ch R = 1,1191,74,74,74
BEGIN DESCRIPTION:
Mapping XS 60c80ada
END DESCRIPTION:
XS GIS Cut Line= 4
      2894688.38      7079600.22      2894712.26      7080036.43
      2894827.27      7080279.48      2895071.27      7080577.47
#Sta/Elev= 30
  4405.1  530.17  4429.8  530.19  4434.8  530.79  4540.1  526.19  4560.1  524.81
  4600.2  523.56  4650.3  522.95  4760.4  518.23  4778.9  518.15  4820.5  517.99
  4830.5  517.04  4912.3  515.01  4932.3  513.92  4995.0  513.85  5000.9  512.96
  5003.3  512.84  5003.8  512.04  5008.8  512.04  5009.3  512.84  5023.3  513.93
  5046.1  514.54  5051.8  514.14  5110.4  514.71  5167.9  515.01  5191.6  515.79
  5222.2  515.68  5251.9  515.73  5325.8  517.29  5333.7  516.88  5496.0  518.56
#Mann=9,-1,0
  4405.1    0.08       0  4778.9    0.05       0  5000.9    0.08       0
  5003.3    0.04       0  5009.3    0.08       0  5051.8    0.05       0
  5110.4    0.08       0  5222.2    0.05       0  5251.9    0.08       0
Bank Sta=4912.3,5167.9
Exp/Cntr=0.3,0.1

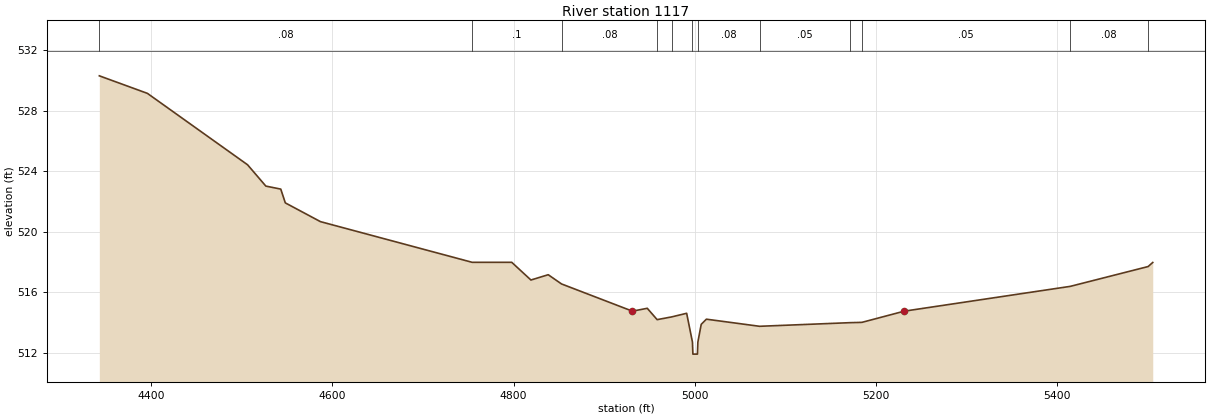
Type RM Length L Ch R = 1,1117,0,0,0
BEGIN DESCRIPTION:
UNT 046 in Running Cr Watershed 1.0
END DESCRIPTION:
XS GIS Cut Line= 4
      2894607.66      7079572.27      2894669.87      7080130.65
      2894861.82      7080479.50      2894998.23      7080630.51
#Sta/Elev= 30
  4342.5  530.32  4395.6  529.16  4506.2  524.44  4526.4  523.03  4542.9  522.83
  4547.9  521.92  4586.7  520.68  4754.3  517.99  4798.0  517.99  4819.2  516.82
  4838.3  517.17  4853.0  516.56  4931.3  514.76  4947.7  514.95  4958.6  514.20
  4974.6  514.38  4991.2  514.62  4997.6  512.72  4998.1  511.92  5003.1  511.92
  5003.6  512.72  5007.3  513.89  5013.0  514.23  5071.7  513.76  5171.8  514.00
  5184.8  514.02  5231.5  514.76  5414.9  516.40  5500.9  517.71  5506.0  517.98
#Mann=12,-1,0
  4342.5    0.08       0  4754.3     0.1       0  4853.0    0.08       0
  4958.6    0.05       0  4974.6    0.08       0  4997.6    0.07       0
  5003.6    0.08       0  5071.7    0.05       0  5171.8    0.08       0
  5184.8    0.05       0  5414.9    0.08       0  5500.9    0.05       0
Bank Sta=4931.3,5231.5
Exp/Cntr=0.3,0.1

Chan Stop Cuts=-1