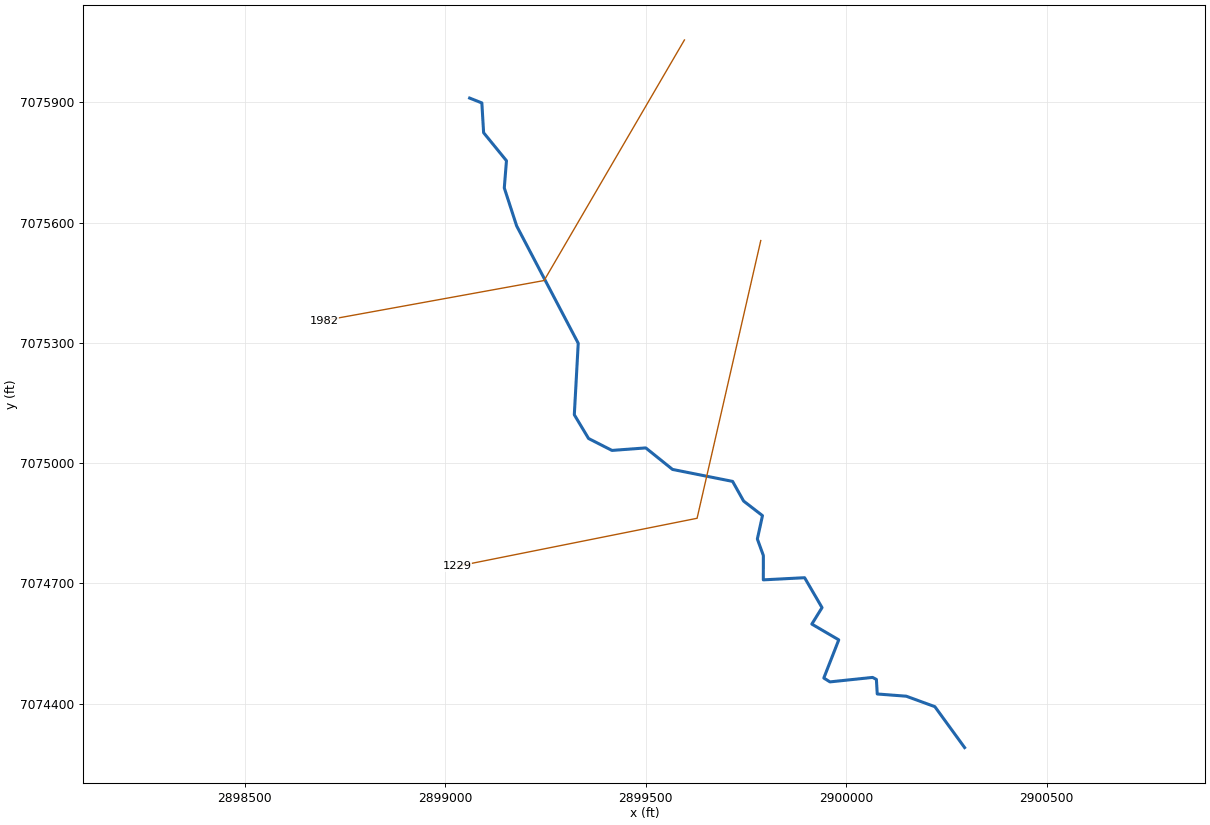
--- UNT 047 in Running Cr Watershed.prj (project) ---

Proj Title=UNT 047 in Running Cr Watershed Base Level Engineering
Current Plan=p01
Default Exp/Contr=0.3,0.1
English Units
Geom File=g01
Flow File=f01
Plan File=p01
BEGIN DESCRIPTION:
UNT 047 in Running Cr Watershed
END DESCRIPTION:

--- UNT 047 in Running Cr Watershed.p01 (plan) ---

Plan Title=Multiple Run
Short Identifier=Multiple
Geom File=g01
Flow File=f01
Subcritical Flow
K Sum by GR= 0
Std Step Tol= 0.01
Critical Tol= 0.01
Num of Std Step Trials= 20
Max Error Tol= 0.3
Flow Tol Ratio= 0.001
Split Flow NTrial= 30
Split Flow Tol= 0.02
Split Flow Ratio= 0.02
Log Output Level= 0
Friction Slope Method= 1
Unsteady Friction Slope Method= 2
Unsteady Bridges Friction Slope Method= 1
Parabolic Critical Depth
Global Vel Dist=  1 , 1 , 1
Global Log Level= 0
CheckData=True
Encroach Param= -1, 0, 0, 0
BEGIN DESCRIPTION:
Multiple Run
END DESCRIPTION:

--- UNT 047 in Running Cr Watershed.f01 (steady flow) ---

Flow Title=Multiple
Number of Profiles=7
Profile Names=10-year,25-year,50-year,1pct_min,100-year,1pct_plu,500-year
River Rch & RM= UNT 047 in Runni,Reach-1,1982
     349     444     518     300     599    1194     796
Boundary for River Rch & Prof#=UNT 047 in Runni,Reach-1,1
Up Type=0
Dn Type=3
Dn Slope=0.005
Boundary for River Rch & Prof#=UNT 047 in Runni,Reach-1,2
Up Type=0
Dn Type=3
Dn Slope=0.005
Boundary for River Rch & Prof#=UNT 047 in Runni,Reach-1,3
Up Type=0
Dn Type=3
Dn Slope=0.005
Boundary for River Rch & Prof#=UNT 047 in Runni,Reach-1,4
Up Type=0
Dn Type=3
Dn Slope=0.005
Boundary for River Rch & Prof#=UNT 047 in Runni,Reach-1,5
Up Type=0
Dn Type=3
Dn Slope=0.005
Boundary for River Rch & Prof#=UNT 047 in Runni,Reach-1,6
Up Type=0
Dn Type=3
Dn Slope=0.005
Boundary for River Rch & Prof#=UNT 047 in Runni,Reach-1,7
Up Type=0
Dn Type=3
Dn Slope=0.005

--- UNT 047 in Running Cr Watershed.g01 (geometry) ---

Geom Title=Existing Conditions

River Reach=UNT 047 in Runni,Reach-1
Reach XY= 30
      2899061.07      7075910.67      2899091.52      7075898.55
      2899095.94      7075824.27      2899152.91      7075754.42
      2899147.50      7075686.57      2899178.31      7075591.84
      2899331.91      7075299.07      2899322.14      7075120.83
      2899357.65      7075061.61      2899416.04      7075031.86
      2899500.37      7075038.13      2899567.12      7074984.45
      2899716.91      7074954.61      2899744.42      7074905.54
      2899791.46      7074869.23      2899778.68      7074810.91
      2899793.66      7074769.74      2899793.58      7074709.05
      2899896.56      7074714.36      2899940.01      7074639.76
      2899914.54      7074598.73      2899981.72      7074559.38
      2899944.43      7074464.15      2899959.73      7074454.54
      2900066.05      7074465.70      2900075.59      7074460.71
      2900077.72      7074424.39      2900150.06      7074418.84
      2900221.43      7074392.75      2900295.59      7074290.71

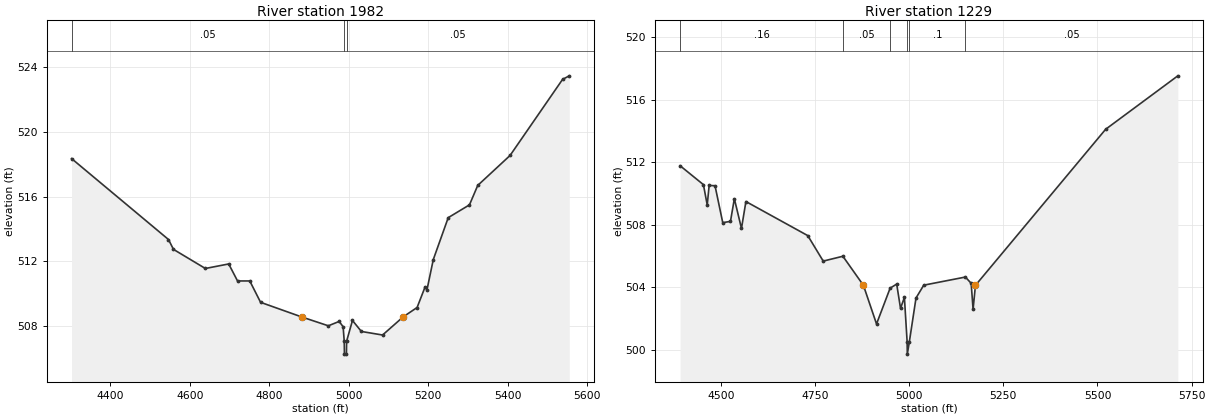
Type RM Length L Ch R = 1,1982,753,753,753
BEGIN DESCRIPTION:
UNT 047 in Running Cr Watershed 2.0
END DESCRIPTION:
XS GIS Cut Line= 3
      2899596.79      7076055.61      2899246.79      7075455.60
      2898698.40      7075355.90
#Sta/Elev= 30
  4302.8  518.35  4546.6  513.35  4559.2  512.74  4639.4  511.56  4698.1  511.84
  4720.3  510.79  4751.1  510.79  4778.3  509.47  4881.3  508.57  4948.7  508.02
  4976.0  508.29  4985.9  507.96  4988.7  507.07  4989.2  506.27  4994.2  506.27
  4994.7  507.07  5009.4  508.35  5031.8  507.67  5085.1  507.45  5136.9  508.57
  5172.0  509.15  5191.9  510.41  5196.9  510.25  5212.7  512.11  5250.3  514.70
  5303.7  515.49  5324.5  516.69  5405.8  518.54  5537.9  523.24  5554.8  523.46
#Mann=3,-1,0
  4302.8    0.05       0  4988.7    0.03       0  4994.7    0.05       0
Bank Sta=4881.3,5136.9
Exp/Cntr=0.3,0.1

Type RM Length L Ch R = 1,1229,0,0,0
BEGIN DESCRIPTION:
UNT 047 in Running Cr Watershed 1.0
END DESCRIPTION:
XS GIS Cut Line= 3
      2899787.19      7075555.32      2899628.33      7074862.61
      2899029.69      7074742.88
#Sta/Elev= 30
  4392.2  511.77  4454.1  510.56  4464.2  509.26  4469.3  510.51  4484.9  510.49
  4505.4  508.13  4525.9  508.21  4536.2  509.66  4555.1  507.76  4566.9  509.48
  4731.1  507.30  4772.1  505.67  4824.3  505.98  4878.8  504.12  4913.6  501.65
  4949.7  503.94  4967.1  504.20  4977.3  502.65  4987.6  503.35  4994.8  500.52
  4995.3  499.72  5000.8  500.52  5018.4  503.31  5038.9  504.13  5149.5  504.65
  5164.8  504.25  5169.9  502.59  5176.2  504.12  5521.7  514.10  5713.4  517.52
#Mann=6,-1,0
  4392.2    0.16       0  4824.3    0.05       0  4949.7     0.1       0
  4994.8    0.07       0  5000.8     0.1       0  5149.5    0.05       0
Bank Sta=4878.8,5176.2
Exp/Cntr=0.3,0.1

Chan Stop Cuts=-1