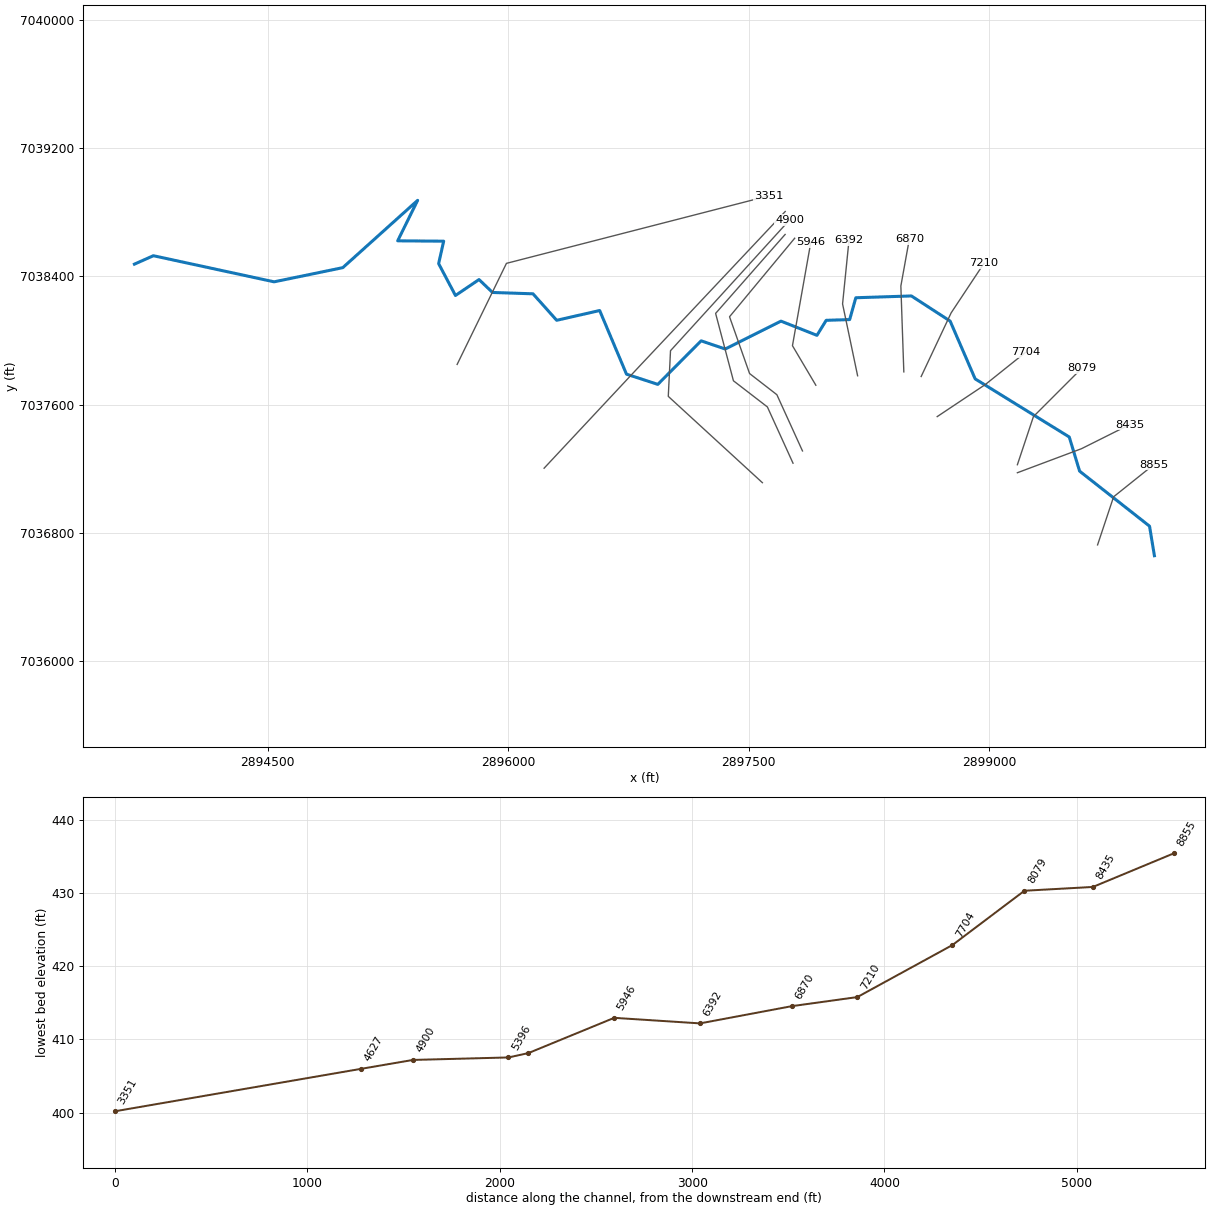
--- UNT 048 in Running Cr Watershed.prj (project) ---

Proj Title=UNT 048 in Running Cr Watershed Base Level Engineering
Current Plan=p01
Default Exp/Contr=0.3,0.1
English Units
Geom File=g01
Flow File=f01
Plan File=p01
BEGIN DESCRIPTION:
UNT 048 in Running Cr Watershed
END DESCRIPTION:

--- UNT 048 in Running Cr Watershed.p01 (plan) ---

Plan Title=Multiple Run
Short Identifier=Multiple
Geom File=g01
Flow File=f01
Subcritical Flow
K Sum by GR= 0
Std Step Tol= 0.01
Critical Tol= 0.01
Num of Std Step Trials= 20
Max Error Tol= 0.3
Flow Tol Ratio= 0.001
Split Flow NTrial= 30
Split Flow Tol= 0.02
Split Flow Ratio= 0.02
Log Output Level= 0
Friction Slope Method= 1
Unsteady Friction Slope Method= 2
Unsteady Bridges Friction Slope Method= 1
Parabolic Critical Depth
Global Vel Dist=  1 , 1 , 1
Global Log Level= 0
CheckData=True
Encroach Param= -1, 0, 0, 0
BEGIN DESCRIPTION:
Multiple Run
END DESCRIPTION:

--- UNT 048 in Running Cr Watershed.f01 (steady flow) ---

Flow Title=Multiple
Number of Profiles=7
Profile Names=10-year,25-year,50-year,1pct_min,100-year,1pct_plu,500-year
River Rch & RM= UNT 048 in Runni,Reach-1,8855
     582     783     948     571    1138    2271    1645
River Rch & RM= UNT 048 in Runni,Reach-1,3351
     750    1021    1244     754    1504    3001    2200
Boundary for River Rch & Prof#=UNT 048 in Runni,Reach-1,1
Up Type=0
Dn Type=3
Dn Slope=0.005
Boundary for River Rch & Prof#=UNT 048 in Runni,Reach-1,2
Up Type=0
Dn Type=3
Dn Slope=0.005
Boundary for River Rch & Prof#=UNT 048 in Runni,Reach-1,3
Up Type=0
Dn Type=3
Dn Slope=0.005
Boundary for River Rch & Prof#=UNT 048 in Runni,Reach-1,4
Up Type=0
Dn Type=3
Dn Slope=0.005
Boundary for River Rch & Prof#=UNT 048 in Runni,Reach-1,5
Up Type=0
Dn Type=3
Dn Slope=0.005
Boundary for River Rch & Prof#=UNT 048 in Runni,Reach-1,6
Up Type=0
Dn Type=3
Dn Slope=0.005
Boundary for River Rch & Prof#=UNT 048 in Runni,Reach-1,7
Up Type=0
Dn Type=3
Dn Slope=0.005

--- UNT 048 in Running Cr Watershed.g01 (geometry) ---

Geom Title=Existing Conditions

River Reach=UNT 048 in Runni,Reach-1
Reach XY= 30
      2900029.44      7036657.42      2899998.98      7036841.95
      2899562.97      7037184.88      2899498.36      7037397.89
      2898911.61      7037760.33      2898755.59      7038120.71
      2898514.02      7038277.39      2898167.44      7038266.15
      2898129.12      7038129.95      2897982.84      7038125.40
      2897925.12      7038031.77      2897700.73      7038120.36
      2897353.31      7037946.41      2897202.86      7037997.50
      2896932.75      7037725.98      2896737.51      7037789.66
      2896570.26      7038186.44      2896302.25      7038125.56
      2896154.60      7038290.70      2895901.98      7038299.10
      2895818.00      7038379.58      2895671.05      7038280.21
      2895566.08      7038478.94      2895597.57      7038618.90
      2895310.66      7038621.00      2895435.22      7038873.62
      2894968.47      7038453.75      2894540.20      7038365.41
      2893787.38      7038528.23      2893669.11      7038475.65

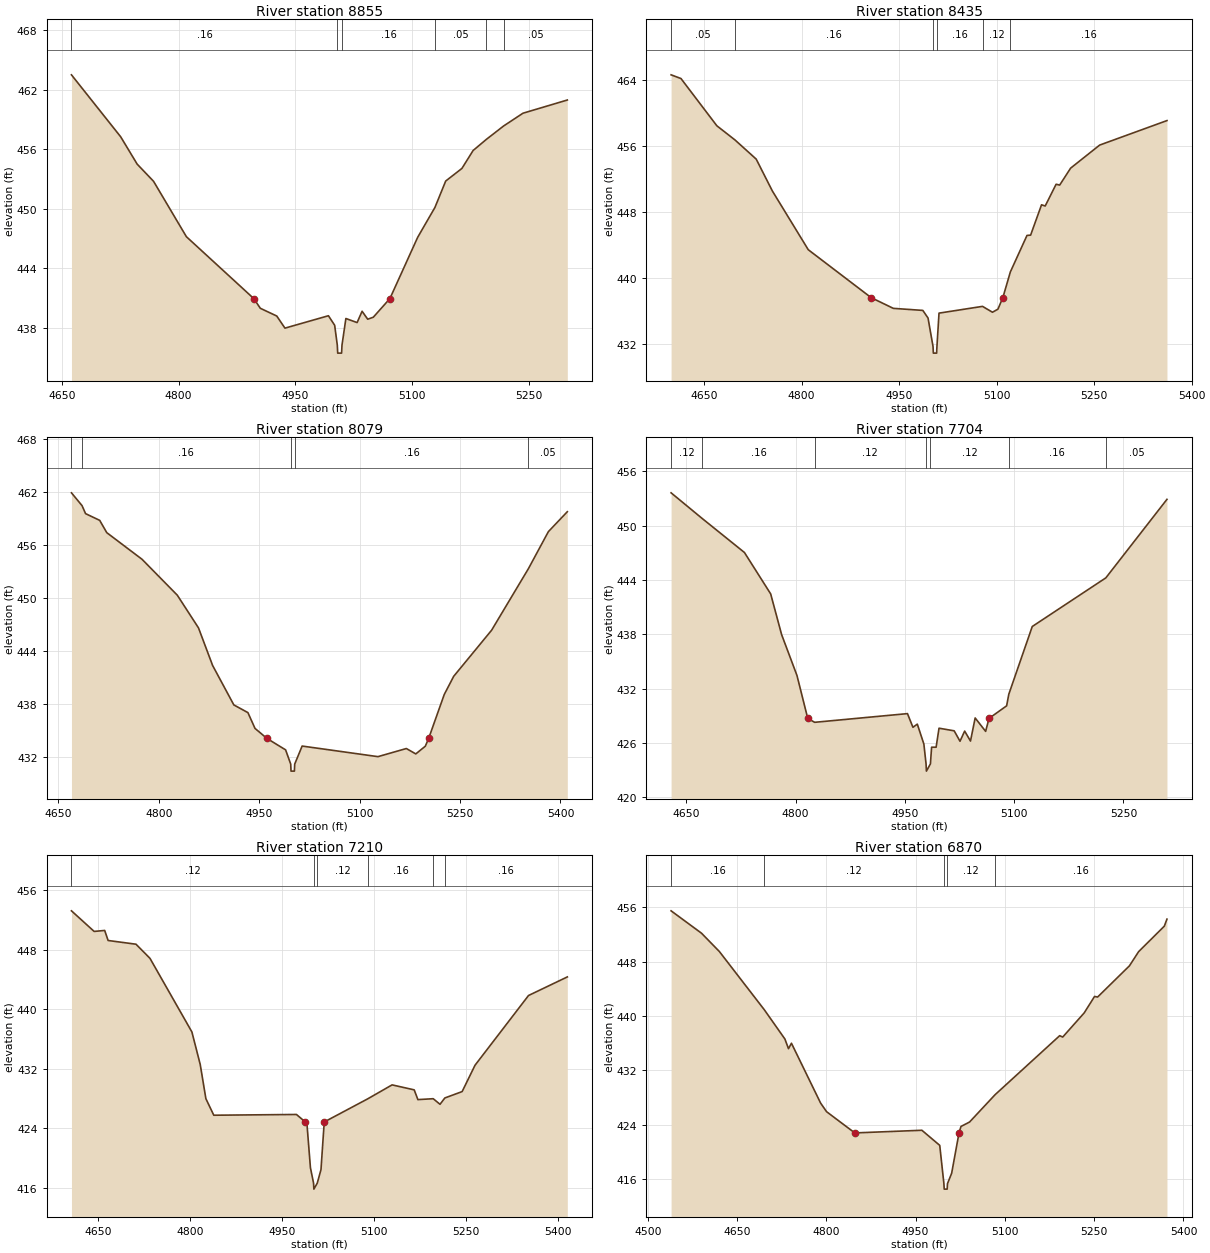
Type RM Length L Ch R = 1,8855,420,420,420
BEGIN DESCRIPTION:
UNT 048 in Running Cr Watershed 11.0
END DESCRIPTION:
XS GIS Cut Line= 3
      2899675.01      7036725.02      2899775.00      7037025.00
      2900025.03      7037225.03
#Sta/Elev= 30
  4662.5  463.52  4725.7  457.27  4746.8  454.52  4767.9  452.78  4810.0  447.20
  4896.5  440.96  4904.9  439.98  4926.0  439.20  4936.5  437.98  4992.3  439.23
  5000.3  438.27  5003.7  436.26  5004.2  435.46  5009.2  435.46  5009.7  436.26
  5014.7  438.95  5029.1  438.54  5035.5  439.68  5042.7  438.88  5049.9  439.08
  5071.2  440.96  5106.8  447.13  5129.0  450.15  5142.8  452.81  5163.6  454.08
  5178.0  455.89  5194.8  457.00  5217.1  458.36  5242.0  459.65  5298.9  460.98
#Mann=6,-1,0
  4662.5    0.16       0  5003.7    0.07       0  5009.7    0.16       0
  5129.0    0.05       0  5194.8    0.12       0  5217.1    0.05       0
Bank Sta=4896.5,5071.2
Exp/Cntr=0.3,0.1

Type RM Length L Ch R = 1,8435,356,356,356
BEGIN DESCRIPTION:
UNT 048 in Running Cr Watershed 10.0
END DESCRIPTION:
XS GIS Cut Line= 3
      2899174.96      7037174.98      2899575.00      7037325.00
      2899875.04      7037475.02
#Sta/Elev= 30
  4599.3  464.62  4614.5  464.17  4669.7  458.44  4697.6  456.72  4730.2  454.40
  4755.1  450.53  4810.3  443.41  4907.0  437.60  4941.1  436.30  4986.5  436.05
  4994.5  435.13  5002.2  431.67  5002.7  430.87  5007.7  430.87  5008.2  431.67
  5011.4  435.72  5078.3  436.54  5093.6  435.83  5102.0  436.20  5109.6  437.60
  5121.1  440.71  5146.7  445.14  5152.3  445.18  5169.1  448.86  5174.7  448.71
  5191.5  451.35  5197.0  451.25  5213.8  453.30  5258.5  456.10  5362.0  459.07
#Mann=6,-1,0
  4599.3    0.05       0  4697.6    0.16       0  5002.2    0.07       0
  5008.2    0.16       0  5078.3    0.12       0  5121.1    0.16       0
Bank Sta=4907,5109.6
Exp/Cntr=0.3,0.1

Type RM Length L Ch R = 1,8079,375,375,375
BEGIN DESCRIPTION:
UNT 048 in Running Cr Watershed 9.0
END DESCRIPTION:
XS GIS Cut Line= 3
      2899175.00      7037224.99      2899275.00      7037525.00
      2899575.00      7037825.00
#Sta/Elev= 30
  4669.7  461.88  4685.5  460.43  4690.8  459.52  4711.9  458.76  4722.4  457.37
  4775.1  454.35  4827.8  450.28  4859.4  446.58  4880.5  442.32  4912.2  437.85
  4933.2  436.98  4943.8  435.19  4961.7  434.05  4989.5  432.76  4997.1  431.15
  4997.6  430.35  5002.6  430.35  5003.1  431.15  5014.2  433.19  5127.4  431.99
  5169.8  432.91  5183.9  432.30  5198.1  433.17  5203.1  434.05  5226.4  439.03
  5240.5  441.09  5297.1  446.31  5352.2  453.30  5381.9  457.48  5410.2  459.74
#Mann=5,-1,0
  4669.7    0.05       0  4685.5    0.16       0  4997.1    0.07       0
  5003.1    0.16       0  5352.2    0.05       0
Bank Sta=4961.7,5203.1
Exp/Cntr=0.3,0.1

Type RM Length L Ch R = 1,7704,494,494,494
BEGIN DESCRIPTION:
UNT 048 in Running Cr Watershed 8.0
END DESCRIPTION:
XS GIS Cut Line= 3
      2898675.00      7037525.00      2898975.00      7037725.00
      2899224.99      7037924.99
#Sta/Elev= 30
  4629.0  453.64  4671.8  450.80  4729.7  447.05  4765.7  442.48  4780.7  437.99
  4801.8  433.47  4816.6  428.73  4826.1  428.30  4953.5  429.26  4961.0  427.75
  4967.0  428.10  4976.0  425.90  4979.0  423.71  4979.5  422.91  4985.0  423.71
  4986.6  425.55  4992.8  425.55  4996.8  427.65  5017.6  427.36  5025.6  426.21
  5032.0  427.33  5040.0  426.23  5046.4  428.78  5060.8  427.30  5065.4  428.73
  5089.6  430.12  5092.6  431.40  5124.8  438.88  5225.8  444.25  5309.7  452.92
#Mann=7,-1,0
  4629.0    0.12       0  4671.8    0.16       0  4826.1    0.12       0
  4979.0    0.07       0  4985.0    0.12       0  5092.6    0.16       0
  5225.8    0.05       0
Bank Sta=4816.6,5065.4
Exp/Cntr=0.3,0.1

Type RM Length L Ch R = 1,7210,340,340,340
BEGIN DESCRIPTION:
UNT 048 in Running Cr Watershed 7.0
END DESCRIPTION:
XS GIS Cut Line= 3
      2898574.99      7037774.97      2898761.98      7038172.01
      2898966.49      7038480.51
#Sta/Elev= 30
  4605.9  453.23  4642.9  450.46  4660.1  450.59  4665.7  449.24  4711.2  448.74
  4734.0  446.84  4802.4  436.94  4816.0  432.56  4825.2  427.97  4838.1  425.74
  4973.0  425.84  4987.4  424.83  4990.2  424.48  4995.8  418.67  5000.9  416.60
  5001.4  415.80  5006.9  416.60  5013.0  418.42  5018.3  424.83  5089.4  427.95
  5129.0  429.82  5165.1  429.15  5171.1  427.84  5196.1  427.96  5207.2  427.21
  5215.1  428.06  5243.3  428.92  5264.3  432.46  5351.6  441.84  5414.9  444.34
#Mann=6,-1,0
  4605.9    0.12       0  5000.9    0.07       0  5006.9    0.12       0
  5089.4    0.16       0  5196.1    0.12       0  5215.1    0.16       0
Bank Sta=4987.4,5018.3
Exp/Cntr=0.3,0.1

Type RM Length L Ch R = 1,6870,478,478,478
BEGIN DESCRIPTION:
UNT 048 in Running Cr Watershed 6.0
END DESCRIPTION:
XS GIS Cut Line= 3
      2898466.85      7037803.93      2898448.34      7038339.28
      2898501.22      7038631.88
#Sta/Elev= 30
  4539.3  455.46  4590.4  452.17  4620.4  449.48  4695.9  440.92  4730.5  436.62
  4736.5  435.20  4741.5  436.00  4790.5  427.20  4800.5  425.94  4847.9  422.82
  4960.6  423.21  4990.6  420.99  4997.6  415.36  4998.1  414.56  5003.1  414.56
  5003.6  415.36  5010.6  416.89  5023.0  422.82  5026.3  423.77  5040.7  424.42
  5083.6  428.44  5192.1  437.11  5197.2  436.91  5233.2  440.45  5250.7  442.88
  5255.8  442.79  5309.3  447.38  5324.7  449.46  5367.9  453.21  5372.3  454.24
#Mann=5,-1,0
  4539.3    0.16       0  4695.9    0.12       0  4997.6    0.07       0
  5003.6    0.12       0  5083.6    0.16       0
Bank Sta=4847.9,5023
Exp/Cntr=0.3,0.1

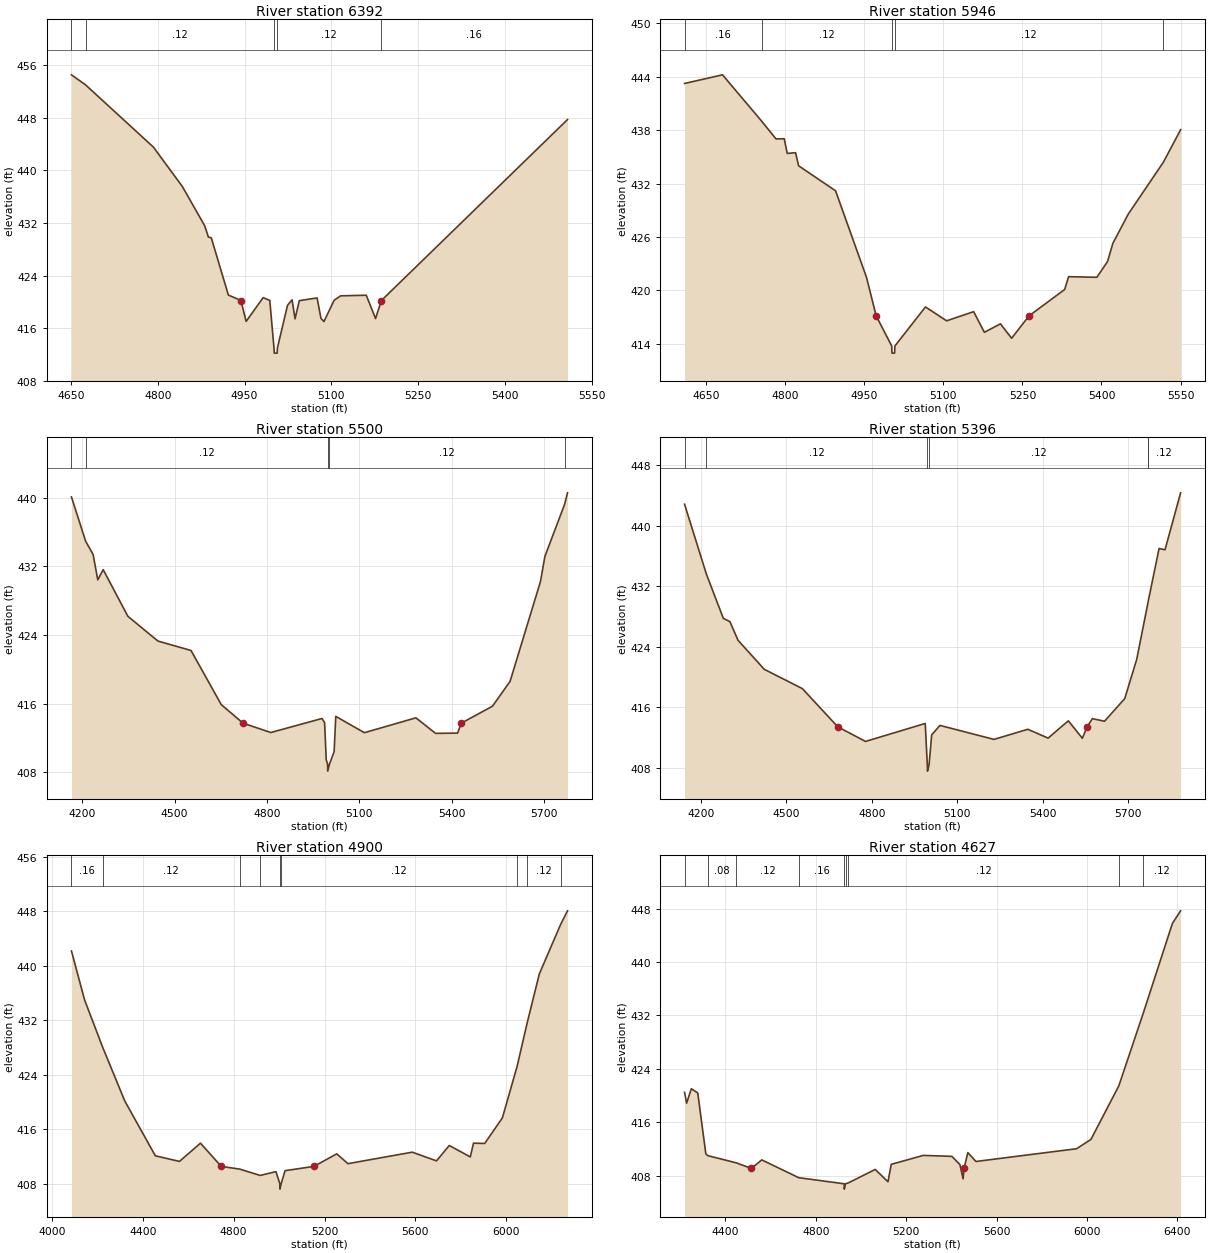
Type RM Length L Ch R = 1,6392,446,446,446
BEGIN DESCRIPTION:
UNT 048 in Running Cr Watershed 5.0
END DESCRIPTION:
XS GIS Cut Line= 3
      2898178.66      7037779.60      2898084.90      7038227.56
      2898125.00      7038624.98
#Sta/Elev= 30
  4650.9  454.51  4675.3  452.98  4792.6  443.51  4842.5  437.53  4881.2  431.55
  4887.4  429.86  4892.5  429.73  4922.0  421.03  4943.7  420.20  4952.7  417.02
  4982.1  420.64  4993.6  420.21  5000.8  413.00  5001.3  412.20  5006.3  412.20
  5006.8  413.00  5024.2  419.47  5032.1  420.31  5037.2  417.42  5044.6  420.18
  5075.3  420.59  5082.0  417.48  5087.2  417.00  5104.7  420.23  5116.0  420.91
  5160.3  421.00  5176.3  417.46  5184.9  419.79  5186.4  420.20  5508.0  447.71
#Mann=5,-1,0
  4650.9    0.16       0  4675.3    0.12       0  5000.8    0.07       0
  5006.8    0.12       0  5184.9    0.16       0
Bank Sta=4943.7,5186.4
Exp/Cntr=0.3,0.1

Type RM Length L Ch R = 1,5946,446,446,446
BEGIN DESCRIPTION:
UNT 048 in Running Cr Watershed 4.0
END DESCRIPTION:
XS GIS Cut Line= 3
      2897918.21      7037720.65      2897772.40      7037967.15
      2897886.72      7038611.49
#Sta/Elev= 30
  4609.3  443.26  4681.3  444.23  4755.7  439.01  4782.7  437.03  4798.3  437.05
  4804.1  435.40  4819.8  435.48  4825.6  434.01  4895.7  431.20  4954.4  421.47
  4972.7  417.15  5002.2  413.76  5002.7  412.96  5007.7  412.96  5008.2  413.76
  5066.2  418.15  5106.3  416.59  5157.6  417.62  5177.9  415.30  5208.4  416.25
  5229.6  414.63  5262.7  417.15  5330.2  420.11  5337.6  421.55  5391.2  421.48
  5411.5  423.25  5421.6  425.29  5450.7  428.57  5517.5  434.42  5550.1  438.06
#Mann=5,-1,0
  4609.3    0.16       0  4755.7    0.12       0  5002.2    0.07       0
  5008.2    0.12       0  5517.5    0.16       0
Bank Sta=4972.7,5262.7
Exp/Cntr=0.3,0.1

Type RM Length L Ch R = 1,5500,104,104,104
BEGIN DESCRIPTION:
Mapping XS a23f16bc
END DESCRIPTION:
XS GIS Cut Line= 5
      2897834.89      7037310.92      2897675.18      7037661.59
      2897505.04      7037793.54      2897380.04      7038147.70
      2897786.29      7038637.29
#Sta/Elev= 30
  4164.6  440.09  4210.6  434.94  4235.0  433.38  4250.1  430.43  4267.7  431.62
  4347.8  426.19  4445.5  423.30  4553.2  422.20  4651.5  415.89  4722.2  413.73
  4812.5  412.64  4978.9  414.27  4987.4  413.79  4992.7  409.47  4997.1  408.94
  4997.6  408.14  5003.1  408.94  5018.4  410.41  5023.7  414.52  5116.7  412.62
  5284.2  414.35  5348.0  412.54  5419.7  412.57  5431.6  413.73  5532.9  415.70
  5590.3  418.60  5689.2  430.25  5703.5  433.16  5767.6  439.24  5777.0  440.57
#Mann=5,-1,0
  4164.6    0.16       0  4210.6    0.12       0  4997.1    0.07       0
  5003.1    0.12       0  5767.6    0.16       0
Bank Sta=4722.2,5431.6
Exp/Cntr=0.3,0.1

Type RM Length L Ch R = 1,5396,496,496,496
BEGIN DESCRIPTION:
Mapping XS 38a2de5e
END DESCRIPTION:
XS GIS Cut Line= 5
      2897775.86      7037234.54      2897616.15      7037585.20
      2897404.35      7037748.40      2897293.23      7038168.54
      2897726.56      7038660.79
#Sta/Elev= 30
  4142.2  442.87  4218.9  433.62  4278.5  427.76  4301.6  427.33  4330.1  424.86
  4422.3  421.02  4556.2  418.46  4680.5  413.41  4778.1  411.47  4987.9  413.85
  4995.3  408.34  4995.8  407.54  5001.3  408.34  5010.6  412.34  5039.6  413.59
  5229.5  411.74  5348.5  413.08  5419.7  411.91  5490.8  414.20  5540.1  411.89
  5556.7  413.41  5575.3  414.49  5617.9  414.14  5689.1  417.15  5731.0  422.33
  5769.8  429.68  5770.1  429.77  5809.6  437.01  5830.5  436.84  5885.3  444.38
#Mann=6,-1,0
  4142.2    0.16       0  4218.9    0.12       0  4995.3    0.07       0
  5001.3    0.12       0  5769.8    0.16       0  5770.1    0.12       0
Bank Sta=4680.5,5556.7
Exp/Cntr=0.3,0.1

Type RM Length L Ch R = 1,4900,273,273,273
BEGIN DESCRIPTION:
UNT 048 in Running Cr Watershed 3.0
END DESCRIPTION:
XS GIS Cut Line= 4
      2897584.90      7037112.98      2896998.10      7037651.18
      2897011.98      7037935.90      2897754.17      7038750.91
#Sta/Elev= 30
  4086.0  442.18  4143.8  434.99  4222.6  428.10  4320.8  420.14  4455.2  412.10
  4561.3  411.27  4653.8  413.95  4745.4  410.54  4826.5  410.14  4916.7  409.21
  4986.2  409.77  5003.2  408.00  5003.7  407.20  5009.2  408.00  5026.2  409.91
  5153.5  410.54  5253.7  412.38  5303.1  410.94  5586.2  412.63  5692.9  411.35
  5749.0  413.61  5841.6  411.93  5855.7  413.95  5905.1  413.91  5982.8  417.66
  6047.6  425.22  6092.6  431.70  6145.6  438.82  6239.0  446.06  6269.6  448.08
#Mann=9,-1,0
  4086.0    0.16       0  4222.6    0.12       0  4826.5    0.16       0
  4916.7    0.12       0  5003.2    0.07       0  5009.2    0.12       0
  6047.6    0.16       0  6092.6    0.12       0  6239.0    0.16       0
Bank Sta=4745.4,5153.5
Exp/Cntr=0.3,0.1

Type RM Length L Ch R = 1,4627,1276,1276,1276
BEGIN DESCRIPTION:
UNT 048 in Running Cr Watershed 2.0
END DESCRIPTION:
XS GIS Cut Line= 3
      2896223.81      7037203.28      2896824.48      7037845.62
      2897727.24      7038803.93
#Sta/Elev= 30
  4218.8  420.47  4227.9  418.85  4248.9  421.01  4277.3  420.37  4312.9  411.26
  4321.5  410.99  4447.5  409.91  4514.6  409.07  4560.6  410.35  4724.6  407.68
  4925.4  406.77  4925.9  405.97  4931.4  406.77  4944.3  406.91  5062.8  408.92
  5119.4  407.07  5133.6  409.68  5275.2  411.02  5402.2  410.88  5437.8  409.65
  5452.0  407.51  5455.8  409.07  5473.0  411.44  5508.6  410.11  5954.1  412.02
  6017.9  413.42  6141.4  421.45  6249.1  432.29  6378.5  445.78  6414.8  447.66
#Mann=9,-1,0
  4218.8    0.05       0  4321.5    0.08       0  4447.5    0.12       0
  4724.6    0.16       0  4925.4    0.07       0  4931.4    0.16       0
  4944.3    0.12       0  6141.4    0.16       0  6249.1    0.12       0
Bank Sta=4514.6,5455.8
Exp/Cntr=0.3,0.1

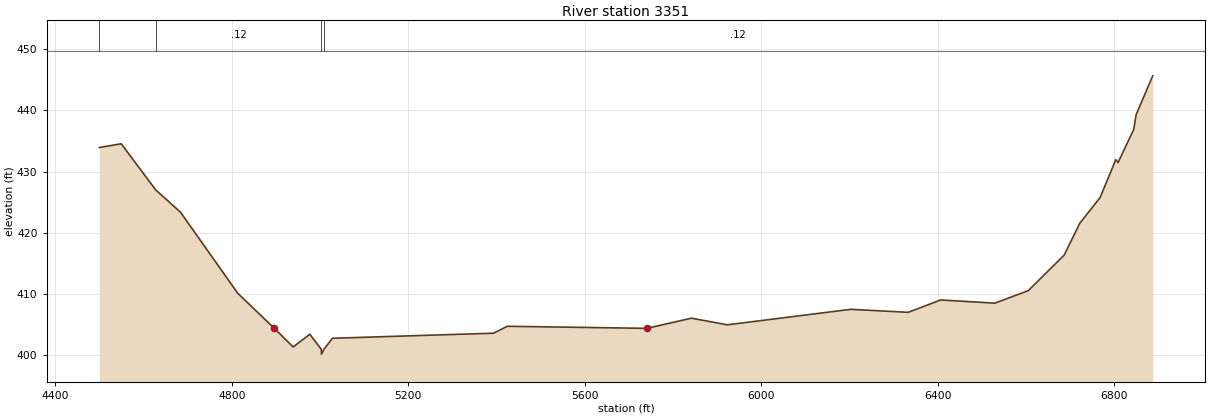
Type RM Length L Ch R = 1,3351,0,0,0
BEGIN DESCRIPTION:
UNT 048 in Running Cr Watershed 1.0
END DESCRIPTION:
XS GIS Cut Line= 3
      2895681.42      7037850.30      2895988.89      7038480.56
      2897621.52      7038900.77
#Sta/Elev= 30
  4499.9  433.94  4549.6  434.55  4627.2  427.05  4683.9  423.36  4813.5  410.13
  4896.5  404.39  4939.1  401.35  4976.8  403.43  5002.8  400.98  5003.3  400.18
  5008.9  400.98  5028.1  402.77  5393.3  403.60  5424.3  404.73  5740.3  404.39
  5841.7  406.05  5923.1  404.97  6202.9  407.50  6333.0  407.01  6406.5  409.03
  6529.2  408.51  6604.9  410.55  6686.3  416.36  6721.8  421.58  6767.7  425.76
  6803.2  431.95  6808.4  431.48  6844.0  436.91  6849.3  439.29  6887.0  445.65
#Mann=4,-1,0
  4499.9    0.16       0  4627.2    0.12       0  5002.8    0.07       0
  5008.9    0.12       0
Bank Sta=4896.5,5740.3
Exp/Cntr=0.3,0.1

Chan Stop Cuts=-1