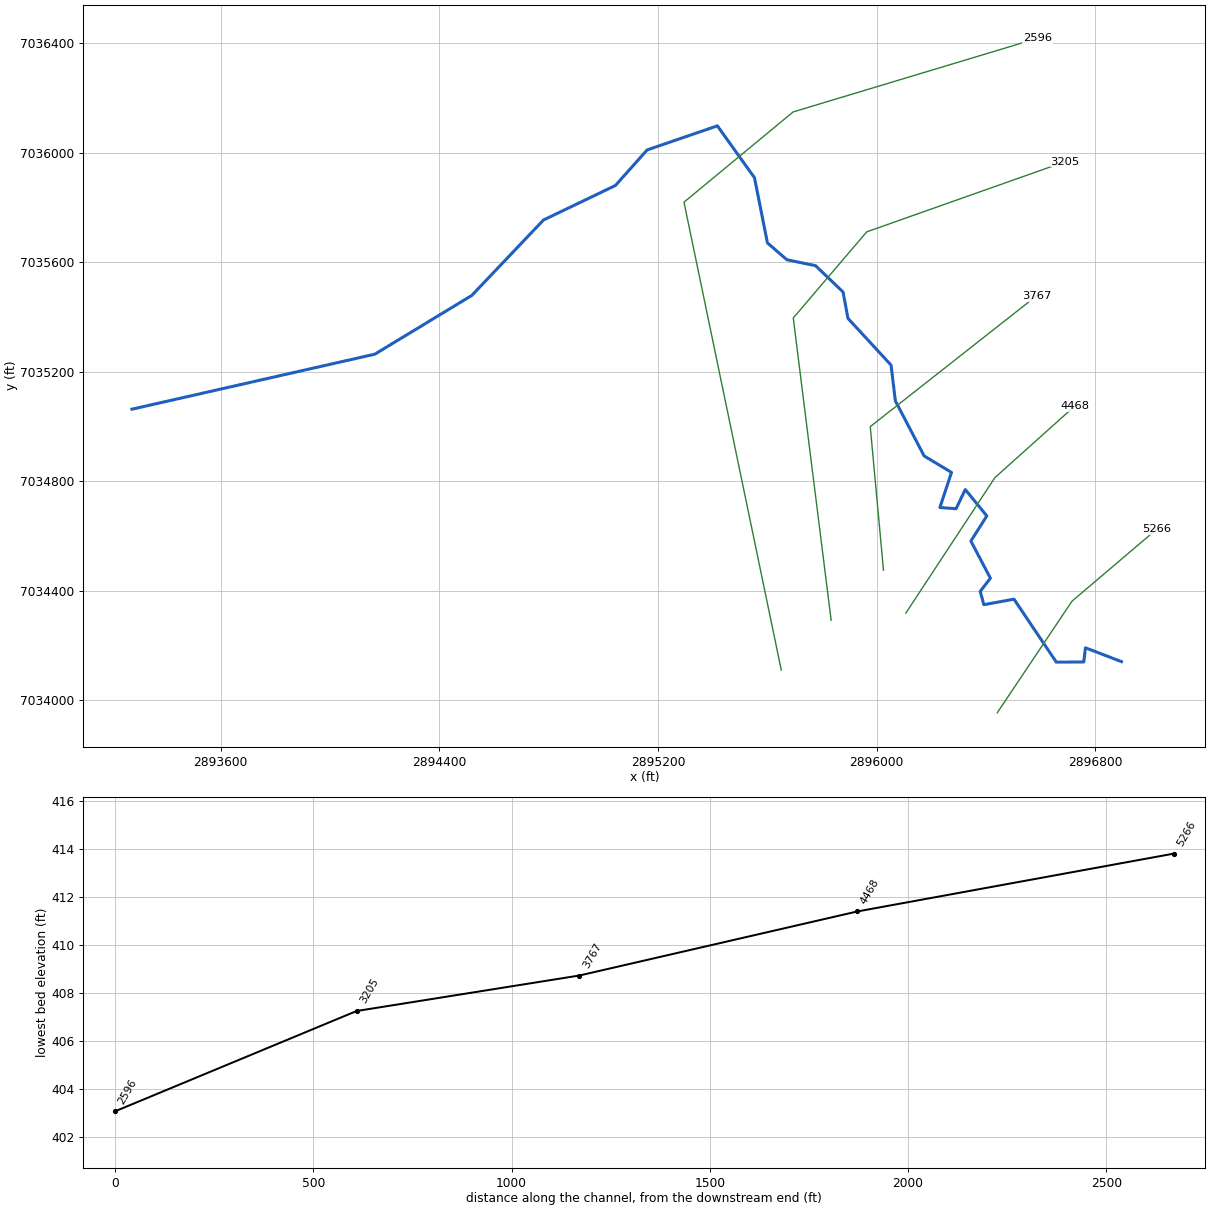
--- UNT 049 in Running Cr Watershed.prj (project) ---

Proj Title=UNT 049 in Running Cr Watershed Base Level Engineering
Current Plan=p01
Default Exp/Contr=0.3,0.1
English Units
Geom File=g01
Flow File=f01
Plan File=p01
BEGIN DESCRIPTION:
UNT 049 in Running Cr Watershed
END DESCRIPTION:

--- UNT 049 in Running Cr Watershed.p01 (plan) ---

Plan Title=Multiple Run
Short Identifier=Multiple
Geom File=g01
Flow File=f01
Subcritical Flow
K Sum by GR= 0
Std Step Tol= 0.01
Critical Tol= 0.01
Num of Std Step Trials= 20
Max Error Tol= 0.3
Flow Tol Ratio= 0.001
Split Flow NTrial= 30
Split Flow Tol= 0.02
Split Flow Ratio= 0.02
Log Output Level= 0
Friction Slope Method= 1
Unsteady Friction Slope Method= 2
Unsteady Bridges Friction Slope Method= 1
Parabolic Critical Depth
Global Vel Dist=  1 , 1 , 1
Global Log Level= 0
CheckData=True
Encroach Param= -1, 0, 0, 0
BEGIN DESCRIPTION:
Multiple Run
END DESCRIPTION:

--- UNT 049 in Running Cr Watershed.f01 (steady flow) ---

Flow Title=Multiple
Number of Profiles=7
Profile Names=10-year,25-year,50-year,1pct_min,100-year,1pct_plu,500-year
River Rch & RM= UNT 049 in Runni,Reach-1,5266
     673     916    1118     679    1354    2703    1991
Boundary for River Rch & Prof#=UNT 049 in Runni,Reach-1,1
Up Type=0
Dn Type=3
Dn Slope=0.005
Boundary for River Rch & Prof#=UNT 049 in Runni,Reach-1,2
Up Type=0
Dn Type=3
Dn Slope=0.005
Boundary for River Rch & Prof#=UNT 049 in Runni,Reach-1,3
Up Type=0
Dn Type=3
Dn Slope=0.005
Boundary for River Rch & Prof#=UNT 049 in Runni,Reach-1,4
Up Type=0
Dn Type=3
Dn Slope=0.005
Boundary for River Rch & Prof#=UNT 049 in Runni,Reach-1,5
Up Type=0
Dn Type=3
Dn Slope=0.005
Boundary for River Rch & Prof#=UNT 049 in Runni,Reach-1,6
Up Type=0
Dn Type=3
Dn Slope=0.005
Boundary for River Rch & Prof#=UNT 049 in Runni,Reach-1,7
Up Type=0
Dn Type=3
Dn Slope=0.005

--- UNT 049 in Running Cr Watershed.g01 (geometry) ---

Geom Title=Existing Conditions

River Reach=UNT 049 in Runni,Reach-1
Reach XY= 30
      2896895.59      7034140.71      2896763.77      7034191.19
      2896757.64      7034139.52      2896657.38      7034138.65
      2896502.38      7034368.95      2896392.05      7034348.81
      2896378.91      7034397.41      2896416.13      7034445.57
      2896344.76      7034581.30      2896402.99      7034673.25
      2896324.18      7034769.58      2896290.47      7034699.52
      2896231.36      7034703.90      2896273.83      7034832.19
      2896173.56      7034892.61      2896068.48      7035093.58
      2896052.72      7035224.49      2895895.09      7035395.25
      2895877.14      7035491.58      2895776.44      7035587.90
      2895671.79      7035609.36      2895600.43      7035671.09
      2895553.14      7035909.28      2895417.41      7036098.87
      2895160.39      7036010.86      2895044.37      7035880.82
      2894781.22      7035754.72      2894518.87      7035478.88
      2894164.31      7035264.33      2893275.92      7035063.33

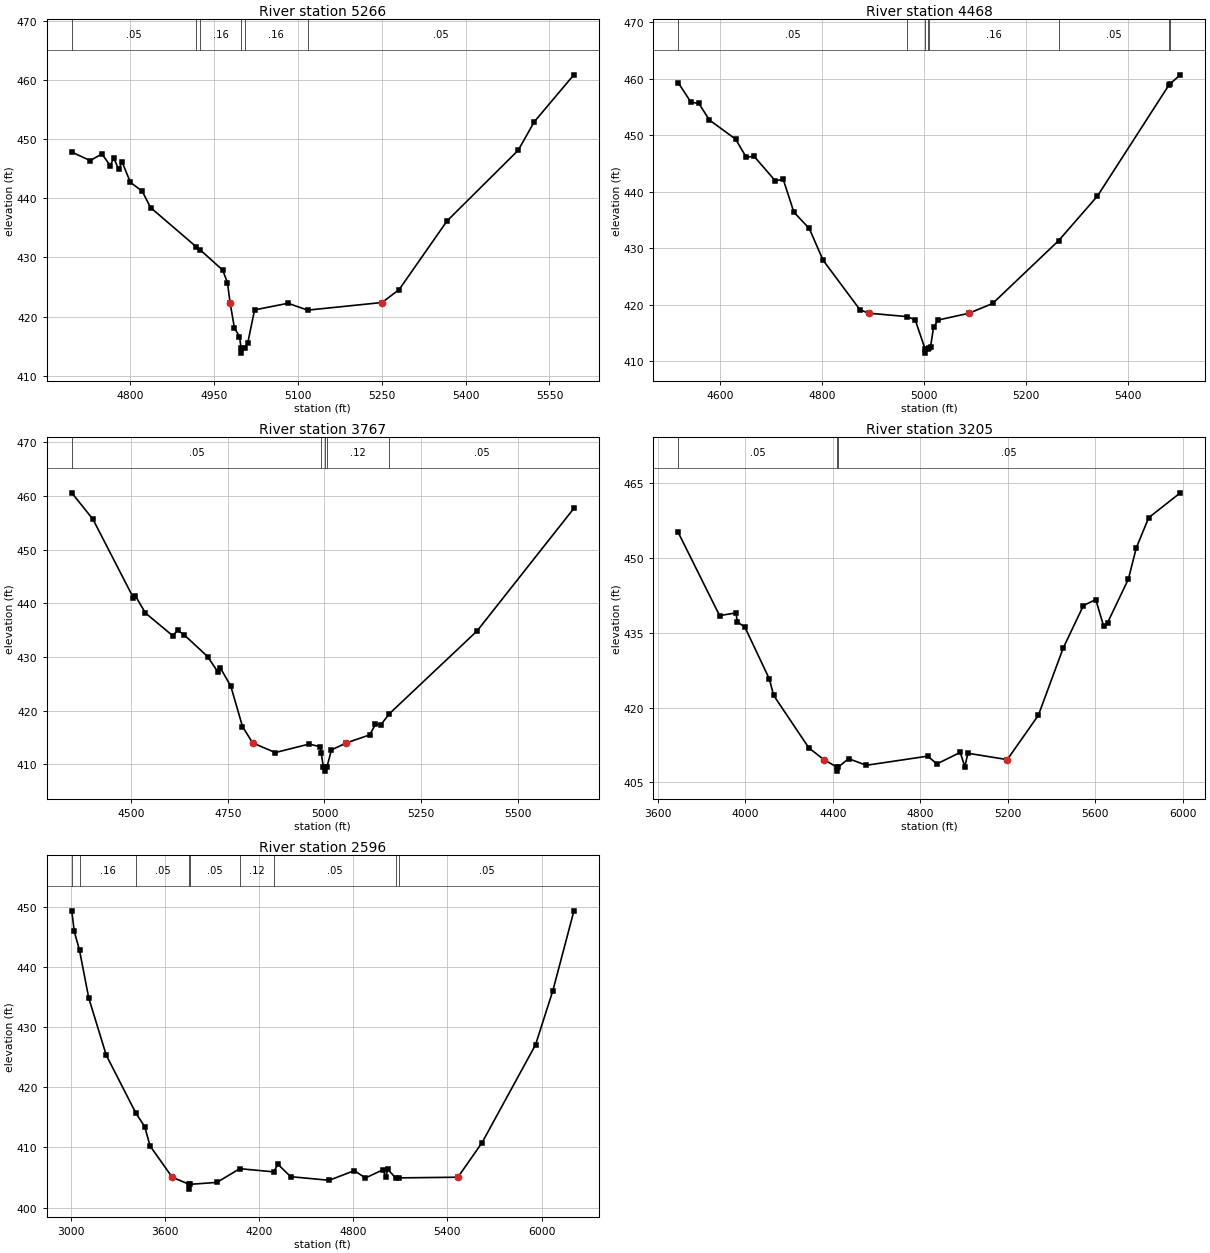
Type RM Length L Ch R = 1,5266,798,798,798
BEGIN DESCRIPTION:
UNT 049 in Running Cr Watershed 5.0
END DESCRIPTION:
XS GIS Cut Line= 3
      2896441.07      7033953.55      2896714.50      7034361.53
      2897025.04      7034625.03
#Sta/Elev= 30
  4695.2  447.80  4728.1  446.37  4749.1  447.49  4764.1  445.50  4770.2  446.83
  4779.1  444.90  4785.2  446.13  4800.2  442.68  4821.2  441.20  4836.2  438.42
  4917.6  431.82  4924.7  431.30  4965.3  427.84  4973.8  425.72  4978.4  422.37
  4986.3  418.05  4995.3  416.61  4998.3  414.61  4998.8  413.81  5004.3  414.61
  5009.9  415.44  5022.3  421.12  5082.2  422.24  5117.2  421.08  5250.4  422.37
  5281.0  424.56  5366.7  436.16  5494.1  448.12  5522.7  452.92  5593.6  460.87
#Mann=6,-1,0
  4695.2    0.05       0  4917.6     0.1       0  4924.7    0.16       0
  4998.3    0.07       0  5004.3    0.16       0  5117.2    0.05       0
Bank Sta=4978.4,5250.4
Exp/Cntr=0.3,0.1

Type RM Length L Ch R = 1,4468,701,701,701
BEGIN DESCRIPTION:
UNT 049 in Running Cr Watershed 4.0
END DESCRIPTION:
XS GIS Cut Line= 3
      2896106.84      7034318.10      2896432.38      7034812.92
      2896724.98      7035074.98
#Sta/Elev= 30
  4517.4  459.26  4542.5  455.79  4557.6  455.62  4578.6  452.66  4629.9  449.28
  4650.9  446.06  4666.0  446.26  4708.1  441.87  4723.2  442.22  4744.3  436.35
  4774.5  433.46  4801.5  427.86  4873.8  419.09  4890.8  418.47  4966.9  417.86
  4982.3  417.29  5001.5  412.20  5002.0  411.40  5007.5  412.20  5009.0  412.29
  5012.4  412.51  5018.4  415.99  5027.5  417.26  5088.1  418.47  5134.3  420.19
  5263.6  431.30  5339.9  439.20  5480.8  458.94  5483.0  459.11  5502.5  460.66
#Mann=8,-1,0
  4517.4    0.05       0  4966.9    0.12       0  5001.5    0.07       0
  5007.5    0.12       0  5009.0    0.16       0  5263.6    0.05       0
  5480.8    0.16       0  5483.0    0.05       0
Bank Sta=4890.8,5088.1
Exp/Cntr=0.3,0.1

Type RM Length L Ch R = 1,3767,562,562,562
BEGIN DESCRIPTION:
UNT 049 in Running Cr Watershed 3.0
END DESCRIPTION:
XS GIS Cut Line= 3
      2896025.00      7034474.99      2895976.65      7034999.55
      2896584.33      7035477.01
#Sta/Elev= 30
  4345.9  460.59  4400.8  455.65  4505.5  441.01  4510.5  441.40  4536.7  438.18
  4607.0  433.97  4620.2  434.97  4637.1  434.11  4697.4  430.08  4724.9  427.13
  4729.9  428.04  4757.6  424.55  4787.8  417.04  4814.0  413.99  4872.7  412.19
  4960.2  413.77  4989.1  413.27  4991.4  412.19  4997.1  409.53  5000.5  409.53
  5001.0  408.73  5006.5  409.53  5018.0  412.68  5056.7  413.99  5117.4  415.49
  5131.8  417.44  5146.3  417.41  5168.2  419.44  5394.9  434.84  5645.5  457.69
#Mann=5,-1,0
  4345.9    0.05       0  4991.4    0.12       0  5000.5    0.07       0
  5006.5    0.12       0  5168.2    0.05       0
Bank Sta=4814,5056.7
Exp/Cntr=0.3,0.1

Type RM Length L Ch R = 1,3205,609,609,609
BEGIN DESCRIPTION:
UNT 049 in Running Cr Watershed 2.0
END DESCRIPTION:
XS GIS Cut Line= 4
      2895833.43      7034292.05      2895695.04      7035396.73
      2895963.63      7035711.36      2896688.43      7035967.43
#Sta/Elev= 30
  3693.5  455.10  3882.5  438.44  3958.0  438.97  3963.0  437.22  3998.8  436.07
  4109.7  425.77  4129.8  422.43  4291.1  411.89  4359.2  409.56  4419.1  408.05
  4419.6  407.25  4425.1  408.05  4472.5  409.75  4553.1  408.42  4833.6  410.25
  4876.5  408.71  4983.0  411.00  5003.8  408.15  5018.1  410.83  5198.0  409.56
  5340.2  418.45  5453.3  431.88  5546.0  440.44  5602.6  441.65  5638.8  436.29
  5656.8  437.03  5751.8  445.76  5788.1  452.04  5844.6  458.06  5989.2  463.05
#Mann=3,-1,0
  3693.5    0.05       0  4419.1    0.03       0  4425.1    0.05       0
Bank Sta=4359.2,5198
Exp/Cntr=0.3,0.1

Type RM Length L Ch R = 1,2596,0,0,0
BEGIN DESCRIPTION:
UNT 049 in Running Cr Watershed 1.0
END DESCRIPTION:
XS GIS Cut Line= 4
      2895651.13      7034109.81      2895295.23      7035819.87
      2895694.54      7036149.73      2896588.59      7036418.81
#Sta/Elev= 30
  3007.3  449.35  3022.8  445.97  3056.6  442.79  3115.4  434.86  3227.1  425.33
  3415.3  415.73  3472.2  413.45  3505.8  410.26  3647.1  405.05  3755.2  403.87
  3755.7  403.07  3761.2  403.87  3931.9  404.19  4077.2  406.47  4294.4  405.94
  4320.0  407.21  4401.7  405.14  4646.9  404.54  4806.7  406.14  4878.4  404.93
  4991.7  406.32  5006.0  405.03  5020.4  406.34  5072.3  404.89  5093.9  404.94
  5467.1  405.05  5621.1  410.81  5961.6  427.08  6071.1  436.00  6205.6  449.29
#Mann=9,-1,0
  3007.3    0.12       0  3056.6    0.16       0  3415.3    0.05       0
  3755.2    0.03       0  3761.2    0.05       0  4077.2    0.12       0
  4294.4    0.05       0  5072.3    0.16       0  5093.9    0.05       0
Bank Sta=3647.1,5467.1
Exp/Cntr=0.3,0.1

Chan Stop Cuts=-1