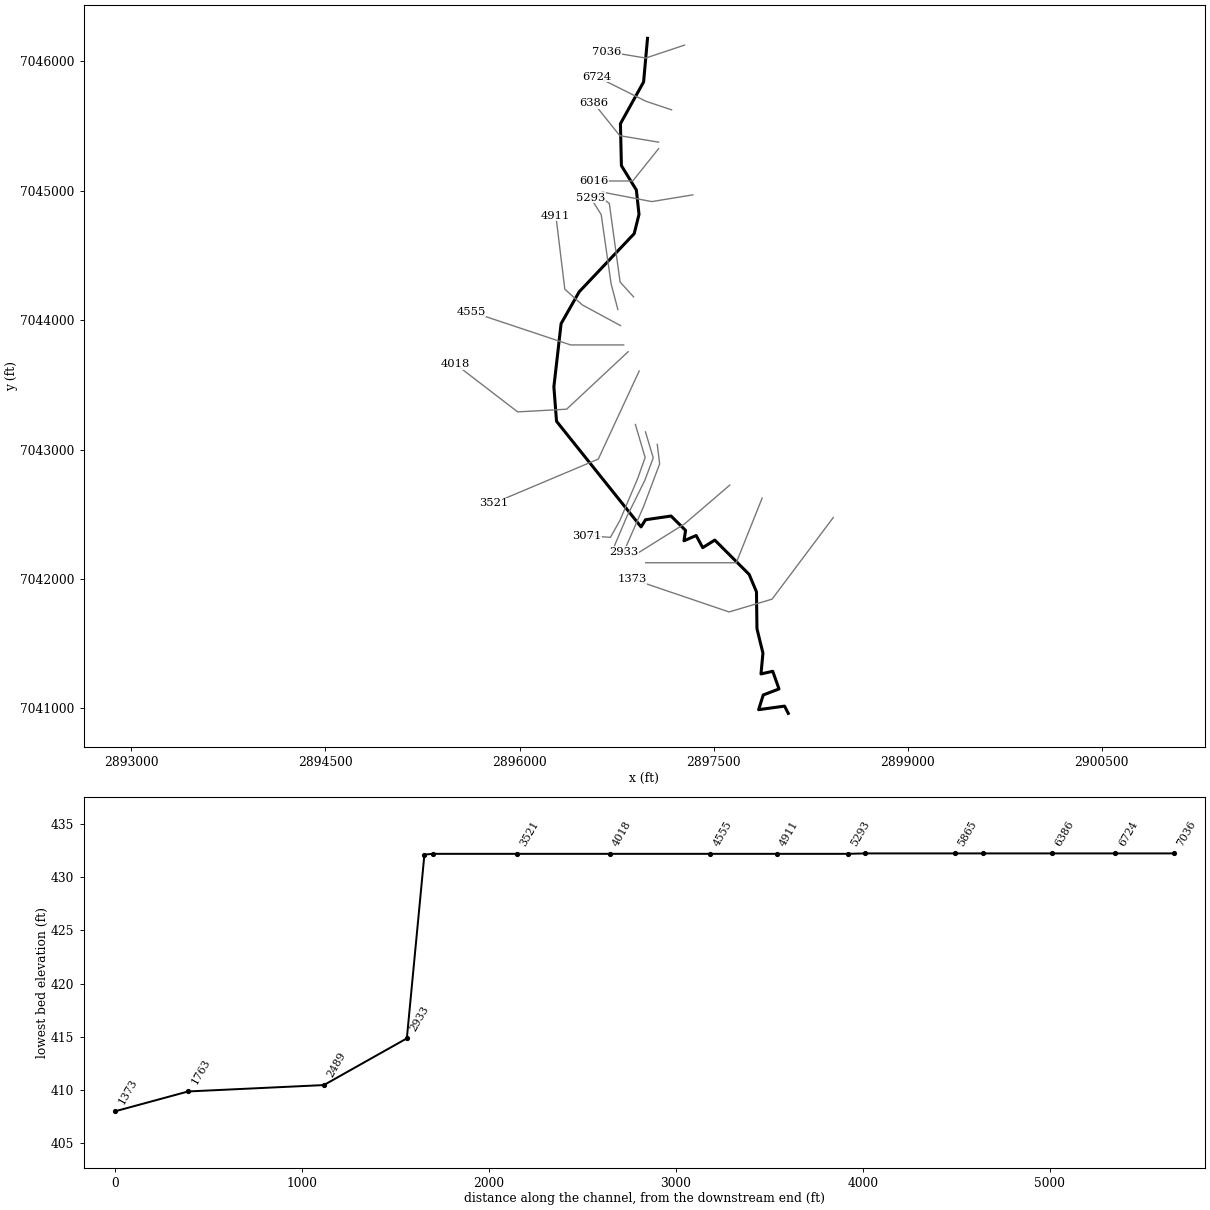
--- UNT 050 in Running Cr Watershed.prj (project) ---

Proj Title=UNT 050 in Running Cr Watershed Base Level Engineering
Current Plan=p01
Default Exp/Contr=0.3,0.1
English Units
Geom File=g01
Flow File=f01
Plan File=p01
BEGIN DESCRIPTION:
UNT 050 in Running Cr Watershed
END DESCRIPTION:

--- UNT 050 in Running Cr Watershed.p01 (plan) ---

Plan Title=Multiple Run
Short Identifier=Multiple
Geom File=g01
Flow File=f01
Subcritical Flow
K Sum by GR= 0
Std Step Tol= 0.01
Critical Tol= 0.01
Num of Std Step Trials= 20
Max Error Tol= 0.3
Flow Tol Ratio= 0.001
Split Flow NTrial= 30
Split Flow Tol= 0.02
Split Flow Ratio= 0.02
Log Output Level= 0
Friction Slope Method= 1
Unsteady Friction Slope Method= 2
Unsteady Bridges Friction Slope Method= 1
Parabolic Critical Depth
Global Vel Dist=  1 , 1 , 1
Global Log Level= 0
CheckData=True
Encroach Param= -1, 0, 0, 0
BEGIN DESCRIPTION:
Multiple Run
END DESCRIPTION:

--- UNT 050 in Running Cr Watershed.f01 (steady flow) ---

Flow Title=Multiple
Number of Profiles=7
Profile Names=10-year,25-year,50-year,1pct_min,100-year,1pct_plu,500-year
River Rch & RM= UNT 050 in Runni,Reach-1,7036
     487     640     761     450     898    1792    1252
River Rch & RM= UNT 050 in Runni,Reach-1,4018
     718     967    1170     703    1404    2801    2023
Boundary for River Rch & Prof#=UNT 050 in Runni,Reach-1,1
Up Type=0
Dn Type=3
Dn Slope=0.005
Boundary for River Rch & Prof#=UNT 050 in Runni,Reach-1,2
Up Type=0
Dn Type=3
Dn Slope=0.005
Boundary for River Rch & Prof#=UNT 050 in Runni,Reach-1,3
Up Type=0
Dn Type=3
Dn Slope=0.005
Boundary for River Rch & Prof#=UNT 050 in Runni,Reach-1,4
Up Type=0
Dn Type=3
Dn Slope=0.005
Boundary for River Rch & Prof#=UNT 050 in Runni,Reach-1,5
Up Type=0
Dn Type=3
Dn Slope=0.005
Boundary for River Rch & Prof#=UNT 050 in Runni,Reach-1,6
Up Type=0
Dn Type=3
Dn Slope=0.005
Boundary for River Rch & Prof#=UNT 050 in Runni,Reach-1,7
Up Type=0
Dn Type=3
Dn Slope=0.005

--- UNT 050 in Running Cr Watershed.g01 (geometry) ---

Geom Title=Existing Conditions

River Reach=UNT 050 in Runni,Reach-1
Reach XY= 30
      2896989.17      7046177.36      2896958.83      7045840.24
      2896779.93      7045517.84      2896787.38      7045193.57
      2896902.93      7045005.35      2896923.43      7044817.12
      2896886.15      7044668.03      2896461.25      7044218.91
      2896321.48      7043972.91      2896265.58      7043484.65
      2896286.07      7043218.15      2896939.26      7042401.96
      2896973.79      7042457.28      2897171.04      7042486.08
      2897283.27      7042374.73      2897270.90      7042294.76
      2897365.01      7042335.41      2897415.82      7042241.74
      2897509.05      7042300.06      2897774.73      7042034.72
      2897831.14      7041900.40      2897834.90      7041615.11
      2897881.11      7041426.53      2897866.06      7041265.89
      2897956.86      7041286.30      2898005.22      7041149.84
      2897883.26      7041103.09      2897847.80      7040989.73
      2898048.20      7041017.13      2898076.78      7040961.04

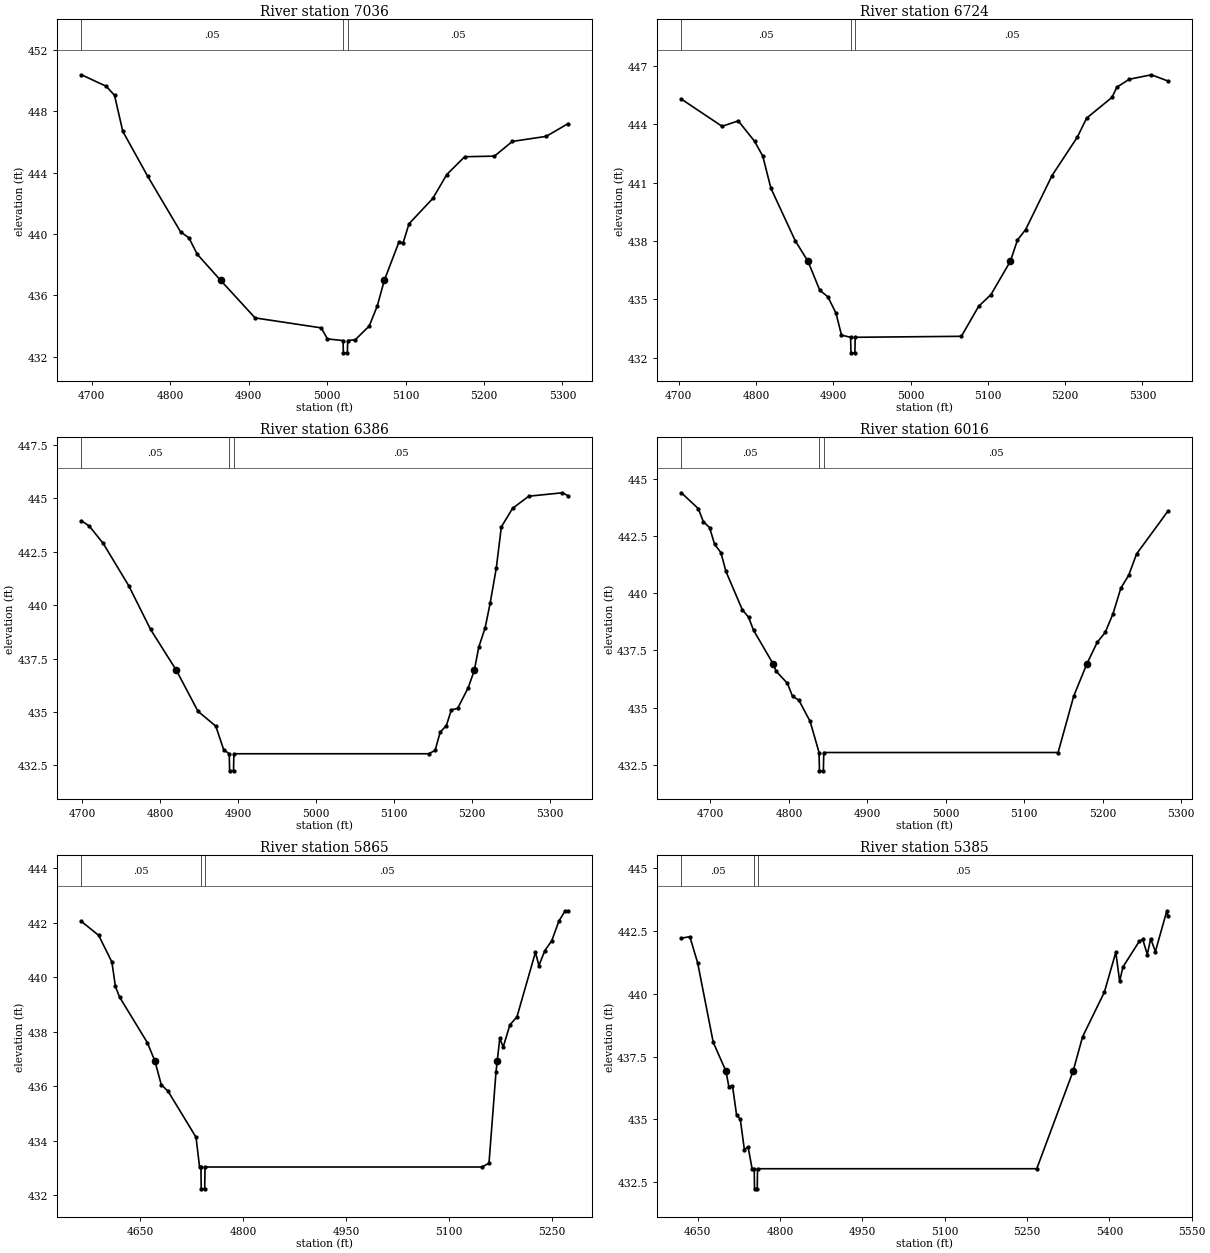
Type RM Length L Ch R = 1,7036,312,312,312
BEGIN DESCRIPTION:
UNT 050 in Running Cr Watershed 8.0
END DESCRIPTION:
XS GIS Cut Line= 3
      2897275.01      7046125.00      2896975.00      7046025.00
      2896674.98      7046075.00
#Sta/Elev= 30
  4686.8  450.39  4718.4  449.64  4729.0  449.05  4739.5  446.70  4771.1  443.78
  4813.3  440.13  4823.8  439.75  4834.4  438.68  4864.1  436.98  4908.2  434.52
  4992.5  433.87  5000.4  433.15  5020.3  433.04  5020.8  432.24  5025.8  432.24
  5026.3  433.04  5036.0  433.10  5053.7  433.99  5063.9  435.29  5073.0  436.98
  5091.8  439.50  5096.8  439.40  5104.4  440.66  5134.8  442.32  5152.6  443.88
  5175.4  445.04  5213.4  445.08  5236.2  446.04  5279.3  446.37  5307.2  447.20
#Mann=3,-1,0
  4686.8    0.05       0  5020.3    0.03       0  5026.3    0.05       0
Bank Sta=4864.1,5073
Exp/Cntr=0.3,0.1

Type RM Length L Ch R = 1,6724,338,338,338
BEGIN DESCRIPTION:
UNT 050 in Running Cr Watershed 7.0
END DESCRIPTION:
XS GIS Cut Line= 3
      2897174.96      7045625.01      2896976.68      7045691.11
      2896600.20      7045879.29
#Sta/Elev= 30
  4703.2  445.29  4755.9  443.89  4776.9  444.17  4798.0  443.12  4808.6  442.36
  4819.1  440.71  4850.7  438.00  4867.1  436.95  4882.4  435.46  4892.9  435.12
  4903.4  434.28  4910.5  433.15  4922.3  433.04  4922.8  432.24  4927.8  432.24
  4928.3  433.04  5065.7  433.09  5088.0  434.63  5104.1  435.24  5129.1  436.95
  5138.3  438.04  5148.9  438.58  5183.1  441.36  5215.9  443.34  5227.8  444.31
  5260.7  445.38  5266.9  445.90  5283.0  446.31  5311.6  446.54  5333.1  446.22
#Mann=3,-1,0
  4703.2    0.05       0  4922.3    0.03       0  4928.3    0.05       0
Bank Sta=4867.1,5129.1
Exp/Cntr=0.3,0.1

Type RM Length L Ch R = 1,6386,370,370,370
BEGIN DESCRIPTION:
UNT 050 in Running Cr Watershed 6.0
END DESCRIPTION:
XS GIS Cut Line= 3
      2897075.01      7045375.00      2896775.00      7045425.00
      2896575.00      7045675.00
#Sta/Elev= 30
  4698.9  443.95  4709.0  443.70  4726.8  442.89  4759.7  440.90  4787.6  438.86
  4820.8  436.94  4848.4  435.03  4871.3  434.33  4881.4  433.23  4888.5  433.04
  4889.0  432.24  4894.0  432.24  4894.5  433.04  5144.7  433.04  5152.7  433.20
  5159.1  434.05  5167.1  434.36  5173.5  435.10  5181.5  435.16  5195.1  436.13
  5202.9  436.94  5208.7  438.04  5216.8  438.93  5223.2  440.08  5231.2  441.75
  5237.6  443.66  5252.0  444.53  5272.8  445.10  5316.0  445.26  5323.2  445.12
#Mann=3,-1,0
  4698.9    0.05       0  4888.5    0.03       0  4894.5    0.05       0
Bank Sta=4820.8,5202.9
Exp/Cntr=0.3,0.1

Type RM Length L Ch R = 1,6016,151,151,151
BEGIN DESCRIPTION:
UNT 050 in Running Cr Watershed 5.0
END DESCRIPTION:
XS GIS Cut Line= 3
      2897074.99      7045324.99      2896875.00      7045075.00
      2896575.04      7045075.00
#Sta/Elev= 30
  4662.9  444.38  4684.5  443.69  4690.9  443.12  4698.9  442.86  4705.3  442.13
  4713.3  441.77  4719.7  440.95  4740.5  439.28  4748.5  438.95  4754.9  438.38
  4779.7  436.92  4783.7  436.59  4798.1  436.06  4804.6  435.49  4812.6  435.33
  4827.0  434.40  4838.4  433.04  4838.9  432.24  4843.9  432.24  4844.4  433.04
  5143.0  433.04  5163.0  435.51  5179.8  436.92  5193.0  437.86  5203.0  438.28
  5213.0  439.10  5223.0  440.22  5233.0  440.78  5243.0  441.71  5283.0  443.58
#Mann=3,-1,0
  4662.9    0.05       0  4838.4   0.033       0  4844.4    0.05       0
Bank Sta=4779.7,5179.8
Exp/Cntr=0.3,0.1

Type RM Length L Ch R = 1,5865,480,480,480
BEGIN DESCRIPTION:
Mapping XS 1a3af547
END DESCRIPTION:
XS GIS Cut Line= 3
      2897339.77      7044967.84      2897022.05      7044915.76
      2896641.84      7044988.68
#Sta/Elev= 30
  4564.3  442.04  4589.4  441.53  4608.7  440.55  4613.8  439.66  4619.8  439.27
  4660.3  437.60  4671.4  436.92  4680.6  436.06  4690.7  435.81  4731.3  434.13
  4736.4  433.05  4738.4  433.04  4738.9  432.24  4743.9  432.24  4744.4  433.04
  5148.0  433.04  5158.2  433.18  5168.4  436.52  5170.2  436.92  5173.9  437.75
  5178.9  437.44  5188.7  438.25  5198.9  438.54  5225.9  440.91  5230.9  440.42
  5239.6  440.97  5249.8  441.34  5260.0  442.05  5269.2  442.43  5273.4  442.43
#Mann=3,-1,0
  4564.3    0.05       0  4738.4   0.033       0  4744.4    0.05       0
Bank Sta=4671.4,5170.2
Exp/Cntr=0.3,0.1

Type RM Length L Ch R = 1,5385,92,92,92
BEGIN DESCRIPTION:
Mapping XS 8786924d
END DESCRIPTION:
XS GIS Cut Line= 4
      2896881.43      7044179.64      2896777.26      7044294.23
      2896693.93      7044901.87      2896597.66      7044970.64
#Sta/Elev= 30
  4620.3  442.21  4635.8  442.27  4650.0  441.23  4678.4  438.07  4701.6  436.92
  4706.8  436.31  4713.5  436.34  4720.9  435.18  4727.7  435.01  4735.1  433.80
  4741.9  433.91  4749.2  433.04  4753.1  433.04  4753.6  432.24  4758.6  432.24
  4759.1  433.04  5267.8  433.04  5334.0  436.92  5351.3  438.29  5390.9  440.06
  5411.8  441.65  5418.8  440.50  5424.9  441.07  5454.4  442.08  5460.9  442.16
  5469.2  441.56  5475.3  442.19  5483.9  441.68  5504.8  443.30  5506.8  443.08
#Mann=3,-1,0
  4620.3    0.05       0  4753.1   0.033       0  4759.1    0.05       0
Bank Sta=4701.6,5334
Exp/Cntr=0.3,0.1

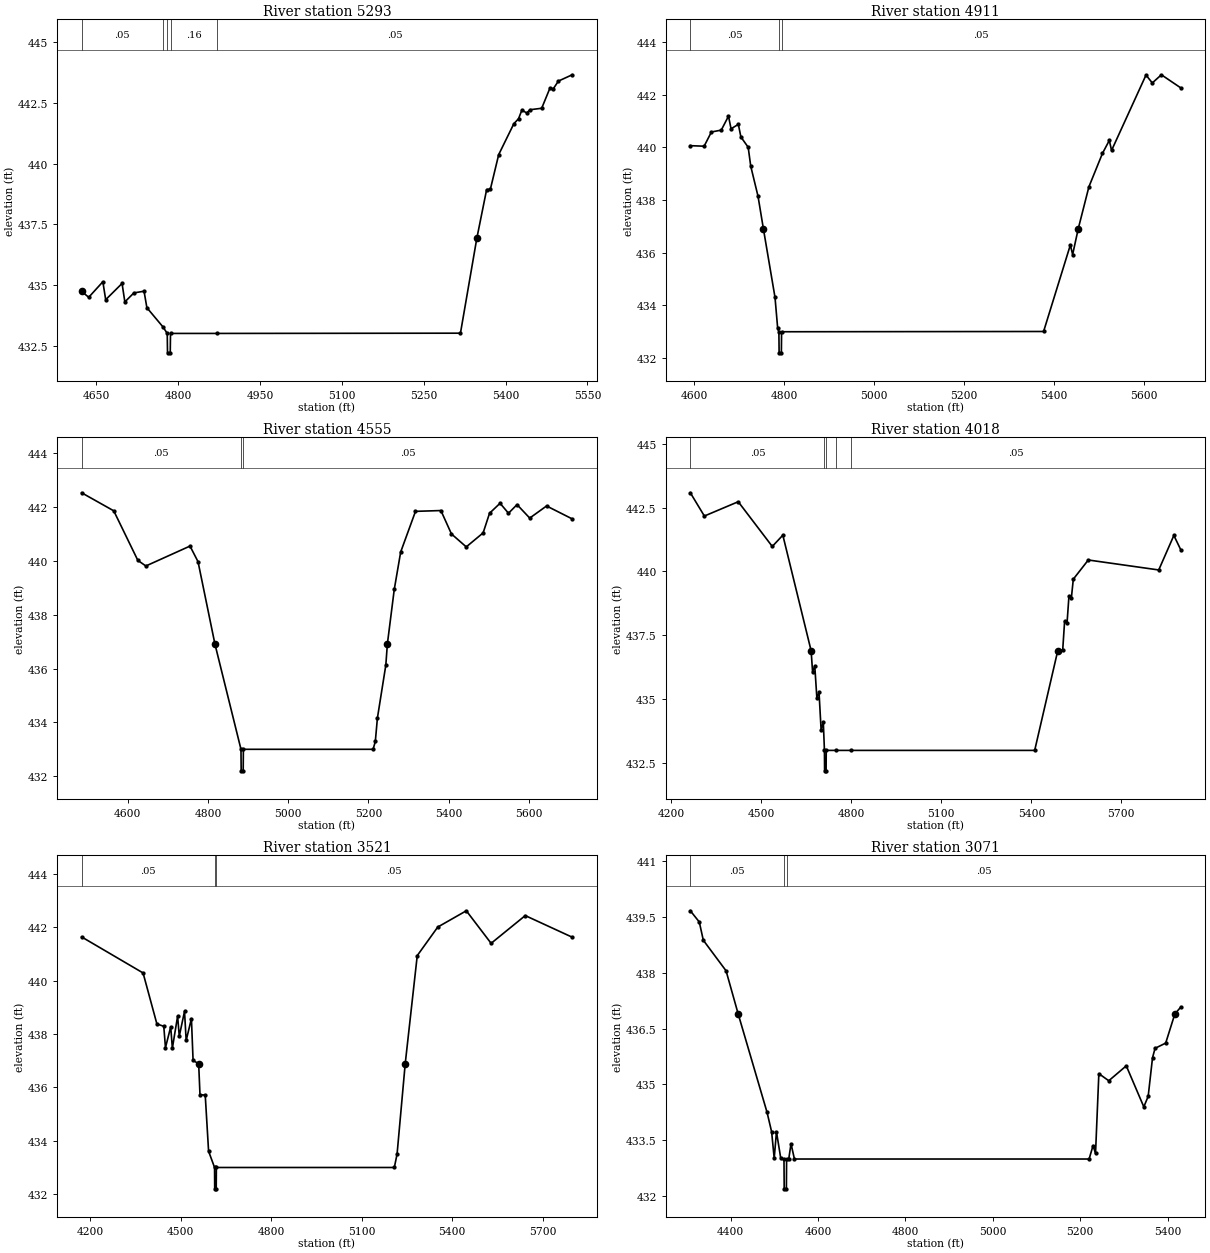
Type RM Length L Ch R = 1,5293,382,382,382
BEGIN DESCRIPTION:
Mapping XS b8c5d66a
END DESCRIPTION:
XS GIS Cut Line= 4
      2896759.91      7044082.39      2896707.82      7044280.34
      2896631.43      7044815.06      2896549.05      7044945.49
#Sta/Elev= 30
  4623.0  434.73  4636.0  434.49  4661.9  435.13  4667.1  434.39  4697.1  435.06
  4702.2  434.30  4718.8  434.67  4737.4  434.74  4742.6  434.06  4772.0  433.27
  4779.9  433.00  4780.4  432.20  4785.4  432.20  4785.9  433.00  4871.6  433.00
  5317.3  433.01  5347.3  436.92  5365.3  438.93  5372.1  438.94  5387.4  440.37
  5415.1  441.64  5423.8  441.85  5429.8  442.20  5438.7  442.09  5445.0  442.22
  5466.2  442.28  5481.5  443.12  5487.4  443.08  5496.8  443.40  5522.1  443.66
#Mann=5,-1,0
  4623.0    0.05       0  4772.0    0.16       0  4779.9   0.033       0
  4785.9    0.16       0  4871.6    0.05       0
Bank Sta=4623,5347.3
Exp/Cntr=0.3,0.1

Type RM Length L Ch R = 1,4911,356,356,356
BEGIN DESCRIPTION:
Mapping XS 30b87cd3
END DESCRIPTION:
XS GIS Cut Line= 4
      2896780.74      7043957.42      2896485.60      7044117.15
      2896350.18      7044238.68      2896280.73      7044808.12
#Sta/Elev= 30
  4591.3  440.06  4622.0  440.04  4638.2  440.58  4660.1  440.65  4676.2  441.18
  4681.9  440.70  4698.1  440.87  4703.8  440.39  4720.0  440.00  4725.7  439.28
  4741.9  438.14  4753.8  436.91  4779.7  434.30  4785.6  433.13  4788.3  433.00
  4788.8  432.20  4793.8  432.20  4794.3  433.00  5377.1  433.01  5436.6  436.29
  5441.7  435.93  5454.2  436.91  5477.9  438.50  5508.1  439.77  5523.3  440.26
  5528.3  439.88  5604.9  442.74  5618.9  442.44  5639.1  442.75  5682.5  442.25
#Mann=3,-1,0
  4591.3    0.05       0  4788.3   0.033       0  4794.3    0.05       0
Bank Sta=4753.8,5454.2
Exp/Cntr=0.3,0.1

Type RM Length L Ch R = 1,4555,537,537,537
BEGIN DESCRIPTION:
Mapping XS 4f96d21a
END DESCRIPTION:
XS GIS Cut Line= 3
      2896804.99      7043808.12      2896395.32      7043808.12
      2895624.49      7044065.06
#Sta/Elev= 30
  4485.3  442.53  4565.3  441.86  4625.3  440.02  4645.3  439.81  4755.3  440.55
  4775.3  439.97  4817.4  436.91  4882.3  433.00  4882.8  432.20  4887.8  432.20
  4888.3  433.00  5211.5  433.00  5217.0  433.29  5222.2  434.16  5243.2  436.13
  5247.0  436.91  5264.2  438.94  5280.2  440.33  5317.1  441.84  5380.4  441.87
  5406.7  441.00  5443.6  440.52  5485.6  441.04  5501.6  441.77  5527.8  442.14
  5548.8  441.77  5570.1  442.09  5601.7  441.59  5643.7  442.04  5707.5  441.56
#Mann=3,-1,0
  4485.3    0.05       0  4882.3   0.033       0  4888.3    0.05       0
Bank Sta=4817.4,5247
Exp/Cntr=0.3,0.1

Type RM Length L Ch R = 1,4018,497,497,497
BEGIN DESCRIPTION:
Mapping XS 2a030bd2
END DESCRIPTION:
XS GIS Cut Line= 4
      2896839.79      7043756.06      2896364.07      7043311.59
      2895985.60      7043290.76      2895506.43      7043658.81
#Sta/Elev= 30
  4264.0  443.08  4310.8  442.17  4423.6  442.73  4537.0  440.98  4572.2  441.42
  4666.4  436.90  4671.3  436.07  4678.6  436.30  4685.5  435.06  4692.8  435.27
  4699.7  433.80  4707.0  434.11  4710.8  433.00  4711.3  432.20  4716.3  432.20
  4716.8  433.00  4749.9  433.00  4798.5  433.00  5411.2  433.00  5488.1  436.90
  5504.6  436.93  5510.9  438.05  5519.1  437.99  5525.4  439.04  5533.6  438.98
  5539.9  439.70  5589.8  440.45  5824.5  440.06  5874.9  441.41  5898.3  440.84
#Mann=5,-1,0
  4264.0    0.05       0  4710.8   0.033       0  4716.8    0.05       0
  4749.9    0.16       0  4798.5    0.05       0
Bank Sta=4666.4,5488.1
Exp/Cntr=0.3,0.1

Type RM Length L Ch R = 1,3521,450,450,450
BEGIN DESCRIPTION:
UNT 050 in Running Cr Watershed 4.0
END DESCRIPTION:
XS GIS Cut Line= 3
      2896924.84      7043606.76      2896608.86      7042926.18
      2895801.60      7042585.91
#Sta/Elev= 30
  4171.1  441.64  4374.8  440.29  4420.6  438.38  4443.5  438.29  4449.0  437.49
  4466.4  438.27  4471.9  437.47  4489.3  438.67  4494.8  437.92  4512.2  438.85
  4517.7  437.76  4535.1  438.58  4540.6  437.01  4559.1  436.89  4563.5  435.73
  4580.9  435.71  4592.0  433.61  4611.8  433.00  4612.3  432.20  4617.3  432.20
  4617.8  433.00  5207.8  433.00  5216.9  433.50  5243.9  436.89  5283.8  440.94
  5351.8  442.01  5446.5  442.62  5528.7  441.40  5641.9  442.44  5797.5  441.63
#Mann=3,-1,0
  4171.1    0.05       0  4611.8   0.033       0  4617.8    0.05       0
Bank Sta=4559.1,5243.9
Exp/Cntr=0.3,0.1

Type RM Length L Ch R = 1,3071,44,44,44
BEGIN DESCRIPTION:
Mapping XS 933f40ba
END DESCRIPTION:
XS GIS Cut Line= 6
      2896895.33      7043193.49      2896970.84      7042938.33
      2896913.55      7042776.87      2896775.53      7042451.35
      2896702.61      7042321.14      2896520.31      7042334.16
#Sta/Elev= 30
  4307.6  439.66  4328.1  439.36  4337.3  438.87  4389.4  438.05  4417.2  436.89
  4483.3  434.25  4493.7  433.73  4499.6  433.02  4504.8  433.73  4514.6  433.02
  4522.0  433.00  4522.5  432.20  4527.5  432.20  4528.0  433.00  4532.9  433.00
  4538.1  433.41  4545.9  433.00  5220.5  433.00  5229.5  433.36  5235.2  433.15
  5242.8  435.29  5265.5  435.10  5305.6  435.50  5345.7  434.40  5355.7  434.68
  5365.7  435.72  5371.5  435.97  5395.8  436.11  5416.7  436.89  5430.6  437.08
#Mann=3,-1,0
  4307.6    0.05       0  4522.0    0.03       0  4528.0    0.05       0
Bank Sta=4417.2,5416.7
Exp/Cntr=0.3,0.1

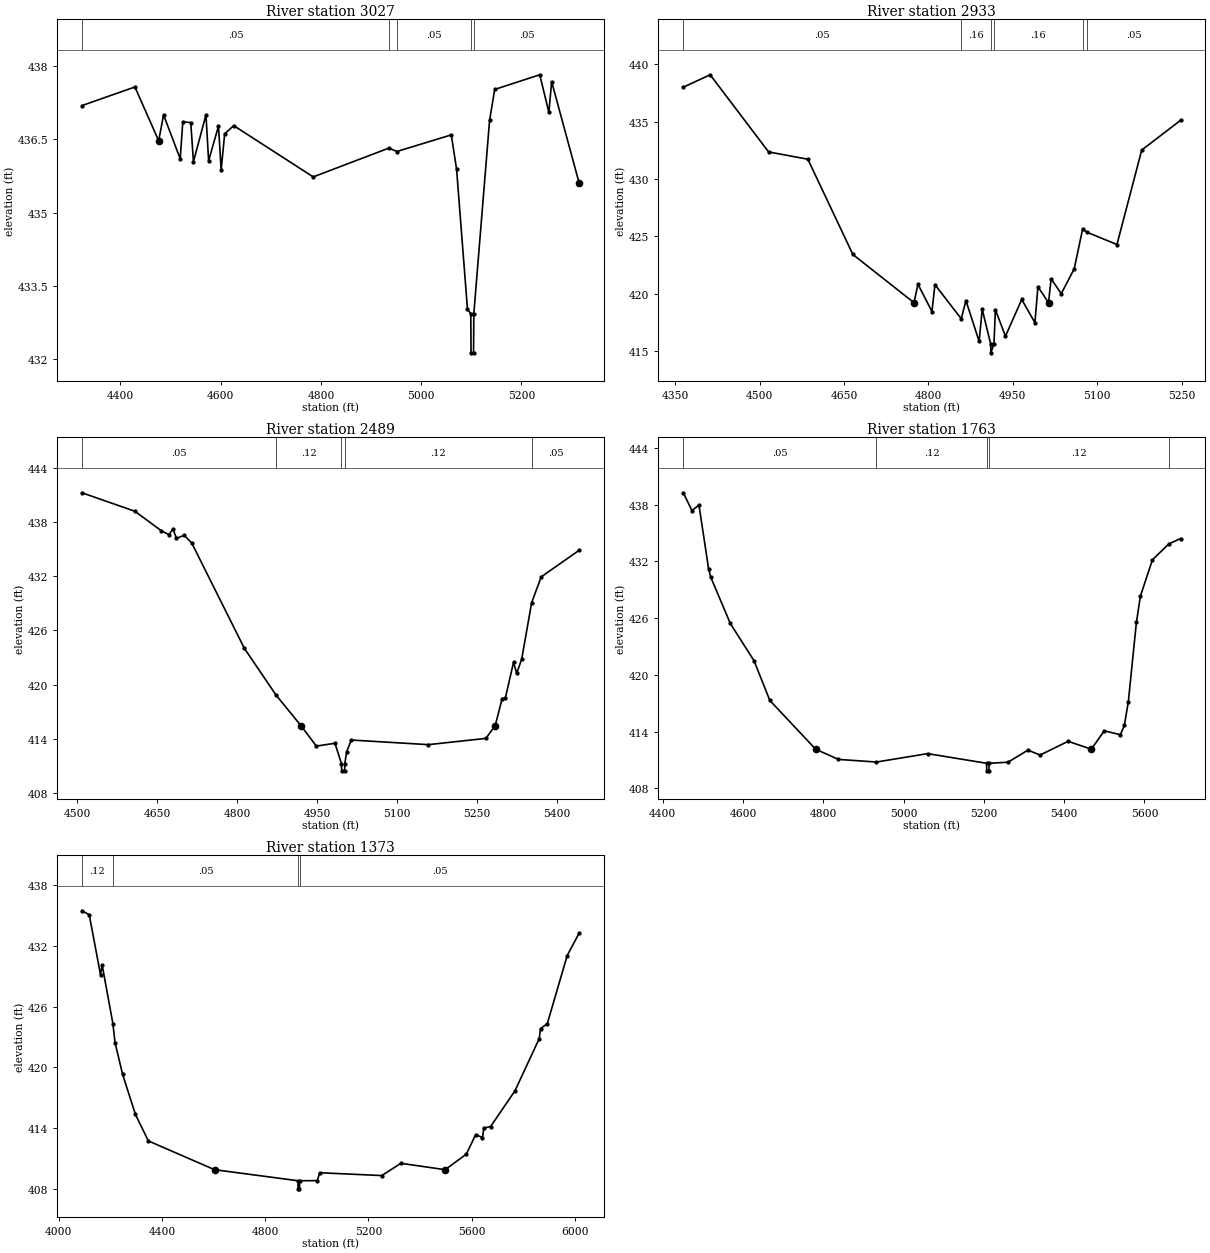
Type RM Length L Ch R = 1,3027,94,94,94
BEGIN DESCRIPTION:
Mapping XS cbb388fc
END DESCRIPTION:
XS GIS Cut Line= 5
      2896973.45      7043136.21      2897033.34      7042935.72
      2896968.23      7042761.24      2896827.61      7042477.39
      2896718.31      7042219.77
#Sta/Elev= 30
  4323.3  437.19  4428.9  437.57  4476.4  436.47  4486.1  437.00  4519.3  436.10
  4524.5  436.86  4540.4  436.84  4545.7  436.04  4570.7  437.00  4576.0  436.06
  4595.7  436.77  4601.0  435.87  4608.0  436.61  4626.0  436.78  4784.7  435.73
  4935.7  436.32  4951.6  436.25  5060.2  436.59  5070.7  435.89  5092.5  433.02
  5099.1  432.93  5099.6  432.13  5104.6  432.13  5105.1  432.93  5136.6  436.89
  5146.8  437.52  5236.7  437.82  5254.9  437.05  5260.4  437.68  5315.4  435.60
#Mann=5,-1,0
  4323.3    0.05       0  4935.7    0.16       0  4951.6    0.05       0
  5099.1    0.03       0  5105.1    0.05       0
Bank Sta=4476.4,5315.4
Exp/Cntr=0.3,0.1

Type RM Length L Ch R = 1,2933,444,444,444
BEGIN DESCRIPTION:
Mapping XS 73b6fc8f
END DESCRIPTION:
XS GIS Cut Line= 4
      2897064.59      7043039.86      2897082.82      7042888.85
      2896960.42      7042563.33      2896806.80      7042211.81
#Sta/Elev= 30
  4364.5  438.00  4412.2  439.08  4516.0  432.36  4585.8  431.72  4665.8  423.42
  4774.4  419.22  4781.4  420.83  4806.3  418.45  4811.6  420.79  4858.3  417.82
  4866.7  419.40  4890.1  415.85  4895.6  418.64  4910.5  415.65  4911.0  414.85
  4916.5  415.65  4919.0  418.61  4936.9  416.30  4965.8  419.50  4989.2  417.48
  4994.6  420.61  5013.4  419.22  5018.0  421.30  5036.0  420.01  5059.0  422.16
  5073.9  425.61  5082.2  425.35  5135.0  424.29  5179.0  432.52  5248.0  435.11
#Mann=6,-1,0
  4364.5    0.05       0  4858.3    0.16       0  4910.5    0.07       0
  4916.5    0.16       0  5073.9    0.12       0  5082.2    0.05       0
Bank Sta=4774.4,5013.4
Exp/Cntr=0.3,0.1

Type RM Length L Ch R = 1,2489,726,726,726
BEGIN DESCRIPTION:
UNT 050 in Running Cr Watershed 3.0
END DESCRIPTION:
XS GIS Cut Line= 3
      2897625.02      7042725.02      2897275.00      7042425.00
      2896875.01      7042175.00
#Sta/Elev= 30
  4508.6  441.24  4608.0  439.19  4657.4  437.04  4671.6  436.61  4679.3  437.23
  4685.9  436.19  4700.2  436.54  4714.4  435.69  4813.2  424.02  4872.6  418.85
  4919.4  415.46  4948.2  413.20  4983.2  413.51  4995.3  411.26  4995.8  410.46
  5001.2  410.46  5001.7  411.26  5005.0  412.56  5013.8  413.87  5158.3  413.36
  5266.2  414.05  5283.7  415.46  5296.8  418.46  5302.7  418.51  5318.1  422.47
  5324.0  421.25  5333.4  422.82  5352.1  429.08  5370.0  431.93  5441.3  434.88
#Mann=5,-1,0
  4508.6    0.05       0  4872.6    0.12       0  4995.3    0.07       0
  5001.7    0.12       0  5352.1    0.05       0
Bank Sta=4919.4,5283.7
Exp/Cntr=0.3,0.1

Type RM Length L Ch R = 1,1763,390,390,390
BEGIN DESCRIPTION:
UNT 050 in Running Cr Watershed 2.0
END DESCRIPTION:
XS GIS Cut Line= 3
      2897874.99      7042624.96      2897675.00      7042125.00
      2896974.98      7042125.00
#Sta/Elev= 30
  4451.5  439.26  4473.0  437.38  4490.5  437.96  4514.7  431.16  4520.1  430.31
  4568.6  425.44  4627.8  421.49  4666.9  417.31  4781.0  412.15  4837.8  411.07
  4932.5  410.79  5060.0  411.68  5206.8  410.66  5207.3  409.86  5212.7  409.86
  5213.2  410.66  5260.0  410.77  5310.0  412.05  5340.0  411.53  5410.0  412.98
  5467.7  412.15  5500.0  414.09  5540.0  413.68  5550.0  414.66  5560.0  417.19
  5580.0  425.55  5590.0  428.33  5620.0  432.18  5661.0  433.86  5690.0  434.42
#Mann=5,-1,0
  4451.5    0.05       0  4932.5    0.12       0  5206.8    0.07       0
  5213.2    0.12       0  5661.0    0.05       0
Bank Sta=4781,5467.7
Exp/Cntr=0.3,0.1

Type RM Length L Ch R = 1,1373,0,0,0
BEGIN DESCRIPTION:
UNT 050 in Running Cr Watershed 1.0
END DESCRIPTION:
XS GIS Cut Line= 4
      2898424.97      7042474.96      2897951.50      7041843.67
      2897619.64      7041744.76      2896870.97      7041999.11
#Sta/Elev= 30
  4090.3  435.45  4118.4  435.06  4162.1  429.15  4168.4  430.11  4210.0  424.32
  4218.4  422.44  4247.5  419.32  4297.5  415.34  4347.5  412.73  4603.9  409.89
  4927.0  408.80  4927.5  408.00  4932.9  408.00  4933.4  408.80  5001.7  408.81
  5011.4  409.59  5251.7  409.31  5325.7  410.52  5497.1  409.89  5578.9  411.42
  5615.6  413.36  5641.7  413.06  5646.9  414.00  5673.1  414.15  5767.2  417.66
  5861.4  422.82  5866.6  423.81  5892.8  424.31  5969.9  431.03  6016.4  433.26
#Mann=4,-1,0
  4090.3    0.12       0  4210.0    0.05       0  4927.0    0.03       0
  4933.4    0.05       0
Bank Sta=4603.9,5497.1
Exp/Cntr=0.3,0.1

Chan Stop Cuts=-1