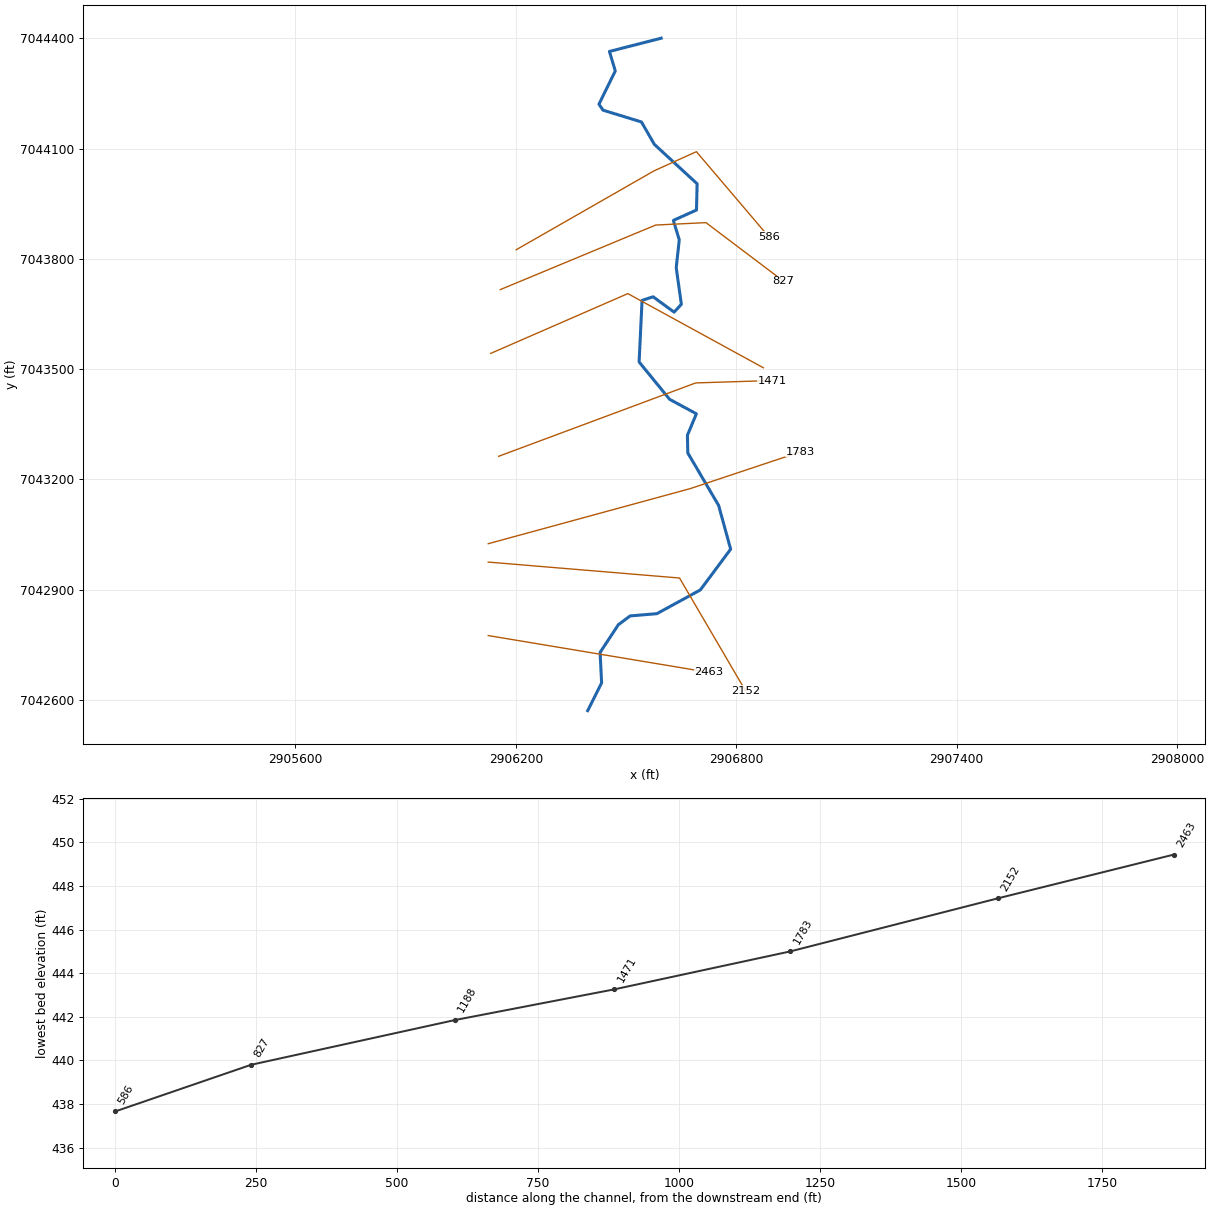
--- UNT 051 in Running Cr Watershed.prj (project) ---

Proj Title=UNT 051 in Running Cr Watershed Base Level Engineering
Current Plan=p01
Default Exp/Contr=0.3,0.1
English Units
Geom File=g01
Flow File=f01
Plan File=p01
BEGIN DESCRIPTION:
UNT 051 in Running Cr Watershed
END DESCRIPTION:

--- UNT 051 in Running Cr Watershed.p01 (plan) ---

Plan Title=Multiple Run
Short Identifier=Multiple
Geom File=g01
Flow File=f01
Subcritical Flow
K Sum by GR= 0
Std Step Tol= 0.01
Critical Tol= 0.01
Num of Std Step Trials= 20
Max Error Tol= 0.3
Flow Tol Ratio= 0.001
Split Flow NTrial= 30
Split Flow Tol= 0.02
Split Flow Ratio= 0.02
Log Output Level= 0
Friction Slope Method= 1
Unsteady Friction Slope Method= 2
Unsteady Bridges Friction Slope Method= 1
Parabolic Critical Depth
Global Vel Dist=  1 , 1 , 1
Global Log Level= 0
CheckData=True
Encroach Param= -1, 0, 0, 0
BEGIN DESCRIPTION:
Multiple Run
END DESCRIPTION:

--- UNT 051 in Running Cr Watershed.f01 (steady flow) ---

Flow Title=Multiple
Number of Profiles=7
Profile Names=10-year,25-year,50-year,1pct_min,100-year,1pct_plu,500-year
River Rch & RM= UNT 051 in Runni,Reach-1,2463
     496     662     798     478     954    1904    1368
Boundary for River Rch & Prof#=UNT 051 in Runni,Reach-1,1
Up Type=0
Dn Type=3
Dn Slope=0.005
Boundary for River Rch & Prof#=UNT 051 in Runni,Reach-1,2
Up Type=0
Dn Type=3
Dn Slope=0.005
Boundary for River Rch & Prof#=UNT 051 in Runni,Reach-1,3
Up Type=0
Dn Type=3
Dn Slope=0.005
Boundary for River Rch & Prof#=UNT 051 in Runni,Reach-1,4
Up Type=0
Dn Type=3
Dn Slope=0.005
Boundary for River Rch & Prof#=UNT 051 in Runni,Reach-1,5
Up Type=0
Dn Type=3
Dn Slope=0.005
Boundary for River Rch & Prof#=UNT 051 in Runni,Reach-1,6
Up Type=0
Dn Type=3
Dn Slope=0.005
Boundary for River Rch & Prof#=UNT 051 in Runni,Reach-1,7
Up Type=0
Dn Type=3
Dn Slope=0.005

--- UNT 051 in Running Cr Watershed.g01 (geometry) ---

Geom Title=Existing Conditions

River Reach=UNT 051 in Runni,Reach-1
Reach XY= 30
      2906395.59      7042570.71      2906433.47      7042646.28
      2906429.39      7042729.19      2906478.99      7042804.39
      2906511.10      7042828.45      2906583.97      7042834.60
      2906702.16      7042899.13      2906784.70      7043010.11
      2906751.99      7043129.21      2906668.10      7043271.98
      2906667.08      7043320.19      2906691.44      7043378.58
      2906618.47      7043418.00      2906535.56      7043519.62
      2906543.58      7043687.23      2906573.69      7043696.95
      2906630.82      7043655.17      2906650.53      7043676.57
      2906636.62      7043775.91      2906644.79      7043852.22
      2906628.82      7043904.87      2906691.67      7043933.11
      2906693.50      7044004.48      2906576.96      7044111.92
      2906541.87      7044172.82      2906437.29      7044204.87
      2906426.27      7044221.16      2906470.72      7044311.62
      2906454.80      7044364.67      2906595.59      7044400.71

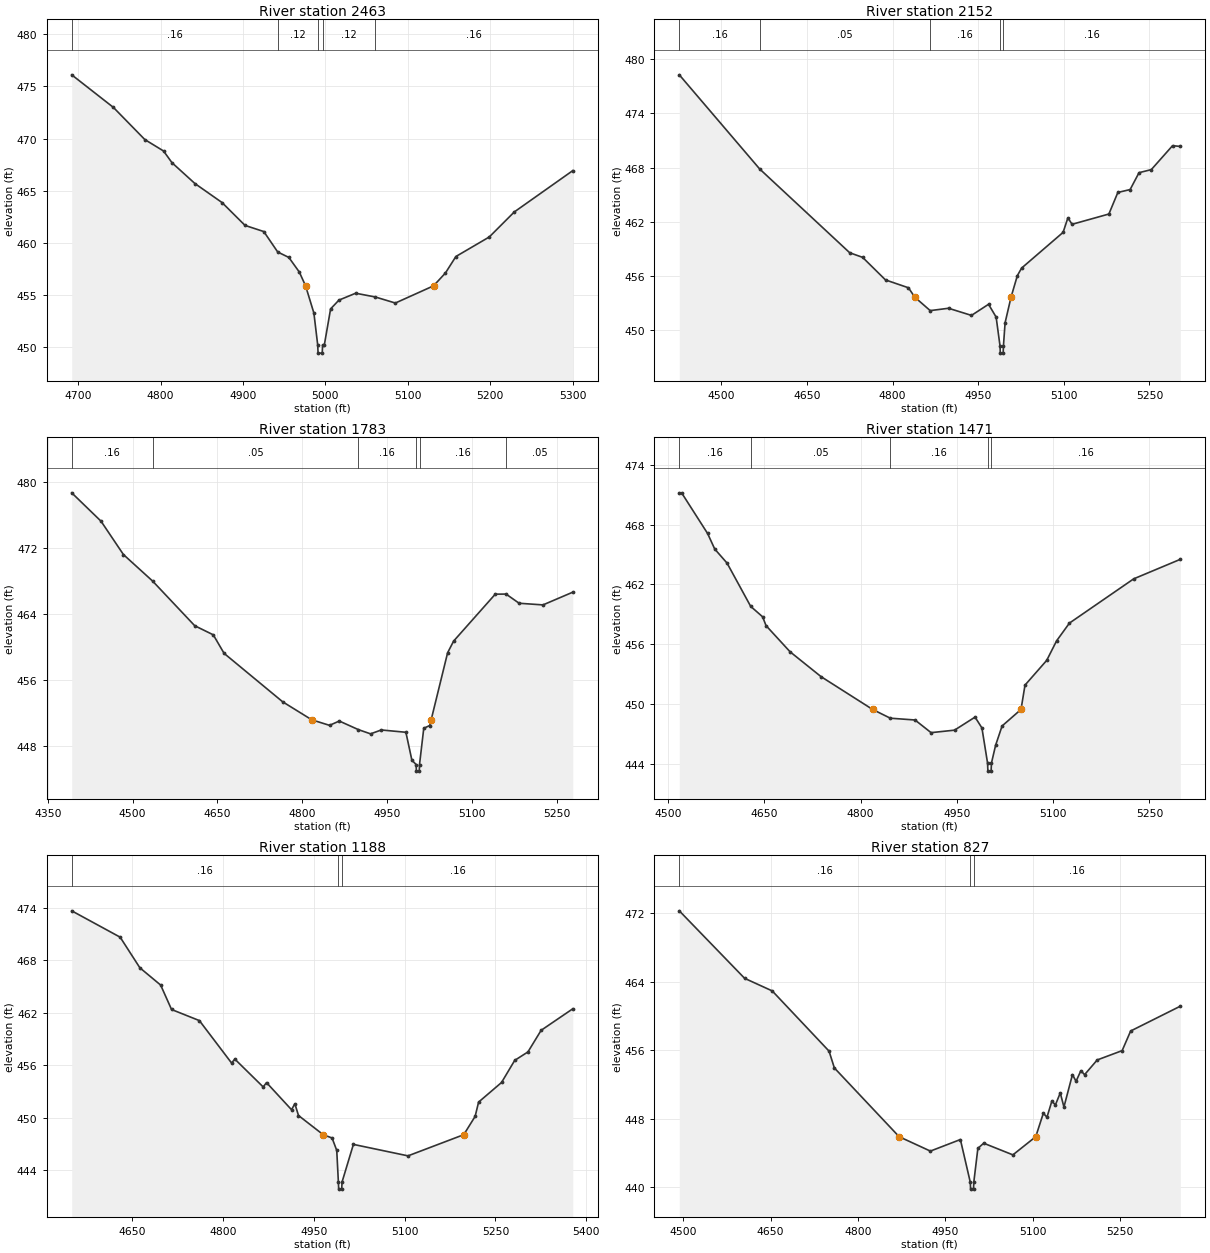
Type RM Length L Ch R = 1,2463,311,311,311
BEGIN DESCRIPTION:
UNT 051 in Running Cr Watershed 5.0
END DESCRIPTION:
XS GIS Cut Line= 3
      2906124.97      7042775.00      2906425.00      7042725.00
      2906725.00      7042675.00
#Sta/Elev= 30
  4692.0  476.11  4742.7  472.98  4780.7  469.91  4803.5  468.81  4813.7  467.69
  4841.6  465.69  4874.5  463.87  4902.4  461.68  4925.2  461.09  4942.1  459.13
  4955.6  458.61  4968.3  457.21  4975.9  455.89  4986.0  453.28  4990.6  450.24
  4991.1  449.44  4996.1  449.44  4996.6  450.24  4998.7  450.24  5006.3  453.68
  5016.4  454.52  5036.7  455.18  5060.6  454.82  5084.9  454.24  5131.3  455.89
  5145.7  457.12  5158.4  458.70  5198.9  460.57  5229.3  462.97  5300.3  466.93
#Mann=5,-1,0
  4692.0    0.16       0  4942.1    0.12       0  4990.6    0.07       0
  4996.6    0.12       0  5060.6    0.16       0
Bank Sta=4975.9,5131.3
Exp/Cntr=0.3,0.1

Type RM Length L Ch R = 1,2152,369,369,369
BEGIN DESCRIPTION:
UNT 051 in Running Cr Watershed 4.0
END DESCRIPTION:
XS GIS Cut Line= 3
      2906125.00      7042975.00      2906645.62      7042931.61
      2906825.02      7042624.96
#Sta/Elev= 30
  4426.4  478.27  4567.2  467.84  4724.9  458.56  4747.5  458.05  4787.6  455.55
  4827.8  454.68  4838.9  453.64  4865.9  452.15  4898.0  452.41  4938.2  451.62
  4968.1  452.85  4981.4  451.43  4988.2  448.24  4988.7  447.44  4993.7  447.44
  4994.2  448.24  4997.1  450.81  5007.5  453.64  5018.6  456.03  5026.0  456.86
  5098.7  460.82  5107.1  462.43  5114.4  461.71  5178.9  462.85  5194.6  465.24
  5216.1  465.56  5231.7  467.43  5253.2  467.77  5290.4  470.42  5304.1  470.34
#Mann=5,-1,0
  4426.4    0.16       0  4567.2    0.05       0  4865.9    0.16       0
  4988.2    0.07       0  4994.2    0.16       0
Bank Sta=4838.9,5007.5
Exp/Cntr=0.3,0.1

Type RM Length L Ch R = 1,1783,312,312,312
BEGIN DESCRIPTION:
UNT 051 in Running Cr Watershed 3.0
END DESCRIPTION:
XS GIS Cut Line= 3
      2906125.04      7043025.01      2906675.00      7043175.00
      2906975.03      7043275.01
#Sta/Elev= 30
  4392.3  478.67  4444.1  475.24  4483.8  471.20  4535.3  468.00  4609.9  462.59
  4642.7  461.49  4661.8  459.25  4765.4  453.39  4816.9  451.21  4848.3  450.54
  4865.6  451.06  4899.4  450.02  4920.9  449.51  4939.9  449.98  4983.4  449.70
  4994.0  446.32  5001.5  445.80  5002.0  445.00  5007.0  445.00  5007.5  445.80
  5015.0  450.18  5025.6  450.52  5028.1  451.21  5057.2  459.32  5067.8  460.73
  5141.5  466.41  5160.6  466.42  5183.7  465.31  5225.9  465.11  5278.6  466.65
#Mann=6,-1,0
  4392.3    0.16       0  4535.3    0.05       0  4899.4    0.16       0
  5001.5    0.07       0  5007.5    0.16       0  5160.6    0.05       0
Bank Sta=4816.9,5028.1
Exp/Cntr=0.3,0.1

Type RM Length L Ch R = 1,1471,283,283,283
BEGIN DESCRIPTION:
UNT 051 in Running Cr Watershed 2.0
END DESCRIPTION:
XS GIS Cut Line= 3
      2906153.26      7043262.91      2906689.62      7043462.56
      2906897.70      7043469.09
#Sta/Elev= 30
  4517.6  471.18  4521.2  471.18  4561.7  467.10  4572.8  465.54  4592.0  464.13
  4628.8  459.79  4647.4  458.74  4652.7  457.86  4690.2  455.23  4738.4  452.74
  4818.7  449.45  4846.3  448.57  4884.8  448.39  4909.8  447.12  4946.3  447.37
  4978.3  448.68  4989.0  447.59  4997.8  444.06  4998.3  443.26  5003.3  443.26
  5003.8  444.06  5010.3  445.85  5020.4  447.79  5049.9  449.45  5056.1  451.89
  5089.9  454.37  5105.3  456.33  5125.3  458.11  5225.4  462.55  5298.1  464.51
#Mann=5,-1,0
  4517.6    0.16       0  4628.8    0.05       0  4846.3    0.16       0
  4997.8    0.07       0  5003.8    0.16       0
Bank Sta=4818.7,5049.9
Exp/Cntr=0.3,0.1

Type RM Length L Ch R = 1,1188,361,361,361
BEGIN DESCRIPTION:
Mapping XS 66f3118a
END DESCRIPTION:
XS GIS Cut Line= 3
      2906131.64      7043542.89      2906504.87      7043705.63
      2906873.81      7043503.80
#Sta/Elev= 30
  4550.0  473.64  4630.0  470.63  4662.6  467.13  4696.9  465.16  4714.9  462.37
  4760.9  461.10  4814.0  456.26  4819.5  456.70  4866.3  453.52  4871.8  454.02
  4913.1  450.92  4918.6  451.60  4924.6  450.26  4965.4  448.07  4980.1  447.69
  4987.8  446.27  4990.5  442.65  4991.0  441.85  4996.0  441.85  4996.5  442.65
  5015.3  446.96  5105.5  445.65  5197.6  448.07  5216.4  450.16  5222.1  451.79
  5260.0  454.03  5281.8  456.56  5303.6  457.52  5325.4  459.99  5377.7  462.45
#Mann=3,-1,0
  4550.0    0.16       0  4990.5    0.07       0  4996.5    0.16       0
Bank Sta=4965.4,5197.6
Exp/Cntr=0.3,0.1

Type RM Length L Ch R = 1,827,241,241,241
BEGIN DESCRIPTION:
Mapping XS b19bb573
END DESCRIPTION:
XS GIS Cut Line= 4
      2906157.68      7043716.50      2906580.82      7043892.26
      2906717.54      7043898.77      2906928.89      7043739.19
#Sta/Elev= 30
  4493.2  472.29  4605.3  464.41  4652.7  462.94  4750.2  455.91  4759.3  453.95
  4870.5  445.92  4924.1  444.24  4975.6  445.59  4992.6  440.60  4993.1  439.80
  4998.1  439.80  4998.6  440.60  5005.6  444.56  5015.6  445.16  5065.7  443.80
  5104.9  445.92  5117.9  448.65  5124.2  448.20  5132.5  450.06  5138.7  449.64
  5147.0  451.03  5153.3  449.39  5167.9  453.17  5174.1  452.39  5182.4  453.63
  5188.7  453.16  5210.4  454.88  5253.2  455.97  5267.8  458.26  5353.1  461.16
#Mann=3,-1,0
  4493.2    0.16       0  4992.6    0.07       0  4998.6    0.16       0
Bank Sta=4870.5,5104.9
Exp/Cntr=0.3,0.1

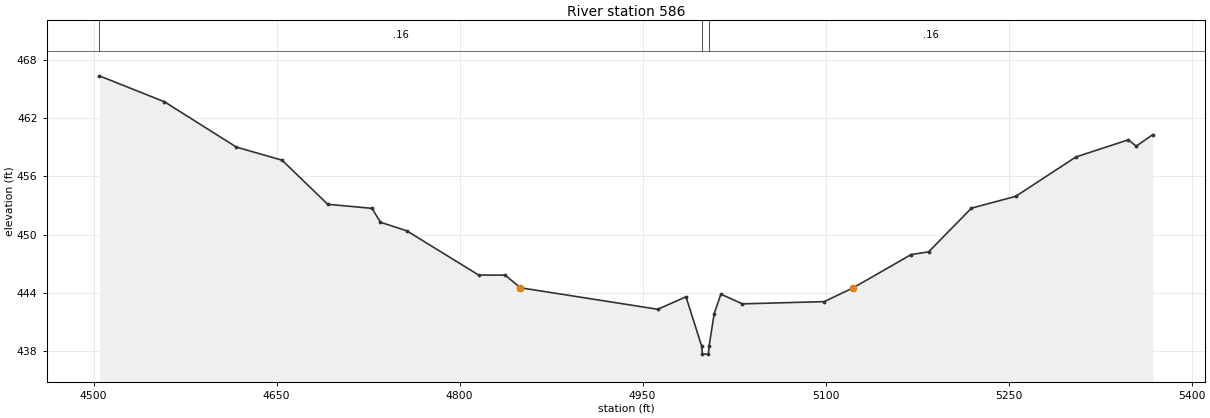
Type RM Length L Ch R = 1,586,0,0,0
BEGIN DESCRIPTION:
UNT 051 in Running Cr Watershed 1.0
END DESCRIPTION:
XS GIS Cut Line= 4
      2906201.02      7043824.97      2906576.48      7044039.83
      2906691.50      7044091.92      2906888.87      7043859.85
#Sta/Elev= 30
  4504.7  466.39  4558.1  463.71  4617.1  459.03  4654.5  457.68  4691.9  453.13
  4728.2  452.71  4735.1  451.28  4756.7  450.39  4815.7  445.82  4837.3  445.82
  4849.9  444.51  4962.5  442.29  4985.6  443.58  4998.5  438.46  4999.0  437.66
  5004.0  437.66  5004.5  438.46  5008.7  441.84  5014.2  443.85  5031.8  442.85
  5098.9  443.08  5122.7  444.51  5170.2  447.94  5184.5  448.22  5219.6  452.73
  5255.9  453.95  5305.3  458.02  5348.1  459.78  5354.7  459.13  5368.2  460.32
#Mann=3,-1,0
  4504.7    0.16       0  4998.5    0.07       0  5004.5    0.16       0
Bank Sta=4849.9,5122.7
Exp/Cntr=0.3,0.1

Chan Stop Cuts=-1