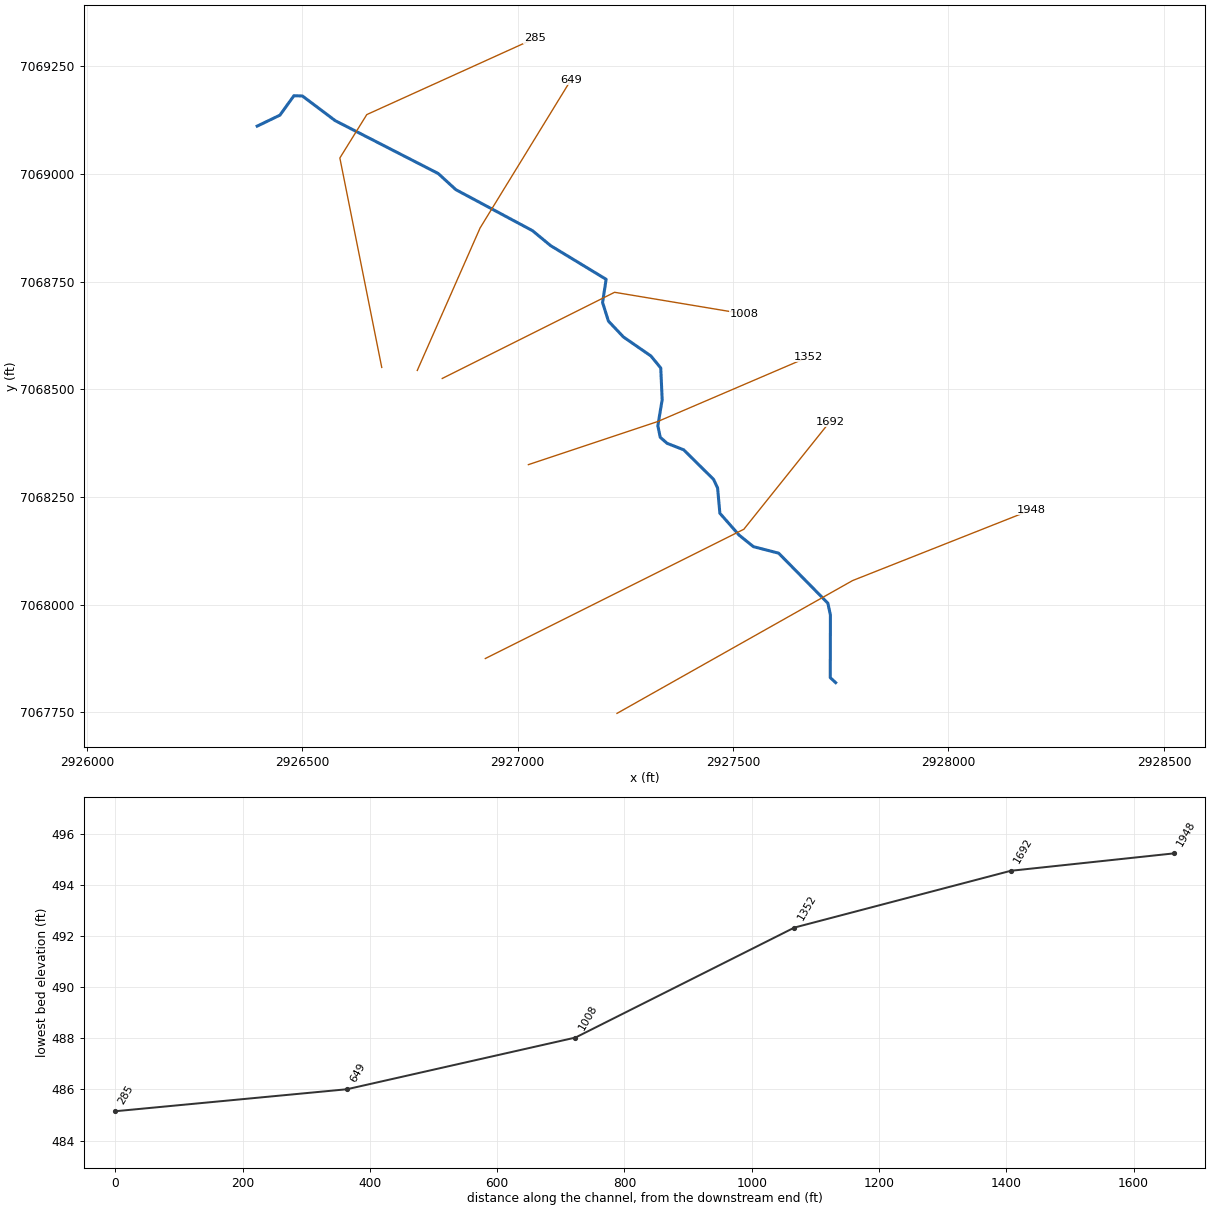
--- UNT 052 in Running Cr Watershed.prj (project) ---

Proj Title=UNT 052 in Running Cr Watershed Base Level Engineering
Current Plan=p01
Default Exp/Contr=0.3,0.1
English Units
Geom File=g01
Flow File=f01
Plan File=p01
BEGIN DESCRIPTION:
UNT 052 in Running Cr Watershed
END DESCRIPTION:

--- UNT 052 in Running Cr Watershed.p01 (plan) ---

Plan Title=Multiple Run
Short Identifier=Multiple
Geom File=g01
Flow File=f01
Subcritical Flow
K Sum by GR= 0
Std Step Tol= 0.01
Critical Tol= 0.01
Num of Std Step Trials= 20
Max Error Tol= 0.3
Flow Tol Ratio= 0.001
Split Flow NTrial= 30
Split Flow Tol= 0.02
Split Flow Ratio= 0.02
Log Output Level= 0
Friction Slope Method= 1
Unsteady Friction Slope Method= 2
Unsteady Bridges Friction Slope Method= 1
Parabolic Critical Depth
Global Vel Dist=  1 , 1 , 1
Global Log Level= 0
CheckData=True
Encroach Param= -1, 0, 0, 0
BEGIN DESCRIPTION:
Multiple Run
END DESCRIPTION:

--- UNT 052 in Running Cr Watershed.f01 (steady flow) ---

Flow Title=Multiple
Number of Profiles=7
Profile Names=10-year,25-year,50-year,1pct_min,100-year,1pct_plu,500-year
River Rch & RM= UNT 052 in Runni,Reach-1,1948
     823    1114    1352     814    1624    3240    2336
Boundary for River Rch & Prof#=UNT 052 in Runni,Reach-1,1
Up Type=0
Dn Type=3
Dn Slope=0.005
Boundary for River Rch & Prof#=UNT 052 in Runni,Reach-1,2
Up Type=0
Dn Type=3
Dn Slope=0.005
Boundary for River Rch & Prof#=UNT 052 in Runni,Reach-1,3
Up Type=0
Dn Type=3
Dn Slope=0.005
Boundary for River Rch & Prof#=UNT 052 in Runni,Reach-1,4
Up Type=0
Dn Type=3
Dn Slope=0.005
Boundary for River Rch & Prof#=UNT 052 in Runni,Reach-1,5
Up Type=0
Dn Type=3
Dn Slope=0.005
Boundary for River Rch & Prof#=UNT 052 in Runni,Reach-1,6
Up Type=0
Dn Type=3
Dn Slope=0.005
Boundary for River Rch & Prof#=UNT 052 in Runni,Reach-1,7
Up Type=0
Dn Type=3
Dn Slope=0.005

--- UNT 052 in Running Cr Watershed.g01 (geometry) ---

Geom Title=Existing Conditions

River Reach=UNT 052 in Runni,Reach-1
Reach XY= 30
      2927738.10      7067818.97      2927725.59      7067830.71
      2927725.93      7067975.85      2927720.03      7068003.38
      2927605.85      7068119.48      2927547.19      7068134.67
      2927513.88      7068161.53      2927469.36      7068212.24
      2927464.09      7068270.76      2927454.65      7068290.89
      2927385.41      7068359.36      2927346.76      7068374.55
      2927330.99      7068388.48      2927325.41      7068415.25
      2927335.46      7068475.81      2927332.14      7068549.36
      2927309.27      7068577.22      2927245.58      7068621.25
      2927210.71      7068658.17      2927197.14      7068701.19
      2927205.35      7068755.14      2927076.63      7068833.20
      2927034.47      7068868.01      2926856.62      7068963.19
      2926815.59      7069000.71      2926576.63      7069123.33
      2926500.45      7069180.58      2926480.78      7069181.24
      2926448.26      7069136.09      2926395.59      7069110.71

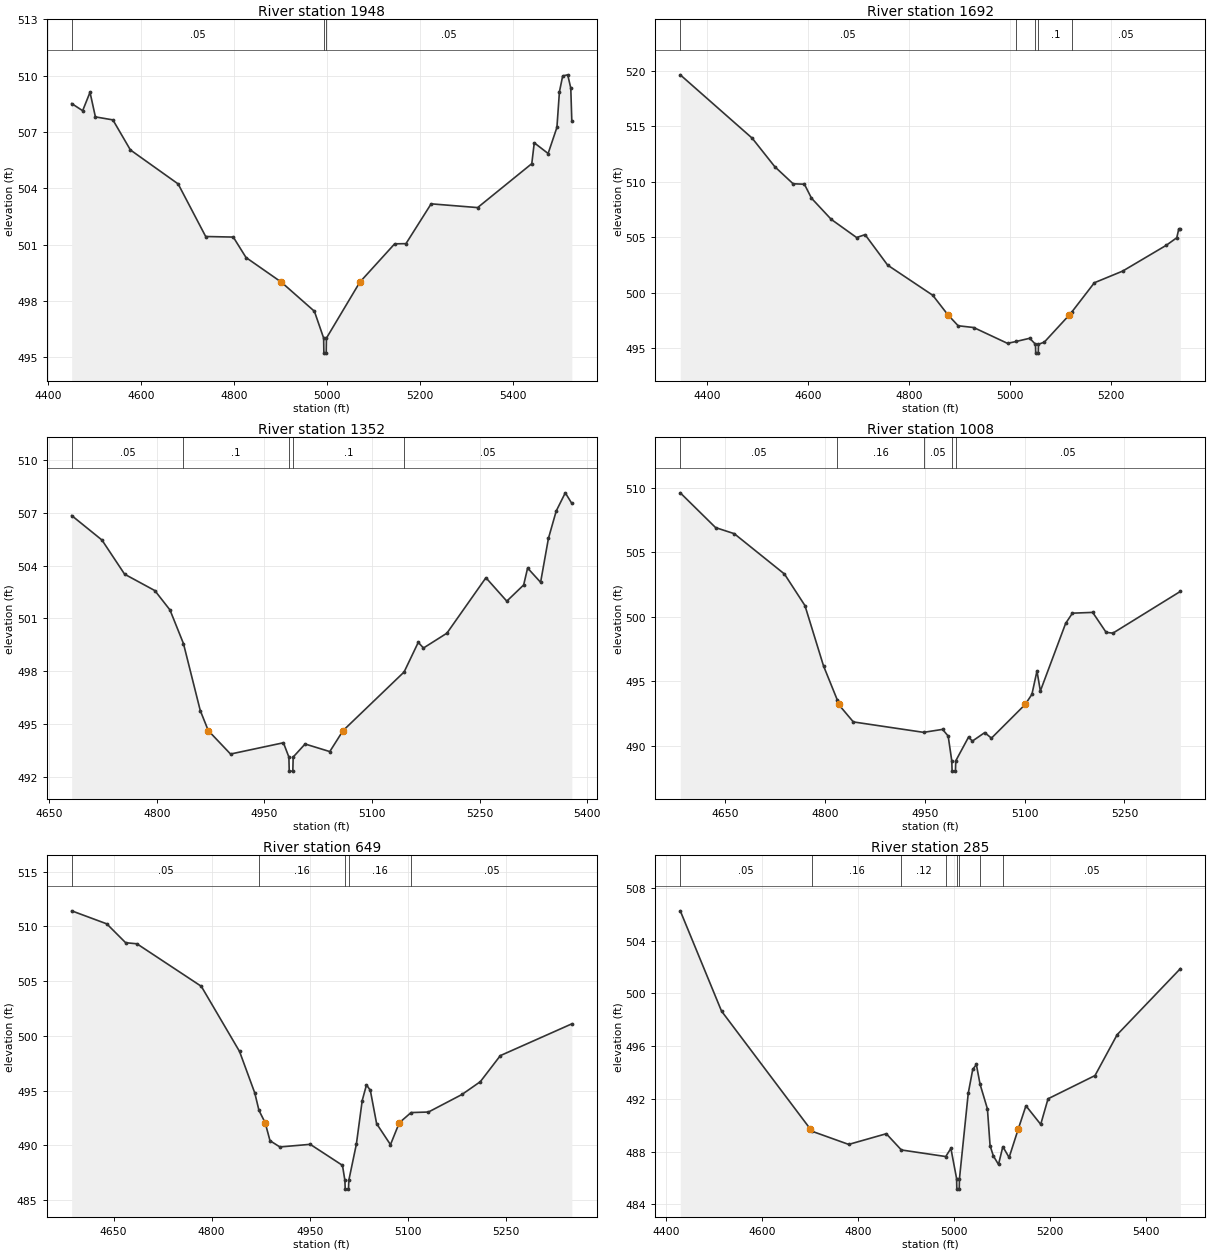
Type RM Length L Ch R = 1,1948,256,256,256
BEGIN DESCRIPTION:
UNT 052 in Running Cr Watershed 6.0
END DESCRIPTION:
XS GIS Cut Line= 3
      2927230.64      7067747.69      2927777.36      7068055.90
      2928193.20      7068220.39
#Sta/Elev= 30
  4451.4  508.52  4475.0  508.14  4490.8  509.12  4502.4  507.81  4540.0  507.65
  4577.6  506.05  4680.2  504.24  4739.4  501.44  4798.7  501.41  4826.1  500.32
  4902.0  499.01  4973.0  497.46  4992.9  496.03  4993.4  495.23  4998.4  495.23
  4998.9  496.03  5070.7  499.01  5145.5  501.05  5169.8  501.06  5223.9  503.18
  5323.8  502.98  5440.2  505.32  5445.5  506.43  5475.3  505.86  5494.2  507.25
  5499.6  509.15  5506.6  509.99  5517.4  510.05  5524.0  509.34  5526.2  507.58
#Mann=3,-1,0
  4451.4    0.05       0  4992.9    0.03       0  4998.9    0.05       0
Bank Sta=4902,5070.7
Exp/Cntr=0.3,0.1

Type RM Length L Ch R = 1,1692,340,340,340
BEGIN DESCRIPTION:
UNT 052 in Running Cr Watershed 5.0
END DESCRIPTION:
XS GIS Cut Line= 3
      2926924.99      7067875.00      2927525.00      7068175.00
      2927725.01      7068425.01
#Sta/Elev= 30
  4347.4  519.66  4490.0  513.94  4534.7  511.37  4571.0  509.83  4593.4  509.79
  4607.4  508.53  4646.5  506.62  4696.8  504.98  4713.6  505.24  4758.3  502.49
  4847.7  499.77  4877.5  498.02  4898.0  497.02  4928.8  496.86  4995.9  495.43
  5012.7  495.60  5039.8  495.89  5051.2  495.35  5051.7  494.55  5056.7  494.55
  5057.2  495.35  5068.7  495.54  5118.6  498.01  5123.9  498.30  5167.9  500.90
  5223.9  501.95  5310.4  504.28  5331.2  504.96  5335.2  505.76  5338.4  505.76
#Mann=5,-1,0
  4347.4    0.05       0  5012.7     0.1       0  5051.2    0.03       0
  5057.2     0.1       0  5123.9    0.05       0
Bank Sta=4877.5,5118.6
Exp/Cntr=0.3,0.1

Type RM Length L Ch R = 1,1352,344,344,344
BEGIN DESCRIPTION:
UNT 052 in Running Cr Watershed 4.0
END DESCRIPTION:
XS GIS Cut Line= 3
      2927025.00      7068325.00      2927325.00      7068425.00
      2927674.99      7068574.99
#Sta/Elev= 30
  4681.4  506.84  4723.6  505.45  4755.2  503.51  4797.3  502.58  4818.4  501.48
  4837.2  499.57  4860.6  495.77  4871.8  494.63  4902.8  493.30  4976.5  493.94
  4984.1  493.13  4984.6  492.33  4989.6  492.33  4990.1  493.13  5006.7  493.87
  5041.1  493.44  5059.6  494.63  5144.7  497.96  5164.4  499.64  5171.7  499.32
  5204.3  500.16  5258.7  503.31  5287.8  501.98  5311.3  502.90  5316.8  503.86
  5334.9  503.05  5345.8  505.54  5356.7  507.10  5369.3  508.13  5378.4  507.53
#Mann=5,-1,0
  4681.4    0.05       0  4837.2     0.1       0  4984.1    0.07       0
  4990.1     0.1       0  5144.7    0.05       0
Bank Sta=4871.8,5059.6
Exp/Cntr=0.3,0.1

Type RM Length L Ch R = 1,1008,359,359,359
BEGIN DESCRIPTION:
UNT 052 in Running Cr Watershed 3.0
END DESCRIPTION:
XS GIS Cut Line= 3
      2926824.99      7068525.00      2927225.00      7068725.00
      2927525.04      7068674.99
#Sta/Elev= 30
  4582.6  509.63  4635.7  506.93  4663.7  506.46  4739.1  503.33  4769.9  500.88
  4797.8  496.20  4818.7  493.53  4820.4  493.21  4842.6  491.85  4948.1  491.04
  4976.7  491.27  4985.1  490.75  4990.5  488.83  4991.0  488.03  4996.0  488.03
  4996.5  488.83  5015.8  490.68  5021.4  490.36  5040.0  491.02  5050.1  490.59
  5100.9  493.21  5110.9  493.99  5118.5  495.80  5123.6  494.25  5161.6  499.50
  5171.8  500.29  5202.2  500.35  5222.4  498.80  5232.6  498.74  5334.0  501.98
#Mann=5,-1,0
  4582.6    0.05       0  4818.7    0.16       0  4948.1    0.05       0
  4990.5    0.03       0  4996.5    0.05       0
Bank Sta=4820.4,5100.9
Exp/Cntr=0.3,0.1

Type RM Length L Ch R = 1,649,364,364,364
BEGIN DESCRIPTION:
UNT 052 in Running Cr Watershed 2.0
END DESCRIPTION:
XS GIS Cut Line= 3
      2926767.08      7068543.67      2926912.92      7068874.42
      2927123.86      7069218.18
#Sta/Elev= 30
  4585.9  511.42  4639.6  510.23  4668.4  508.51  4685.7  508.41  4784.1  504.53
  4842.6  498.58  4865.9  494.79  4872.3  493.20  4881.8  492.07  4889.2  490.43
  4904.3  489.86  4950.7  490.10  5000.0  488.18  5003.7  486.81  5004.2  486.01
  5009.2  486.01  5009.7  486.81  5021.3  490.13  5030.2  494.10  5036.7  495.53
  5042.6  495.03  5052.2  491.99  5073.4  490.07  5086.9  492.07  5104.9  493.00
  5131.5  493.05  5182.7  494.65  5210.8  495.82  5241.4  498.20  5350.7  501.10
#Mann=5,-1,0
  4585.9    0.05       0  4872.3    0.16       0  5003.7    0.07       0
  5009.7    0.16       0  5104.9    0.05       0
Bank Sta=4881.8,5086.9
Exp/Cntr=0.3,0.1

Type RM Length L Ch R = 1,285,0,0,0
BEGIN DESCRIPTION:
UNT 052 in Running Cr Watershed 1.0
END DESCRIPTION:
XS GIS Cut Line= 4
      2926684.62      7068550.63      2926587.40      7069036.74
      2926649.90      7069137.44      2927040.30      7069314.42
#Sta/Elev= 30
  4429.8  506.25  4515.8  498.65  4700.5  489.73  4703.5  489.55  4781.0  488.54
  4859.4  489.35  4890.8  488.12  4983.4  487.62  4994.1  488.24  5006.0  485.95
  5006.5  485.15  5011.5  485.15  5012.0  485.95  5030.3  492.42  5039.7  494.23
  5047.2  494.60  5054.9  493.11  5070.3  491.23  5075.8  488.45  5082.6  487.67
  5093.4  487.02  5102.4  488.37  5115.5  487.55  5134.7  489.72  5150.6  491.47
  5181.4  490.06  5196.7  492.00  5294.6  493.76  5340.8  496.86  5472.7  501.87
#Mann=8,-1,0
  4429.8    0.05       0  4703.5    0.16       0  4890.8    0.12       0
  4983.4    0.07       0  5006.0    0.07       0  5012.0    0.07       0
  5054.9    0.16       0  5102.4    0.05       0
Bank Sta=4700.5,5134.7
Exp/Cntr=0.3,0.1

Chan Stop Cuts=-1