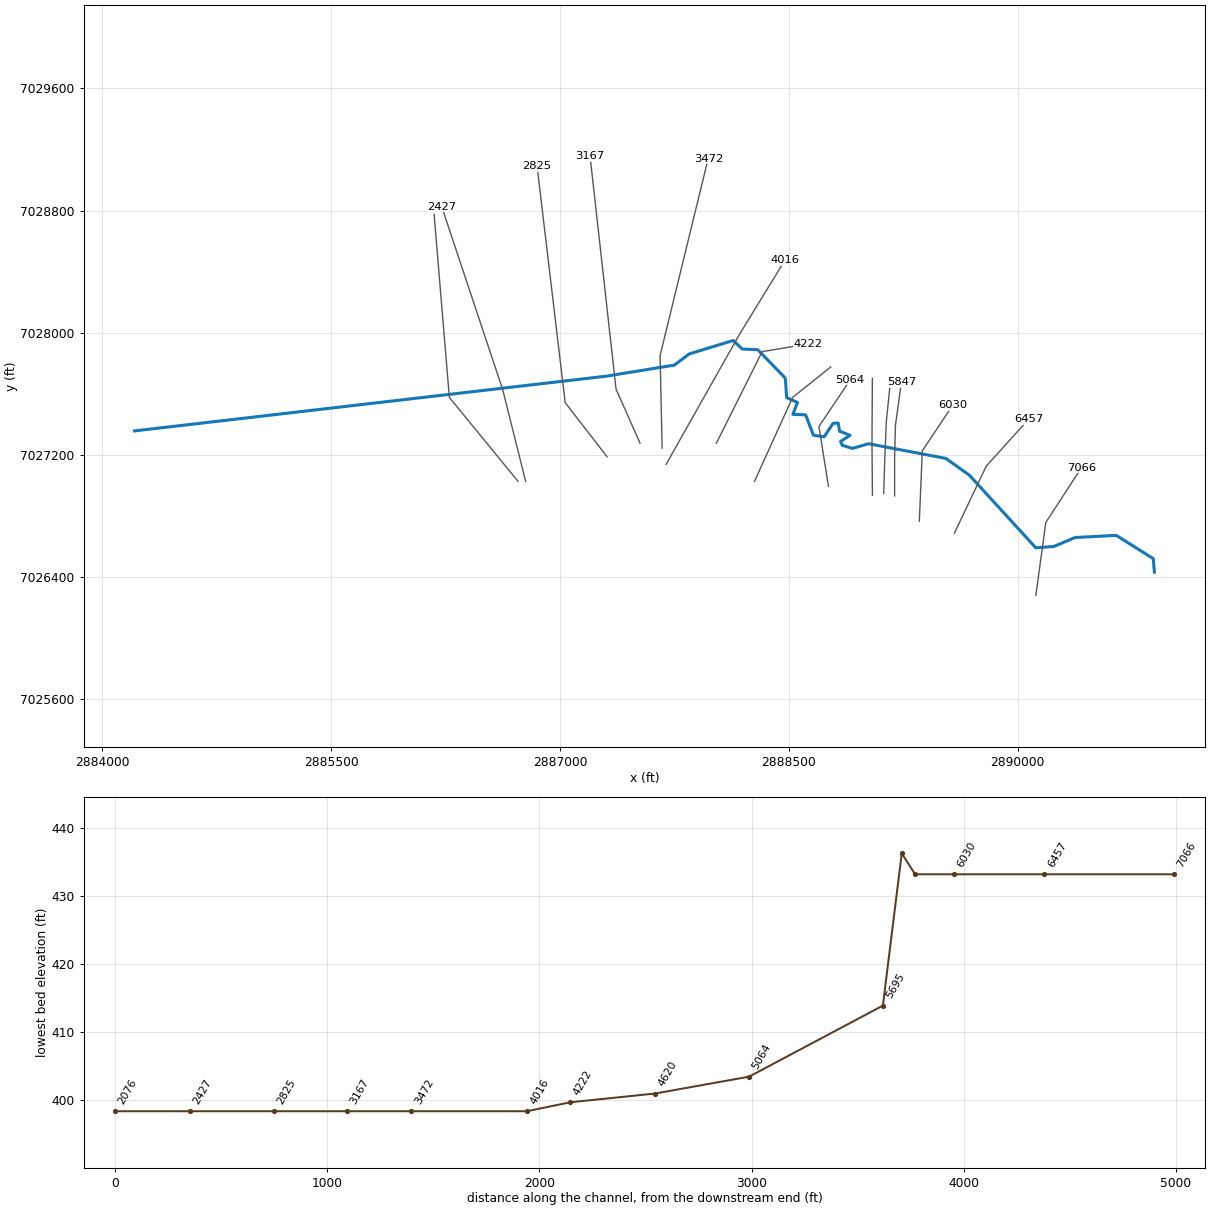
--- UNT 053 in Running Cr Watershed.prj (project) ---

Proj Title=UNT 053 in Running Cr Watershed Base Level Engineering
Current Plan=p01
Default Exp/Contr=0.3,0.1
English Units
Geom File=g01
Flow File=f01
Plan File=p01
BEGIN DESCRIPTION:
UNT 053 in Running Cr Watershed
END DESCRIPTION:

--- UNT 053 in Running Cr Watershed.p01 (plan) ---

Plan Title=Multiple Run
Short Identifier=Multiple
Geom File=g01
Flow File=f01
Subcritical Flow
K Sum by GR= 0
Std Step Tol= 0.01
Critical Tol= 0.01
Num of Std Step Trials= 20
Max Error Tol= 0.3
Flow Tol Ratio= 0.001
Split Flow NTrial= 30
Split Flow Tol= 0.02
Split Flow Ratio= 0.02
Log Output Level= 0
Friction Slope Method= 1
Unsteady Friction Slope Method= 2
Unsteady Bridges Friction Slope Method= 1
Parabolic Critical Depth
Global Vel Dist=  1 , 1 , 1
Global Log Level= 0
CheckData=True
Encroach Param= -1, 0, 0, 0
BEGIN DESCRIPTION:
Multiple Run
END DESCRIPTION:

--- UNT 053 in Running Cr Watershed.f01 (steady flow) ---

Flow Title=Multiple
Number of Profiles=7
Profile Names=10-year,25-year,50-year,1pct_min,100-year,1pct_plu,500-year
River Rch & RM= UNT 053 in Runni,Reach-1,7066
     564     758     917     552    1102    2199    1592
River Rch & RM= UNT 053 in Runni,Reach-1,3472
     649     874    1058     636    1269    2533    1831
Boundary for River Rch & Prof#=UNT 053 in Runni,Reach-1,1
Up Type=0
Dn Type=3
Dn Slope=0.005
Boundary for River Rch & Prof#=UNT 053 in Runni,Reach-1,2
Up Type=0
Dn Type=3
Dn Slope=0.005
Boundary for River Rch & Prof#=UNT 053 in Runni,Reach-1,3
Up Type=0
Dn Type=3
Dn Slope=0.005
Boundary for River Rch & Prof#=UNT 053 in Runni,Reach-1,4
Up Type=0
Dn Type=3
Dn Slope=0.005
Boundary for River Rch & Prof#=UNT 053 in Runni,Reach-1,5
Up Type=0
Dn Type=3
Dn Slope=0.005
Boundary for River Rch & Prof#=UNT 053 in Runni,Reach-1,6
Up Type=0
Dn Type=3
Dn Slope=0.005
Boundary for River Rch & Prof#=UNT 053 in Runni,Reach-1,7
Up Type=0
Dn Type=3
Dn Slope=0.005

--- UNT 053 in Running Cr Watershed.g01 (geometry) ---

Geom Title=Existing Conditions

River Reach=UNT 053 in Runni,Reach-1
Reach XY= 30
      2890896.40      7026429.80      2890888.59      7026518.35
      2890646.40      7026670.69      2890376.25      7026656.72
      2890237.72      7026598.12      2890118.73      7026589.23
      2889683.61      7027065.20      2889529.10      7027175.31
      2889022.94      7027271.22      2888917.36      7027240.83
      2888850.53      7027261.22      2888839.20      7027286.14
      2888901.50      7027326.92      2888833.54      7027352.98
      2888823.34      7027407.35      2888790.49      7027405.08
      2888731.59      7027316.73      2888661.36      7027326.92
      2888610.38      7027460.59      2888526.56      7027463.99
      2888557.14      7027542.15      2888485.78      7027573.86
      2888476.72      7027701.87      2888296.61      7027887.64
      2888194.66      7027892.17      2888135.38      7027948.06
      2887848.03      7027860.32      2887749.57      7027786.64
      2887304.90      7027714.42      2884211.46      7027355.53

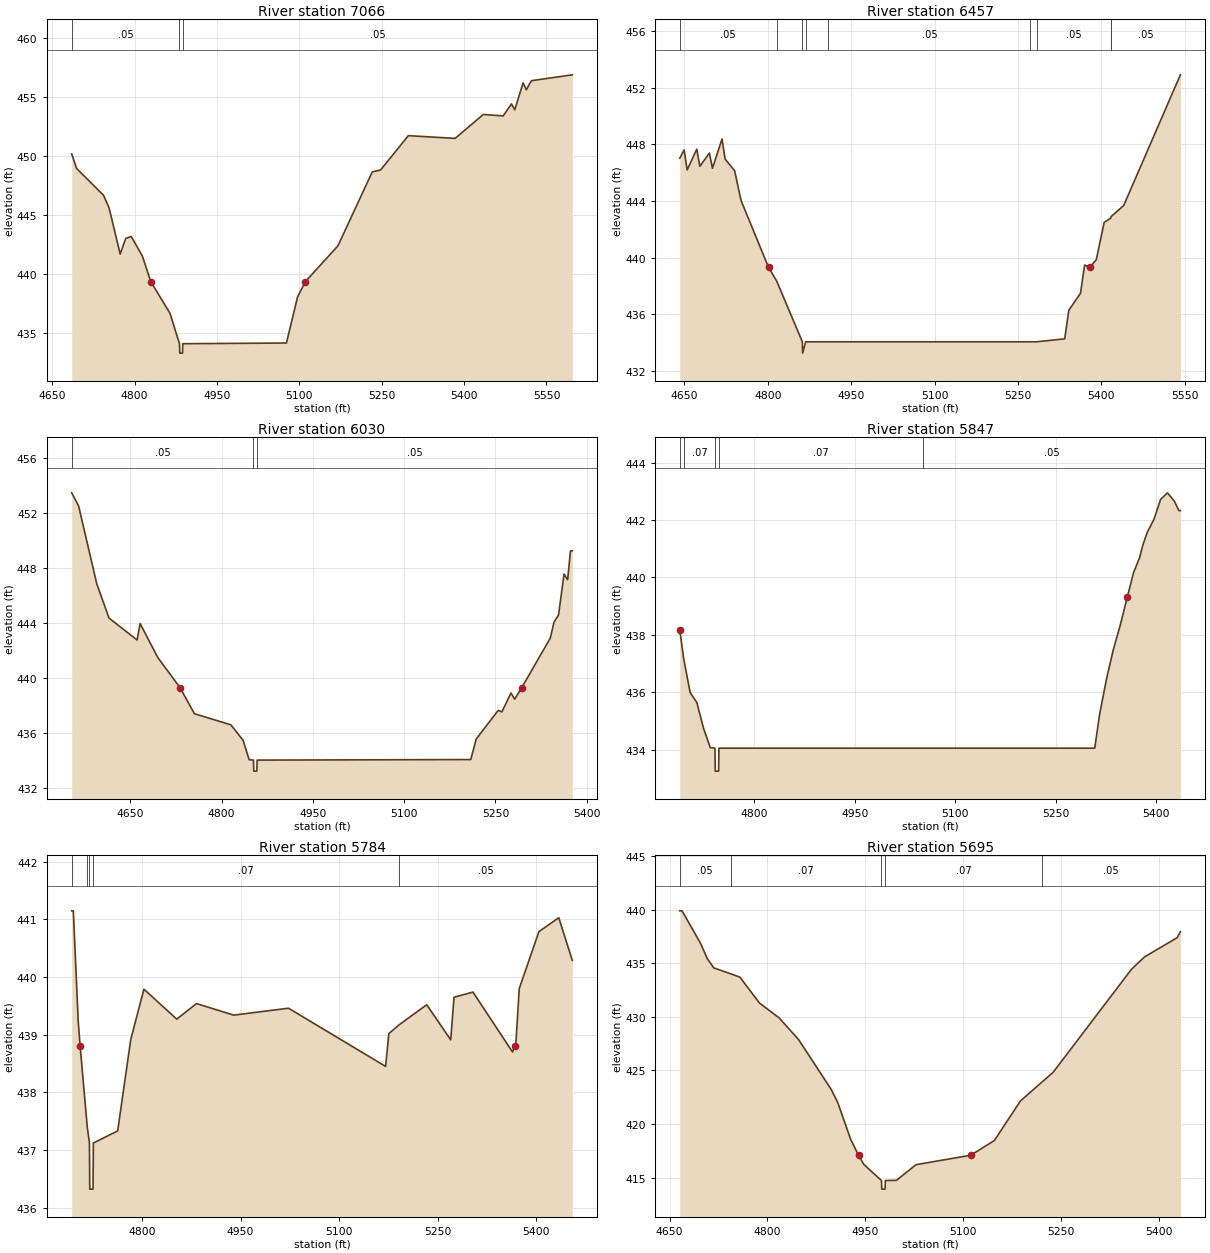
Type RM Length L Ch R = 1,7066,609,609,609
BEGIN DESCRIPTION:
UNT 053 in Running Cr Watershed 12.0
END DESCRIPTION:
XS GIS Cut Line= 3
      2890119.28      7026277.52      2890184.39      7026754.99
      2890418.78      7027115.26
#Sta/Elev= 30
  4685.4  450.18  4694.4  448.94  4743.4  446.66  4753.5  445.59  4773.7  441.67
  4783.8  443.00  4793.9  443.16  4814.1  441.50  4829.5  439.32  4864.5  436.63
  4881.7  434.05  4882.2  433.25  4887.2  433.25  4887.7  434.05  5076.5  434.11
  5096.7  438.02  5110.9  439.32  5170.3  442.37  5232.8  448.65  5247.9  448.81
  5298.5  451.73  5383.7  451.50  5435.0  453.53  5471.2  453.41  5486.4  454.43
  5492.3  453.93  5507.5  456.22  5513.4  455.63  5522.6  456.40  5597.1  456.90
#Mann=3,-1,0
  4685.4    0.05       0  4881.7   0.033       0  4887.7    0.05       0
Bank Sta=4829.5,5110.9
Exp/Cntr=0.3,0.1

Type RM Length L Ch R = 1,6457,427,427,427
BEGIN DESCRIPTION:
Mapping XS 7daf1713
END DESCRIPTION:
XS GIS Cut Line= 3
      2889585.42      7026685.54      2889793.76      7027123.92
      2890071.51      7027432.04
#Sta/Elev= 30
  4641.9  447.02  4649.7  447.60  4655.2  446.19  4672.4  447.66  4678.0  446.45
  4695.1  447.38  4700.7  446.31  4717.9  448.38  4723.4  446.96  4740.6  446.13
  4752.0  444.04  4801.5  439.31  4816.2  438.34  4862.3  434.05  4862.8  433.25
  4868.3  434.05  4908.8  434.05  5272.5  434.05  5283.4  434.05  5334.1  434.26
  5341.5  436.28  5362.5  437.48  5369.9  439.47  5379.7  439.31  5390.9  439.86
  5405.1  442.49  5416.7  442.78  5417.9  442.91  5440.2  443.68  5542.1  452.91
#Mann=9,-1,0
  4641.9    0.05       0  4816.2    0.16       0  4862.3   0.033       0
  4868.3    0.16       0  4908.8    0.05       0  5272.5    0.07       0
  5283.4    0.05       0  5416.7    0.07       0  5417.9    0.05       0
Bank Sta=4801.5,5379.7
Exp/Cntr=0.3,0.1

Type RM Length L Ch R = 1,6030,183,183,183
BEGIN DESCRIPTION:
UNT 053 in Running Cr Watershed 11.0
END DESCRIPTION:
XS GIS Cut Line= 3
      2889355.40      7026763.72      2889375.00      7027225.00
      2889575.02      7027525.04
#Sta/Elev= 30
  4553.9  453.45  4565.2  452.51  4595.2  446.83  4615.2  444.36  4661.3  442.77
  4666.3  443.96  4695.3  441.50  4731.9  439.31  4755.4  437.42  4815.4  436.61
  4835.4  435.49  4845.4  434.08  4852.5  434.05  4853.0  433.25  4858.0  433.25
  4858.5  434.05  5209.4  434.09  5218.4  435.58  5254.5  437.66  5260.5  437.55
  5275.5  438.92  5281.5  438.47  5293.2  439.31  5340.1  442.91  5346.1  444.06
  5353.6  444.58  5362.6  447.55  5368.6  447.14  5373.2  449.24  5376.2  449.24
#Mann=3,-1,0
  4553.9    0.05       0  4852.5   0.033       0  4858.5    0.05       0
Bank Sta=4731.9,5293.2
Exp/Cntr=0.3,0.1

Type RM Length L Ch R = 1,5847,63,63,63
BEGIN DESCRIPTION:
Mapping XS 9562ed65
END DESCRIPTION:
XS GIS Cut Line= 4
      2889193.50      7026929.49      2889193.50      7027184.68
      2889198.71      7027390.41      2889237.77      7027674.24
#Sta/Elev= 27
  4688.5  438.17  4694.4  437.16  4704.0  435.99  4714.0  435.64  4724.0  434.74
  4734.0  434.07  4741.0  434.05  4741.5  433.25  4746.5  433.25  4747.0  434.05
  5052.0  434.05  5308.1  434.05  5315.6  435.26  5325.7  436.46  5335.8  437.48
  5345.9  438.31  5356.7  439.31  5366.1  440.17  5375.1  440.69  5380.1  441.14
  5386.3  441.56  5396.4  442.02  5406.5  442.72  5416.6  442.95  5426.7  442.67
  5433.9  442.33  5436.0  442.33
#Mann=5,-1,0
  4688.5    0.05       0  4694.4    0.07       0  4741.0    0.07       0
  4747.0    0.07       0  5052.0    0.05       0
Bank Sta=4688.5,5356.7
Exp/Cntr=0.3,0.1

Type RM Length L Ch R = 1,5784,89,89,89
BEGIN DESCRIPTION:
Mapping XS 30ed9d3d
END DESCRIPTION:
XS GIS Cut Line= 4
      2889121.89      7026945.06      2889128.40      7027153.43
      2889138.81      7027413.85      2889168.76      7027705.51
#Sta/Elev= 30
  4692.9  441.15  4695.4  441.15  4702.8  439.24  4705.7  438.81  4716.6  437.40
  4719.9  437.12  4720.4  436.32  4725.4  436.32  4725.9  437.12  4762.9  437.33
  4782.9  438.92  4802.9  439.79  4852.9  439.27  4882.9  439.54  4939.7  439.34
  5023.0  439.46  5170.9  438.45  5175.9  439.02  5191.3  439.17  5233.5  439.52
  5270.1  438.91  5275.1  439.65  5303.9  439.74  5364.2  438.70  5367.8  438.81
  5369.3  438.85  5374.4  439.80  5404.4  440.79  5434.6  441.03  5455.2  440.29
#Mann=5,-1,0
  4692.9    0.05       0  4716.6    0.07       0  4719.9    0.07       0
  4725.9    0.07       0  5191.3    0.05       0
Bank Sta=4705.7,5367.8
Exp/Cntr=0.3,0.1

Type RM Length L Ch R = 1,5695,631,631,631
BEGIN DESCRIPTION:
UNT 053 in Running Cr Watershed 10.0
END DESCRIPTION:
XS GIS Cut Line= 3
      2889048.10      7026932.93      2889045.06      7027271.88
      2889047.67      7027700.11
#Sta/Elev= 30
  4665.6  439.88  4669.1  439.88  4697.7  436.82  4707.7  435.43  4717.7  434.56
  4743.7  434.01  4757.7  433.70  4787.7  431.29  4817.7  429.91  4847.7  427.88
  4897.7  423.23  4907.7  422.01  4927.7  418.55  4939.6  417.10  4947.7  416.24
  4974.7  414.74  4975.2  413.94  4980.2  413.94  4980.7  414.74  4997.7  414.76
  5027.7  416.22  5111.6  417.10  5147.7  418.47  5187.7  422.16  5220.1  423.89
  5237.7  424.82  5357.7  434.42  5377.7  435.58  5427.7  437.37  5432.8  437.93
#Mann=5,-1,0
  4665.6    0.05       0  4743.7    0.07       0  4974.7    0.07       0
  4980.7    0.07       0  5220.1    0.05       0
Bank Sta=4939.6,5111.6
Exp/Cntr=0.3,0.1

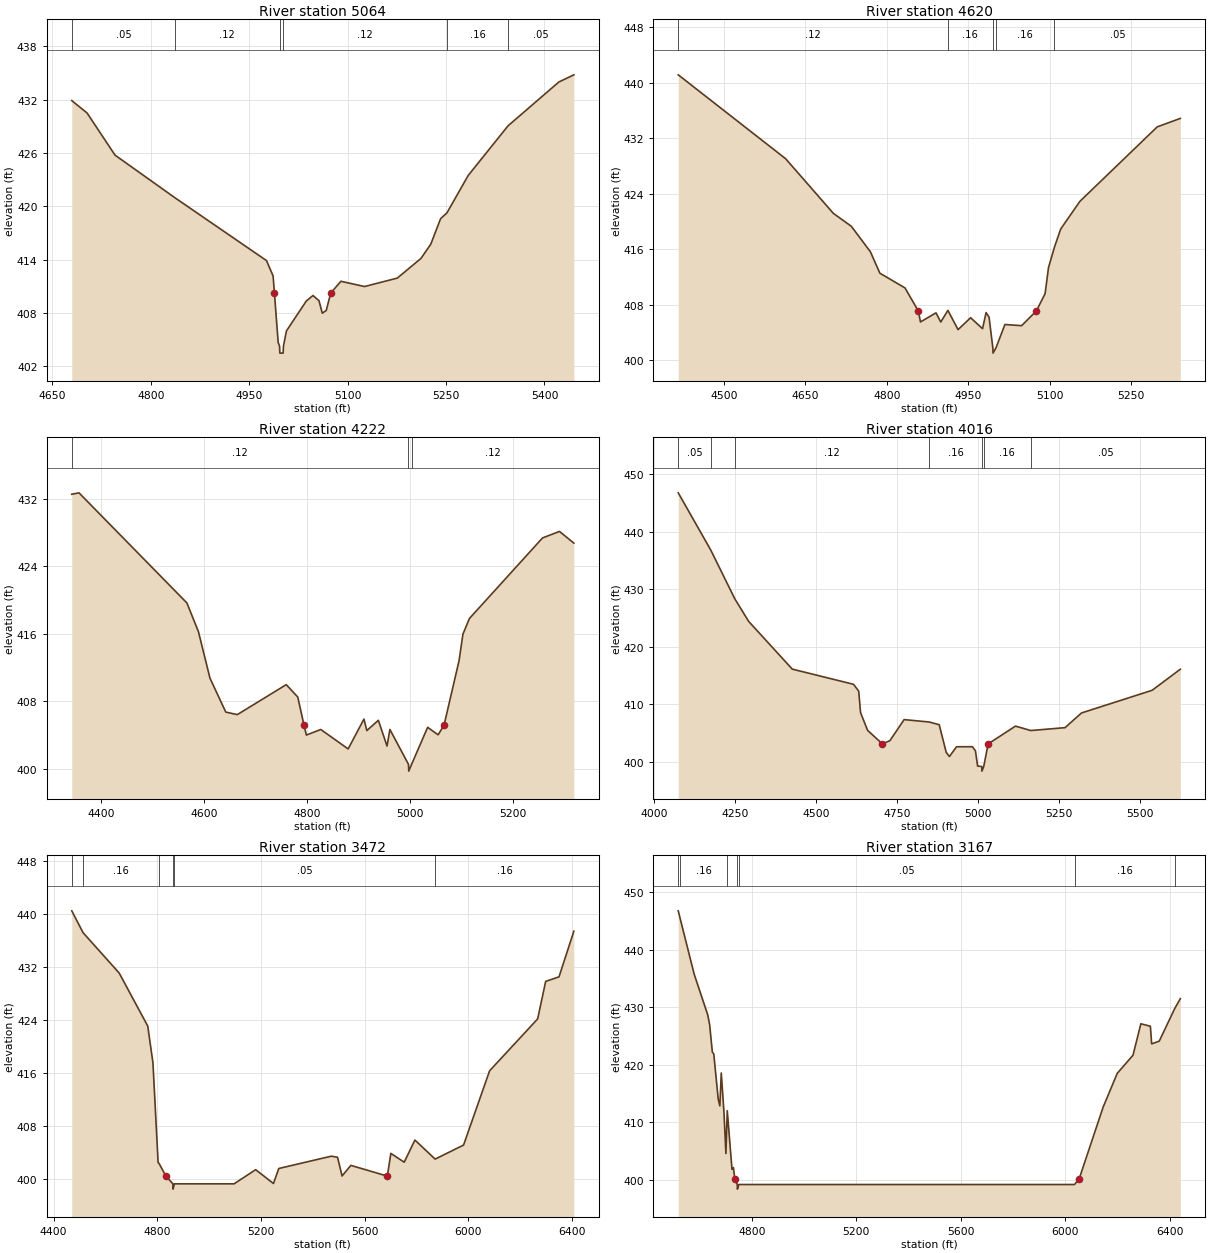
Type RM Length L Ch R = 1,5064,444,444,444
BEGIN DESCRIPTION:
UNT 053 in Running Cr Watershed 9.0
END DESCRIPTION:
XS GIS Cut Line= 3
      2888759.90      7026992.01      2888697.41      7027384.34
      2888902.24      7027689.85
#Sta/Elev= 30
  4679.7  431.89  4703.0  430.50  4745.6  425.76  4837.0  420.96  4976.4  413.90
  4986.5  412.17  4988.5  410.24  4994.3  404.66  4996.3  404.29  4996.8  403.49
  5001.8  403.49  5002.3  404.29  5006.8  405.98  5037.1  409.35  5047.3  409.97
  5056.4  409.39  5061.5  407.98  5067.5  408.29  5074.3  410.24  5089.8  411.57
  5125.9  410.98  5175.8  411.93  5211.8  414.14  5226.8  415.74  5241.8  418.62
  5251.4  419.26  5283.8  423.47  5344.6  429.06  5421.9  433.98  5444.8  434.79
#Mann=6,-1,0
  4679.7    0.05       0  4837.0    0.12       0  4996.3    0.07       0
  5002.3    0.12       0  5251.4    0.16       0  5344.6    0.05       0
Bank Sta=4988.5,5074.3
Exp/Cntr=0.3,0.1

Type RM Length L Ch R = 1,4620,398,398,398
BEGIN DESCRIPTION:
UNT 053 in Running Cr Watershed 8.0
END DESCRIPTION:
XS GIS Cut Line= 3
      2888274.98      7027024.96      2888525.00      7027575.00
      2888775.04      7027775.03
#Sta/Elev= 30
  4415.9  441.17  4613.7  429.06  4701.5  421.18  4734.5  419.32  4769.6  415.65
  4787.2  412.54  4833.4  410.42  4857.9  407.09  4861.9  405.51  4890.5  406.82
  4899.3  405.50  4912.4  407.18  4931.1  404.40  4954.2  406.12  4976.2  404.54
  4982.7  406.86  4988.2  406.20  4995.1  401.81  4995.6  401.01  5001.1  401.81
  5017.4  405.14  5048.1  404.97  5075.2  407.09  5091.3  409.58  5097.7  413.38
  5108.6  416.31  5120.1  418.92  5155.4  422.91  5297.8  433.66  5340.3  434.88
#Mann=5,-1,0
  4415.9    0.12       0  4912.4    0.16       0  4995.1    0.07       0
  5001.1    0.16       0  5108.6    0.05       0
Bank Sta=4857.9,5075.2
Exp/Cntr=0.3,0.1

Type RM Length L Ch R = 1,4222,206,206,206
BEGIN DESCRIPTION:
UNT 053 in Running Cr Watershed 7.0
END DESCRIPTION:
XS GIS Cut Line= 3
      2888024.98      7027274.97      2888325.00      7027875.00
      2888625.00      7027925.00
#Sta/Elev= 30
  4342.8  432.51  4356.8  432.68  4566.4  419.64  4588.8  416.24  4611.2  410.73
  4641.9  406.72  4664.3  406.42  4759.3  409.97  4781.7  408.50  4793.8  405.16
  4798.4  404.00  4826.4  404.66  4879.5  402.36  4910.2  405.89  4915.8  404.53
  4938.2  405.75  4955.0  402.70  4960.6  404.66  4996.7  400.53  4997.2  399.73
  5002.7  400.53  5033.9  404.92  5054.2  404.03  5065.7  405.16  5094.8  412.78
  5102.4  415.94  5115.0  417.80  5257.0  427.34  5289.9  428.11  5317.8  426.73
#Mann=3,-1,0
  4342.8    0.12       0  4996.7    0.07       0  5002.7    0.12       0
Bank Sta=4793.8,5065.7
Exp/Cntr=0.3,0.1

Type RM Length L Ch R = 1,4016,544,544,544
BEGIN DESCRIPTION:
UNT 053 in Running Cr Watershed 6.0
END DESCRIPTION:
XS GIS Cut Line= 3
      2887695.66      7027136.05      2888176.57      7027988.50
      2888475.01      7028475.02
#Sta/Elev= 30
  4073.8  446.75  4174.1  436.82  4248.5  428.33  4291.3  424.41  4425.7  416.13
  4614.9  413.49  4630.8  412.29  4636.5  408.57  4658.2  405.49  4703.9  403.14
  4727.0  403.70  4770.9  407.36  4848.5  406.94  4879.2  406.47  4900.9  401.66
  4910.7  400.95  4932.7  402.64  4981.7  402.65  4991.1  401.94  4997.7  399.29
  5010.6  399.21  5011.1  398.41  5016.6  399.21  5030.3  403.14  5114.7  406.23
  5161.6  405.46  5267.5  405.96  5318.3  408.51  5536.3  412.45  5623.3  416.11
#Mann=7,-1,0
  4073.8    0.05       0  4174.1    0.16       0  4248.5    0.12       0
  4848.5    0.16       0  5010.6    0.07       0  5016.6    0.16       0
  5161.6    0.05       0
Bank Sta=4703.9,5030.3
Exp/Cntr=0.3,0.1

Type RM Length L Ch R = 1,3472,305,305,305
BEGIN DESCRIPTION:
UNT 053 in Running Cr Watershed 5.0
END DESCRIPTION:
XS GIS Cut Line= 3
      2887669.63      7027242.00      2887656.31      7027849.76
      2887971.55      7029140.61
#Sta/Elev= 30
  4470.1  440.48  4513.7  437.18  4653.1  431.07  4763.2  423.06  4783.2  417.52
  4803.2  402.43  4807.1  402.28  4833.0  400.38  4860.2  399.21  4860.7  398.41
  4866.2  399.21  5096.2  399.21  5179.5  401.35  5248.1  399.26  5268.7  401.53
  5471.2  403.39  5495.2  403.23  5512.8  400.40  5546.6  402.00  5687.3  400.38
  5701.0  403.81  5752.5  402.48  5793.7  405.83  5871.8  402.95  5981.4  405.07
  6081.9  416.30  6267.2  424.14  6298.1  429.81  6349.6  430.50  6406.8  437.40
#Mann=6,-1,0
  4470.1    0.05       0  4513.7    0.16       0  4807.1    0.05       0
  4860.2   0.033       0  4866.2    0.05       0  5871.8    0.16       0
Bank Sta=4833,5687.3
Exp/Cntr=0.3,0.1

Type RM Length L Ch R = 1,3167,342,342,342
BEGIN DESCRIPTION:
UNT 053 in Running Cr Watershed 4.0
END DESCRIPTION:
XS GIS Cut Line= 3
      2887525.00      7027274.99      2887367.53      7027629.31
      2887197.41      7029155.12
#Sta/Elev= 30
  4518.1  446.77  4526.0  445.34  4579.0  435.79  4631.0  428.71  4638.5  426.96
  4648.7  422.23  4654.2  421.90  4671.3  414.03  4677.5  412.88  4682.9  418.59
  4693.2  411.81  4700.7  404.59  4705.9  412.04  4724.0  401.85  4729.4  402.16
  4734.7  400.23  4744.2  399.21  4744.7  398.41  4750.2  399.21  6035.9  399.21
  6054.0  400.23  6145.6  412.67  6199.5  418.52  6259.9  421.68  6290.0  427.14
  6326.4  426.72  6331.4  423.65  6360.5  424.13  6419.4  429.76  6441.1  431.50
#Mann=7,-1,0
  4518.1    0.05       0  4526.0    0.16       0  4705.9    0.05       0
  4744.2   0.033       0  4750.2    0.05       0  6035.9    0.16       0
  6419.4    0.08       0
Bank Sta=4734.7,6054
Exp/Cntr=0.3,0.1

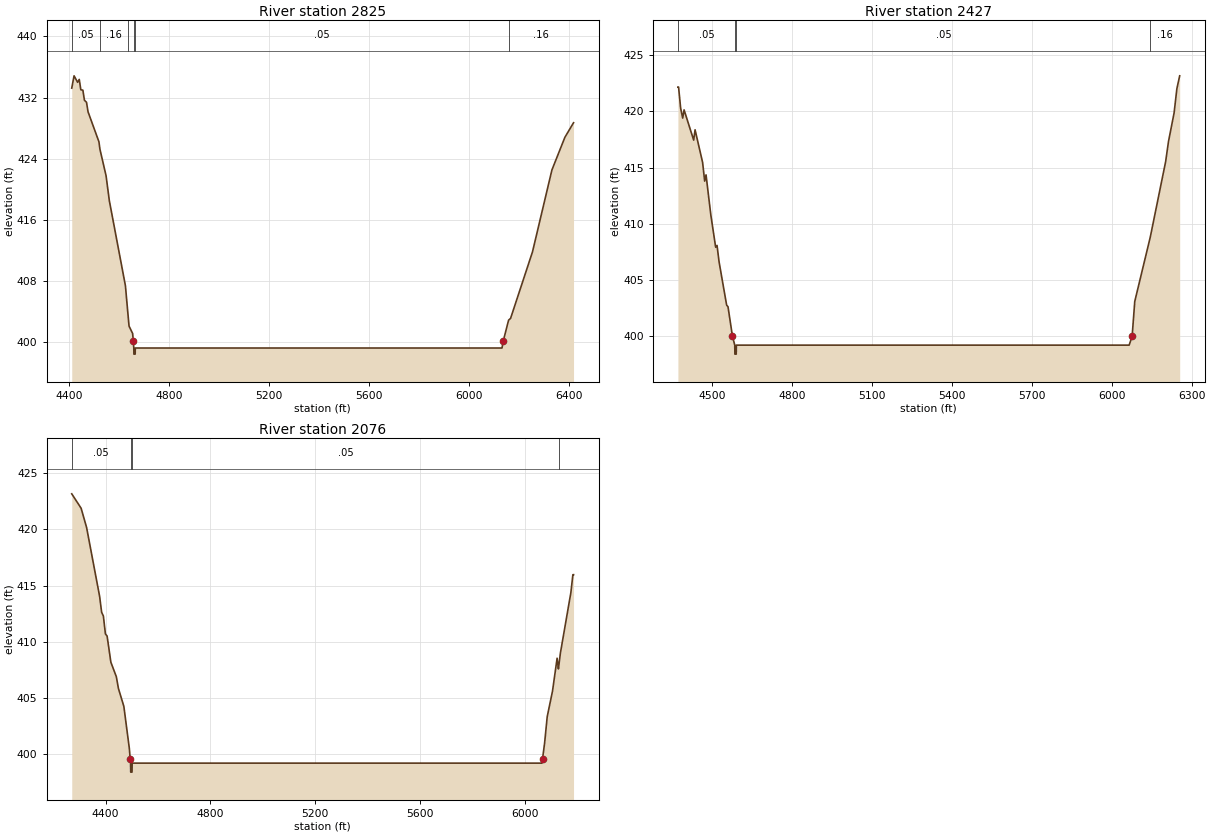
Type RM Length L Ch R = 1,2825,398,398,398
BEGIN DESCRIPTION:
UNT 053 in Running Cr Watershed 3.0
END DESCRIPTION:
XS GIS Cut Line= 3
      2887308.50      7027186.44      2887034.21      7027540.59
      2886850.18      7029089.24
#Sta/Elev= 30
  4411.0  433.23  4420.2  434.84  4434.5  433.99  4441.0  434.37  4447.3  433.02
  4455.5  432.96  4461.8  431.64  4470.0  431.38  4476.3  430.12  4519.8  426.20
  4523.7  425.24  4548.3  421.76  4561.4  418.49  4625.7  407.37  4634.8  404.04
  4640.2  402.08  4654.7  401.10  4657.0  400.14  4659.2  399.21  4659.7  398.41
  4664.7  398.41  4665.2  399.21  6132.3  399.21  6137.4  400.14  6158.7  402.86
  6166.6  403.09  6254.3  411.80  6332.0  422.52  6384.0  426.80  6418.5  428.70
#Mann=6,-1,0
  4411.0    0.05       0  4523.7    0.16       0  4634.8    0.05       0
  4659.2   0.033       0  4665.2    0.05       0  6158.7    0.16       0
Bank Sta=4657,6137.4
Exp/Cntr=0.3,0.1

Type RM Length L Ch R = 1,2427,351,351,351
BEGIN DESCRIPTION:
UNT 053 in Running Cr Watershed 2.0
END DESCRIPTION:
XS GIS Cut Line= 3
      2886774.99      7027025.03      2886625.00      7027625.00
      2886225.01      7028824.96
#Sta/Elev= 30
  4371.9  422.17  4374.4  422.17  4382.2  420.29  4389.9  419.41  4395.1  420.14
  4431.1  417.45  4436.3  418.37  4464.6  415.47  4472.4  413.80  4477.5  414.36
  4495.6  410.77  4513.6  407.92  4518.8  408.08  4526.5  406.61  4554.8  402.77
  4560.0  402.62  4576.7  399.99  4585.3  399.21  4585.8  398.41  4590.8  398.41
  4591.3  399.21  6065.5  399.21  6076.7  399.99  6086.6  403.10  6144.8  408.82
  6202.5  415.54  6213.1  417.32  6234.2  419.87  6244.7  422.04  6255.2  423.17
#Mann=4,-1,0
  4371.9    0.05       0  4585.3   0.033       0  4591.3    0.05       0
  6144.8    0.16       0
Bank Sta=4576.7,6076.7
Exp/Cntr=0.3,0.1

Type RM Length L Ch R = 1,2076,0,0,0
BEGIN DESCRIPTION:
UNT 053 in Running Cr Watershed 1.0
END DESCRIPTION:
XS GIS Cut Line= 3
      2886724.99      7027025.02      2886275.00      7027575.00
      2886175.00      7028775.03
#Sta/Elev= 30
  4271.1  423.16  4307.0  421.87  4327.8  420.16  4377.3  414.06  4385.2  412.62
  4391.7  412.30  4399.6  410.70  4406.0  410.51  4420.4  408.18  4441.2  406.90
  4449.1  405.86  4469.9  404.26  4490.7  400.54  4494.2  399.58  4495.6  399.21
  4496.1  398.41  4501.1  398.41  4501.6  399.21  6065.5  399.21  6067.6  399.58
  6075.5  401.00  6085.5  403.35  6105.6  405.61  6123.2  408.54  6128.2  407.59
  6129.0  407.74  6135.7  408.99  6175.8  414.39  6183.4  415.97  6185.9  415.97
#Mann=4,-1,0
  4271.1    0.05       0  4495.6   0.033       0  4501.6    0.05       0
  6129.0    0.12       0
Bank Sta=4494.2,6067.6
Exp/Cntr=0.3,0.1

Chan Stop Cuts=-1