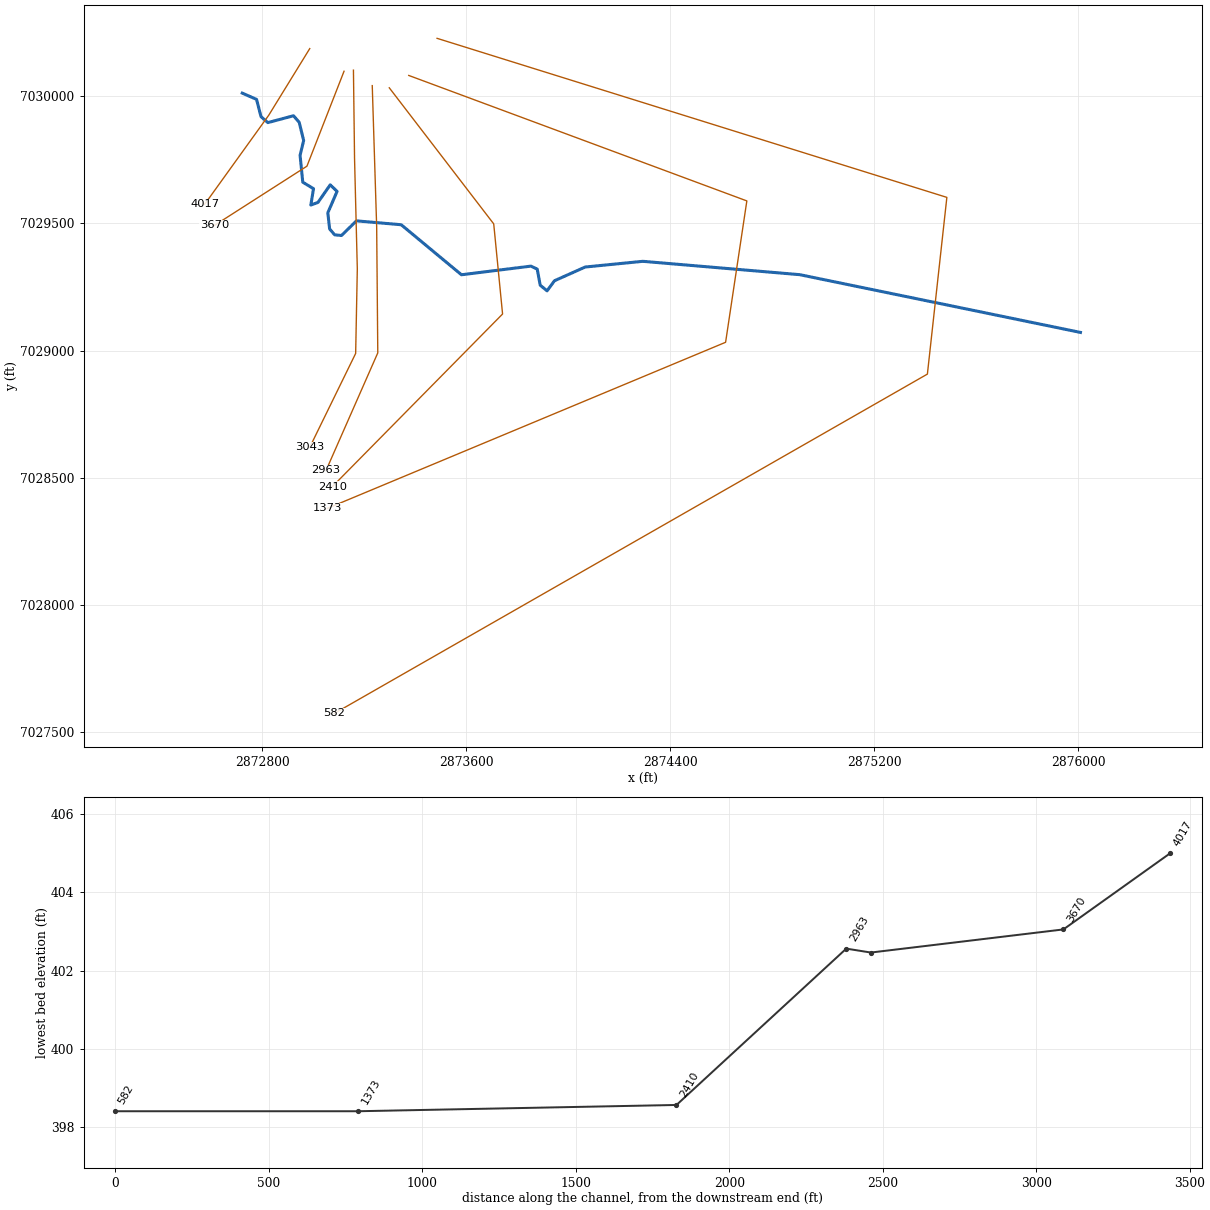
--- UNT 054 in Running Cr Watershed.prj (project) ---

Proj Title=UNT 054 in Running Cr Watershed Base Level Engineering
Current Plan=p01
Default Exp/Contr=0.3,0.1
English Units
Geom File=g01
Flow File=f01
Plan File=p01
BEGIN DESCRIPTION:
UNT 054 in Running Cr Watershed
END DESCRIPTION:

--- UNT 054 in Running Cr Watershed.p01 (plan) ---

Plan Title=Multiple Run
Short Identifier=Multiple
Geom File=g01
Flow File=f01
Subcritical Flow
K Sum by GR= 0
Std Step Tol= 0.01
Critical Tol= 0.01
Num of Std Step Trials= 20
Max Error Tol= 0.3
Flow Tol Ratio= 0.001
Split Flow NTrial= 30
Split Flow Tol= 0.02
Split Flow Ratio= 0.02
Log Output Level= 0
Friction Slope Method= 1
Unsteady Friction Slope Method= 2
Unsteady Bridges Friction Slope Method= 1
Parabolic Critical Depth
Global Vel Dist=  1 , 1 , 1
Global Log Level= 0
CheckData=True
Encroach Param= -1, 0, 0, 0
BEGIN DESCRIPTION:
Multiple Run
END DESCRIPTION:

--- UNT 054 in Running Cr Watershed.f01 (steady flow) ---

Flow Title=Multiple
Number of Profiles=7
Profile Names=10-year,25-year,50-year,1pct_min,100-year,1pct_plu,500-year
River Rch & RM= UNT 054 in Runni,Reach-1,4017
     620     838    1016     614    1224    2443    1778
River Rch & RM= UNT 054 in Runni,Reach-1,582
     832    1143    1402     854    1705    3402    2526
Boundary for River Rch & Prof#=UNT 054 in Runni,Reach-1,1
Up Type=0
Dn Type=3
Dn Slope=0.005
Boundary for River Rch & Prof#=UNT 054 in Runni,Reach-1,2
Up Type=0
Dn Type=3
Dn Slope=0.005
Boundary for River Rch & Prof#=UNT 054 in Runni,Reach-1,3
Up Type=0
Dn Type=3
Dn Slope=0.005
Boundary for River Rch & Prof#=UNT 054 in Runni,Reach-1,4
Up Type=0
Dn Type=3
Dn Slope=0.005
Boundary for River Rch & Prof#=UNT 054 in Runni,Reach-1,5
Up Type=0
Dn Type=3
Dn Slope=0.005
Boundary for River Rch & Prof#=UNT 054 in Runni,Reach-1,6
Up Type=0
Dn Type=3
Dn Slope=0.005
Boundary for River Rch & Prof#=UNT 054 in Runni,Reach-1,7
Up Type=0
Dn Type=3
Dn Slope=0.005

--- UNT 054 in Running Cr Watershed.g01 (geometry) ---

Geom Title=Existing Conditions

River Reach=UNT 054 in Runni,Reach-1
Reach XY= 30
      2872721.07      7030012.13      2872777.24      7029987.55
      2872794.79      7029919.68      2872821.71      7029896.28
      2872922.35      7029923.19      2872944.58      7029897.45
      2872962.13      7029826.06      2872948.09      7029767.55
      2872958.62      7029662.23      2873000.75      7029636.49
      2872990.22      7029572.13      2873018.30      7029582.66
      2873066.28      7029651.70      2873093.20      7029625.96
      2873056.92      7029541.70      2873063.94      7029478.51
      2873083.84      7029455.10      2873110.75      7029452.76
      2873169.26      7029510.11      2873344.80      7029494.89
      2873581.18      7029298.30      2873853.84      7029332.23
      2873878.42      7029320.53      2873890.12      7029257.34
      2873917.03      7029235.10      2873946.29      7029274.89
      2874066.82      7029328.72      2874292.74      7029351.13
      2874908.42      7029298.66      2876009.76      7029071.70

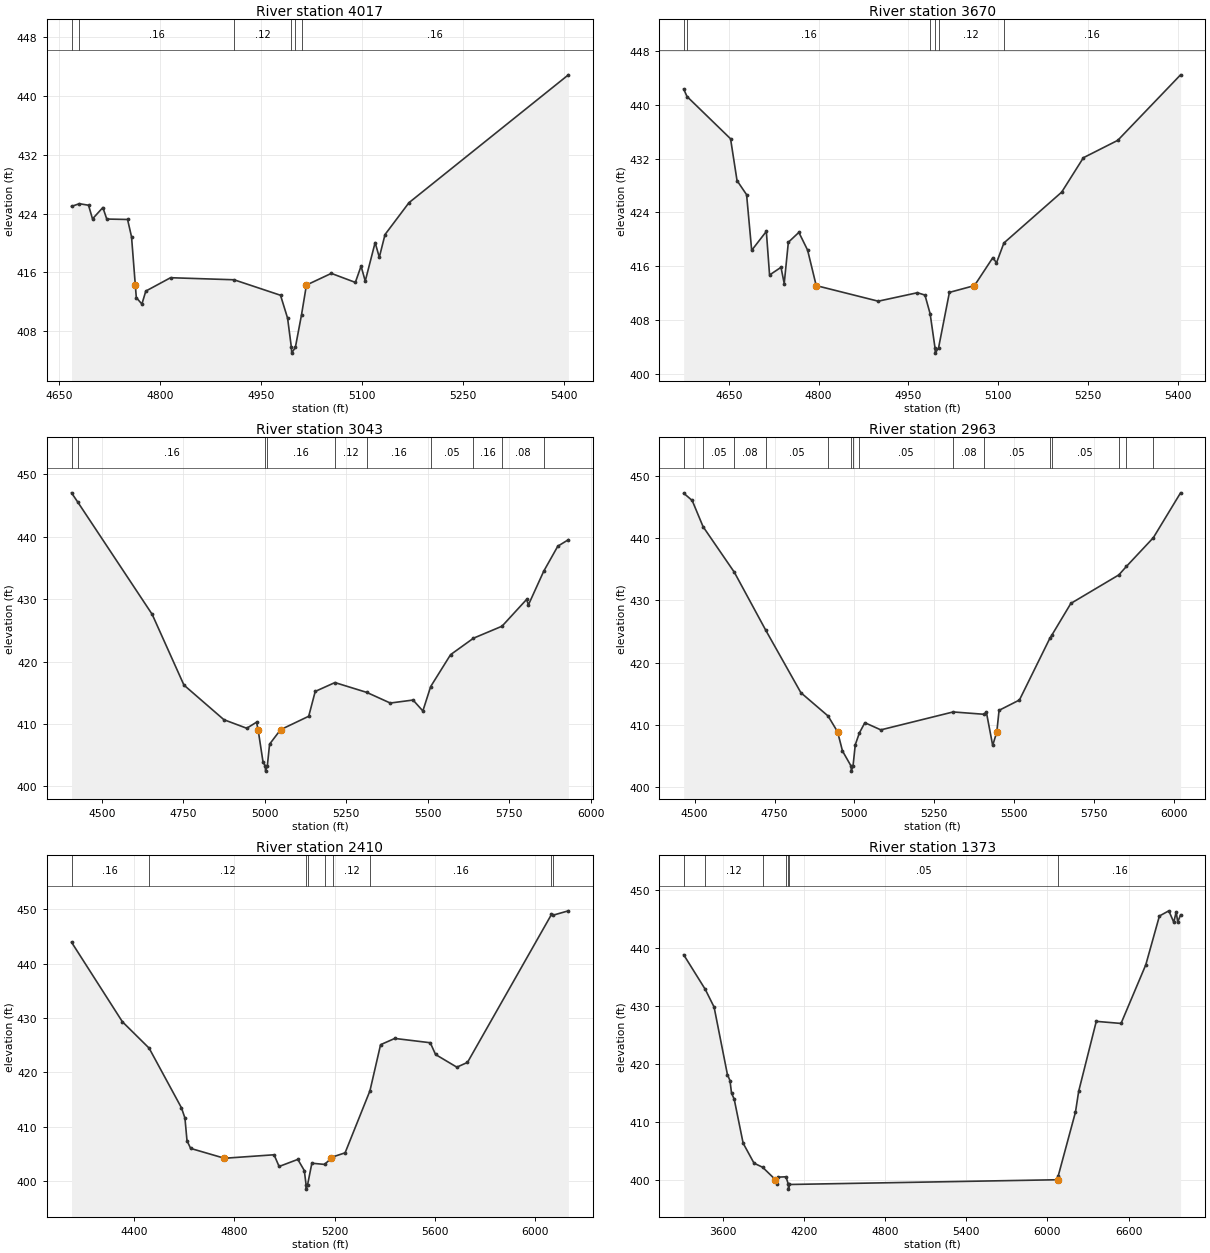
Type RM Length L Ch R = 1,4017,347,347,347
BEGIN DESCRIPTION:
UNT 054 in Running Cr Watershed 5.0
END DESCRIPTION:
XS GIS Cut Line= 3
      2872986.00      7030187.06      2872825.00      7029925.00
      2872573.67      7029575.07
#Sta/Elev= 30
  4668.5  424.97  4680.1  425.34  4693.8  425.13  4699.7  423.27  4715.1  424.82
  4720.9  423.25  4751.8  423.19  4757.7  420.83  4763.3  414.26  4764.8  412.55
  4773.1  411.67  4778.9  413.44  4815.7  415.26  4910.0  414.98  4979.1  412.87
  4989.6  409.75  4995.2  405.79  4995.7  404.99  5001.2  405.79  5010.3  410.21
  5017.6  414.26  5054.6  415.85  5090.3  414.62  5098.8  416.84  5105.0  414.80
  5119.7  420.05  5125.9  418.04  5134.4  421.14  5170.0  425.48  5406.9  442.89
#Mann=6,-1,0
  4668.5    0.05       0  4680.1    0.16       0  4910.0    0.12       0
  4995.2    0.07       0  5001.2    0.12       0  5010.3    0.16       0
Bank Sta=4763.3,5017.6
Exp/Cntr=0.3,0.1

Type RM Length L Ch R = 1,3670,627,627,627
BEGIN DESCRIPTION:
UNT 054 in Running Cr Watershed 4.0
END DESCRIPTION:
XS GIS Cut Line= 3
      2873120.52      7030098.03      2872975.00      7029725.00
      2872612.74      7029492.60
#Sta/Elev= 30
  4574.3  442.35  4579.9  441.24  4652.7  434.95  4663.5  428.73  4679.5  426.63
  4688.0  418.35  4712.5  421.17  4717.9  414.68  4737.0  415.82  4742.4  413.41
  4749.3  419.55  4766.9  421.02  4781.5  418.38  4795.9  413.10  4899.6  410.78
  4965.1  412.04  4977.7  411.69  4986.4  408.90  4994.5  403.85  4995.0  403.05
  5000.5  403.85  5018.6  412.09  5060.5  413.10  5091.3  417.27  5097.3  416.48
  5109.7  419.44  5206.3  427.01  5242.6  432.13  5300.1  434.72  5405.1  444.47
#Mann=6,-1,0
  4574.3    0.05       0  4579.9    0.16       0  4986.4    0.12       0
  4994.5    0.07       0  5000.5    0.12       0  5109.7    0.16       0
Bank Sta=4795.9,5060.5
Exp/Cntr=0.3,0.1

Type RM Length L Ch R = 1,3043,80,80,80
BEGIN DESCRIPTION:
Mapping XS 0ca9647d
END DESCRIPTION:
XS GIS Cut Line= 5
      2873157.43      7030102.36      2873161.77      7029755.18
      2873172.62      7029321.15      2873166.11      7028989.12
      2872986.00      7028620.21
#Sta/Elev= 30
  4407.0  447.05  4425.5  445.62  4654.4  427.58  4751.8  416.25  4874.4  410.70
  4944.4  409.33  4974.5  410.30  4979.3  409.10  4994.5  403.89  5001.5  403.26
  5002.0  402.46  5007.5  403.26  5014.5  406.78  5048.2  409.10  5134.5  411.25
  5154.5  415.23  5214.9  416.65  5312.8  415.07  5384.6  413.37  5454.6  413.85
  5484.6  412.10  5508.6  416.01  5569.6  421.12  5639.9  423.76  5727.4  425.68
  5802.8  429.97  5808.4  429.10  5855.4  434.50  5898.5  438.50  5931.0  439.54
#Mann=10,-1,0
  4407.0    0.05       0  4425.5    0.16       0  5001.5    0.07       0
  5007.5    0.16       0  5214.9    0.12       0  5312.8    0.16       0
  5508.6    0.05       0  5639.9    0.16       0  5727.4    0.08       0
  5855.4    0.16       0
Bank Sta=4979.3,5048.2
Exp/Cntr=0.3,0.1

Type RM Length L Ch R = 1,2963,553,553,553
BEGIN DESCRIPTION:
Mapping XS e68200d8
END DESCRIPTION:
XS GIS Cut Line= 4
      2873231.22      7030041.61      2873248.58      7029486.08
      2873252.92      7028991.29      2873050.15      7028529.67
#Sta/Elev= 30
  4465.7  447.22  4492.3  446.05  4526.4  441.84  4624.3  434.51  4722.1  425.24
  4832.5  415.16  4917.7  411.41  4947.3  408.87  4962.6  405.80  4989.6  403.36
  4990.1  402.56  4995.6  403.36  5002.6  406.79  5015.5  408.70  5032.6  410.34
  5082.6  409.19  5309.0  412.07  5406.8  411.69  5412.6  412.10  5432.6  406.69
  5445.5  408.87  5452.6  412.33  5516.3  413.99  5611.4  423.90  5617.2  424.37
  5677.2  429.51  5827.3  434.09  5851.0  435.45  5935.3  440.07  6020.5  447.28
#Mann=15,-1,0
  4465.7    0.08       0  4526.4    0.05       0  4624.3    0.08       0
  4722.1    0.05       0  4917.7    0.08       0  4989.6    0.07       0
  4995.6    0.08       0  5015.5    0.05       0  5309.0    0.08       0
  5406.8    0.05       0  5611.4    0.16       0  5617.2    0.05       0
  5827.3    0.16       0  5851.0    0.08       0  5935.3    0.05       0
Bank Sta=4947.3,5445.5
Exp/Cntr=0.3,0.1

Type RM Length L Ch R = 1,2410,1037,1037,1037
BEGIN DESCRIPTION:
UNT 054 in Running Cr Watershed 3.0
END DESCRIPTION:
XS GIS Cut Line= 4
      2873298.06      7030032.95      2873707.78      7029498.23
      2873742.50      7029144.07      2873074.99      7028466.14
#Sta/Elev= 30
  4150.3  443.93  4353.2  429.31  4459.6  424.47  4588.6  413.51  4602.5  411.62
  4610.7  407.47  4625.2  406.05  4759.9  404.24  4957.8  404.88  4977.9  402.73
  5052.5  404.03  5078.4  401.98  5085.4  399.37  5085.9  398.57  5091.4  399.37
  5108.5  403.33  5159.0  403.11  5186.0  404.24  5192.7  404.50  5241.0  405.24
  5340.0  416.63  5382.4  425.10  5439.0  426.25  5580.5  425.46  5601.6  423.30
  5686.5  420.97  5728.9  421.85  6063.8  449.03  6068.7  448.87  6131.2  449.69
#Mann=9,-1,0
  4150.3    0.16       0  4459.6    0.12       0  5085.4    0.07       0
  5091.4    0.12       0  5159.0    0.16       0  5192.7    0.12       0
  5340.0    0.16       0  6063.8    0.05       0  6068.7    0.16       0
Bank Sta=4759.9,5186
Exp/Cntr=0.3,0.1

Type RM Length L Ch R = 1,1373,791,791,791
BEGIN DESCRIPTION:
UNT 054 in Running Cr Watershed 2.0
END DESCRIPTION:
XS GIS Cut Line= 4
      2873374.44      7030081.57      2874700.83      7029588.51
      2874617.50      7029032.96      2873055.01      7028380.18
#Sta/Elev= 30
  3313.2  438.87  3472.9  432.88  3537.8  429.84  3636.3  418.19  3655.2  417.15
  3666.6  414.98  3686.3  413.95  3752.4  406.34  3832.8  402.89  3896.5  402.18
  3991.4  400.03  4004.2  399.23  4009.5  400.48  4068.5  400.54  4086.9  399.21
  4087.4  398.41  4092.9  399.21  6075.2  400.03  6080.0  400.71  6207.1  411.71
  6230.9  415.31  6360.8  427.37  6543.7  427.01  6726.6  437.14  6827.2  445.56
  6896.7  446.45  6933.3  444.47  6950.9  446.28  6962.5  444.51  6983.4  445.76
#Mann=7,-1,0
  3313.2    0.16       0  3472.9    0.12       0  3896.5    0.07       0
  4068.5    0.05       0  4086.9   0.033       0  4092.9    0.05       0
  6080.0    0.16       0
Bank Sta=3991.4,6075.2
Exp/Cntr=0.3,0.1

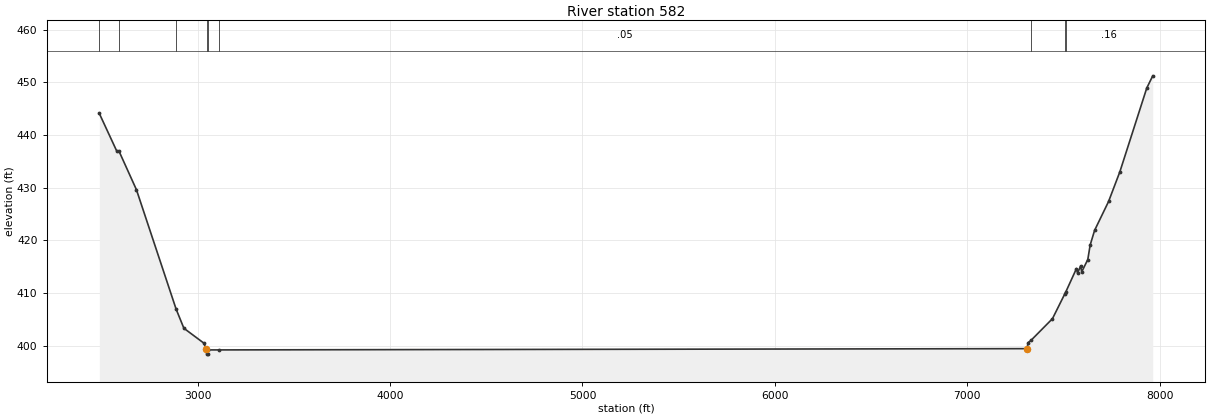
Type RM Length L Ch R = 1,582,0,0,0
BEGIN DESCRIPTION:
UNT 054 in Running Cr Watershed 1.0
END DESCRIPTION:
XS GIS Cut Line= 4
      2873485.54      7030227.41      2875485.56      7029602.40
      2875409.17      7028907.96      2873082.80      7027574.64
#Sta/Elev= 30
  2488.8  444.08  2579.0  436.97  2591.4  436.90  2681.7  429.61  2888.1  406.93
  2928.3  403.32  3033.0  400.47  3041.7  399.45  3046.2  399.21  3046.7  398.41
  3052.1  398.41  3052.6  399.21  3108.6  399.21  7311.2  399.45  7316.2  400.58
  7331.1  401.01  7443.0  405.14  7507.2  409.85  7511.2  410.13  7567.7  414.65
  7573.4  413.80  7589.2  415.14  7595.0  414.03  7626.6  416.36  7638.9  419.11
  7662.0  421.90  7734.6  427.38  7793.5  433.04  7933.1  448.91  7964.2  451.23
#Mann=9,-1,0
  2488.8    0.16       0  2591.4    0.12       0  2888.1    0.07       0
  3046.2   0.033       0  3052.6    0.07       0  3108.6    0.05       0
  7331.1    0.16       0  7507.2    0.05       0  7511.2    0.16       0
Bank Sta=3041.7,7311.2
Exp/Cntr=0.3,0.1

Chan Stop Cuts=-1