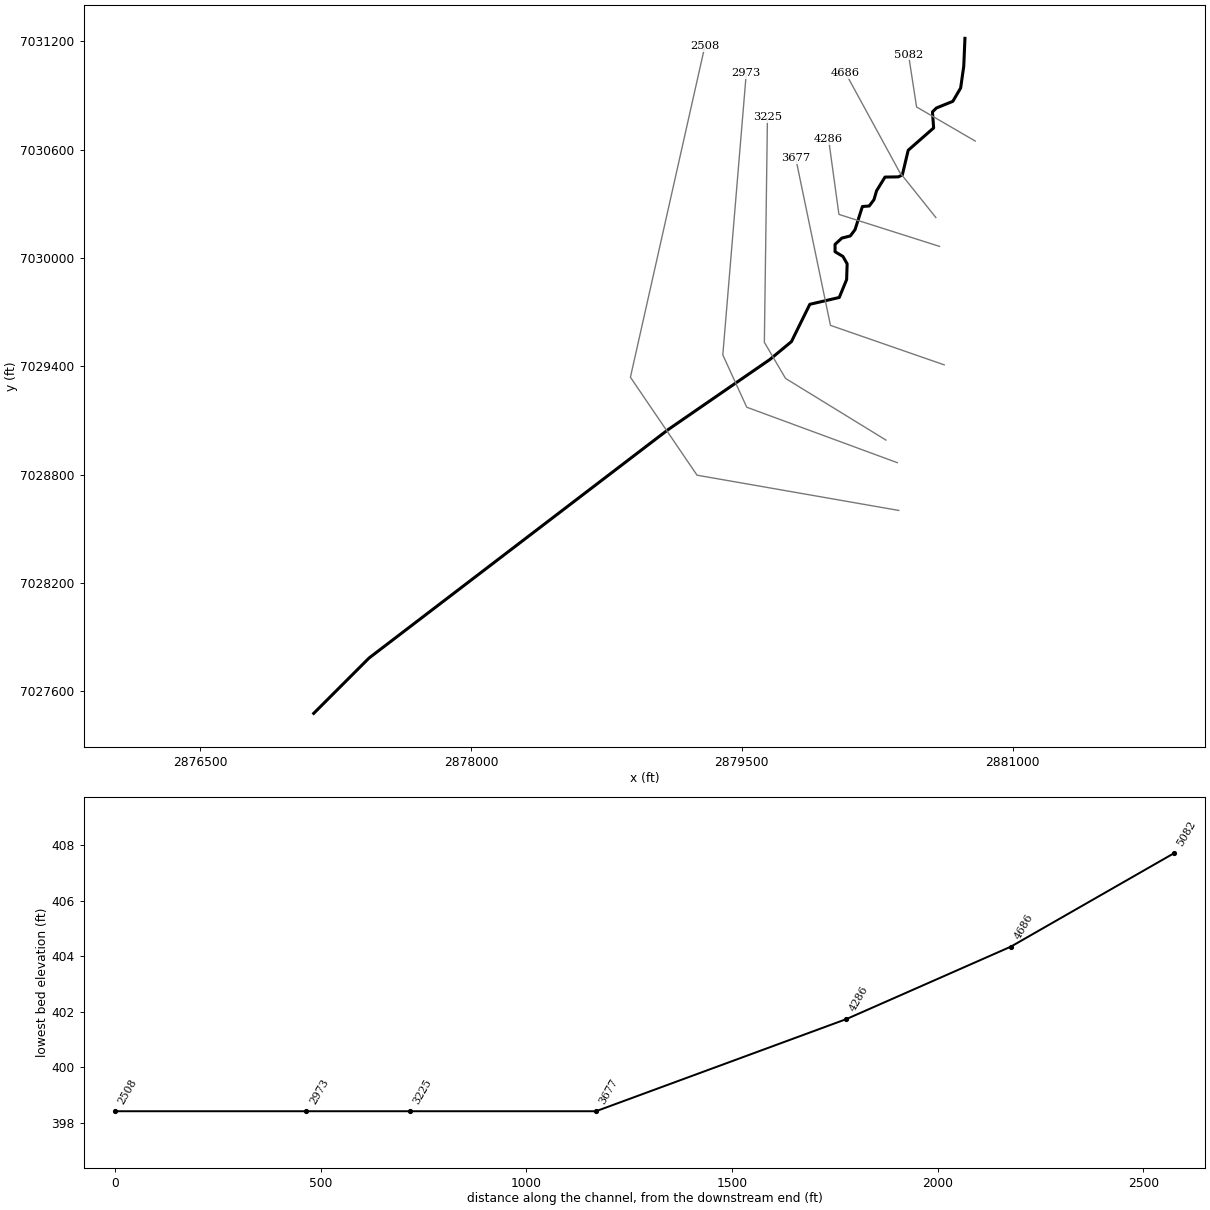
--- UNT 055 in Running Cr Watershed.prj (project) ---

Proj Title=UNT 055 in Running Cr Watershed Base Level Engineering
Current Plan=p01
Default Exp/Contr=0.3,0.1
English Units
Geom File=g01
Flow File=f01
Plan File=p01
BEGIN DESCRIPTION:
UNT 055 in Running Cr Watershed
END DESCRIPTION:

--- UNT 055 in Running Cr Watershed.p01 (plan) ---

Plan Title=Multiple Run
Short Identifier=Multiple
Geom File=g01
Flow File=f01
Subcritical Flow
K Sum by GR= 0
Std Step Tol= 0.01
Critical Tol= 0.01
Num of Std Step Trials= 20
Max Error Tol= 0.3
Flow Tol Ratio= 0.001
Split Flow NTrial= 30
Split Flow Tol= 0.02
Split Flow Ratio= 0.02
Log Output Level= 0
Friction Slope Method= 1
Unsteady Friction Slope Method= 2
Unsteady Bridges Friction Slope Method= 1
Parabolic Critical Depth
Global Vel Dist=  1 , 1 , 1
Global Log Level= 0
CheckData=True
Encroach Param= -1, 0, 0, 0
BEGIN DESCRIPTION:
Multiple Run
END DESCRIPTION:

--- UNT 055 in Running Cr Watershed.f01 (steady flow) ---

Flow Title=Multiple
Number of Profiles=7
Profile Names=10-year,25-year,50-year,1pct_min,100-year,1pct_plu,500-year
River Rch & RM= UNT 055 in Runni,Reach-1,5082
     272     342     394     227     452     902     594
River Rch & RM= UNT 055 in Runni,Reach-1,2508
     373     476     555     322     642    1281     858
Boundary for River Rch & Prof#=UNT 055 in Runni,Reach-1,1
Up Type=0
Dn Type=3
Dn Slope=0.005
Boundary for River Rch & Prof#=UNT 055 in Runni,Reach-1,2
Up Type=0
Dn Type=3
Dn Slope=0.005
Boundary for River Rch & Prof#=UNT 055 in Runni,Reach-1,3
Up Type=0
Dn Type=3
Dn Slope=0.005
Boundary for River Rch & Prof#=UNT 055 in Runni,Reach-1,4
Up Type=0
Dn Type=3
Dn Slope=0.005
Boundary for River Rch & Prof#=UNT 055 in Runni,Reach-1,5
Up Type=0
Dn Type=3
Dn Slope=0.005
Boundary for River Rch & Prof#=UNT 055 in Runni,Reach-1,6
Up Type=0
Dn Type=3
Dn Slope=0.005
Boundary for River Rch & Prof#=UNT 055 in Runni,Reach-1,7
Up Type=0
Dn Type=3
Dn Slope=0.005

--- UNT 055 in Running Cr Watershed.g01 (geometry) ---

Geom Title=Existing Conditions

River Reach=UNT 055 in Runni,Reach-1
Reach XY= 30
      2880736.11      7031217.47      2880729.60      7031063.56
      2880712.26      7030942.17      2880668.91      7030868.47
      2880577.87      7030831.62      2880556.19      7030809.95
      2880562.69      7030721.07      2880421.79      7030597.52
      2880389.28      7030460.95      2880367.60      7030450.11
      2880293.30      7030448.94      2880246.71      7030373.23
      2880232.15      7030323.72      2880205.94      7030288.78
      2880168.08      7030285.86      2880127.31      7030157.73
      2880101.10      7030122.79      2880054.51      7030111.14
      2880016.65      7030076.19      2880016.65      7030035.42
      2880060.34      7030009.21      2880083.63      7029968.44
      2880080.72      7029881.08      2880039.95      7029782.07
      2879876.87      7029744.21      2879774.95      7029537.45
      2879655.55      7029438.44      2879093.51      7029051.13
      2877435.21      7027784.77      2877128.77      7027478.33

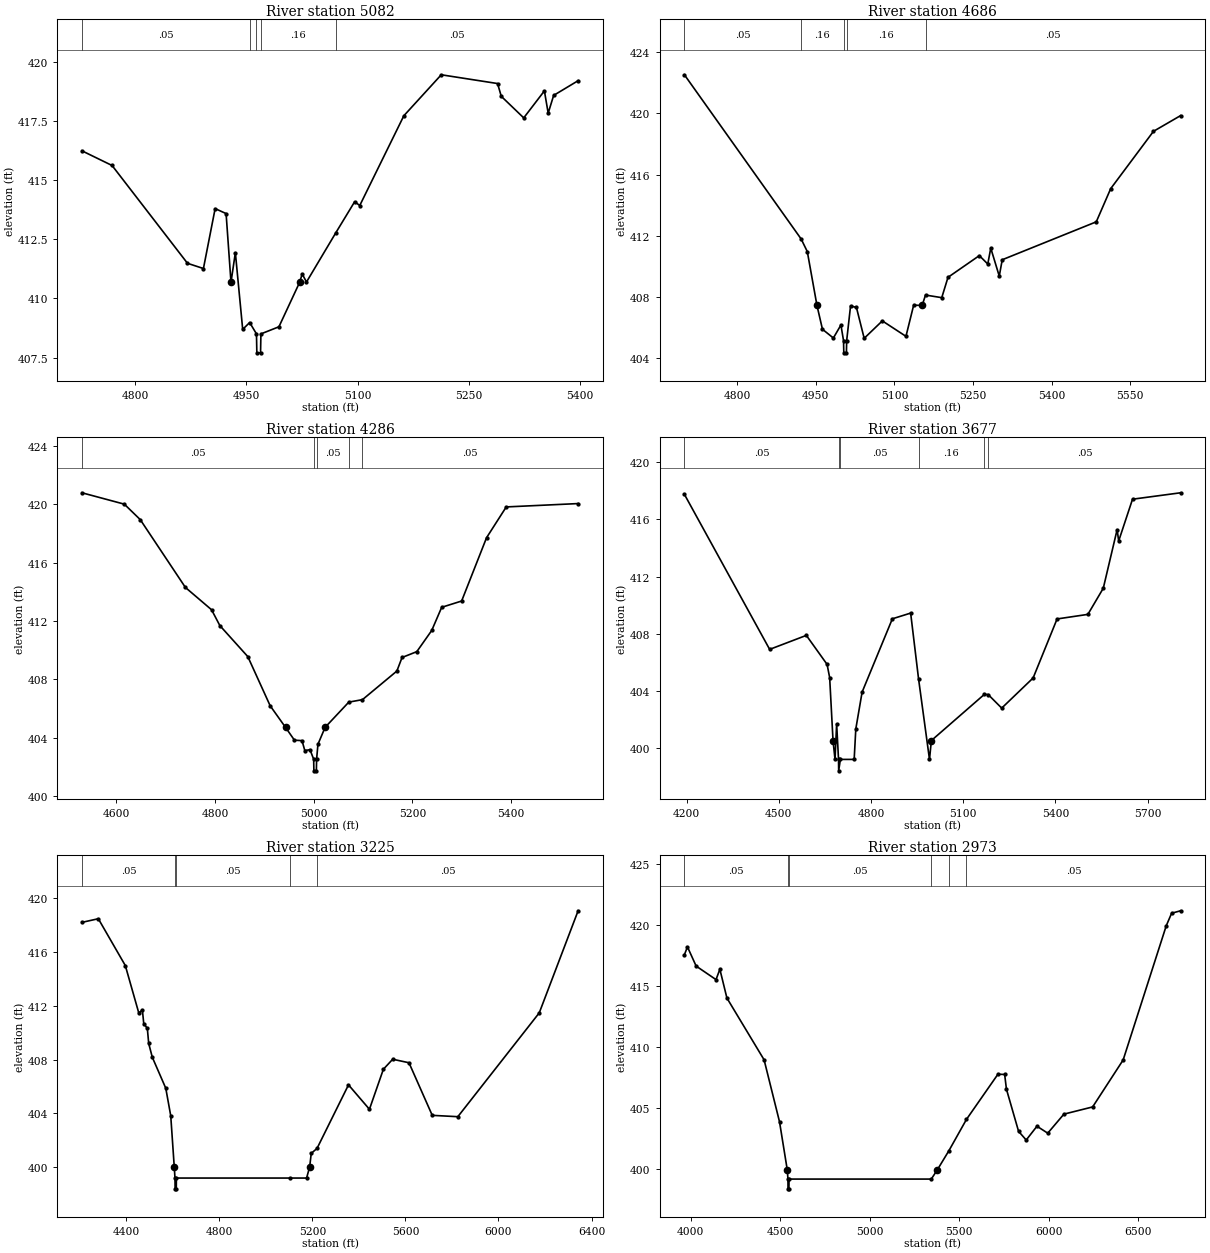
Type RM Length L Ch R = 1,5082,396,396,396
BEGIN DESCRIPTION:
UNT 055 in Running Cr Watershed 9.0
END DESCRIPTION:
XS GIS Cut Line= 3
      2880793.27      7030648.41      2880468.15      7030837.33
      2880423.49      7031127.59
#Sta/Elev= 30
  4727.9  416.23  4768.6  415.61  4870.4  411.48  4891.9  411.26  4907.7  413.79
  4922.5  413.58  4929.1  410.68  4935.0  411.93  4944.9  408.69  4954.3  408.98
  4963.5  408.50  4964.0  407.70  4969.0  407.70  4969.5  408.50  4993.8  408.80
  5021.8  410.68  5025.2  411.03  5031.0  410.69  5070.4  412.76  5096.0  414.08
  5102.9  413.92  5162.4  417.71  5212.9  419.44  5288.9  419.07  5293.9  418.53
  5324.2  417.62  5352.1  418.76  5357.2  417.82  5364.6  418.57  5397.6  419.19
#Mann=5,-1,0
  4727.9    0.05       0  4954.3    0.16       0  4963.5    0.07       0
  4969.5    0.16       0  5070.4    0.05       0
Bank Sta=4929.1,5021.8
Exp/Cntr=0.3,0.1

Type RM Length L Ch R = 1,4686,400,400,400
BEGIN DESCRIPTION:
UNT 055 in Running Cr Watershed 8.0
END DESCRIPTION:
XS GIS Cut Line= 3
      2880575.01      7030224.98      2880375.00      7030475.00
      2880074.99      7031025.02
#Sta/Elev= 30
  4699.2  422.53  4921.9  411.79  4933.7  410.96  4952.1  407.44  4962.6  405.88
  4983.4  405.31  4997.8  406.16  5002.8  405.14  5003.3  404.34  5008.3  404.34
  5008.8  405.14  5016.2  407.41  5027.4  407.31  5042.2  405.29  5076.8  406.43
  5121.9  405.42  5136.6  407.46  5152.8  407.44  5159.2  408.12  5190.2  407.95
  5202.1  409.28  5261.9  410.70  5278.0  410.15  5283.7  411.19  5299.9  409.36
  5305.6  410.43  5485.0  412.91  5512.5  415.08  5594.1  418.83  5645.9  419.86
#Mann=5,-1,0
  4699.2    0.05       0  4921.9    0.16       0  5002.8    0.07       0
  5008.8    0.16       0  5159.2    0.05       0
Bank Sta=4952.1,5152.8
Exp/Cntr=0.3,0.1

Type RM Length L Ch R = 1,4286,609,609,609
BEGIN DESCRIPTION:
UNT 055 in Running Cr Watershed 7.0
END DESCRIPTION:
XS GIS Cut Line= 3
      2880595.36      7030065.08      2880038.07      7030242.16
      2879980.79      7030658.80
#Sta/Elev= 30
  4530.3  420.79  4616.2  420.01  4648.5  418.95  4740.0  414.30  4793.0  412.77
  4809.7  411.69  4866.4  409.56  4911.7  406.19  4942.8  404.71  4960.9  403.83
  4976.2  403.80  4981.9  403.12  4992.4  403.18  4999.8  402.53  5000.3  401.73
  5005.3  401.73  5005.8  402.53  5008.5  403.55  5023.0  404.71  5071.0  406.44
  5098.7  406.61  5168.4  408.57  5178.9  409.50  5208.8  409.90  5239.0  411.35
  5259.2  412.94  5299.6  413.37  5350.1  417.71  5390.0  419.82  5535.6  420.05
#Mann=5,-1,0
  4530.3    0.05       0  4999.8    0.03       0  5005.8    0.05       0
  5071.0    0.16       0  5098.7    0.05       0
Bank Sta=4942.8,5023
Exp/Cntr=0.3,0.1

Type RM Length L Ch R = 1,3677,452,452,452
BEGIN DESCRIPTION:
UNT 055 in Running Cr Watershed 6.0
END DESCRIPTION:
XS GIS Cut Line= 3
      2880621.38      7029408.83      2879991.20      7029627.57
      2879798.48      7030554.69
#Sta/Elev= 30
  4193.0  417.76  4470.3  406.91  4589.6  407.89  4657.1  405.86  4665.5  404.93
  4676.4  400.53  4682.9  399.21  4688.2  401.70  4694.3  399.21  4694.8  398.41
  4700.3  399.21  4745.2  399.21  4750.5  401.34  4771.0  403.92  4869.4  409.05
  4928.9  409.45  4954.5  404.87  4990.2  399.21  4996.3  400.53  5168.6  403.76
  5181.0  403.75  5225.1  402.80  5327.3  404.91  5405.2  409.04  5505.4  409.36
  5555.5  411.19  5600.5  415.29  5605.6  414.50  5650.6  417.42  5807.0  417.87
#Mann=6,-1,0
  4193.0    0.05       0  4694.3    0.07       0  4700.3    0.05       0
  4954.5    0.16       0  5168.6    0.12       0  5181.0    0.05       0
Bank Sta=4676.4,4996.3
Exp/Cntr=0.3,0.1

Type RM Length L Ch R = 1,3225,252,252,252
BEGIN DESCRIPTION:
UNT 055 in Running Cr Watershed 5.0
END DESCRIPTION:
XS GIS Cut Line= 4
      2880298.52      7028992.14      2879742.38      7029333.71
      2879625.00      7029533.82      2879642.21      7030781.95
#Sta/Elev= 30
  4209.5  418.17  4280.0  418.44  4396.0  414.97  4454.0  411.45  4469.4  411.67
  4475.3  410.67  4490.7  410.31  4496.6  409.19  4512.0  408.17  4570.0  405.87
  4591.3  403.83  4606.4  400.04  4609.6  399.21  4610.1  398.41  4615.1  398.41
  4615.6  399.21  5103.8  399.21  5175.3  399.21  5188.5  400.04  5195.3  401.04
  5220.2  401.41  5355.4  406.12  5445.4  404.31  5505.4  407.28  5545.4  408.02
  5615.4  407.76  5715.4  403.86  5825.4  403.76  6175.4  411.46  6342.4  419.03
#Mann=5,-1,0
  4209.5    0.05       0  4609.6   0.033       0  4615.6    0.05       0
  5103.8    0.07       0  5220.2    0.05       0
Bank Sta=4606.4,5188.5
Exp/Cntr=0.3,0.1

Type RM Length L Ch R = 1,2973,465,465,465
BEGIN DESCRIPTION:
UNT 055 in Running Cr Watershed 4.0
END DESCRIPTION:
XS GIS Cut Line= 4
      2880361.00      7028867.15      2879527.56      7029174.15
      2879394.89      7029463.73      2879525.00      7031025.01
#Sta/Elev= 30
  3964.6  417.59  3981.7  418.23  4030.2  416.66  4141.3  415.55  4162.8  416.40
  4202.2  414.04  4410.0  408.98  4496.1  403.91  4539.8  399.94  4543.3  399.21
  4543.8  398.41  4548.8  398.41  4549.3  399.21  5344.4  399.21  5377.1  399.94
  5442.8  401.53  5541.1  404.10  5717.0  407.80  5754.6  407.78  5764.6  406.57
  5832.4  403.12  5875.0  402.41  5935.2  403.54  5995.4  402.97  6085.7  404.53
  6246.3  405.12  6416.9  408.97  6657.7  419.96  6687.8  420.99  6738.0  421.19
#Mann=6,-1,0
  3964.6    0.05       0  4543.3   0.033       0  4549.3    0.05       0
  5344.4    0.07       0  5442.8    0.12       0  5541.1    0.05       0
Bank Sta=4539.8,5377.1
Exp/Cntr=0.3,0.1

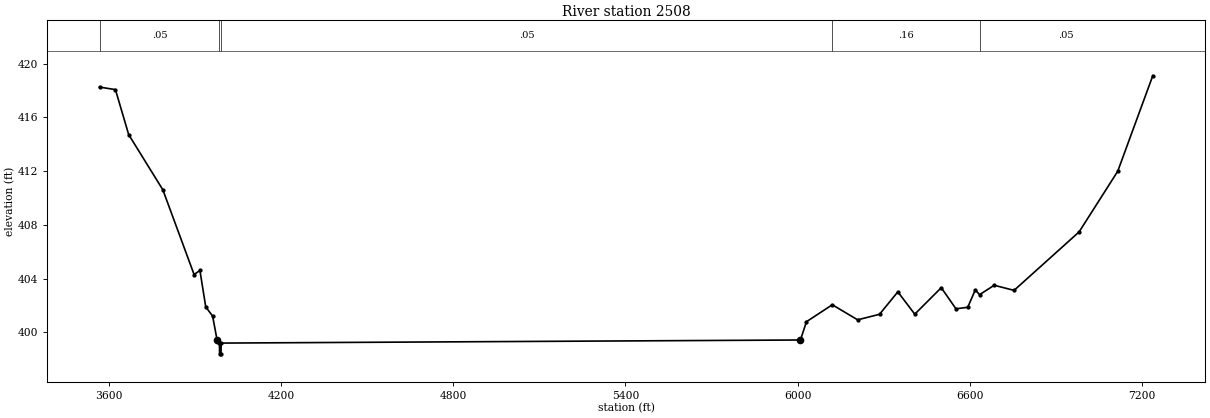
Type RM Length L Ch R = 1,2508,0,0,0
BEGIN DESCRIPTION:
UNT 055 in Running Cr Watershed 3.0
END DESCRIPTION:
XS GIS Cut Line= 4
      2880369.64      7028602.41      2879252.05      7028797.71
      2878883.13      7029340.25      2879295.46      7031174.05
#Sta/Elev= 30
  3567.4  418.25  3622.9  418.06  3669.1  414.71  3788.1  410.61  3896.9  404.31
  3917.3  404.61  3937.6  401.90  3961.5  401.22  3977.1  399.44  3985.3  399.21
  3985.8  398.41  3990.8  398.41  3991.3  399.21  6009.9  399.44  6030.9  400.80
  6120.9  402.06  6209.2  400.94  6285.4  401.35  6349.3  403.02  6408.3  401.36
  6500.6  403.33  6551.8  401.76  6592.8  401.87  6619.3  403.17  6634.1  402.81
  6685.1  403.51  6754.3  403.13  6981.0  407.48  7115.6  411.99  7237.6  419.09
#Mann=5,-1,0
  3567.4    0.05       0  3985.3   0.033       0  3991.3    0.05       0
  6120.9    0.16       0  6634.1    0.05       0
Bank Sta=3977.1,6009.9
Exp/Cntr=0.3,0.1

Chan Stop Cuts=-1