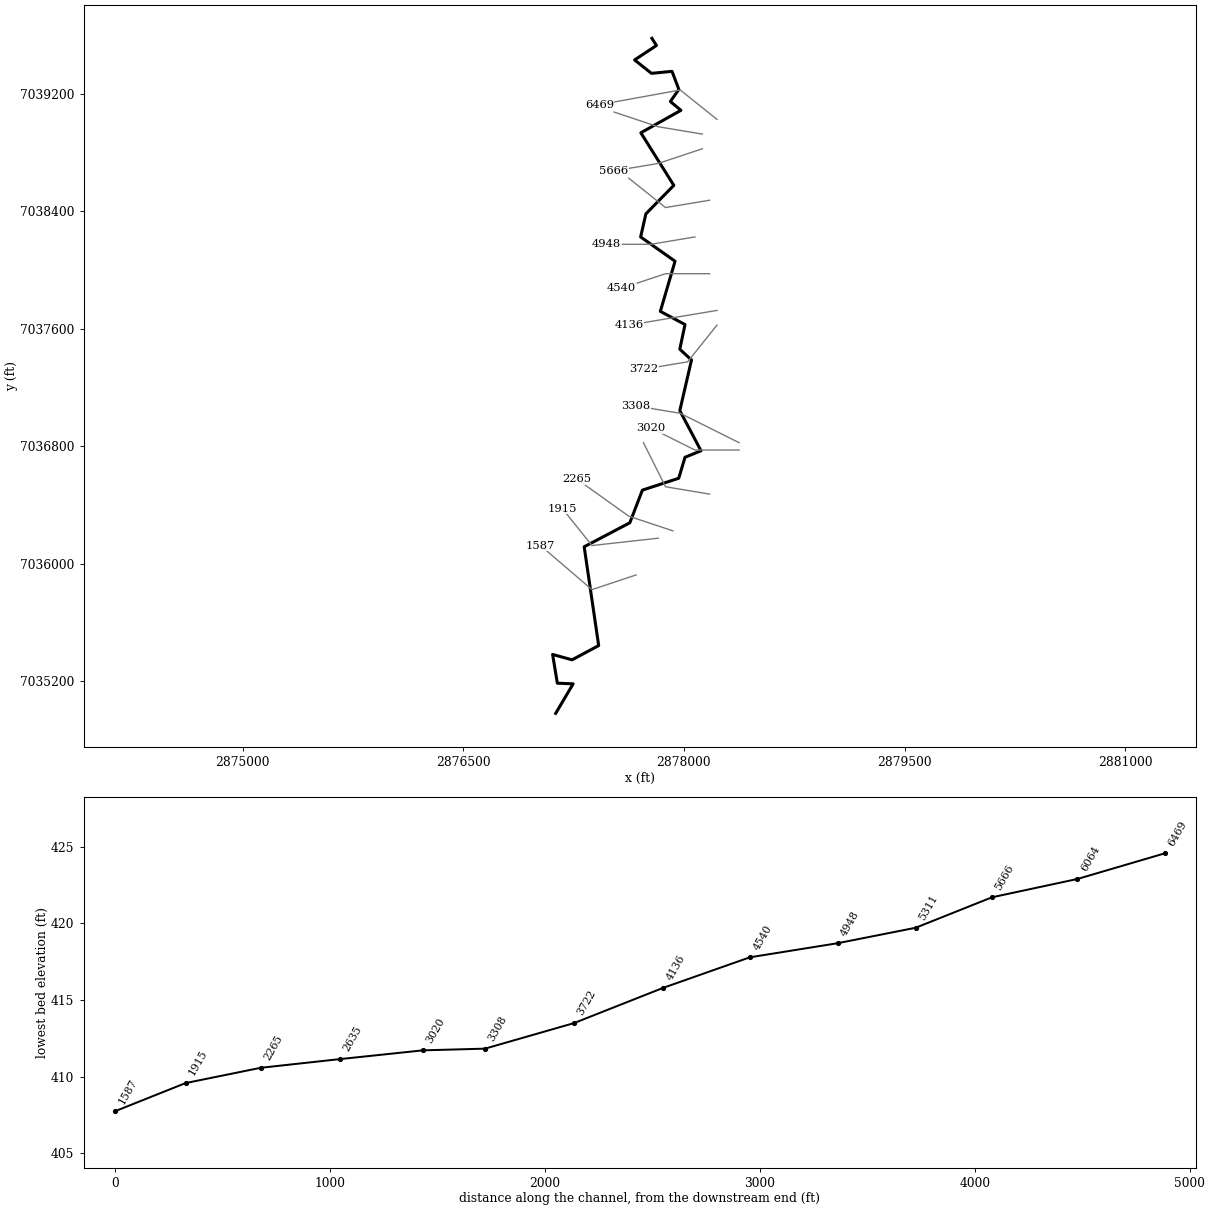
--- UNT 056 in Running Cr Watershed.prj (project) ---

Proj Title=UNT 056 in Running Cr Watershed Base Level Engineering
Current Plan=p01
Default Exp/Contr=0.3,0.1
English Units
Geom File=g01
Flow File=f01
Plan File=p01
BEGIN DESCRIPTION:
UNT 056 in Running Cr Watershed
END DESCRIPTION:

--- UNT 056 in Running Cr Watershed.p01 (plan) ---

Plan Title=Multiple Run
Short Identifier=Multiple
Geom File=g01
Flow File=f01
Subcritical Flow
K Sum by GR= 0
Std Step Tol= 0.01
Critical Tol= 0.01
Num of Std Step Trials= 20
Max Error Tol= 0.3
Flow Tol Ratio= 0.001
Split Flow NTrial= 30
Split Flow Tol= 0.02
Split Flow Ratio= 0.02
Log Output Level= 0
Friction Slope Method= 1
Unsteady Friction Slope Method= 2
Unsteady Bridges Friction Slope Method= 1
Parabolic Critical Depth
Global Vel Dist=  1 , 1 , 1
Global Log Level= 0
CheckData=True
Encroach Param= -1, 0, 0, 0
BEGIN DESCRIPTION:
Multiple Run
END DESCRIPTION:

--- UNT 056 in Running Cr Watershed.f01 (steady flow) ---

Flow Title=Multiple
Number of Profiles=7
Profile Names=10-year,25-year,50-year,1pct_min,100-year,1pct_plu,500-year
River Rch & RM= UNT 056 in Runni,Reach-1,6469
     451     589     698     411     820    1637    1134
River Rch & RM= UNT 056 in Runni,Reach-1,3020
     464     606     718     423     844    1684    1167
Boundary for River Rch & Prof#=UNT 056 in Runni,Reach-1,1
Up Type=0
Dn Type=3
Dn Slope=0.005
Boundary for River Rch & Prof#=UNT 056 in Runni,Reach-1,2
Up Type=0
Dn Type=3
Dn Slope=0.005
Boundary for River Rch & Prof#=UNT 056 in Runni,Reach-1,3
Up Type=0
Dn Type=3
Dn Slope=0.005
Boundary for River Rch & Prof#=UNT 056 in Runni,Reach-1,4
Up Type=0
Dn Type=3
Dn Slope=0.005
Boundary for River Rch & Prof#=UNT 056 in Runni,Reach-1,5
Up Type=0
Dn Type=3
Dn Slope=0.005
Boundary for River Rch & Prof#=UNT 056 in Runni,Reach-1,6
Up Type=0
Dn Type=3
Dn Slope=0.005
Boundary for River Rch & Prof#=UNT 056 in Runni,Reach-1,7
Up Type=0
Dn Type=3
Dn Slope=0.005

--- UNT 056 in Running Cr Watershed.g01 (geometry) ---

Geom Title=Existing Conditions

River Reach=UNT 056 in Runni,Reach-1
Reach XY= 30
      2877782.41      7039576.54      2877813.30      7039528.00
      2877664.73      7039429.44      2877779.47      7039338.23
      2877919.17      7039351.80      2877965.69      7039228.88
      2877907.85      7039146.89      2877979.53      7039086.69
      2877707.39      7038933.70      2877931.35      7038575.94
      2877741.56      7038382.33      2877705.80      7038225.03
      2877939.81      7038059.90      2877839.78      7037718.61
      2878007.48      7037628.88      2877972.17      7037461.18
      2878051.61      7037387.63      2877972.17      7037043.40
      2878116.34      7036769.79      2878007.48      7036725.66
      2877964.82      7036582.97      2877717.68      7036502.06
      2877632.36      7036279.93      2877321.97      7036116.64
      2877420.53      7035444.38      2877239.59      7035347.29
      2877107.20      7035384.06      2877139.56      7035188.41
      2877246.95      7035184.00      2877128.20      7034982.93

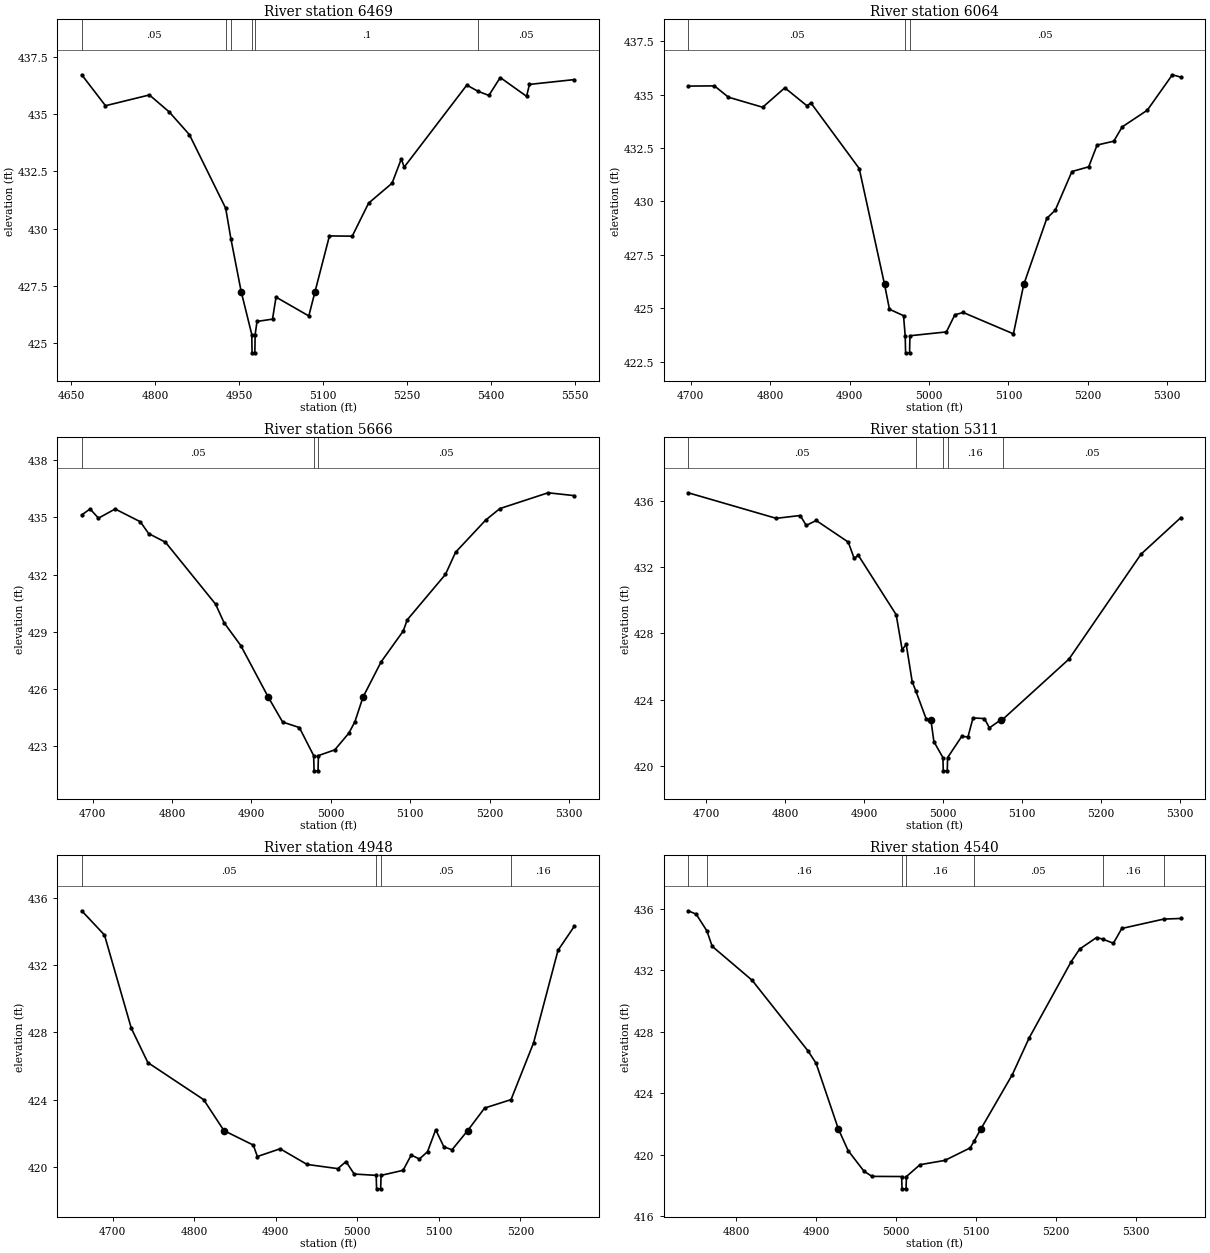
Type RM Length L Ch R = 1,6469,405,405,405
BEGIN DESCRIPTION:
UNT 056 in Running Cr Watershed 14.0
END DESCRIPTION:
XS GIS Cut Line= 3
      2878224.98      7039025.01      2877975.00      7039225.00
      2877424.95      7039124.99
#Sta/Elev= 30
  4669.1  436.71  4711.5  435.36  4789.9  435.83  4825.2  435.09  4861.2  434.10
  4926.0  430.89  4935.4  429.55  4953.7  427.25  4972.6  425.38  4973.1  424.58
  4978.1  424.58  4978.6  425.38  4982.0  425.95  5009.6  426.05  5015.9  427.01
  5074.4  426.19  5085.5  427.25  5111.2  429.68  5151.9  429.67  5181.1  431.11
  5223.0  431.98  5239.5  433.04  5244.6  432.68  5356.4  436.26  5376.4  435.99
  5395.8  435.81  5416.1  436.59  5463.1  435.77  5468.2  436.29  5548.3  436.50
#Mann=6,-1,0
  4669.1    0.05       0  4926.0    0.16       0  4935.4     0.1       0
  4972.6    0.07       0  4978.6     0.1       0  5376.4    0.05       0
Bank Sta=4953.7,5085.5
Exp/Cntr=0.3,0.1

Type RM Length L Ch R = 1,6064,398,398,398
BEGIN DESCRIPTION:
UNT 056 in Running Cr Watershed 13.0
END DESCRIPTION:
XS GIS Cut Line= 3
      2878125.00      7038925.00      2877825.00      7038975.00
      2877524.97      7039075.01
#Sta/Elev= 30
  4696.7  435.40  4729.7  435.41  4747.4  434.88  4790.5  434.41  4818.4  435.32
  4846.2  434.48  4851.3  434.61  4912.1  431.54  4944.0  426.11  4950.2  424.95
  4967.9  424.65  4970.0  423.71  4970.5  422.91  4975.5  422.91  4976.0  423.71
  5021.9  423.89  5032.5  424.69  5043.0  424.80  5106.3  423.80  5119.3  426.11
  5148.4  429.21  5159.0  429.59  5180.0  431.40  5201.1  431.62  5211.7  432.64
  5232.7  432.82  5243.3  433.49  5274.9  434.27  5306.5  435.93  5317.1  435.82
#Mann=3,-1,0
  4696.7    0.05       0  4970.0    0.03       0  4976.0    0.05       0
Bank Sta=4944,5119.3
Exp/Cntr=0.3,0.1

Type RM Length L Ch R = 1,5666,355,355,355
BEGIN DESCRIPTION:
UNT 056 in Running Cr Watershed 12.0
END DESCRIPTION:
XS GIS Cut Line= 3
      2878124.99      7038825.00      2877825.00      7038725.00
      2877524.95      7038674.99
#Sta/Elev= 30
  4686.4  435.13  4696.9  435.44  4707.5  434.96  4728.5  435.44  4760.2  434.77
  4770.7  434.15  4791.8  433.70  4855.0  430.45  4865.6  429.48  4886.7  428.28
  4921.4  425.57  4939.4  424.27  4960.5  423.98  4978.5  422.51  4979.0  421.71
  4984.0  421.71  4984.5  422.51  5005.1  422.81  5022.9  423.69  5030.5  424.29
  5040.6  425.57  5063.4  427.42  5091.3  429.04  5096.4  429.63  5144.5  432.01
  5157.2  433.17  5195.2  434.86  5213.0  435.46  5273.8  436.29  5306.8  436.14
#Mann=3,-1,0
  4686.4    0.05       0  4978.5    0.03       0  4984.5    0.05       0
Bank Sta=4921.4,5040.6
Exp/Cntr=0.3,0.1

Type RM Length L Ch R = 1,5311,363,363,363
BEGIN DESCRIPTION:
UNT 056 in Running Cr Watershed 11.0
END DESCRIPTION:
XS GIS Cut Line= 3
      2878175.03      7038475.00      2877875.00      7038425.00
      2877625.02      7038624.99
#Sta/Elev= 30
  4677.3  436.48  4788.8  434.94  4819.3  435.11  4826.9  434.51  4839.5  434.81
  4880.1  433.51  4887.7  432.52  4892.8  432.72  4940.9  429.13  4948.5  427.01
  4953.6  427.35  4961.2  425.09  4965.9  424.52  4978.9  422.85  4984.9  422.79
  4988.7  421.48  5000.1  420.52  5000.6  419.72  5005.6  419.72  5006.1  420.52
  5023.9  421.79  5031.9  421.77  5038.3  422.91  5052.7  422.87  5059.1  422.31
  5073.4  422.79  5076.1  422.83  5160.0  426.46  5251.2  432.78  5301.6  434.98
#Mann=5,-1,0
  4677.3    0.05       0  4965.9    0.16       0  5000.1    0.07       0
  5006.1    0.16       0  5076.1    0.05       0
Bank Sta=4984.9,5073.4
Exp/Cntr=0.3,0.1

Type RM Length L Ch R = 1,4948,408,408,408
BEGIN DESCRIPTION:
UNT 056 in Running Cr Watershed 10.0
END DESCRIPTION:
XS GIS Cut Line= 3
      2878075.01      7038225.00      2877775.00      7038175.00
      2877475.05      7038175.00
#Sta/Elev= 30
  4662.1  435.23  4690.0  433.79  4722.9  428.25  4743.2  426.21  4811.6  424.01
  4836.5  422.17  4872.5  421.31  4877.5  420.63  4905.4  421.09  4938.4  420.16
  4976.2  419.91  4986.2  420.33  4996.2  419.59  5023.2  419.51  5023.7  418.71
  5028.7  418.71  5029.2  419.51  5056.2  419.81  5066.2  420.72  5076.2  420.48
  5086.2  420.92  5096.2  422.22  5106.2  421.21  5116.2  421.03  5135.4  422.17
  5156.2  423.51  5188.6  424.01  5216.2  427.38  5246.2  432.88  5266.2  434.31
#Mann=4,-1,0
  4662.1    0.05       0  5023.2    0.03       0  5029.2    0.05       0
  5188.6    0.16       0
Bank Sta=4836.5,5135.4
Exp/Cntr=0.3,0.1

Type RM Length L Ch R = 1,4540,404,404,404
BEGIN DESCRIPTION:
UNT 056 in Running Cr Watershed 9.0
END DESCRIPTION:
XS GIS Cut Line= 3
      2878174.97      7037975.00      2877875.00      7037975.00
      2877575.00      7037875.00
#Sta/Elev= 30
  4740.2  435.87  4750.2  435.65  4763.6  434.56  4770.2  433.56  4820.2  431.35
  4890.2  426.75  4900.2  425.95  4928.0  421.69  4940.2  420.28  4960.2  418.93
  4970.2  418.60  5007.2  418.59  5007.7  417.79  5012.7  417.79  5013.2  418.59
  5030.2  419.36  5061.3  419.64  5092.9  420.45  5098.0  420.90  5106.4  421.69
  5145.6  425.21  5166.7  427.60  5219.4  432.57  5229.9  433.38  5251.0  434.13
  5258.5  434.03  5272.1  433.76  5282.6  434.72  5335.1  435.33  5356.4  435.37
#Mann=7,-1,0
  4740.2     0.1       0  4763.6    0.16       0  5007.2    0.07       0
  5013.2    0.16       0  5098.0    0.05       0  5258.5    0.16       0
  5335.1    0.05       0
Bank Sta=4928,5106.4
Exp/Cntr=0.3,0.1

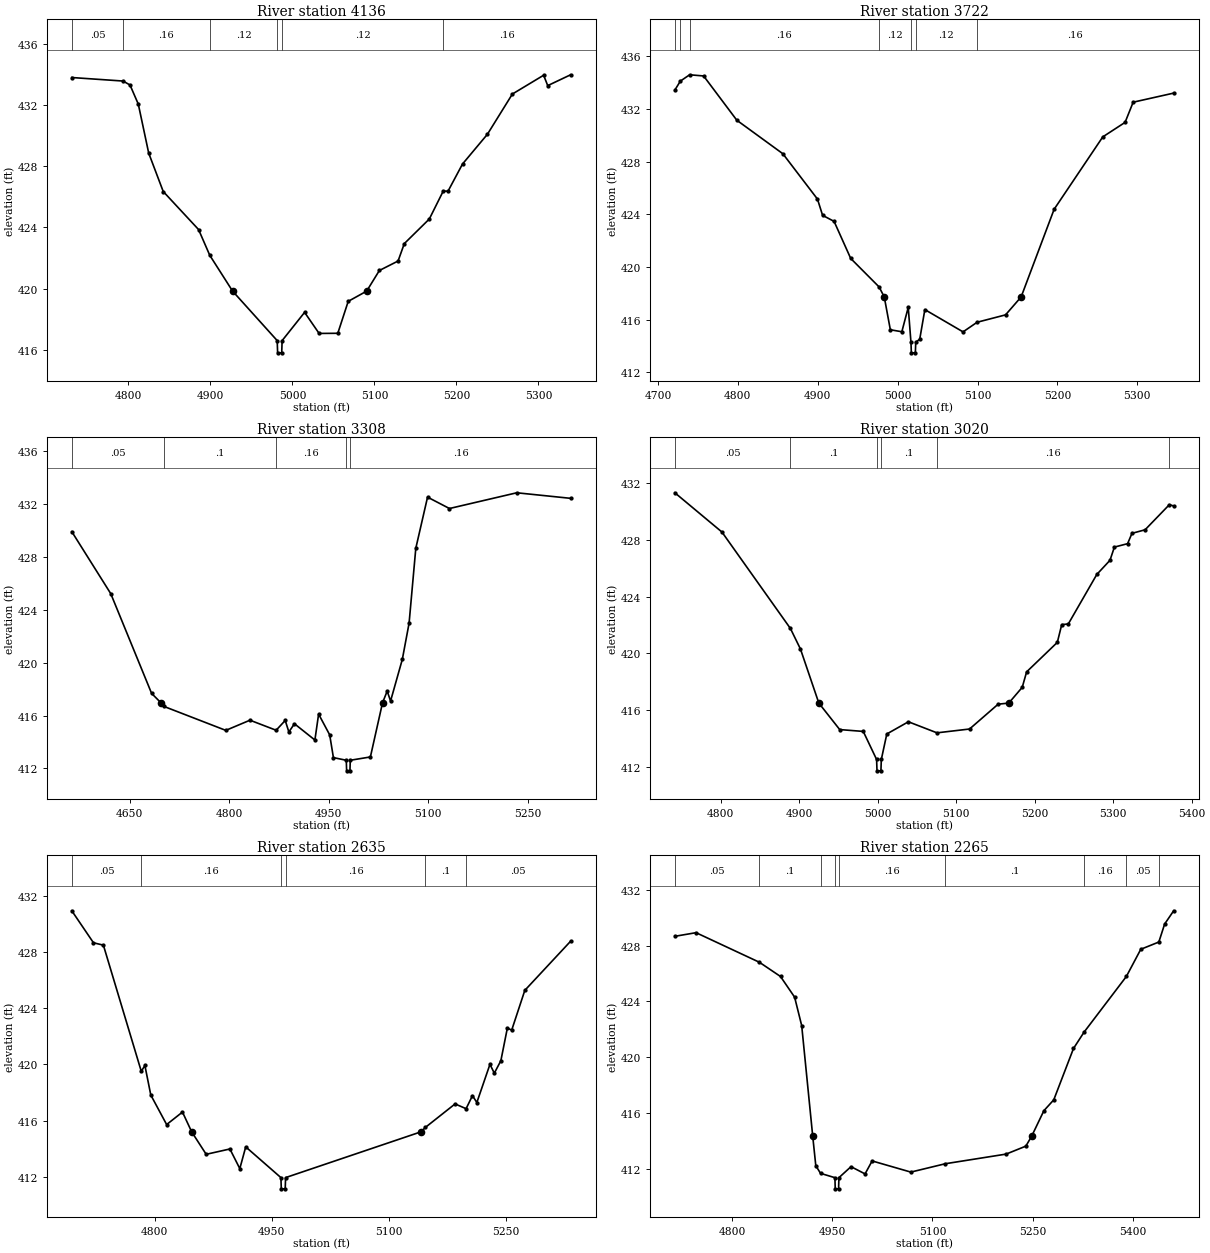
Type RM Length L Ch R = 1,4136,414,414,414
BEGIN DESCRIPTION:
UNT 056 in Running Cr Watershed 8.0
END DESCRIPTION:
XS GIS Cut Line= 3
      2878225.02      7037725.00      2877925.00      7037675.00
      2877625.00      7037625.00
#Sta/Elev= 30
  4730.9  433.81  4793.4  433.58  4801.9  433.32  4812.0  432.07  4824.7  428.86
  4842.4  426.35  4885.5  423.86  4899.2  422.17  4927.0  419.83  4981.4  416.59
  4981.9  415.79  4986.9  415.79  4987.4  416.59  5014.8  418.44  5032.5  417.06
  5055.3  417.07  5068.0  419.16  5090.5  419.83  5106.0  421.18  5128.8  421.80
  5136.4  422.94  5166.9  424.55  5183.9  426.38  5189.7  426.37  5207.4  428.15
  5237.8  430.10  5268.2  432.73  5306.3  433.96  5311.3  433.28  5339.2  433.99
#Mann=6,-1,0
  4730.9    0.05       0  4793.4    0.16       0  4899.2    0.12       0
  4981.4    0.07       0  4987.4    0.12       0  5183.9    0.16       0
Bank Sta=4927,5090.5
Exp/Cntr=0.3,0.1

Type RM Length L Ch R = 1,3722,414,414,414
BEGIN DESCRIPTION:
UNT 056 in Running Cr Watershed 7.0
END DESCRIPTION:
XS GIS Cut Line= 3
      2878224.99      7037624.99      2878025.00      7037375.00
      2877724.98      7037325.00
#Sta/Elev= 30
  4721.2  433.42  4728.1  434.10  4739.7  434.58  4757.2  434.49  4798.8  431.13
  4856.4  428.59  4899.7  425.15  4906.1  423.92  4920.5  423.46  4941.3  420.65
  4976.8  418.49  4983.3  417.73  4990.9  415.24  5005.3  415.09  5013.3  416.94
  5016.7  414.29  5017.2  413.49  5022.2  413.49  5022.7  414.29  5027.7  414.53
  5034.1  416.77  5081.9  415.08  5099.5  415.81  5135.1  416.37  5154.6  417.73
  5195.9  424.38  5256.8  429.87  5284.7  430.97  5294.8  432.50  5345.5  433.19
#Mann=7,-1,0
  4721.2    0.16       0  4728.1    0.05       0  4739.7    0.16       0
  4976.8    0.12       0  5016.7    0.07       0  5022.7    0.12       0
  5099.5    0.16       0
Bank Sta=4983.3,5154.6
Exp/Cntr=0.3,0.1

Type RM Length L Ch R = 1,3308,288,288,288
BEGIN DESCRIPTION:
UNT 056 in Running Cr Watershed 6.0
END DESCRIPTION:
XS GIS Cut Line= 3
      2878375.02      7036824.99      2877975.00      7037025.00
      2877674.98      7037075.00
#Sta/Elev= 30
  4562.9  429.91  4621.6  425.22  4683.1  417.68  4697.1  416.97  4701.8  416.69
  4794.9  414.88  4831.3  415.65  4870.7  414.89  4884.4  415.63  4889.9  414.76
  4898.3  415.38  4929.1  414.15  4934.7  416.11  4951.4  414.54  4957.0  412.82
  4976.4  412.62  4976.9  411.82  4981.9  411.82  4982.4  412.62  5012.7  412.87
  5031.0  416.97  5038.0  417.85  5043.1  417.10  5060.8  420.25  5071.0  422.99
  5081.1  428.65  5098.8  432.52  5131.8  431.66  5233.2  432.85  5314.3  432.43
#Mann=5,-1,0
  4562.9    0.05       0  4701.8     0.1       0  4870.7    0.16       0
  4976.4    0.07       0  4982.4    0.16       0
Bank Sta=4697.1,5031
Exp/Cntr=0.3,0.1

Type RM Length L Ch R = 1,3020,385,385,385
BEGIN DESCRIPTION:
UNT 056 in Running Cr Watershed 5.0
END DESCRIPTION:
XS GIS Cut Line= 3
      2878374.96      7036775.00      2878075.00      7036775.00
      2877774.98      7036925.01
#Sta/Elev= 30
  4741.6  431.32  4801.6  428.55  4888.8  421.75  4901.6  420.30  4925.0  416.49
  4951.6  414.62  4981.6  414.49  4998.6  412.51  4999.1  411.71  5004.1  411.71
  5004.6  412.51  5011.6  414.31  5039.1  415.17  5075.5  414.39  5117.0  414.66
  5153.4  416.41  5167.0  416.49  5184.1  417.60  5189.7  418.69  5228.8  420.77
  5234.4  422.02  5242.8  422.07  5279.1  425.56  5295.9  426.56  5301.5  427.49
  5318.3  427.73  5323.9  428.46  5340.6  428.71  5371.5  430.48  5377.0  430.39
#Mann=6,-1,0
  4741.6    0.05       0  4888.8     0.1       0  4998.6    0.07       0
  5004.6     0.1       0  5075.5    0.16       0  5371.5    0.05       0
Bank Sta=4925,5167
Exp/Cntr=0.3,0.1

Type RM Length L Ch R = 1,2635,370,370,370
BEGIN DESCRIPTION:
UNT 056 in Running Cr Watershed 4.0
END DESCRIPTION:
XS GIS Cut Line= 3
      2878174.95      7036475.01      2877875.00      7036525.00
      2877725.00      7036825.00
#Sta/Elev= 30
  4693.8  430.95  4721.6  428.67  4734.3  428.50  4782.9  419.51  4787.5  419.93
  4795.1  417.82  4815.4  415.72  4835.7  416.61  4847.5  415.20  4866.1  413.60
  4896.5  413.98  4909.2  412.58  4916.8  414.13  4961.9  411.94  4962.4  411.14
  4967.4  411.14  4967.9  411.94  5141.4  415.20  5147.2  415.52  5185.2  417.19
  5199.3  416.85  5207.5  417.78  5213.1  417.29  5229.9  420.01  5235.5  419.38
  5243.9  420.27  5252.2  422.59  5257.8  422.45  5274.6  425.28  5333.3  428.78
#Mann=6,-1,0
  4693.8    0.05       0  4782.9    0.16       0  4961.9    0.07       0
  4967.9    0.16       0  5147.2     0.1       0  5199.3    0.05       0
Bank Sta=4847.5,5141.4
Exp/Cntr=0.3,0.1

Type RM Length L Ch R = 1,2265,350,350,350
BEGIN DESCRIPTION:
UNT 056 in Running Cr Watershed 3.0
END DESCRIPTION:
XS GIS Cut Line= 3
      2877925.03      7036224.99      2877625.00      7036325.00
      2877274.98      7036575.01
#Sta/Elev= 30
  4714.6  428.67  4746.3  428.93  4841.1  426.81  4872.7  425.79  4893.8  424.31
  4904.4  422.27  4920.9  414.34  4925.5  412.23  4932.6  411.68  4954.1  411.37
  4954.6  410.57  4959.6  410.57  4960.1  411.37  4978.2  412.16  4999.2  411.64
  5009.8  412.57  5067.7  411.77  5119.4  412.37  5210.3  413.06  5239.8  413.63
  5248.5  414.34  5266.8  416.17  5281.6  416.95  5311.1  420.63  5326.9  421.80
  5390.2  425.79  5411.8  427.74  5438.8  428.26  5447.5  429.55  5461.0  430.50
#Mann=9,-1,0
  4714.6    0.05       0  4841.1     0.1       0  4932.6    0.16       0
  4954.1    0.07       0  4960.1    0.16       0  5119.4     0.1       0
  5326.9    0.16       0  5390.2    0.05       0  5438.8    0.16       0
Bank Sta=4920.9,5248.5
Exp/Cntr=0.3,0.1

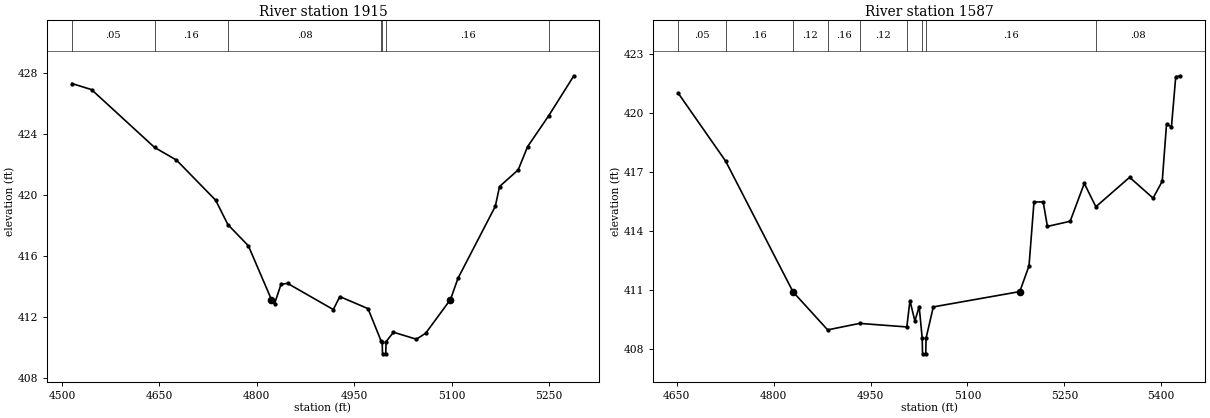
Type RM Length L Ch R = 1,1915,328,328,328
BEGIN DESCRIPTION:
UNT 056 in Running Cr Watershed 2.0
END DESCRIPTION:
XS GIS Cut Line= 3
      2877825.05      7036175.01      2877375.00      7036125.00
      2877174.98      7036375.02
#Sta/Elev= 30
  4515.4  427.33  4545.6  426.93  4642.7  423.13  4676.4  422.30  4736.8  419.66
  4755.6  418.06  4787.1  416.67  4822.6  413.14  4827.4  412.86  4837.4  414.14
  4847.5  414.20  4917.9  412.48  4928.0  413.33  4971.4  412.54  4991.5  410.42
  4993.2  410.37  4993.7  409.57  4998.7  409.57  4999.2  410.37  5010.6  410.99
  5045.9  410.53  5060.3  410.93  5098.4  413.14  5109.9  414.53  5167.5  419.27
  5173.9  420.56  5202.7  421.66  5217.1  423.18  5249.9  425.23  5288.4  427.84
#Mann=7,-1,0
  4515.4    0.05       0  4642.7    0.16       0  4755.6    0.08       0
  4991.5    0.16       0  4993.2    0.07       0  4999.2    0.16       0
  5249.9     0.1       0
Bank Sta=4822.6,5098.4
Exp/Cntr=0.3,0.1

Type RM Length L Ch R = 1,1587,0,0,0
BEGIN DESCRIPTION:
UNT 056 in Running Cr Watershed 1.0
END DESCRIPTION:
XS GIS Cut Line= 3
      2877675.02      7035925.01      2877375.00      7035825.00
      2877025.02      7036124.98
#Sta/Elev= 30
  4652.4  420.99  4725.6  417.54  4829.2  410.93  4829.5  410.90  4883.5  408.95
  4932.9  409.28  5006.1  409.10  5010.9  410.44  5018.6  409.40  5025.2  410.14
  5029.9  408.53  5030.4  407.73  5035.4  407.73  5035.9  408.53  5047.1  410.12
  5181.0  410.90  5195.3  412.21  5203.0  415.46  5217.2  415.47  5223.8  414.22
  5259.0  414.48  5280.9  416.41  5298.8  415.22  5351.1  416.72  5387.4  415.66
  5401.6  416.52  5408.2  419.41  5415.9  419.30  5422.5  421.84  5429.6  421.89
#Mann=9,-1,0
  4652.4    0.05       0  4725.6    0.16       0  4829.2    0.12       0
  4883.5    0.16       0  4932.9    0.12       0  5006.1    0.16       0
  5029.9    0.07       0  5035.9    0.16       0  5298.8    0.08       0
Bank Sta=4829.5,5181
Exp/Cntr=0.3,0.1

Chan Stop Cuts=-1