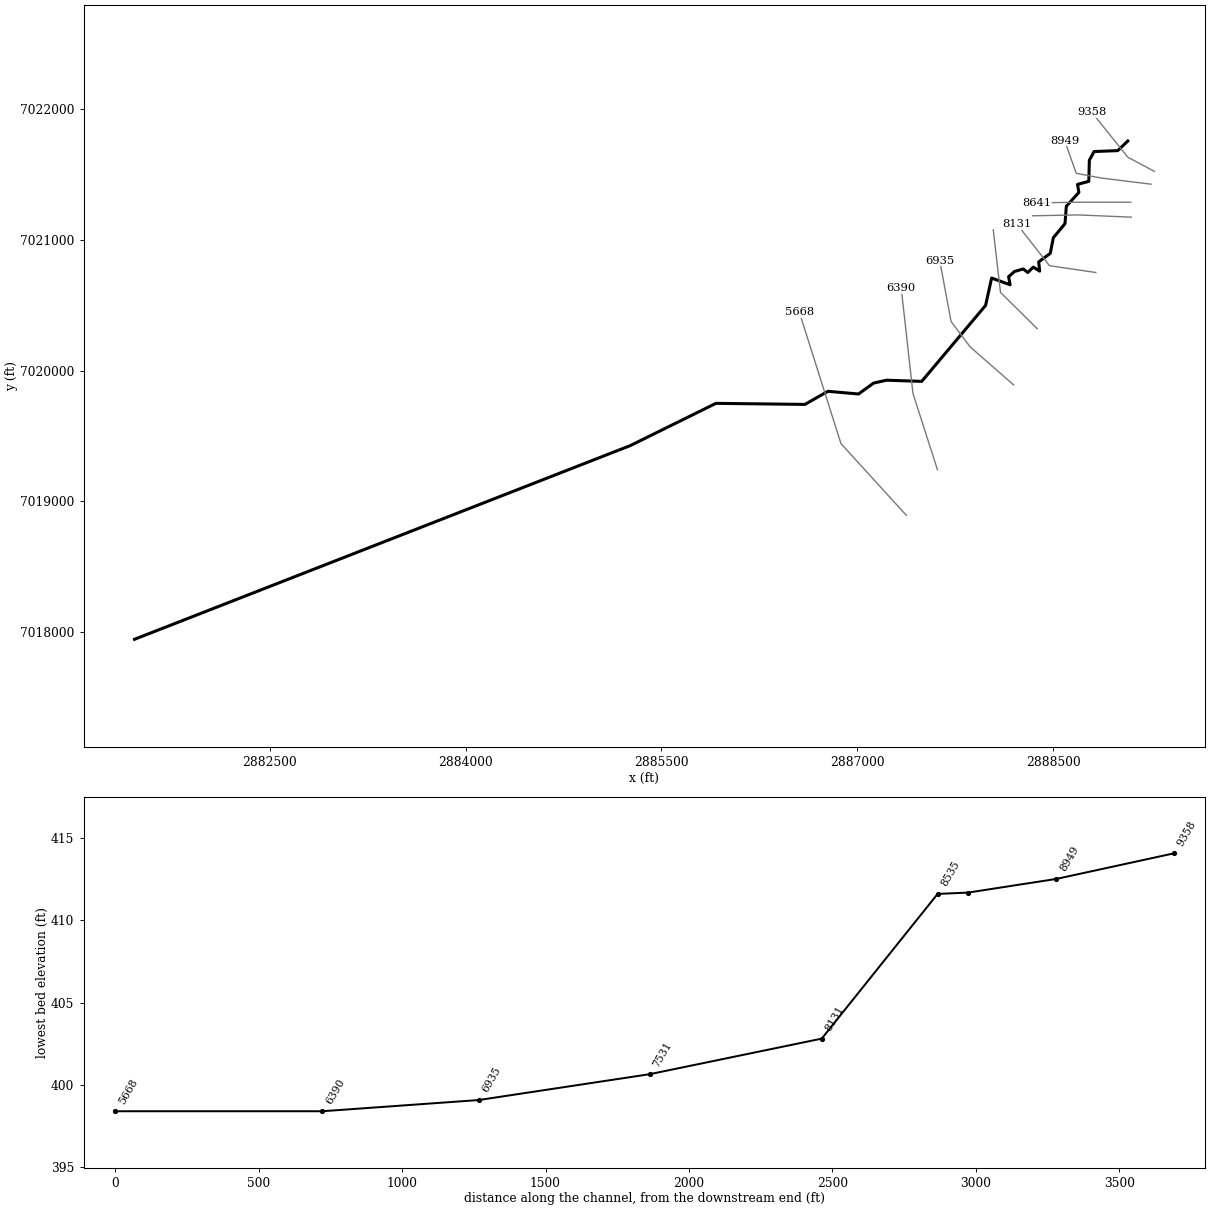
--- UNT 057 in Running Cr Watershed.prj (project) ---

Proj Title=UNT 057 in Running Cr Watershed Base Level Engineering
Current Plan=p01
Default Exp/Contr=0.3,0.1
English Units
Geom File=g01
Flow File=f01
Plan File=p01
BEGIN DESCRIPTION:
UNT 057 in Running Cr Watershed
END DESCRIPTION:

--- UNT 057 in Running Cr Watershed.p01 (plan) ---

Plan Title=Multiple Run
Short Identifier=Multiple
Geom File=g01
Flow File=f01
Subcritical Flow
K Sum by GR= 0
Std Step Tol= 0.01
Critical Tol= 0.01
Num of Std Step Trials= 20
Max Error Tol= 0.3
Flow Tol Ratio= 0.001
Split Flow NTrial= 30
Split Flow Tol= 0.02
Split Flow Ratio= 0.02
Log Output Level= 0
Friction Slope Method= 1
Unsteady Friction Slope Method= 2
Unsteady Bridges Friction Slope Method= 1
Parabolic Critical Depth
Global Vel Dist=  1 , 1 , 1
Global Log Level= 0
CheckData=True
Encroach Param= -1, 0, 0, 0
BEGIN DESCRIPTION:
Multiple Run
END DESCRIPTION:

--- UNT 057 in Running Cr Watershed.f01 (steady flow) ---

Flow Title=Multiple
Number of Profiles=7
Profile Names=10-year,25-year,50-year,1pct_min,100-year,1pct_plu,500-year
River Rch & RM= UNT 057 in Runni,Reach-1,9358
     372     484     572     337     672    1341     929
River Rch & RM= UNT 057 in Runni,Reach-1,8949
     418     547     650     385     767    1531    1069
River Rch & RM= UNT 057 in Runni,Reach-1,7531
     787    1070    1304     789    1574    3141    2298
Boundary for River Rch & Prof#=UNT 057 in Runni,Reach-1,1
Up Type=0
Dn Type=3
Dn Slope=0.005
Boundary for River Rch & Prof#=UNT 057 in Runni,Reach-1,2
Up Type=0
Dn Type=3
Dn Slope=0.005
Boundary for River Rch & Prof#=UNT 057 in Runni,Reach-1,3
Up Type=0
Dn Type=3
Dn Slope=0.005
Boundary for River Rch & Prof#=UNT 057 in Runni,Reach-1,4
Up Type=0
Dn Type=3
Dn Slope=0.005
Boundary for River Rch & Prof#=UNT 057 in Runni,Reach-1,5
Up Type=0
Dn Type=3
Dn Slope=0.005
Boundary for River Rch & Prof#=UNT 057 in Runni,Reach-1,6
Up Type=0
Dn Type=3
Dn Slope=0.005
Boundary for River Rch & Prof#=UNT 057 in Runni,Reach-1,7
Up Type=0
Dn Type=3
Dn Slope=0.005

--- UNT 057 in Running Cr Watershed.g01 (geometry) ---

Geom Title=Existing Conditions

River Reach=UNT 057 in Runni,Reach-1
Reach XY= 30
      2889071.22      7021757.74      2888994.19      7021684.01
      2888813.19      7021676.96      2888776.74      7021610.29
      2888772.50      7021448.67      2888686.16      7021425.44
      2888696.69      7021364.12      2888600.53      7021258.01
      2888590.25      7021125.01      2888500.98      7021016.61
      2888477.57      7020897.32      2888388.79      7020831.70
      2888396.51      7020760.93      2888347.61      7020791.81
      2888305.15      7020750.64      2888270.41      7020777.66
      2888203.49      7020758.36      2888158.46      7020718.47
      2888170.04      7020656.70      2888028.50      7020708.17
      2887982.18      7020498.43      2887493.21      7019916.83
      2887224.28      7019925.83      2887125.20      7019903.96
      2887009.40      7019820.32      2886775.21      7019840.91
      2886598.93      7019740.54      2885917.42      7019748.61
      2885263.28      7019425.76      2881465.81      7017941.91

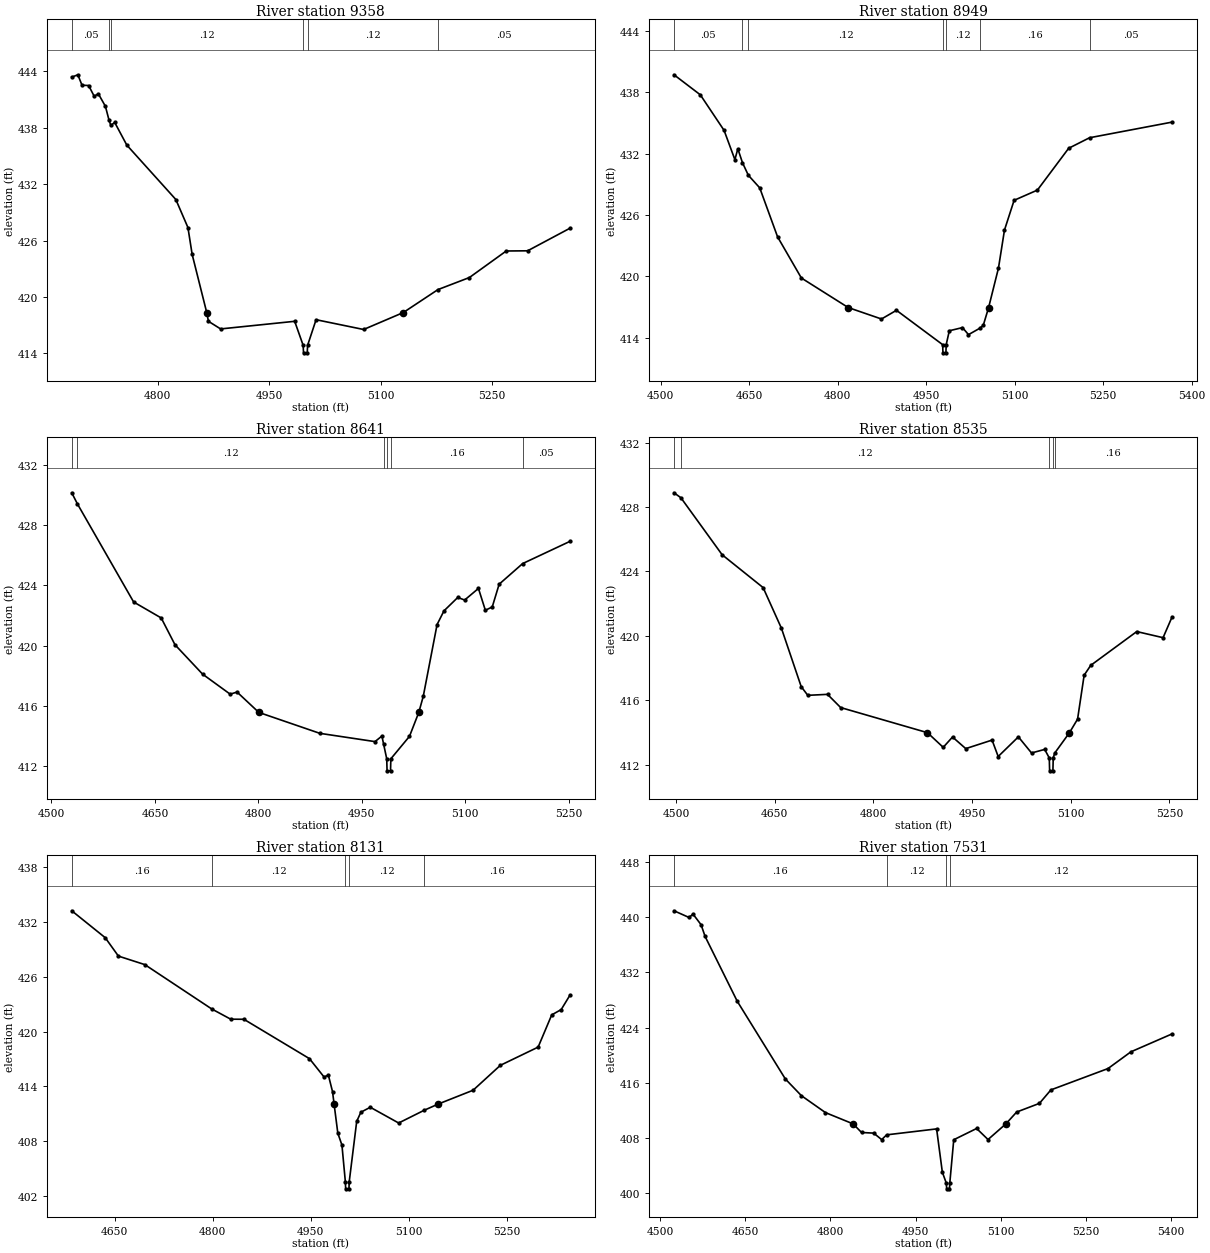
Type RM Length L Ch R = 1,9358,409,409,409
BEGIN DESCRIPTION:
UNT 057 in Running Cr Watershed 2.0
END DESCRIPTION:
XS GIS Cut Line= 3
      2889275.01      7021524.99      2889072.18      7021632.71
      2888796.15      7021976.44
#Sta/Elev= 30
  4684.1  443.36  4692.3  443.61  4697.9  442.50  4706.8  442.47  4714.3  441.33
  4719.9  441.59  4729.4  440.26  4734.3  438.78  4736.7  438.23  4741.9  438.55
  4758.2  436.14  4824.2  430.36  4840.5  427.38  4846.2  424.52  4865.8  418.35
  4868.1  417.42  4884.5  416.61  4984.2  417.42  4995.6  414.87  4996.1  414.07
  5001.1  414.07  5001.6  414.87  5013.0  417.59  5077.0  416.55  5130.4  418.35
  5177.1  420.79  5219.4  422.07  5269.0  424.89  5297.8  424.91  5354.6  427.30
#Mann=6,-1,0
  4684.1    0.05       0  4734.3    0.16       0  4736.7    0.12       0
  4995.6    0.07       0  5001.6    0.12       0  5177.1    0.05       0
Bank Sta=4865.8,5130.4
Exp/Cntr=0.3,0.1

Type RM Length L Ch R = 1,8949,308,308,308
BEGIN DESCRIPTION:
Mapping XS aca8bfb8
END DESCRIPTION:
XS GIS Cut Line= 4
      2889249.26      7021426.99      2888869.05      7021473.86
      2888676.34      7021510.32      2888587.84      7021760.20
#Sta/Elev= 30
  4522.4  439.72  4567.0  437.76  4607.3  434.28  4625.6  431.42  4630.6  432.48
  4638.4  431.13  4648.4  429.89  4667.7  428.66  4698.0  423.86  4738.3  419.84
  4817.7  416.95  4874.1  415.83  4899.5  416.68  4977.8  413.32  4978.3  412.52
  4983.3  412.52  4983.8  413.32  4989.1  414.68  5011.4  414.99  5021.6  414.30
  5040.3  414.91  5046.6  415.20  5055.7  416.95  5072.4  420.81  5082.6  424.53
  5098.9  427.44  5138.4  428.44  5191.4  432.53  5226.8  433.56  5366.7  435.09
#Mann=7,-1,0
  4522.4    0.05       0  4638.4    0.16       0  4648.4    0.12       0
  4977.8    0.07       0  4983.8    0.12       0  5040.3    0.16       0
  5226.8    0.05       0
Bank Sta=4817.7,5055.7
Exp/Cntr=0.3,0.1

Type RM Length L Ch R = 1,8641,106,106,106
BEGIN DESCRIPTION:
Mapping XS 2504cf45
END DESCRIPTION:
XS GIS Cut Line= 3
      2889094.71      7021288.96      2888679.82      7021288.96
      2888372.55      7021283.76
#Sta/Elev= 30
  4529.4  430.15  4537.5  429.42  4619.1  422.90  4659.1  421.84  4679.1  420.06
  4719.1  418.11  4759.1  416.78  4769.1  416.92  4800.6  415.57  4889.1  414.18
  4969.1  413.63  4979.1  414.00  4981.7  413.44  4986.1  412.49  4986.6  411.69
  4991.6  411.69  4992.1  412.49  5019.1  413.98  5032.6  415.57  5039.1  416.64
  5059.1  421.40  5069.1  422.31  5089.1  423.20  5099.1  423.03  5119.1  423.80
  5129.1  422.35  5139.1  422.57  5149.1  424.08  5183.2  425.45  5251.6  426.92
#Mann=6,-1,0
  4529.4    0.16       0  4537.5    0.12       0  4981.7    0.16       0
  4986.1    0.07       0  4992.1    0.16       0  5183.2    0.05       0
Bank Sta=4800.6,5032.6
Exp/Cntr=0.3,0.1

Type RM Length L Ch R = 1,8535,404,404,404
BEGIN DESCRIPTION:
Mapping XS 466cfde9
END DESCRIPTION:
XS GIS Cut Line= 3
      2889098.18      7021174.38      2888688.50      7021191.74
      2888341.32      7021184.80
#Sta/Elev= 30
  4496.7  428.88  4507.2  428.57  4569.9  425.03  4632.2  422.99  4660.0  420.47
  4690.1  416.84  4700.1  416.30  4730.1  416.36  4750.1  415.54  4882.1  413.98
  4906.0  413.07  4920.2  413.71  4940.3  412.99  4980.3  413.52  4989.6  412.50
  5020.3  413.72  5040.3  412.72  5060.3  412.94  5067.3  412.41  5067.8  411.61
  5072.8  411.61  5073.3  412.41  5075.5  412.71  5098.0  413.98  5110.3  414.82
  5120.3  417.55  5130.3  418.16  5200.3  420.26  5240.3  419.88  5254.0  421.17
#Mann=5,-1,0
  4496.7    0.16       0  4507.2    0.12       0  5067.3    0.07       0
  5073.3    0.12       0  5075.5    0.16       0
Bank Sta=4882.1,5098
Exp/Cntr=0.3,0.1

Type RM Length L Ch R = 1,8131,600,600,600
BEGIN DESCRIPTION:
Mapping XS 4736ec6d
END DESCRIPTION:
XS GIS Cut Line= 3
      2888825.64      7020750.77      2888471.48      7020802.85
      2888222.41      7021121.11
#Sta/Elev= 30
  4584.4  433.19  4635.6  430.25  4655.8  428.24  4696.2  427.31  4798.5  422.47
  4827.6  421.35  4847.8  421.34  4948.1  417.04  4970.5  415.03  4977.0  415.25
  4983.4  413.44  4985.8  412.08  4991.5  408.90  4997.8  407.60  5003.0  403.62
  5003.5  402.82  5008.5  402.82  5009.0  403.62  5020.4  410.19  5026.8  411.19
  5041.2  411.73  5084.6  410.01  5123.6  411.40  5145.1  412.08  5198.5  413.59
  5240.2  416.31  5298.0  418.30  5318.8  421.82  5333.3  422.40  5346.5  423.95
#Mann=5,-1,0
  4584.4    0.16       0  4798.5    0.12       0  5003.0    0.07       0
  5009.0    0.12       0  5123.6    0.16       0
Bank Sta=4985.8,5145.1
Exp/Cntr=0.3,0.1

Type RM Length L Ch R = 1,7531,596,596,596
BEGIN DESCRIPTION:
Mapping XS c1e509c6
END DESCRIPTION:
XS GIS Cut Line= 3
      2888377.70      7020320.24      2888096.48      7020597.99
      2888040.93      7021077.12
#Sta/Elev= 30
  4524.4  440.93  4550.9  439.96  4557.9  440.45  4572.1  438.91  4579.2  437.21
  4635.8  427.83  4720.6  416.57  4748.9  414.15  4791.3  411.70  4839.9  410.07
  4854.9  408.82  4876.2  408.73  4890.3  407.79  4899.1  408.48  4987.1  409.34
  4997.2  403.08  5004.3  401.46  5004.8  400.66  5009.8  400.66  5010.3  401.46
  5017.3  407.77  5057.6  409.40  5077.7  407.80  5109.2  410.07  5128.1  411.78
  5168.3  413.04  5188.5  414.99  5289.1  418.08  5329.4  420.50  5402.0  423.10
#Mann=4,-1,0
  4524.4    0.16       0  4899.1    0.12       0  5004.3    0.07       0
  5010.3    0.12       0
Bank Sta=4839.9,5109.2
Exp/Cntr=0.3,0.1

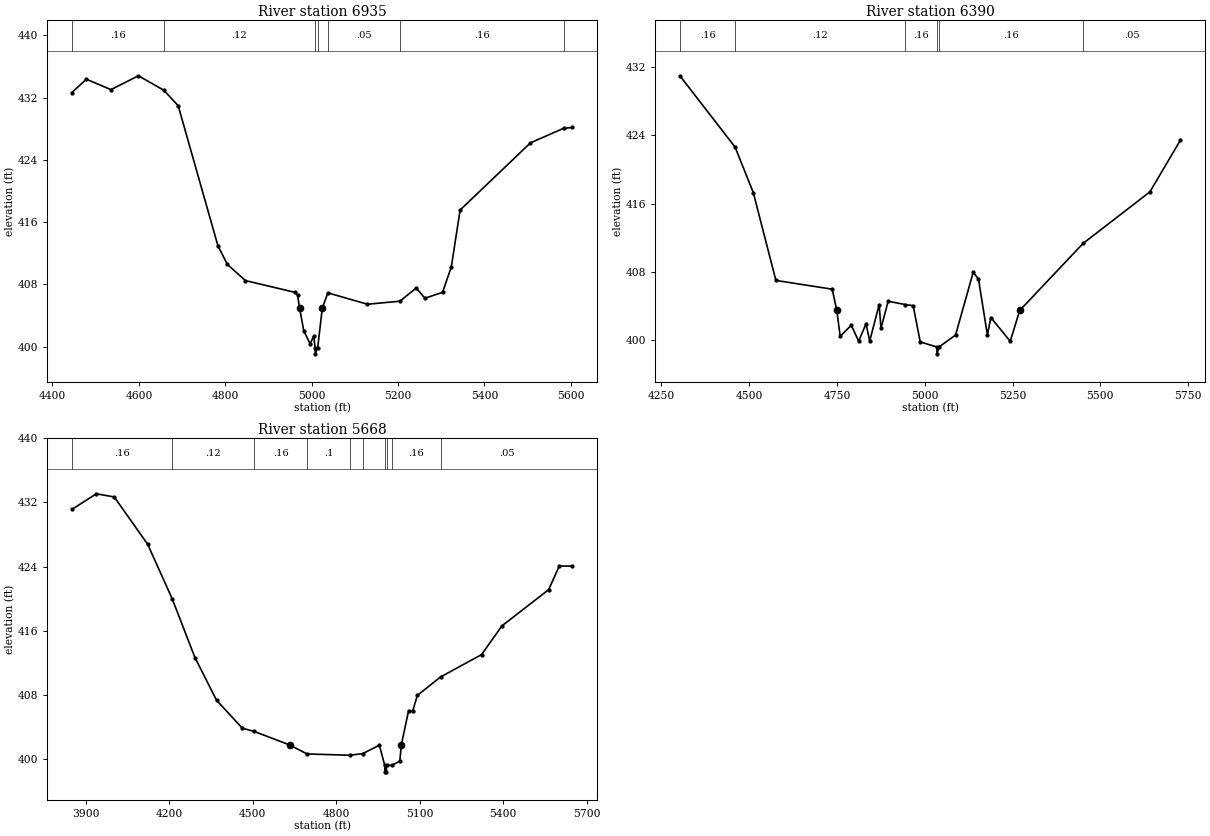
Type RM Length L Ch R = 1,6935,545,545,545
BEGIN DESCRIPTION:
Mapping XS 0275acc9
END DESCRIPTION:
XS GIS Cut Line= 4
      2888197.15      7019889.69      2887863.84      7020181.33
      2887718.01      7020375.77      2887631.30      7020840.51
#Sta/Elev= 30
  4444.9  432.65  4478.4  434.36  4535.3  433.02  4598.9  434.80  4657.6  432.95
  4691.0  430.96  4783.0  412.97  4804.9  410.57  4846.6  408.50  4961.0  406.99
  4967.4  406.62  4972.1  404.95  4981.8  402.04  4996.4  400.37  5004.7  401.38
  5008.0  399.89  5008.5  399.09  5014.0  399.89  5024.6  404.95  5037.5  406.92
  5129.2  405.46  5204.4  405.85  5242.0  407.54  5262.3  406.23  5303.0  406.99
  5323.3  410.25  5343.7  417.56  5506.6  426.19  5583.2  428.05  5603.6  428.16
#Mann=7,-1,0
  4444.9    0.16       0  4657.6    0.12       0  5008.0    0.07       0
  5014.0    0.12       0  5037.5    0.05       0  5204.4    0.16       0
  5583.2    0.05       0
Bank Sta=4972.1,5024.6
Exp/Cntr=0.3,0.1

Type RM Length L Ch R = 1,6390,722,722,722
BEGIN DESCRIPTION:
Mapping XS c7d26e66
END DESCRIPTION:
XS GIS Cut Line= 3
      2887613.85      7019240.34      2887426.34      7019823.69
      2887336.22      7020631.33
#Sta/Elev= 30
  4302.6  430.98  4459.8  422.63  4511.8  417.28  4576.0  407.01  4736.5  405.98
  4749.4  403.49  4759.2  400.46  4790.7  401.76  4811.7  399.90  4832.7  401.92
  4843.2  399.91  4870.1  404.17  4875.3  401.39  4895.7  404.57  4944.9  404.18
  4967.0  404.05  4987.1  399.81  5034.4  399.21  5034.9  398.41  5040.4  399.21
  5087.7  400.61  5138.0  407.97  5153.0  407.17  5178.3  400.63  5188.3  402.66
  5243.4  399.88  5270.4  403.49  5450.8  411.34  5641.1  417.38  5728.0  423.43
#Mann=6,-1,0
  4302.6    0.16       0  4459.8    0.12       0  4944.9    0.16       0
  5034.4    0.07       0  5040.4    0.16       0  5450.8    0.05       0
Bank Sta=4749.4,5270.4
Exp/Cntr=0.3,0.1

Type RM Length L Ch R = 1,5668,0,0,0
BEGIN DESCRIPTION:
UNT 057 in Running Cr Watershed 1.0
END DESCRIPTION:
XS GIS Cut Line= 3
      2887375.62      7018890.73      2886874.80      7019440.71
      2886556.22      7020446.21
#Sta/Elev= 30
  3849.9  431.12  3938.0  433.07  4002.2  432.67  4122.5  426.76  4210.6  419.96
  4292.1  412.66  4369.8  407.33  4462.4  403.85  4505.5  403.44  4632.6  401.76
  4694.9  400.64  4848.3  400.48  4895.3  400.68  4954.9  401.73  4974.2  399.21
  4974.7  398.41  4980.2  398.41  4980.7  399.21  5000.5  399.21  5028.3  399.76
  5033.8  401.76  5059.8  406.03  5074.3  405.94  5091.3  407.94  5175.0  410.24
  5322.0  413.02  5395.5  416.61  5563.3  421.12  5601.4  424.06  5648.5  424.06
#Mann=10,-1,0
  3849.9    0.16       0  4210.6    0.12       0  4505.5    0.16       0
  4694.9     0.1       0  4848.3    0.05       0  4895.3    0.07       0
  4974.2    0.07       0  4980.7    0.07       0  5000.5    0.16       0
  5175.0    0.05       0
Bank Sta=4632.6,5033.8
Exp/Cntr=0.3,0.1

Chan Stop Cuts=-1