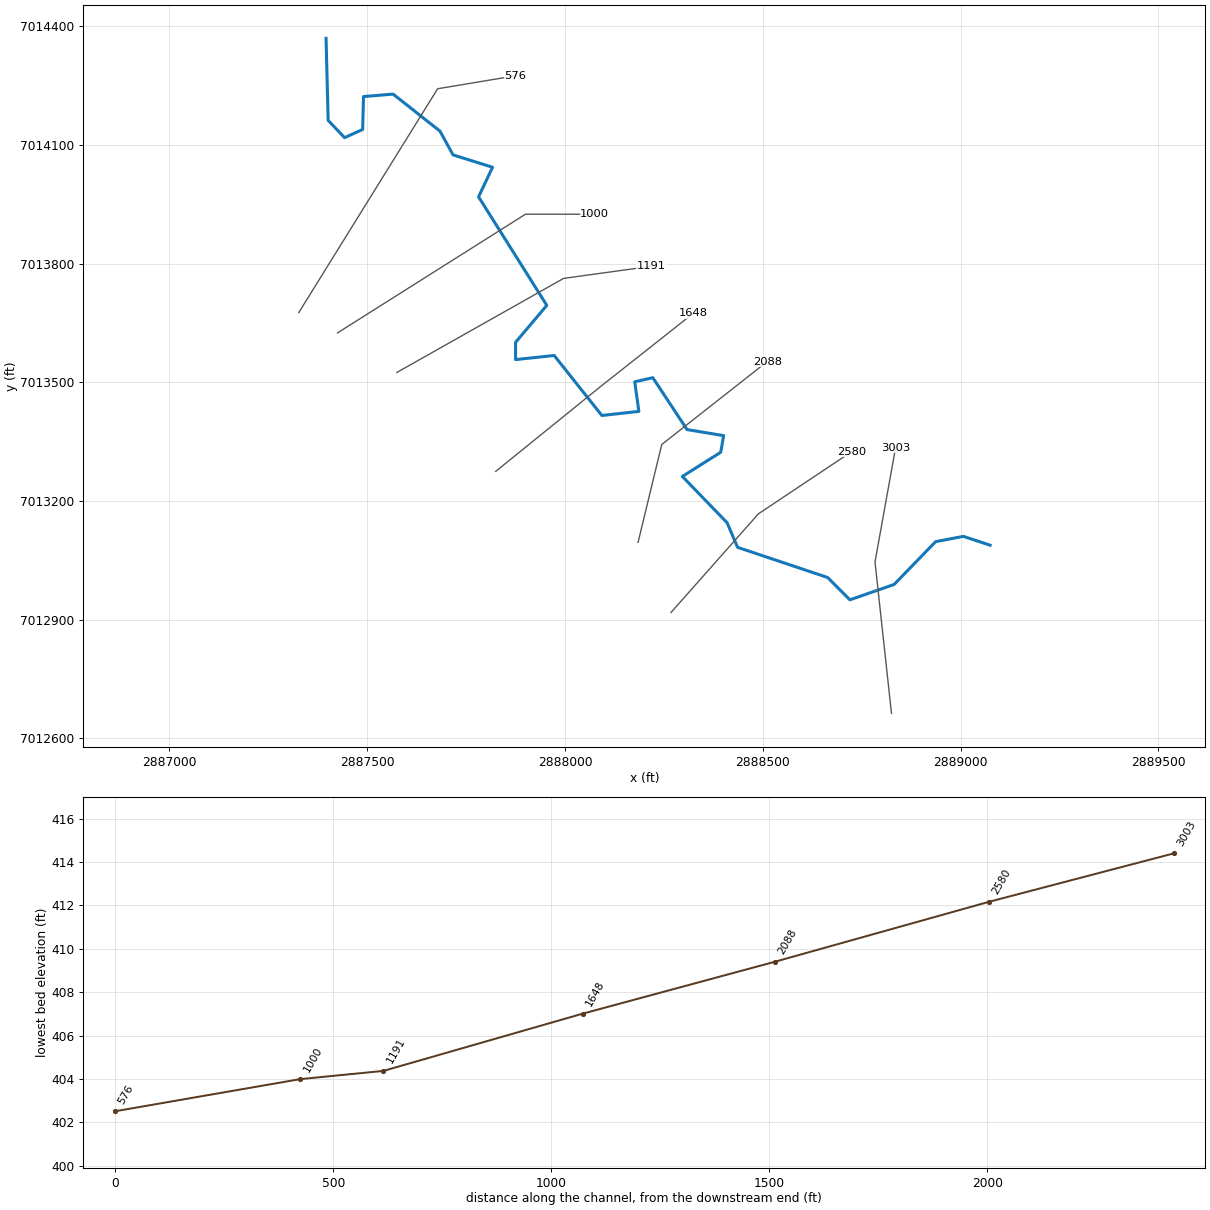
--- UNT 058 in Running Cr Watershed.prj (project) ---

Proj Title=UNT 058 in Running Cr Watershed Base Level Engineering
Current Plan=p01
Default Exp/Contr=0.3,0.1
English Units
Geom File=g01
Flow File=f01
Plan File=p01
BEGIN DESCRIPTION:
UNT 058 in Running Cr Watershed
END DESCRIPTION:

--- UNT 058 in Running Cr Watershed.p01 (plan) ---

Plan Title=Multiple Run
Short Identifier=Multiple
Geom File=g01
Flow File=f01
Subcritical Flow
K Sum by GR= 0
Std Step Tol= 0.01
Critical Tol= 0.01
Num of Std Step Trials= 20
Max Error Tol= 0.3
Flow Tol Ratio= 0.001
Split Flow NTrial= 30
Split Flow Tol= 0.02
Split Flow Ratio= 0.02
Log Output Level= 0
Friction Slope Method= 1
Unsteady Friction Slope Method= 2
Unsteady Bridges Friction Slope Method= 1
Parabolic Critical Depth
Global Vel Dist=  1 , 1 , 1
Global Log Level= 0
CheckData=True
Encroach Param= -1, 0, 0, 0
BEGIN DESCRIPTION:
Multiple Run
END DESCRIPTION:

--- UNT 058 in Running Cr Watershed.f01 (steady flow) ---

Flow Title=Multiple
Number of Profiles=7
Profile Names=10-year,25-year,50-year,1pct_min,100-year,1pct_plu,500-year
River Rch & RM= UNT 058 in Runni,Reach-1,3003
     609     821     996     601    1198    2391    1737
Boundary for River Rch & Prof#=UNT 058 in Runni,Reach-1,1
Up Type=0
Dn Type=3
Dn Slope=0.005
Boundary for River Rch & Prof#=UNT 058 in Runni,Reach-1,2
Up Type=0
Dn Type=3
Dn Slope=0.005
Boundary for River Rch & Prof#=UNT 058 in Runni,Reach-1,3
Up Type=0
Dn Type=3
Dn Slope=0.005
Boundary for River Rch & Prof#=UNT 058 in Runni,Reach-1,4
Up Type=0
Dn Type=3
Dn Slope=0.005
Boundary for River Rch & Prof#=UNT 058 in Runni,Reach-1,5
Up Type=0
Dn Type=3
Dn Slope=0.005
Boundary for River Rch & Prof#=UNT 058 in Runni,Reach-1,6
Up Type=0
Dn Type=3
Dn Slope=0.005
Boundary for River Rch & Prof#=UNT 058 in Runni,Reach-1,7
Up Type=0
Dn Type=3
Dn Slope=0.005

--- UNT 058 in Running Cr Watershed.g01 (geometry) ---

Geom Title=Existing Conditions

River Reach=UNT 058 in Runni,Reach-1
Reach XY= 30
      2889074.61      7013088.39      2889007.22      7013110.69
      2888936.98      7013097.32      2888831.99      7012989.04
      2888720.29      7012950.31      2888664.00      7013006.76
      2888436.40      7013082.97      2888409.87      7013145.19
      2888296.77      7013262.19      2888393.80      7013323.34
      2888401.10      7013365.37      2888308.60      7013380.65
      2888222.16      7013511.83      2888176.44      7013501.44
      2888186.83      7013426.64      2888093.33      7013416.25
      2887972.81      7013567.93      2887875.16      7013557.54
      2887875.16      7013601.18      2887954.11      7013694.68
      2887781.65      7013968.96      2887816.98      7014043.76
      2887717.24      7014074.93      2887683.99      7014135.18
      2887565.56      7014228.69      2887490.76      7014222.45
      2887488.68      7014139.34      2887442.96      7014118.56
      2887401.41      7014162.20      2887396.12      7014369.65

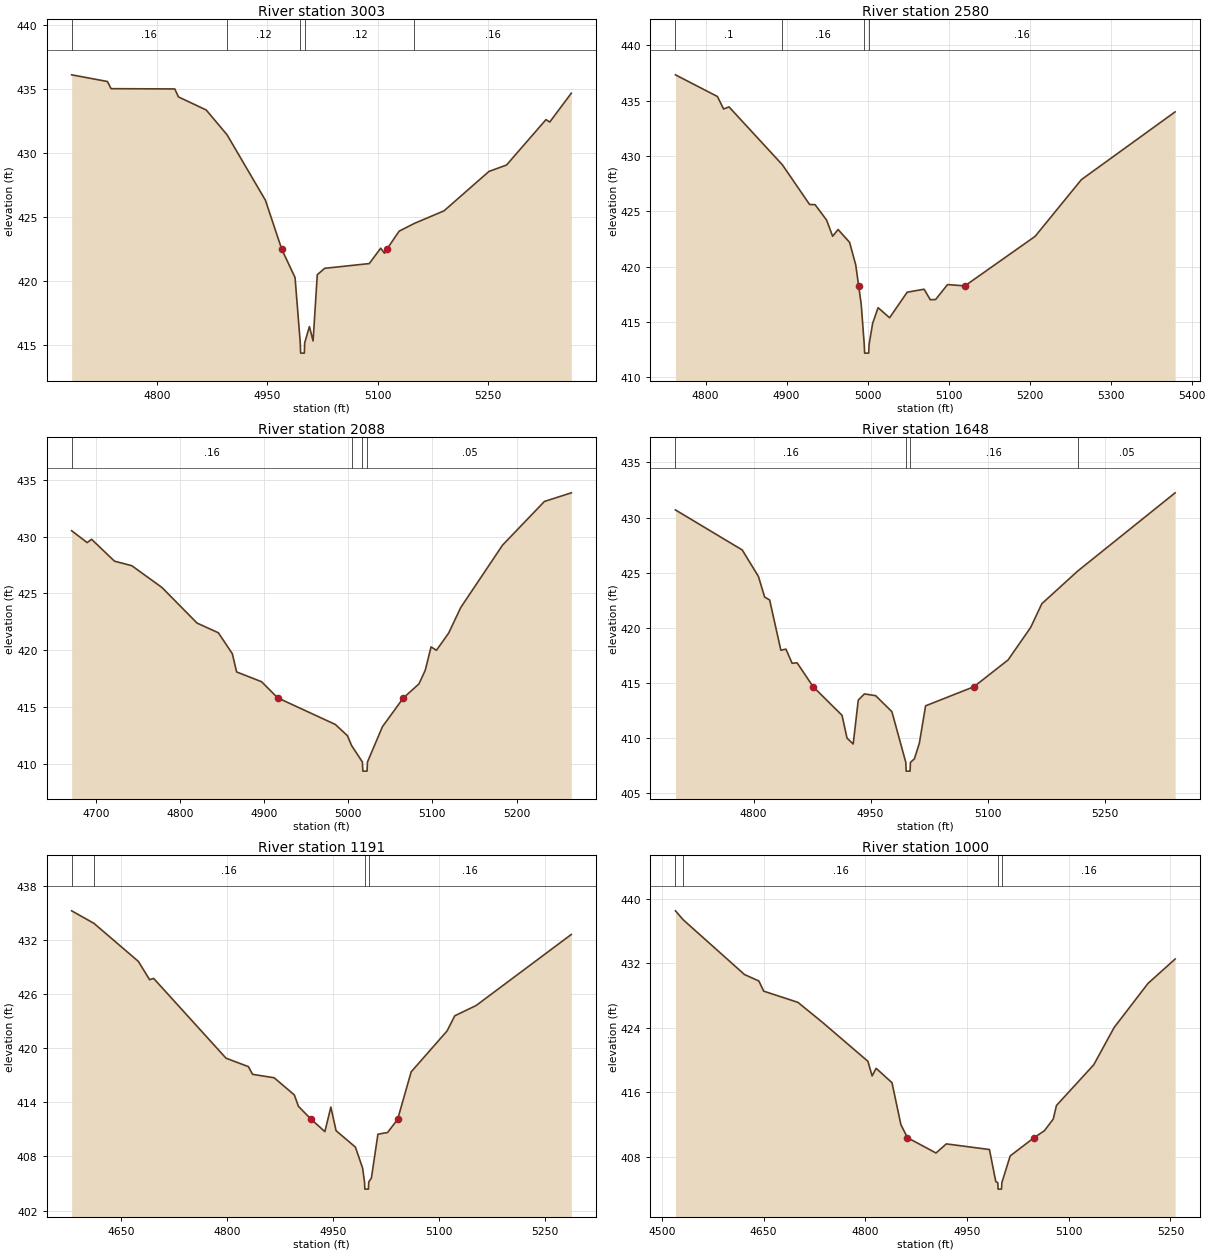
Type RM Length L Ch R = 1,3003,423,423,423
BEGIN DESCRIPTION:
UNT 058 in Running Cr Watershed 7.0
END DESCRIPTION:
XS GIS Cut Line= 3
      2888825.43      7012663.26      2888783.76      7013046.04
      2888835.85      7013335.14
#Sta/Elev= 30
  4684.3  436.09  4732.9  435.57  4737.9  435.01  4824.4  434.99  4829.4  434.37
  4867.1  433.35  4895.4  431.42  4947.6  426.31  4969.8  422.49  4987.8  420.29
  4994.9  415.20  4995.4  414.40  5000.4  414.40  5000.9  415.20  5007.3  416.47
  5012.3  415.35  5018.0  420.51  5028.1  421.01  5088.6  421.38  5104.2  422.58
  5109.3  422.18  5112.4  422.49  5129.3  423.91  5149.9  424.51  5190.2  425.49
  5251.2  428.56  5275.1  429.06  5328.7  432.60  5333.8  432.41  5363.1  434.66
#Mann=5,-1,0
  4684.3    0.16       0  4895.4    0.12       0  4994.9    0.07       0
  5000.9    0.12       0  5149.9    0.16       0
Bank Sta=4969.8,5112.4
Exp/Cntr=0.3,0.1

Type RM Length L Ch R = 1,2580,492,492,492
BEGIN DESCRIPTION:
UNT 058 in Running Cr Watershed 6.0
END DESCRIPTION:
XS GIS Cut Line= 3
      2888268.11      7012918.40      2888489.09      7013167.73
      2888725.01      7013325.00
#Sta/Elev= 30
  4762.9  437.34  4814.7  435.38  4822.3  434.25  4829.0  434.44  4894.9  429.20
  4928.5  425.61  4935.2  425.60  4949.4  424.21  4956.9  422.74  4963.6  423.35
  4977.8  422.19  4985.4  420.15  4989.0  418.25  4992.1  416.64  4995.9  412.97
  4996.4  412.17  5001.4  412.17  5001.9  412.97  5006.3  414.87  5013.0  416.28
  5027.2  415.37  5048.9  417.68  5069.8  417.95  5077.4  417.00  5084.0  417.02
  5098.7  418.37  5120.1  418.25  5206.8  422.73  5263.9  427.86  5379.6  433.99
#Mann=4,-1,0
  4762.9     0.1       0  4894.9    0.16       0  4995.9    0.07       0
  5001.9    0.16       0
Bank Sta=4989,5120.1
Exp/Cntr=0.3,0.1

Type RM Length L Ch R = 1,2088,440,440,440
BEGIN DESCRIPTION:
UNT 058 in Running Cr Watershed 5.0
END DESCRIPTION:
XS GIS Cut Line= 3
      2888184.80      7013095.50      2888244.70      7013342.91
      2888511.44      7013552.68
#Sta/Elev= 30
  4671.2  430.51  4689.7  429.47  4694.9  429.76  4722.1  427.84  4742.7  427.44
  4778.5  425.53  4820.3  422.40  4845.6  421.55  4862.2  419.71  4867.3  418.11
  4897.0  417.25  4916.2  415.83  4984.6  413.50  4999.0  412.51  5004.0  411.64
  5016.8  410.20  5017.3  409.40  5022.3  409.40  5022.8  410.20  5040.6  413.30
  5065.5  415.83  5084.0  417.06  5091.5  418.26  5098.4  420.31  5104.8  420.01
  5119.3  421.52  5133.7  423.77  5183.4  429.25  5233.1  433.08  5265.1  433.84
#Mann=4,-1,0
  4671.2    0.16       0  5004.0    0.05       0  5016.8    0.07       0
  5022.8    0.05       0
Bank Sta=4916.2,5065.5
Exp/Cntr=0.3,0.1

Type RM Length L Ch R = 1,1648,457,457,457
BEGIN DESCRIPTION:
UNT 058 in Running Cr Watershed 4.0
END DESCRIPTION:
XS GIS Cut Line= 3
      2887824.98      7013274.98      2888091.19      7013490.36
      2888325.04      7013675.03
#Sta/Elev= 30
  4699.9  430.69  4785.5  427.06  4806.3  424.65  4814.2  422.79  4820.6  422.53
  4835.0  417.97  4841.5  418.07  4849.4  416.79  4855.8  416.83  4876.4  414.66
  4913.4  412.07  4919.8  410.00  4927.7  409.47  4934.2  413.45  4942.1  414.01
  4956.5  413.85  4977.3  412.40  4995.1  407.81  4995.6  407.01  5000.6  407.01
  5001.1  407.81  5006.1  408.12  5012.5  409.54  5020.5  412.93  5082.4  414.66
  5126.2  417.09  5155.1  420.03  5169.5  422.19  5215.3  425.14  5340.3  432.24
#Mann=4,-1,0
  4699.9    0.16       0  4995.1    0.07       0  5001.1    0.16       0
  5215.3    0.05       0
Bank Sta=4876.4,5082.4
Exp/Cntr=0.3,0.1

Type RM Length L Ch R = 1,1191,191,191,191
BEGIN DESCRIPTION:
UNT 058 in Running Cr Watershed 3.0
END DESCRIPTION:
XS GIS Cut Line= 3
      2887575.02      7013525.01      2887996.66      7013762.86
      2888218.66      7013793.43
#Sta/Elev= 30
  4579.4  435.23  4610.9  433.85  4674.0  429.62  4689.9  427.59  4695.6  427.74
  4798.2  418.89  4830.0  417.95  4835.8  417.10  4866.4  416.72  4895.0  414.82
  4900.9  413.55  4919.0  412.10  4938.3  410.75  4946.8  413.47  4954.2  410.85
  4981.6  409.03  4991.8  406.70  4994.5  405.17  4995.0  404.37  5000.0  404.37
  5000.5  405.17  5004.2  405.58  5013.5  410.46  5027.2  410.65  5041.4  412.10
  5060.6  417.37  5111.5  421.91  5122.4  423.59  5152.7  424.73  5287.6  432.61
#Mann=4,-1,0
  4579.4    0.05       0  4610.9    0.16       0  4994.5    0.07       0
  5000.5    0.16       0
Bank Sta=4919,5041.4
Exp/Cntr=0.3,0.1

Type RM Length L Ch R = 1,1000,424,424,424
BEGIN DESCRIPTION:
UNT 058 in Running Cr Watershed 2.0
END DESCRIPTION:
XS GIS Cut Line= 3
      2887425.00      7013625.00      2887900.08      7013925.00
      2888075.01      7013925.00
#Sta/Elev= 30
  4520.1  438.50  4531.8  437.37  4621.9  430.60  4643.1  429.80  4650.2  428.54
  4700.7  427.15  4737.2  424.65  4803.9  419.84  4810.1  418.03  4816.0  418.97
  4839.4  417.19  4852.5  411.99  4862.2  410.37  4904.3  408.47  4919.5  409.60
  4983.1  408.90  4992.5  404.92  4995.4  404.79  4995.9  403.99  5000.9  403.99
  5001.4  404.79  5013.7  408.11  5048.9  410.37  5064.1  411.23  5077.2  412.68
  5081.9  414.36  5136.9  419.41  5166.9  424.02  5216.9  429.50  5256.9  432.52
#Mann=4,-1,0
  4520.1    0.05       0  4531.8    0.16       0  4995.4    0.07       0
  5001.4    0.16       0
Bank Sta=4862.2,5048.9
Exp/Cntr=0.3,0.1

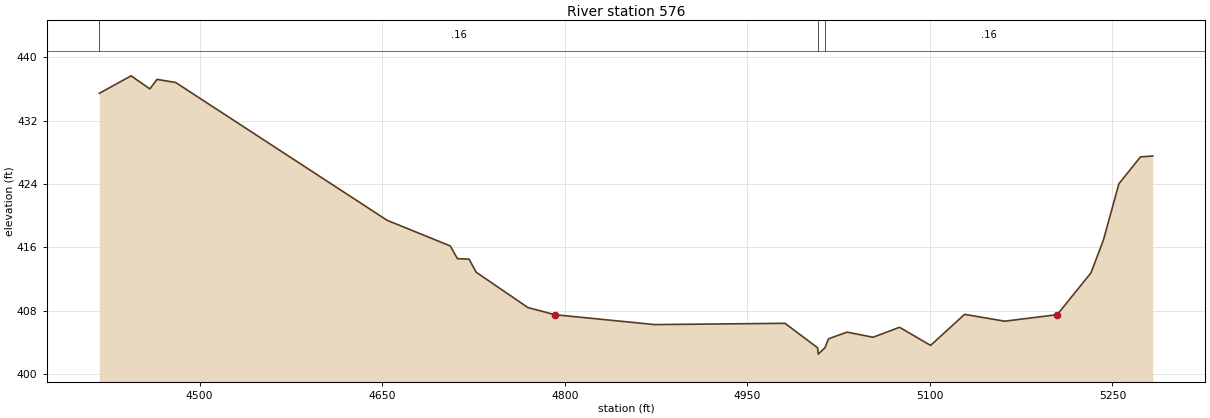
Type RM Length L Ch R = 1,576,0,0,0
BEGIN DESCRIPTION:
UNT 058 in Running Cr Watershed 1.0
END DESCRIPTION:
XS GIS Cut Line= 3
      2887327.15      7013676.34      2887678.17      7014242.20
      2887874.97      7014275.00
#Sta/Elev= 30
  4417.7  435.44  4443.8  437.65  4459.2  436.00  4465.1  437.20  4480.4  436.81
  4654.1  419.41  4706.0  416.17  4711.9  414.56  4721.4  414.51  4727.3  412.85
  4769.8  408.39  4791.9  407.49  4873.8  406.24  4981.0  406.40  5007.8  403.31
  5008.3  402.51  5013.8  403.31  5016.7  404.44  5032.0  405.29  5053.3  404.64
  5075.1  405.90  5100.6  403.61  5128.5  407.53  5161.5  406.67  5204.6  407.49
  5232.4  412.78  5242.6  416.93  5255.3  424.02  5273.0  427.41  5283.1  427.53
#Mann=3,-1,0
  4417.7    0.16       0  5007.8    0.07       0  5013.8    0.16       0
Bank Sta=4791.9,5204.6
Exp/Cntr=0.3,0.1

Chan Stop Cuts=-1