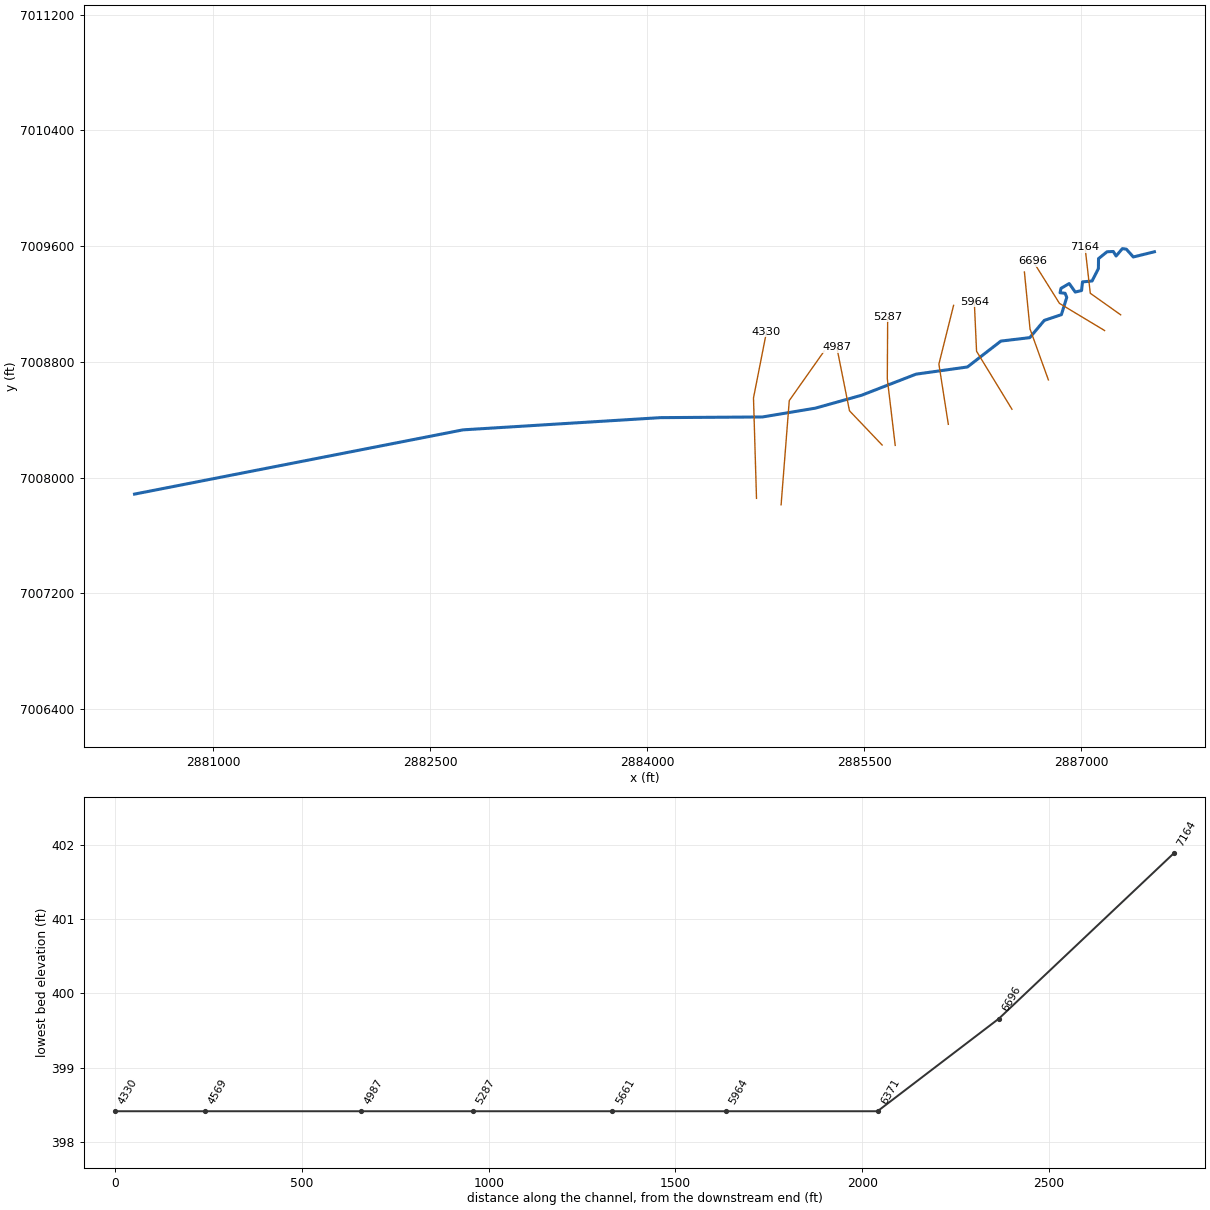
--- UNT 059 in Running Cr Watershed.prj (project) ---

Proj Title=UNT 059 in Running Cr Watershed Base Level Engineering
Current Plan=p01
Default Exp/Contr=0.3,0.1
English Units
Geom File=g01
Flow File=f01
Plan File=p01
BEGIN DESCRIPTION:
UNT 059 in Running Cr Watershed
END DESCRIPTION:

--- UNT 059 in Running Cr Watershed.p01 (plan) ---

Plan Title=Multiple Run
Short Identifier=Multiple
Geom File=g01
Flow File=f01
Subcritical Flow
K Sum by GR= 0
Std Step Tol= 0.01
Critical Tol= 0.01
Num of Std Step Trials= 20
Max Error Tol= 0.3
Flow Tol Ratio= 0.001
Split Flow NTrial= 30
Split Flow Tol= 0.02
Split Flow Ratio= 0.02
Log Output Level= 0
Friction Slope Method= 1
Unsteady Friction Slope Method= 2
Unsteady Bridges Friction Slope Method= 1
Parabolic Critical Depth
Global Vel Dist=  1 , 1 , 1
Global Log Level= 0
CheckData=True
Encroach Param= -1, 0, 0, 0
BEGIN DESCRIPTION:
Multiple Run
END DESCRIPTION:

--- UNT 059 in Running Cr Watershed.f01 (steady flow) ---

Flow Title=Multiple
Number of Profiles=7
Profile Names=10-year,25-year,50-year,1pct_min,100-year,1pct_plu,500-year
River Rch & RM= UNT 059 in Runni,Reach-1,7164
     499     666     803     482     962    1918    1380
River Rch & RM= UNT 059 in Runni,Reach-1,4569
     546     731     881     529    1056    2106    1516
Boundary for River Rch & Prof#=UNT 059 in Runni,Reach-1,1
Up Type=0
Dn Type=3
Dn Slope=0.005
Boundary for River Rch & Prof#=UNT 059 in Runni,Reach-1,2
Up Type=0
Dn Type=3
Dn Slope=0.005
Boundary for River Rch & Prof#=UNT 059 in Runni,Reach-1,3
Up Type=0
Dn Type=3
Dn Slope=0.005
Boundary for River Rch & Prof#=UNT 059 in Runni,Reach-1,4
Up Type=0
Dn Type=3
Dn Slope=0.005
Boundary for River Rch & Prof#=UNT 059 in Runni,Reach-1,5
Up Type=0
Dn Type=3
Dn Slope=0.005
Boundary for River Rch & Prof#=UNT 059 in Runni,Reach-1,6
Up Type=0
Dn Type=3
Dn Slope=0.005
Boundary for River Rch & Prof#=UNT 059 in Runni,Reach-1,7
Up Type=0
Dn Type=3
Dn Slope=0.005

--- UNT 059 in Running Cr Watershed.g01 (geometry) ---

Geom Title=Existing Conditions

River Reach=UNT 059 in Runni,Reach-1
Reach XY= 30
      2887508.22      7009561.09      2887362.34      7009525.09
      2887314.04      7009579.08      2887286.57      7009582.87
      2887242.99      7009531.72      2887224.05      7009562.98
      2887180.48      7009561.09      2887121.75      7009513.73
      2887120.80      7009444.58      2887077.23      7009359.33
      2887010.93      7009352.70      2887004.29      7009293.02
      2886960.72      7009282.60      2886919.05      7009341.33
      2886862.21      7009308.18      2886855.58      7009277.87
      2886890.63      7009274.08      2886902.00      7009245.66
      2886865.05      7009126.31      2886746.65      7009086.53
      2886646.25      7008967.18      2886446.38      7008943.50
      2886215.26      7008764.47      2885859.48      7008714.72
      2885483.71      7008569.11      2885164.31      7008479.87
      2884797.93      7008418.81      2884093.37      7008414.11
      2882726.51      7008329.56      2880455.71      7007885.37

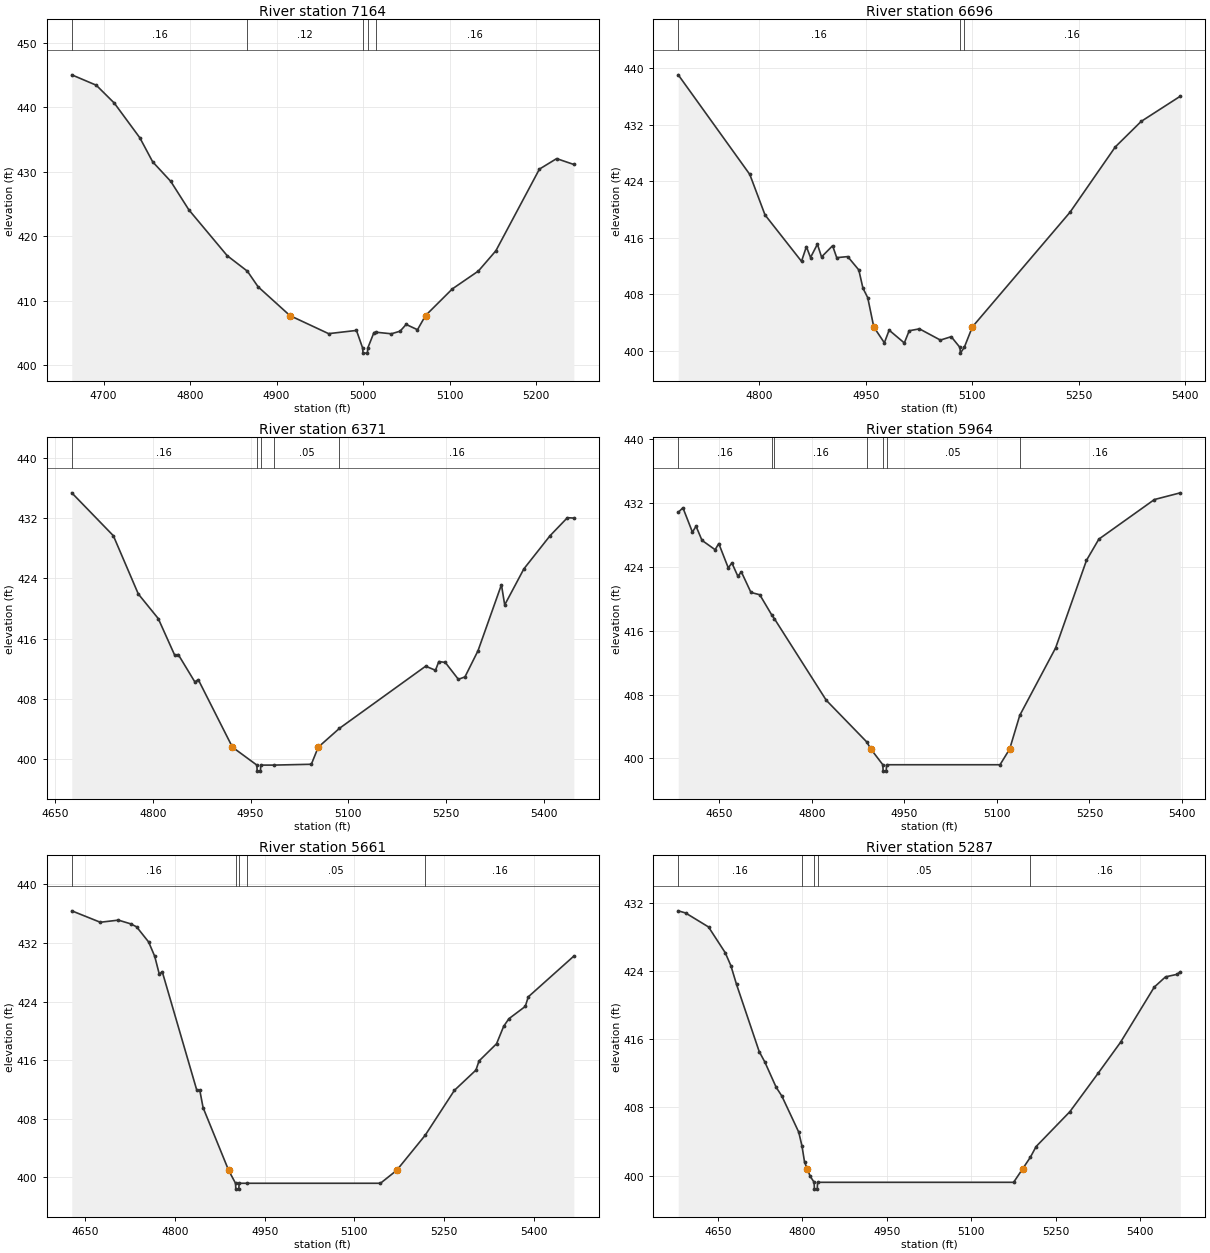
Type RM Length L Ch R = 1,7164,468,468,468
BEGIN DESCRIPTION:
UNT 059 in Running Cr Watershed 10.0
END DESCRIPTION:
XS GIS Cut Line= 3
      2887274.99      7009125.01      2887064.76      7009274.20
      2887028.30      7009594.54
#Sta/Elev= 30
  4663.3  445.04  4691.6  443.43  4712.5  440.65  4742.0  435.27  4756.8  431.55
  4777.7  428.52  4798.6  424.11  4842.9  417.00  4866.2  414.60  4878.6  412.18
  4915.4  407.71  4960.1  404.91  4992.3  405.41  4999.4  402.69  4999.9  401.89
  5004.9  401.89  5005.4  402.69  5012.5  405.08  5015.0  405.13  5032.6  404.89
  5042.7  405.29  5049.7  406.34  5062.8  405.52  5072.1  407.71  5103.1  411.85
  5133.2  414.62  5153.4  417.76  5203.7  430.42  5223.6  432.05  5243.5  431.14
#Mann=5,-1,0
  4663.3    0.16       0  4866.2    0.12       0  4999.4    0.07       0
  5005.4    0.12       0  5015.0    0.16       0
Bank Sta=4915.4,5072.1
Exp/Cntr=0.3,0.1

Type RM Length L Ch R = 1,6696,325,325,325
BEGIN DESCRIPTION:
UNT 059 in Running Cr Watershed 9.0
END DESCRIPTION:
XS GIS Cut Line= 3
      2887163.71      7009016.40      2886851.63      7009204.22
      2886669.47      7009494.68
#Sta/Elev= 30
  4686.0  439.10  4786.8  424.98  4808.2  419.25  4859.6  412.67  4866.5  414.75
  4872.3  413.21  4882.0  415.10  4887.8  413.29  4903.4  414.88  4909.2  413.19
  4924.7  413.34  4940.3  411.45  4946.1  408.88  4952.9  407.51  4961.4  403.37
  4976.3  401.12  4983.0  402.92  5004.4  401.10  5011.3  402.83  5025.7  403.10
  5055.2  401.51  5070.5  401.99  5082.8  400.46  5083.3  399.66  5088.8  400.46
  5100.2  403.37  5237.8  419.63  5301.5  428.88  5338.0  432.50  5393.1  436.07
#Mann=3,-1,0
  4686.0    0.16       0  5082.8    0.07       0  5088.8    0.16       0
Bank Sta=4961.4,5100.2
Exp/Cntr=0.3,0.1

Type RM Length L Ch R = 1,6371,407,407,407
BEGIN DESCRIPTION:
UNT 059 in Running Cr Watershed 8.0
END DESCRIPTION:
XS GIS Cut Line= 3
      2886775.00      7008675.01      2886648.09      7009026.81
      2886609.16      7009421.30
#Sta/Elev= 30
  4675.7  435.33  4739.5  429.64  4777.8  421.91  4808.4  418.65  4833.8  413.76
  4839.1  413.88  4864.5  410.25  4869.8  410.55  4922.2  401.59  4959.7  399.21
  4960.2  398.41  4965.2  398.41  4965.7  399.21  4985.3  399.21  5043.3  399.32
  5053.9  401.59  5086.5  404.09  5218.7  412.33  5233.8  411.79  5238.9  412.95
  5248.8  412.83  5268.9  410.59  5279.0  410.91  5299.1  414.39  5335.0  423.14
  5340.0  420.46  5369.4  425.24  5409.6  429.64  5436.2  432.03  5446.1  431.98
#Mann=5,-1,0
  4675.7    0.16       0  4959.7   0.035       0  4965.7    0.16       0
  4985.3    0.05       0  5086.5    0.16       0
Bank Sta=4922.2,5053.9
Exp/Cntr=0.3,0.1

Type RM Length L Ch R = 1,5964,303,303,303
BEGIN DESCRIPTION:
UNT 059 in Running Cr Watershed 7.0
END DESCRIPTION:
XS GIS Cut Line= 3
      2886523.09      7008472.12      2886278.30      7008873.16
      2886262.67      7009216.96
#Sta/Elev= 30
  4583.3  430.81  4590.9  431.38  4606.3  428.33  4612.2  429.07  4621.8  427.30
  4643.1  426.13  4649.0  426.90  4664.4  423.86  4670.3  424.47  4679.9  422.82
  4685.7  423.34  4701.2  420.78  4715.5  420.49  4735.3  417.91  4739.3  417.48
  4823.2  407.29  4889.1  402.05  4895.6  401.17  4915.0  399.21  4915.5  398.41
  4920.5  398.41  4921.0  399.21  5105.0  399.21  5120.6  401.17  5137.0  405.39
  5195.1  413.83  5245.2  424.80  5265.2  427.45  5355.3  432.41  5397.3  433.25
#Mann=7,-1,0
  4583.3    0.16       0  4735.3    0.05       0  4739.3    0.16       0
  4889.1    0.05       0  4915.0   0.033       0  4921.0    0.05       0
  5137.0    0.16       0
Bank Sta=4895.6,5120.6
Exp/Cntr=0.3,0.1

Type RM Length L Ch R = 1,5661,374,374,374
BEGIN DESCRIPTION:
UNT 059 in Running Cr Watershed 6.0
END DESCRIPTION:
XS GIS Cut Line= 3
      2886083.00      7008367.91      2886017.88      7008784.62
      2886119.34      7009190.46
#Sta/Elev= 30
  4627.3  436.40  4675.0  434.84  4705.3  435.13  4725.6  434.63  4735.7  434.22
  4755.9  432.15  4766.1  430.19  4773.7  427.77  4778.7  428.09  4836.4  411.94
  4841.5  411.91  4847.0  409.54  4889.8  400.97  4901.3  399.21  4901.8  398.41
  4906.8  398.41  4907.3  399.21  4920.8  399.21  5143.8  399.21  5170.9  400.97
  5218.7  405.77  5267.5  411.89  5303.6  414.66  5308.7  415.90  5338.1  418.26
  5350.0  420.64  5358.7  421.67  5386.1  423.35  5391.2  424.66  5467.4  430.22
#Mann=5,-1,0
  4627.3    0.16       0  4901.3   0.033       0  4907.3    0.16       0
  4920.8    0.05       0  5218.7    0.16       0
Bank Sta=4889.8,5170.9
Exp/Cntr=0.3,0.1

Type RM Length L Ch R = 1,5287,300,300,300
BEGIN DESCRIPTION:
UNT 059 in Running Cr Watershed 5.0
END DESCRIPTION:
XS GIS Cut Line= 3
      2885715.81      7008222.07      2885661.11      7008683.06
      2885663.71      7009111.33
#Sta/Elev= 30
  4579.3  431.07  4592.3  430.82  4633.1  429.18  4662.8  426.16  4672.9  424.63
  4682.9  422.44  4723.2  414.56  4733.3  413.32  4753.4  410.36  4763.5  409.33
  4793.5  405.10  4799.3  403.46  4803.8  401.60  4808.7  400.77  4813.9  399.91
  4820.9  399.21  4821.4  398.41  4826.4  398.41  4826.9  399.21  5175.5  399.21
  5191.3  400.77  5205.3  402.16  5215.5  403.41  5275.5  407.50  5325.5  411.99
  5365.5  415.64  5425.5  422.12  5445.5  423.32  5465.5  423.61  5471.8  423.91
#Mann=5,-1,0
  4579.3    0.16       0  4799.3    0.05       0  4820.9   0.033       0
  4826.9    0.05       0  5205.3    0.16       0
Bank Sta=4808.7,5191.3
Exp/Cntr=0.3,0.1

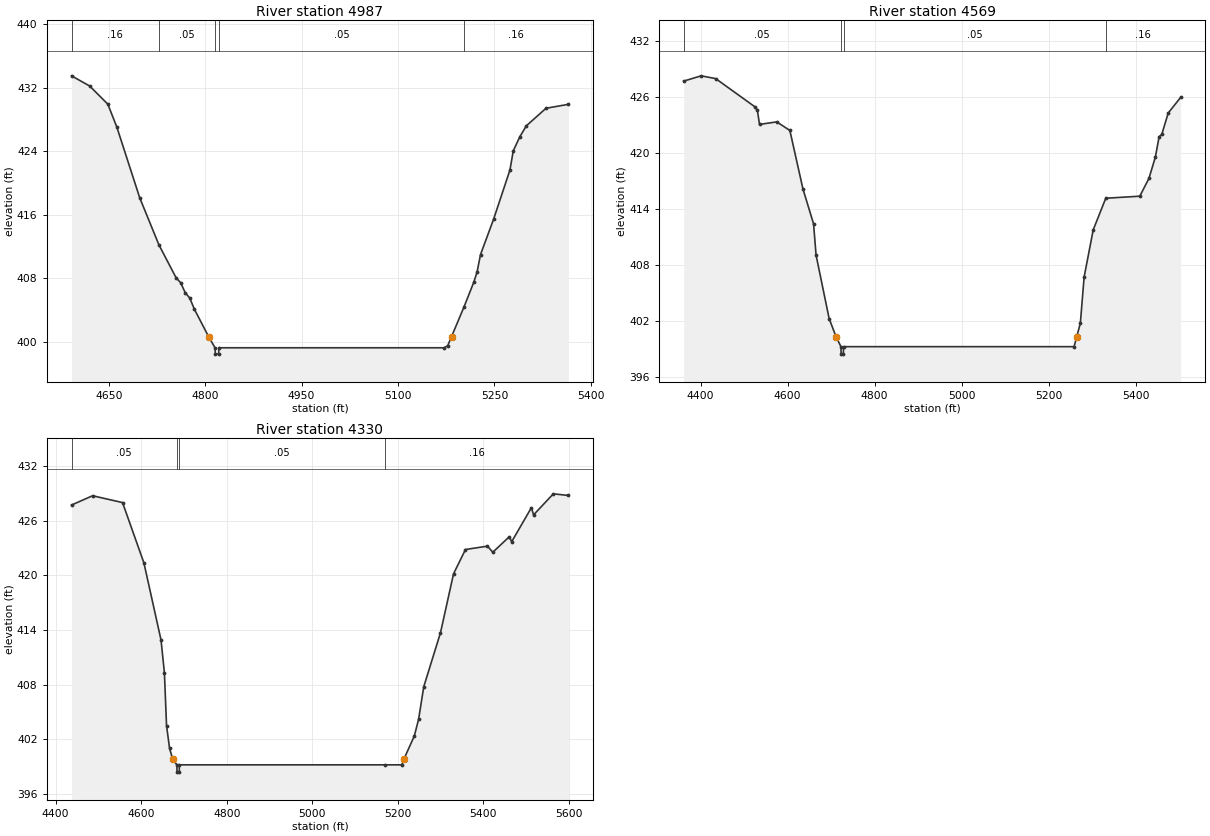
Type RM Length L Ch R = 1,4987,418,418,418
BEGIN DESCRIPTION:
UNT 059 in Running Cr Watershed 4.0
END DESCRIPTION:
XS GIS Cut Line= 3
      2885625.02      7008224.98      2885399.53      7008461.51
      2885312.16      7008899.19
#Sta/Elev= 30
  4592.0  433.48  4620.2  432.20  4648.5  429.91  4662.6  427.00  4698.2  418.09
  4728.1  412.16  4754.8  408.02  4761.7  407.42  4769.0  406.14  4775.9  405.49
  4783.1  404.08  4805.3  400.61  4815.3  399.21  4815.8  398.41  4820.8  398.41
  4821.3  399.21  5172.0  399.21  5177.3  399.48  5183.2  400.61  5202.3  404.29
  5217.9  407.48  5223.0  408.77  5228.3  410.95  5248.7  415.42  5274.1  421.61
  5279.3  424.03  5289.4  425.79  5299.6  427.18  5330.2  429.39  5365.1  429.89
#Mann=5,-1,0
  4592.0    0.16       0  4728.1    0.05       0  4815.3   0.033       0
  4821.3    0.05       0  5202.3    0.16       0
Bank Sta=4805.3,5183.2
Exp/Cntr=0.3,0.1

Type RM Length L Ch R = 1,4569,239,239,239
BEGIN DESCRIPTION:
UNT 059 in Running Cr Watershed 3.0
END DESCRIPTION:
XS GIS Cut Line= 3
      2884926.74      7007811.54      2884983.16      7008532.02
      2885225.03      7008875.04
#Sta/Elev= 30
  4361.0  427.69  4401.2  428.26  4434.7  427.96  4525.0  424.93  4530.4  424.61
  4535.4  423.05  4575.1  423.32  4605.2  422.40  4635.3  416.12  4659.7  412.38
  4665.4  409.04  4695.5  402.22  4711.2  400.30  4722.6  399.21  4723.1  398.41
  4728.1  398.41  4728.6  399.21  5258.6  399.21  5264.8  400.30  5273.0  401.72
  5281.7  406.68  5302.6  411.74  5331.4  415.13  5409.7  415.35  5430.7  417.26
  5445.5  419.55  5454.1  421.73  5460.2  421.98  5475.0  424.27  5503.4  425.94
#Mann=4,-1,0
  4361.0    0.05       0  4722.6   0.033       0  4728.6    0.05       0
  5331.4    0.16       0
Bank Sta=4711.2,5264.8
Exp/Cntr=0.3,0.1

Type RM Length L Ch R = 1,4330,0,0,0
BEGIN DESCRIPTION:
UNT 059 in Running Cr Watershed 2.0
END DESCRIPTION:
XS GIS Cut Line= 3
      2884756.60      7007855.77      2884735.77      7008550.25
      2884826.04      7009008.55
#Sta/Elev= 30
  4437.1  427.72  4486.4  428.74  4556.4  427.99  4606.4  421.37  4646.4  412.91
  4654.3  409.32  4659.3  403.52  4666.4  401.01  4673.5  399.86  4683.4  399.21
  4683.9  398.41  4688.9  398.41  4689.4  399.21  5170.3  399.21  5209.4  399.21
  5214.5  399.86  5238.7  402.38  5248.8  404.24  5260.7  407.78  5299.8  413.70
  5330.4  420.18  5358.3  422.84  5409.7  423.21  5422.1  422.54  5461.0  424.25
  5466.1  423.68  5512.4  427.43  5517.5  426.64  5563.7  428.95  5599.0  428.77
#Mann=4,-1,0
  4437.1    0.05       0  4683.4   0.033       0  4689.4    0.05       0
  5170.3    0.16       0
Bank Sta=4673.5,5214.5
Exp/Cntr=0.3,0.1

Chan Stop Cuts=-1