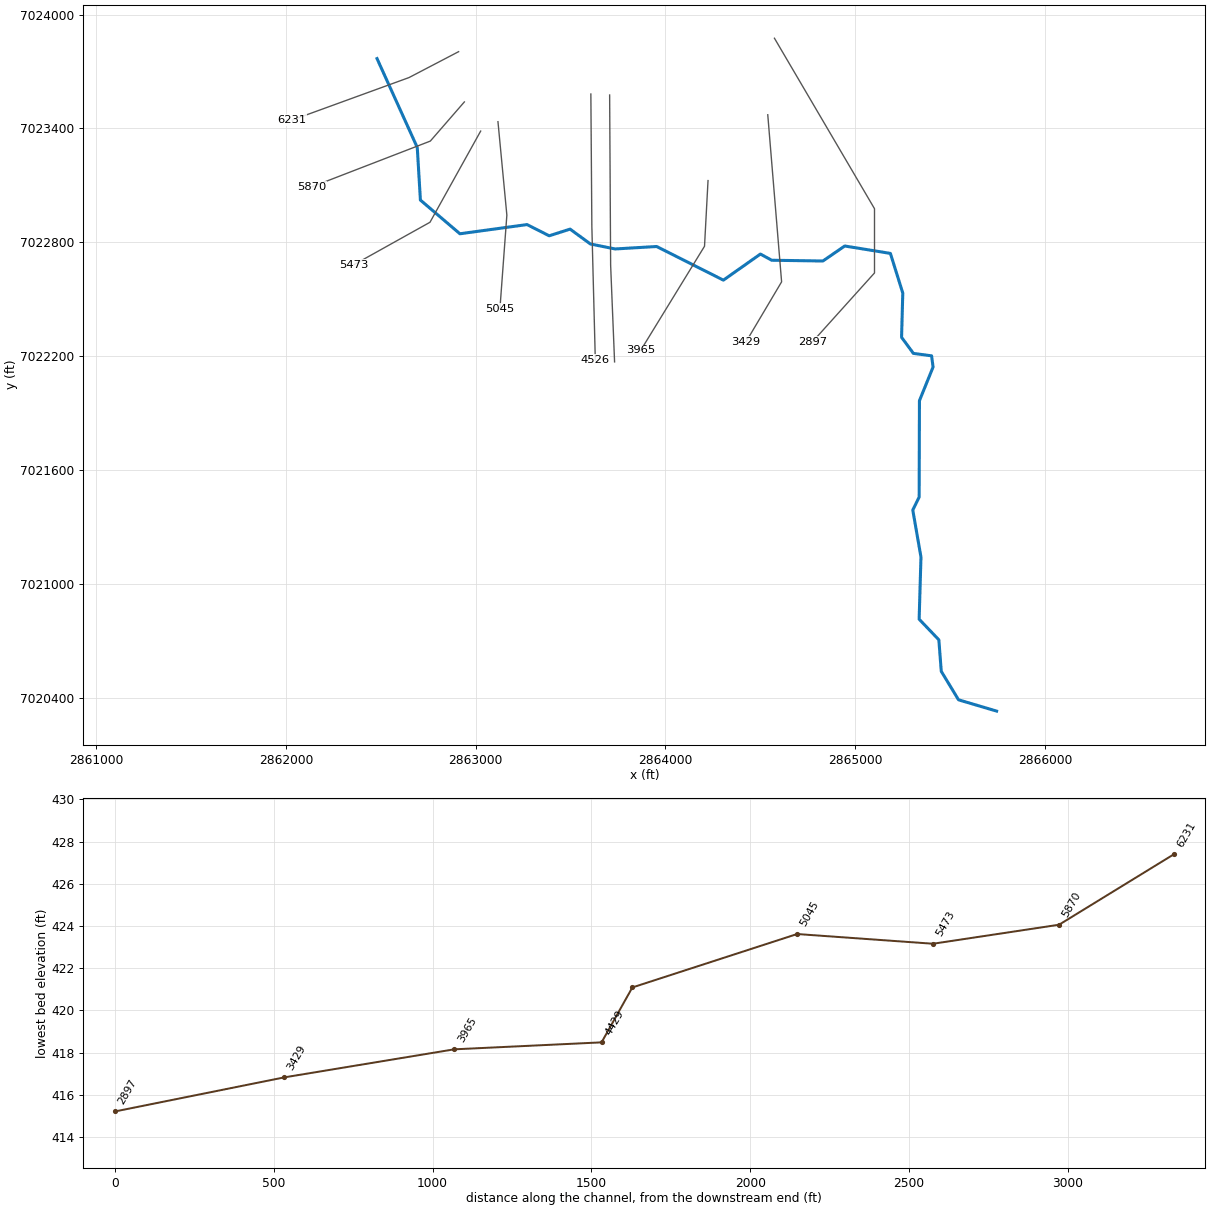
--- UNT 060 in Running Cr Watershed.prj (project) ---

Proj Title=UNT 060 in Running Cr Watershed Base Level Engineering
Current Plan=p01
Default Exp/Contr=0.3,0.1
English Units
Geom File=g01
Flow File=f01
Plan File=p01
BEGIN DESCRIPTION:
UNT 060 in Running Cr Watershed
END DESCRIPTION:

--- UNT 060 in Running Cr Watershed.p01 (plan) ---

Plan Title=Multiple Run
Short Identifier=Multiple
Geom File=g01
Flow File=f01
Subcritical Flow
K Sum by GR= 0
Std Step Tol= 0.01
Critical Tol= 0.01
Num of Std Step Trials= 20
Max Error Tol= 0.3
Flow Tol Ratio= 0.001
Split Flow NTrial= 30
Split Flow Tol= 0.02
Split Flow Ratio= 0.02
Log Output Level= 0
Friction Slope Method= 1
Unsteady Friction Slope Method= 2
Unsteady Bridges Friction Slope Method= 1
Parabolic Critical Depth
Global Vel Dist=  1 , 1 , 1
Global Log Level= 0
CheckData=True
Encroach Param= -1, 0, 0, 0
BEGIN DESCRIPTION:
Multiple Run
END DESCRIPTION:

--- UNT 060 in Running Cr Watershed.f01 (steady flow) ---

Flow Title=Multiple
Number of Profiles=7
Profile Names=10-year,25-year,50-year,1pct_min,100-year,1pct_plu,500-year
River Rch & RM= UNT 060 in Runni,Reach-1,6231
     491     646     771     457     912    1819    1277
River Rch & RM= UNT 060 in Runni,Reach-1,3429
     567     751     899     535    1067    2129    1505
Boundary for River Rch & Prof#=UNT 060 in Runni,Reach-1,1
Up Type=0
Dn Type=3
Dn Slope=0.005
Boundary for River Rch & Prof#=UNT 060 in Runni,Reach-1,2
Up Type=0
Dn Type=3
Dn Slope=0.005
Boundary for River Rch & Prof#=UNT 060 in Runni,Reach-1,3
Up Type=0
Dn Type=3
Dn Slope=0.005
Boundary for River Rch & Prof#=UNT 060 in Runni,Reach-1,4
Up Type=0
Dn Type=3
Dn Slope=0.005
Boundary for River Rch & Prof#=UNT 060 in Runni,Reach-1,5
Up Type=0
Dn Type=3
Dn Slope=0.005
Boundary for River Rch & Prof#=UNT 060 in Runni,Reach-1,6
Up Type=0
Dn Type=3
Dn Slope=0.005
Boundary for River Rch & Prof#=UNT 060 in Runni,Reach-1,7
Up Type=0
Dn Type=3
Dn Slope=0.005

--- UNT 060 in Running Cr Watershed.g01 (geometry) ---

Geom Title=Existing Conditions

River Reach=UNT 060 in Runni,Reach-1
Reach XY= 30
      2862480.55      7023767.76      2862692.67      7023299.48
      2862709.22      7023022.32      2862917.44      7022844.81
      2863271.33      7022893.23      2863387.90      7022834.15
      2863498.08      7022869.28      2863605.07      7022791.03
      2863735.57      7022764.74      2863954.34      7022777.71
      2864305.91      7022600.46      2864501.15      7022737.93
      2864560.66      7022705.30      2864830.51      7022701.32
      2864945.48      7022780.35      2865186.10      7022741.33
      2865251.38      7022532.35      2865245.00      7022299.22
      2865307.27      7022214.58      2865403.08      7022201.81
      2865411.06      7022142.73      2865339.21      7021965.48
      2865337.61      7021457.69      2865304.08      7021389.03
      2865347.19      7021141.52      2865337.61      7020814.18
      2865441.40      7020705.59      2865454.18      7020539.52
      2865545.20      7020389.42      2865745.81      7020330.00

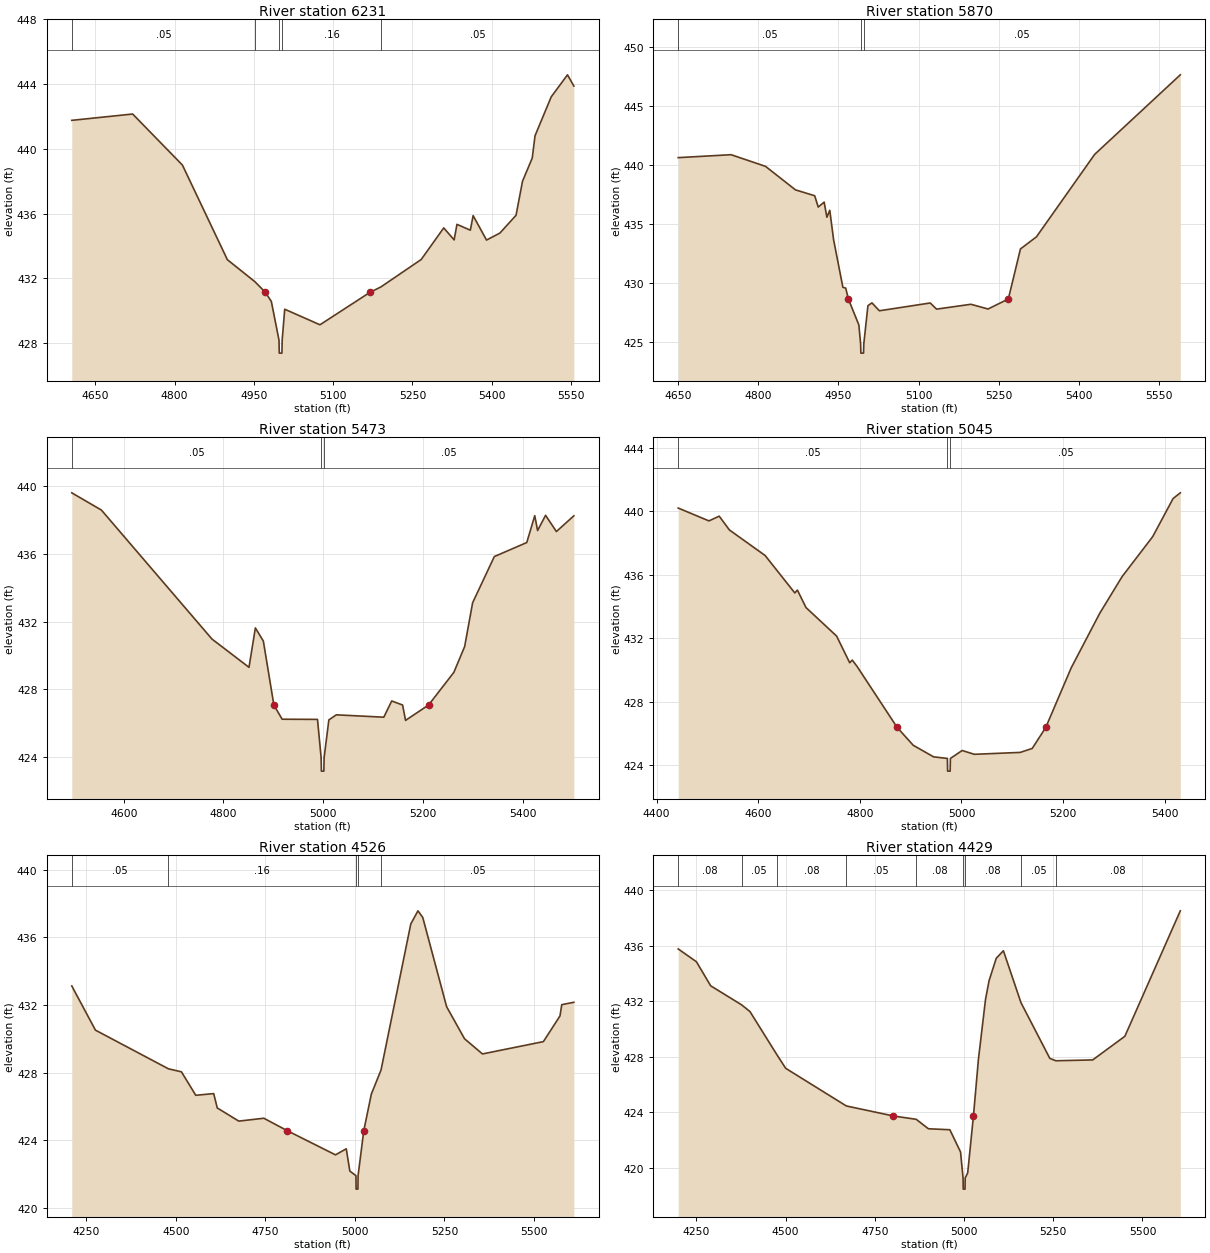
Type RM Length L Ch R = 1,6231,361,361,361
BEGIN DESCRIPTION:
UNT 060 in Running Cr Watershed 9.0
END DESCRIPTION:
XS GIS Cut Line= 3
      2862910.51      7023804.18      2862649.18      7023667.73
      2862033.72      7023443.92
#Sta/Elev= 30
  4605.5  441.76  4720.7  442.15  4814.8  439.00  4899.8  433.16  4951.9  431.80
  4971.8  431.14  4983.0  430.58  4997.5  428.19  4998.0  427.39  5003.0  427.39
  5003.5  428.19  5008.3  430.10  5075.0  429.14  5169.4  431.14  5190.4  431.48
  5266.5  433.17  5309.1  435.12  5328.8  434.38  5334.1  435.34  5359.4  434.98
  5364.7  435.88  5390.0  434.37  5415.3  434.80  5445.9  435.90  5458.1  438.00
  5476.5  439.43  5481.8  440.81  5512.4  443.21  5543.2  444.57  5555.2  443.88
#Mann=5,-1,0
  4605.5    0.05       0  4951.9    0.16       0  4997.5    0.07       0
  5003.5    0.16       0  5190.4    0.05       0
Bank Sta=4971.8,5169.4
Exp/Cntr=0.3,0.1

Type RM Length L Ch R = 1,5870,397,397,397
BEGIN DESCRIPTION:
UNT 060 in Running Cr Watershed 8.0
END DESCRIPTION:
XS GIS Cut Line= 3
      2862940.87      7023539.42      2862761.48      7023333.10
      2862138.96      7023092.77
#Sta/Elev= 30
  4649.8  440.63  4748.8  440.88  4813.4  439.89  4869.4  437.90  4905.5  437.40
  4912.1  436.44  4923.2  436.86  4928.3  435.58  4933.7  436.17  4940.9  433.67
  4958.3  429.64  4963.6  429.57  4968.6  428.65  4988.2  426.45  4991.5  424.86
  4992.0  424.06  4997.0  424.06  4997.5  424.86  5005.2  428.08  5012.8  428.32
  5026.6  427.65  5122.0  428.31  5133.8  427.79  5198.1  428.20  5230.3  427.80
  5268.3  428.65  5291.0  432.89  5321.0  433.92  5430.1  440.91  5590.5  447.65
#Mann=3,-1,0
  4649.8    0.05       0  4991.5    0.03       0  4997.5    0.05       0
Bank Sta=4968.6,5268.3
Exp/Cntr=0.3,0.1

Type RM Length L Ch R = 1,5473,428,428,428
BEGIN DESCRIPTION:
UNT 060 in Running Cr Watershed 7.0
END DESCRIPTION:
XS GIS Cut Line= 3
      2863026.79      7023385.74      2862759.71      7022905.41
      2862360.11      7022682.63
#Sta/Elev= 30
  4495.7  439.62  4555.2  438.60  4777.0  430.97  4851.2  429.30  4864.0  431.63
  4880.0  430.85  4901.1  427.07  4917.7  426.23  4988.6  426.22  4995.9  423.96
  4996.4  423.16  5001.4  423.16  5001.9  423.96  5011.4  426.19  5026.4  426.49
  5121.6  426.35  5137.5  427.31  5159.3  427.07  5165.2  426.16  5211.4  427.07
  5262.1  429.00  5283.8  430.53  5299.8  433.12  5343.3  435.85  5408.4  436.68
  5424.4  438.27  5430.1  437.39  5446.1  438.29  5467.8  437.33  5502.8  438.26
#Mann=3,-1,0
  4495.7    0.05       0  4995.9    0.03       0  5001.9    0.05       0
Bank Sta=4901.1,5211.4
Exp/Cntr=0.3,0.1

Type RM Length L Ch R = 1,5045,519,519,519
BEGIN DESCRIPTION:
UNT 060 in Running Cr Watershed 6.0
END DESCRIPTION:
XS GIS Cut Line= 3
      2863117.95      7023435.27      2863164.83      7022943.06
      2863128.37      7022450.85
#Sta/Elev= 30
  4442.7  440.20  4503.2  439.39  4523.3  439.69  4543.4  438.82  4613.7  437.21
  4672.1  434.85  4677.2  435.03  4694.1  433.93  4754.4  432.13  4780.1  430.45
  4785.1  430.62  4794.6  430.22  4873.6  426.37  4905.1  425.25  4945.2  424.52
  4972.3  424.42  4972.8  423.62  4977.8  423.62  4978.3  424.42  5001.4  424.92
  5025.4  424.68  5115.7  424.80  5139.3  425.05  5165.9  426.37  5216.0  430.13
  5272.2  433.57  5316.2  435.88  5376.4  438.40  5416.5  440.80  5430.7  441.16
#Mann=3,-1,0
  4442.7    0.05       0  4972.3    0.03       0  4978.3    0.05       0
Bank Sta=4873.6,5165.9
Exp/Cntr=0.3,0.1

Type RM Length L Ch R = 1,4526,97,97,97
BEGIN DESCRIPTION:
UNT 060 in Running Cr Watershed 5.0
END DESCRIPTION:
XS GIS Cut Line= 3
      2863607.53      7023581.08      2863612.74      7022883.17
      2863630.97      7022180.04
#Sta/Elev= 30
  4209.9  433.13  4276.0  430.51  4479.6  428.22  4516.0  428.04  4556.0  426.65
  4606.0  426.75  4616.0  425.90  4676.0  425.12  4746.0  425.29  4811.6  424.55
  4946.0  423.12  4976.0  423.48  4986.0  422.16  5003.0  421.89  5003.5  421.09
  5008.5  421.09  5009.0  421.89  5024.9  424.55  5046.0  426.72  5073.1  428.15
  5156.1  436.80  5176.1  437.58  5189.5  437.19  5256.1  431.90  5306.1  430.00
  5356.2  429.10  5526.2  429.83  5572.5  431.35  5577.5  432.02  5611.2  432.16
#Mann=5,-1,0
  4209.9    0.05       0  4479.6    0.16       0  5003.0    0.07       0
  5009.0    0.16       0  5073.1    0.05       0
Bank Sta=4811.6,5024.9
Exp/Cntr=0.3,0.1

Type RM Length L Ch R = 1,4429,464,464,464
BEGIN DESCRIPTION:
UNT 060 in Running Cr Watershed 4.0
END DESCRIPTION:
XS GIS Cut Line= 3
      2863706.49      7023575.86      2863711.70      7022680.04
      2863732.53      7022169.80
#Sta/Elev= 30
  4199.5  435.76  4250.4  434.84  4290.4  433.11  4377.0  431.74  4400.4  431.26
  4474.8  428.20  4500.4  427.18  4670.4  424.47  4802.3  423.75  4866.1  423.51
  4900.4  422.83  4960.4  422.76  4990.4  421.16  4997.4  419.29  4997.9  418.49
  5002.9  418.49  5003.4  419.29  5010.4  419.66  5026.5  423.75  5040.4  427.81
  5060.4  432.15  5070.4  433.49  5090.4  435.09  5110.4  435.63  5159.6  431.90
  5240.5  427.89  5257.4  427.72  5360.6  427.78  5450.7  429.48  5606.0  438.50
#Mann=9,-1,0
  4199.5    0.08       0  4377.0    0.05       0  4474.8    0.08       0
  4670.4    0.05       0  4866.1    0.08       0  4997.4    0.07       0
  5003.4    0.08       0  5159.6    0.05       0  5257.4    0.08       0
Bank Sta=4802.3,5026.5
Exp/Cntr=0.3,0.1

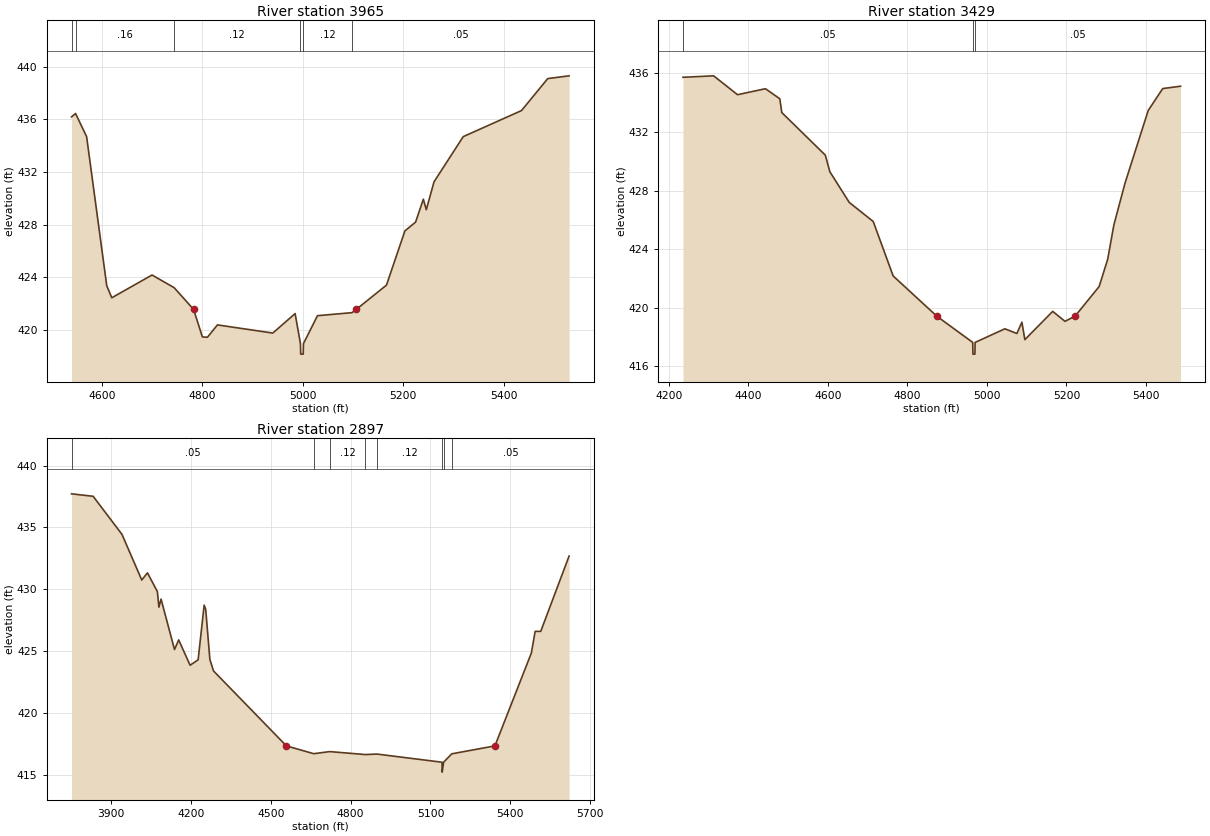
Type RM Length L Ch R = 1,3965,536,536,536
BEGIN DESCRIPTION:
UNT 060 in Running Cr Watershed 3.0
END DESCRIPTION:
XS GIS Cut Line= 3
      2864225.00      7023125.00      2864206.49      7022779.00
      2863869.94      7022230.16
#Sta/Elev= 30
  4539.7  436.18  4547.7  436.44  4569.7  434.68  4609.8  423.35  4619.8  422.44
  4699.9  424.17  4743.9  423.21  4782.6  421.56  4800.1  419.47  4810.1  419.44
  4830.1  420.38  4940.3  419.76  4984.7  421.24  4995.3  418.96  4995.8  418.16
  5000.8  418.16  5001.3  418.96  5029.2  421.08  5097.9  421.31  5106.5  421.56
  5166.5  423.40  5203.2  427.52  5224.5  428.19  5239.9  429.93  5245.8  429.13
  5261.2  431.25  5319.3  434.68  5435.3  436.66  5487.5  439.09  5530.0  439.30
#Mann=6,-1,0
  4539.7     0.1       0  4547.7    0.16       0  4743.9    0.12       0
  4995.3    0.07       0  5001.3    0.12       0  5097.9    0.05       0
Bank Sta=4782.6,5106.5
Exp/Cntr=0.3,0.1

Type RM Length L Ch R = 1,3429,532,532,532
BEGIN DESCRIPTION:
UNT 060 in Running Cr Watershed 2.0
END DESCRIPTION:
XS GIS Cut Line= 3
      2864539.82      7023471.73      2864612.74      7022591.50
      2864425.02      7022275.04
#Sta/Elev= 30
  4235.7  435.74  4312.7  435.84  4372.9  434.55  4443.1  434.96  4479.2  434.27
  4484.2  433.33  4593.7  430.42  4605.0  429.29  4653.9  427.19  4714.1  425.89
  4764.2  422.17  4874.1  419.42  4964.3  417.63  4964.8  416.83  4969.8  416.83
  4970.3  417.63  5045.2  418.56  5075.3  418.24  5088.0  419.01  5095.4  417.82
  5165.4  419.75  5196.3  419.07  5221.6  419.42  5282.3  421.45  5303.7  423.31
  5319.3  425.66  5347.4  428.52  5405.6  433.47  5442.1  434.97  5486.9  435.13
#Mann=3,-1,0
  4235.7    0.05       0  4964.3    0.03       0  4970.3    0.05       0
Bank Sta=4874.1,5221.6
Exp/Cntr=0.3,0.1

Type RM Length L Ch R = 1,2897,0,0,0
BEGIN DESCRIPTION:
UNT 060 in Running Cr Watershed 1.0
END DESCRIPTION:
XS GIS Cut Line= 4
      2864575.00      7023875.00      2865102.33      7022976.92
      2865102.33      7022638.37      2864774.97      7022274.97
#Sta/Elev= 30
  3751.7  437.72  3832.9  437.52  3941.2  434.44  4015.5  430.75  4036.9  431.33
  4074.1  429.82  4079.9  428.56  4088.0  429.21  4138.5  425.13  4154.2  425.91
  4197.1  423.86  4227.2  424.30  4249.9  428.72  4255.7  428.38  4271.4  424.33
  4285.1  423.40  4558.9  417.34  4661.7  416.71  4721.3  416.88  4855.3  416.64
  4899.3  416.68  5143.5  416.02  5144.0  415.22  5149.5  416.02  5180.0  416.70
  5342.2  417.34  5479.1  424.85  5493.3  426.60  5514.3  426.60  5620.8  432.69
#Mann=8,-1,0
  3751.7    0.05       0  4661.7    0.07       0  4721.3    0.12       0
  4855.3    0.07       0  4899.3    0.12       0  5143.5    0.07       0
  5149.5    0.12       0  5180.0    0.05       0
Bank Sta=4558.9,5342.2
Exp/Cntr=0.3,0.1

Chan Stop Cuts=-1