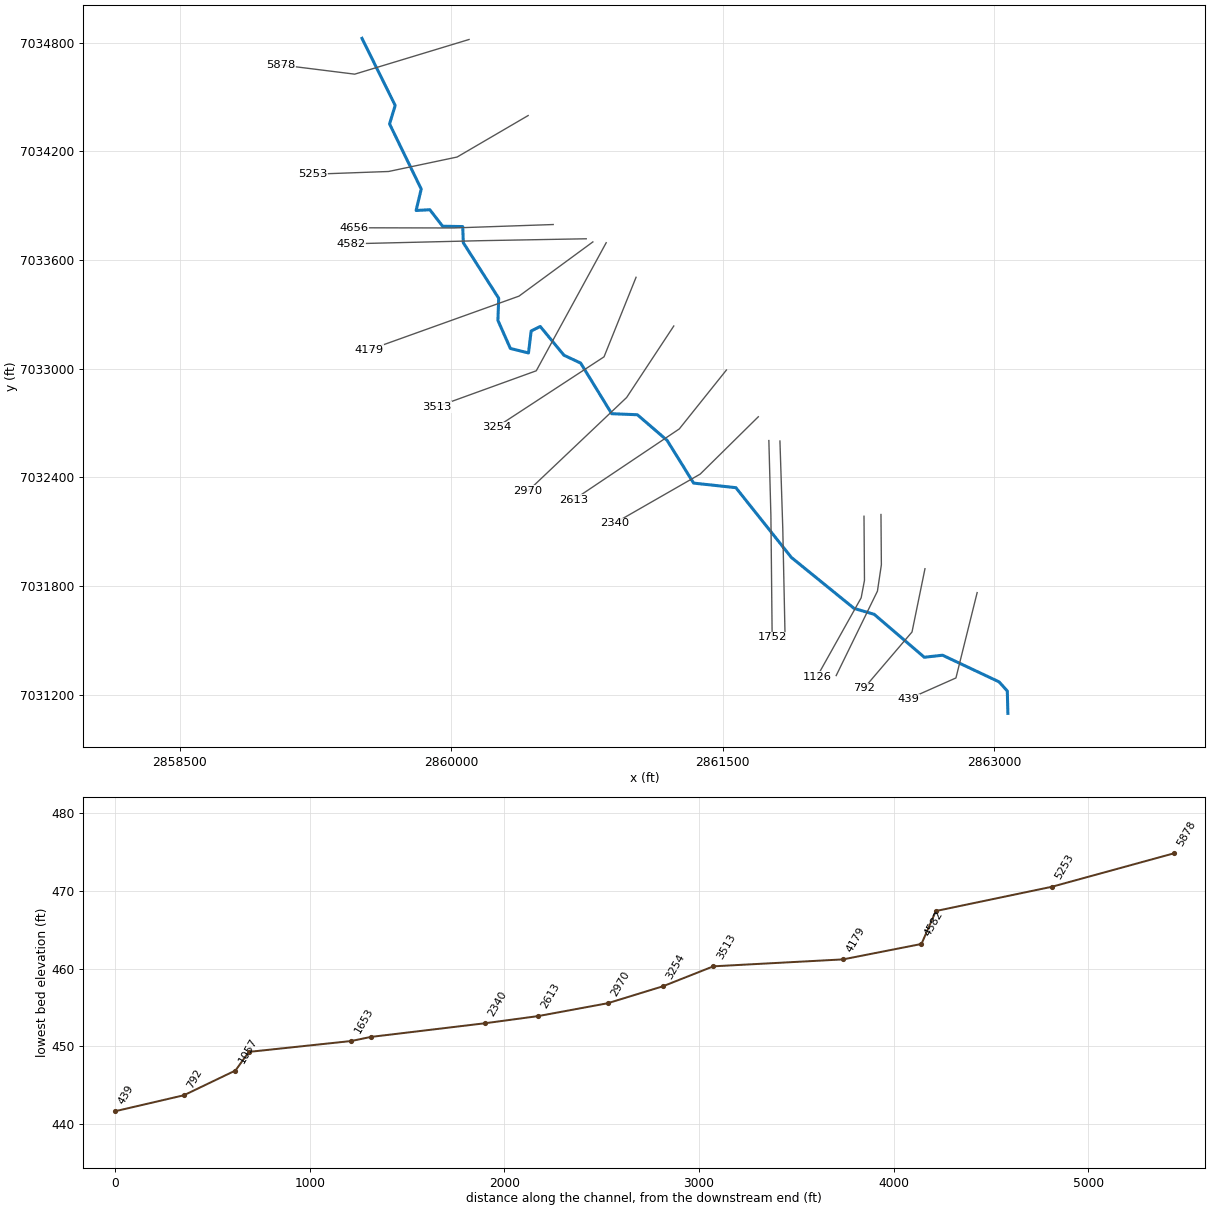
--- UNT 061 in Running Cr Watershed.prj (project) ---

Proj Title=UNT 061 in Running Cr Watershed Base Level Engineering
Current Plan=p01
Default Exp/Contr=0.3,0.1
English Units
Geom File=g01
Flow File=f01
Plan File=p01
BEGIN DESCRIPTION:
UNT 061 in Running Cr Watershed
END DESCRIPTION:

--- UNT 061 in Running Cr Watershed.p01 (plan) ---

Plan Title=Multiple Run
Short Identifier=Multiple
Geom File=g01
Flow File=f01
Subcritical Flow
K Sum by GR= 0
Std Step Tol= 0.01
Critical Tol= 0.01
Num of Std Step Trials= 20
Max Error Tol= 0.3
Flow Tol Ratio= 0.001
Split Flow NTrial= 30
Split Flow Tol= 0.02
Split Flow Ratio= 0.02
Log Output Level= 0
Friction Slope Method= 1
Unsteady Friction Slope Method= 2
Unsteady Bridges Friction Slope Method= 1
Parabolic Critical Depth
Global Vel Dist=  1 , 1 , 1
Global Log Level= 0
CheckData=True
Encroach Param= -1, 0, 0, 0
BEGIN DESCRIPTION:
Multiple Run
END DESCRIPTION:

--- UNT 061 in Running Cr Watershed.f01 (steady flow) ---

Flow Title=Multiple
Number of Profiles=7
Profile Names=10-year,25-year,50-year,1pct_min,100-year,1pct_plu,500-year
River Rch & RM= UNT 061 in Runni,Reach-1,5878
     391     510     604     356     711    1418     985
Boundary for River Rch & Prof#=UNT 061 in Runni,Reach-1,1
Up Type=0
Dn Type=3
Dn Slope=0.005
Boundary for River Rch & Prof#=UNT 061 in Runni,Reach-1,2
Up Type=0
Dn Type=3
Dn Slope=0.005
Boundary for River Rch & Prof#=UNT 061 in Runni,Reach-1,3
Up Type=0
Dn Type=3
Dn Slope=0.005
Boundary for River Rch & Prof#=UNT 061 in Runni,Reach-1,4
Up Type=0
Dn Type=3
Dn Slope=0.005
Boundary for River Rch & Prof#=UNT 061 in Runni,Reach-1,5
Up Type=0
Dn Type=3
Dn Slope=0.005
Boundary for River Rch & Prof#=UNT 061 in Runni,Reach-1,6
Up Type=0
Dn Type=3
Dn Slope=0.005
Boundary for River Rch & Prof#=UNT 061 in Runni,Reach-1,7
Up Type=0
Dn Type=3
Dn Slope=0.005

--- UNT 061 in Running Cr Watershed.g01 (geometry) ---

Geom Title=Existing Conditions

River Reach=UNT 061 in Runni,Reach-1
Reach XY= 30
      2859507.03      7034824.68      2859690.52      7034453.90
      2859659.31      7034352.09      2859834.30      7033992.08
      2859806.02      7033873.89      2859881.78      7033877.93
      2859952.58      7033786.69      2860063.61      7033785.00
      2860066.62      7033695.65      2860262.12      7033389.17
      2860257.86      7033266.76      2860326.67      7033111.64
      2860426.77      7033086.86      2860441.58      7033208.23
      2860491.68      7033233.12      2860622.47      7033074.39
      2860715.02      7033030.79      2860886.30      7032751.35
      2861028.09      7032745.53      2861192.41      7032604.14
      2861338.90      7032367.92      2861572.34      7032342.65
      2861878.85      7031957.26      2862225.62      7031675.52
      2862336.02      7031643.30      2862613.19      7031405.96
      2862713.96      7031417.24      2863026.38      7031269.95
      2863071.62      7031219.51      2863074.75      7031096.00

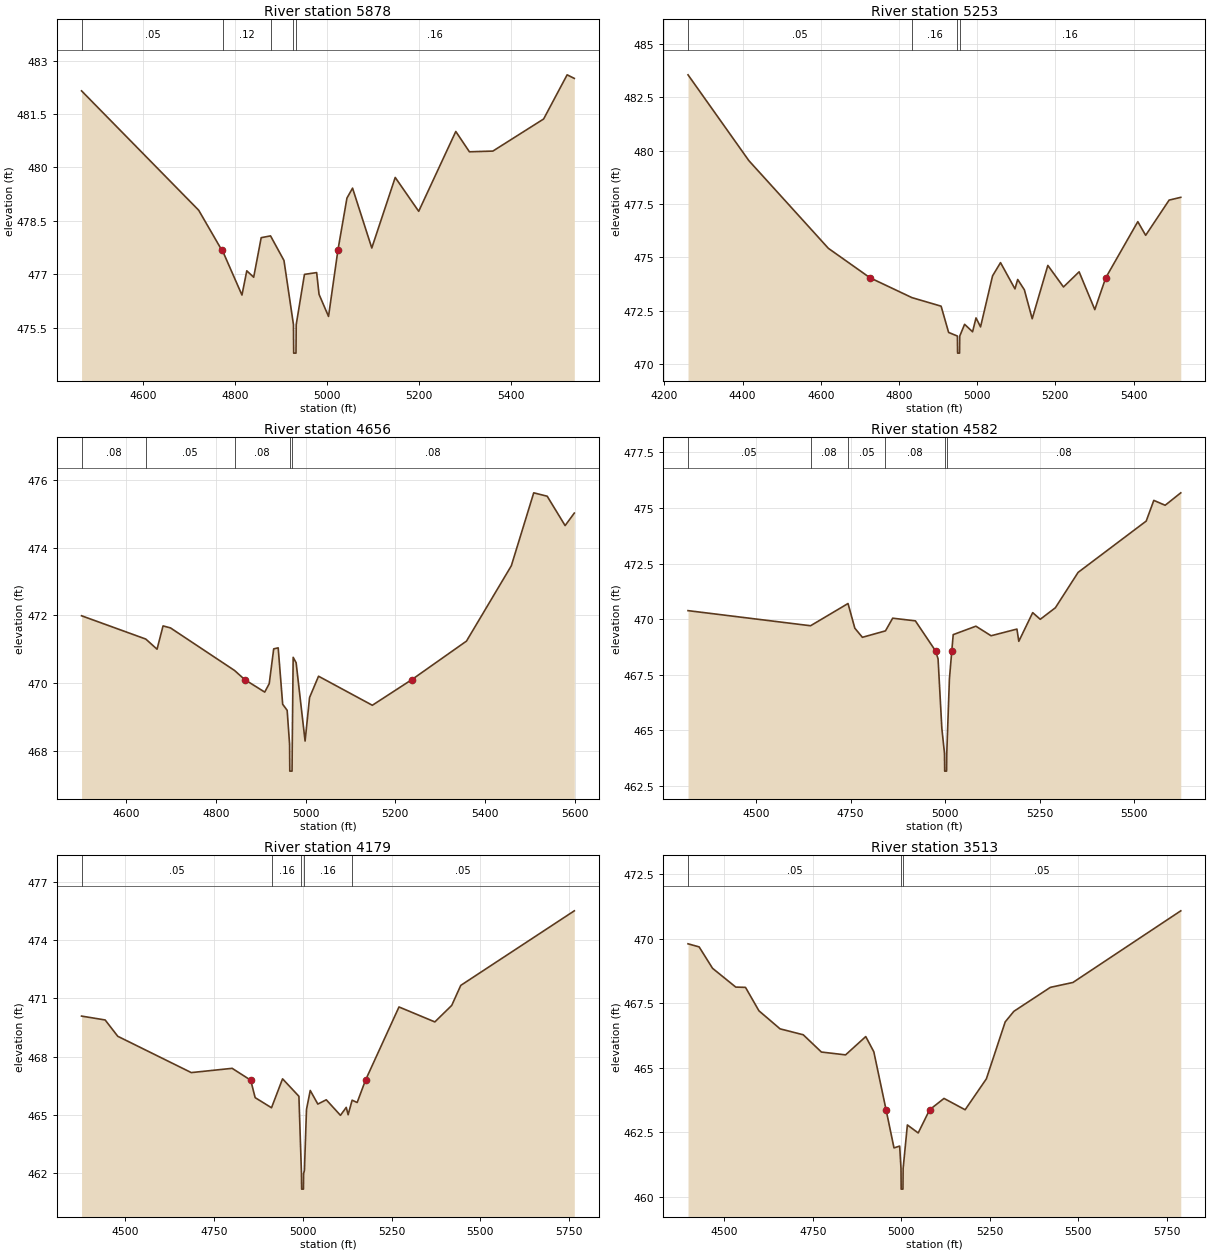
Type RM Length L Ch R = 1,5878,625,625,625
BEGIN DESCRIPTION:
UNT 061 in Running Cr Watershed 14.0
END DESCRIPTION:
XS GIS Cut Line= 3
      2860098.50      7034818.35      2859466.92      7034626.79
      2859059.48      7034677.72
#Sta/Elev= 30
  4467.0  482.15  4721.5  478.80  4771.7  477.68  4774.8  477.62  4815.5  476.42
  4826.0  477.10  4841.0  476.92  4857.3  478.03  4877.6  478.08  4906.8  477.39
  4927.4  475.59  4927.9  474.79  4932.9  474.79  4933.4  475.59  4951.3  477.00
  4977.8  477.05  4983.0  476.44  5003.6  475.82  5024.0  477.68  5043.6  479.14
  5055.8  479.42  5097.6  477.74  5148.5  479.72  5199.5  478.77  5280.1  481.01
  5309.7  480.44  5360.7  480.46  5470.9  481.36  5522.0  482.60  5537.6  482.50
#Mann=5,-1,0
  4467.0    0.05       0  4774.8    0.12       0  4877.6    0.16       0
  4927.4    0.07       0  4933.4    0.16       0
Bank Sta=4771.7,5024
Exp/Cntr=0.3,0.1

Type RM Length L Ch R = 1,5253,597,597,597
BEGIN DESCRIPTION:
UNT 061 in Running Cr Watershed 13.0
END DESCRIPTION:
XS GIS Cut Line= 4
      2860424.88      7034398.20      2860032.53      7034169.05
      2859654.06      7034089.18      2859235.21      7034073.99
#Sta/Elev= 30
  4260.6  483.55  4416.2  479.53  4619.6  475.42  4726.1  474.04  4833.4  473.11
  4907.9  472.71  4927.1  471.48  4949.6  471.31  4950.1  470.51  4955.1  470.51
  4955.6  471.31  4968.0  471.86  4988.4  471.51  4997.2  472.16  5008.8  471.74
  5039.5  474.13  5059.9  474.75  5096.8  473.52  5103.8  473.96  5120.8  473.48
  5140.9  472.12  5180.9  474.62  5220.9  473.61  5260.9  474.32  5301.0  472.55
  5329.0  474.04  5411.0  476.67  5431.1  476.03  5491.1  477.68  5520.9  477.81
#Mann=4,-1,0
  4260.6    0.05       0  4833.4    0.16       0  4949.6    0.07       0
  4955.6    0.16       0
Bank Sta=4726.1,5329
Exp/Cntr=0.3,0.1

Type RM Length L Ch R = 1,4656,74,74,74
BEGIN DESCRIPTION:
UNT 061 in Running Cr Watershed 12.0
END DESCRIPTION:
XS GIS Cut Line= 3
      2860563.31      7033796.21      2860013.52      7033777.25
      2859464.54      7033778.29
#Sta/Elev= 30
  4500.2  471.99  4643.5  471.30  4668.6  471.00  4682.0  471.69  4698.6  471.63
  4841.5  470.37  4864.2  470.10  4908.8  469.73  4918.8  469.98  4928.8  471.01
  4938.8  471.04  4948.8  469.37  4958.8  469.19  4964.2  468.19  4964.7  467.39
  4969.7  467.39  4970.2  468.19  4972.2  470.76  4978.8  470.60  4998.8  468.28
  5008.8  469.57  5028.8  470.20  5148.8  469.34  5237.0  470.10  5358.8  471.24
  5458.8  473.47  5508.8  475.63  5538.8  475.53  5578.8  474.66  5599.3  475.03
#Mann=5,-1,0
  4500.2    0.08       0  4643.5    0.05       0  4841.5    0.08       0
  4964.2    0.07       0  4970.2    0.08       0
Bank Sta=4864.2,5237
Exp/Cntr=0.3,0.1

Type RM Length L Ch R = 1,4582,403,403,403
BEGIN DESCRIPTION:
UNT 061 in Running Cr Watershed 11.0
END DESCRIPTION:
XS GIS Cut Line= 3
      2860745.79      7033717.53      2860171.16      7033707.11
      2859443.69      7033689.75
#Sta/Elev= 30
  4320.4  470.38  4644.3  469.70  4743.3  470.70  4761.3  469.59  4781.3  469.18
  4842.3  469.47  4861.3  470.04  4921.3  469.92  4974.6  468.57  4981.3  468.21
  4991.3  465.08  4998.3  463.96  4998.8  463.16  5003.8  463.16  5004.3  463.96
  5011.3  467.31  5017.6  468.57  5021.3  469.30  5081.3  469.68  5121.4  469.25
  5189.7  469.55  5194.7  469.00  5231.4  470.29  5251.4  469.99  5291.4  470.51
  5351.4  472.10  5531.5  474.41  5551.5  475.34  5581.5  475.12  5622.8  475.68
#Mann=6,-1,0
  4320.4    0.05       0  4644.3    0.08       0  4743.3    0.05       0
  4842.3    0.08       0  4998.3    0.07       0  5004.3    0.08       0
Bank Sta=4974.6,5017.6
Exp/Cntr=0.3,0.1

Type RM Length L Ch R = 1,4179,666,666,666
BEGIN DESCRIPTION:
UNT 061 in Running Cr Watershed 10.0
END DESCRIPTION:
XS GIS Cut Line= 3
      2860782.31      7033700.19      2860374.29      7033400.69
      2859545.64      7033103.44
#Sta/Elev= 30
  4377.7  470.09  4444.1  469.89  4479.6  469.05  4686.5  467.18  4801.4  467.40
  4853.6  466.79  4866.2  465.89  4912.2  465.37  4943.3  466.86  4989.3  465.96
  4996.5  461.98  4997.0  461.18  5002.0  461.18  5002.5  461.98  5004.8  462.14
  5010.6  465.28  5021.2  466.26  5042.5  465.56  5066.3  465.78  5106.2  464.98
  5122.5  465.39  5127.8  465.01  5139.0  465.76  5153.2  465.64  5176.7  466.79
  5270.9  470.56  5371.8  469.79  5419.3  470.64  5444.7  471.67  5764.2  475.51
#Mann=5,-1,0
  4377.7    0.05       0  4912.2    0.16       0  4996.5    0.07       0
  5002.5    0.16       0  5139.0    0.05       0
Bank Sta=4853.6,5176.7
Exp/Cntr=0.3,0.1

Type RM Length L Ch R = 1,3513,259,259,259
BEGIN DESCRIPTION:
UNT 061 in Running Cr Watershed 9.0
END DESCRIPTION:
XS GIS Cut Line= 3
      2860856.05      7033695.81      2860469.77      7032988.36
      2859918.55      7032788.70
#Sta/Elev= 30
  4397.1  469.81  4428.5  469.69  4466.4  468.86  4532.0  468.13  4559.5  468.12
  4597.5  467.21  4657.2  466.51  4722.7  466.28  4774.0  465.61  4842.3  465.50
  4899.3  466.21  4922.1  465.62  4956.7  463.37  4979.1  461.89  4995.1  461.96
  4998.9  461.09  4999.4  460.29  5004.4  460.29  5004.9  461.09  5016.9  462.78
  5047.5  462.47  5079.8  463.37  5120.4  463.81  5180.1  463.37  5240.1  464.57
  5293.3  466.78  5317.8  467.19  5420.9  468.12  5484.7  468.31  5789.4  471.09
#Mann=3,-1,0
  4397.1    0.05       0  4998.9    0.03       0  5004.9    0.05       0
Bank Sta=4956.7,5079.8
Exp/Cntr=0.3,0.1

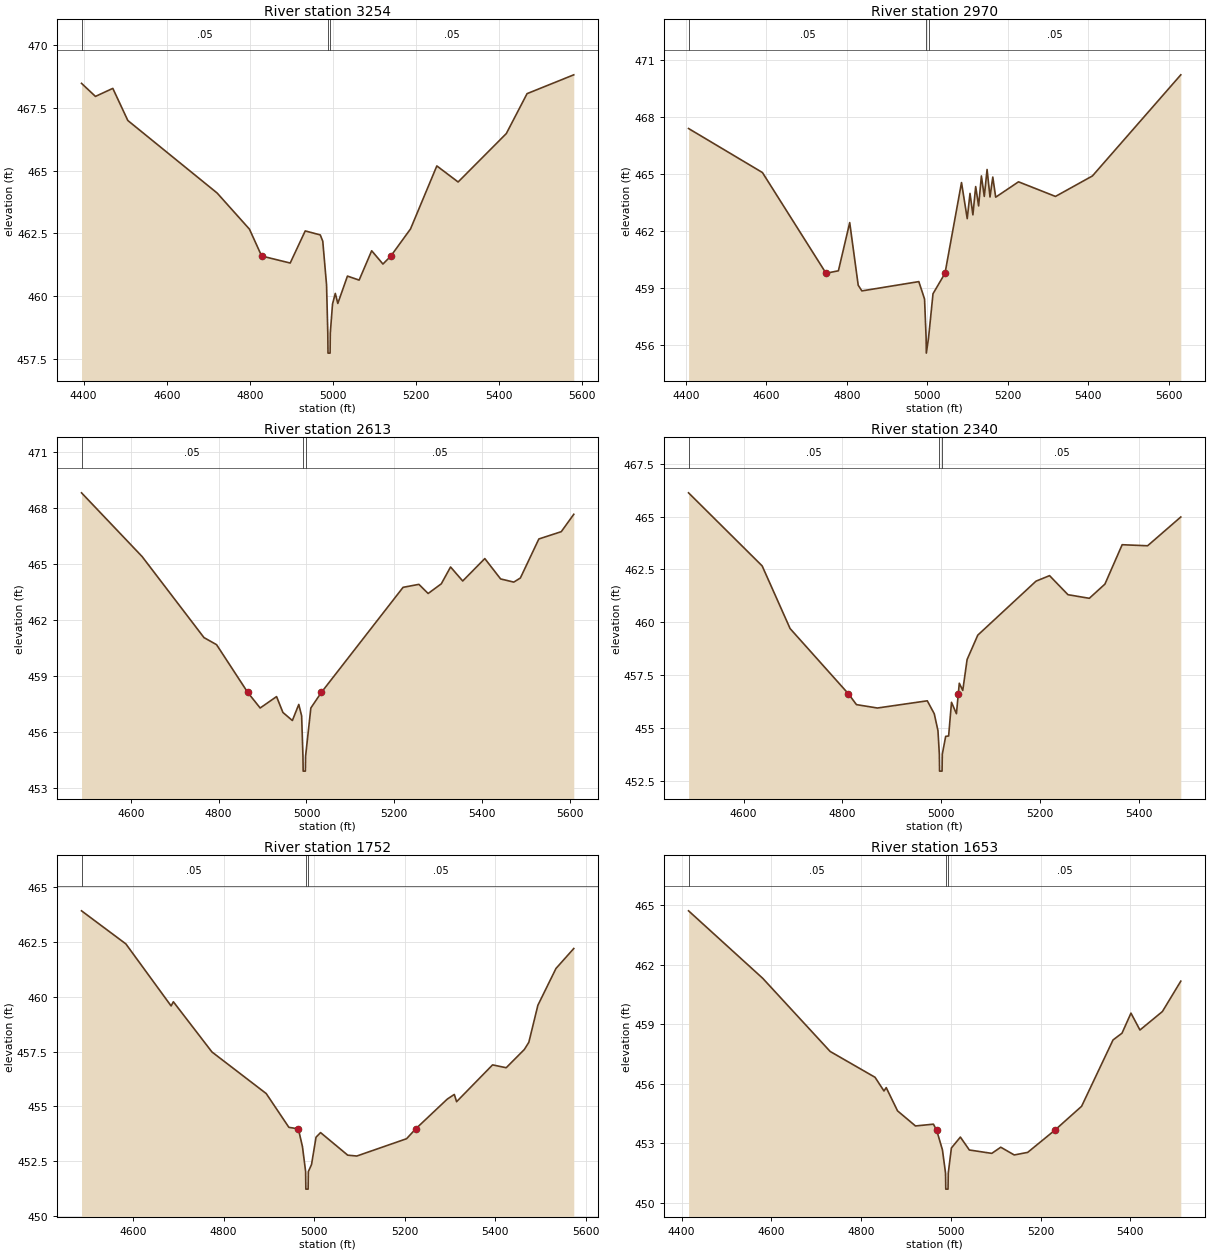
Type RM Length L Ch R = 1,3254,284,284,284
BEGIN DESCRIPTION:
UNT 061 in Running Cr Watershed 8.0
END DESCRIPTION:
XS GIS Cut Line= 3
      2861020.98      7033504.83      2860844.02      7033065.34
      2860249.19      7032676.36
#Sta/Elev= 30
  4395.0  468.48  4428.5  467.96  4470.3  468.28  4506.4  467.00  4721.3  464.11
  4799.1  462.67  4828.4  461.60  4897.1  461.32  4933.3  462.60  4969.5  462.44
  4975.5  462.19  4984.6  460.45  4987.6  458.53  4988.1  457.73  4993.1  457.73
  4993.6  458.53  4999.0  459.69  5005.7  460.11  5011.7  459.71  5034.9  460.80
  5063.0  460.64  5093.2  461.81  5120.3  461.28  5139.4  461.60  5186.7  462.68
  5250.0  465.19  5301.2  464.55  5417.2  466.48  5467.1  468.07  5579.5  468.82
#Mann=3,-1,0
  4395.0    0.05       0  4987.6    0.03       0  4993.6    0.05       0
Bank Sta=4828.4,5139.4
Exp/Cntr=0.3,0.1

Type RM Length L Ch R = 1,2970,357,357,357
BEGIN DESCRIPTION:
UNT 061 in Running Cr Watershed 7.0
END DESCRIPTION:
XS GIS Cut Line= 3
      2861229.33      7033235.76      2860968.90      7032840.79
      2860424.99      7032324.99
#Sta/Elev= 30
  4407.1  467.39  4590.6  465.07  4748.6  459.76  4779.3  459.89  4807.4  462.43
  4828.5  459.13  4837.6  458.83  4979.1  459.32  4993.3  458.40  4997.2  456.35
  4997.7  455.55  5003.2  456.35  5014.3  458.68  5044.1  459.76  5085.1  464.54
  5099.3  462.64  5106.2  463.97  5113.4  462.84  5120.3  464.33  5127.6  463.31
  5134.5  464.89  5141.7  463.81  5148.6  465.23  5155.9  463.78  5162.8  464.83
  5170.0  463.77  5226.7  464.58  5318.5  463.81  5410.3  464.89  5629.8  470.22
#Mann=3,-1,0
  4407.1    0.05       0  4997.2    0.03       0  5003.2    0.05       0
Bank Sta=4748.6,5044.1
Exp/Cntr=0.3,0.1

Type RM Length L Ch R = 1,2613,273,273,273
BEGIN DESCRIPTION:
UNT 061 in Running Cr Watershed 6.0
END DESCRIPTION:
XS GIS Cut Line= 3
      2861520.10      7032992.68      2861259.70      7032667.18
      2860674.99      7032274.99
#Sta/Elev= 30
  4487.8  468.80  4625.7  465.39  4766.6  461.05  4795.3  460.67  4866.4  458.11
  4894.6  457.28  4931.9  457.89  4946.4  457.04  4967.9  456.61  4982.5  457.47
  4989.0  456.86  4992.0  454.70  4992.5  453.90  4997.5  453.90  4998.0  454.70
  5010.0  457.28  5033.8  458.11  5220.0  463.74  5256.0  463.90  5277.1  463.41
  5307.1  463.93  5328.1  464.83  5355.8  464.08  5406.1  465.28  5442.1  464.19
  5472.1  464.02  5487.1  464.24  5529.2  466.33  5580.2  466.72  5608.7  467.65
#Mann=3,-1,0
  4487.8    0.05       0  4992.0    0.03       0  4998.0    0.05       0
Bank Sta=4866.4,5033.8
Exp/Cntr=0.3,0.1

Type RM Length L Ch R = 1,2340,588,588,588
BEGIN DESCRIPTION:
UNT 061 in Running Cr Watershed 5.0
END DESCRIPTION:
XS GIS Cut Line= 3
      2861696.31      7032734.43      2861375.15      7032417.61
      2860902.04      7032146.33
#Sta/Elev= 30
  4488.6  466.12  4637.6  462.67  4694.2  459.71  4811.9  456.64  4828.5  456.12
  4870.9  455.96  4971.9  456.30  4986.0  455.69  4993.5  454.89  4996.3  453.78
  4996.8  452.98  5001.8  452.98  5002.3  453.78  5009.1  454.62  5015.1  454.64
  5020.9  456.23  5030.9  455.69  5034.7  456.64  5036.7  457.13  5043.7  456.79
  5052.5  458.25  5074.1  459.40  5192.0  461.95  5219.4  462.21  5256.7  461.31
  5299.9  461.14  5331.5  461.81  5366.4  463.67  5417.9  463.62  5485.1  464.98
#Mann=3,-1,0
  4488.6    0.05       0  4996.3    0.03       0  5002.3    0.05       0
Bank Sta=4811.9,5034.7
Exp/Cntr=0.3,0.1

Type RM Length L Ch R = 1,1752,99,99,99
BEGIN DESCRIPTION:
UNT 061 in Running Cr Watershed 4.0
END DESCRIPTION:
XS GIS Cut Line= 3
      2861754.49      7032602.97      2861765.78      7032187.58
      2861772.72      7031515.66
#Sta/Elev= 30
  4486.1  463.92  4584.1  462.41  4684.0  459.58  4689.0  459.77  4774.2  457.48
  4894.2  455.58  4944.2  454.04  4965.1  453.97  4974.2  453.16  4981.2  452.02
  4981.7  451.22  4986.7  451.22  4987.2  452.02  4994.2  452.34  5004.2  453.59
  5014.2  453.80  5074.2  452.77  5094.2  452.73  5204.2  453.52  5224.4  453.97
  5294.2  455.33  5309.7  455.54  5314.7  455.21  5394.2  456.89  5424.3  456.76
  5464.3  457.59  5474.3  457.92  5494.3  459.61  5534.3  461.29  5573.6  462.20
#Mann=3,-1,0
  4486.1    0.05       0  4981.2    0.03       0  4987.2    0.05       0
Bank Sta=4965.1,5224.4
Exp/Cntr=0.3,0.1

Type RM Length L Ch R = 1,1653,527,527,527
BEGIN DESCRIPTION:
UNT 061 in Running Cr Watershed 3.0
END DESCRIPTION:
XS GIS Cut Line= 3
      2861815.69      7032600.33      2861831.32      7032119.87
      2861844.34      7031504.02
#Sta/Elev= 30
  4415.6  464.71  4581.0  461.31  4731.1  457.63  4831.1  456.33  4851.0  455.64
  4856.0  455.81  4881.2  454.64  4921.2  453.88  4961.2  453.97  4968.4  453.66
  4981.2  452.68  4988.2  451.50  4988.7  450.70  4993.7  450.70  4994.2  451.50
  5001.2  452.77  5021.2  453.32  5041.2  452.67  5091.2  452.50  5111.2  452.81
  5141.2  452.42  5171.2  452.55  5231.3  453.66  5291.3  454.87  5361.3  458.21
  5381.3  458.55  5401.3  459.56  5421.3  458.71  5471.3  459.64  5512.3  461.17
#Mann=3,-1,0
  4415.6    0.05       0  4988.2    0.03       0  4994.2    0.05       0
Bank Sta=4968.4,5231.3
Exp/Cntr=0.3,0.1

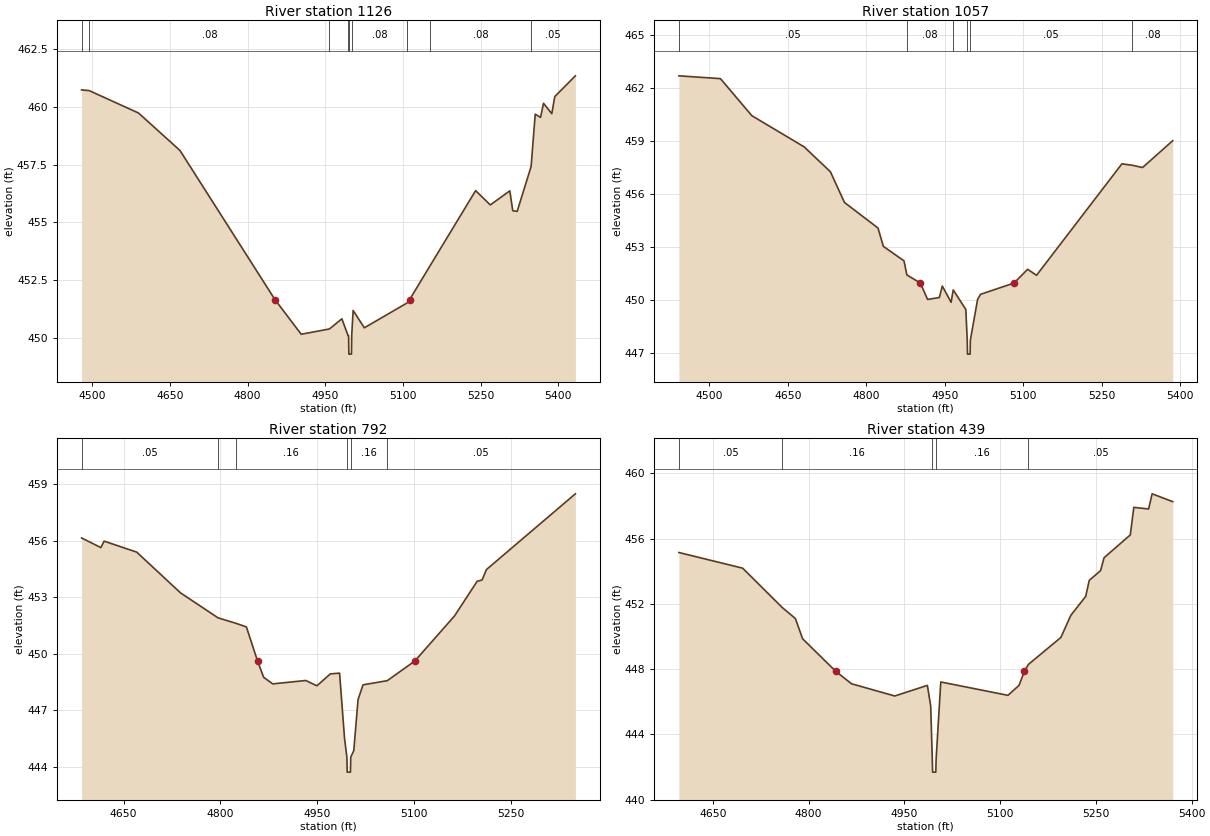
Type RM Length L Ch R = 1,1126,69,69,69
BEGIN DESCRIPTION:
UNT 061 in Running Cr Watershed 2.0
END DESCRIPTION:
XS GIS Cut Line= 4
      2862280.03      7032184.88      2862282.63      7031830.74
      2862264.40      7031734.38      2862019.64      7031296.92
#Sta/Elev= 30
  4479.5  460.74  4494.2  460.71  4589.4  459.74  4669.4  458.12  4852.9  451.66
  4903.6  450.16  4958.1  450.39  4982.1  450.83  4994.1  450.10  4995.1  450.10
  4995.6  449.30  5000.6  449.30  5001.1  450.10  5003.8  451.19  5025.5  450.44
  5107.7  451.51  5112.9  451.66  5152.8  453.14  5240.4  456.38  5268.7  455.76
  5306.4  456.37  5312.1  455.51  5320.6  455.48  5347.5  457.42  5355.5  459.69
  5365.8  459.55  5371.5  460.16  5387.5  459.71  5393.2  460.45  5433.0  461.35
#Mann=9,-1,0
  4479.5    0.05       0  4494.2    0.08       0  4958.1    0.05       0
  4994.1    0.08       0  4995.1    0.07       0  5001.1    0.08       0
  5107.7    0.05       0  5152.8    0.08       0  5347.5    0.05       0
Bank Sta=4852.9,5112.9
Exp/Cntr=0.3,0.1

Type RM Length L Ch R = 1,1057,265,265,265
BEGIN DESCRIPTION:
Mapping XS 94e5831f
END DESCRIPTION:
XS GIS Cut Line= 4
      2862373.78      7032194.44      2862375.95      7031916.67
      2862354.25      7031771.27      2862126.40      7031304.73
#Sta/Elev= 30
  4441.6  462.69  4521.0  462.53  4581.0  460.43  4681.1  458.66  4731.2  457.25
  4758.1  455.51  4822.2  454.06  4832.4  453.02  4871.9  452.20  4877.4  451.40
  4903.2  450.94  4917.0  450.01  4939.5  450.12  4945.1  450.77  4962.0  449.85
  4966.0  450.55  4990.1  449.44  4992.8  447.71  4993.3  446.91  4998.3  446.91
  4998.8  447.71  5012.6  450.01  5018.2  450.30  5082.2  450.94  5108.3  451.72
  5125.3  451.38  5288.5  457.70  5308.2  457.62  5328.0  457.49  5385.6  459.01
#Mann=6,-1,0
  4441.6    0.05       0  4877.4    0.08       0  4966.0    0.05       0
  4992.8    0.04       0  4998.8    0.05       0  5308.2    0.08       0
Bank Sta=4903.2,5082.2
Exp/Cntr=0.3,0.1

Type RM Length L Ch R = 1,792,353,353,353
BEGIN DESCRIPTION:
Mapping XS 4af7480e
END DESCRIPTION:
XS GIS Cut Line= 3
      2862616.84      7031895.01      2862545.22      7031545.58
      2862280.47      7031235.26
#Sta/Elev= 30
  4585.0  456.15  4614.8  455.64  4619.9  455.98  4670.3  455.40  4738.1  453.24
  4796.4  451.91  4823.4  451.63  4840.2  451.43  4857.5  449.62  4866.9  448.76
  4881.0  448.41  4932.1  448.59  4949.4  448.31  4970.2  448.94  4984.5  448.98
  4992.2  445.50  4995.8  444.53  4996.3  443.73  5001.3  443.73  5001.8  444.53
  5006.5  444.87  5013.1  447.58  5020.8  448.36  5058.3  448.58  5100.9  449.62
  5162.4  452.01  5197.5  453.85  5205.2  453.92  5211.8  454.47  5349.6  458.49
#Mann=6,-1,0
  4585.0    0.05       0  4796.4     0.1       0  4823.4    0.16       0
  4995.8    0.07       0  5001.8    0.16       0  5058.3    0.05       0
Bank Sta=4857.5,5100.9
Exp/Cntr=0.3,0.1

Type RM Length L Ch R = 1,439,0,0,0
BEGIN DESCRIPTION:
UNT 061 in Running Cr Watershed 1.0
END DESCRIPTION:
XS GIS Cut Line= 3
      2862905.03      7031763.01      2862787.84      7031291.67
      2862524.97      7031174.99
#Sta/Elev= 30
  4597.0  455.15  4696.8  454.19  4759.0  451.77  4779.4  451.10  4790.7  449.86
  4842.7  447.86  4867.3  447.10  4935.0  446.35  4986.1  447.00  4991.3  445.74
  4993.8  442.48  4994.3  441.68  4999.3  441.68  4999.8  442.48  5007.1  447.21
  5112.3  446.39  5129.6  447.00  5138.1  447.86  5144.4  448.29  5195.2  449.94
  5210.8  451.30  5234.1  452.46  5239.6  453.44  5257.4  454.04  5262.8  454.83
  5303.9  456.23  5309.4  457.92  5332.6  457.82  5338.1  458.75  5370.3  458.27
#Mann=5,-1,0
  4597.0    0.05       0  4759.0    0.16       0  4993.8    0.07       0
  4999.8    0.16       0  5144.4    0.05       0
Bank Sta=4842.7,5138.1
Exp/Cntr=0.3,0.1

Chan Stop Cuts=-1