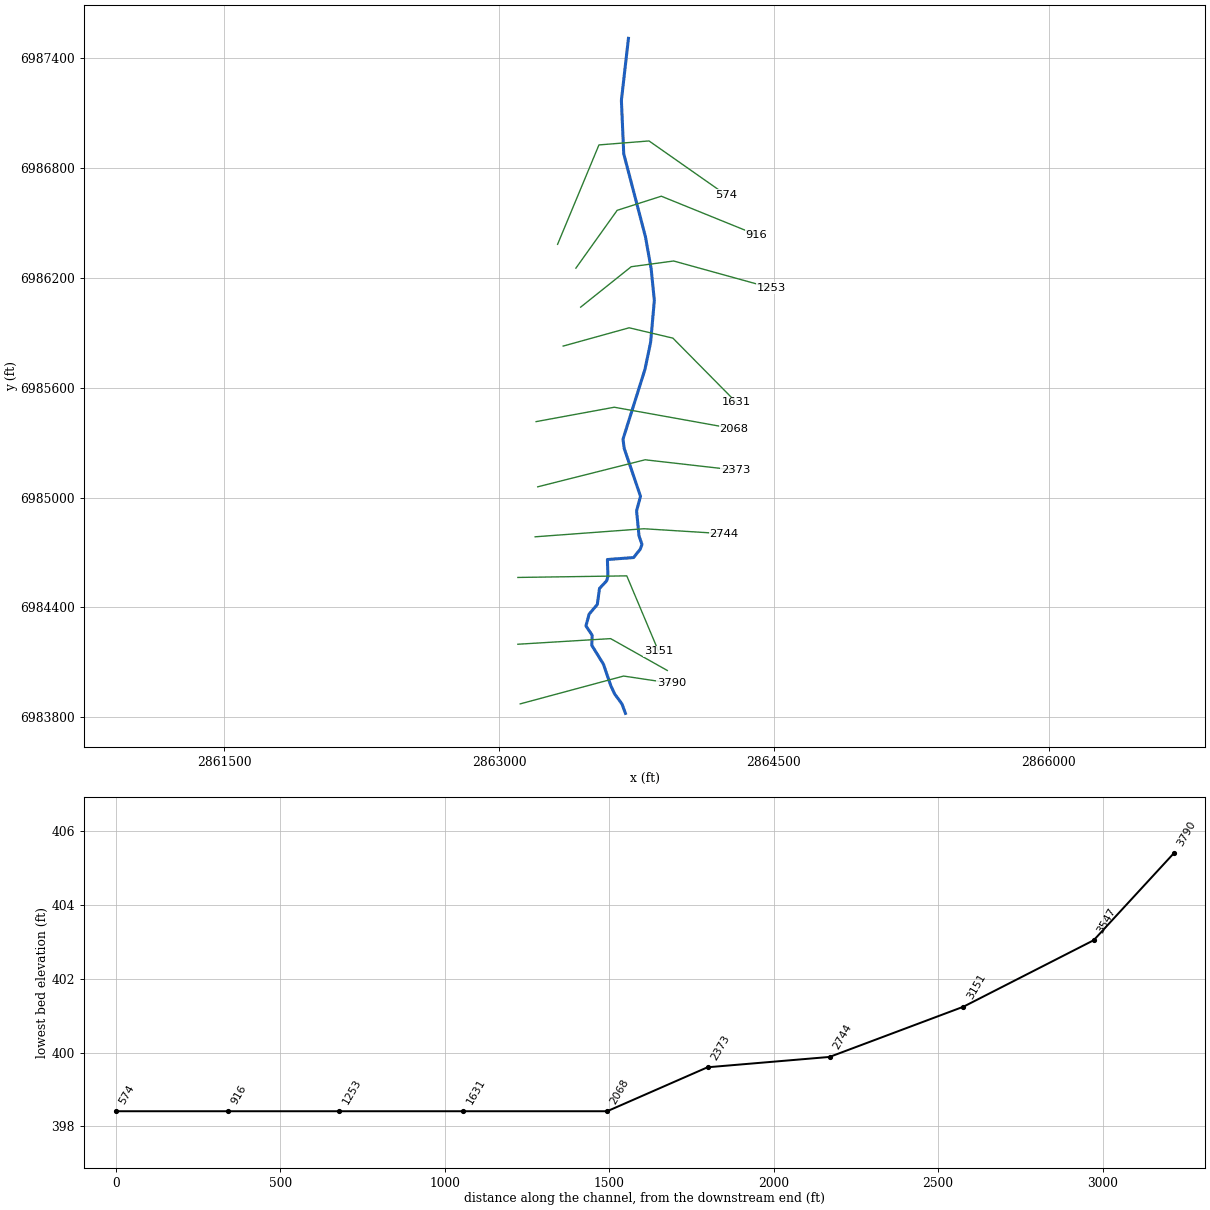
--- UNT 062 in Running Cr Watershed.prj (project) ---

Proj Title=UNT 062 in Running Cr Watershed Base Level Engineering
Current Plan=p01
Default Exp/Contr=0.3,0.1
English Units
Geom File=g01
Flow File=f01
Plan File=p01
BEGIN DESCRIPTION:
UNT 062 in Running Cr Watershed
END DESCRIPTION:

--- UNT 062 in Running Cr Watershed.p01 (plan) ---

Plan Title=Multiple Run
Short Identifier=Multiple
Geom File=g01
Flow File=f01
Subcritical Flow
K Sum by GR= 0
Std Step Tol= 0.01
Critical Tol= 0.01
Num of Std Step Trials= 20
Max Error Tol= 0.3
Flow Tol Ratio= 0.001
Split Flow NTrial= 30
Split Flow Tol= 0.02
Split Flow Ratio= 0.02
Log Output Level= 0
Friction Slope Method= 1
Unsteady Friction Slope Method= 2
Unsteady Bridges Friction Slope Method= 1
Parabolic Critical Depth
Global Vel Dist=  1 , 1 , 1
Global Log Level= 0
CheckData=True
Encroach Param= -1, 0, 0, 0
BEGIN DESCRIPTION:
Multiple Run
END DESCRIPTION:

--- UNT 062 in Running Cr Watershed.f01 (steady flow) ---

Flow Title=Multiple
Number of Profiles=7
Profile Names=10-year,25-year,50-year,1pct_min,100-year,1pct_plu,500-year
River Rch & RM= UNT 062 in Runni,Reach-1,3790
     487     642     766     454     906    1807    1270
Boundary for River Rch & Prof#=UNT 062 in Runni,Reach-1,1
Up Type=0
Dn Type=3
Dn Slope=0.005
Boundary for River Rch & Prof#=UNT 062 in Runni,Reach-1,2
Up Type=0
Dn Type=3
Dn Slope=0.005
Boundary for River Rch & Prof#=UNT 062 in Runni,Reach-1,3
Up Type=0
Dn Type=3
Dn Slope=0.005
Boundary for River Rch & Prof#=UNT 062 in Runni,Reach-1,4
Up Type=0
Dn Type=3
Dn Slope=0.005
Boundary for River Rch & Prof#=UNT 062 in Runni,Reach-1,5
Up Type=0
Dn Type=3
Dn Slope=0.005
Boundary for River Rch & Prof#=UNT 062 in Runni,Reach-1,6
Up Type=0
Dn Type=3
Dn Slope=0.005
Boundary for River Rch & Prof#=UNT 062 in Runni,Reach-1,7
Up Type=0
Dn Type=3
Dn Slope=0.005

--- UNT 062 in Running Cr Watershed.g01 (geometry) ---

Geom Title=Existing Conditions

River Reach=UNT 062 in Runni,Reach-1
Reach XY= 30
      2863690.54      6983822.03      2863671.66      6983873.26
      2863631.22      6983928.53      2863609.65      6983975.71
      2863570.56      6984090.30      2863507.20      6984192.75
      2863508.55      6984249.37      2863474.85      6984299.24
      2863492.37      6984363.95      2863536.86      6984416.53
      2863548.99      6984504.15      2863588.09      6984545.94
      2863594.83      6984570.20      2863592.13      6984661.87
      2863735.02      6984672.66      2863771.42      6984718.49
      2863780.86      6984744.10      2863764.68      6984791.28
      2863751.20      6984927.44      2863772.77      6985006.97
      2863683.80      6985268.50      2863677.06      6985318.37
      2863797.03      6985699.87      2863828.04      6985848.16
      2863848.26      6986075.98      2863830.74      6986249.88
      2863799.73      6986423.78      2863681.23      6986876.57
      2863668.36      6987168.17      2863706.96      6987506.95

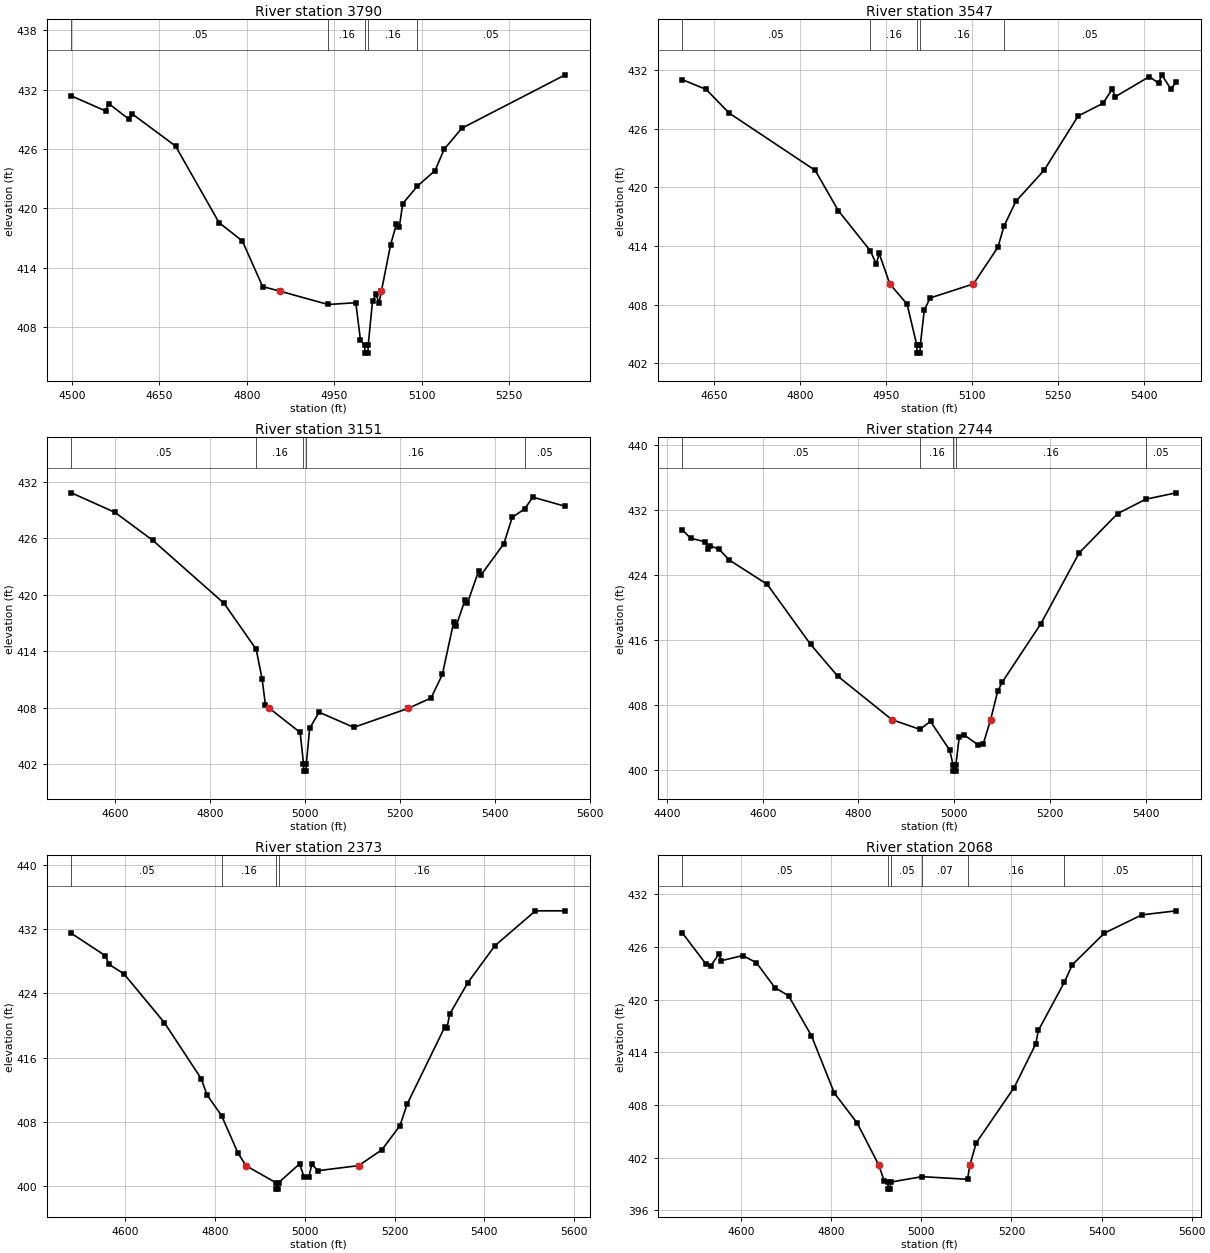
Type RM Length L Ch R = 1,3790,243,243,243
BEGIN DESCRIPTION:
UNT 062 in Running Cr Watershed 10.0
END DESCRIPTION:
XS GIS Cut Line= 3
      2863116.18      6983873.90      2863680.43      6984025.81
      2863940.38      6983986.82
#Sta/Elev= 30
  4499.0  431.36  4557.8  429.84  4563.0  430.59  4597.8  429.01  4603.0  429.56
  4677.7  426.30  4752.4  418.56  4792.3  416.72  4827.1  412.11  4857.2  411.64
  4939.4  410.30  4986.9  410.48  4994.9  406.71  5002.2  406.19  5002.7  405.39
  5007.7  405.39  5008.2  406.19  5015.6  410.63  5021.6  411.31  5026.8  410.46
  5030.8  411.64  5046.7  416.35  5056.4  418.38  5061.6  418.13  5067.4  420.48
  5092.5  422.25  5122.9  423.82  5138.5  425.98  5168.9  428.10  5346.2  433.49
#Mann=5,-1,0
  4499.0    0.05       0  4939.4    0.16       0  5002.2    0.07       0
  5008.2    0.16       0  5092.5    0.05       0
Bank Sta=4857.2,5030.8
Exp/Cntr=0.3,0.1

Type RM Length L Ch R = 1,3547,396,396,396
BEGIN DESCRIPTION:
UNT 062 in Running Cr Watershed 9.0
END DESCRIPTION:
XS GIS Cut Line= 3
      2863103.19      6984199.43      2863609.64      6984230.12
      2863919.14      6984056.20
#Sta/Elev= 30
  4594.5  431.02  4636.4  430.01  4676.5  427.59  4826.7  421.73  4866.8  417.63
  4922.9  413.51  4933.3  412.15  4938.3  413.24  4956.9  410.12  4987.0  408.06
  5004.1  403.84  5004.6  403.04  5009.6  403.04  5010.1  403.84  5017.1  407.44
  5027.1  408.68  5103.0  410.12  5145.6  413.87  5156.4  416.05  5176.9  418.56
  5226.5  421.76  5285.8  427.30  5329.2  428.60  5345.1  430.03  5350.9  429.28
  5410.2  431.33  5426.1  430.65  5431.8  431.51  5447.8  430.04  5456.9  430.78
#Mann=5,-1,0
  4594.5    0.05       0  4922.9    0.16       0  5004.1    0.07       0
  5010.1    0.16       0  5156.4    0.05       0
Bank Sta=4956.9,5103
Exp/Cntr=0.3,0.1

Type RM Length L Ch R = 1,3151,407,407,407
BEGIN DESCRIPTION:
UNT 062 in Running Cr Watershed 8.0
END DESCRIPTION:
XS GIS Cut Line= 3
      2863103.20      6984564.01      2863697.79      6984572.69
      2863870.69      6984162.06
#Sta/Elev= 30
  4508.4  430.81  4600.2  428.73  4680.2  425.75  4830.2  419.06  4897.7  414.18
  4910.2  411.02  4917.1  408.30  4925.7  407.91  4990.3  405.35  4997.3  402.04
  4997.8  401.24  5002.8  401.24  5003.3  402.04  5010.3  405.79  5030.3  407.50
  5103.1  405.89  5217.9  407.91  5266.0  409.01  5289.8  411.51  5313.5  417.05
  5318.9  416.66  5337.3  419.41  5342.7  419.10  5366.4  422.54  5371.8  422.12
  5419.3  425.40  5436.9  428.20  5463.3  429.11  5480.3  430.35  5548.6  429.38
#Mann=5,-1,0
  4508.4    0.05       0  4897.7    0.16       0  4997.3    0.07       0
  5003.3    0.16       0  5463.3    0.05       0
Bank Sta=4925.7,5217.9
Exp/Cntr=0.3,0.1

Type RM Length L Ch R = 1,2744,371,371,371
BEGIN DESCRIPTION:
UNT 062 in Running Cr Watershed 7.0
END DESCRIPTION:
XS GIS Cut Line= 3
      2863197.75      6984785.94      2863791.45      6984829.92
      2864227.27      6984802.72
#Sta/Elev= 30
  4431.9  429.56  4449.2  428.54  4479.3  428.10  4485.6  427.20  4490.6  427.61
  4509.4  427.15  4529.4  425.88  4609.6  422.85  4699.9  415.48  4756.3  411.59
  4870.0  406.21  4928.4  405.02  4950.6  406.00  4990.7  402.46  4997.7  400.68
  4998.2  399.88  5003.2  399.88  5003.7  400.68  5010.7  404.10  5020.8  404.35
  5050.8  403.06  5060.8  403.23  5076.2  406.21  5090.9  409.69  5100.9  410.86
  5181.1  418.01  5261.2  426.72  5341.4  431.56  5400.8  433.34  5463.9  434.12
#Mann=5,-1,0
  4431.9    0.05       0  4928.4    0.16       0  4997.7    0.07       0
  5003.7    0.16       0  5400.8    0.05       0
Bank Sta=4870,5076.2
Exp/Cntr=0.3,0.1

Type RM Length L Ch R = 1,2373,305,305,305
BEGIN DESCRIPTION:
UNT 062 in Running Cr Watershed 6.0
END DESCRIPTION:
XS GIS Cut Line= 3
      2863211.68      6985058.80      2863797.61      6985206.37
      2864290.99      6985150.11
#Sta/Elev= 30
  4479.5  431.48  4555.1  428.70  4563.3  427.62  4596.4  426.45  4686.6  420.37
  4768.8  413.38  4782.0  411.33  4814.2  408.77  4851.0  404.09  4868.5  402.53
  4935.3  400.40  4935.8  399.60  4940.8  399.60  4941.3  400.40  4988.2  402.75
  4998.5  401.05  5008.8  401.11  5015.4  402.67  5029.5  401.90  5119.7  402.53
  5171.7  404.51  5211.9  407.51  5227.6  410.16  5312.0  419.83  5317.0  419.74
  5322.7  421.41  5362.9  425.31  5423.3  429.93  5513.9  434.29  5580.3  434.29
#Mann=4,-1,0
  4479.5    0.05       0  4814.2    0.16       0  4935.3    0.07       0
  4941.3    0.16       0
Bank Sta=4868.5,5119.7
Exp/Cntr=0.3,0.1

Type RM Length L Ch R = 1,2068,437,437,437
BEGIN DESCRIPTION:
UNT 062 in Running Cr Watershed 5.0
END DESCRIPTION:
XS GIS Cut Line= 3
      2863202.99      6985414.70      2863629.66      6985493.22
      2864281.87      6985375.97
#Sta/Elev= 30
  4469.1  427.61  4522.0  424.02  4532.2  423.82  4550.5  425.20  4555.6  424.42
  4603.3  425.02  4633.8  424.20  4674.5  421.37  4705.0  420.44  4755.9  415.88
  4806.7  409.35  4857.5  405.93  4905.3  401.16  4917.3  399.36  4925.7  399.21
  4926.2  398.41  4931.2  398.41  4931.7  399.21  5001.4  399.83  5102.4  399.53
  5107.7  401.16  5121.7  403.68  5205.9  409.98  5253.8  414.94  5259.6  416.48
  5317.7  422.01  5335.1  423.97  5406.2  427.57  5489.5  429.65  5565.6  430.11
#Mann=6,-1,0
  4469.1    0.05       0  4925.7   0.035       0  4931.7    0.05       0
  5001.4    0.07       0  5102.4    0.16       0  5317.7    0.05       0
Bank Sta=4905.3,5107.7
Exp/Cntr=0.3,0.1

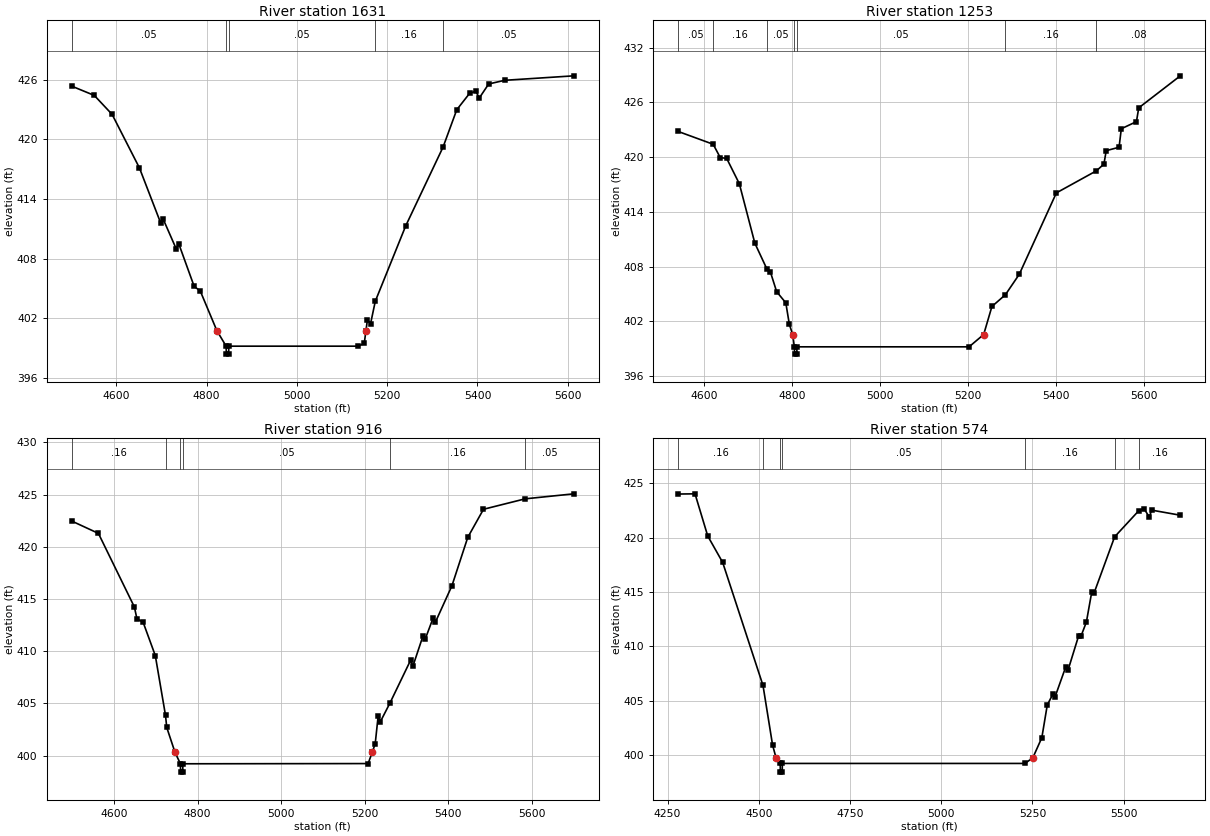
Type RM Length L Ch R = 1,1631,378,378,378
BEGIN DESCRIPTION:
UNT 062 in Running Cr Watershed 4.0
END DESCRIPTION:
XS GIS Cut Line= 4
      2863350.60      6985827.04      2863710.81      6985926.86
      2863949.52      6985870.43      2864296.18      6985519.44
#Sta/Elev= 30
  4501.2  425.36  4551.1  424.43  4590.6  422.52  4651.0  417.15  4698.6  411.55
  4703.8  411.98  4732.9  408.97  4738.1  409.53  4772.4  405.22  4785.9  404.76
  4822.7  400.77  4843.2  399.21  4843.7  398.41  4848.7  398.41  4849.2  399.21
  5135.1  399.21  5149.2  399.48  5153.0  400.77  5156.2  401.84  5163.3  401.49
  5173.7  403.73  5241.1  411.31  5323.9  419.24  5354.2  422.99  5382.5  424.63
  5396.7  424.86  5403.8  424.15  5424.9  425.58  5460.4  425.95  5613.6  426.40
#Mann=5,-1,0
  4501.2    0.05       0  4843.2   0.033       0  4849.2    0.05       0
  5173.7    0.16       0  5323.9    0.05       0
Bank Sta=4822.7,5153
Exp/Cntr=0.3,0.1

Type RM Length L Ch R = 1,1253,337,337,337
BEGIN DESCRIPTION:
UNT 062 in Running Cr Watershed 3.0
END DESCRIPTION:
XS GIS Cut Line= 4
      2863446.04      6986039.69      2863722.08      6986260.30
      2863953.86      6986291.44      2864487.71      6986143.87
#Sta/Elev= 30
  4541.4  422.81  4620.8  421.41  4637.0  419.94  4651.4  419.87  4680.3  417.08
  4715.5  410.57  4742.5  407.78  4750.7  407.44  4765.1  405.25  4785.9  404.03
  4793.9  401.68  4801.5  400.56  4805.3  399.21  4805.8  398.41  4810.8  398.41
  4811.3  399.21  5202.4  399.21  5235.6  400.56  5254.3  403.63  5285.0  404.92
  5316.5  407.16  5400.8  416.08  5491.8  418.50  5508.9  419.24  5514.1  420.71
  5543.3  421.08  5548.4  423.11  5582.8  423.89  5588.0  425.40  5682.5  428.91
#Mann=7,-1,0
  4541.4    0.05       0  4620.8    0.16       0  4742.5    0.05       0
  4805.3   0.033       0  4811.3    0.05       0  5285.0    0.16       0
  5491.8    0.08       0
Bank Sta=4801.5,5235.6
Exp/Cntr=0.3,0.1

Type RM Length L Ch R = 1,916,342,342,342
BEGIN DESCRIPTION:
UNT 062 in Running Cr Watershed 2.0
END DESCRIPTION:
XS GIS Cut Line= 4
      2863419.99      6986252.35      2863645.29      6986568.06
      2863886.32      6986645.16      2864405.23      6986434.68
#Sta/Elev= 30
  4499.1  422.47  4562.8  421.29  4648.8  414.24  4655.0  413.10  4669.7  412.78
  4698.9  409.58  4723.3  403.85  4726.3  402.69  4745.8  400.33  4758.9  399.21
  4759.4  398.41  4764.4  398.41  4764.9  399.21  5207.9  399.23  5218.0  400.33
  5224.9  401.14  5231.9  403.77  5237.3  403.25  5259.9  405.01  5309.6  409.14
  5315.0  408.56  5339.1  411.45  5344.5  411.16  5363.2  413.16  5368.6  412.76
  5408.4  416.27  5446.3  420.91  5483.9  423.60  5583.5  424.60  5700.0  425.08
#Mann=6,-1,0
  4499.1    0.16       0  4723.3    0.05       0  4758.9   0.033       0
  4764.9    0.05       0  5259.9    0.16       0  5583.5    0.05       0
Bank Sta=4745.8,5218
Exp/Cntr=0.3,0.1

Type RM Length L Ch R = 1,574,0,0,0
BEGIN DESCRIPTION:
UNT 062 in Running Cr Watershed 1.0
END DESCRIPTION:
XS GIS Cut Line= 4
      2863320.17      6986382.55      2863545.88      6986925.12
      2863819.32      6986946.82      2864240.17      6986651.79
#Sta/Elev= 30
  4279.2  424.02  4325.2  424.04  4360.0  420.16  4401.0  417.72  4511.5  406.39
  4537.7  400.91  4547.3  399.72  4558.6  399.21  4559.1  398.41  4564.1  398.41
  4564.6  399.21  5229.2  399.21  5250.8  399.72  5275.6  401.58  5290.5  404.59
  5305.3  405.56  5311.4  405.30  5341.0  408.09  5347.1  407.77  5376.7  410.99
  5382.9  410.93  5397.7  412.23  5412.5  415.02  5418.6  414.89  5475.1  420.08
  5541.7  422.50  5555.4  422.68  5570.3  421.90  5576.4  422.54  5655.1  422.07
#Mann=7,-1,0
  4279.2    0.16       0  4511.5    0.05       0  4558.6   0.033       0
  4564.6    0.05       0  5229.2    0.16       0  5475.1    0.12       0
  5541.7    0.16       0
Bank Sta=4547.3,5250.8
Exp/Cntr=0.3,0.1

Chan Stop Cuts=-1