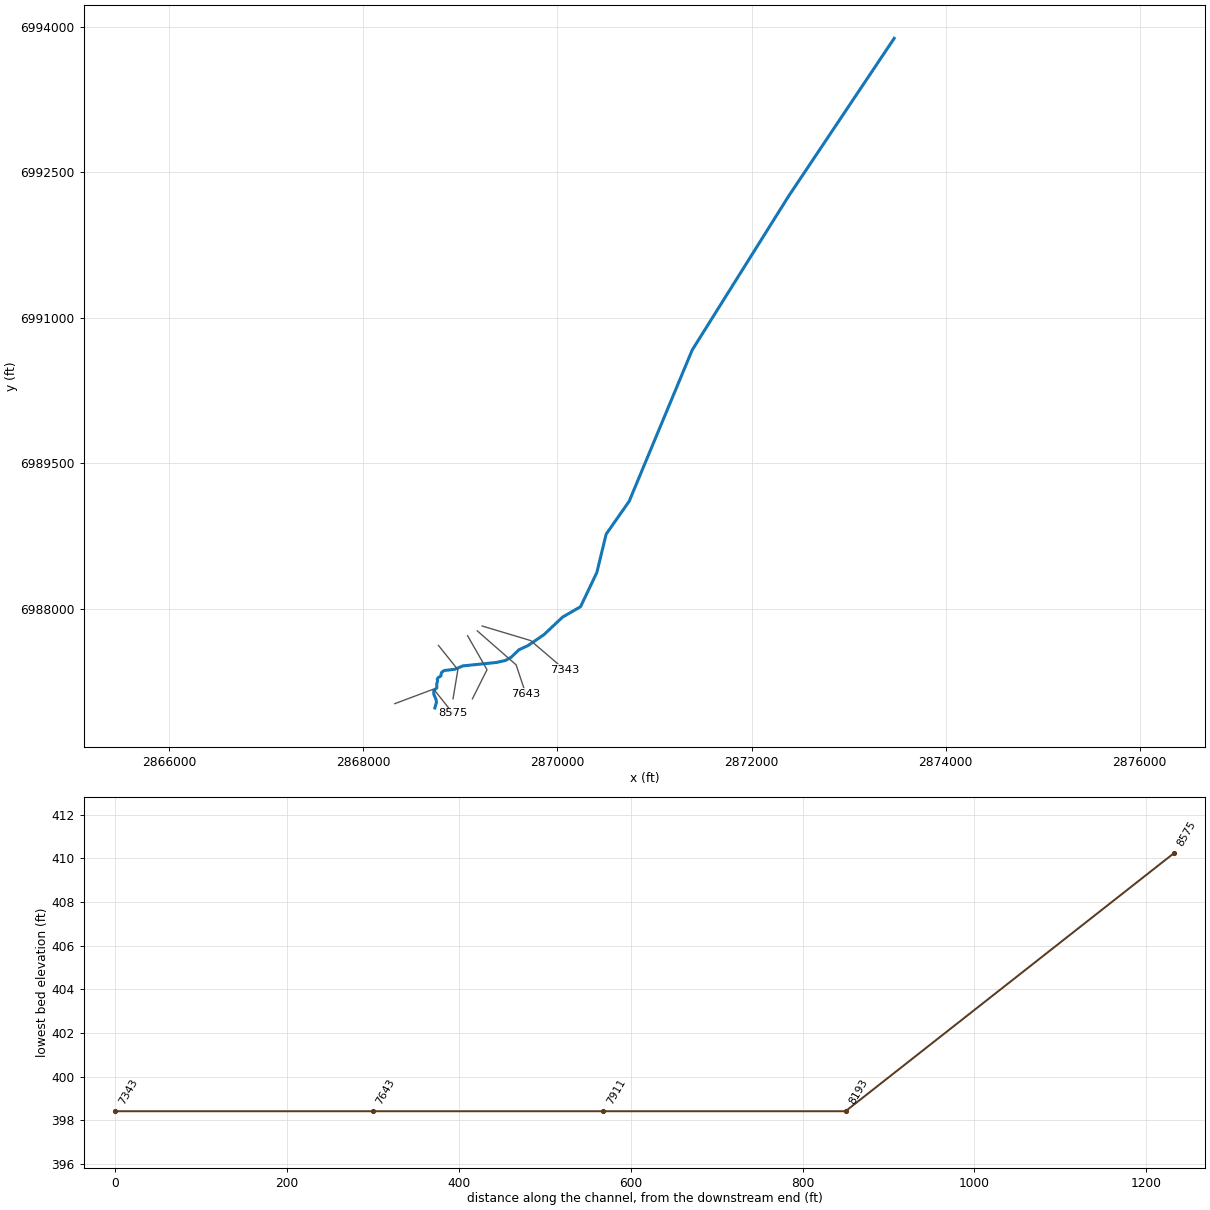
--- UNT 063 in Running Cr Watershed.prj (project) ---

Proj Title=UNT 063 in Running Cr Watershed Base Level Engineering
Current Plan=p01
Default Exp/Contr=0.3,0.1
English Units
Geom File=g01
Flow File=f01
Plan File=p01
BEGIN DESCRIPTION:
UNT 063 in Running Cr Watershed
END DESCRIPTION:

--- UNT 063 in Running Cr Watershed.p01 (plan) ---

Plan Title=Multiple Run
Short Identifier=Multiple
Geom File=g01
Flow File=f01
Subcritical Flow
K Sum by GR= 0
Std Step Tol= 0.01
Critical Tol= 0.01
Num of Std Step Trials= 20
Max Error Tol= 0.3
Flow Tol Ratio= 0.001
Split Flow NTrial= 30
Split Flow Tol= 0.02
Split Flow Ratio= 0.02
Log Output Level= 0
Friction Slope Method= 1
Unsteady Friction Slope Method= 2
Unsteady Bridges Friction Slope Method= 1
Parabolic Critical Depth
Global Vel Dist=  1 , 1 , 1
Global Log Level= 0
CheckData=True
Encroach Param= -1, 0, 0, 0
BEGIN DESCRIPTION:
Multiple Run
END DESCRIPTION:

--- UNT 063 in Running Cr Watershed.f01 (steady flow) ---

Flow Title=Multiple
Number of Profiles=7
Profile Names=10-year,25-year,50-year,1pct_min,100-year,1pct_plu,500-year
River Rch & RM= UNT 063 in Runni,Reach-1,8575
     145     177     201     114     228     455     291
Boundary for River Rch & Prof#=UNT 063 in Runni,Reach-1,1
Up Type=0
Dn Type=3
Dn Slope=0.005
Boundary for River Rch & Prof#=UNT 063 in Runni,Reach-1,2
Up Type=0
Dn Type=3
Dn Slope=0.005
Boundary for River Rch & Prof#=UNT 063 in Runni,Reach-1,3
Up Type=0
Dn Type=3
Dn Slope=0.005
Boundary for River Rch & Prof#=UNT 063 in Runni,Reach-1,4
Up Type=0
Dn Type=3
Dn Slope=0.005
Boundary for River Rch & Prof#=UNT 063 in Runni,Reach-1,5
Up Type=0
Dn Type=3
Dn Slope=0.005
Boundary for River Rch & Prof#=UNT 063 in Runni,Reach-1,6
Up Type=0
Dn Type=3
Dn Slope=0.005
Boundary for River Rch & Prof#=UNT 063 in Runni,Reach-1,7
Up Type=0
Dn Type=3
Dn Slope=0.005

--- UNT 063 in Running Cr Watershed.g01 (geometry) ---

Geom Title=Existing Conditions

River Reach=UNT 063 in Runni,Reach-1
Reach XY= 30
      2868737.79      6986980.97      2868754.45      6987039.30
      2868750.29      6987065.69      2868726.67      6987123.33
      2868726.67      6987160.13      2868758.62      6987188.61
      2868756.54      6987228.88      2868765.56      6987254.58
      2868762.09      6987278.19      2868773.20      6987294.16
      2868799.59      6987309.44      2868803.76      6987337.91
      2868811.40      6987351.11      2868834.31      6987366.38
      2868943.69      6987379.58      2869027.02      6987414.30
      2869369.04      6987449.02      2869464.52      6987469.86
      2869523.55      6987502.84      2869605.15      6987580.97
      2869698.90      6987624.37      2869860.93      6987735.29
      2870054.80      6987917.77      2870238.83      6988023.67
      2870406.43      6988375.95      2870502.41      6988771.12
      2870739.51      6989109.85      2871388.73      6990667.97
      2872384.82      6992257.53      2873469.73      6993879.30

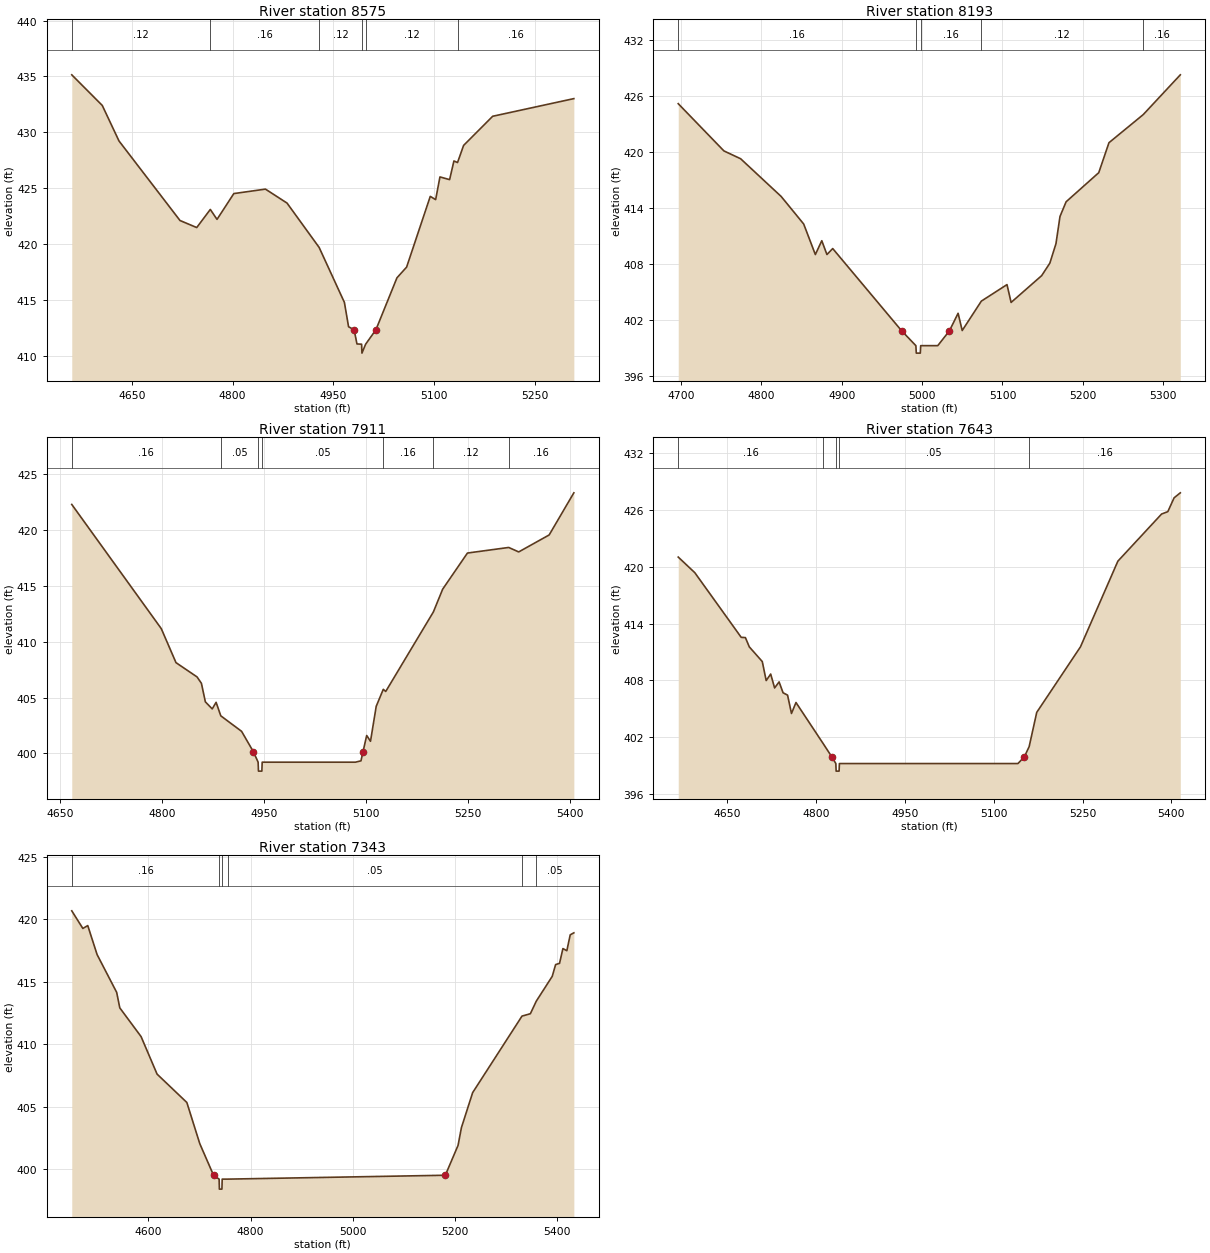
Type RM Length L Ch R = 1,8575,382,382,382
BEGIN DESCRIPTION:
UNT 063 in Running Cr Watershed 13.0
END DESCRIPTION:
XS GIS Cut Line= 3
      2868325.03      6987025.01      2868725.00      6987175.00
      2868924.98      6986925.02
#Sta/Elev= 30
  4560.6  435.14  4606.0  432.40  4630.9  429.22  4721.7  422.10  4746.6  421.47
  4766.8  423.09  4776.8  422.20  4801.8  424.51  4848.9  424.91  4881.0  423.66
  4928.8  419.69  4966.4  414.77  4972.6  412.59  4980.9  412.32  4985.1  411.05
  4992.0  411.03  4992.5  410.23  4998.0  411.03  5013.3  412.32  5044.6  416.97
  5059.0  417.93  5094.2  424.26  5102.2  423.97  5108.6  426.00  5123.0  425.76
  5129.4  427.43  5134.8  427.29  5143.8  428.82  5187.1  431.43  5307.9  433.01
#Mann=6,-1,0
  4560.6    0.12       0  4766.8    0.16       0  4928.8    0.12       0
  4992.0    0.07       0  4998.0    0.12       0  5134.8    0.16       0
Bank Sta=4980.9,5013.3
Exp/Cntr=0.3,0.1

Type RM Length L Ch R = 1,8193,282,282,282
BEGIN DESCRIPTION:
UNT 063 in Running Cr Watershed 12.0
END DESCRIPTION:
XS GIS Cut Line= 3
      2868775.02      6987624.98      2868975.00      6987375.00
      2868924.99      6987074.97
#Sta/Elev= 30
  4696.8  425.13  4753.6  420.07  4774.4  419.23  4824.8  415.19  4852.8  412.24
  4867.3  408.97  4875.3  410.45  4881.7  408.97  4888.9  409.61  4974.6  400.80
  4992.3  399.21  4992.8  398.41  4997.8  398.41  4998.3  399.21  5019.5  399.21
  5034.0  400.80  5044.8  402.68  5049.9  400.83  5073.7  403.98  5105.6  405.75
  5110.7  403.84  5148.7  406.71  5158.9  408.05  5166.5  410.14  5171.5  413.05
  5179.1  414.62  5219.7  417.74  5232.4  420.95  5275.0  423.96  5321.1  428.22
#Mann=5,-1,0
  4696.8    0.16       0  4992.3    0.07       0  4998.3    0.16       0
  5073.7    0.12       0  5275.0    0.16       0
Bank Sta=4974.6,5034
Exp/Cntr=0.3,0.1

Type RM Length L Ch R = 1,7911,268,268,268
BEGIN DESCRIPTION:
UNT 063 in Running Cr Watershed 11.0
END DESCRIPTION:
XS GIS Cut Line= 3
      2869075.01      6987724.98      2869275.00      6987375.00
      2869125.00      6987075.00
#Sta/Elev= 30
  4667.1  422.28  4798.8  411.16  4820.4  408.12  4851.4  406.84  4857.8  406.27
  4863.6  404.61  4873.7  403.98  4879.4  404.57  4886.3  403.36  4916.9  401.97
  4934.2  400.15  4941.2  399.21  4941.7  398.41  4946.7  398.41  4947.2  399.21
  5084.2  399.21  5092.5  399.33  5095.5  400.15  5100.9  401.60  5106.5  401.08
  5114.9  404.21  5125.3  405.73  5128.9  405.54  5199.0  412.66  5212.7  414.70
  5249.1  417.93  5309.8  418.43  5324.5  418.03  5369.3  419.55  5405.6  423.32
#Mann=7,-1,0
  4667.1    0.16       0  4886.3    0.05       0  4941.2   0.033       0
  4947.2    0.05       0  5125.3    0.16       0  5199.0    0.12       0
  5309.8    0.16       0
Bank Sta=4934.2,5095.5
Exp/Cntr=0.3,0.1

Type RM Length L Ch R = 1,7643,300,300,300
BEGIN DESCRIPTION:
UNT 063 in Running Cr Watershed 10.0
END DESCRIPTION:
XS GIS Cut Line= 3
      2869175.02      6987774.98      2869575.00      6987425.00
      2869675.00      6987125.01
#Sta/Elev= 30
  4567.3  421.03  4595.3  419.38  4673.6  412.55  4680.7  412.52  4687.3  411.54
  4709.2  409.99  4715.8  407.98  4723.4  408.67  4730.0  407.20  4737.6  407.84
  4744.3  406.69  4751.9  406.44  4758.5  404.50  4766.1  405.66  4811.7  401.35
  4826.4  399.94  4833.4  399.21  4833.9  398.41  4838.9  398.41  4839.4  399.21
  5140.9  399.21  5151.8  399.94  5159.8  401.00  5172.6  404.62  5246.4  411.54
  5309.6  420.60  5383.4  425.58  5393.9  425.83  5404.5  427.29  5415.0  427.82
#Mann=5,-1,0
  4567.3    0.16       0  4811.7    0.05       0  4833.4   0.033       0
  4839.4    0.05       0  5159.8    0.16       0
Bank Sta=4826.4,5151.8
Exp/Cntr=0.3,0.1

Type RM Length L Ch R = 1,7343,0,0,0
BEGIN DESCRIPTION:
UNT 063 in Running Cr Watershed 9.0
END DESCRIPTION:
XS GIS Cut Line= 3
      2869225.00      6987825.00      2869725.00      6987675.00
      2870075.01      6987374.99
#Sta/Elev= 30
  4450.0  420.67  4471.7  419.26  4481.3  419.49  4499.6  417.17  4537.9  414.15
  4544.0  412.91  4585.7  410.61  4617.0  407.61  4675.3  405.34  4700.6  402.05
  4727.6  399.52  4738.5  399.21  4739.0  398.41  4744.0  398.41  4744.5  399.21
  4755.5  399.21  5181.4  399.52  5206.3  401.91  5212.9  403.33  5234.9  406.13
  5331.5  412.25  5347.9  412.44  5359.4  413.44  5390.7  415.43  5397.3  416.37
  5405.0  416.47  5411.6  417.65  5419.3  417.48  5425.9  418.75  5433.0  418.91
#Mann=6,-1,0
  4450.0    0.16       0  4738.5   0.033       0  4744.5    0.16       0
  4755.5    0.05       0  5331.5    0.16       0  5359.4    0.05       0
Bank Sta=4727.6,5181.4
Exp/Cntr=0.3,0.1

Chan Stop Cuts=-1